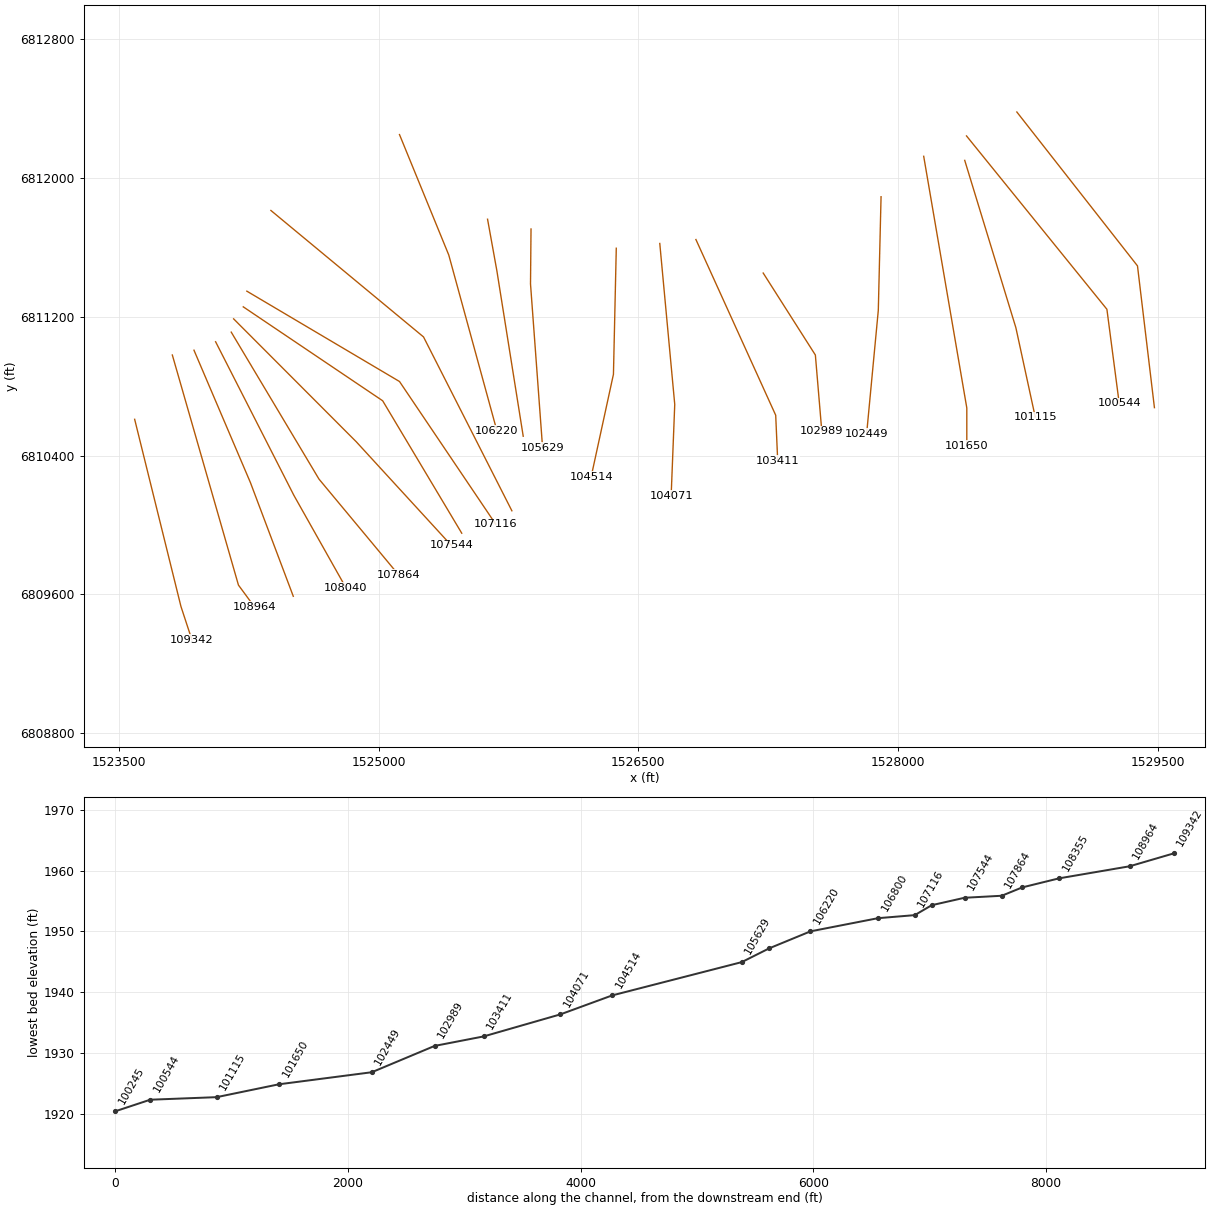
HEC-RAS study Little Elm Creek.prj: Little Elm Creek Base Level Engineering

--- Little Elm Creek.g01 (geometry) --- (continued)

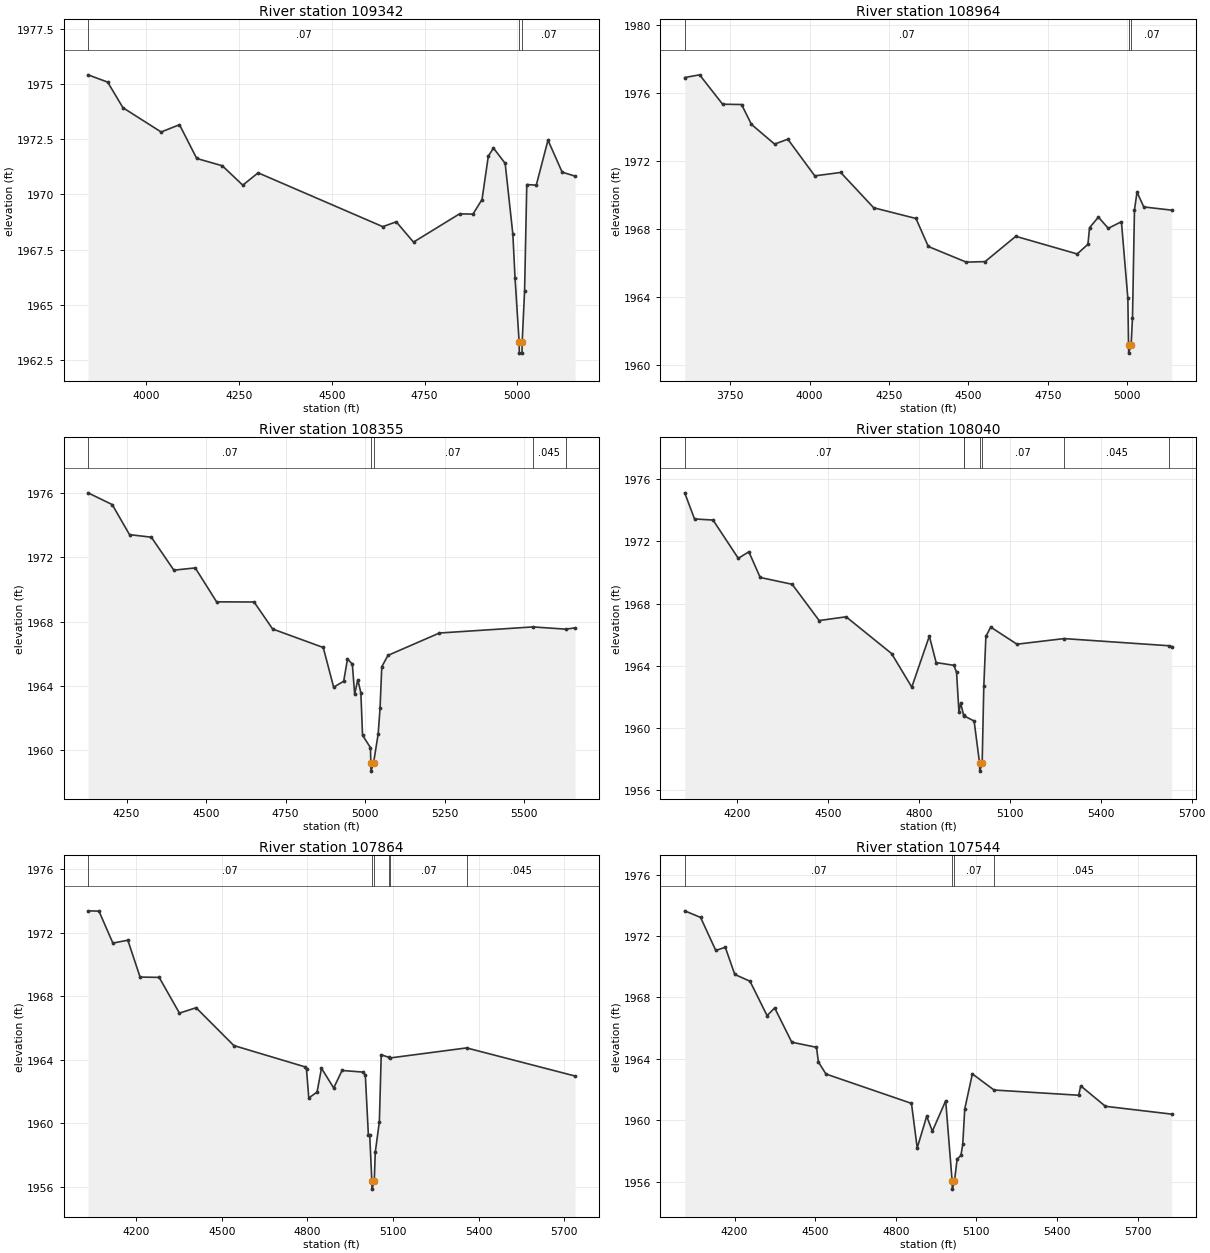
Type RM Length L Ch R = 1 ,109342  ,378,378,378
BEGIN DESCRIPTION:
Little Elm Creek 109262.11
END DESCRIPTION:
XS GIS Cut Line= 3
      1523589.91      6810609.42      1523857.35      6809530.49
      1523920.44      6809338.68
#Sta/Elev= 30
  3842.4 1975.42  3895.4 1975.09  3936.6 1973.93  4039.6 1972.83  4089.1 1973.16
  4135.6 1971.63  4204.5  1971.3  4259.8 1970.42  4301.1 1970.98  4637.4 1968.54
  4673.6 1968.76  4720.2 1967.84  4844.3 1969.12  4880.6 1969.11    4905 1969.77
    4922 1971.74  4935.9  1972.1  4967.4 1971.41  4988.2 1968.19    4994 1966.22
  5005.1 1963.31  5005.6 1962.81  5012.8 1962.81  5013.3 1963.31  5019.8 1965.64
  5025.7 1970.45  5051.3 1970.42  5082.9 1972.46  5121.1 1971.01  5155.9 1970.83
#Mann= 3 ,-1 , 0
  3842.4     .07       0  5005.1     .07       0  5013.3     .07       0
Bank Sta=5005.1,5013.3
XS Rating Curve= 0 ,0
Exp/Cntr=0.3,0.1

Type RM Length L Ch R = 1 ,108964  ,609,609,609
BEGIN DESCRIPTION:
Little Elm Creek 108965.56
END DESCRIPTION:
XS GIS Cut Line= 3
      1523807.61       6810980.1      1524189.57      6809653.68
      1524280.67      6809529.91
#Sta/Elev= 30
  3606.6 1976.93  3653.5 1977.09    3726 1975.36  3785.7 1975.34  3816.9 1974.17
  3889.8 1973.01  3931.4  1973.3  4016.3 1971.14  4097.9 1971.34  4201.9 1969.26
    4335 1968.63  4373.9 1966.98  4493.3 1966.06  4552.7 1966.09  4649.4 1967.58
  4842.9 1966.54  4876.6 1967.11  4881.8 1968.09  4909.6 1968.71  4940.8 1968.05
  4982.1 1968.44  5002.4 1963.92  5004.5  1961.2    5005  1960.7  5012.7  1961.2
    5017 1962.77  5023.2 1969.13  5031.2 1970.18  5052.5 1969.31  5140.6 1969.12
#Mann= 3 ,-1 , 0
  3606.6     .07       0  5004.5     .07       0  5012.7     .07       0
Bank Sta=5004.5,5012.7
XS Rating Curve= 0 ,0
Exp/Cntr=0.3,0.1

Type RM Length L Ch R = 1 ,108355  ,315,315,315
BEGIN DESCRIPTION:
Little Elm Creek 108353.97
END DESCRIPTION:
XS GIS Cut Line= 3
      1523932.61      6811007.88      1524259.01      6810243.95
      1524506.39      6809589.16
#Sta/Elev= 30
  4128.9 1976.02  4204.9 1975.29  4259.3 1973.42  4327.9 1973.26  4398.7 1971.21
  4465.9 1971.35    4533 1969.24  4650.8 1969.23  4709.1 1967.55  4868.2  1966.4
  4900.9 1963.93  4932.4  1964.3  4944.4 1965.68  4959.6 1965.37  4966.9 1963.49
  4976.7  1964.4  4986.4 1963.59  4991.7 1960.94  5016.6 1960.17  5017.7 1959.21
  5018.2 1958.71  5026.2 1959.21  5040.8 1961.02  5046.7 1962.62  5052.1  1965.2
  5071.6 1965.91  5233.2  1967.3  5527.1 1967.68  5630.7 1967.54  5659.6 1967.62
#Mann= 5 ,-1 , 0
  4128.9     .07       0  5017.7     .07       0  5026.2     .07       0
  5527.1    .045       0  5630.7     .07       0
Bank Sta=5017.7,5026.2
XS Rating Curve= 0 ,0
Exp/Cntr=0.3,0.1

Type RM Length L Ch R = 1 ,108040  ,176,176,176
BEGIN DESCRIPTION:
Little Elm Creek 108166.51
END DESCRIPTION:
XS GIS Cut Line= 3
      1524057.61      6811056.48      1524509.95      6810170.86
      1524810.65      6809638.12
#Sta/Elev= 30
  4028.1 1975.12  4060.5 1973.44  4121.6 1973.37  4204.8 1970.91  4239.7 1971.33
  4277.1 1969.68  4382.6 1969.24  4471.5 1966.91  4560.4 1967.15  4710.3 1964.79
    4777 1962.63  4834.9 1965.91  4857.3 1964.21  4915.9 1964.03  4924.7 1963.58
  4932.5 1961.03  4938.1  1961.6  4947.8 1960.84  4948.9 1960.79  4982.6 1960.45
  5000.6 1957.73  5001.1 1957.23  5009.1 1957.73  5014.5 1962.68  5021.4 1965.89
  5037.3 1966.49  5123.9 1965.39  5279.3 1965.75  5625.1 1965.29  5634.3 1965.24
#Mann= 7 ,-1 , 0
  4028.1     .07       0  4947.8    .045       0  4948.9     .07       0
  5000.6     .07       0  5009.1     .07       0  5279.3    .045       0
  5625.1     .07       0
Bank Sta=5000.6,5009.1
XS Rating Curve= 0 ,0
Exp/Cntr=0.3,0.1

Type RM Length L Ch R = 1 ,107864  ,320,320,320
BEGIN DESCRIPTION:
Little Elm Creek 107863.59
END DESCRIPTION:
XS GIS Cut Line= 3
      1524147.89      6811112.03      1524654.85      6810264.79
      1525115.62      6809711.84
#Sta/Elev= 30
    4031 1973.38  4069.4 1973.36  4118.1 1971.35  4170.6 1971.53  4213.4 1969.21
  4280.4 1969.19  4351.4 1966.94  4409.8 1967.28    4542  1964.9    4791 1963.56
  4796.8  1963.4  4804.8  1961.6  4833.8 1961.97  4849.3 1963.47  4892.1 1962.23
  4921.4 1963.33  4993.3 1963.23  5002.9 1963.06  5013.6 1959.29  5018.3 1959.29
  5025.8 1956.36  5026.3 1955.86  5034.3 1956.36  5037.8 1958.18  5052.2 1960.11
  5058.7 1964.32  5084.8 1964.16  5090.5 1964.12  5357.9 1964.75  5738.1 1962.98
#Mann= 6 ,-1 , 0
    4031     .07       0  5025.8     .07       0  5034.3     .07       0
  5084.8    .045       0  5090.5     .07       0  5357.9    .045       0
Bank Sta=5025.8,5034.3
XS Rating Curve= 0 ,0
Exp/Cntr=0.3,0.1

Type RM Length L Ch R = 1 ,107544  ,282,282,282
BEGIN DESCRIPTION:
Little Elm Creek 107544.45
END DESCRIPTION:
XS GIS Cut Line= 3
      1524161.76      6811188.43      1524870.13      6810480.06
      1525418.85      6809883.12
#Sta/Elev= 30
  4014.5 1973.64  4073.7 1973.21  4130.2 1971.06  4165.6 1971.27  4200.9  1969.5
  4257.5 1969.06  4321.1 1966.82  4349.4 1967.32  4413.1 1965.09    4505 1964.76
  4512.1  1963.8  4540.3 1963.02  4858.5 1961.11  4879.8 1958.21  4915.1 1960.27
  4936.3  1959.3  4985.8 1961.28  5009.9 1956.03  5010.4 1955.53  5018.4 1956.03
  5028.4 1957.49  5042.5 1957.72  5049.3 1958.44  5056.7 1960.74  5085.1 1963.03
  5165.6 1961.98  5480.9 1961.64  5488.3 1962.25  5580.2 1960.92  5827.1 1960.41
#Mann= 4 ,-1 , 0
  4014.5     .07       0  5009.9     .07       0  5018.4     .07       0
  5165.6    .045       0
Bank Sta=5009.9,5018.4
XS Rating Curve= 0 ,0
Exp/Cntr=0.3,0.1

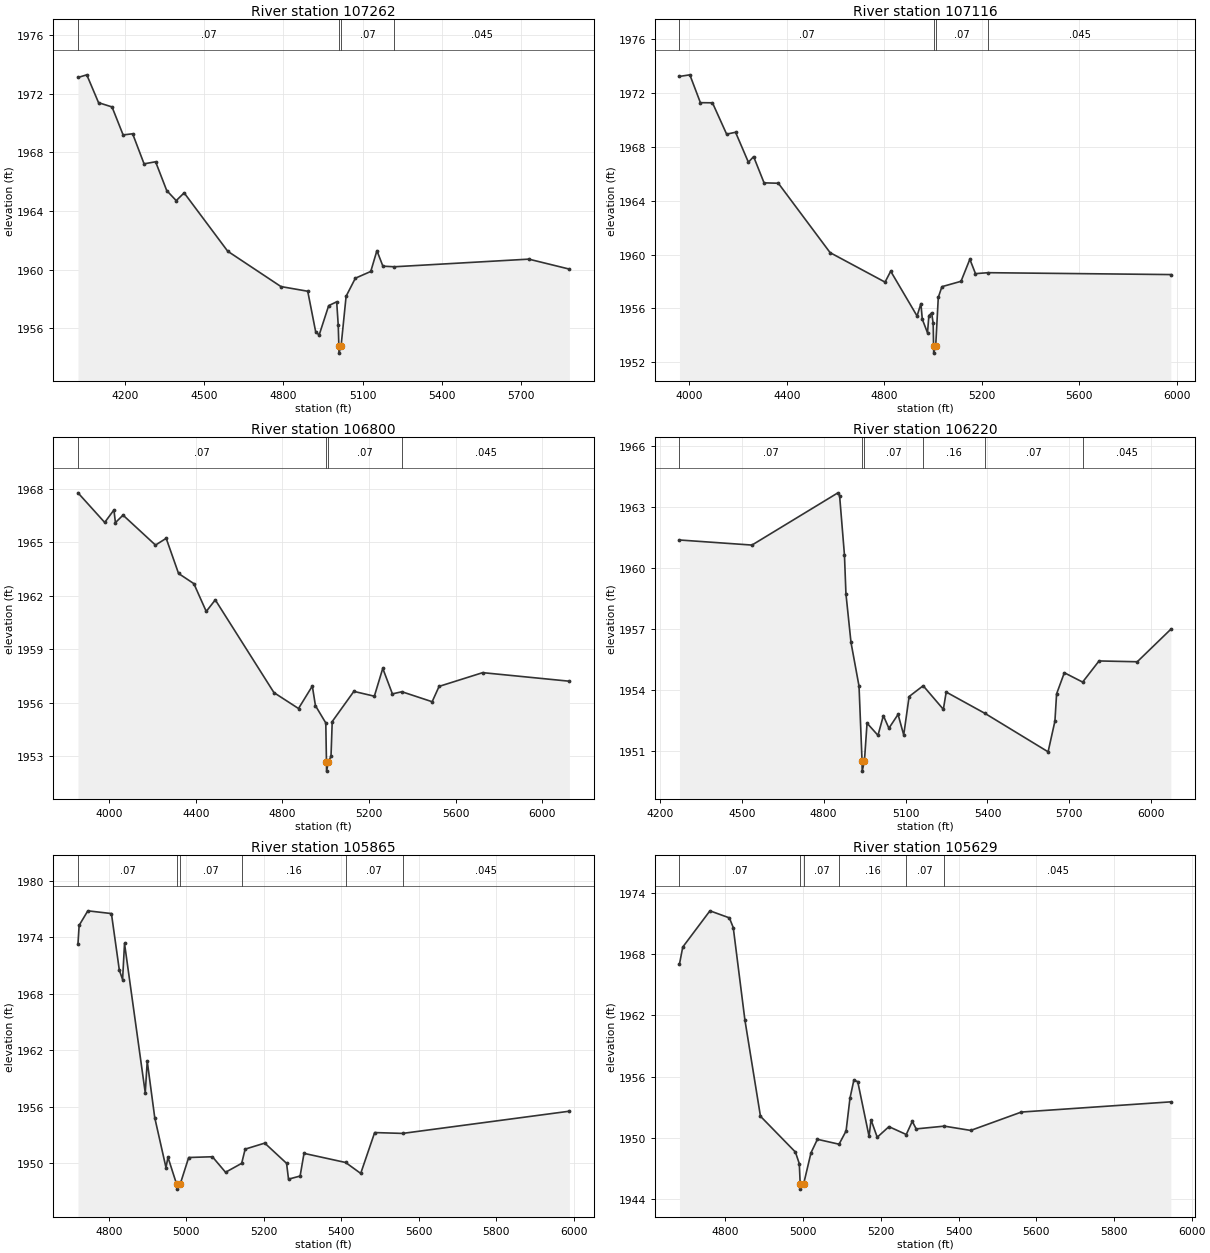
Type RM Length L Ch R = 1 ,107262  ,146,146,146
BEGIN DESCRIPTION:
Little Elm Creek 107260.92
END DESCRIPTION:
XS GIS Cut Line= 3
      1524217.35      6811257.84       1525022.9      6810716.18
      1525479.77      6809952.66
#Sta/Elev= 30
    4022 1973.11  4055.3 1973.29  4099.9 1971.39  4150.9  1971.1  4192.9 1969.19
  4228.9 1969.27  4272.2 1967.22  4315.9 1967.36  4357.9  1965.4  4393.9 1964.71
  4423.9 1965.24  4588.9 1961.26  4790.4 1958.85  4891.9 1958.53  4921.8 1955.78
    4935 1955.54  4971.2 1957.55  5001.5 1957.81  5007.3 1956.23  5009.7 1954.81
  5010.2 1954.31  5018.2 1954.81  5037.2 1958.19  5072.2 1959.42  5130.5 1959.88
  5153.8  1961.3  5176.5 1960.24    5220  1960.2  5728.9 1960.72  5882.5 1960.04
#Mann= 4 ,-1 , 0
    4022     .07       0  5009.7     .07       0  5018.2     .07       0
    5220    .045       0
Bank Sta=5009.7,5018.2
XS Rating Curve= 0 ,0
Exp/Cntr=0.3,0.1

Type RM Length L Ch R = 1 ,107116  ,316,316,316
BEGIN DESCRIPTION:
Little Elm Creek 107115.65
END DESCRIPTION:
XS GIS Cut Line= 3
      1524238.21       6811348.1      1525120.13      6810827.29
      1525676.25      6810004.29
#Sta/Elev= 30
  3959.1 1973.25  4001.8 1973.37  4045.1  1971.3  4094.7 1971.29  4152.8 1968.96
  4189.5  1969.1  4242.2 1966.87  4263.6 1967.29  4306.5 1965.34  4365.1 1965.31
  4577.7 1960.15  4803.2 1957.96  4826.4 1958.77  4934.7 1955.44  4950.4 1956.36
  4956.2  1955.2  4977.6 1954.19  4983.2 1955.47  4994.5 1955.67  5000.8 1954.91
  5002.5 1953.18    5003 1952.68  5011.1 1953.18  5021.8 1956.82  5036.7 1957.62
  5115.2 1958.02  5151.4 1959.66  5174.5 1958.59  5226.5 1958.66  5976.6 1958.52
#Mann= 4 ,-1 , 0
  3959.1     .07       0  5002.5     .07       0  5011.1     .07       0
  5226.5    .045       0
Bank Sta=5002.5,5011.1
XS Rating Curve= 0 ,0
Exp/Cntr=0.3,0.1

Type RM Length L Ch R = 1 ,106800  ,580,580,580
BEGIN DESCRIPTION:
Little Elm Creek 106799.89
END DESCRIPTION:
XS GIS Cut Line= 3
      1524377.07       6811813.4      1525259.01      6811084.23
      1525769.39      6810081.93
#Sta/Elev= 30
  3856.2 1967.78  3979.6 1966.12  4022.2 1966.82  4029.1 1966.11  4064.2 1966.53
  4214.1 1964.85  4263.5 1965.23  4320.6 1963.26  4391.2 1962.69  4448.5 1961.13
  4490.2 1961.78  4761.2 1956.58  4874.5 1955.69  4938.3 1956.95  4952.7 1955.85
  5000.5 1954.88  5003.6 1952.68  5004.1 1952.18  5012.2 1952.68  5024.6 1953.02
  5030.2 1954.96  5130.1 1956.65  5224.7 1956.38  5263.6 1957.94  5308.1 1956.51
  5351.9 1956.63  5491.6 1956.07  5523.7 1956.93    5725  1957.7  6125.3 1957.22
#Mann= 4 ,-1 , 0
  3856.2     .07       0  5003.6     .07       0  5012.2     .07       0
  5351.9    .045       0
Bank Sta=5003.6,5012.2
XS Rating Curve= 0 ,0
Exp/Cntr=0.3,0.1

Type RM Length L Ch R = 1 ,106220  ,355,355,355
BEGIN DESCRIPTION:
Little Elm Creek 106219.94
END DESCRIPTION:
XS GIS Cut Line= 3
      1525120.13      6812250.88      1525404.85      6811556.45
      1525682.58       6810544.4
#Sta/Elev= 30
  4271.8 1961.39  4537.4 1961.14  4852.3 1963.71  4858.5 1963.56  4876.2 1960.66
  4881.7 1958.74  4900.2 1956.35  4929.6  1954.2  4940.7 1950.52  4941.2 1950.02
  4949.4 1950.52    4959 1952.38    4999 1951.78  5018.8 1952.75    5039 1952.13
  5072.6 1952.81  5093.3  1951.8  5113.1 1953.69  5164.6 1954.22  5238.5 1953.06
  5248.9 1953.91    5391 1952.86  5622.2 1950.97  5647.2 1952.48  5653.3 1953.82
  5681.7 1954.86  5748.7  1954.4  5808.8 1955.44  5948.8  1955.4  6071.8    1957
#Mann= 6 ,-1 , 0
  4271.8     .07       0  4940.7     .07       0  4949.4     .07       0
  5164.6     .16       0    5391     .07       0  5748.7    .045       0
Bank Sta=4940.7,4949.4
XS Rating Curve= 0 ,0
Exp/Cntr=0.3,0.1

Type RM Length L Ch R = 1 ,105865  ,236,236,236
BEGIN DESCRIPTION:
Little Elm Creek 105864.72
END DESCRIPTION:
XS GIS Cut Line= 3
      1525628.92      6811762.96      1525682.63      6811466.18
      1525834.93      6810511.75
#Sta/Elev= 30
  4720.6 1973.31  4723.6 1975.26    4746  1976.8  4806.9 1976.51  4827.3  1970.5
  4835.7  1969.5  4840.7 1973.33  4894.2 1957.46  4899.3 1960.83  4918.7 1954.82
  4947.7 1949.52  4952.8 1950.62  4975.3 1947.73  4975.8 1947.23  4984.1 1947.73
  5006.3 1950.59  5067.5 1950.67  5101.4 1949.02    5143 1949.97    5152 1951.48
  5202.6 1952.12  5258.9 1949.97  5263.9 1948.29  5293.8 1948.62  5303.9 1951.03
  5411.3 1950.06  5450.2  1948.9  5486.2 1953.24  5558.3 1953.15  5988.7 1955.51
#Mann= 6 ,-1 , 0
  4720.6     .07       0  4975.3     .07       0  4984.1     .07       0
    5143     .16       0  5411.3     .07       0  5558.3    .045       0
Bank Sta=4975.3,4984.1
XS Rating Curve= 0 ,0
Exp/Cntr=0.3,0.1

Type RM Length L Ch R = 1 ,105629  ,1115,1115,1115
BEGIN DESCRIPTION:
Little Elm Creek 105629.04
END DESCRIPTION:
XS GIS Cut Line= 3
      1525880.03      6811706.54      1525877.07      6811389.79
      1525946.93      6810444.33
#Sta/Elev= 30
  4681.6    1967  4690.1 1968.68  4760.1 1972.23  4810.1 1971.54  4820.1 1970.59
  4850.1 1961.53  4890.1 1952.11  4980.1  1948.6  4990.1 1947.46  4992.4 1945.47
  4992.9 1944.97  5001.2 1945.47  5020.2 1948.53  5036.7 1949.85  5092.4 1949.37
  5110.5 1950.67  5120.5 1953.87  5130.5 1955.64  5140.5  1955.5  5169.7 1950.13
  5174.7 1951.76  5190.7 1950.05  5220.8 1951.09  5265.4 1950.32  5280.9 1951.61
  5290.9 1950.87  5363.4 1951.14  5431.3 1950.72  5561.7 1952.52  5946.4 1953.52
#Mann= 6 ,-1 , 0
  4681.6     .07       0  4992.4     .07       0  5001.2     .07       0
  5092.4     .16       0  5265.4     .07       0  5363.4    .045       0
Bank Sta=4992.4,5001.2
XS Rating Curve= 0 ,0
Exp/Cntr=0.3,0.1

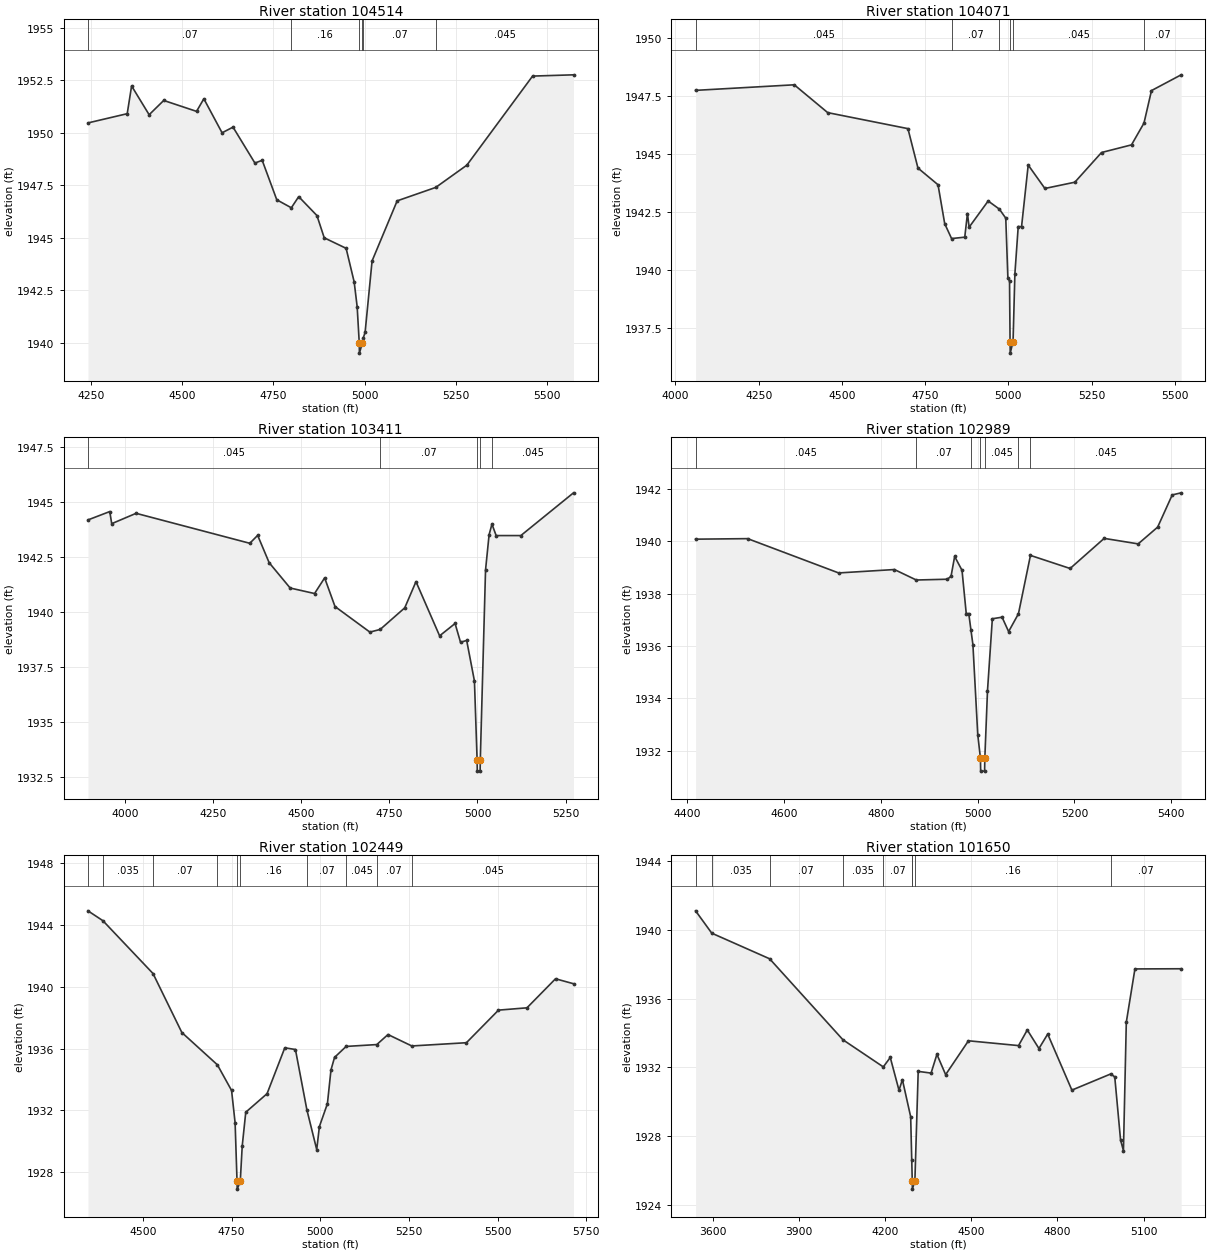
Type RM Length L Ch R = 1 ,104514  ,443,443,443
BEGIN DESCRIPTION:
Little Elm Creek 104513.75
END DESCRIPTION:
XS GIS Cut Line= 3
      1526372.63      6811595.71      1526356.24      6810868.95
      1526227.52      6810278.36
#Sta/Elev= 30
  4241.4 1950.46  4349.1  1950.9  4361.1 1952.22  4409.2 1950.85  4449.2 1951.53
  4539.2 1951.01  4559.2 1951.61  4609.2 1949.99  4639.2 1950.26  4699.2 1948.55
  4719.2 1948.68  4759.2  1946.8  4799.1 1946.42  4819.3 1946.95  4869.3 1946.05
  4889.3 1944.99  4949.3 1944.49  4971.4 1942.89  4979.6 1941.71  4985.3    1940
  4985.8  1939.5  4994.2    1940  4995.9  1940.2  5001.4 1940.49  5020.5 1943.89
  5089.3 1946.75  5195.1 1947.39  5280.4 1948.45  5460.6 1952.69  5572.8 1952.75
#Mann= 6 ,-1 , 0
  4241.4     .07       0  4799.1     .16       0  4985.3     .07       0
  4994.2     .16       0  4995.9     .07       0  5195.1    .045       0
Bank Sta=4985.3,4994.2
XS Rating Curve= 0 ,0
Exp/Cntr=0.3,0.1

Type RM Length L Ch R = 1 ,104071  ,660,660,660
BEGIN DESCRIPTION:
Little Elm Creek 104071
END DESCRIPTION:
XS GIS Cut Line= 3
      1526623.96      6811623.14       1526710.4      6810695.34
      1526689.68      6810168.97
#Sta/Elev= 30
  4060.6 1947.73    4357 1947.97  4457.5 1946.77  4698.5 1946.08  4728.6 1944.38
  4788.9 1943.66    4809 1941.98  4829.6 1941.34  4869.2  1941.4  4877.3 1942.42
  4882.3 1941.83  4939.5 1942.96  4973.1 1942.61  4992.4 1942.22  4998.7 1939.66
  5003.7  1939.5  5005.3  1936.9  5005.8  1936.4  5014.3  1936.9  5019.8 1939.82
  5029.8 1941.86  5039.8 1941.85  5059.8 1944.51  5109.9  1943.5  5199.9 1943.77
    5280 1945.05  5370.1 1945.38  5407.6 1946.32  5430.1 1947.72  5519.2  1948.4
#Mann= 6 ,-1 , 0
  4060.6    .045       0  4829.6     .07       0  4973.1    .045       0
  5005.3    .045       0  5014.3    .045       0  5407.6     .07       0
Bank Sta=5005.3,5014.3
XS Rating Curve= 0 ,0
Exp/Cntr=0.3,0.1

Type RM Length L Ch R = 1 ,103411  ,422,422,422
BEGIN DESCRIPTION:
Little Elm Creek 103410.96
END DESCRIPTION:
XS GIS Cut Line= 3
      1526832.75      6811645.88      1527293.74      6810632.84
      1527305.34      6810368.79
#Sta/Elev= 30
  3895.1 1944.18    3957 1944.56  3962.5 1944.01  4031.7 1944.48  4354.2 1943.12
  4376.5 1943.48  4409.1 1942.24  4468.7 1941.09  4537.9 1940.84  4566.5 1941.55
  4595.9 1940.25  4694.8 1939.09    4724 1939.21  4793.7 1940.19  4825.6 1941.38
  4892.6 1938.92  4936.5 1939.48  4951.9 1938.63  4969.4 1938.71  4991.4 1936.87
    4999 1933.28  4999.5 1932.78  5007.5 1932.78    5008 1933.28  5022.9 1941.91
    5033 1943.51  5041.1 1943.99    5053 1943.47    5123 1943.47  5272.4 1945.41
#Mann= 5 ,-1 , 0
  3895.1    .045       0    4724     .07       0    4999     .07       0
    5008     .07       0  5041.1    .045       0
Bank Sta=4999,5008
XS Rating Curve= 0 ,0
Exp/Cntr=0.3,0.1

Type RM Length L Ch R = 1 ,102989  ,540,540,540
BEGIN DESCRIPTION:
Little Elm Creek 102988.99
END DESCRIPTION:
XS GIS Cut Line= 3
      1527221.51      6811452.63       1527522.9      6810980.06
      1527560.17      6810539.64
#Sta/Elev= 30
  4417.8 1940.08  4525.3  1940.1  4713.2 1938.79  4828.3 1938.92  4873.5 1938.52
  4937.5 1938.55  4945.2 1938.66  4952.7 1939.42  4967.9 1938.89  4976.6 1937.24
  4981.8 1937.24  4986.4  1936.6  4990.4 1936.05  5000.4 1932.61  5005.9 1931.72
  5006.4 1931.22  5014.5 1931.22    5015 1931.72  5020.5 1934.29  5030.5 1937.04
  5050.6  1937.1  5064.1 1936.55  5084.4 1937.23  5109.2 1939.46  5191.1 1938.96
  5261.4 1940.11  5331.6  1939.9  5371.8 1940.54  5401.9 1941.77  5420.3 1941.85
#Mann= 7 ,-1 , 0
  4417.8    .045       0  4873.5     .07       0  4986.4    .045       0
  5005.9    .045       0    5015    .045       0  5084.4     .07       0
  5109.2    .045       0
Bank Sta=5005.9,5015
XS Rating Curve= 0 ,0
Exp/Cntr=0.3,0.1

Type RM Length L Ch R = 1 ,102449  ,799,799,799
BEGIN DESCRIPTION:
Little Elm Creek 102448.625
END DESCRIPTION:
XS GIS Cut Line= 3
      1527902.45      6811892.65      1527886.55      6811238.15
      1527819.26      6810527.52
#Sta/Elev= 30
  4345.3 1944.92  4387.5 1944.28  4528.7 1940.86    4610 1937.04  4710.1 1934.95
  4750.1 1933.29  4760.1 1931.19  4765.5  1927.4    4766  1926.9  4774.6  1927.4
  4780.1 1929.69  4790.1 1931.88  4850.1 1933.08  4900.1 1936.05  4930.1 1935.94
  4962.4 1932.03  4990.1 1929.46  4997.6 1930.95  5020.2 1932.43  5030.3 1934.62
  5040.3 1935.43    5073 1936.14  5159.4 1936.26    5191 1936.91    5258 1936.17
    5412 1936.38  5502.4 1938.49  5582.7 1938.64  5663.1 1940.52  5713.8  1940.2
#Mann= 10 ,-1 , 0
  4345.3     .07       0  4387.5    .035       0  4528.7     .07       0
  4710.1     .16       0  4765.5     .07       0  4774.6     .16       0
  4962.4     .07       0    5073    .045       0  5159.4     .07       0
    5258    .045       0
Bank Sta=4765.5,4774.6
XS Rating Curve= 0 ,0
Exp/Cntr=0.3,0.1

Type RM Length L Ch R = 1 ,101650  ,535,535,535
BEGIN DESCRIPTION:
Little Elm Creek 101650.274
END DESCRIPTION:
XS GIS Cut Line= 3
      1528148.82       6812125.7       1528397.9      6810674.51
       1528397.9      6810457.22
#Sta/Elev= 30
  3540.8 1941.11  3597.1 1939.81  3798.5 1938.32  4053.5 1933.61  4194.1 1932.03
  4218.3 1932.58  4248.7 1930.67  4260.5 1931.29  4289.3 1929.13    4293 1926.63
  4294.8 1925.42  4295.3 1924.92    4304 1925.42  4315.5 1931.77  4360.3 1931.67
  4380.6 1932.76    4411 1931.58  4490.4 1933.55  4664.7 1933.27  4695.1 1934.18
  4735.7  1933.1  4766.2 1933.94  4850.3 1930.68  4985.4 1931.62  4999.5 1931.45
  5019.7 1927.78  5029.7 1927.16  5039.7 1934.63  5069.7 1937.73  5230.5 1937.74
#Mann= 9 ,-1 , 0
  3540.8     .07       0  3597.1    .035       0  3798.5     .07       0
  4053.5    .035       0  4194.1     .07       0    4293     .16       0
  4294.8     .07       0    4304     .16       0  4985.4     .07       0
Bank Sta=4294.8,4304
XS Rating Curve= 0 ,0
Exp/Cntr=0.3,0.1

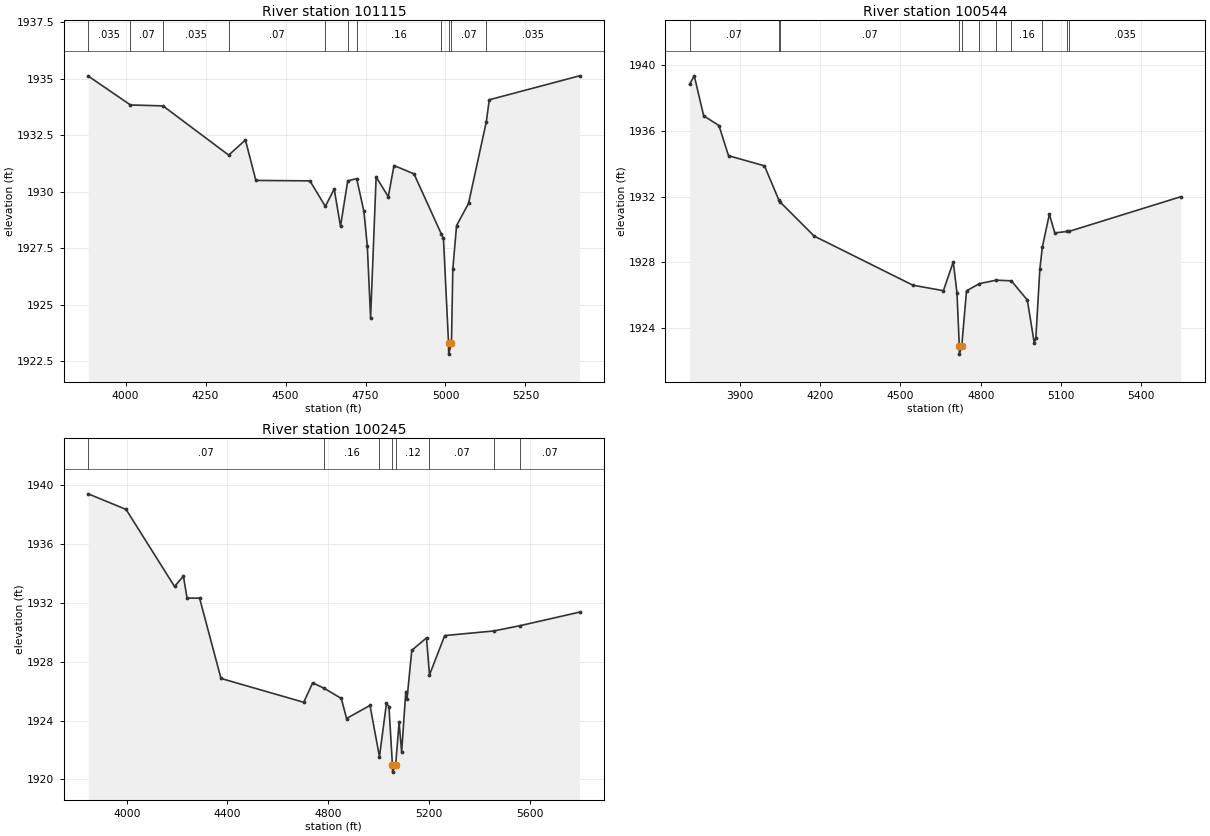
Type RM Length L Ch R = 1 ,101115  ,571,571,571
BEGIN DESCRIPTION:
Little Elm Creek 30.0
END DESCRIPTION:
XS GIS Cut Line= 3
      1528385.86      6812102.28      1528681.43      6811137.33
      1528793.35      6810622.25
#Sta/Elev= 30
  3882.9 1935.12    4015 1933.84  4116.6  1933.8  4322.2 1931.62  4374.4 1932.29
  4407.1  1930.5  4576.2 1930.48  4624.4 1929.35  4652.1 1930.12  4671.8 1928.47
  4694.4 1930.48  4722.3 1930.58    4745 1929.13  4755.7 1927.58  4765.9 1924.41
  4783.2 1930.65  4821.2 1929.78  4839.1 1931.16  4901.6 1930.79  4986.7 1928.14
  4993.7 1927.94  5009.6 1923.31  5010.1 1922.81  5018.8 1923.31    5023 1926.57
  5034.7  1928.5  5072.1 1929.48  5127.7 1933.09    5137 1934.07  5419.2 1935.13
#Mann= 11 ,-1 , 0
  3882.9    .035       0    4015     .07       0  4116.6    .035       0
  4322.2     .07       0  4624.4     .16       0  4694.4     .07       0
  4722.3     .16       0  4986.7     .07       0  5009.6     .07       0
  5018.8     .07       0  5127.7    .035       0
Bank Sta=5009.6,5018.8
XS Rating Curve= 0 ,0
Exp/Cntr=0.3,0.1

Type RM Length L Ch R = 1 ,100544  ,299,299,299
BEGIN DESCRIPTION:
Little Elm Creek 100543.727
END DESCRIPTION:
XS GIS Cut Line= 3
      1528396.17      6812243.15      1529207.31      6811243.82
      1529278.49      6810701.27
#Sta/Elev= 30
  3712.9 1938.84  3730.4 1939.36  3765.6 1936.92  3822.6 1936.33  3858.3 1934.49
  3992.6 1933.87  4045.9  1931.8  4049.4 1931.69    4178 1929.59  4547.2 1926.59
  4660.7 1926.26  4697.4 1928.01  4711.3 1926.14    4720 1922.89  4720.5 1922.39
  4729.2 1922.89  4746.9 1926.25  4795.3 1926.69  4857.8  1926.9  4914.3 1926.86
  4973.9 1925.69    5000 1923.06  5005.9  1923.4  5020.8 1927.59  5030.1 1928.92
  5056.3 1930.92  5076.5 1929.78  5121.9 1929.87  5128.9 1929.87  5547.2 1931.99
#Mann= 11 ,-1 , 0
  3712.9     .07       0  4045.9    .035       0  4049.4     .07       0
    4720     .07       0  4729.2     .07       0  4795.3     .16       0
  4857.8     .07       0  4914.3     .16       0  5030.1     .12       0
  5121.9     .07       0  5128.9    .035       0
Bank Sta=4720,4729.2
XS Rating Curve= 0 ,0
Exp/Cntr=0.3,0.1

Type RM Length L Ch R = 1 ,100245  ,626,626,626
BEGIN DESCRIPTION:
Little Elm Creek 100244.65
END DESCRIPTION:
XS GIS Cut Line= 3
      1528686.97       6812381.1      1529384.01      6811493.95
      1529481.91      6810676.52
#Sta/Elev= 30
  3847.1 1939.39  3997.5 1938.33    4190  1933.1  4225.2  1933.8  4239.7 1932.31
  4289.4 1932.31  4374.4 1926.86  4703.1 1925.24  4738.6 1926.56  4782.3 1926.21
  4852.4  1925.5  4873.3 1924.14  4966.3 1925.03  5003.9 1921.55  5031.7 1925.16
  5041.7 1924.95  5055.4    1921  5055.9  1920.5  5068.3    1921    5082 1923.88
  5092.1 1921.86  5108.5 1925.96  5113.5 1925.48  5132.4 1928.77  5190.8 1929.61
  5202.7  1927.1  5263.3 1929.77  5457.1 1930.08  5562.3 1930.44  5798.6 1931.36
#Mann= 8 ,-1 , 0
  3847.1     .07       0  4782.3     .16       0  5003.9     .12       0
  5055.4     .07       0  5068.3     .12       0  5202.7     .07       0
  5457.1    .035       0  5562.3     .07       0
Bank Sta=5055.4,5068.3
XS Rating Curve= 0 ,0
Exp/Cntr=0.3,0.1