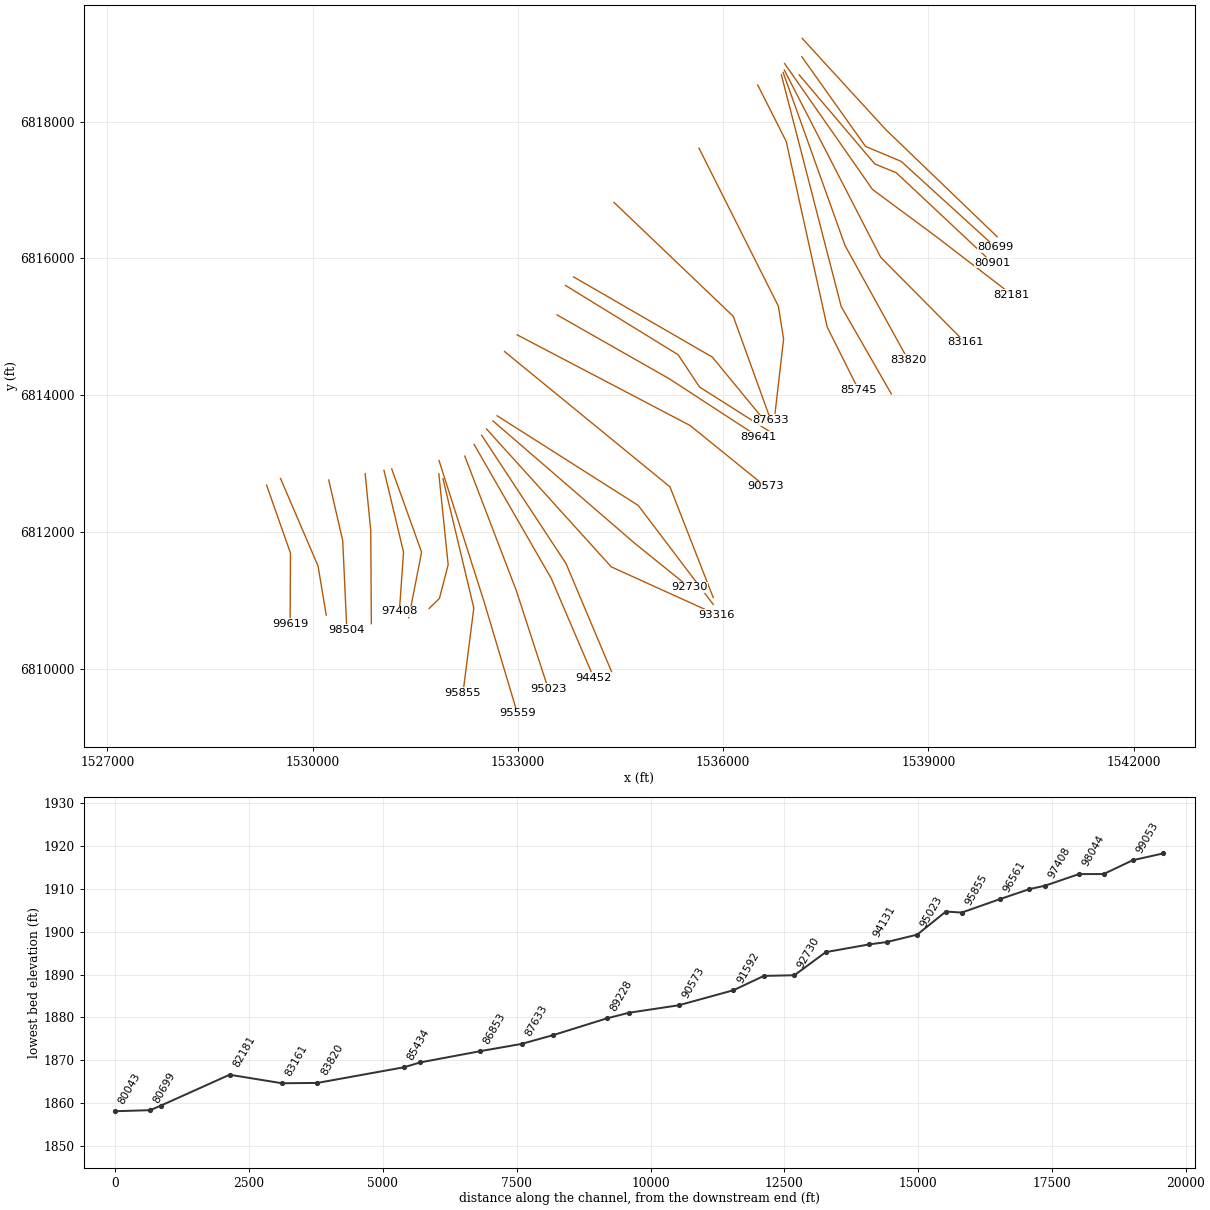
HEC-RAS study Little Elm Creek.prj: Little Elm Creek Base Level Engineering

--- Little Elm Creek.g01 (geometry) --- (continued)

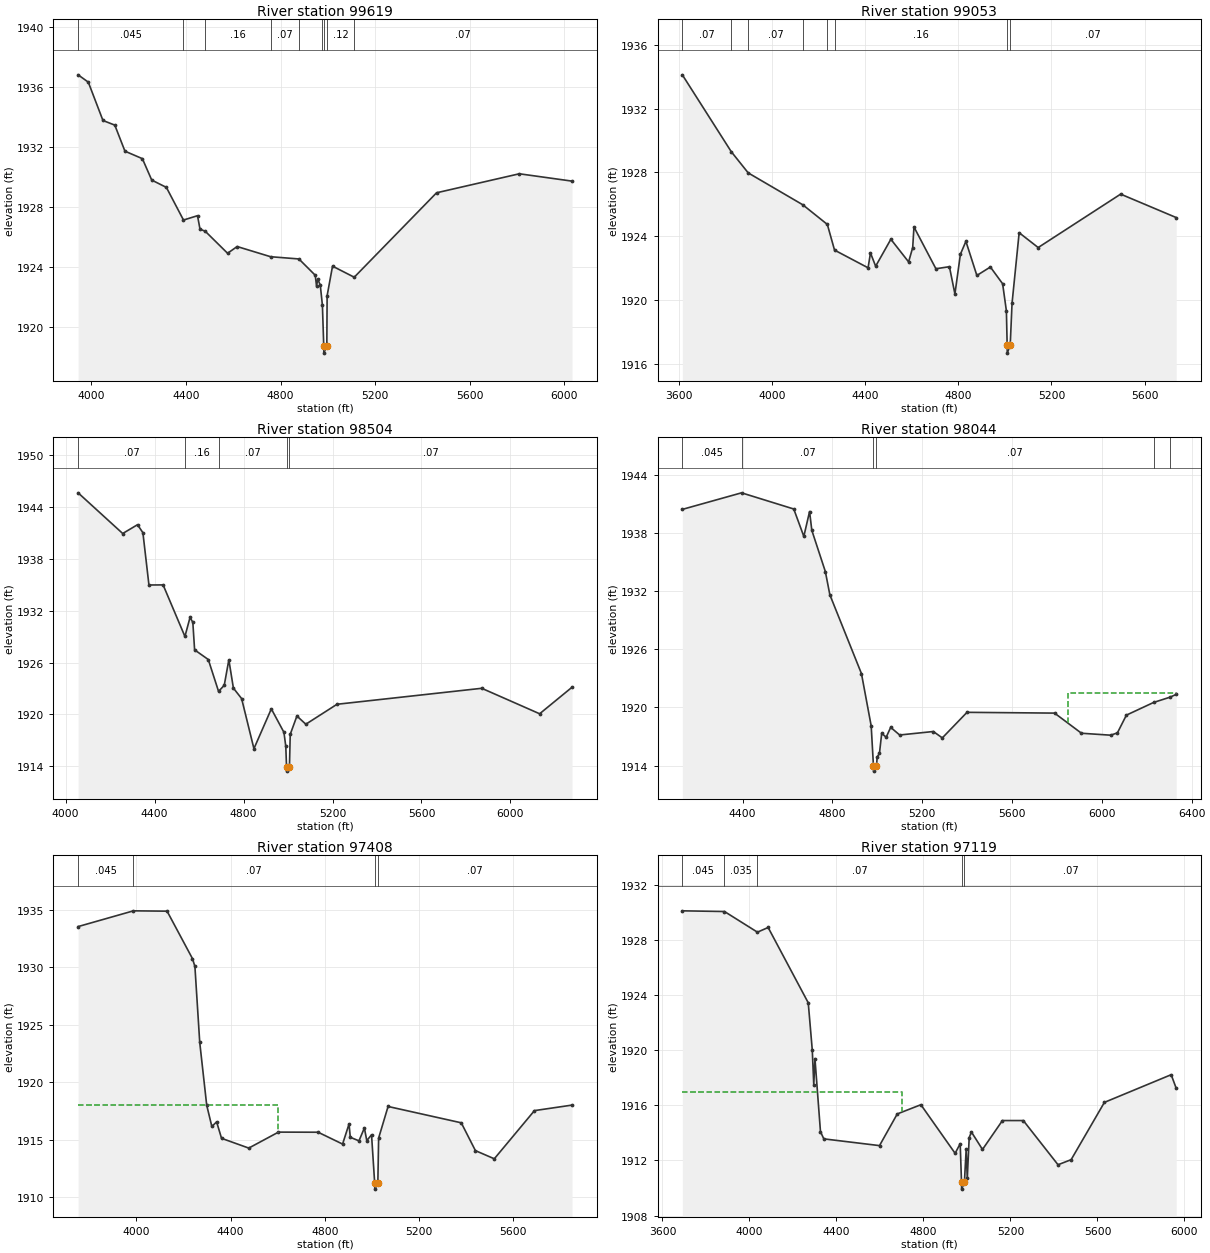
Type RM Length L Ch R = 1 ,99619   ,566,566,566
BEGIN DESCRIPTION:
Little Elm Creek 99618.94
END DESCRIPTION:
XS GIS Cut Line= 3
        1529326.      6812684.46      1529675.68       6811688.4
      1529670.13      6810655.07
#Sta/Elev= 30
  3943.6 1936.83  3986.7 1936.34  4048.7 1933.78  4098.8 1933.47  4141.7 1931.73
  4215.4 1931.23    4255  1929.8    4317 1929.31  4389.3 1927.13  4448.6 1927.42
  4459.2 1926.52  4481.4 1926.38  4575.8 1924.91  4616.3 1925.36  4757.7 1924.68
  4877.5 1924.53  4946.7 1923.44    4952 1922.72  4957.3 1923.18  4967.9 1922.78
  4976.9 1921.44  4982.5 1918.74    4983 1918.24  4995.6 1918.74  4996.8 1922.07
  5019.7 1924.05  5111.5 1923.31  5459.7 1928.95  5809.7 1930.22  6032.6 1929.73
#Mann= 9 ,-1 , 0
  3943.6    .045       0  4389.3     .07       0  4481.4     .16       0
  4757.7     .07       0  4877.5     .16       0  4976.9     .12       0
  4982.5     .07       0  4995.6     .12       0  5111.5     .07       0
Bank Sta=4982.5,4995.6
XS Rating Curve= 0 ,0
Exp/Cntr=0.3,0.1

Type RM Length L Ch R = 1 ,99053   ,549,549,549
BEGIN DESCRIPTION:
Little Elm Creek 99052.73
END DESCRIPTION:
XS GIS Cut Line= 3
      1529529.76       6812781.2      1530078.46       6811500.9
      1530198.19      6810782.54
#Sta/Elev= 30
  3614.7 1934.12  3824.9  1929.3  3897.7 1927.97  4132.2 1925.97  4237.5 1924.74
  4268.4 1923.13  4412.4 1922.02  4422.8 1922.95    4445 1922.12  4510.3 1923.81
  4586.5 1922.39  4604.1 1923.29  4609.5 1924.58  4703.8 1921.96  4761.8 1922.09
  4785.4 1920.38    4809 1922.87  4832.6 1923.68  4879.7 1921.54  4937.7 1922.07
  4990.3 1921.02  5006.5 1919.32  5009.8 1917.17  5010.3 1916.67  5022.9 1917.17
  5030.8  1919.8  5061.3 1924.22    5143 1923.29  5497.2 1926.64  5735.9 1925.17
#Mann= 8 ,-1 , 0
  3614.7     .07       0  3824.9    .045       0  3897.7     .07       0
  4132.2     .16       0  4237.5     .07       0  4268.4     .16       0
  5009.8     .07       0  5022.9     .07       0
Bank Sta=5009.8,5022.9
XS Rating Curve= 0 ,0
Exp/Cntr=0.3,0.1

Type RM Length L Ch R = 1 ,98504   ,460,460,460
BEGIN DESCRIPTION:
Little Elm Creek 98504.59
END DESCRIPTION:
XS GIS Cut Line= 3
      1530235.06      6812758.34      1530439.57      6811868.95
      1530499.21      6810562.61
#Sta/Elev= 30
  4056.4 1945.65  4256.9 1940.94  4323.5 1941.96  4347.7 1941.03  4374.8 1934.98
  4438.5 1934.99  4536.6 1929.02  4559.5 1931.22  4572.1 1930.66  4580.1 1927.47
  4641.6 1926.35  4687.8 1922.66  4713.4 1923.37    4734 1926.32  4754.5 1923.04
  4791.4 1921.83  4846.8 1916.03    4925 1920.64  4981.7 1917.92    4990  1916.3
  4993.4 1913.93  4993.9 1913.43  5006.5 1913.93    5010 1917.69    5040 1919.81
  5080.1 1918.86  5220.2 1921.17  5870.9 1923.02  6131.2 1920.07  6276.7 1923.14
#Mann= 5 ,-1 , 0
  4056.4     .07       0  4536.6     .16       0  4687.8     .07       0
  4993.4     .07       0  5006.5     .07       0
Bank Sta=4993.4,5006.5
XS Rating Curve= 0 ,0
Exp/Cntr=0.3,0.1

Type RM Length L Ch R = 1 ,98044   ,636,636,636
BEGIN DESCRIPTION:
Little Elm Creek 98044.05
END DESCRIPTION:
XS GIS Cut Line= 3
      1530767.29      6812852.06      1530849.29      6812014.79
      1530857.69      6810655.99
#Sta/Elev= 30
  4131.2 1940.44    4395 1942.15  4627.6 1940.48  4672.4 1937.65    4698 1940.22
    4708 1938.28  4768.3 1934.02  4788.4 1931.62  4929.1 1923.49  4972.5 1918.09
  4982.7 1913.92  4983.2 1913.42  4995.9 1913.92  4999.3 1914.89  5009.3 1915.25
  5019.3 1917.32  5039.3 1916.92  5059.3 1917.94  5099.3 1917.15  5249.3 1917.51
  5289.3 1916.85  5399.3 1919.49  5789.3 1919.41  5909.3 1917.33  6039.3 1917.13
  6069.3 1917.37  6109.3  1919.2  6230.6 1920.51  6303.1 1921.05  6331.3 1921.34
#Mann= 6 ,-1 , 0
  4131.2    .045       0    4395     .07       0  4982.7     .07       0
  4995.9     .07       0  6230.6    .035       0  6303.1     .07       0
#XS Ineff= 2 , 0
       0                    5850       0  1921.5
Permanent Ineff=
       F       F
Bank Sta=4982.7,4995.9
XS Rating Curve= 0 ,0
Exp/Cntr=0.3,0.1

Type RM Length L Ch R = 1 ,97408   ,289,289,289
BEGIN DESCRIPTION:
Little Elm Creek 97407.86
END DESCRIPTION:
XS GIS Cut Line= 3
      1531042.19      6812900.38      1531328.46      6811702.29
      1531267.65      6810838.85
#Sta/Elev= 30
  3752.4 1933.54  3987.5 1934.91  4130.2 1934.88  4238.1 1930.75  4248.4 1930.07
  4268.9 1923.46  4298.5    1918  4320.3 1916.15  4340.6 1916.55  4361.5 1915.12
  4477.1 1914.27  4603.3 1915.66  4771.6 1915.65  4875.5 1914.62    4903 1916.37
  4908.2 1915.21  4945.1  1914.9  4968.1 1916.02  4978.3 1914.92  4998.5 1915.43
  5011.9  1911.2  5012.4  1910.7  5025.2  1911.2  5028.6 1915.14  5068.7 1917.89
  5379.5 1916.47  5439.6 1914.05  5519.8 1913.34  5690.3 1917.53  5849.8 1918.01
#Mann= 4 ,-1 , 0
  3752.4    .045       0  3987.5     .07       0  5011.9     .07       0
  5025.2     .07       0
#XS Ineff= 2 , 0
       0    4600    1918               0
Permanent Ineff=
       F       F
Bank Sta=5011.9,5025.2
XS Rating Curve= 0 ,0
Exp/Cntr=0.3,0.1

Type RM Length L Ch R = 1 ,97119   ,558,558,558
BEGIN DESCRIPTION:
Little Elm Creek 97118.72
END DESCRIPTION:
XS GIS Cut Line= 3
      1531155.38      6812920.33      1531592.35      6811702.29
      1531404.84      6810743.91
#Sta/Elev= 30
  3691.4 1930.13  3885.2 1930.08  4036.6 1928.58  4085.9 1928.92  4270.3 1923.45
  4288.8 1920.02  4295.7  1917.5  4301.1  1919.4  4326.5 1914.09  4341.9 1913.57
  4597.9 1913.08  4679.5 1915.38  4788.1 1916.05  4945.5 1912.52  4968.8 1913.22
  4974.9 1910.42  4975.4 1909.92  4988.2 1910.42  4996.3 1912.82  5001.4  1910.7
  5010.2 1913.66  5020.4 1914.07  5071.3  1912.8    5163  1914.9    5259  1914.9
  5418.6 1911.69  5478.9 1912.06  5631.8 1916.22  5938.8 1918.23    5962 1917.24
#Mann= 5 ,-1 , 0
  3691.4    .045       0  3885.2    .035       0  4036.6     .07       0
  4974.9     .07       0  4988.2     .07       0
#XS Ineff= 2 , 0
       0    4700    1917               0
Permanent Ineff=
       F       F
Bank Sta=4974.9,4988.2
XS Rating Curve= 0 ,0
Exp/Cntr=0.3,0.1

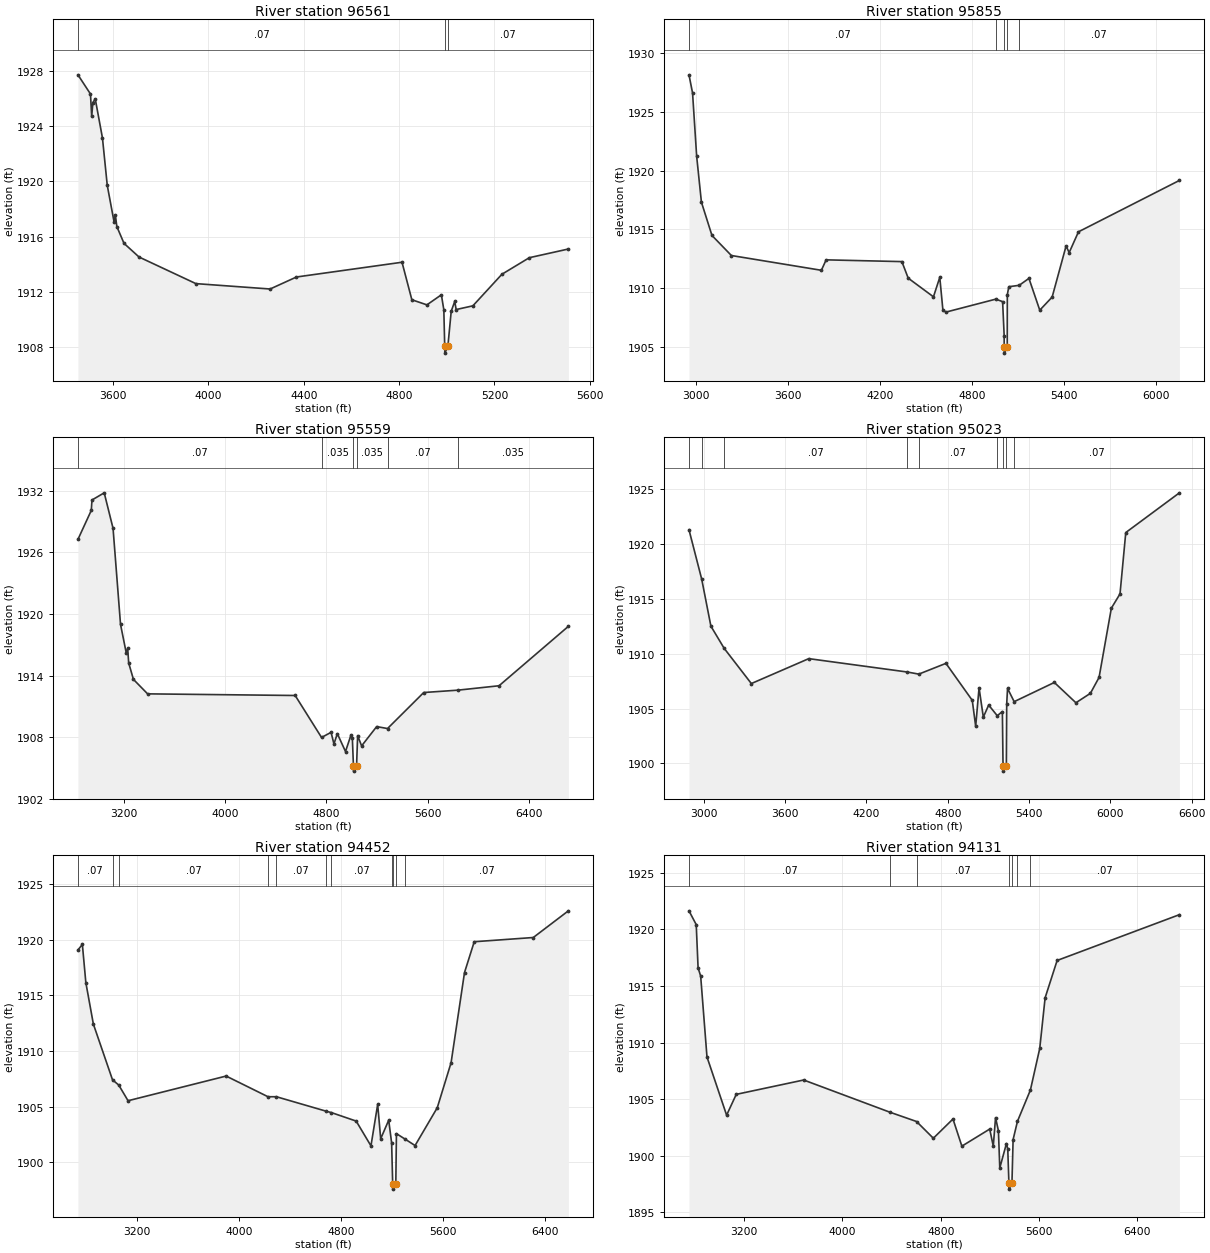
Type RM Length L Ch R = 1 ,96561   ,706,706,706
BEGIN DESCRIPTION:
Little Elm Creek 25.0
END DESCRIPTION:
XS GIS Cut Line= 4
      1531844.11      6812850.33      1531980.53      6811518.71
      1531853.23      6811026.01       1531702.9      6810878.33
#Sta/Elev= 30
  3452.1 1927.73  3504.7 1926.34  3509.8 1924.71  3514.8 1925.72  3524.8 1925.98
    3555 1923.15  3575.1 1919.72  3604.1 1917.03  3609.1 1917.57  3615.3 1916.73
  3645.4 1915.51  3708.4 1914.52    3947 1912.59  4258.6  1912.2  4369.2 1913.07
  4812.1 1914.14  4853.4 1911.42  4916.6 1911.05  4977.3 1911.78  4987.6 1910.69
  4991.3 1908.05  4991.8 1907.55  5004.6 1908.05  5018.6 1910.59  5033.4  1911.3
  5039.3 1910.71  5109.5 1910.98  5231.4 1913.27  5346.4 1914.47  5510.3  1915.1
#Mann= 3 ,-1 , 0
  3452.1     .07       0  4991.3     .07       0  5004.6     .07       0
Bank Sta=4991.3,5004.6
XS Rating Curve= 0 ,0
Exp/Cntr=0.3,0.1

Type RM Length L Ch R = 1 ,95855   ,296,296,296
BEGIN DESCRIPTION:
Little Elm Creek 95793.766
END DESCRIPTION:
XS GIS Cut Line= 3
      1531904.86      6812776.78      1532355.64      6810885.15
      1532197.87      6809645.85
#Sta/Elev= 30
  2957.3 1928.17  2980.6 1926.63  3007.4 1921.22  3038.3 1917.32    3107 1914.48
  3233.4 1912.77  3819.6 1911.51  3850.4  1912.4  4343.8 1912.25    4385 1910.84
  4549.4 1909.25  4590.6 1910.91  4611.1  1908.1  4631.7 1907.95  4954.8 1909.05
  4999.8 1908.84  5009.9 1905.94  5010.1 1904.95  5010.6 1904.45  5029.9 1904.95
  5030.4 1909.43  5040.2 1910.11  5107.8 1910.23  5171.2 1910.82  5241.8 1908.11
  5322.4 1909.23  5413.1 1913.58  5433.3 1913.02  5493.8 1914.79  6151.2 1919.17
#Mann= 5 ,-1 , 0
  2957.3     .07       0  4954.8    .035       0  5010.1    .035       0
  5029.9    .035       0  5107.8     .07       0
Bank Sta=5010.1,5029.9
XS Rating Curve= 0 ,0
Exp/Cntr=0.3,0.1

Type RM Length L Ch R = 1 ,95559   ,536,536,536
BEGIN DESCRIPTION:
Little Elm Creek 95559.28
END DESCRIPTION:
XS GIS Cut Line= 3
      1531847.52      6813042.08      1532509.01      6810966.18
      1532992.51      6809343.53
#Sta/Elev= 30
  2838.6 1927.27  2944.1  1930.1  2949.3 1931.11    3046 1931.81  3115.8 1928.35
  3174.8 1918.99  3220.7 1916.16  3231.2 1916.65  3239.2 1915.23  3276.7 1913.63
  3388.6 1912.22  4553.6 1912.06  4761.8 1907.97    4837 1908.47  4859.6 1907.34
  4886.5 1908.34    4951  1906.6  4994.4 1908.22  5004.9 1907.92  5013.7 1905.19
  5014.2 1904.69  5038.2 1905.19  5046.8 1908.15  5078.1 1907.15    5197 1909.03
  5282.7 1908.84  5568.5 1912.35  5838.4 1912.58  6163.2 1913.01  6710.5  1918.8
#Mann= 6 ,-1 , 0
  2838.6     .07       0  4761.8    .035       0  5013.7    .035       0
  5038.2    .035       0  5282.7     .07       0  5838.4    .035       0
Bank Sta=5013.7,5038.2
XS Rating Curve= 0 ,0
Exp/Cntr=0.3,0.1

Type RM Length L Ch R = 1 ,95023   ,571,571,571
BEGIN DESCRIPTION:
Little Elm Creek 95023.394
END DESCRIPTION:
XS GIS Cut Line= 3
      1532223.75      6813108.28      1532977.72      6811137.48
       1533443.9      6809701.35
#Sta/Elev= 30
  2889.9  1921.3  2983.9 1916.79  3051.7 1912.51  3149.6 1910.49  3350.2 1907.28
  3774.2 1909.55  4502.3 1908.33  4586.3 1908.14  4786.6 1909.12  4980.9 1905.75
  5006.1 1903.38    5031 1906.89  5062.5 1904.22  5101.9 1905.32  5165.4 1904.35
  5203.1 1904.73    5208  1899.8  5208.5  1899.3  5232.5  1899.8  5235.1 1905.43
  5241.3 1906.84  5290.1 1905.63  5586.7 1907.38  5745.9 1905.53  5852.9 1906.39
  5916.8 1907.84  6007.5 1914.15  6071.4 1915.45  6113.9 1921.04  6509.9 1924.66
#Mann= 9 ,-1 , 0
  2889.9     .07       0  2983.9    .035       0  3149.6     .07       0
  4502.3    .035       0  4586.3     .07       0  5165.4    .035       0
    5208     .07       0  5232.5    .035       0  5290.1     .07       0
Bank Sta=5208,5232.5
XS Rating Curve= 0 ,0
Exp/Cntr=0.3,0.1

Type RM Length L Ch R = 1 ,94452   ,321,321,321
BEGIN DESCRIPTION:
Little Elm Creek 94452.106
END DESCRIPTION:
XS GIS Cut Line= 3
      1532359.98      6813278.36      1533487.05      6811318.99
      1534109.46      6809863.16
#Sta/Elev= 30
  2739.6 1919.08  2774.3 1919.58  2801.6 1916.14  2860.6 1912.41  3010.6  1907.4
  3059.4 1906.93  3132.3 1905.52  3901.1 1907.74    4229 1905.88    4295 1905.88
  4681.5 1904.59  4726.7 1904.45  4920.2 1903.69    5036 1901.46  5088.7 1905.19
  5112.3  1902.1  5175.1 1903.77    5198 1901.73  5206.3 1898.07  5206.8 1897.57
  5230.8 1898.07  5235.7 1902.56  5303.3 1902.07  5381.7 1901.49  5555.7 1904.89
    5664 1908.94  5769.2 1917.05  5845.4 1919.82  6308.2  1920.2  6583.3  1922.6
#Mann= 11 ,-1 , 0
  2739.6     .07       0  3010.6    .035       0  3059.4     .07       0
    4229    .035       0    4295     .07       0  4681.5    .035       0
  4726.7     .07       0    5198    .035       0  5206.3     .07       0
  5230.8    .035       0  5303.3     .07       0
Bank Sta=5206.3,5230.8
XS Rating Curve= 0 ,0
Exp/Cntr=0.3,0.1

Type RM Length L Ch R = 1 ,94131   ,815,815,815
BEGIN DESCRIPTION:
Little Elm Creek 94131.21
END DESCRIPTION:
XS GIS Cut Line= 3
      1532468.81      6813414.18      1533703.46      6811535.62
      1534378.71       6809931.3
#Sta/Elev= 30
  2752.8 1921.65  2811.8 1920.43  2826.9 1916.61    2848 1915.87  2899.2 1908.73
  3058.9 1903.58  3137.2 1905.42  3685.6 1906.69  4384.8 1903.85  4603.4 1903.02
  4740.1 1901.54  4899.8 1903.24  4972.1 1900.84  5198.5 1902.35  5227.6 1900.84
    5246 1903.36  5269.4  1902.2  5280.5 1898.91  5334.5 1901.07  5345.4 1900.59
  5354.8 1897.54  5355.3 1897.04  5379.3 1897.54  5388.8 1901.42  5424.3 1903.04
  5529.4  1905.8  5605.4 1909.48  5649.2 1913.96  5746.8 1917.26  6741.4 1921.31
#Mann= 7 ,-1 , 0
  2752.8     .07       0  4384.8    .035       0  4603.4     .07       0
  5354.8     .07       0  5379.3     .07       0  5424.3    .035       0
  5529.4     .07       0
Bank Sta=5354.8,5379.3
XS Rating Curve= 0 ,0
Exp/Cntr=0.3,0.1

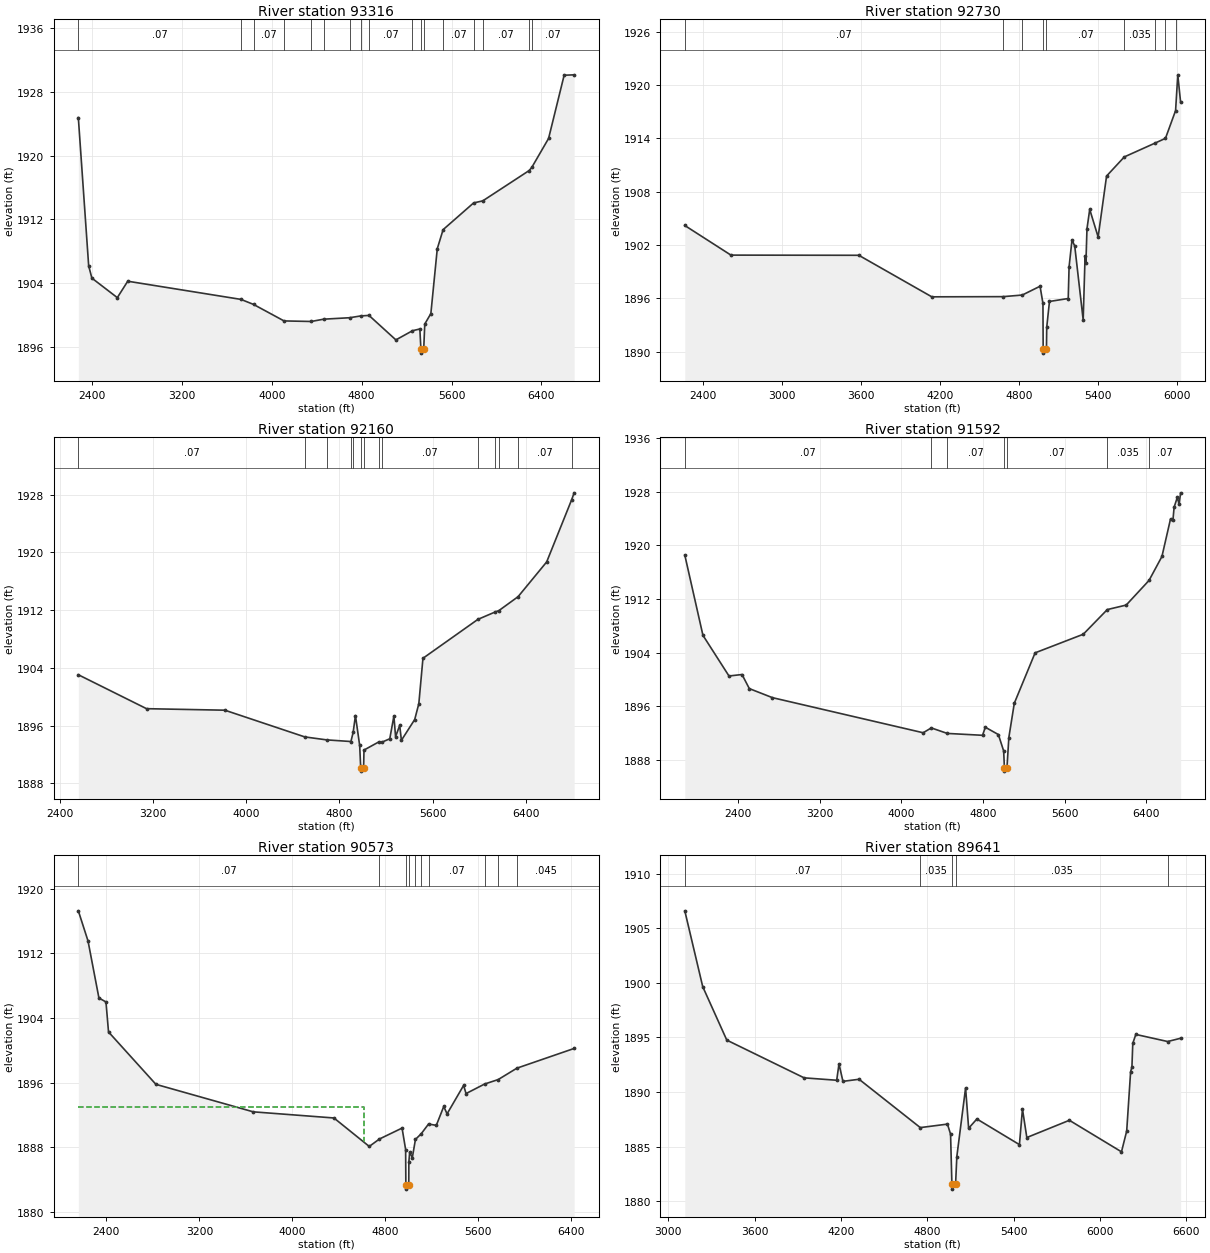
Type RM Length L Ch R = 1 ,93316   ,586,586,586
BEGIN DESCRIPTION:
Little Elm Creek 93316.093
END DESCRIPTION:
XS GIS Cut Line= 3
      1532541.51      6813504.83      1534365.51      6811486.78
      1535905.03      6810787.98
#Sta/Elev= 30
  2279.8 1924.77  2371.8 1906.18  2400.2 1904.64  2626.6 1902.19  2719.3 1904.25
  3726.7 1901.97  3838.3 1901.34  4109.7 1899.27  4351.3  1899.2    4463 1899.49
  4693.1 1899.67  4794.1  1899.9  4865.6 1899.96  5104.8 1896.89  5252.4 1898.04
  5317.9 1898.26  5327.4 1895.73  5327.9 1895.23  5352.3 1895.73  5361.8 1898.88
  5415.9 1900.19    5473 1908.33    5525 1910.72  5796.1 1914.07  5877.8 1914.33
  6290.2 1918.13  6313.9 1918.53  6463.2 1922.16  6601.6 1930.09  6690.7 1930.14
#Mann= 17 ,-1 , 0
  2279.8     .07       0  3726.7     .16       0  3838.3     .07       0
  4109.7    .035       0  4351.3     .07       0    4463    .035       0
  4693.1     .07       0  4794.1    .035       0  4865.6     .07       0
  5252.4    .035       0  5327.4     .07       0  5352.3    .035       0
    5525     .07       0  5796.1    .035       0  5877.8     .07       0
  6290.2    .035       0  6313.9     .07       0
Bank Sta=5327.4,5352.3
XS Rating Curve= 0 ,0
Exp/Cntr=0.3,0.1

Type RM Length L Ch R = 1 ,92730   ,570,570,570
BEGIN DESCRIPTION:
Little Elm Creek 92729.902
END DESCRIPTION:
XS GIS Cut Line= 3
      1532635.96      6813622.82      1534707.47      6811832.43
      1535505.04      6811187.97
#Sta/Elev= 30
    2262 1904.19  2612.2 1900.86    3583 1900.84  4136.9 1896.17  4678.1 1896.19
  4823.3 1896.37  4958.5 1897.36  4980.4 1895.43  4982.1 1890.34  4982.6 1889.84
  5007.1 1890.34  5009.1 1892.74  5029.9 1895.65  5172.3 1895.98  5178.7 1899.53
    5201 1902.58  5221.8 1901.87  5285.8 1893.57  5300.2 1900.76  5306.6 1900.01
  5314.6 1903.82  5335.4    1906  5399.3  1902.9  5463.3 1909.75  5597.9  1911.9
  5832.3 1913.46  5910.4 1913.99  5987.2 1917.11  6003.8 1921.13  6025.4 1918.04
#Mann= 9 ,-1 , 0
    2262     .07       0  4678.1    .035       0  4823.3     .07       0
  4982.1     .07       0  5007.1     .07       0  5597.9    .035       0
  5832.3     .07       0  5910.4    .035       0  5987.2     .07       0
Bank Sta=4982.1,5007.1
XS Rating Curve= 0 ,0
Exp/Cntr=0.3,0.1

Type RM Length L Ch R = 1 ,92160   ,568,568,568
BEGIN DESCRIPTION:
Little Elm Creek 92160.123
END DESCRIPTION:
XS GIS Cut Line= 3
      1532696.38      6813698.08      1534758.54      6812386.54
      1535854.98      6810938.02
#Sta/Elev= 30
  2556.1 1903.04  3142.2 1898.34  3815.3 1898.13  4501.8 1894.43    4689 1894.02
  4898.4 1893.79  4917.5 1895.05  4937.3 1897.39  4973.7 1893.24  4982.4 1890.19
  4982.9 1889.69  5007.5 1890.19  5010.7 1892.61  5136.3 1893.72  5163.5 1893.69
  5232.3 1894.17  5267.7 1897.32  5282.2 1894.46  5317.6 1896.03  5332.2 1893.96
  5446.6 1896.84    5482 1899.04  5517.4 1905.32  5989.5 1910.71  6134.4 1911.71
  6169.3 1911.92  6334.6 1913.85  6580.6 1918.67  6794.1 1927.24  6816.7 1928.24
#Mann= 14 ,-1 , 0
  2556.1     .07       0  4501.8     .16       0    4689     .07       0
  4898.4    .035       0  4917.5     .07       0  4982.4     .07       0
  5007.5     .07       0  5136.3    .035       0  5163.5     .07       0
  5989.5    .035       0  6134.4     .07       0  6169.3    .035       0
  6334.6     .07       0  6794.1    .035       0
Bank Sta=4982.4,5007.5
XS Rating Curve= 0 ,0
Exp/Cntr=0.3,0.1

Type RM Length L Ch R = 1 ,91592   ,1019,1019,1019
BEGIN DESCRIPTION:
Little Elm Creek 91591.516
END DESCRIPTION:
XS GIS Cut Line= 3
        1532805.        6814638.      1535223.19      6812657.81
      1535855.01      6811037.97
#Sta/Elev= 30
  1874.5 1918.55  2052.5 1906.59    2308 1900.53  2435.8 1900.75  2507.5 1898.65
  2734.4  1897.3  4212.9 1892.07  4292.8 1892.79  4449.5 1891.97  4795.5 1891.69
    4823 1892.89  4950.8  1891.8  5002.6 1889.36  5010.1 1886.85  5010.6 1886.35
  5035.2 1886.85  5053.5 1891.36  5107.1 1896.47  5311.1 1903.98  5783.4 1906.75
  6019.5 1910.43  6204.7  1911.1  6428.6 1914.77  6555.3 1918.34  6639.5 1923.93
  6663.5 1923.78  6674.8 1925.68  6706.5 1927.16  6723.7 1926.12  6738.7 1927.83
#Mann= 7 ,-1 , 0
  1874.5     .07       0  4292.8     .16       0  4449.5     .07       0
  5010.1     .07       0  5035.2     .07       0  6019.5    .035       0
  6428.6     .07       0
Bank Sta=5010.1,5035.2
XS Rating Curve= 0 ,0
Exp/Cntr=0.3,0.1

Type RM Length L Ch R = 1 ,90573   ,932,932,932
BEGIN DESCRIPTION:
Little Elm Creek 90573.16
END DESCRIPTION:
XS GIS Cut Line= 3
      1532988.22      6814882.82      1535515.96      6813556.45
      1536613.18      6812667.56
#Sta/Elev= 30
  2158.5 1917.27  2241.9 1913.54  2335.7 1906.49  2396.3    1906  2418.3 1902.29
  2826.1 1895.81  3663.6 1892.41    4358 1891.65  4661.9 1888.13  4749.8 1889.05
  4944.3  1890.4    4975 1887.75  4976.9 1883.35  4977.4 1882.85    5002 1883.35
  5002.7 1886.21  5009.7  1887.4  5032.8 1886.76  5059.5    1889  5108.6 1889.69
  5172.1  1890.9    5239 1890.74    5303 1893.07  5331.7 1892.16    5474 1895.68
  5494.8 1894.67  5654.8 1895.85  5771.4  1896.4  5932.5 1897.81  6425.2 1900.25
#Mann= 10 ,-1 , 0
  2158.5     .07       0  4749.8     .16       0  4976.9     .07       0
    5002     .16       0  5059.5     .07       0  5108.6     .16       0
  5172.1     .07       0  5654.8    .045       0  5771.4     .07       0
  5932.5    .045       0
#XS Ineff= 2 , 0
       0    4620    1893               0
Permanent Ineff=
       F       F
Bank Sta=4976.9,5002
XS Rating Curve= 0 ,0
Exp/Cntr=0.3,0.1

Type RM Length L Ch R = 1 ,89641   ,413,413,413
BEGIN DESCRIPTION:
Little Elm Creek 89641.49
END DESCRIPTION:
XS GIS Cut Line= 3
      1533571.54       6815174.5      1535217.35      6814237.01
      1536515.93       6813389.8
#Sta/Elev= 30
  3115.6 1906.61  3240.1 1899.66  3407.3 1894.76  3944.7  1891.3  4170.9 1891.08
  4186.8 1892.58  4214.1 1890.98  4326.5 1891.17  4751.6 1886.74  4940.3 1887.06
  4961.9 1886.14  4971.1  1881.6  4971.6  1881.1  4996.9  1881.6  5005.5 1884.09
  5066.3 1890.38  5087.4 1886.68  5144.7 1887.53  5440.3 1885.18  5461.4 1888.44
  5491.7 1885.83  5787.3 1887.41  6149.4 1884.52  6185.6 1886.43  6212.8 1891.86
  6221.9 1892.29  6227.8 1894.46  6248.9 1895.28  6470.2 1894.63  6560.2 1894.93
#Mann= 5 ,-1 , 0
  3115.6     .07       0  4751.6    .035       0  4971.1     .07       0
  4996.9    .035       0  6470.2    .035       0
Bank Sta=4971.1,4996.9
XS Rating Curve= 0 ,0
Exp/Cntr=0.3,0.1

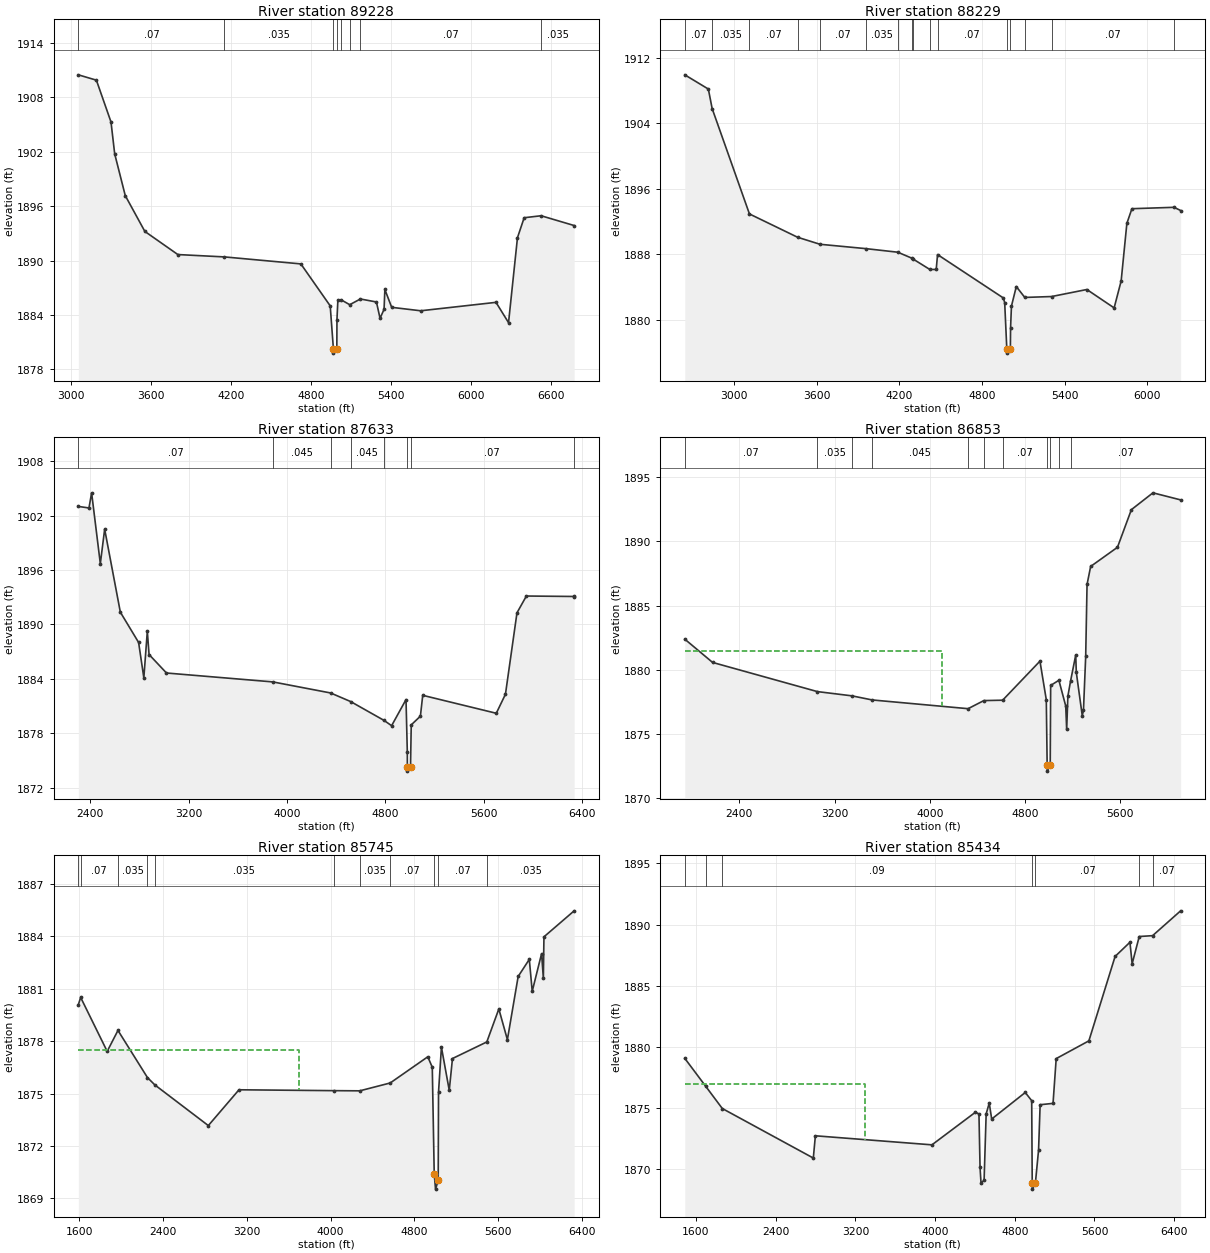
Type RM Length L Ch R = 1 ,89228   ,999,999,999
BEGIN DESCRIPTION:
Little Elm Creek 89227.65
END DESCRIPTION:
XS GIS Cut Line= 4
      1533696.54      6815605.05      1535342.35      6814591.18
      1535654.85      6814118.95      1536681.32        6813467.
#Sta/Elev= 30
  3057.3 1910.48  3192.6 1909.89  3302.1 1905.28  3329.8 1901.76    3409 1897.16
  3555.8 1893.21    3803 1890.66  4152.4  1890.4  4724.6 1889.63  4944.7    1885
  4968.4 1880.29  4968.9 1879.79  4994.2 1880.29  4995.2 1883.47  5002.2 1885.66
  5026.4 1885.67  5090.9 1885.13  5170.9 1885.76    5291 1885.43  5318.1 1883.63
  5348.2 1884.62  5354.2 1886.81  5405.3 1884.84  5622.8 1884.46  6186.9 1885.39
  6280.9 1883.15  6347.8 1892.52  6397.9 1894.72  6524.9 1894.94  6772.6 1893.86
#Mann= 8 ,-1 , 0
  3057.3     .07       0  4152.4    .035       0  4968.4    .035       0
  4994.2    .035       0  5026.4     .07       0  5090.9    .035       0
  5170.9     .07       0  6524.9    .035       0
Bank Sta=4968.4,4994.2
XS Rating Curve= 0 ,0
Exp/Cntr=0.3,0.1

Type RM Length L Ch R = 1 ,88229   ,596,596,596
BEGIN DESCRIPTION:
Little Elm Creek 88229.2
END DESCRIPTION:
XS GIS Cut Line= 3
      1533814.53      6815730.09      1535842.35      6814556.45
       1536640.5      6813584.79
#Sta/Elev= 30
  2641.7 1909.93  2812.7 1908.19  2840.4  1905.8  3111.1 1892.92  3460.5 1890.07
  3623.4 1889.21  3955.2 1888.68  4188.4 1888.24  4290.4 1887.51  4301.8 1887.38
  4420.9 1886.13  4467.3 1886.13  4477.1 1887.95  4955.2 1882.64  4964.6 1882.06
    4980  1876.4  4980.5  1875.9  5005.8  1876.4  5007.3    1879  5013.7 1881.65
  5048.9 1884.04  5110.5 1882.71  5305.2 1882.82  5561.2 1883.68  5759.3 1881.43
  5810.2 1884.72  5851.8 1891.77  5888.4 1893.56  6194.5 1893.73  6242.1 1893.34
#Mann= 16 ,-1 , 0
  2641.7     .07       0  2840.4    .035       0  3111.1     .07       0
  3460.5    .035       0  3623.4     .07       0  3955.2    .035       0
  4188.4     .07       0  4290.4    .045       0  4301.8    .035       0
  4420.9    .045       0  4477.1     .07       0    4980     .07       0
  5005.8     .07       0  5110.5    .035       0  5305.2     .07       0
  6194.5    .035       0
Bank Sta=4980,5005.8
XS Rating Curve= 0 ,0
Exp/Cntr=0.3,0.1

Type RM Length L Ch R = 1 ,87633   ,780,780,780
BEGIN DESCRIPTION:
Little Elm Creek 87632.77
END DESCRIPTION:
XS GIS Cut Line= 3
      1534404.87      6816820.32       1536147.9      6815153.68
      1536696.49      6813632.91
#Sta/Elev= 30
  2304.5 1903.02    2391 1902.85  2412.4 1904.52  2483.2 1896.71  2518.4 1900.51
  2645.8 1891.36  2794.2 1888.02  2836.7 1884.12    2865 1889.25  2879.1 1886.69
  3020.7 1884.65  3884.2 1883.67    4354 1882.45  4517.2  1881.5  4787.4 1879.43
  4849.7 1878.84  4966.7 1881.72  4977.3 1875.92  4977.5 1874.33    4978 1873.83
  5003.3 1874.33  5009.2 1878.93  5083.6 1879.89  5102.5 1882.19  5700.2 1880.21
  5774.6 1882.31  5868.3 1891.29  5944.7 1893.14  6330.6 1893.09  6332.8 1893.06
#Mann= 8 ,-1 , 0
  2304.5     .07       0  3884.2    .045       0    4354     .07       0
  4517.2    .045       0  4787.4     .07       0  4977.5     .07       0
  5003.3     .07       0  6330.6    .035       0
Bank Sta=4977.5,5003.3
XS Rating Curve= 0 ,0
Exp/Cntr=0.3,0.1

Type RM Length L Ch R = 1 ,86853   ,1108,1108,1108
BEGIN DESCRIPTION:
Little Elm Creek 86853.268
END DESCRIPTION:
XS GIS Cut Line= 4
      1535646.81      6817614.56      1536806.83      6815303.27
      1536884.01      6814820.34      1536759.02      6813737.04
#Sta/Elev= 30
    1942 1882.39  2175.4 1880.58  3055.7 1878.31  3345.6 1877.98  3516.1 1877.66
  4321.9 1876.98  4454.4 1877.61  4612.3 1877.64  4925.8 1880.68    4979 1877.68
  4986.3 1872.62  4986.8 1872.12  5012.1 1872.62  5015.8 1878.79  5084.9 1879.19
  5142.3 1877.19  5150.3 1875.36  5160.4 1877.96  5183.8 1879.17  5226.2 1881.15
  5231.3  1879.8  5281.2 1876.44  5291.3 1876.84  5310.1 1881.06  5321.5 1886.65
  5351.7 1888.05  5576.9 1889.54  5693.9 1892.47  5875.1 1893.78  6107.6 1893.23
#Mann= 11 ,-1 , 0
    1942     .07       0  3055.7    .035       0  3345.6     .07       0
  3516.1    .045       0  4321.9     .07       0  4454.4    .045       0
  4612.3     .07       0  4986.3     .07       0  5012.1     .07       0
  5084.9     .16       0  5183.8     .07       0
#XS Ineff= 2 , 0
       0    4100  1881.5               0
Permanent Ineff=
       F       F
Bank Sta=4986.3,5012.1
XS Rating Curve= 0 ,0
Exp/Cntr=0.3,0.1

Type RM Length L Ch R = 1 ,85745   ,311,311,311
BEGIN DESCRIPTION:
Little Elm Creek 20.0
END DESCRIPTION:
XS GIS Cut Line= 4
      1536505.58      6818538.09      1536922.22      6817711.82
      1537521.01      6814997.59      1537980.28      6814077.85
#Sta/Elev= 30
  1592.3 1880.09  1614.5 1880.51  1867.7 1877.42  1970.5 1878.62  2252.1 1875.92
  2322.5  1875.5  2833.1 1873.17  3125.8 1875.22  4032.9 1875.17  4278.9 1875.16
  4569.3 1875.61  4928.1 1877.11  4970.9 1876.51  4989.5 1870.39  5002.1 1869.53
  5027.5 1870.03  5030.5 1875.08  5058.2 1877.66  5132.9 1875.19  5163.6 1877.01
  5491.4 1877.96  5606.2 1879.85  5687.9 1878.09  5790.7 1881.71    5897 1882.69
  5924.9 1880.86  6014.4 1883.02  6031.2 1881.61  6036.8 1883.98  6325.2 1885.47
#Mann= 11 ,-1 , 0
  1592.3    .035       0  1614.5     .07       0  1970.5    .035       0
  2252.1     .07       0  2322.5    .035       0  4032.9     .07       0
  4278.9    .035       0  4569.3     .07       0  4989.5     .07       0
  5027.5     .07       0  5491.4    .035       0
#XS Ineff= 2 , 0
       0    3700  1877.5               0
Permanent Ineff=
       F       F
Bank Sta=4989.5,5027.5
XS Rating Curve= 0 ,0
Exp/Cntr=0.3,0.1

Type RM Length L Ch R = 1 ,85434   ,1614,1614,1614
BEGIN DESCRIPTION:
Little Elm Creek 85434.25
END DESCRIPTION:
XS GIS Cut Line= 3
      1536850.88      6818687.18      1537725.16      6815297.77
      1538459.51      6814016.56
#Sta/Elev= 30
  1487.9 1879.07  1698.3 1876.78  1864.3 1874.97    2778 1870.92  2798.6 1872.74
  3968.7    1872  4405.8 1874.67  4440.7 1874.52  4451.6 1870.15  4461.3 1868.88
  4492.3  1869.1    4513 1874.53  4543.9 1875.41  4568.5 1874.11  4905.4 1876.28
  4970.1 1875.61  4975.4 1868.88  4975.9 1868.38  5007.2 1868.88    5039 1871.57
  5054.8 1875.28  5184.3 1875.39    5216 1879.05    5544  1880.5  5807.2  1887.4
  5956.2 1888.56  5978.4  1886.8  6049.6 1889.03  6183.7  1889.1    6465 1891.13
#Mann= 7 ,-1 , 0
  1487.9     .07       0  1698.3    .035       0  1864.3     .09       0
  4975.4     .07       0  5007.2     .07       0  6049.6    .035       0
  6183.7     .07       0
#XS Ineff= 2 , 0
       0    3300    1877               0
Permanent Ineff=
       F       F
Bank Sta=4975.4,5007.2
XS Rating Curve= 0 ,0
Exp/Cntr=0.3,0.1

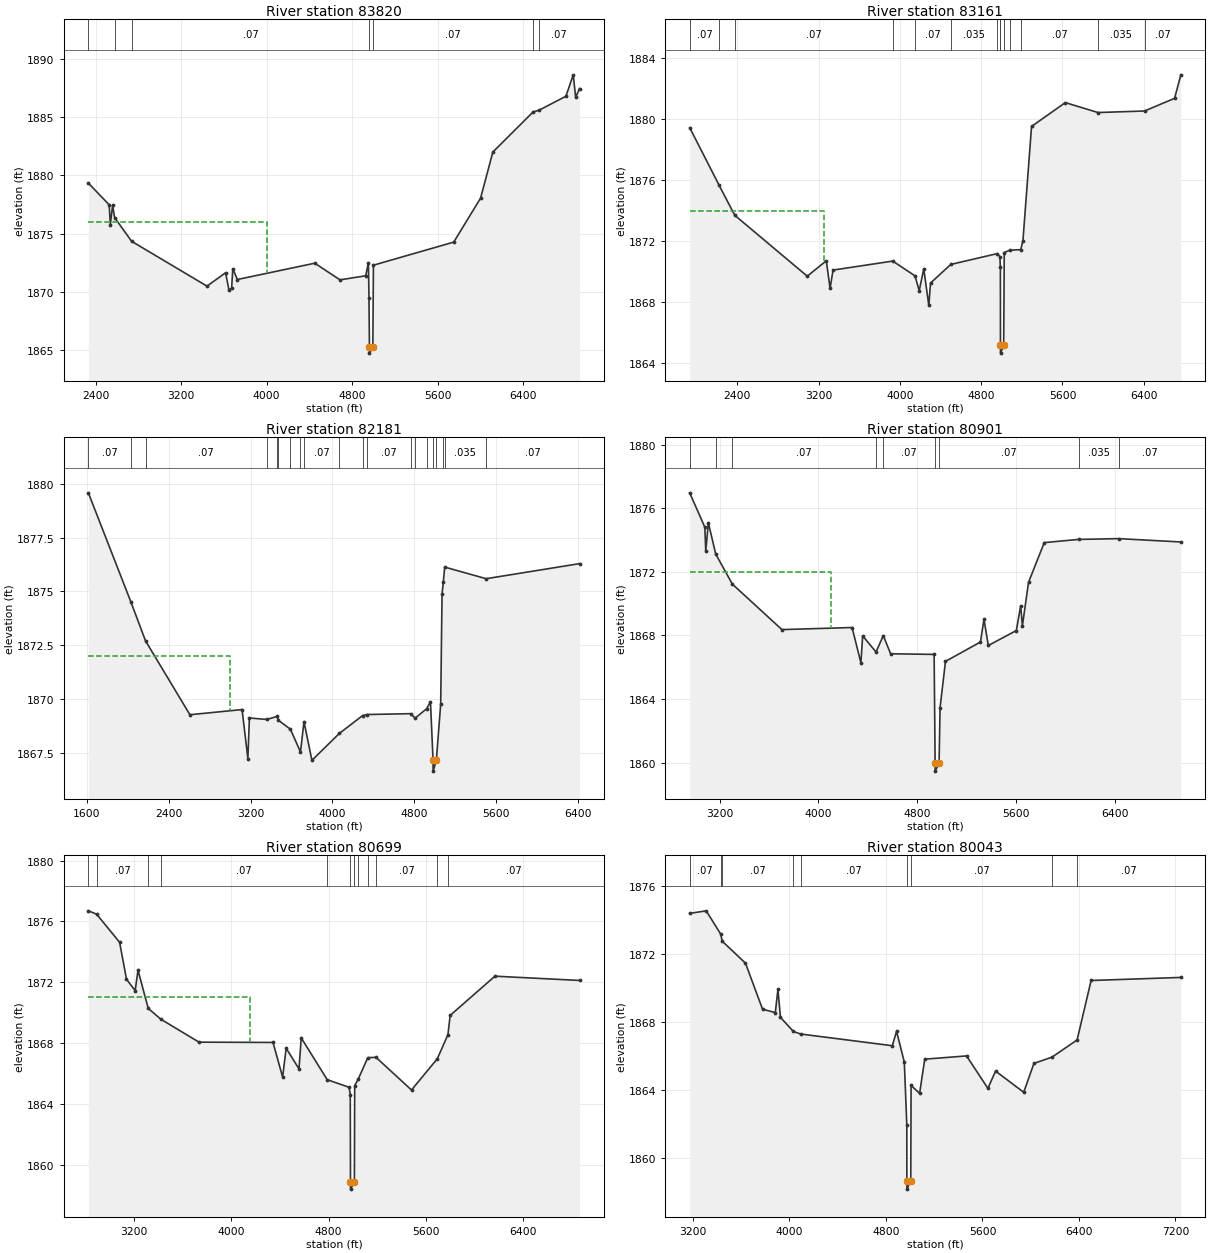
Type RM Length L Ch R = 1 ,83820   ,659,659,659
BEGIN DESCRIPTION:
Little Elm Creek 83819.888
END DESCRIPTION:
XS GIS Cut Line= 3
      1536876.91      6818721.91      1537782.45       6816188.4
      1538704.34       6814516.5
#Sta/Elev= 30
  2330.2 1879.34  2525.5 1877.47  2536.1 1875.78  2557.4 1877.43    2576 1876.38
  2735.3 1874.34  3441.4 1870.49  3615.5 1871.64  3646.3 1870.19  3671.7 1870.29
    3683 1871.98  3725.5 1871.06  4450.9 1872.46  4686.6 1871.03  4927.5 1871.38
    4953 1872.49  4958.3 1869.49  4962.5 1865.24    4963 1864.74  4994.4 1865.24
  4999.9 1872.29    5752 1874.27  6003.2 1878.04  6118.2    1882    6496 1885.45
  6548.3 1885.58  6802.6 1886.79  6871.1 1888.63  6893.9  1886.7  6929.9 1887.45
#Mann= 7 ,-1 , 0
  2330.2     .07       0    2576    .035       0  2735.3     .07       0
  4962.5     .07       0  4994.4     .07       0    6496    .035       0
  6548.3     .07       0
#XS Ineff= 2 , 0
       0    4000    1876               0
Permanent Ineff=
       F       F
Bank Sta=4962.5,4994.4
XS Rating Curve= 0 ,0
Exp/Cntr=0.3,0.1

Type RM Length L Ch R = 1 ,83161   ,980,980,980
BEGIN DESCRIPTION:
Little Elm Creek 83160.617
END DESCRIPTION:
XS GIS Cut Line= 3
      1536894.27      6818756.62      1538303.29      6816016.52
      1539537.03      6814772.37
#Sta/Elev= 30
  1931.5 1879.43  2221.4 1875.65    2375 1873.69  3088.2  1869.7  3275.8 1870.71
    3313  1868.9  3342.3  1870.1    3930 1870.69  4148.9 1869.72  4190.1 1868.75
  4234.8 1870.18  4284.8 1867.78  4301.3 1869.25  4500.8 1870.47  4958.9 1871.18
  4983.7 1870.98  4988.9 1870.28  4989.5 1865.16    4990 1864.66  5021.4 1865.16
  5026.9 1871.25  5080.4  1871.4  5189.2 1871.44  5210.8 1872.03  5295.6 1879.51
    5628 1881.07  5949.4 1880.42  6407.5 1880.52  6702.8 1881.35  6764.8 1882.89
#Mann= 14 ,-1 , 0
  1931.5     .07       0  2221.4    .035       0    2375     .07       0
    3930    .035       0  4148.9     .07       0  4500.8    .035       0
  4958.9     .12       0  4983.7     .07       0  4989.5     .07       0
  5021.4     .07       0  5080.4     .16       0  5189.2     .07       0
  5949.4    .035       0  6407.5     .07       0
#XS Ineff= 2 , 0
       0    3250    1874               0
Permanent Ineff=
       F       F
Bank Sta=4989.5,5021.4
XS Rating Curve= 0 ,0
Exp/Cntr=0.3,0.1

Type RM Length L Ch R = 1 ,82181   ,1280,1280,1280
BEGIN DESCRIPTION:
Little Elm Creek 82181.45
END DESCRIPTION:
XS GIS Cut Line= 4
      1536898.61       6818852.1      1538183.12      6817009.97
      1539115.79      6816318.61      1540219.93      6815469.67
#Sta/Elev= 30
  1614.4 1879.58  2028.5 1874.53  2173.4  1872.7  2606.9 1869.27  3116.6 1869.51
  3173.3 1867.23  3188.1 1869.12  3357.7 1869.05  3458.9 1869.19  3471.4 1869.01
  3588.6  1868.6  3687.3 1867.54  3721.6 1868.95  3798.9 1867.15  4066.5  1868.4
  4294.1 1869.23    4339 1869.28  4764.7 1869.32  4807.5 1869.11  4920.1 1869.55
  4957.5 1869.87  4982.9 1867.15  4983.4 1866.65  5014.8 1867.15  5057.4 1869.76
  5070.6 1874.87  5083.1 1875.44  5096.4 1876.13  5501.8 1875.59  6413.9 1876.29
#Mann= 20 ,-1 , 0
  1614.4     .07       0  2028.5    .035       0  2173.4     .07       0
  3357.7    .035       0  3458.9     .07       0  3471.4    .035       0
  3588.6     .07       0  3687.3    .035       0  3721.6     .07       0
  4066.5     .07       0  4294.1    .035       0    4339     .07       0
  4764.7     .16       0  4807.5     .07       0  4920.1     .16       0
  4982.9     .07       0  5014.8     .07       0  5083.1     .07       0
  5096.4    .035       0  5501.8     .07       0
#XS Ineff= 2 , 0
       0    3000    1872               0
Permanent Ineff=
       F       F
Bank Sta=4982.9,5014.8
XS Rating Curve= 0 ,0
Exp/Cntr=0.3,0.1

Type RM Length L Ch R = 1 ,80901   ,202,202,202
BEGIN DESCRIPTION:
Little Elm Creek 80901.46
END DESCRIPTION:
XS GIS Cut Line= 4
      1537111.32      6818687.13      1538217.09      6817382.65
      1538529.41      6817255.24      1539935.64      6815935.82
#Sta/Elev= 30
  2957.5 1876.97    3080 1874.81  3087.5 1873.29  3108.6 1875.09  3168.2 1873.12
  3302.8 1871.23    3704 1868.37  4271.9  1868.5  4343.4 1866.28  4357.6 1867.98
  4465.5 1866.96  4524.6 1867.99  4583.9 1866.85  4936.1 1866.81  4944.1 1859.97
  4944.6 1859.47  4976.2 1859.97  4984.1 1863.46    5028 1866.37  5311.2 1867.59
  5339.6 1869.02  5374.7 1867.37  5601.4 1868.31  5636.5 1869.87  5650.7 1868.61
  5700.1 1871.34  5827.5 1873.84  6106.6 1874.04  6429.6 1874.09  6933.2 1873.88
#Mann= 9 ,-1 , 0
  2957.5     .07       0  3168.2    .035       0  3302.8     .07       0
  4465.5    .035       0  4524.6     .07       0  4944.1     .07       0
  4976.2     .07       0  6106.6    .035       0  6429.6     .07       0
#XS Ineff= 2 , 0
       0    4100    1872               0
Permanent Ineff=
       F       F
Bank Sta=4944.1,4976.2
XS Rating Curve= 0 ,0
Exp/Cntr=0.3,0.1

Type RM Length L Ch R = 1 ,80699   ,656,656,656
BEGIN DESCRIPTION:
Little Elm Creek 80698.68
END DESCRIPTION:
XS GIS Cut Line= 4
      1537150.39      6818951.87       1538081.2      6817639.96
       1538603.2      6817420.17      1539982.58      6816162.24
#Sta/Elev= 30
  2823.3  1876.7  2891.3 1876.48  3080.6 1874.63  3137.2  1872.2  3208.6 1871.45
    3232 1872.79  3316.2 1870.28  3419.7 1869.57  3733.9 1868.06  4342.9 1868.04
    4422 1865.76    4451 1867.66  4556.8  1866.3  4575.1 1868.34  4788.8 1865.59
  4969.1 1865.09  4978.5  1864.6  4980.5 1858.89    4981 1858.39  5012.6 1858.89
    5015  1865.2  5044.3 1865.63    5123 1867.04  5190.5 1867.06  5482.5 1864.91
  5695.2 1866.97  5782.1 1868.55  5800.7 1869.82  6168.9  1872.4  6865.1 1872.12
#Mann= 12 ,-1 , 0
  2823.3    .035       0  2891.3     .07       0  3316.2    .035       0
  3419.7     .07       0  4788.8     .16       0  4980.5     .07       0
  5012.6     .16       0  5044.3     .07       0    5123     .16       0
  5190.5     .07       0  5695.2    .045       0  5782.1     .07       0
#XS Ineff= 2 , 0
       0    4150    1871               0
Permanent Ineff=
       F       F
Bank Sta=4980.5,5012.6
XS Rating Curve= 0 ,0
Exp/Cntr=0.3,0.1

Type RM Length L Ch R = 1 ,80043   ,169,169,169
BEGIN DESCRIPTION:
Little Elm Creek 80043.37
END DESCRIPTION:
XS GIS Cut Line= 3
      1537154.73      6819220.97        1538383.      6817879.86
      1540006.29      6816317.33
#Sta/Elev= 30
    3173 1874.37    3310 1874.52  3430.9 1873.14  3441.6 1872.74  3635.5 1871.44
  3776.8 1868.73  3882.8 1868.53  3904.4 1869.89  3925.4 1868.25  4032.3 1867.42
  4091.9 1867.27  4852.8 1866.58  4887.9 1867.43  4952.1 1865.62    4973 1861.91
  4973.2 1858.64  4973.8 1858.14  5005.7 1858.64  5008.3 1864.24  5079.1 1863.78
  5121.5 1865.79  5468.1 1865.98  5645.1 1864.07  5708.6 1865.09  5941.9 1863.84
  6026.8 1865.54  6177.1 1865.91  6384.6 1866.92  6500.7 1870.42  7244.7  1870.6
#Mann= 9 ,-1 , 0
    3173     .07       0  3430.9    .035       0  3441.6     .07       0
  4032.3    .035       0  4091.9     .07       0  4973.2     .07       0
  5005.7     .07       0  6177.1    .045       0  6384.6     .07       0
Bank Sta=4973.2,5005.7
XS Rating Curve= 0 ,0
Exp/Cntr=0.3,0.1