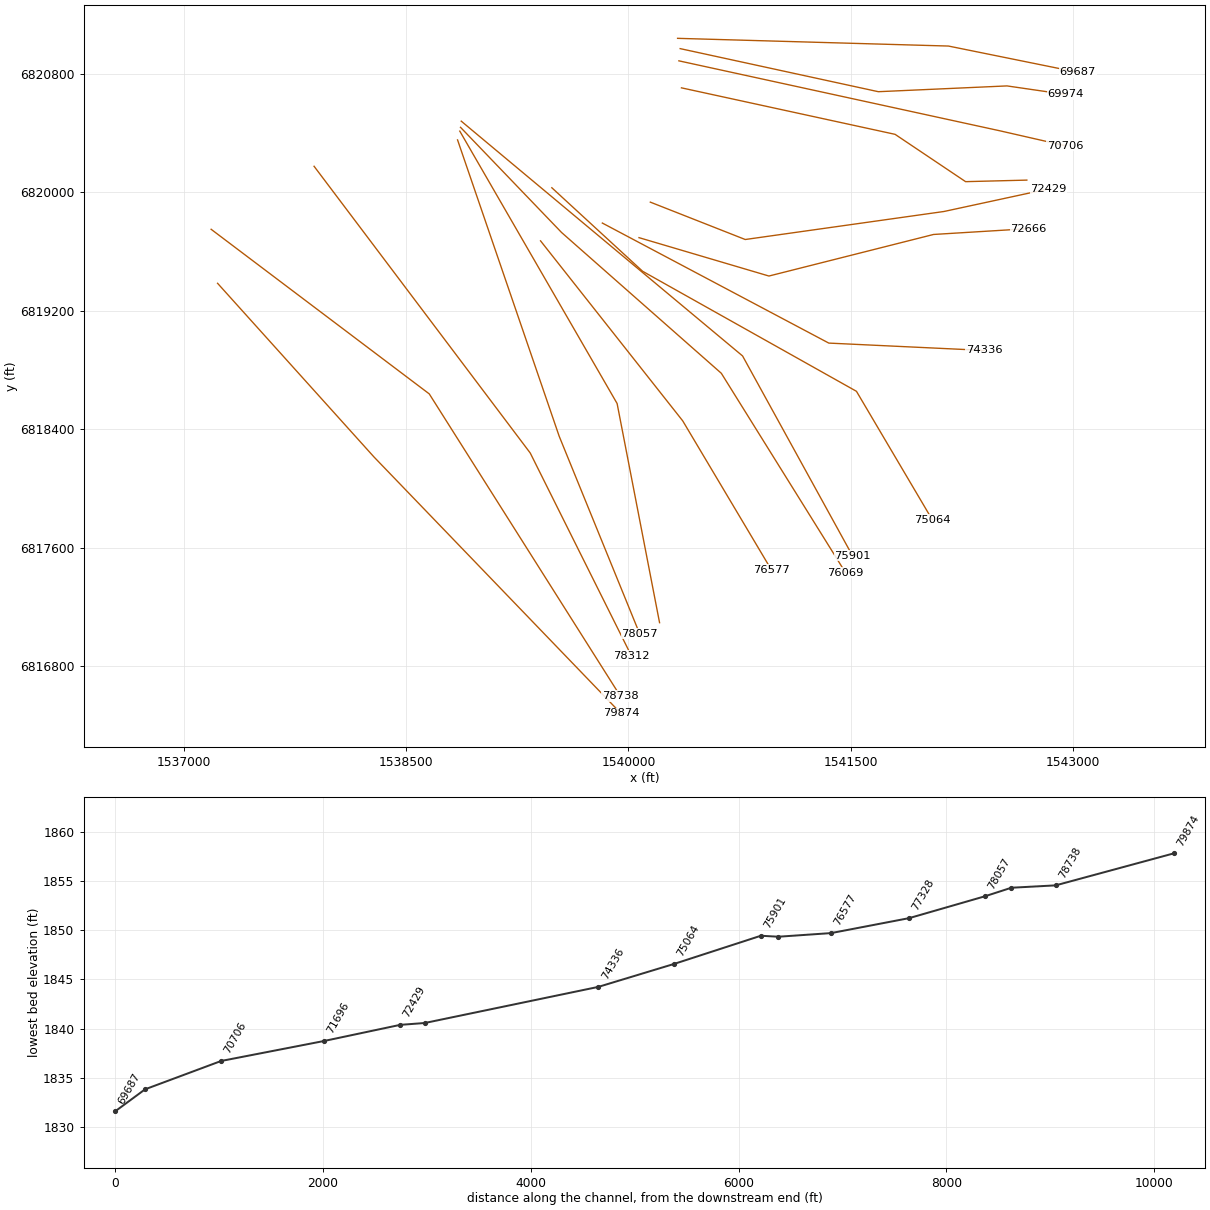
HEC-RAS study Little Elm Creek.prj: Little Elm Creek Base Level Engineering

--- Little Elm Creek.g01 (geometry) --- (continued)

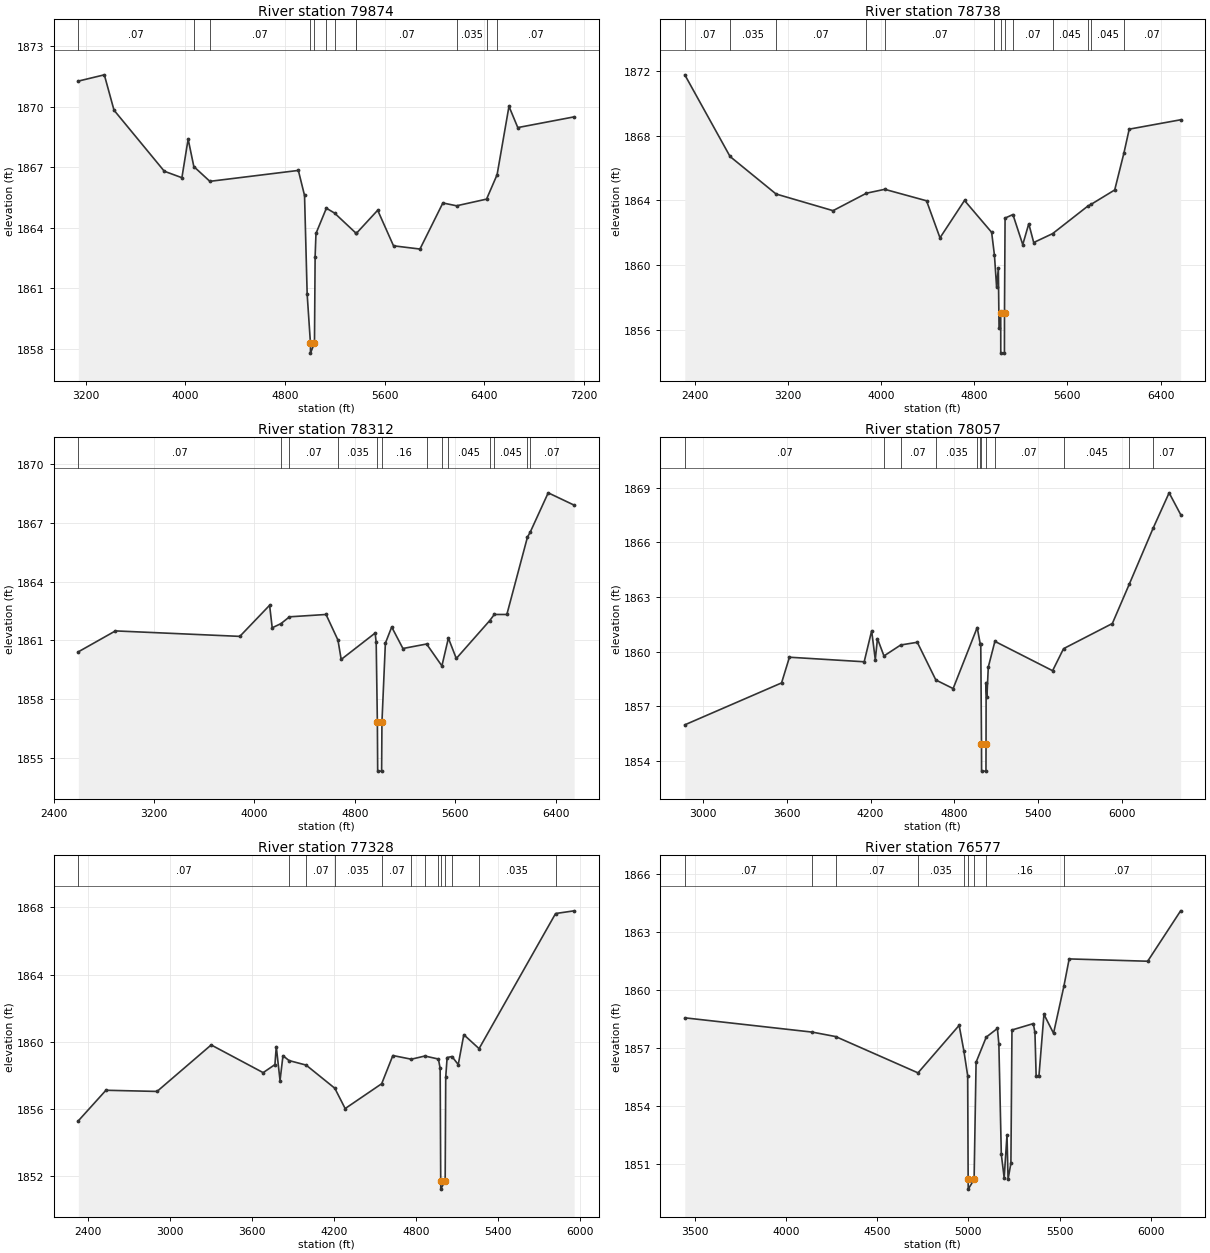
Type RM Length L Ch R = 1 ,79874   ,1136,1136,1136
BEGIN DESCRIPTION:
Little Elm Creek 79873.79
END DESCRIPTION:
XS GIS Cut Line= 3
      1537228.49      6819385.93      1538283.18      6818214.06
      1539949.51      6816482.64
#Sta/Elev= 30
  3141.4 1871.26    3350 1871.57  3427.8 1869.82  3831.4  1866.8  3972.7 1866.48
  4022.7 1868.39  4068.5 1867.03  4197.1  1866.3  4907.3 1866.84    4957  1865.6
  4978.1 1860.71  5004.3  1858.3  5004.8  1857.8  5036.8  1858.3  5041.9 1862.57
  5048.8 1863.72  5132.2 1864.97  5197.8 1864.73  5372.6 1863.72  5373.5 1863.73
  5544.1 1864.87  5671.1 1863.11  5883.4 1862.95  6067.3 1865.23  6177.2 1865.09
  6417.9 1865.42  6502.6 1866.63  6597.8 1870.01  6668.6 1868.96    7121 1869.49
#Mann= 12 ,-1 , 0
  3141.4     .07       0  4068.5    .035       0  4197.1     .07       0
  5004.3     .07       0  5036.8     .07       0  5132.2     .16       0
  5197.8     .07       0  5372.6     .16       0  5373.5     .07       0
  6177.2    .035       0  6417.9    .045       0  6502.6     .07       0
Bank Sta=5004.3,5036.8
XS Rating Curve= 0 ,0
Exp/Cntr=0.3,0.1

Type RM Length L Ch R = 1 ,78738   ,426,426,426
BEGIN DESCRIPTION:
Little Elm Creek 78738.08
END DESCRIPTION:
XS GIS Cut Line= 3
      1537185.05      6819750.54      1538656.44      6818639.41
      1539945.51      6816599.47
#Sta/Elev= 30
  2315.4 1871.76  2703.9 1866.71    3099 1864.39  3588.1 1863.36  3875.1 1864.44
    4032 1864.68    4391 1863.97  4506.3 1861.68  4716.8 1863.99  4949.8 1862.02
  4974.1 1860.59  4992.2 1858.65  5007.5 1859.79  5013.4 1856.11  5027.7 1857.05
  5028.2 1854.55  5059.6 1854.55  5060.2 1857.05  5065.1  1862.9  5132.5 1863.12
  5216.9 1861.26  5268.6 1862.55    5311 1861.39  5473.2 1861.94  5775.1 1863.64
  5805.8 1863.76  6006.3 1864.64  6085.7 1866.93  6130.9  1868.4  6572.3 1868.98
#Mann= 13 ,-1 , 0
  2315.4     .07       0  2703.9    .035       0    3099     .07       0
  3875.1    .035       0    4032     .07       0  4974.1     .16       0
  5027.7     .07       0  5060.2     .16       0  5132.5     .07       0
  5473.2    .045       0  5775.1    .035       0  5805.8    .045       0
  6085.7     .07       0
Bank Sta=5027.7,5060.2
XS Rating Curve= 0 ,0
Exp/Cntr=0.3,0.1

Type RM Length L Ch R = 1 ,78312   ,255,255,255
BEGIN DESCRIPTION:
Little Elm Creek 78311.91
END DESCRIPTION:
XS GIS Cut Line= 3
      1537879.51       6820175.9      1539337.86       6818240.1
      1540019.27      6816872.96
#Sta/Elev= 30
    2597 1860.41  2892.8 1861.48  3883.9  1861.2  4121.2 1862.79    4142 1861.64
  4211.1 1861.85  4279.7  1862.2  4570.9 1862.32    4666 1861.01  4691.7 1860.02
  4962.3 1861.37  4970.6 1860.89    4980 1856.81  4982.5 1854.31  5013.9 1854.31
  5016.5 1856.81  5043.8 1860.85  5094.2 1861.68  5183.7 1860.58  5372.3 1860.81
  5494.3 1859.69  5545.9 1861.11    5609 1860.07  5875.8 1862.01  5911.9 1862.32
  6011.8 1862.32  6176.2 1866.28  6197.4 1866.52  6341.4 1868.54  6548.2 1867.91
#Mann= 13 ,-1 , 0
    2597     .07       0  4211.1    .035       0  4279.7     .07       0
    4666    .035       0    4980     .07       0  5016.5     .16       0
  5372.3     .16       0  5494.3     .07       0  5545.9    .045       0
  5875.8    .035       0  5911.9    .045       0  6176.2    .035       0
  6197.4     .07       0
Bank Sta=4980,5016.5
XS Rating Curve= 0 ,0
Exp/Cntr=0.3,0.1

Type RM Length L Ch R = 1 ,78057   ,729,729,729
BEGIN DESCRIPTION:
Little Elm Creek 78056.57
END DESCRIPTION:
XS GIS Cut Line= 3
       1538847.4      6820353.84      1539533.18      6818352.95
      1540075.21      6817021.72
#Sta/Elev= 30
  2869.2 1855.98  3562.5 1858.28    3619 1859.69  4154.5 1859.44    4208 1861.14
    4234 1859.56  4249.6 1860.71  4296.2 1859.76  4415.9 1860.36    4535 1860.51
    4668 1858.44  4791.8 1857.97  4964.2 1861.32  4986.4  1860.4  4989.7  1860.4
    4995 1854.94  4995.6 1853.44    5027 1853.44  5027.5 1854.94  5028.2  1858.3
  5033.6  1857.5  5043.7 1859.15    5091 1860.56  5504.4 1858.95    5583 1860.16
  5932.5 1861.54    6055 1863.72  6224.1 1866.76  6339.3 1868.71  6421.7 1867.52
#Mann= 12 ,-1 , 0
  2869.2     .07       0  4296.2    .035       0  4415.9     .07       0
    4668    .035       0  4964.2     .07       0  4986.4     .16       0
    4995     .07       0  5027.5     .16       0    5091     .07       0
    5583    .045       0    6055    .035       0  6224.1     .07       0
Bank Sta=4995,5027.5
XS Rating Curve= 0 ,0
Exp/Cntr=0.3,0.1

Type RM Length L Ch R = 1 ,77328   ,751,751,751
BEGIN DESCRIPTION:
Little Elm Creek 77328.3
END DESCRIPTION:
XS GIS Cut Line= 3
      1538862.56      6820413.08       1539923.8       6818574.3
      1540210.14      6817094.91
#Sta/Elev= 30
  2330.1 1855.29  2532.2 1857.11  2906.3 1857.04  3302.6 1859.81  3683.2 1858.16
  3769.4 1858.64  3779.2 1859.71  3806.7 1857.69  3828.3 1859.17  3872.5 1858.88
  3997.6 1858.61  4207.8 1857.23  4283.5 1856.02  4550.9  1857.5  4632.7 1859.18
  4767.8 1858.96    4867 1859.15  4966.3 1858.97    4979 1858.41  4983.1 1851.72
  4983.7 1851.22  5015.7 1851.72  5019.8 1857.89    5030 1859.06  5065.5 1859.12
  5111.4 1858.64  5152.2 1860.42  5263.9 1859.59  5824.1 1867.64    5960  1867.8
#Mann= 13 ,-1 , 0
  2330.1     .07       0  3872.5    .035       0  3997.6     .07       0
  4207.8    .035       0  4550.9     .07       0  4767.8    .035       0
    4867     .07       0  4966.3     .16       0  4983.1     .07       0
  5015.7     .16       0  5065.5     .07       0  5263.9    .035       0
  5824.1     .07       0
Bank Sta=4983.1,5015.7
XS Rating Curve= 0 ,0
Exp/Cntr=0.3,0.1

Type RM Length L Ch R = 1 ,76577   ,508,508,508
BEGIN DESCRIPTION:
Little Elm Creek 76576.56
END DESCRIPTION:
XS GIS Cut Line= 3
      1539407.28      6819672.43      1540366.51      6818457.12
      1540964.61      6817451.61
#Sta/Elev= 30
  3445.1 1858.57  4143.8 1857.83  4271.9  1857.6  4723.6 1855.72  4949.1 1858.18
  4975.2 1856.85  4995.8 1855.58  4998.5  1850.2    4999  1849.7  5031.1  1850.2
    5042 1856.27  5097.6 1857.57  5158.9 1858.02  5166.9  1857.2  5180.3  1851.5
  5195.9 1850.29  5211.5  1852.5  5217.3 1850.21  5232.9 1851.04  5238.7 1857.94
  5355.6 1858.27  5364.7 1857.81  5371.2 1855.56  5386.8 1855.58    5414 1858.75
  5466.6 1857.77  5523.2  1860.2  5552.3 1861.62  5982.7  1861.5  6163.3 1864.11
#Mann= 9 ,-1 , 0
  3445.1     .07       0  4143.8    .035       0  4271.9     .07       0
  4723.6    .035       0  4975.2     .07       0  4998.5     .07       0
  5031.1     .07       0  5097.6     .16       0  5523.2     .07       0
Bank Sta=4998.5,5031.1
XS Rating Curve= 0 ,0
Exp/Cntr=0.3,0.1

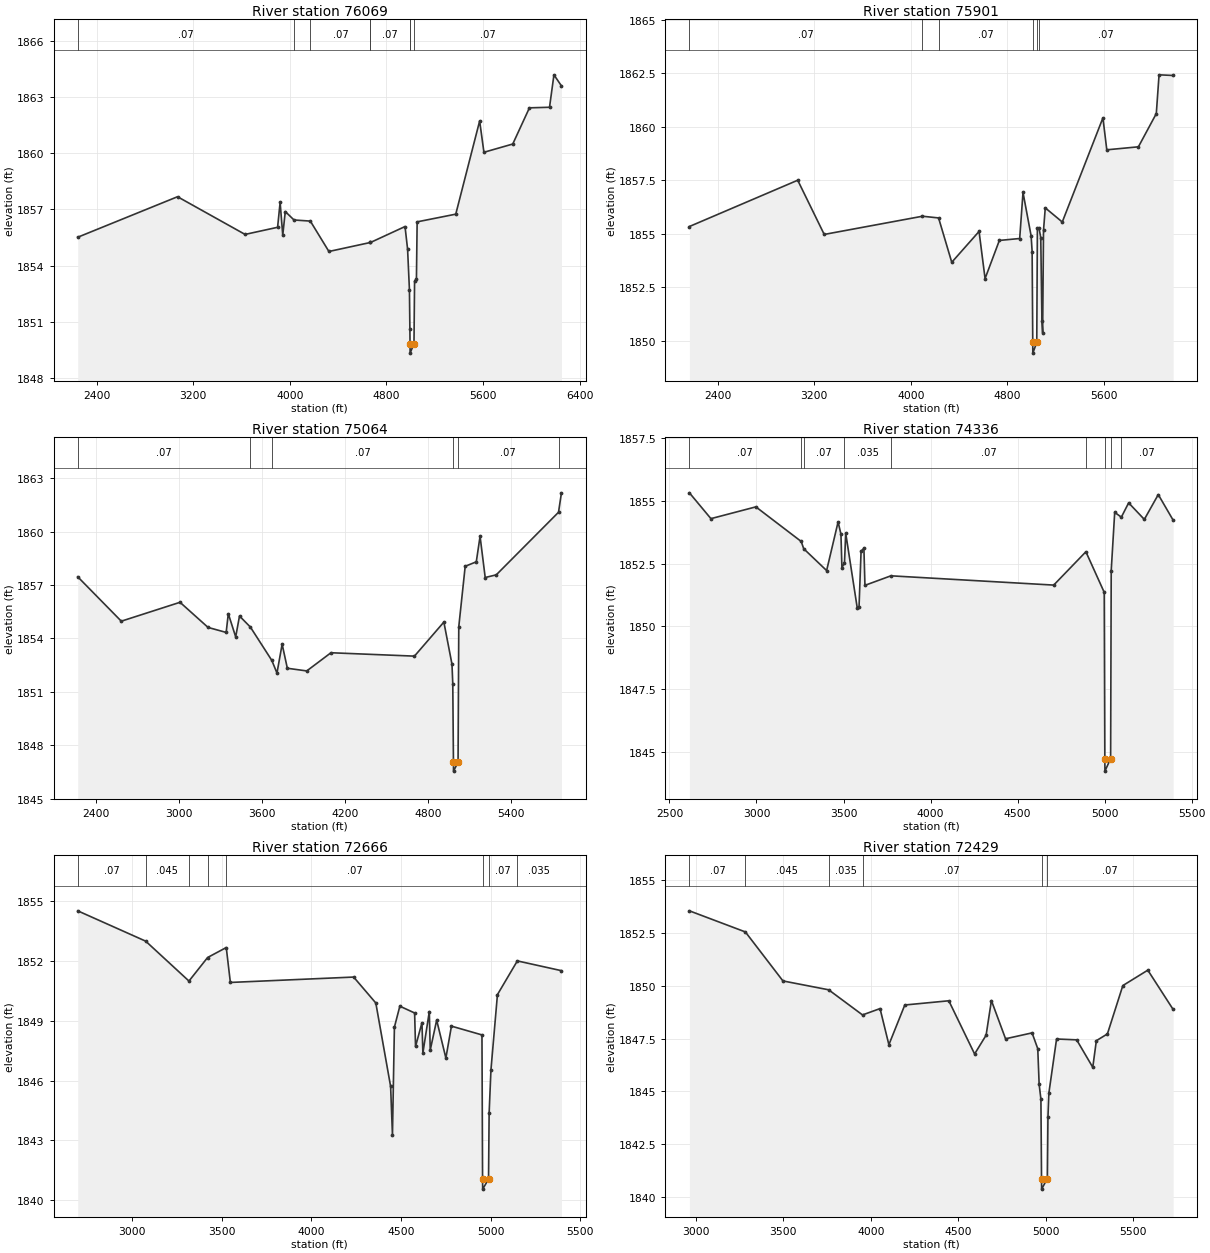
Type RM Length L Ch R = 1 ,76069   ,168,168,168
BEGIN DESCRIPTION:
Little Elm Creek 76069.11
END DESCRIPTION:
XS GIS Cut Line= 4
      1538867.31        6820439.      1539548.97      6819728.99
      1540626.93       6818778.3      1541464.55      6817432.89
#Sta/Elev= 30
  2242.9 1855.51  3069.5 1857.67  3628.9 1855.66  3898.3 1856.04  3919.2 1857.37
    3941 1855.62  3961.9 1856.88  4034.2 1856.43  4169.5 1856.37  4323.3 1854.75
  4666.8 1855.23  4667.7 1855.23  4953.7 1856.08    4975 1854.87  4990.3  1852.7
  4993.9 1850.63  4995.3 1849.83  4995.8 1849.33  5027.9 1849.83  5032.8 1853.15
  5048.2 1853.29  5054.1 1856.33  5373.9 1856.74  5571.8 1861.71  5607.2 1860.04
    5846 1860.48  5984.1 1862.41  6150.5 1862.44  6187.1 1864.17  6249.3 1863.58
#Mann= 8 ,-1 , 0
  2242.9     .07       0  4034.2    .035       0  4169.5     .07       0
  4666.8    .035       0  4667.7     .07       0  4993.9     .16       0
  4995.3     .07       0  5027.9     .07       0
Bank Sta=4995.3,5027.9
XS Rating Curve= 0 ,0
Exp/Cntr=0.3,0.1

Type RM Length L Ch R = 1 ,75901   ,837,837,837
BEGIN DESCRIPTION:
Little Elm Creek 75900.74
END DESCRIPTION:
XS GIS Cut Line= 3
      1538872.27      6820480.49      1540770.16      6818895.48
      1541512.34      6817545.66
#Sta/Elev= 30
  2164.1 1855.34  3062.6  1857.5  3282.5 1854.97  4097.7 1855.82  4231.3 1855.74
  4340.6 1853.67  4567.1 1855.11    4617 1852.91  4735.6 1854.69  4904.2 1854.78
  4931.7 1856.93  4999.1  1854.9  5007.4 1854.17  5012.6 1849.93  5013.2 1849.43
  5045.8 1849.93    5051 1855.25  5065.1 1855.25    5079 1854.82  5088.9 1850.91
  5094.6 1850.38  5101.8 1855.16  5116.4 1856.21  5257.5 1855.55  5594.7 1860.41
  5626.8 1858.92  5889.2 1859.06  6037.6 1860.61  6060.4 1862.42  6177.2 1862.39
#Mann= 6 ,-1 , 0
  2164.1     .07       0  4097.7    .035       0  4231.3     .07       0
  5012.6     .07       0  5045.8     .07       0  5065.1     .07       0
Bank Sta=5012.6,5045.8
XS Rating Curve= 0 ,0
Exp/Cntr=0.3,0.1

Type RM Length L Ch R = 1 ,75064   ,728,728,728
BEGIN DESCRIPTION:
Little Elm Creek 75064.2
END DESCRIPTION:
XS GIS Cut Line= 4
      1539483.46       6820030.9      1540095.65       6819467.2
      1541538.38      6818656.77      1542050.26      6817789.18
#Sta/Elev= 30
  2270.4 1857.46  2585.1 1854.97  3009.4 1856.03    3212 1854.62  3342.7 1854.34
  3358.1 1855.39  3411.5 1854.09    3439 1855.26  3517.6 1854.64  3672.5 1852.77
  3709.7 1852.06    3747 1853.68  3784.6 1852.33  3924.9 1852.18  4099.7  1853.2
  4702.8 1853.01  4915.3 1854.92  4973.9 1852.56  4979.7 1851.46  4984.5 1847.06
  4985.1 1846.56  5017.8 1847.06    5023 1854.66  5069.4 1858.05  5149.5  1858.3
  5176.8 1859.73  5213.9 1857.42  5293.9 1857.57  5743.5 1861.08  5764.7 1862.17
#Mann= 6 ,-1 , 0
  2270.4     .07       0  3517.6    .035       0  3672.5     .07       0
  4984.5     .07       0  5017.8     .07       0  5743.5    .035       0
Bank Sta=4984.5,5017.8
XS Rating Curve= 0 ,0
Exp/Cntr=0.3,0.1

Type RM Length L Ch R = 1 ,74336   ,1670,1670,1670
BEGIN DESCRIPTION:
Little Elm Creek 74605.87
END DESCRIPTION:
XS GIS Cut Line= 3
      1539824.14      6819792.65      1541351.75      6818982.29
      1542400.34      6818932.79
#Sta/Elev= 30
  2614.6 1855.33  2738.2  1854.3  2996.4 1854.77  3256.9 1853.39  3271.3  1853.1
  3402.9 1852.23  3468.8 1854.17  3485.2 1853.68  3490.8 1852.35  3505.4 1852.53
  3512.8 1853.71  3578.8 1850.74  3589.1 1850.78  3600.8    1853  3617.1 1853.12
    3623 1851.64  3772.1 1852.02  4707.5 1851.65  4892.4 1852.98  4997.8 1851.36
  5001.2 1844.73  5001.8 1844.23  5034.5 1844.73  5037.9 1852.23  5057.9 1854.55
  5096.1 1854.36    5138 1854.93  5228.1 1854.27  5308.2 1855.26  5393.6 1854.24
#Mann= 9 ,-1 , 0
  2614.6     .07       0  3256.9    .045       0  3271.3     .07       0
  3505.4    .035       0  3772.1     .07       0  4892.4     .16       0
  5001.2     .07       0  5034.5     .16       0  5096.1     .07       0
Bank Sta=5001.2,5034.5
XS Rating Curve= 0 ,0
Exp/Cntr=0.3,0.1

Type RM Length L Ch R = 1 ,72666   ,237,237,237
BEGIN DESCRIPTION:
Little Elm Creek 73698.04
END DESCRIPTION:
XS GIS Cut Line= 4
      1540071.41      6819694.08        1540948.      6819434.97
      1542058.37      6819715.59      1542697.91      6819754.78
#Sta/Elev= 30
  2695.5 1854.51  3074.8 1852.99  3316.4 1850.99  3420.5 1852.17  3524.6 1852.67
  3547.5 1850.92  4235.7 1851.19  4359.4 1849.89    4442 1845.71  4452.3 1843.27
  4463.2 1848.68  4493.5 1849.73    4576 1849.39  4581.1 1847.71    4617  1848.9
  4622.1 1847.38    4658 1849.46  4663.2 1847.53  4699.1 1849.03  4750.5 1847.13
  4781.5 1848.73  4951.9 1848.29  4955.3 1841.06  4955.9 1840.56  4988.6 1841.06
  4991.9 1844.36    5002 1846.53  5038.3 1850.31  5149.4    1852  5395.6 1851.51
#Mann= 8 ,-1 , 0
  2695.5     .07       0  3074.8    .045       0  3316.4     .07       0
  3420.5    .035       0  3524.6     .07       0  4955.3     .07       0
  4988.6     .07       0  5149.4    .035       0
Bank Sta=4955.3,4988.6
XS Rating Curve= 0 ,0
Exp/Cntr=0.3,0.1

Type RM Length L Ch R = 1 ,72429   ,733,733,733
BEGIN DESCRIPTION:
Little Elm Creek 72429.183
END DESCRIPTION:
XS GIS Cut Line= 4
      1540147.85       6819933.8      1540788.11      6819681.54
      1542128.81      6819870.69      1542833.68       6820023.1
#Sta/Elev= 30
  2964.4 1853.55  3284.2 1852.55  3498.7 1850.23  3759.8 1849.81  3953.3 1848.62
  4053.4 1848.92  4103.9 1847.21  4194.8 1849.09  4446.3 1849.29  4593.6 1846.77
  4659.3 1847.66  4689.6  1849.3  4770.4 1847.49  4921.9 1847.77  4954.4 1847.02
  4962.3 1845.33  4972.4 1844.63  4975.9 1840.87  4976.5 1840.37  5009.2 1840.87
  5012.6 1843.78  5017.7 1844.91  5061.8 1847.48  5176.6 1847.44  5268.6 1846.14
  5289.1  1847.4  5352.2 1847.72  5440.4 1850.01    5583 1850.74  5727.7 1848.88
#Mann= 6 ,-1 , 0
  2964.4     .07       0  3284.2    .045       0  3759.8    .035       0
  3953.3     .07       0  4975.9     .07       0  5009.2     .07       0
Bank Sta=4975.9,5009.2
XS Rating Curve= 0 ,0
Exp/Cntr=0.3,0.1

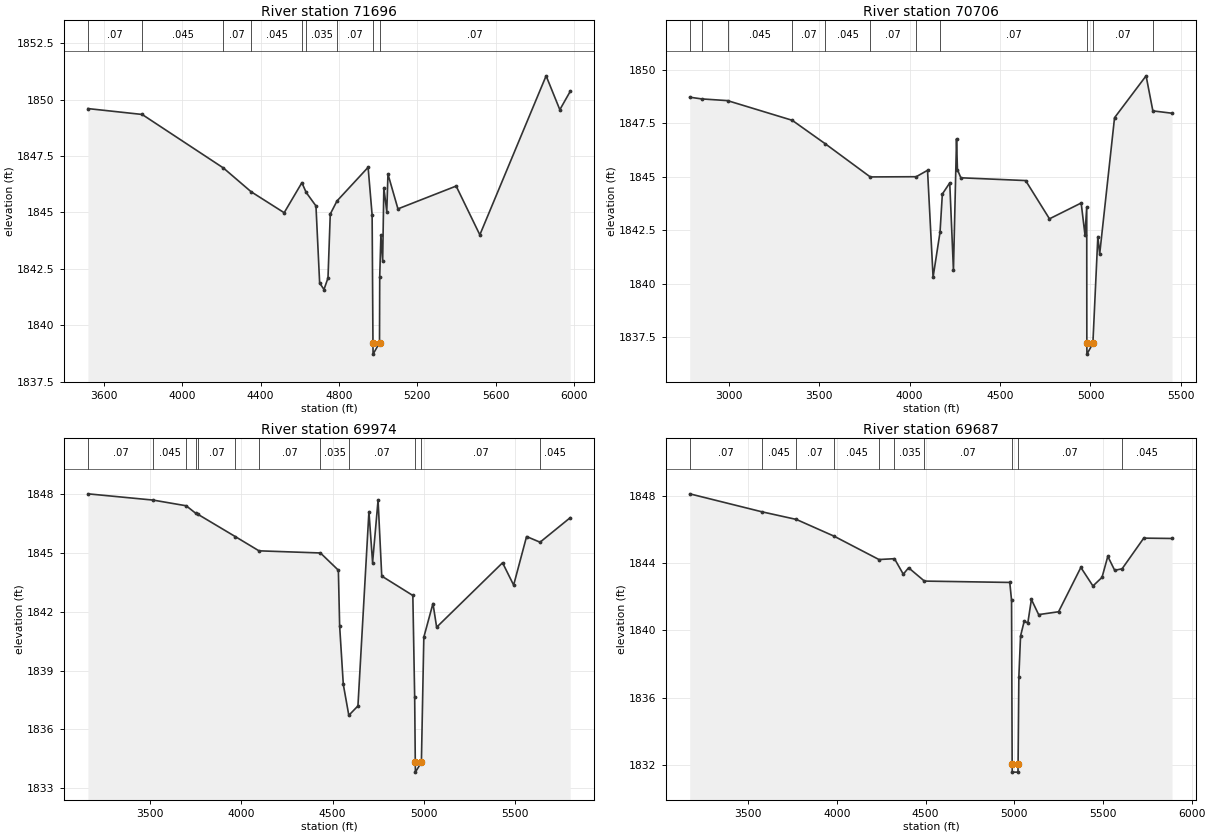
Type RM Length L Ch R = 1 ,71696   ,990,990,990
BEGIN DESCRIPTION:
Little Elm Creek 71696.32
END DESCRIPTION:
XS GIS Cut Line= 4
      1540357.87      6820705.37      1541798.95      6820391.52
      1542274.64      6820072.08      1542687.85       6820082.5
#Sta/Elev= 30
  3518.7  1849.6  3795.5 1849.34  4210.2 1846.97  4351.4 1845.92  4520.3 1844.99
  4610.7 1846.32  4632.4 1845.89  4682.5 1845.29  4701.3 1841.88  4723.4 1841.59
  4743.9  1842.1  4755.5 1844.93  4789.8 1845.51  4948.6    1847  4969.1 1844.89
  4973.4 1839.23    4974 1838.73  5006.8 1839.23  5007.9 1842.15  5013.9    1844
  5022.9 1842.87  5028.9  1846.1  5043.9 1845.04  5049.9  1846.7  5100.9 1845.16
  5397.9 1846.17  5518.8 1844.01    5857 1851.05    5927 1849.55  5979.9 1850.36
#Mann= 9 ,-1 , 0
  3518.7     .07       0  3795.5    .045       0  4210.2     .07       0
  4351.4    .045       0  4610.7     .07       0  4632.4    .035       0
  4789.8     .07       0  4973.4     .07       0  5006.8     .07       0
Bank Sta=4973.4,5006.8
XS Rating Curve= 0 ,0
Exp/Cntr=0.3,0.1

Type RM Length L Ch R = 1 ,70706   ,732,732,732
BEGIN DESCRIPTION:
Little Elm Creek 70706.25
END DESCRIPTION:
XS GIS Cut Line= 3
      1540340.42      6820887.68      1542503.81      6820415.83
      1542944.81      6820315.13
#Sta/Elev= 30
  2784.4 1848.72  2850.4 1848.64  2993.3 1848.56  3350.8 1847.64  3532.3 1846.55
  3782.5 1844.99  4036.7    1845  4099.2  1845.3  4129.9  1840.3  4168.4 1842.41
  4181.1 1844.19    4222 1844.71  4242.5 1840.62  4259.5 1846.77  4264.6 1845.33
  4283.4 1844.95  4641.6 1844.82  4773.4 1843.03  4948.7 1843.77  4969.6 1842.29
  4979.4 1843.57    4980  1837.2  4980.6  1836.7  5013.4  1837.2  5040.9  1842.2
  5051.1 1841.39  5133.2 1847.76  5307.6 1849.72  5345.1 1848.08    5451 1847.97
#Mann= 11 ,-1 , 0
  2784.4    .045       0  2850.4     .07       0  2993.3    .045       0
  3350.8     .07       0  3532.3    .045       0  3782.5     .07       0
  4036.7    .035       0  4168.4     .07       0    4980     .07       0
  5013.4     .07       0  5345.1    .045       0
Bank Sta=4980,5013.4
XS Rating Curve= 0 ,0
Exp/Cntr=0.3,0.1

Type RM Length L Ch R = 1 ,69974   ,287,287,287
BEGIN DESCRIPTION:
Little Elm Creek 69974.39
END DESCRIPTION:
XS GIS Cut Line= 4
      1540349.15      6820970.14      1541685.95      6820679.34
      1542554.01       6820718.4      1542951.13      6820660.62
#Sta/Elev= 30
  3161.5 1848.03  3518.6 1847.71  3699.1 1847.42  3752.3 1847.03  3764.1 1846.98
  3967.2 1845.85  4097.3 1845.12  4433.6 1845.01  4531.6 1844.13  4538.6 1841.28
  4558.6  1838.3  4588.8 1836.72  4638.7  1837.2  4698.8 1847.12  4718.8 1844.52
  4748.8 1847.71  4768.9 1843.83    4939 1842.84    4949 1837.67  4952.4 1834.32
    4953 1833.82  4985.8 1834.32  4999.1 1840.71  5049.1 1842.43  5069.2 1841.22
  5429.8 1844.51  5490.4 1843.37  5561.2 1845.85  5634.9 1845.56  5799.8 1846.81
#Mann= 12 ,-1 , 0
  3161.5     .07       0  3518.6    .045       0  3699.1     .07       0
  3752.3    .045       0  3764.1     .07       0  3967.2    .045       0
  4097.3     .07       0  4433.6    .035       0  4588.8     .07       0
  4952.4     .07       0  4985.8     .07       0  5634.9    .045       0
Bank Sta=4952.4,4985.8
XS Rating Curve= 0 ,0
Exp/Cntr=0.3,0.1

Type RM Length L Ch R = 1 ,69687   ,336,336,336
BEGIN DESCRIPTION:
Little Elm Creek 69686.76
END DESCRIPTION:
XS GIS Cut Line= 3
      1540331.78      6821039.58      1542159.04       6820987.5
      1543031.75       6820810.4
#Sta/Elev= 30
  3170.8 1848.11  3578.7 1847.04  3771.8 1846.59  3983.6  1845.6  4237.4 1844.21
  4324.8 1844.26  4374.5 1843.34  4404.5 1843.72  4493.6 1842.93  4974.8 1842.85
  4984.8 1841.79  4988.2 1832.09  4988.8 1831.59    5021 1831.59  5021.6 1832.09
  5025.9 1837.24  5035.5 1839.67  5055.9 1840.54  5076.6 1840.45  5096.7 1841.84
  5137.5 1840.94  5249.8 1841.11  5375.4 1843.74  5443.6 1842.64  5494.7 1843.15
  5527.3  1844.4  5566.1 1843.57  5607.9 1843.66  5729.9 1845.48  5889.3 1845.46
#Mann= 10 ,-1 , 0
  3170.8     .07       0  3578.7    .045       0  3771.8     .07       0
  3983.6    .045       0  4237.4     .07       0  4324.8    .035       0
  4493.6     .07       0  4988.2     .07       0  5021.6     .07       0
  5607.9    .045       0
Bank Sta=4988.2,5021.6
XS Rating Curve= 0 ,0
Exp/Cntr=0.3,0.1