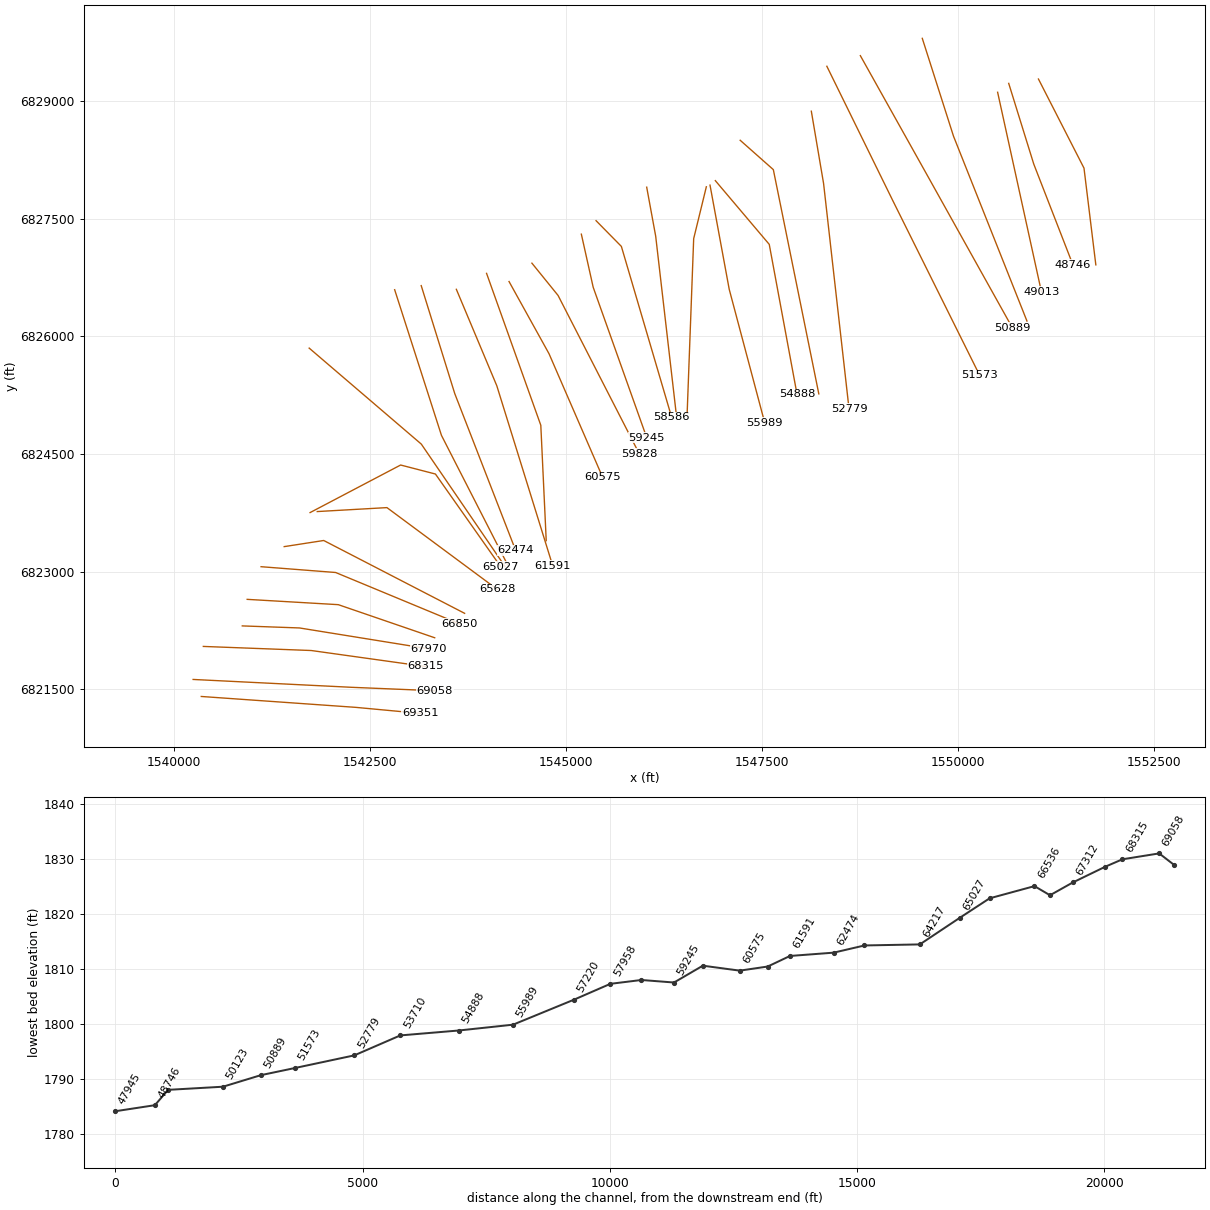
HEC-RAS study Little Elm Creek.prj: Little Elm Creek Base Level Engineering

--- Little Elm Creek.g01 (geometry) --- (continued)

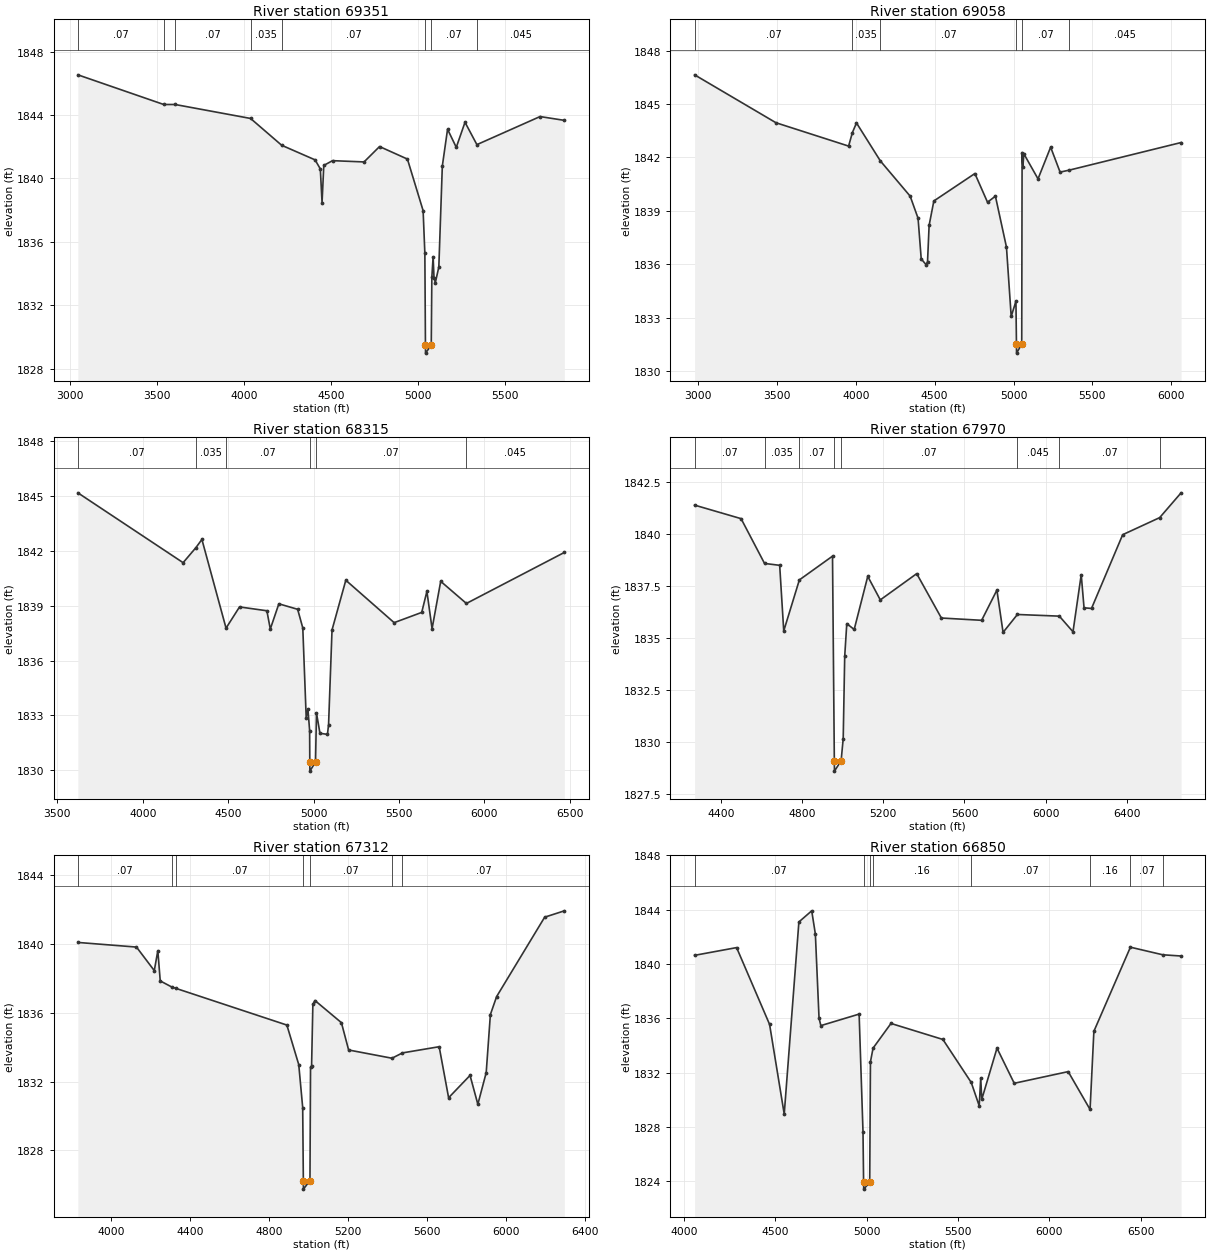
Type RM Length L Ch R = 1 ,69351   ,293,293,293
BEGIN DESCRIPTION:
Little Elm Creek 69351.4
END DESCRIPTION:
XS GIS Cut Line= 3
      1540353.46      6821408.51      1542323.97      6821269.62
       1543144.2      6821192.97
#Sta/Elev= 30
  3043.9 1846.53    3538 1844.66  3603.5 1844.66  4037.7 1843.78  4216.6 1842.09
  4408.8 1841.17  4438.9  1840.6  4448.9 1838.48  4458.9 1840.82  4509.1 1841.12
  4690.6 1841.04  4779.7 1842.01  4940.1 1841.22  5030.4 1837.97  5040.4 1835.28
  5043.8 1829.49  5044.4 1828.99  5077.2 1829.49  5080.6 1833.77    5088 1835.07
    5093 1833.74  5100.7 1833.43  5120.8 1834.42  5140.9 1840.78    5171  1843.1
  5221.2 1841.96  5271.4 1843.54  5339.8 1842.13  5703.3  1843.9  5843.1 1843.66
#Mann= 8 ,-1 , 0
  3043.9     .07       0    3538    .045       0  3603.5     .07       0
  4037.7    .035       0  4216.6     .07       0  5043.8     .07       0
  5077.2     .07       0  5339.8    .045       0
Bank Sta=5043.8,5077.2
XS Rating Curve= 0 ,0
Exp/Cntr=0.3,0.1

Type RM Length L Ch R = 1 ,69058   ,743,743,743
BEGIN DESCRIPTION:
Little Elm Creek 69058.04
END DESCRIPTION:
XS GIS Cut Line= 3
      1540249.33      6821625.52      1542263.21      6821525.69
      1543331.64      6821481.43
#Sta/Elev= 30
  2977.2 1846.64  3493.5 1843.95  3954.1 1842.64  3978.1  1843.4  4004.1 1843.94
  4155.3 1841.81  4344.5 1839.83  4394.6 1838.59  4414.6 1836.31  4445.8 1835.98
  4454.7 1836.16  4464.7 1838.19  4494.7 1839.56    4755  1841.1  4835.1 1839.49
  4885.2 1839.83  4955.3 1836.97  4985.3 1833.08  5015.4 1833.93  5018.7 1831.52
  5019.3 1831.02  5052.1 1831.52  5054.5 1842.28  5059.5 1841.49  5065.4 1842.21
  5155.5  1840.8  5235.5 1842.58  5295.4 1841.18  5353.3 1841.29  6062.9 1842.84
#Mann= 6 ,-1 , 0
  2977.2     .07       0  3978.1    .035       0  4155.3     .07       0
  5018.7     .07       0  5052.1     .07       0  5353.3    .045       0
Bank Sta=5018.7,5052.1
XS Rating Curve= 0 ,0
Exp/Cntr=0.3,0.1

Type RM Length L Ch R = 1 ,68315   ,345,345,345
BEGIN DESCRIPTION:
Little Elm Creek 68315.37
END DESCRIPTION:
XS GIS Cut Line= 3
      1540379.48      6822046.53       1541755.4      6821994.44
      1543211.82      6821790.72
#Sta/Elev= 30
  3620.3 1845.17  4236.3 1841.35    4311 1842.17  4346.3 1842.62  4487.6 1837.77
  4566.5 1838.93  4726.6 1838.72  4746.6 1837.72  4796.7  1839.1  4906.7  1838.8
  4936.8 1837.78  4956.8 1832.86  4966.8 1833.35  4976.8 1832.17  4977.8 1830.45
  4978.4 1829.95  5011.2 1830.45    5017 1833.13  5037.2 1832.02  5081.2 1831.96
  5087.7  1832.5  5107.9 1837.67  5188.6 1840.39  5471.4 1838.07  5632.9 1838.63
  5663.2 1839.78  5693.5 1837.74    5744 1840.33  5894.4 1839.12  6467.8 1841.91
#Mann= 6 ,-1 , 0
  3620.3     .07       0    4311    .035       0  4487.6     .07       0
  4977.8     .07       0  5011.2     .07       0  5894.4    .045       0
Bank Sta=4977.8,5011.2
XS Rating Curve= 0 ,0
Exp/Cntr=0.3,0.1

Type RM Length L Ch R = 1 ,67970   ,658,658,658
BEGIN DESCRIPTION:
Little Elm Creek 67969.82
END DESCRIPTION:
XS GIS Cut Line= 3
      1540876.16      6822308.19      1541605.37      6822282.15
       1543250.6      6822016.62
#Sta/Elev= 30
  4270.6 1841.38  4499.6 1840.73  4615.1 1838.58  4689.7 1838.49  4709.7 1835.34
  4786.7 1837.79  4949.9 1838.93  4958.9 1829.11  4959.5 1828.61  4992.3 1829.11
  5002.6 1830.17    5010 1834.12  5020.2 1835.69  5056.7 1835.41  5123.5 1837.96
  5185.3 1836.83  5364.6 1838.09  5486.1 1835.96  5684.5 1835.85  5759.6  1837.3
    5790 1835.27  5860.6 1836.13  6067.1 1836.05  6134.4  1835.3  6174.9 1838.04
  6188.8 1836.45  6225.6 1836.42  6379.1 1839.96  6561.4 1840.78  6666.8 1841.97
#Mann= 8 ,-1 , 0
  4270.6     .07       0  4615.1    .035       0  4786.7     .07       0
  4958.9     .07       0  4992.3     .07       0  5860.6    .045       0
  6067.1     .07       0  6561.4    .045       0
Bank Sta=4958.9,4992.3
XS Rating Curve= 0 ,0
Exp/Cntr=0.3,0.1

Type RM Length L Ch R = 1 ,67312   ,462,462,462
BEGIN DESCRIPTION:
Little Elm Creek 67311.56
END DESCRIPTION:
XS GIS Cut Line= 3
      1540938.74      6822646.73      1542100.16      6822579.02
      1543329.28      6822157.16
#Sta/Elev= 30
  3831.6  1840.1  4128.4 1839.83  4218.5 1838.46  4236.4 1839.62  4248.6 1837.86
  4306.3 1837.51  4329.6 1837.42  4889.7 1835.29  4949.8 1832.99  4969.8 1830.49
  4973.1 1826.24  4973.7 1825.74  5006.6 1826.24  5009.5 1832.83  5014.8 1832.91
  5021.3  1836.5  5031.8 1836.72  5165.8 1835.43  5202.3 1833.84  5421.6 1833.36
    5475 1833.67  5660.7 1834.03  5708.5 1831.06    5817 1832.36  5856.5 1830.68
  5898.8 1832.52  5919.9  1835.9  5951.6 1836.95  6194.8 1841.57  6294.5 1841.94
#Mann= 7 ,-1 , 0
  3831.6     .07       0  4306.3    .035       0  4329.6     .07       0
  4973.1     .07       0  5006.6     .07       0  5421.6    .045       0
    5475     .07       0
Bank Sta=4973.1,5006.6
XS Rating Curve= 0 ,0
Exp/Cntr=0.3,0.1

Type RM Length L Ch R = 1 ,66850   ,314,314,314
BEGIN DESCRIPTION:
Little Elm Creek 66850.4
END DESCRIPTION:
XS GIS Cut Line= 3
      1541115.66      6823063.02      1542066.16      6822989.23
      1543646.05      6822333.84
#Sta/Elev= 30
  4058.2 1840.64  4288.2 1841.21  4468.8 1835.55    4549 1828.94  4629.3  1843.1
  4699.5 1843.92  4719.5 1842.21  4739.6 1836.01  4749.6 1835.46  4959.1 1836.31
  4980.3 1827.64  4983.6 1823.91  4984.3 1823.41  5017.1 1823.91  5021.1 1832.79
  5035.4  1833.8  5133.5 1835.62  5417.8 1834.44    5573 1831.27  5616.6 1829.55
    5625  1831.6  5630.5 1830.02    5714  1833.8  5808.4 1831.21  6103.8 1832.07
  6223.6 1829.28  6244.5 1835.04  6444.5 1841.24  6621.8 1840.68    6722 1840.59
#Mann= 8 ,-1 , 0
  4058.2     .07       0  4983.6     .07       0  5017.1     .07       0
  5035.4     .16       0    5573     .07       0  6223.6     .16       0
  6444.5     .07       0  6621.8    .035       0
Bank Sta=4983.6,5017.1
XS Rating Curve= 0 ,0
Exp/Cntr=0.3,0.1

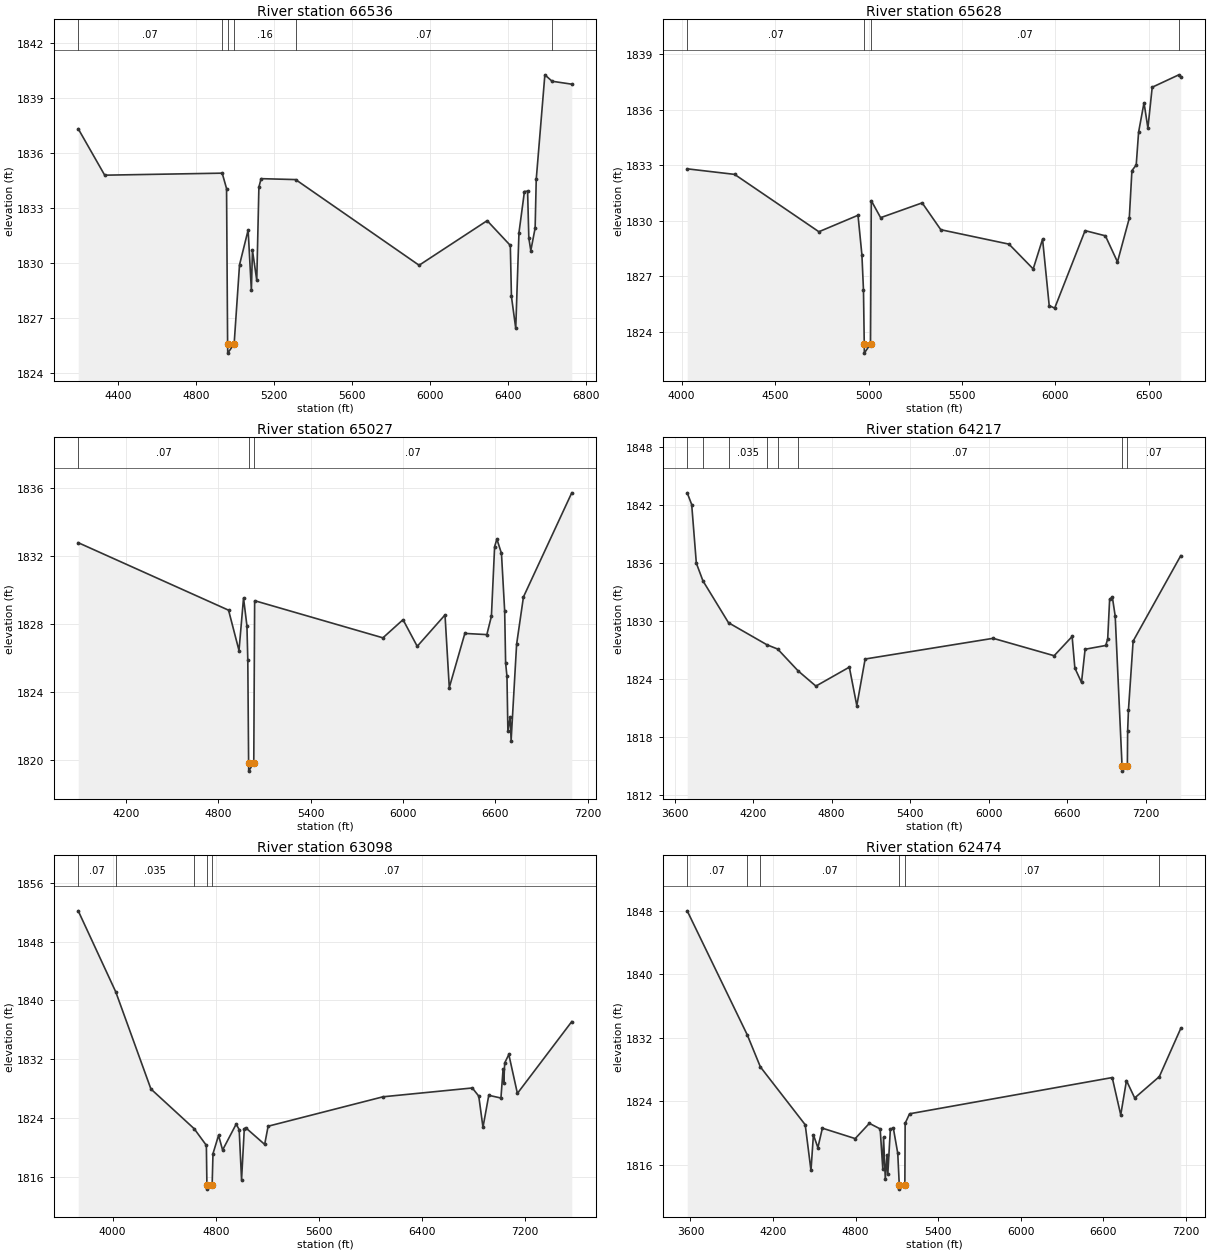
Type RM Length L Ch R = 1 ,66536   ,908,908,908
BEGIN DESCRIPTION:
Little Elm Creek 66536.38
END DESCRIPTION:
XS GIS Cut Line= 3
      1541410.79       6823319.1      1541914.25      6823397.22
      1543710.58      6822468.69
#Sta/Elev= 30
  4194.5  1837.3  4330.3 1834.77  4933.1 1834.88  4955.4 1834.04  4960.8 1825.57
  4961.5 1825.07  4994.3 1825.57  5021.9 1829.88  5066.1 1831.78  5082.7 1828.49
  5088.3 1830.67  5110.4 1829.04  5121.3 1834.12  5132.6 1834.58  5309.6 1834.53
  5943.1 1829.86  6292.1 1832.29    6411 1830.94  6416.7 1828.16  6438.8 1826.42
  6455.3 1831.63  6483.4 1833.88  6499.6  1833.9  6505.9 1831.34  6516.1 1830.66
  6538.3 1831.89  6543.9 1834.54  6588.2 1840.24  6625.2 1839.89  6726.1 1839.73
#Mann= 6 ,-1 , 0
  4194.5     .07       0  4933.1     .16       0  4960.8     .07       0
  4994.3     .16       0  5309.6     .07       0  6625.2    .035       0
Bank Sta=4960.8,4994.3
XS Rating Curve= 0 ,0
Exp/Cntr=0.3,0.1

Type RM Length L Ch R = 1 ,65628   ,601,601,601
BEGIN DESCRIPTION:
Little Elm Creek 65911.96
END DESCRIPTION:
XS GIS Cut Line= 3
      1541831.82      6823766.15      1542720.41      6823816.47
      1544126.08      6822774.77
#Sta/Elev= 30
  4030.3 1832.81  4283.9 1832.51  4734.6 1829.41  4943.8  1830.3  4964.7 1828.16
  4973.1 1826.25  4977.2 1823.35  4977.8 1822.85  5010.7 1823.35  5014.8 1831.09
  5064.8 1830.17    5287 1830.97  5386.6 1829.52  5751.4 1828.74  5880.8  1827.4
  5930.9 1829.01  5966.4 1825.42  5995.6 1825.28  6158.3 1829.47  6266.9 1829.19
  6331.6 1827.78  6394.7 1830.14  6408.8 1832.71  6431.8 1833.02  6444.5 1834.79
  6473.5 1836.38  6494.3 1835.01  6517.3 1837.22  6659.6 1837.89  6669.9 1837.77
#Mann= 4 ,-1 , 0
  4030.3     .07       0  4977.2     .07       0  5010.7     .07       0
  6659.6    .035       0
Bank Sta=4977.2,5010.7
XS Rating Curve= 0 ,0
Exp/Cntr=0.3,0.1

Type RM Length L Ch R = 1 ,65027   ,810,810,810
BEGIN DESCRIPTION:
Little Elm Creek 64968.41
END DESCRIPTION:
XS GIS Cut Line= 4
      1541740.62      6823753.11      1542895.03      6824359.59
      1543338.71      6824244.69      1544169.57      6823065.06
#Sta/Elev= 30
  3890.8 1832.79  4867.2 1828.81    4935 1826.43  4964.4 1829.53  4986.5 1827.89
  4992.1 1825.89  4997.4 1819.82  4998.1 1819.32  5030.9 1819.82  5036.6 1829.37
  5869.6 1827.18  6000.2 1828.25  6092.5 1826.68  6272.9 1828.53  6300.7 1824.25
  6401.7 1827.44  6544.6 1827.37  6574.2 1828.45  6595.1 1832.56  6609.9    1833
  6639.5 1832.16  6660.4 1828.75  6666.5  1825.7  6675.2 1824.91  6681.3 1821.68
  6696.1 1822.51  6702.2 1821.12  6737.9  1826.8  6782.3 1829.59    7096 1835.73
#Mann= 3 ,-1 , 0
  3890.8     .07       0  4997.4     .07       0  5030.9     .07       0
Bank Sta=4997.4,5030.9
XS Rating Curve= 0 ,0
Exp/Cntr=0.3,0.1

Type RM Length L Ch R = 1 ,64217   ,1119,1119,1119
BEGIN DESCRIPTION:
Little Elm Creek 64209.7
END DESCRIPTION:
XS GIS Cut Line= 3
      1541728.97       6825850.1      1543158.59      6824626.24
      1544226.85      6823064.34
#Sta/Elev= 30
  3695.2 1843.24  3729.5 1842.03    3765 1835.97  3815.6 1834.14  4011.1 1829.81
  4305.2 1827.53  4387.1 1827.09  4543.6 1824.83  4679.4 1823.26  4935.1 1825.22
  4992.2 1821.24  5055.9 1826.06  6034.7  1828.2  6501.3  1826.4  6638.8 1828.39
  6659.7 1825.13  6710.5 1823.64    6738 1827.07    6896 1827.46  6910.9 1828.15
  6925.8 1832.26  6946.8 1832.43  6968.2  1830.5  7020.7 1814.97  7021.7 1814.47
  7061.2 1814.97  7063.3 1818.59  7069.4 1820.75  7105.3 1827.91  7469.4 1836.74
#Mann= 8 ,-1 , 0
  3695.2    .035       0  3815.6     .07       0  4011.1    .035       0
  4305.2     .07       0  4387.1    .035       0  4543.6     .07       0
  7020.7     .07       0  7061.2     .07       0
Bank Sta=7020.7,7061.2
XS Rating Curve= 0 ,0
Exp/Cntr=0.3,0.1

Type RM Length L Ch R = 1 ,63098   ,624,624,624
BEGIN DESCRIPTION:
Little Elm Creek 63069.68
END DESCRIPTION:
XS GIS Cut Line= 3
      1542818.92      6826594.61      1543415.69      6824737.14
      1544270.45      6823064.68
#Sta/Elev= 30
    3733 1852.19  4024.5 1841.14  4297.1 1827.92  4633.2  1822.5  4727.3 1820.24
  4731.5 1814.78  4732.5 1814.28    4772 1814.78  4778.6 1819.11  4821.8  1821.6
  4853.3 1819.61  4958.3 1823.13  4981.7  1822.4  5000.3 1815.55  5021.4 1822.47
  5031.9 1822.65  5179.6 1820.37  5206.4 1822.85  6098.5 1826.86  6790.7 1828.06
  6840.7 1826.95  6873.4  1822.7  6918.3 1827.06  7012.8 1826.69  7029.4 1830.64
  7035.1  1828.8  7041.9 1831.47  7073.9 1832.62  7140.5 1827.32  7562.2  1837.1
#Mann= 5 ,-1 , 0
    3733     .07       0  4024.5    .035       0  4633.2     .07       0
  4731.5     .07       0    4772     .07       0
Bank Sta=4731.5,4772
XS Rating Curve= 0 ,0
Exp/Cntr=0.3,0.1

Type RM Length L Ch R = 1 ,62474   ,883,883,883
BEGIN DESCRIPTION:
Little Elm Creek 62473.71
END DESCRIPTION:
XS GIS Cut Line= 3
      1543157.45      6826646.75      1543584.54      6825271.73
      1544361.26      6823271.68
#Sta/Elev= 30
  3576.2 1847.99  4012.3 1832.39  4107.8 1828.35  4433.5 1821.07  4475.4 1815.32
  4493.1  1819.8  4525.6 1818.19  4558.2 1820.64  4796.6 1819.33  4899.6 1821.25
    4978 1820.55  4997.2  1815.5  5002.5 1819.49  5015.4 1814.27  5028.3 1817.26
  5033.6 1814.86  5052.2 1820.55  5073.7 1820.65  5105.8 1817.48  5116.9 1813.47
  5117.9 1812.97  5157.4 1813.47  5159.5 1821.25  5191.6 1822.45  6663.8 1827.01
  6725.7 1822.31  6767.3 1826.63  6827.1 1824.44  7006.2 1827.13  7161.6 1833.19
#Mann= 6 ,-1 , 0
  3576.2     .07       0  4012.3    .035       0  4107.8     .07       0
  5116.9     .07       0  5157.4     .07       0  7006.2     .16       0
Bank Sta=5116.9,5157.4
XS Rating Curve= 0 ,0
Exp/Cntr=0.3,0.1

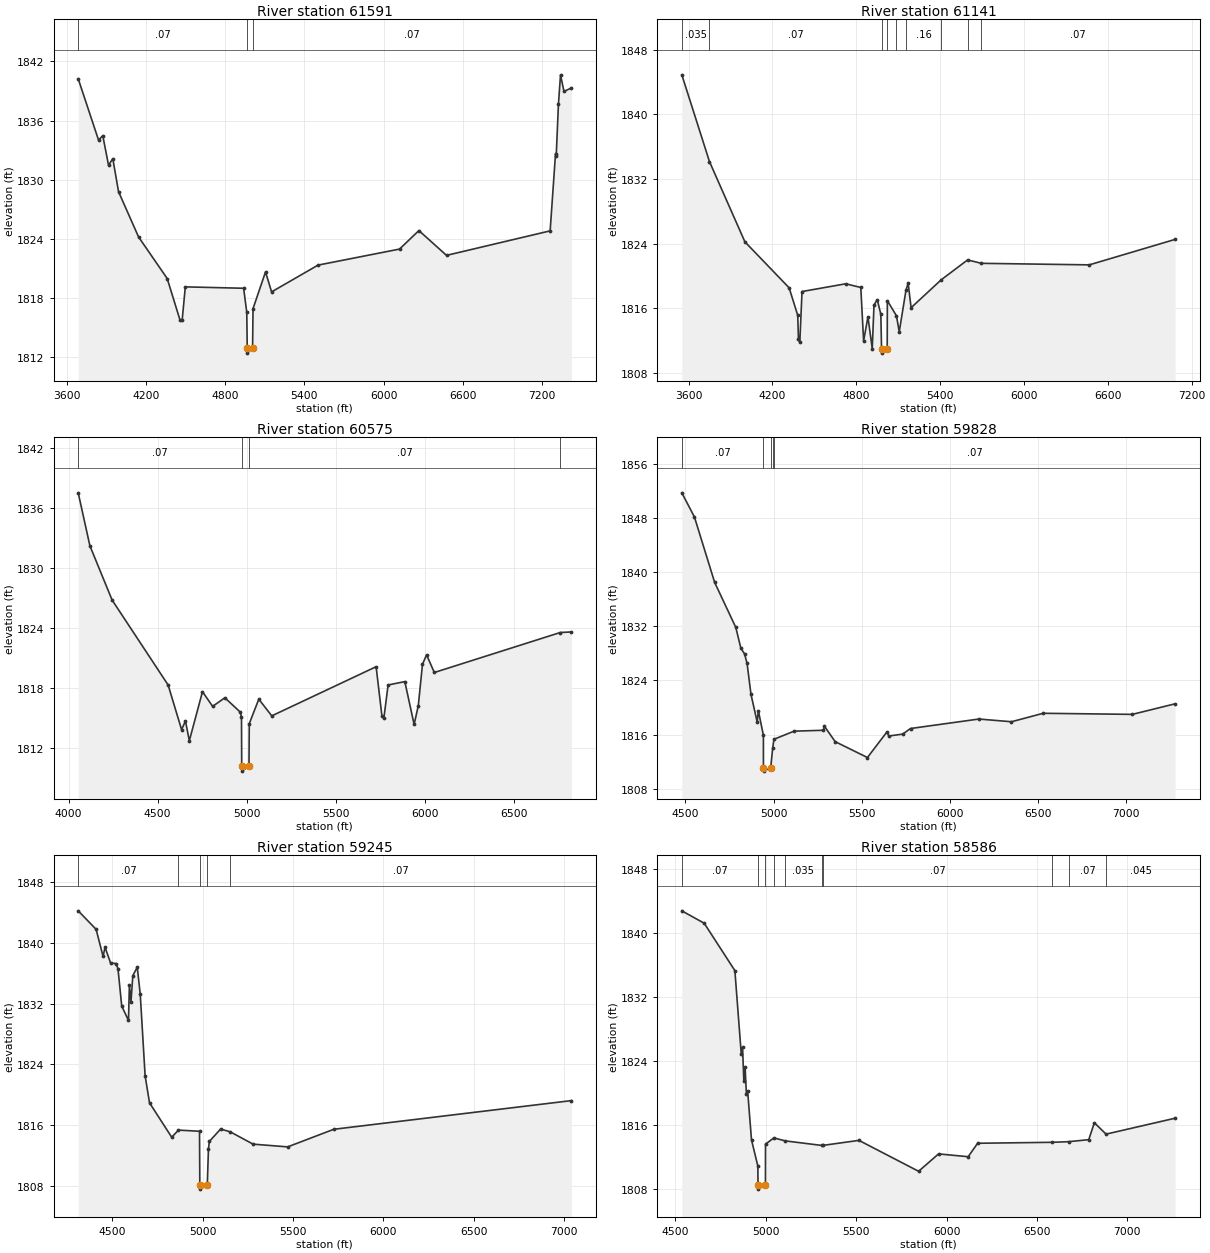
Type RM Length L Ch R = 1 ,61591   ,450,450,450
BEGIN DESCRIPTION:
Little Elm Creek 61590.57
END DESCRIPTION:
XS GIS Cut Line= 3
      1543605.36      6826599.89      1544120.99      6825370.69
      1544834.53      6823073.84
#Sta/Elev= 30
  3686.1 1840.24    3840 1834.02  3872.5 1834.46  3915.9 1831.46  3948.4 1832.12
  3991.8 1828.77  4143.6 1824.17  4360.5 1819.95  4458.1 1815.71    4474 1815.72
  4497.8  1819.1  4939.8 1818.96  4963.6 1816.52  4967.1 1812.87  4968.1 1812.37
  5007.6 1812.87  5011.1 1816.89  5105.7 1820.62  5151.7 1818.59  5503.6 1821.31
  6121.4 1822.94  6268.1 1824.82  6477.4  1822.3  7262.8 1824.79  7303.6 1832.64
  7308.9 1832.44  7325.6 1837.64  7341.4 1840.64  7367.5 1838.95  7424.2 1839.31
#Mann= 3 ,-1 , 0
  3686.1     .07       0  4967.1     .07       0  5007.6     .07       0
Bank Sta=4967.1,5007.6
XS Rating Curve= 0 ,0
Exp/Cntr=0.3,0.1

Type RM Length L Ch R = 1 ,61141   ,566,566,566
BEGIN DESCRIPTION:
Little Elm Creek 61108.8
END DESCRIPTION:
XS GIS Cut Line= 3
      1543990.78      6826802.99      1544682.38        6824866.
      1544751.31      6823395.06
#Sta/Elev= 30
  3551.6 1844.88  3749.5 1834.14  4002.9 1824.22  4319.3 1818.53  4380.9 1815.13
  4386.2 1812.16  4395.7 1811.78  4411.7 1818.07  4724.9 1819.03  4832.2 1818.57
  4852.3 1811.95  4883.2 1814.94    4914 1811.01  4926.7 1816.41  4950.1 1817.06
  4975.6 1815.25  4980.7 1810.95  4981.7 1810.45  5021.2 1810.95  5022.2 1816.94
  5087.3 1815.07  5107.2 1813.09  5155.9 1818.27  5170.9  1819.1  5192.1 1816.07
  5406.7 1819.51  5596.3 1821.98  5695.3 1821.56  6467.3 1821.37  7080.9 1824.52
#Mann= 9 ,-1 , 0
  3551.6    .035       0  3749.5     .07       0  4980.7     .07       0
  5021.2     .07       0  5087.3     .07       0  5155.9     .16       0
  5406.7     .07       0  5596.3     .16       0  5695.3     .07       0
Bank Sta=4980.7,5021.2
XS Rating Curve= 0 ,0
Exp/Cntr=0.3,0.1

Type RM Length L Ch R = 1 ,60575   ,747,747,747
BEGIN DESCRIPTION:
Little Elm Creek 60583.14
END DESCRIPTION:
XS GIS Cut Line= 3
      1544277.24      6826698.83      1544786.87      6825778.84
       1545471.5       6824201.2
#Sta/Elev= 30
  4053.8 1837.55  4119.5 1832.25  4244.3 1826.82  4559.1 1818.32  4634.7 1813.85
  4656.4 1814.72  4678.2 1812.74  4752.1 1817.65  4809.2 1816.18  4877.8 1817.04
  4965.5 1815.59  4971.3 1815.07  4972.6  1810.2  4973.6  1809.7  5013.4  1810.2
    5015 1814.45  5068.6  1816.9  5141.5 1815.23  5727.8 1820.15  5760.5 1815.21
  5771.7 1815.05  5795.1 1818.32    5889 1818.66  5941.3 1814.37  5964.8 1816.25
  5988.3 1820.39  6011.2 1821.34  6054.8 1819.57  6762.2 1823.57  6825.3 1823.63
#Mann= 4 ,-1 , 0
  4053.8     .07       0  4972.6     .07       0  5013.4     .07       0
  6762.2     .16       0
Bank Sta=4972.6,5013.4
XS Rating Curve= 0 ,0
Exp/Cntr=0.3,0.1

Type RM Length L Ch R = 1 ,59828   ,583,583,583
BEGIN DESCRIPTION:
Little Elm Creek 59828.36
END DESCRIPTION:
XS GIS Cut Line= 3
      1544568.89      6826933.21      1544902.24      6826521.73
      1545938.16      6824501.95
#Sta/Elev= 30
  4479.4 1851.74  4550.8 1848.18  4665.8 1838.49  4785.8 1831.84  4814.5 1828.77
  4835.3 1827.94  4849.7 1826.52    4872 1821.94  4907.2 1817.85  4913.7 1819.54
  4942.4 1815.89  4942.6  1811.1  4943.6  1810.6  4983.8  1811.1  4995.1 1814.01
  5002.3 1815.31  5116.8 1816.51  5282.9 1816.64  5288.7 1817.24  5349.7 1814.96
  5532.8 1812.61  5643.8  1816.4  5653.8 1815.79  5732.6 1816.07  5777.4  1816.9
  6165.3  1818.3  6350.5  1817.9  6530.4 1819.15  7036.1 1818.99  7278.9 1820.55
#Mann= 5 ,-1 , 0
  4479.4     .07       0  4942.6     .07       0  4983.8     .07       0
  4995.1     .16       0  5002.3     .07       0
Bank Sta=4942.6,4983.8
XS Rating Curve= 0 ,0
Exp/Cntr=0.3,0.1

Type RM Length L Ch R = 1 ,59245   ,659,659,659
BEGIN DESCRIPTION:
Little Elm Creek 59244.8
END DESCRIPTION:
XS GIS Cut Line= 3
      1545199.13      6827302.94      1545350.16       6826625.9
      1546032.46       6824709.2
#Sta/Elev= 30
  4311.8 1844.23  4410.9 1841.79  4449.3 1838.22  4460.3 1839.43    4491 1837.35
  4521.8 1837.28    4532 1836.57  4552.5 1831.68  4589.9 1829.78    4595 1834.44
  4603.7 1832.27    4614 1835.69  4638.5  1836.8    4655 1833.22  4681.9 1822.49
  4706.2 1818.92  4829.1 1814.38  4866.3 1815.32  4982.8 1815.17  4984.5 1808.04
  4985.5 1807.54  5025.7 1808.04  5032.3 1812.87  5037.6 1813.84  5099.3 1815.46
  5152.2  1815.1  5279.2 1813.47  5470.3 1813.11  5725.5 1815.43    7040 1819.21
#Mann= 5 ,-1 , 0
  4311.8     .07       0  4866.3     .16       0  4984.5     .07       0
  5025.7     .16       0  5152.2     .07       0
Bank Sta=4984.5,5025.7
XS Rating Curve= 0 ,0
Exp/Cntr=0.3,0.1

Type RM Length L Ch R = 1 ,58586   ,628,628,628
BEGIN DESCRIPTION:
Little Elm Creek 58585.94
END DESCRIPTION:
XS GIS Cut Line= 3
      1545386.62      6827474.86      1545709.54      6827146.73
      1546350.17      6824969.61
#Sta/Elev= 30
  4535.2 1842.77  4659.1 1841.22  4828.8  1835.3  4864.2 1824.86  4871.2 1825.75
  4878.4 1821.49  4885.4 1823.25  4892.5 1819.87  4899.5 1820.22  4920.8 1814.15
  4956.1 1810.87  4956.7  1808.5  4957.7    1808    4998  1808.5  4998.3 1813.62
  5044.8  1814.4  5106.6 1814.03  5309.2 1813.46  5317.6 1813.47  5515.5 1814.09
  5845.6 1810.23  5956.1  1812.4    6120 1812.05  6172.2 1813.73  6585.4 1813.85
  6677.2 1813.93  6787.2 1814.18  6818.4 1816.29  6883.2 1814.87    7265 1816.86
#Mann= 10 ,-1 , 0
  4535.2     .07       0  4956.7     .07       0    4998     .07       0
  5044.8     .16       0  5106.6    .035       0  5309.2     .16       0
  5317.6     .07       0  6585.4    .045       0  6677.2     .07       0
  6883.2    .045       0
Bank Sta=4956.7,4998
XS Rating Curve= 0 ,0
Exp/Cntr=0.3,0.1

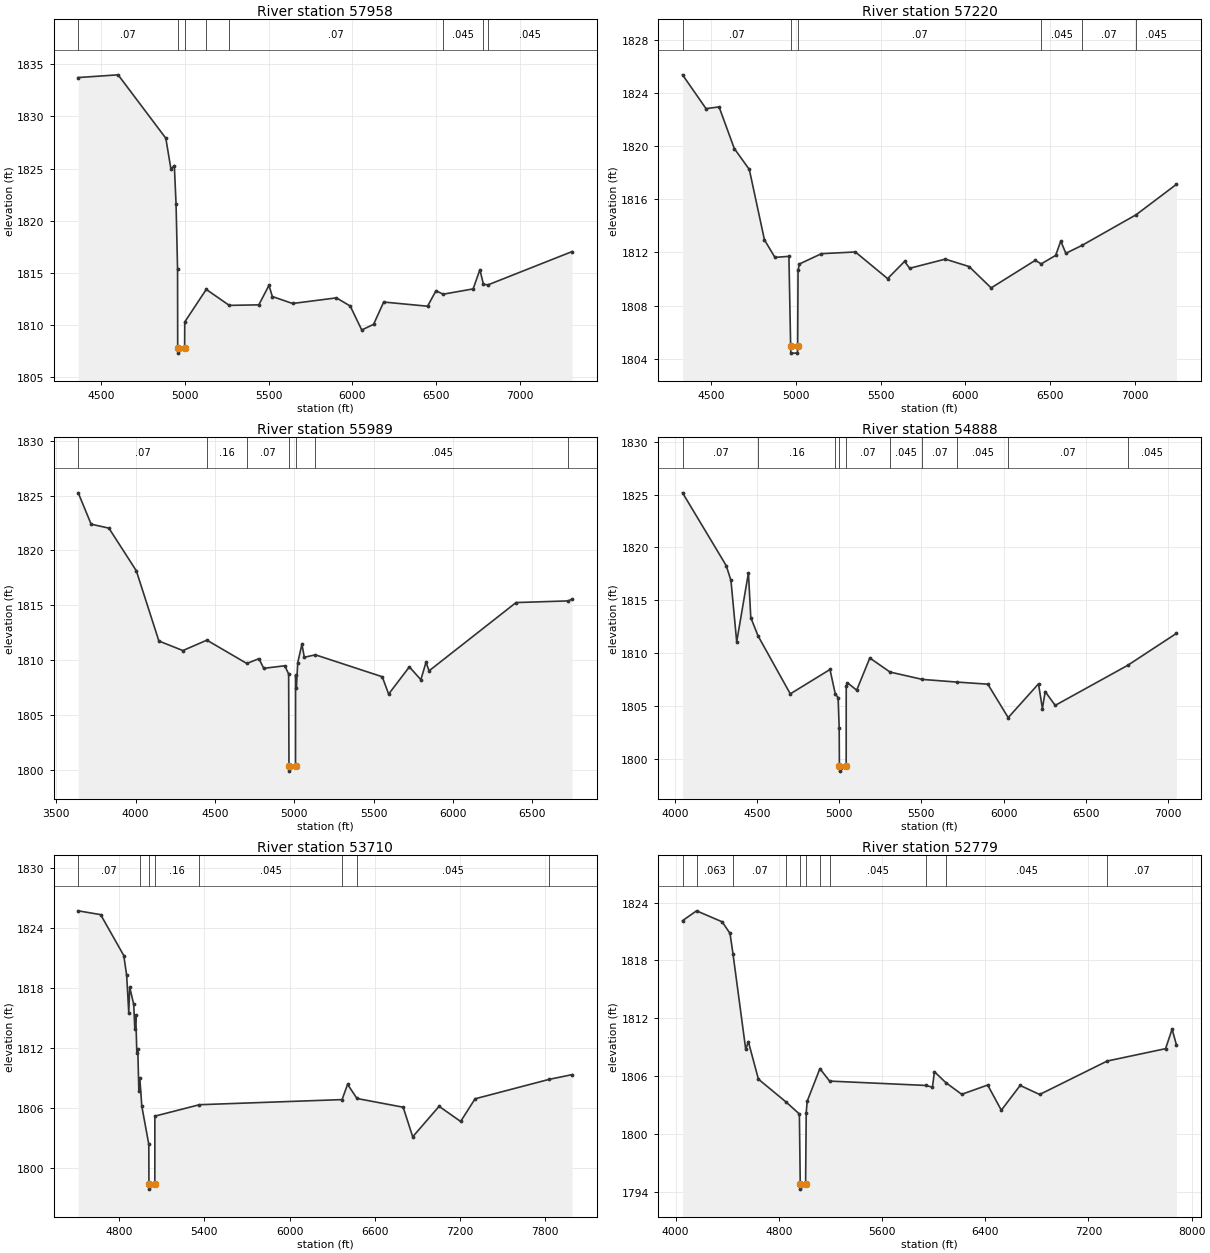
Type RM Length L Ch R = 1 ,57958   ,738,738,738
BEGIN DESCRIPTION:
Little Elm Creek 57958.43
END DESCRIPTION:
XS GIS Cut Line= 3
      1546032.46      6827901.92      1546147.04      6827276.94
      1546412.49      6824981.54
#Sta/Elev= 30
  4364.8 1833.73  4602.6 1833.99  4887.3 1827.91  4917.8 1824.95  4938.1 1825.29
  4948.3 1821.62  4957.3 1815.36  4958.1  1807.8  4959.1  1807.3  4999.4  1807.8
  5000.2 1810.29  5128.4 1813.41  5265.8 1811.88  5442.1 1811.93  5502.5  1813.8
  5522.6 1812.73  5643.4 1812.06  5905.1  1812.6  5987.1 1811.82  6056.1 1809.52
  6126.6 1810.06    6187  1812.2  6448.7  1811.8  6499.1 1813.29  6541.1 1812.95
  6720.5 1813.46  6760.8  1815.3  6782.1 1813.89  6809.7 1813.85  7310.9 1817.04
#Mann= 8 ,-1 , 0
  4364.8     .07       0  4958.1     .07       0  4999.4     .07       0
  5128.4    .035       0  5265.8     .07       0  6541.1    .045       0
  6782.1     .07       0  6809.7    .045       0
Bank Sta=4958.1,4999.4
XS Rating Curve= 0 ,0
Exp/Cntr=0.3,0.1

Type RM Length L Ch R = 1 ,57220   ,1231,1231,1231
BEGIN DESCRIPTION:
Little Elm Creek 57219.61
END DESCRIPTION:
XS GIS Cut Line= 3
      1546792.87      6827907.17      1546631.41      6827245.69
      1546548.08      6825016.55
#Sta/Elev= 30
  4332.8  1825.4  4471.2 1822.85  4548.1 1822.98  4637.9 1819.84  4726.4 1818.26
  4815.7 1812.95  4877.5 1811.63  4959.9 1811.71  4970.1 1804.91  4971.1 1804.41
  5010.4 1804.41  5011.4 1804.91  5013.7 1810.65  5021.4 1811.13  5151.5 1811.91
  5351.6 1812.04  5541.8 1810.03  5641.8 1811.33  5671.8 1810.81    5882  1811.5
  6022.1 1810.94  6152.2 1809.33  6412.4 1811.41    6447 1811.14  6532.4 1811.78
  6562.5 1812.86  6592.5 1811.94    6687 1812.53  7007.1 1814.85  7244.4 1817.14
#Mann= 6 ,-1 , 0
  4332.8     .07       0  4970.1     .07       0  5011.4     .07       0
    6447    .045       0    6687     .07       0  7007.1    .045       0
Bank Sta=4970.1,5011.4
XS Rating Curve= 0 ,0
Exp/Cntr=0.3,0.1

Type RM Length L Ch R = 1 ,55989   ,1101,1101,1101
BEGIN DESCRIPTION:
Little Elm Creek 55988.63
END DESCRIPTION:
XS GIS Cut Line= 3
      1546839.74      6827927.99      1547084.54      6826599.86
      1547537.67      6824896.71
#Sta/Elev= 30
  3638.4 1825.26  3719.7  1822.4  3831.6 1822.04  4004.5 1818.15  4146.8 1811.74
  4298.1 1810.87  4449.3 1811.82  4701.2 1809.69  4777.3 1810.13  4807.8 1809.25
    4940 1809.48  4964.6 1808.74  4966.7 1800.37  4967.7 1799.87    5008 1800.37
  5008.3  1808.6  5013.4 1807.46  5021.9 1809.76  5048.4 1811.45  5063.3 1810.26
  5133.6 1810.48  5554.7 1808.48  5594.9  1806.9  5725.5 1809.38    5798 1808.21
  5830.6 1809.81  5849.7 1809.02  6398.1 1815.25  6727.3  1815.4  6751.3 1815.57
#Mann= 7 ,-1 , 0
  3638.4     .07       0  4449.3     .16       0  4701.2     .07       0
  4966.7     .07       0    5008     .07       0  5133.6    .045       0
  6727.3     .07       0
Bank Sta=4966.7,5008
XS Rating Curve= 0 ,0
Exp/Cntr=0.3,0.1

Type RM Length L Ch R = 1 ,54888   ,1178,1178,1178
BEGIN DESCRIPTION:
Little Elm Creek 54888.26
END DESCRIPTION:
XS GIS Cut Line= 3
      1546907.44      6827985.29      1547594.95      6827172.77
      1547948.96      6825262.15
#Sta/Elev= 30
  4045.4 1825.18  4311.5 1818.28  4340.1 1816.88  4375.2 1811.06  4446.6  1817.6
  4460.9 1813.36  4505.3 1811.62  4701.5 1806.13  4943.2 1808.44  4975.4 1806.13
  4992.6 1805.77  4999.2 1802.93  5000.6 1799.31  5001.6 1798.81  5041.9 1799.31
  5042.1 1806.85  5049.8 1807.18  5105.8 1806.48  5185.8 1809.53  5308.7  1808.2
  5505.7  1807.5  5714.7 1807.25  5904.4 1807.05  6028.5 1803.88    6213 1807.08
  6236.8 1804.74  6253.7 1806.35  6314.7 1805.04  6755.7 1808.83  7052.9 1811.86
#Mann= 10 ,-1 , 0
  4045.4     .07       0  4505.3     .16       0  4975.4     .07       0
  5000.6     .07       0  5041.9     .07       0  5308.7    .045       0
  5505.7     .07       0  5714.7    .045       0  6028.5     .07       0
  6755.7    .045       0
Bank Sta=5000.6,5041.9
XS Rating Curve= 0 ,0
Exp/Cntr=0.3,0.1

Type RM Length L Ch R = 1 ,53710   ,931,931,931
BEGIN DESCRIPTION:
Little Elm Creek 53924.02
END DESCRIPTION:
XS GIS Cut Line= 3
      1547224.37      6828500.06      1547646.97       6828125.8
      1548226.92      6825266.62
#Sta/Elev= 30
  4510.3 1825.68  4668.3  1825.3  4831.4 1821.22  4851.8 1819.24  4866.5 1815.53
  4873.2 1818.07  4901.6 1816.34  4909.2 1813.88  4915.8 1815.28  4923.4 1811.51
  4930.1 1811.86  4937.6 1807.71  4944.3 1809.04  4958.5 1806.19  5007.8 1802.39
  5008.9 1798.42  5009.9 1797.92  5050.3 1798.42  5050.5  1805.2  5364.9 1806.34
  6370.3 1806.85  6409.2 1808.37  6475.7 1806.96  6801.2 1806.09  6868.4 1803.14
  7054.5 1806.18  7206.5 1804.67  7307.9 1806.93  7830.9 1808.87  7992.2 1809.34
#Mann= 8 ,-1 , 0
  4510.3     .07       0  4944.3     .16       0  5008.9     .07       0
  5050.3     .16       0  5364.9    .045       0  6370.3     .07       0
  6475.7    .045       0  7830.9     .07       0
Bank Sta=5008.9,5050.3
XS Rating Curve= 0 ,0
Exp/Cntr=0.3,0.1

Type RM Length L Ch R = 1 ,52779   ,1206,1206,1206
BEGIN DESCRIPTION:
Little Elm Creek 52781.62
END DESCRIPTION:
XS GIS Cut Line= 3
       1548131.4      6828870.73      1548287.66      6827948.81
      1548612.31      6825074.55
#Sta/Elev= 30
  4054.4 1822.12  4162.9 1823.14  4361.4    1822  4422.3  1820.8    4445 1818.71
    4544 1808.78  4564.3 1809.58  4642.4 1805.69  4856.7 1803.32  4959.9 1802.08
  4966.6 1794.79  4967.6 1794.29    5008 1794.79  5012.9 1802.22  5020.5 1803.41
  5118.9 1806.78  5194.1 1805.49  5938.1 1805.04    5991 1804.86  6006.7 1806.46
  6094.9 1805.33    6218 1804.12  6419.3 1805.08    6525 1802.47  6670.9 1805.04
  6821.9  1804.1  7345.7 1807.57    7798 1808.85  7848.3 1810.87    7882 1809.25
#Mann= 11 ,-1 , 0
  4054.4     .07       0  4162.9    .063       0    4445     .07       0
  4856.7     .16       0  4966.6     .07       0    5008     .16       0
  5118.9     .07       0  5194.1    .045       0  5938.1     .07       0
  6094.9    .045       0  7345.7     .07       0
Bank Sta=4966.6,5008
XS Rating Curve= 0 ,0
Exp/Cntr=0.3,0.1

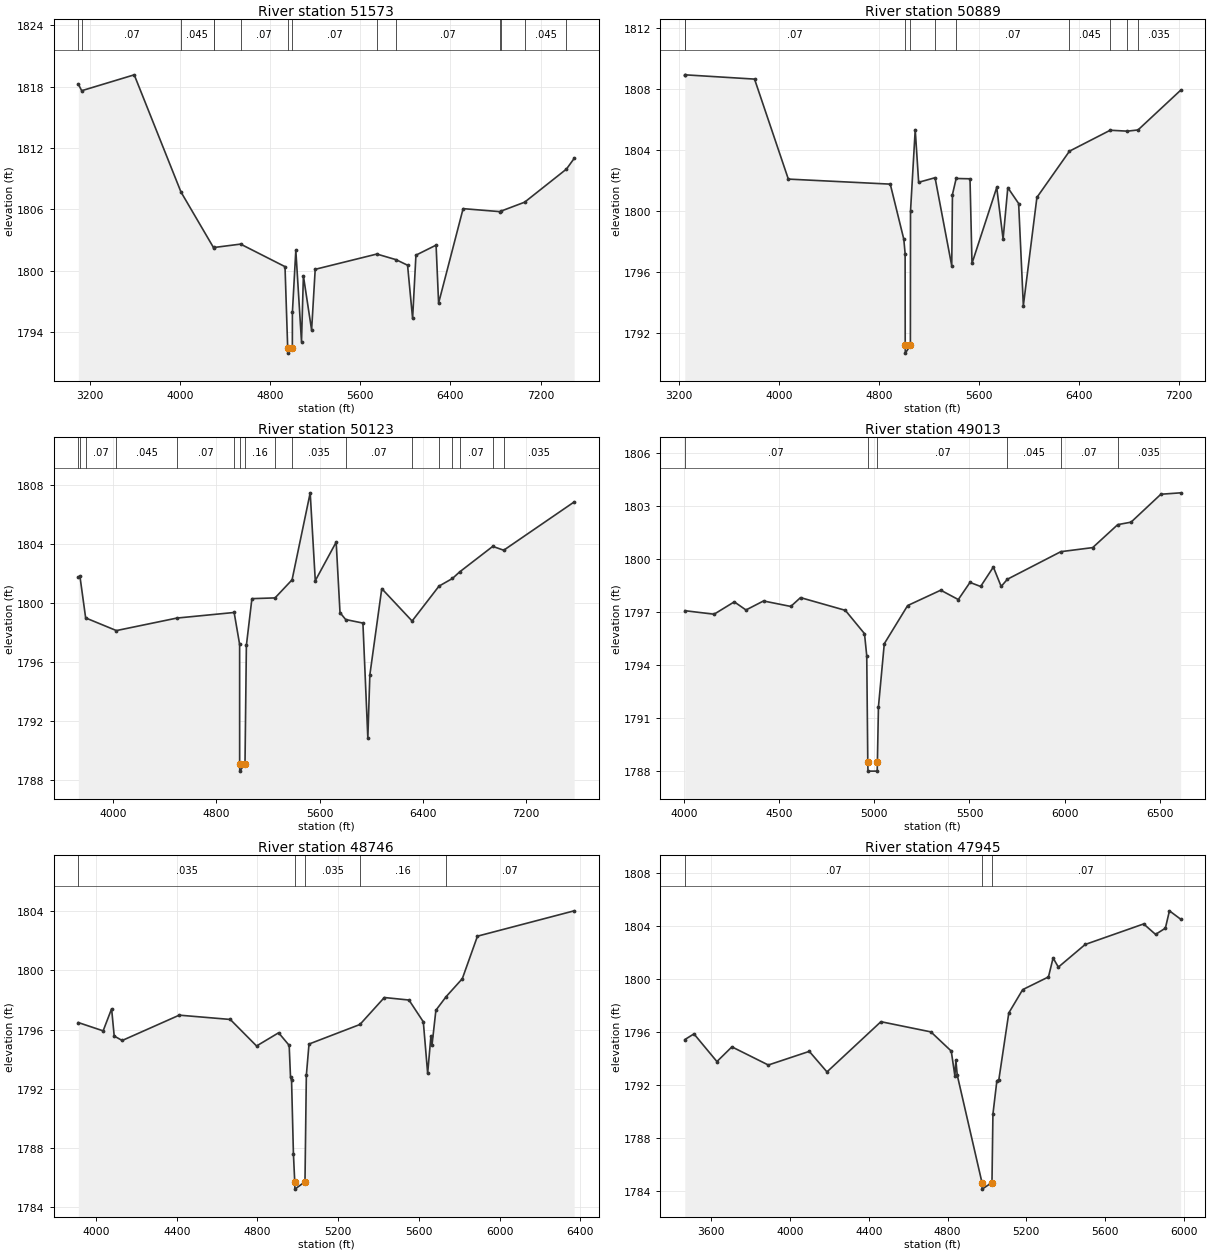
Type RM Length L Ch R = 1 ,51573   ,684,684,684
BEGIN DESCRIPTION:
Little Elm Creek 51572.93
END DESCRIPTION:
XS GIS Cut Line= 3
      1548329.32      6829443.61      1549167.87      6827735.27
      1550278.68      6825501.35
#Sta/Elev= 30
    3100 1818.23  3129.8 1817.59  3595.8 1819.14  4010.2 1807.71  4301.2 1802.24
  4304.9 1802.29  4539.3 1802.62  4933.2 1800.42    4957 1792.48    4958 1791.98
  4998.4 1792.48  4998.7 1795.95  5029.1 1802.01  5079.5 1793.09  5096.3 1799.52
  5169.1 1794.23    5201 1800.16  5747.8 1801.65  5918.1  1801.1  6020.2 1800.56
    6065 1795.36  6094.5 1801.54  6273.2 1802.52  6295.5 1796.86    6513 1806.08
  6837.5 1805.79  6851.7 1805.85  7058.5 1806.71  7429.3 1809.94  7497.9 1810.98
#Mann= 14 ,-1 , 0
    3100    .035       0  3129.8     .07       0  4010.2    .045       0
  4301.2     .07       0  4304.9    .045       0  4539.3     .07       0
    4957     .07       0  4998.4     .07       0  5747.8    .045       0
  5918.1     .07       0  6837.5    .045       0  6851.7    .035       0
  7058.5    .045       0  7429.3    .035       0
Bank Sta=4957,4998.4
XS Rating Curve= 0 ,0
Exp/Cntr=0.3,0.1

Type RM Length L Ch R = 1 ,50889   ,766,766,766
BEGIN DESCRIPTION:
Little Elm Creek 50888.93
END DESCRIPTION:
XS GIS Cut Line= 3
       1548756.4      6829579.04      1549615.79      6828042.56
      1550693.13      6826111.67
#Sta/Elev= 30
  3244.8 1808.92  3247.9 1808.92  3803.5 1808.64  4074.1 1802.09  4890.6 1801.76
  4999.1 1798.15  5009.6 1797.21  5010.3 1791.19  5011.3 1790.69  5051.8 1791.19
  5052.8 1799.99  5090.5 1805.33  5117.9 1801.88  5249.4 1802.18    5383 1796.41
  5388.7 1801.08  5418.5 1802.13  5529.3 1802.11  5545.3 1796.57  5743.4 1801.54
  5794.4 1798.16  5832.1 1801.53  5918.9 1800.49  5956.6  1793.8  6065.2 1800.89
  6326.1 1803.92  6652.4 1805.29  6790.1 1805.23  6875.3 1805.31  7216.4 1807.91
#Mann= 10 ,-1 , 0
  3244.8    .035       0  3247.9     .07       0  5010.3     .07       0
  5051.8     .07       0  5249.4    .035       0  5418.5     .07       0
  6326.1    .045       0  6652.4    .035       0  6790.1    .045       0
  6875.3    .035       0
Bank Sta=5010.3,5051.8
XS Rating Curve= 0 ,0
Exp/Cntr=0.3,0.1

Type RM Length L Ch R = 1 ,50123   ,1110,1110,1110
BEGIN DESCRIPTION:
Little Elm Creek 50124.35
END DESCRIPTION:
XS GIS Cut Line= 3
      1549546.08      6829799.75      1549943.91      6828552.98
       1550880.7      6826195.38
#Sta/Elev= 30
  3728.9 1801.77  3741.2 1801.84  3785.7    1799  4024.2 1798.14  4493.2 1798.99
  4937.4 1799.37  4979.9  1797.2  4980.1 1789.09  4981.1 1788.59  5021.6 1789.09
  5032.3 1797.13  5075.2 1800.31  5254.6 1800.36  5386.7 1801.59  5527.2  1807.5
  5566.7 1801.53  5728.7 1804.15  5758.4 1799.36  5802.3 1798.89  5936.1 1798.65
  5974.3 1790.84  5989.9 1795.13  6082.3 1800.99  6317.6 1798.79  6526.1 1801.16
  6630.4 1801.68  6685.5 1802.12  6943.1 1803.86  7028.3  1803.6  7574.5 1806.88
#Mann= 17 ,-1 , 0
  3728.9     .07       0  3741.2    .035       0  3785.7     .07       0
  4024.2    .045       0  4493.2     .07       0  4937.4     .16       0
  4980.1     .07       0  5021.6     .16       0  5254.6     .07       0
  5386.7    .035       0  5802.3     .07       0  6317.6    .045       0
  6526.1     .07       0  6630.4    .045       0  6685.5     .07       0
  6943.1    .045       0  7028.3    .035       0
Bank Sta=4980.1,5021.6
XS Rating Curve= 0 ,0
Exp/Cntr=0.3,0.1

Type RM Length L Ch R = 1 ,49013   ,267,267,267
BEGIN DESCRIPTION:
Little Elm Creek 49062.97
END DESCRIPTION:
XS GIS Cut Line= 2
      1550506.74       6829112.1      1551065.45      6826566.59
#Sta/Elev= 30
  4003.7  1797.1  4157.6  1796.9  4263.8  1797.6  4325.3 1797.14  4417.4 1797.65
  4560.8 1797.34  4611.9 1797.84  4847.4 1797.12  4948.2  1795.8    4960 1794.55
  4965.5 1788.52  4966.5 1788.02    5015 1788.02    5016 1788.52  5021.5 1791.66
  5052.2 1795.23    5175 1797.39  5349.1 1798.26  5441.2 1797.73  5502.7  1798.7
  5558.6 1798.47  5625.5 1799.57  5666.5 1798.47  5699.3 1798.88  5980.2 1800.44
  6147.6 1800.67  6279.2 1801.97  6349.2 1802.11    6506 1803.69  6609.8 1803.77
#Mann= 6 ,-1 , 0
  4003.7     .07       0  4965.5     .07       0    5016     .07       0
  5699.3    .045       0  5980.2     .07       0  6279.2    .035       0
Bank Sta=4965.5,5016
XS Rating Curve= 0 ,0
Exp/Cntr=0.3,0.1

Type RM Length L Ch R = 1 ,48746   ,801,801,801
BEGIN DESCRIPTION:
Little Elm Creek 48746.41
END DESCRIPTION:
XS GIS Cut Line= 3
      1550648.13      6829225.39      1550967.36      6828196.79
      1551466.85      6826911.65
#Sta/Elev= 30
  3912.8 1796.47  4035.7 1795.91  4077.6  1797.4  4090.5 1795.56    4130 1795.26
  4412.7 1796.97  4665.3 1796.68  4795.6 1794.89  4904.8 1795.78  4957.1 1794.93
  4963.7 1792.79  4968.9 1792.57  4978.1 1787.63  4984.6 1785.73  4985.6 1785.23
  5035.4 1785.73  5042.1  1792.9  5055.3 1795.02  5307.5 1796.34  5428.4 1798.16
  5550.5 1797.99  5621.5 1796.52    5643 1793.04  5659.3 1795.57  5664.7 1794.97
  5683.8  1797.3  5734.6 1798.22  5814.6 1799.43  5889.7  1802.3  6368.6 1804.01
#Mann= 5 ,-1 , 0
  3912.8    .035       0  4984.6    .035       0  5035.4    .035       0
  5307.5     .16       0  5734.6     .07       0
Bank Sta=4984.6,5035.4
XS Rating Curve= 0 ,0
Exp/Cntr=0.3,0.1

Type RM Length L Ch R = 1 ,47945   ,429,429,429
BEGIN DESCRIPTION:
Little Elm Creek 47944.59
END DESCRIPTION:
XS GIS Cut Line= 3
      1551027.14       6829281.1      1551607.99      6828144.71
      1551758.87      6826911.64
#Sta/Elev= 30
  3465.6 1795.42  3512.1 1795.85  3628.8 1793.76  3704.9 1794.87  3889.8  1793.5
    4098 1794.53  4187.8 1792.98  4461.8 1796.77  4715.7    1796  4819.1 1794.55
  4837.5 1792.68  4842.5 1793.87  4849.3 1792.75    4975 1784.63    4976 1784.13
  5025.9 1784.63  5030.7 1789.79  5050.8 1792.31  5060.9  1792.4  5111.3 1797.43
  5181.8 1799.19  5312.8 1800.15  5336.3 1801.58  5363.1 1800.89  5499.3  1802.6
  5796.3 1804.15  5856.8 1803.36  5906.6 1803.83  5927.3 1805.14  5984.1 1804.51
#Mann= 3 ,-1 , 0
  3465.6     .07       0    4975     .07       0  5025.9     .07       0
Bank Sta=4975,5025.9
XS Rating Curve= 0 ,0
Exp/Cntr=0.3,0.1