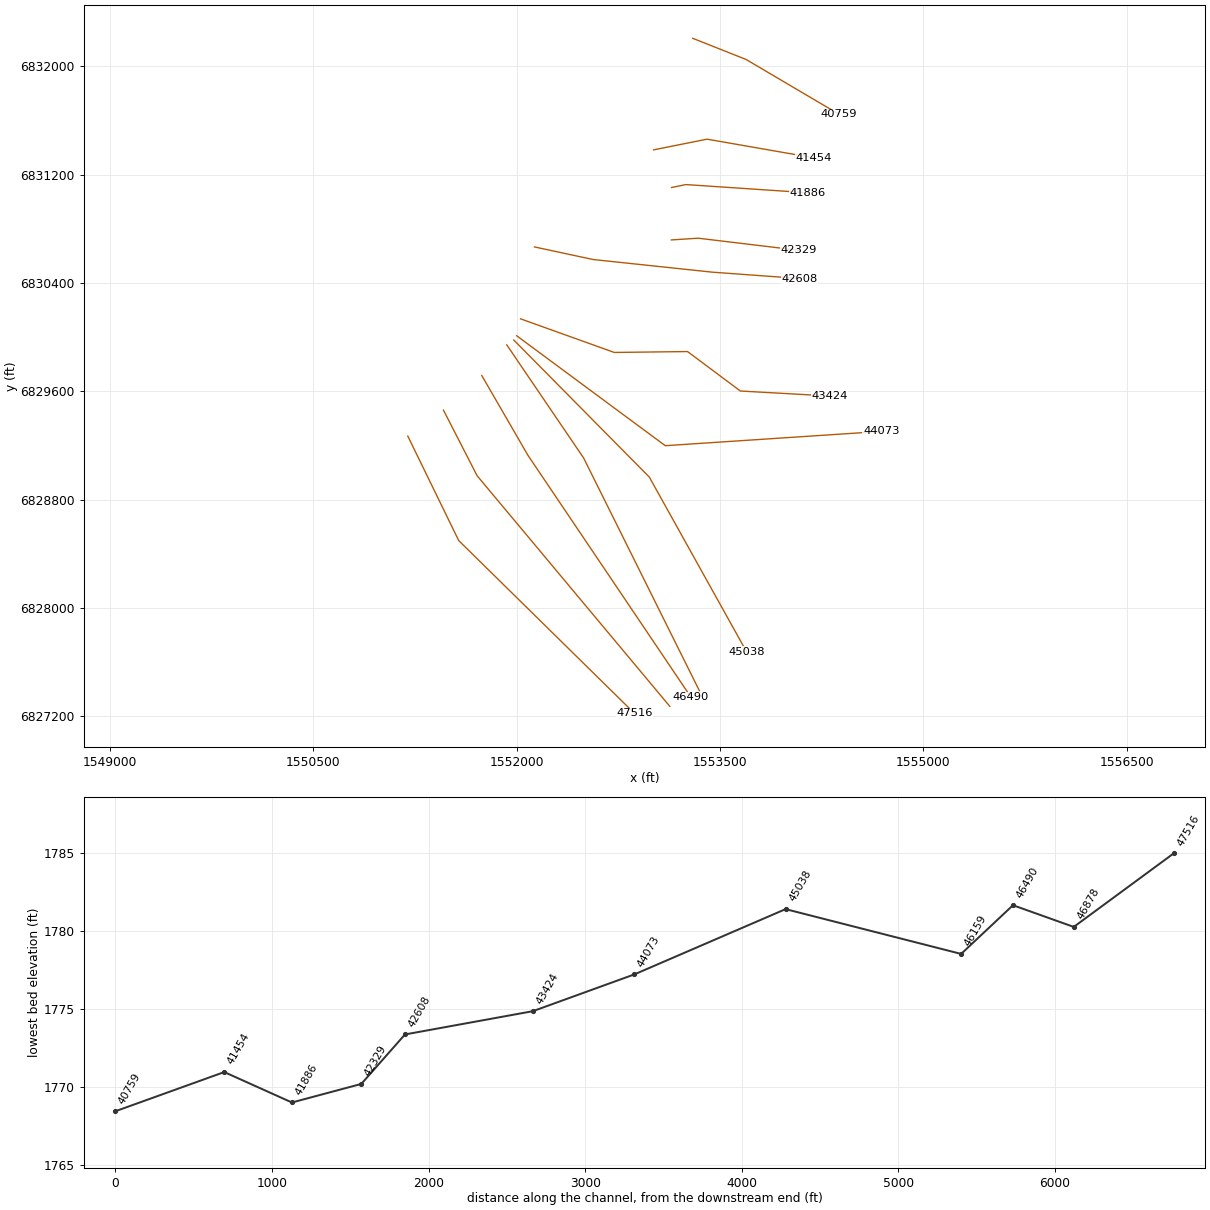
HEC-RAS study Little Elm Creek.prj: Little Elm Creek Base Level Engineering

--- Little Elm Creek.g01 (geometry) --- (continued)

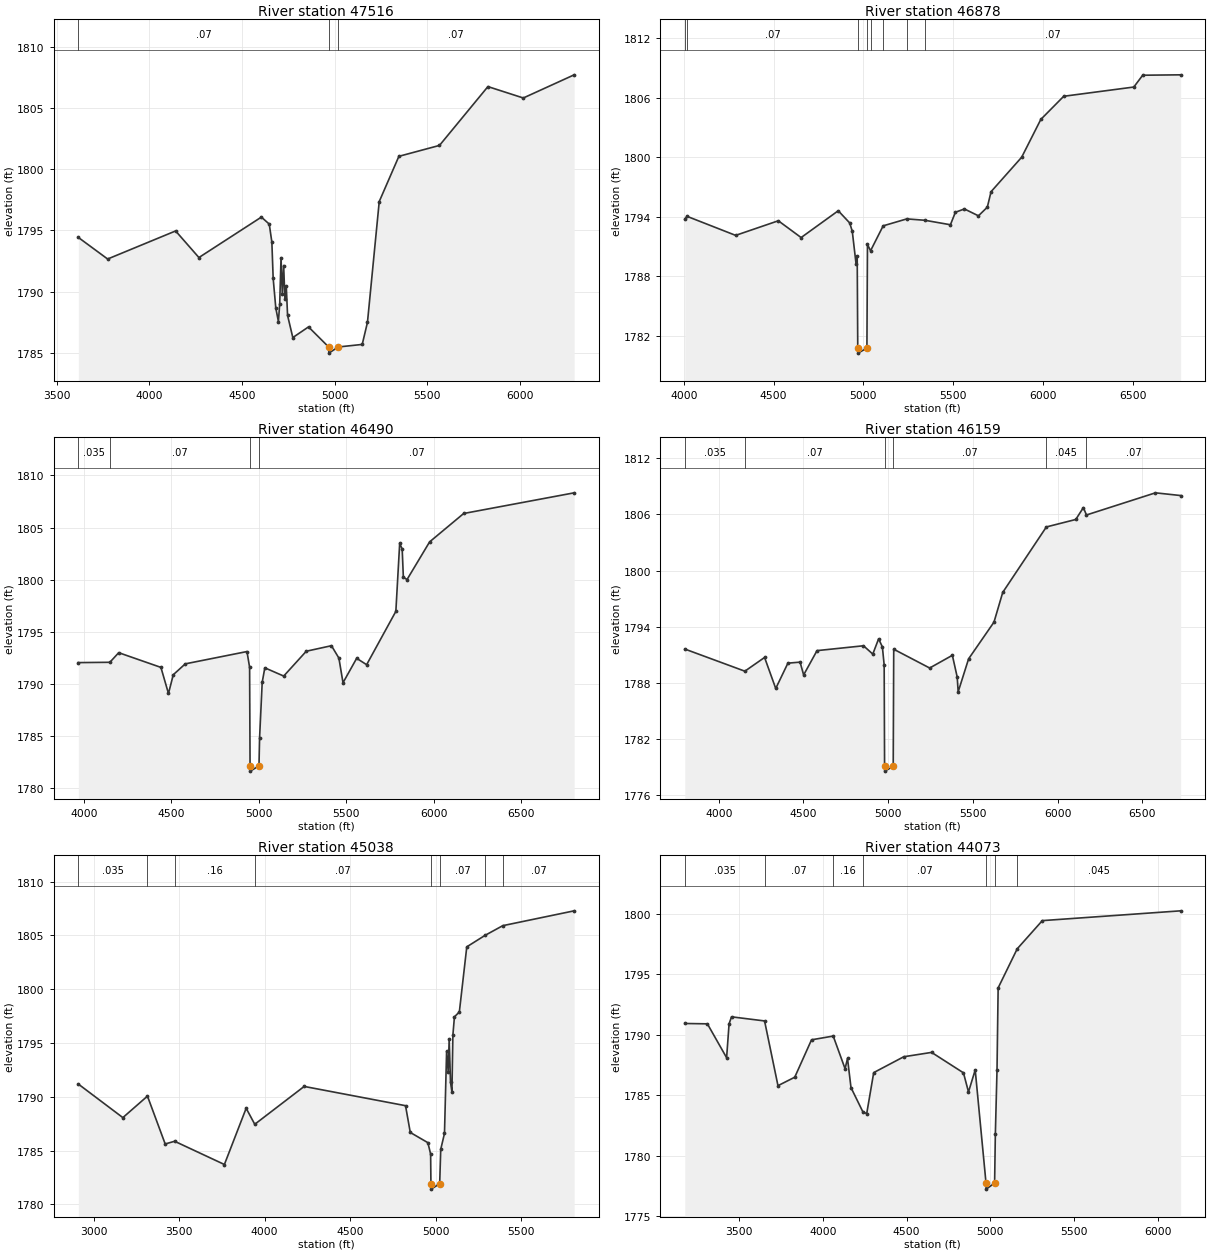
Type RM Length L Ch R = 1 ,47516   ,638,638,638
BEGIN DESCRIPTION:
Little Elm Creek 47515.65
END DESCRIPTION:
XS GIS Cut Line= 3
       1551195.9      6829270.33      1551571.53      6828498.87
      1552868.31      6827222.92
#Sta/Elev= 30
  3616.7 1794.42    3775 1792.66    4142 1794.95  4267.8 1792.78  4605.1 1796.08
  4647.6 1795.51  4661.7 1794.04  4668.7 1791.09  4682.9 1788.67    4697 1787.56
  4704.1 1788.99  4711.2 1792.77  4718.2  1789.8  4725.3 1792.13  4732.3 1789.39
  4739.5 1790.45  4746.5 1788.06  4774.8 1786.25  4859.6 1787.12  4968.5 1785.48
  4969.5 1784.98  5019.5 1785.48  5149.6 1785.69  5177.9 1787.49  5241.5 1797.35
  5347.6 1801.04  5566.8 1801.93  5828.4 1806.73  6019.4  1805.8    6294 1807.69
#Mann= 3 ,-1 , 0
  3616.7     .07       0  4968.5     .07       0  5019.5     .07       0
Bank Sta=4968.5,5019.5
XS Rating Curve= 0 ,0
Exp/Cntr=0.3,0.1

Type RM Length L Ch R = 1 ,46878   ,388,388,388
BEGIN DESCRIPTION:
Little Elm Creek 46878.45
END DESCRIPTION:
XS GIS Cut Line= 3
      1551459.14      6829461.68      1551706.95      6828978.04
      1553128.84      6827274.89
#Sta/Elev= 30
  4005.6 1793.77  4017.7 1794.05  4288.8 1792.13  4526.6  1793.6  4653.6 1791.91
  4860.5 1794.61  4924.3 1793.38  4938.6 1792.54  4959.5 1789.28    4966 1790.08
  4969.1 1780.77  4970.1 1780.27  5020.1 1780.77  5023.2 1791.22  5040.4 1790.58
  5110.6 1793.09  5242.3 1793.79  5343.2 1793.65  5485.3  1793.2  5513.1 1794.46
  5563.3 1794.79  5641.4  1794.1  5690.9 1794.97  5711.7 1796.53  5882.2    1800
  5988.9 1803.81  6116.5 1806.14  6506.9 1807.07  6556.4 1808.26  6767.7  1808.3
#Mann= 8 ,-1 , 0
  4005.6    .035       0  4017.7     .07       0  4969.1     .07       0
  5020.1     .07       0  5040.4    .035       0  5110.6     .07       0
  5242.3    .035       0  5343.2     .07       0
Bank Sta=4969.1,5020.1
XS Rating Curve= 0 ,0
Exp/Cntr=0.3,0.1

Type RM Length L Ch R = 1 ,46490   ,331,331,331
BEGIN DESCRIPTION:
Little Elm Creek 46490.172
END DESCRIPTION:
XS GIS Cut Line= 3
      1551741.53      6829717.79      1552081.95      6829129.08
      1553284.92      6827342.84
#Sta/Elev= 30
    3969 1792.06  4149.2 1792.09  4199.8 1793.01    4441  1791.6  4484.1  1789.1
  4511.7  1790.9  4580.2 1791.94  4932.8 1793.12  4947.8 1791.61  4950.4 1782.16
  4951.4 1781.66  5001.4 1782.16  5004.8 1784.82  5019.8 1790.17  5034.8 1791.56
  5142.7 1790.77  5271.7 1793.15  5415.6 1793.68  5458.1 1792.49  5481.6 1790.13
  5559.6 1792.47  5616.6 1791.86  5783.6 1796.97  5805.5 1803.49  5819.8 1802.94
  5826.5 1800.24  5847.5 1800.02  5976.6 1803.63  6171.3 1806.35  6802.6 1808.33
#Mann= 4 ,-1 , 0
    3969    .035       0  4149.2     .07       0  4950.4     .07       0
  5001.4     .07       0
Bank Sta=4950.4,5001.4
XS Rating Curve= 0 ,0
Exp/Cntr=0.3,0.1

Type RM Length L Ch R = 1 ,46159   ,1121,1121,1121
BEGIN DESCRIPTION:
Little Elm Creek 46158.732
END DESCRIPTION:
XS GIS Cut Line= 3
      1551926.18      6829943.81      1552493.41      6829108.25
      1553346.72       6827391.2
#Sta/Elev= 30
  3799.4  1791.6    4154 1789.23  4270.4  1790.7  4336.3 1787.38  4408.1 1790.09
    4480  1790.2    4501 1788.83    4580 1791.43  4854.3 1791.95  4909.3 1791.06
  4943.6 1792.69  4965.9 1791.83  4976.5 1789.88  4978.9 1779.04  4979.9 1778.54
  5029.9 1779.04  5032.9 1791.58  5245.1 1789.57  5379.1 1790.93  5407.7  1788.6
  5413.3 1787.02  5474.9 1790.55  5624.8 1794.48  5676.5 1797.66    5934 1804.66
  6107.7 1805.46  6152.5 1806.73  6170.7 1805.94  6578.1 1808.31  6726.7 1808.02
#Mann= 6 ,-1 , 0
  3799.4    .035       0    4154     .07       0  4978.9     .07       0
  5029.9     .07       0    5934    .045       0  6170.7     .07       0
Bank Sta=4978.9,5029.9
XS Rating Curve= 0 ,0
Exp/Cntr=0.3,0.1

Type RM Length L Ch R = 1 ,45038   ,965,965,965
BEGIN DESCRIPTION:
Little Elm Creek 45037.72
END DESCRIPTION:
XS GIS Cut Line= 3
      1551977.97      6829979.43      1552977.78      6828967.62
      1553696.52      6827675.98
#Sta/Elev= 30
  2910.5 1791.18    3171 1788.06  3314.9 1790.06  3418.6 1785.61  3473.9 1785.86
    3765  1783.7  3892.3 1788.93  3942.6 1787.44  4231.7 1790.96  4824.6 1789.17
  4852.4 1786.68  4955.4 1785.73  4971.4 1784.67  4973.2 1781.91  4974.2 1781.41
  5024.4 1781.91  5030.6 1785.11  5052.5 1786.59  5064.9 1794.22  5074.3 1792.33
    5080 1795.36  5087.8 1791.35    5096 1790.44  5101.7 1795.75  5110.7 1797.43
  5139.5 1797.89  5182.9 1803.94    5290 1805.01  5393.5 1805.91  5811.1 1807.29
#Mann= 8 ,-1 , 0
  2910.5    .035       0  3314.9     .07       0  3473.9     .16       0
  3942.6     .07       0  4973.2     .07       0  5024.4     .07       0
    5290    .045       0  5393.5     .07       0
Bank Sta=4973.2,5024.4
XS Rating Curve= 0 ,0
Exp/Cntr=0.3,0.1

Type RM Length L Ch R = 1 ,44073   ,649,649,649
BEGIN DESCRIPTION:
Little Elm Creek 44072.9
END DESCRIPTION:
XS GIS Cut Line= 3
      1551998.89      6830011.44      1553095.62      6829199.39
       1554689.4      6829304.87
#Sta/Elev= 30
  3174.6 1790.92  3309.6 1790.89  3424.4 1788.09  3439.1 1790.89  3453.7 1791.47
  3651.1 1791.13  3731.2 1785.78  3831.4 1786.48  3931.6 1789.57  4061.2 1789.88
    4132 1787.18  4146.6 1788.03  4167.4 1785.62  4239.3 1783.59  4261.4 1783.48
  4303.1 1786.86  4482.6 1788.17  4648.9 1788.53  4839.3 1786.84  4869.3 1785.26
  4909.4 1787.08    4974 1777.73    4975 1777.23  5025.3 1777.73  5029.7 1781.75
  5039.7 1787.11  5046.4 1793.86  5160.3 1797.09  5310.3 1799.42  6136.5 1800.23
#Mann= 7 ,-1 , 0
  3174.6    .035       0  3651.1     .07       0  4061.2     .16       0
  4239.3     .07       0    4974     .07       0  5025.3     .07       0
  5160.3    .045       0
Bank Sta=4974,5025.3
XS Rating Curve= 0 ,0
Exp/Cntr=0.3,0.1

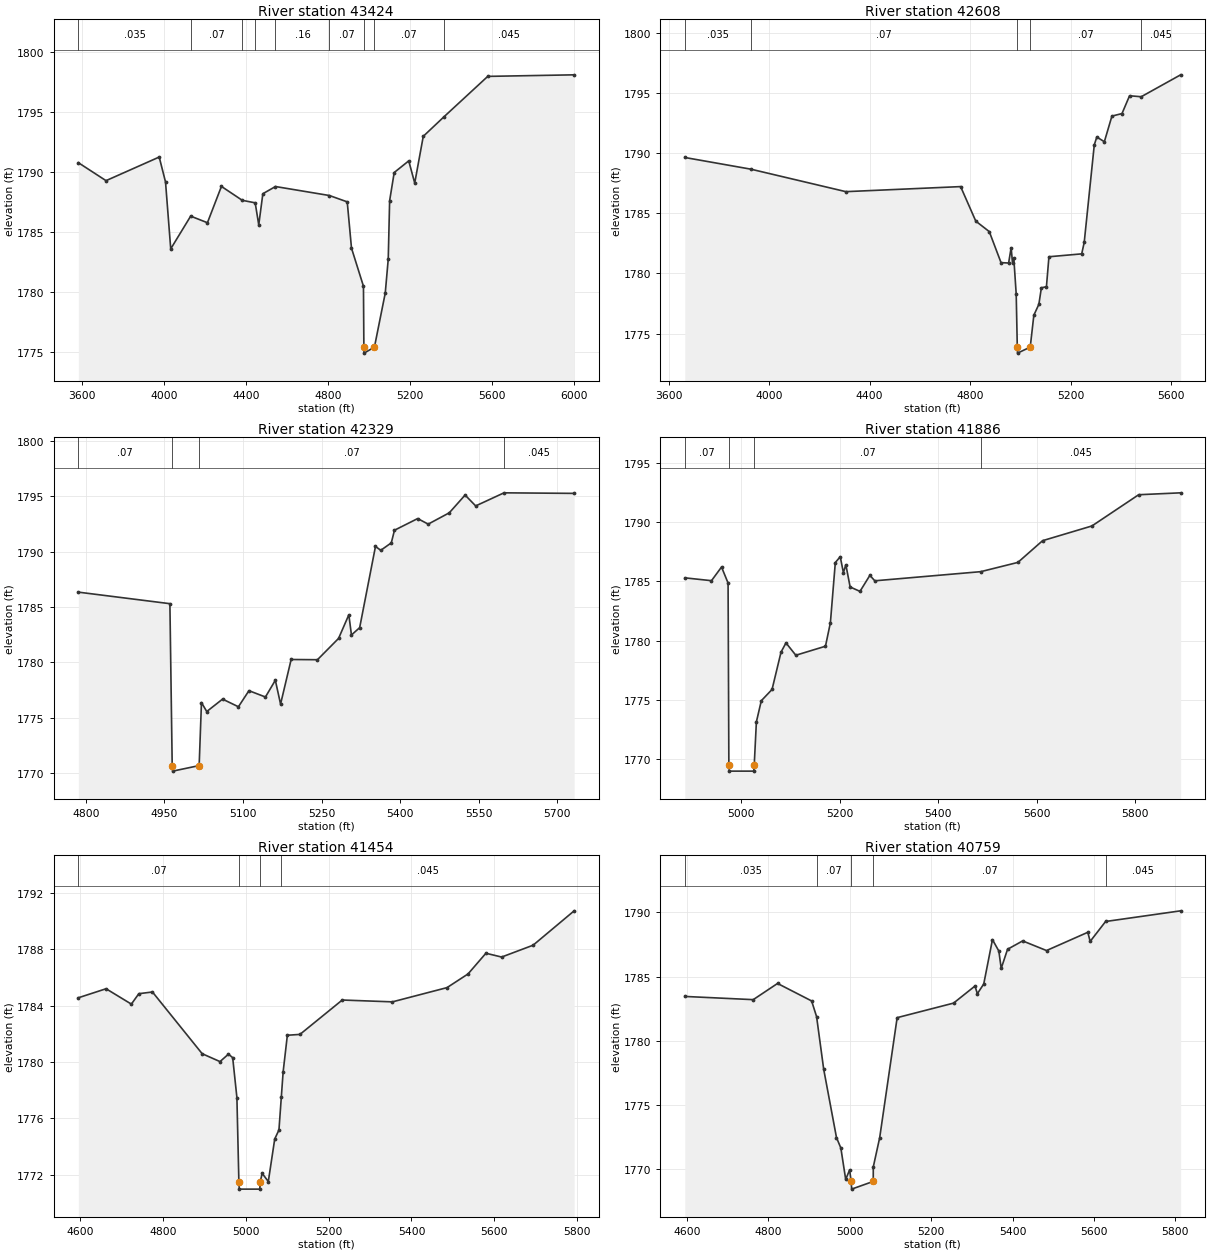
Type RM Length L Ch R = 1 ,43424   ,816,816,816
BEGIN DESCRIPTION:
Little Elm Creek 43345.92
END DESCRIPTION:
XS GIS Cut Line= 5
      1552027.87      6830136.08      1552719.21      6829887.92
      1553259.86      6829894.45      1553649.58      6829603.15
      1554305.98      6829566.53
#Sta/Elev= 30
  3581.1 1790.76  3716.2 1789.26  3975.7 1791.23  4006.5 1789.15  4031.9 1783.57
  4129.2  1786.3    4211 1785.75  4279.3 1788.78  4380.9 1787.62    4444 1787.41
  4461.4 1785.57  4481.4 1788.17    4543 1788.77  4806.2 1788.02  4893.1 1787.49
  4913.9 1783.63  4972.3 1780.45  4974.3 1775.37  4975.3 1774.87  5025.8 1775.37
  5078.6 1779.88  5093.2 1782.72    5100 1787.59  5122.3 1789.94  5193.2 1790.91
  5222.4 1789.06  5264.1 1792.96  5364.6 1794.58  5578.7 1797.96  6000.3 1798.09
#Mann= 9 ,-1 , 0
  3581.1    .035       0  4129.2     .07       0  4380.9     .16       0
    4444     .07       0    4543     .16       0  4806.2     .07       0
  4974.3     .07       0  5025.8     .07       0  5364.6    .045       0
Bank Sta=4974.3,5025.8
XS Rating Curve= 0 ,0
Exp/Cntr=0.3,0.1

Type RM Length L Ch R = 1 ,42608   ,279,279,279
BEGIN DESCRIPTION:
Little Elm Creek 42608.37
END DESCRIPTION:
XS GIS Cut Line= 4
      1552130.52      6830667.06       1552563.5      6830574.01
      1553443.28      6830480.64      1554087.79      6830433.77
#Sta/Elev= 30
  3664.4 1789.64  3927.1 1788.67  4305.6  1786.8  4762.4 1787.22  4822.8 1784.35
  4876.5 1783.48  4923.3  1780.9  4953.5 1780.87  4963.5 1782.14  4969.1 1780.86
  4974.1 1781.28  4983.7 1778.28    4988 1773.88    4989 1773.38  5039.5 1773.88
  5053.9 1776.53  5073.9 1777.44  5083.9 1778.81    5104  1778.9    5114 1781.39
  5244.4 1781.63  5254.4 1782.58  5294.5 1790.69  5304.5 1791.34  5334.6 1790.95
  5364.7 1793.08  5404.8 1793.29  5434.9 1794.77  5481.4 1794.69  5638.2 1796.51
#Mann= 5 ,-1 , 0
  3664.4    .035       0  3927.1     .07       0    4988     .07       0
  5039.5     .07       0  5481.4    .045       0
Bank Sta=4988,5039.5
XS Rating Curve= 0 ,0
Exp/Cntr=0.3,0.1

Type RM Length L Ch R = 1 ,42329   ,443,443,443
BEGIN DESCRIPTION:
Little Elm Creek 42328.99
END DESCRIPTION:
XS GIS Cut Line= 3
      1553140.44      6830718.64      1553337.98      6830731.58
      1554081.76      6830642.14
#Sta/Elev= 30
  4785.5 1786.34  4960.4  1785.3  4964.8 1770.71  4965.8 1770.21  5016.3 1770.71
  5020.7 1776.39  5030.8 1775.58    5061  1776.7  5091.3 1776.01  5111.4 1777.46
  5142.9 1776.89  5161.8  1778.4  5171.8 1776.25    5192 1780.27  5242.3 1780.25
  5282.6 1782.17  5302.2  1784.3  5307.2 1782.48  5322.9 1783.14  5353.1 1790.46
  5363.2 1790.11  5383.3 1790.78  5389.4 1791.92  5433.7 1792.97  5453.8 1792.47
  5494.1 1793.49  5524.3 1795.09  5544.5 1794.11  5598.6 1795.29  5732.6 1795.24
#Mann= 4 ,-1 , 0
  4785.5     .07       0  4964.8     .07       0  5016.3     .07       0
  5598.6    .045       0
Bank Sta=4964.8,5016.3
XS Rating Curve= 0 ,0
Exp/Cntr=0.3,0.1

Type RM Length L Ch R = 1 ,41886   ,432,432,432
BEGIN DESCRIPTION:
Little Elm Creek 41885.92
END DESCRIPTION:
XS GIS Cut Line= 3
      1553141.93      6831105.74      1553247.71      6831127.41
      1554144.72      6831067.28
#Sta/Elev= 30
  4885.2  1785.3  4939.4 1785.06  4959.8 1786.21  4973.1 1784.86  4974.7 1769.52
  4975.7 1769.02  5025.2 1769.02  5026.2 1769.52  5030.6 1773.17  5040.6 1774.95
  5062.4  1775.9  5080.7 1779.05  5090.7 1779.82  5110.7 1778.78  5170.9 1779.54
  5180.9 1781.52  5190.9 1786.59  5200.9 1787.08  5207.3 1785.74  5212.3  1786.4
    5221 1784.53    5241 1784.16  5261.1 1785.51  5271.1 1785.05  5486.3 1785.82
  5561.7  1786.6  5611.9 1788.43  5712.1 1789.67    5807  1792.3  5892.2 1792.46
#Mann= 4 ,-1 , 0
  4885.2     .07       0  4974.7     .07       0  5026.2     .07       0
  5486.3    .045       0
Bank Sta=4974.7,5026.2
XS Rating Curve= 0 ,0
Exp/Cntr=0.3,0.1

Type RM Length L Ch R = 1 ,41454   ,695,695,695
BEGIN DESCRIPTION:
Little Elm Creek 41453.75
END DESCRIPTION:
XS GIS Cut Line= 3
      1553009.35      6831383.78      1553403.86      6831462.68
      1554187.59      6831325.92
#Sta/Elev= 30
  4595.2 1784.55  4662.2 1785.19  4723.3  1784.1  4741.4 1784.84  4774.3 1784.96
  4894.4 1780.58  4937.5 1780.02  4957.9 1780.55  4968.1  1780.3  4978.3 1777.47
  4983.1 1771.47  4984.1 1770.97  5033.6 1770.97  5034.6 1771.47  5039.3 1772.09
  5054.2 1771.51  5069.7 1774.53  5079.9 1775.17  5085.7 1777.54    5090 1779.29
  5100.2 1781.89  5130.6 1781.95  5232.8 1784.39    5354 1784.26  5485.9 1785.27
  5536.7 1786.24  5579.9 1787.71  5617.9 1787.44  5693.9 1788.28  5793.1 1790.72
#Mann= 4 ,-1 , 0
  4595.2     .07       0  4983.1     .07       0  5034.6     .07       0
  5085.7    .045       0
Bank Sta=4983.1,5034.6
XS Rating Curve= 0 ,0
Exp/Cntr=0.3,0.1

Type RM Length L Ch R = 1 ,40759   ,0,0,0
BEGIN DESCRIPTION:
Little Elm Creek 40758.895
END DESCRIPTION:
XS GIS Cut Line= 3
      1553298.72      6832207.22      1553692.15      6832051.02
       1554376.5      6831647.22
#Sta/Elev= 30
  4594.9 1783.45    4763  1783.2  4822.7 1784.46  4906.4  1783.1  4918.6 1781.88
  4936.1 1777.78  4967.5 1772.47  4978.2 1771.66  4990.1 1769.22  4999.7 1769.95
  5003.6 1769.06  5004.7 1768.46  5057.8 1769.06  5057.9 1770.19  5073.6 1772.46
  5116.5  1781.8    5255 1782.93  5307.7 1784.26  5313.5 1783.66  5329.2 1784.42
  5350.6 1787.87  5366.3 1786.98  5372.1 1785.63  5387.7 1787.12  5424.8 1787.77
  5483.4 1787.02  5584.8 1788.44  5590.6 1787.73  5628.5 1789.28  5812.8 1790.11
#Mann= 5 ,-1 , 0
  4594.9    .035       0  4918.6     .07       0  5003.6     .07       0
  5057.8     .07       0  5628.5    .045       0
Bank Sta=5003.6,5057.8
XS Rating Curve= 0 ,0
Exp/Cntr=0.3,0.1

Chan Stop Cuts=-1
Use User Specified Reach Order=0
Composite Channel Slope=5