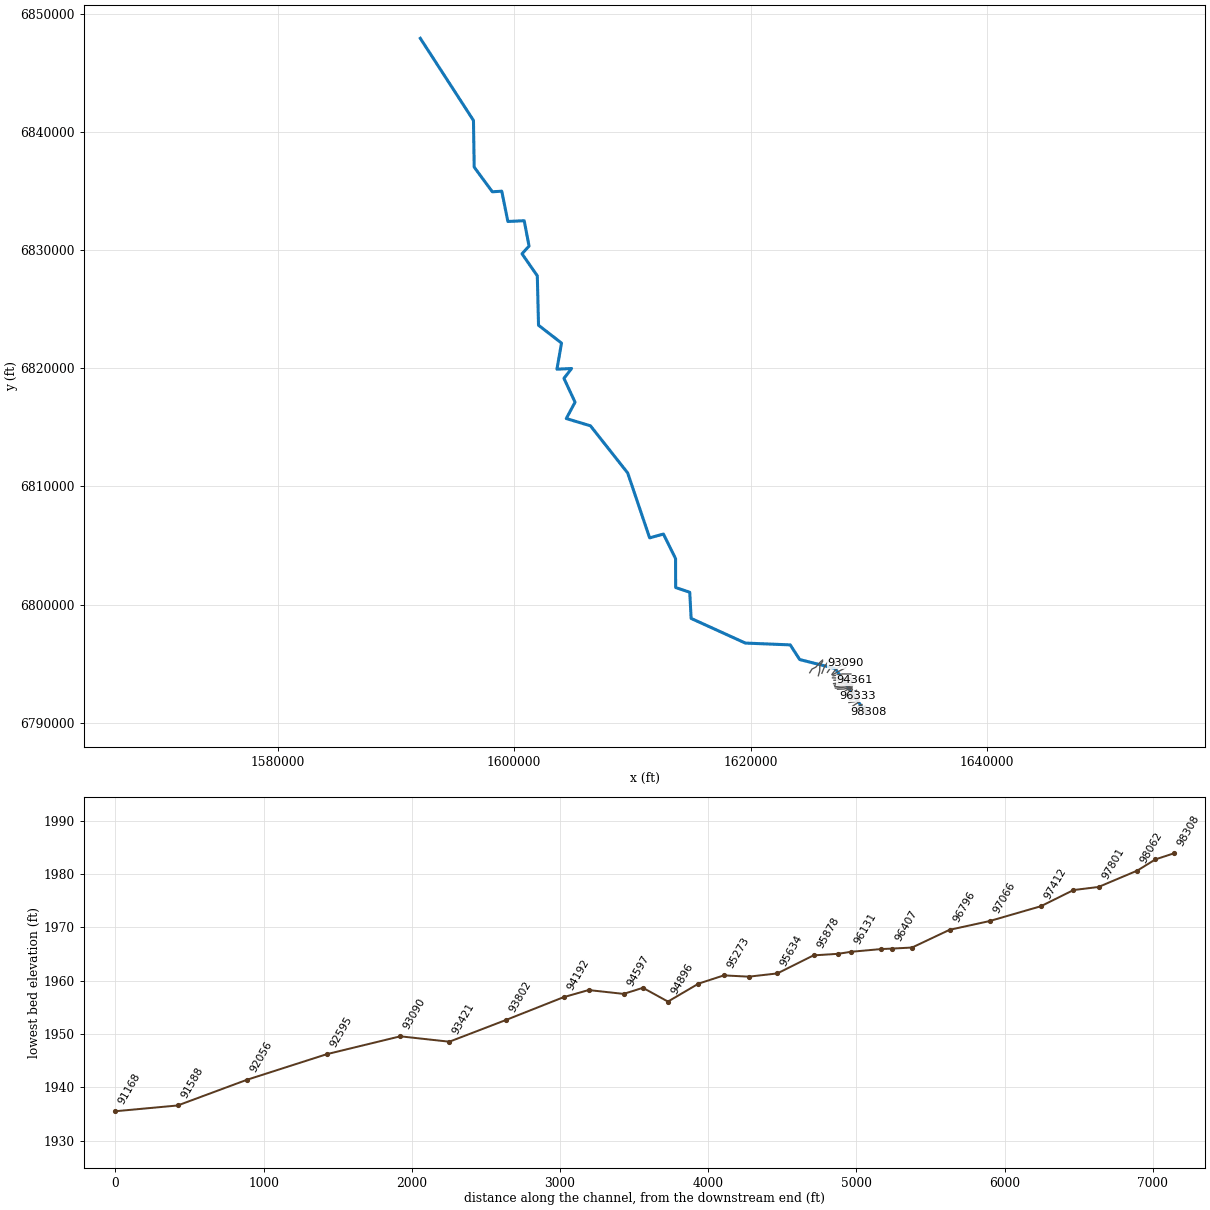
--- Lytle Creek.prj (project) ---

Proj Title=Lytle Creek Base Level Engineering
Current Plan=p01
Default Exp/Contr=0.3,0.1
English Units
Geom File=g01
Flow File=f01
Plan File=p01
Y Axis Title=Elevation
X Axis Title(PF)=Main Channel Distance
X Axis Title(XS)=Station
BEGIN DESCRIPTION:
Lytle Creek
END DESCRIPTION:
DSS Export Rating Curves= 0
DSS Export Rating Curve Sorted= 0
DSS Export Volume Flow Curves= 0
DXF OffsetX= 0
DXF OffsetY= 0
DXF ScaleX= 1
DXF ScaleY= 10

--- Lytle Creek.p01 (plan) ---

Plan Title=Multiple Run
Short Identifier=Multiple
Geom File=g01
Flow File=f01
Subcritical Flow
K Sum by GR= 0
Std Step Tol= 0.01
Critical Tol= 0.01
Num of Std Step Trials= 20
Max Error Tol= 0.3
Flow Tol Ratio= 0.001
Split Flow NTrial= 30
Split Flow Tol= 0.02
Split Flow Ratio= 0.02
Log Output Level= 0
Friction Slope Method= 1
Unsteady Friction Slope Method= 2
Unsteady Bridges Friction Slope Method= 1
Parabolic Critical Depth
Global Vel Dist=  1 , 1 , 1
Global Log Level= 0
CheckData=True
Encroach Param= -1, 0, 0, 0
BEGIN DESCRIPTION:
Multiple Run
END DESCRIPTION:

--- Lytle Creek.f01 (steady flow) ---

Flow Title=Multiple
Program Version=4.10
Number of Profiles= 7
Profile Names=10-year,25-year,50-year,1pct_min,100-year,1pct_plu,500-year
River Rch & RM=Lytle Creek,Reach-1         ,98308
     293     415     518     402     644     887    1010
River Rch & RM=Lytle Creek,Reach-1         ,98062
     386     554     698     545     874    1200    1390
River Rch & RM=Lytle Creek,Reach-1         ,95273
     584     845    1070     839    1350    1850    2150
River Rch & RM=Lytle Creek,Reach-1         ,94896
     584     845    1070     839    1350    1850    2150
River Rch & RM=Lytle Creek,Reach-1         ,81638
     934    1390    1790    1420    2280    3130    3760
River Rch & RM=Lytle Creek,Reach-1         ,77441
     966    1430    1840    1460    2340    3220    3840
River Rch & RM=Lytle Creek,Reach-1         ,70752
    1020    1510    1940    1540    2460    3390    4040
River Rch & RM=Lytle Creek,Reach-1         ,67151
    1250    1870    2420    1930    3100    4260    5130
River Rch & RM=Lytle Creek,Reach-1         ,66394
    1250    1870    2420    1930    3100    4260    5130
River Rch & RM=Lytle Creek,Reach-1         ,63521
    1360    2030    2630    2100    3370    4630    5590
River Rch & RM=Lytle Creek,Reach-1         ,60584
    1500    2250    2920    2330    3740    5150    6230
River Rch & RM=Lytle Creek,Reach-1         ,59570
    2080    3140    4080    3270    5240    7210    8770
River Rch & RM=Lytle Creek,Reach-1         ,57862
    2080    3140    4080    3270    5240    7210    8770
River Rch & RM=Lytle Creek,Reach-1         ,54626
    2530    3840    5010    4030    6450    8880   10900
River Rch & RM=Lytle Creek,Reach-1         ,51501
    2530    3840    5010    4030    6450    8880   10900
River Rch & RM=Lytle Creek,Reach-1         ,51006
    2530    3840    5010    4030    6450    8880   10900
River Rch & RM=Lytle Creek,Reach-1         ,48582
    2610    3950    5160    4140    6640    9140   11200
River Rch & RM=Lytle Creek,Reach-1         ,48112
    2610    3950    5160    4140    6640    9140   11200
River Rch & RM=Lytle Creek,Reach-1         ,43609
    2610    3930    5120    4110    6580    9050   11000
River Rch & RM=Lytle Creek,Reach-1         ,33980
    2610    3930    5120    4110    6580    9050   11000
River Rch & RM=Lytle Creek,Reach-1         ,32322
    2740    4130    5370    4300    6900    9490   11500
River Rch & RM=Lytle Creek,Reach-1         ,31426
    2740    4130    5370    4300    6900    9490   11500
River Rch & RM=Lytle Creek,Reach-1         ,27876
    2980    4490    5840    4680    7500   10300   12500
River Rch & RM=Lytle Creek,Reach-1         ,23761
    2980    4490    5840    4680    7500   10300   12500
River Rch & RM=Lytle Creek,Reach-1         ,20069
    2980    4490    5840    4680    7500   10300   12500
River Rch & RM=Lytle Creek,Reach-1         ,17031
    2960    4460    5800    4640    7430   10200   12400
River Rch & RM=Lytle Creek,Reach-1         ,9717
    3000    4510    5860    4690    7510   10300   12500
River Rch & RM=Lytle Creek,Reach-1         ,8974
    3000    4510    5850    4680    7500   10300   12500
River Rch & RM=Lytle Creek,Reach-1         ,7067
    2940    4410    5710    4550    7300   10000   12100
Boundary for River Rch & Prof#=Lytle Creek,Reach-1         , 1
Up Type= 0
Dn Type= 3
Dn Slope=0.001
Boundary for River Rch & Prof#=Lytle Creek,Reach-1         , 2
Up Type= 0
Dn Type= 3
Dn Slope=0.001
Boundary for River Rch & Prof#=Lytle Creek,Reach-1         , 3
Up Type= 0
Dn Type= 3
Dn Slope=0.001
Boundary for River Rch & Prof#=Lytle Creek,Reach-1         , 4
Up Type= 0
Dn Type= 3
Dn Slope=0.001
Boundary for River Rch & Prof#=Lytle Creek,Reach-1         , 5
Up Type= 0
Dn Type= 3
Dn Slope=0.001
Boundary for River Rch & Prof#=Lytle Creek,Reach-1         , 6
Up Type= 0
Dn Type= 3
Dn Slope=0.001
Boundary for River Rch & Prof#=Lytle Creek,Reach-1         , 7
Up Type= 0
Dn Type= 3
Dn Slope=0.001
DSS Import GetInterval= 0
DSS Import GetPeak= 0
DSS Import FillOption= 0

--- Lytle Creek.g01 (geometry) ---

Geom Title=Existing Conditions
Program Version=4.10

River Reach=Lytle Creek     ,Reach-1
Reach XY= 30
        1629755.        6790838.      1627153.53      6794584.45
      1624152.71      6795343.06      1623353.45      6796584.25
        1619555.        6796738.      1614968.37      6798824.77
      1614849.15      6801040.29      1613658.03      6801439.39
      1613649.54      6803890.45      1612625.16      6805968.42
      1611457.17      6805643.44      1609599.48      6811140.43
      1606449.39      6815132.41      1604406.27      6815747.48
      1605146.98      6817134.64      1604206.04      6819148.44
      1604853.03      6819982.36      1603615.28      6819927.84
      1604001.46      6822136.54      1602056.05      6823648.43
      1601953.05      6827832.11      1600656.04      6829698.43
      1601254.41      6830348.62      1600843.92      6832498.05
      1599462.48      6832431.94      1598944.25      6834997.71
      1598148.41      6834945.74      1596613.14      6837031.94
      1596551.39       6840986.5        1592055.        6847938.

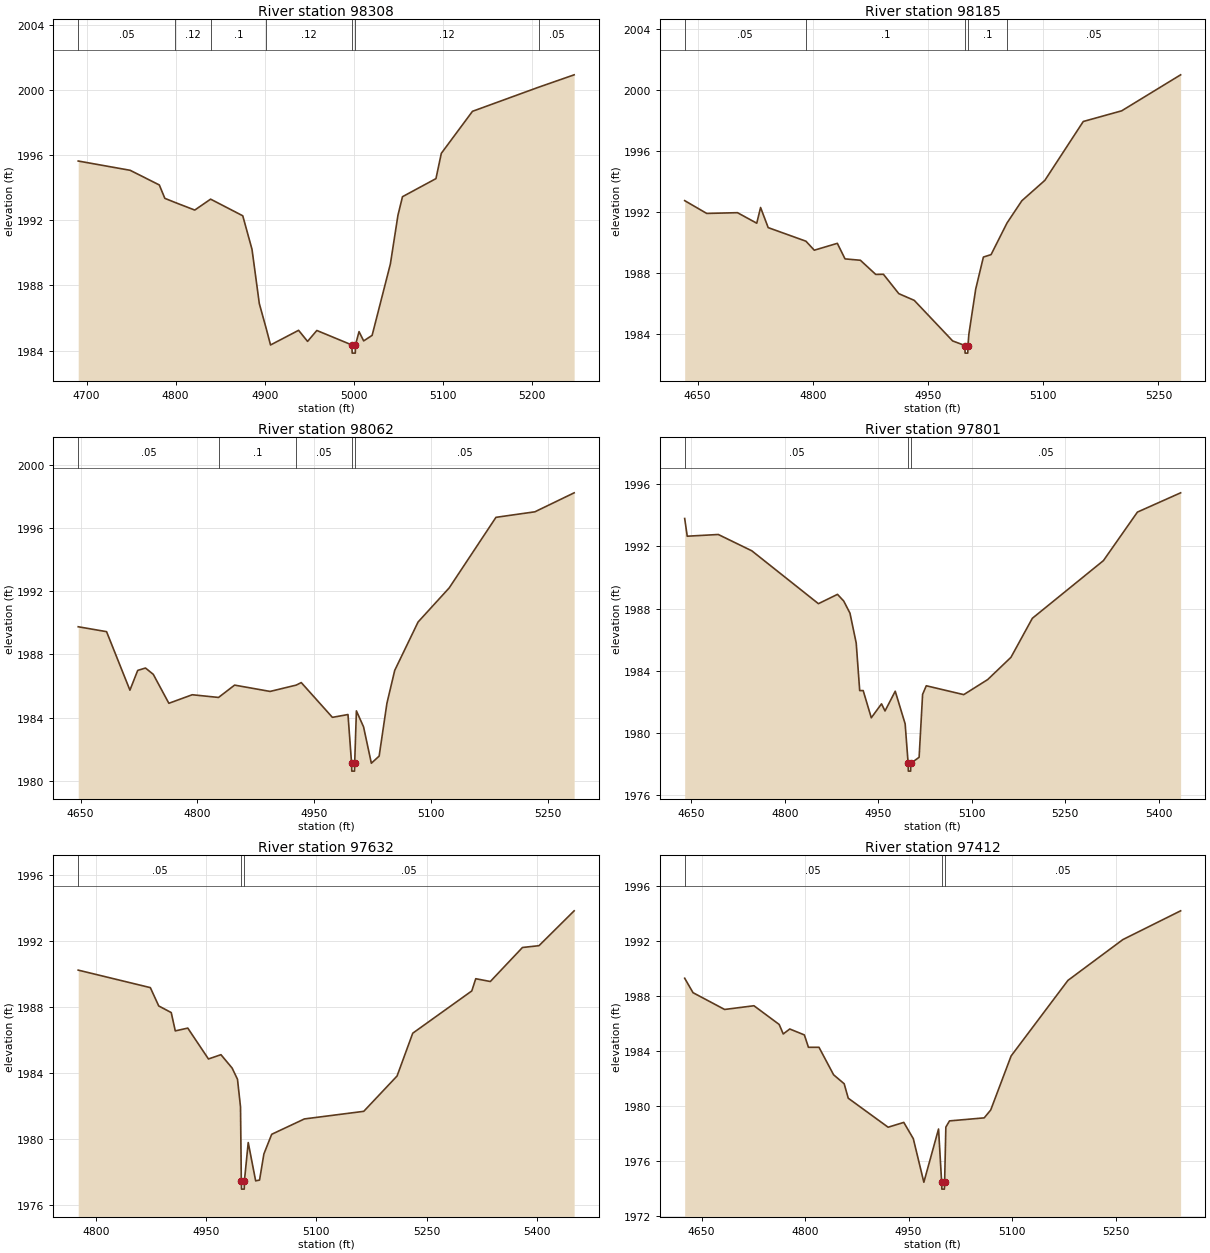
Type RM Length L Ch R = 1 ,98308   ,123,123,123
BEGIN DESCRIPTION:
Lytle Creek 98308.404
END DESCRIPTION:
XS GIS Cut Line= 3
      1629457.47      6790785.77      1629754.74      6790871.55
      1629996.49      6790925.08
#Sta/Elev= 30
  4690.6 1995.63    4749 1995.06  4781.7 1994.16  4787.9 1993.34  4799.7 1993.08
  4821.5 1992.62  4839.3 1993.29  4875.4 1992.27  4885.8 1990.21    4894 1986.88
  4901.9 1985.32  4906.6 1984.34  4938.1 1985.24  4948.2 1984.56  4958.6 1985.23
    4998 1984.34  4998.3 1983.84  5001.8 1983.84    5002 1984.34    5006 1985.16
  5011.2 1984.59  5020.7 1984.93  5041.2 1989.31  5049.7  1992.3  5054.8 1993.44
  5092.4 1994.55  5098.4  1996.1  5133.4 1998.68  5207.7 2000.16  5247.6 2000.92
#Mann= 7 ,-1 , 0
  4690.6     .05       0  4799.7     .12       0  4839.3      .1       0
  4901.9     .12       0    4998     .07       0    5002     .12       0
  5207.7     .05       0
Bank Sta=4998,5002
XS Rating Curve= 0 ,0
Exp/Cntr=0.3,0.1

Type RM Length L Ch R = 1 ,98185   ,123,123,123
BEGIN DESCRIPTION:
Lytle Creek 98184.62
END DESCRIPTION:
XS GIS Cut Line= 3
      1629336.34      6790970.66      1629702.23      6790979.78
      1629981.73      6790979.78
#Sta/Elev= 30
  4633.3 1992.72    4662 1991.88    4702 1991.93  4727.1 1991.24  4732.1 1992.27
    4742 1990.95  4791.1 1990.06    4802 1989.47    4832 1989.92    4842  1988.9
    4862 1988.81    4882 1987.88    4892 1987.89    4912 1986.62  4932.1 1986.18
  4982.1 1983.52    4998 1983.22  4998.3 1982.72  5001.8 1982.72    5002 1983.22
  5003.2 1983.96  5012.1 1986.92  5022.1 1989.02  5032.1 1989.18  5052.8 1991.25
  5072.1 1992.71  5102.1 1994.05  5152.1 1997.91  5202.1 1998.61  5278.8 2000.97
#Mann= 5 ,-1 , 0
  4633.3     .05       0  4791.1      .1       0    4998     .07       0
    5002      .1       0  5052.8     .05       0
Bank Sta=4998,5002
XS Rating Curve= 0 ,0
Exp/Cntr=0.3,0.1

Type RM Length L Ch R = 1 ,98062   ,261,261,261
BEGIN DESCRIPTION:
Lytle Creek 98062.36
END DESCRIPTION:
XS GIS Cut Line= 3
      1629268.65      6791077.43       1629621.5      6791069.62
      1629905.36      6791069.62
#Sta/Elev= 30
    4647 1989.74  4683.4 1989.43  4713.4 1985.73  4723.4 1986.98  4733.4 1987.13
  4743.4 1986.73  4763.4  1984.9  4793.4 1985.44  4827.2 1985.27  4847.8 1986.05
  4893.4 1985.65  4926.9 1986.05  4933.4 1986.21  4973.4 1984.01  4993.4 1984.19
    4998 1981.11  4998.3 1980.61  5001.8 1980.61    5002 1981.11  5004.2 1984.42
  5013.4 1983.41  5023.4 1981.11  5033.4 1981.56  5043.4  1984.9  5053.4 1986.98
  5083.4 1990.04  5123.4  1992.2  5183.4 1996.66  5233.4 1997.01  5283.8 1998.21
#Mann= 5 ,-1 , 0
    4647     .05       0  4827.2      .1       0  4926.9     .05       0
    4998     .05       0    5002     .05       0
Bank Sta=4998,5002
XS Rating Curve= 0 ,0
Exp/Cntr=0.3,0.1

Type RM Length L Ch R = 1 ,97801   ,169,169,169
BEGIN DESCRIPTION:
Mapping XS cb8f6ab7
END DESCRIPTION:
XS GIS Cut Line= 5
      1629054.17      6791042.31       1629262.5      6791120.44
      1629321.09       6791116.1        1629575.      6791250.64
      1629791.01      6791319.77
#Sta/Elev= 30
  4639.5  1993.8  4643.6 1992.66  4693.4 1992.77  4747.2 1991.72    4854 1988.32
  4884.6 1988.92  4894.6 1988.49  4904.6 1987.71  4914.6 1985.79  4920.2 1982.73
  4925.8 1982.73  4938.8 1980.98  4955.2 1981.88  4960.8 1981.42  4977.2 1982.69
  4993.1 1980.59  4997.9 1978.05  4998.2 1977.55  5001.9 1977.55  5002.1 1978.05
  5015.5 1978.44  5021.1 1982.49    5027 1983.04  5087.1 1982.47  5125.5 1983.44
  5162.8 1984.87  5197.1 1987.38  5311.1 1991.09  5365.6 1994.21  5434.9 1995.45
#Mann= 3 ,-1 , 0
  4639.5     .05       0  4997.9     .05       0  5002.1     .05       0
Bank Sta=4997.9,5002.1
XS Rating Curve= 0 ,0
Exp/Cntr=0.3,0.1

Type RM Length L Ch R = 1 ,97632   ,220,220,220
BEGIN DESCRIPTION:
Lytle Creek 97631.83
END DESCRIPTION:
XS GIS Cut Line= 3
      1629036.85      6791107.37      1629237.39      6791205.04
      1629660.95      6791360.95
#Sta/Elev= 30
  4776.1 1990.23  4874.2 1989.17  4885.6 1988.06  4902.6 1987.66  4908.1 1986.55
  4925.1 1986.72  4953.2 1984.85  4970.2 1985.11  4985.4  1984.3  4992.7 1983.62
  4996.8 1981.95  4997.9 1977.47  4998.2 1976.97  5001.9 1976.97  5002.1 1977.47
  5007.3 1979.79  5017.4 1977.47  5022.7 1977.52  5028.6  1979.1  5039.2 1980.29
  5083.7 1981.22  5164.4 1981.68  5209.7 1983.82    5231 1986.41  5311.3 1988.97
  5316.7 1989.71  5336.5 1989.54  5380.2  1991.6  5402.7 1991.71  5450.5 1993.82
#Mann= 3 ,-1 , 0
  4776.1     .05       0  4997.9     .05       0  5002.1     .05       0
Bank Sta=4997.9,5002.1
XS Rating Curve= 0 ,0
Exp/Cntr=0.3,0.1

Type RM Length L Ch R = 1 ,97412   ,346,346,346
BEGIN DESCRIPTION:
Lytle Creek 97411.86
END DESCRIPTION:
XS GIS Cut Line= 3
      1628795.95      6791178.98      1629113.69      6791378.21
      1629420.99      6791532.51
#Sta/Elev= 30
  4625.4 1989.27  4637.5 1988.22  4683.3    1987  4725.8 1987.27  4762.4 1985.91
  4768.3 1985.22  4777.7 1985.58  4798.9 1985.15  4804.8 1984.25  4820.1 1984.25
  4841.3 1982.25  4856.6  1981.6  4862.5 1980.55  4920.3 1978.44    4943 1978.79
  4956.8 1977.61  4972.1 1974.44  4993.4 1978.31  4997.9 1974.44  4998.2 1973.94
  5001.9 1973.94  5002.2 1974.44    5004 1978.45  5009.3  1978.9  5059.6 1979.12
    5069 1979.69  5098.6 1983.62  5180.9 1989.11  5260.6 1992.08  5344.3 1994.17
#Mann= 3 ,-1 , 0
  4625.4     .05       0  4997.9     .05       0  5002.2     .05       0
Bank Sta=4997.9,5002.2
XS Rating Curve= 0 ,0
Exp/Cntr=0.3,0.1

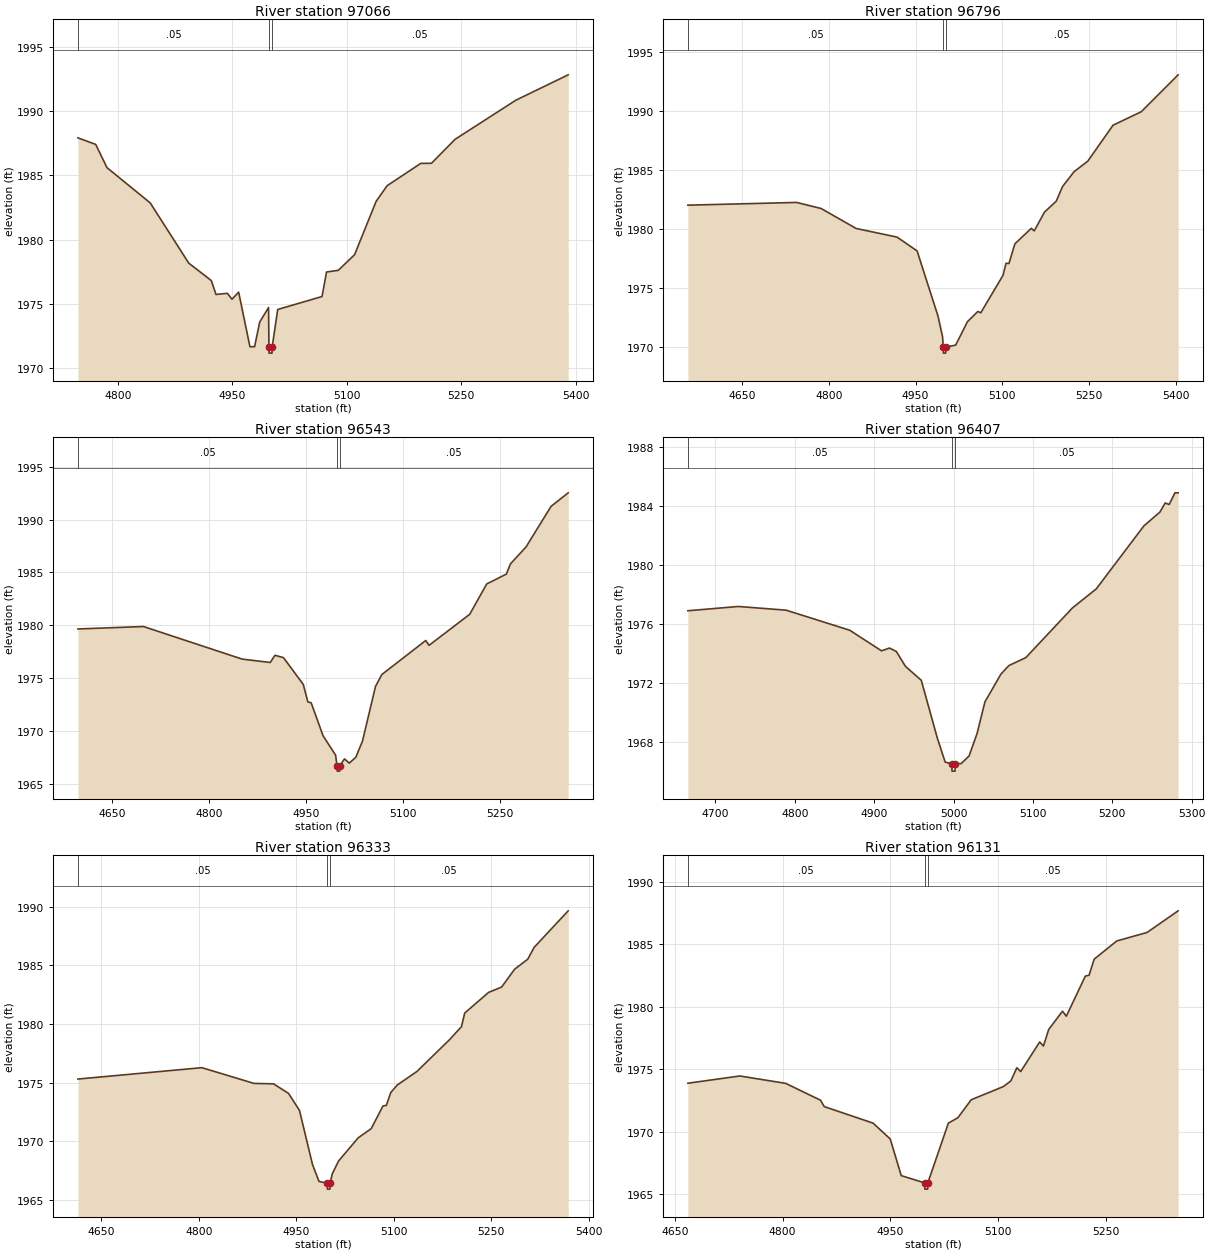
Type RM Length L Ch R = 1 ,97066   ,270,270,270
BEGIN DESCRIPTION:
Lytle Creek 97066.38
END DESCRIPTION:
XS GIS Cut Line= 3
      1628640.01      6791400.23      1628845.72      6791544.75
      1629180.22      6791747.79
#Sta/Elev= 30
  4747.5 1987.93  4770.8 1987.42  4785.6 1985.61  4842.3 1982.86  4892.8 1978.17
  4922.4 1976.81  4928.5 1975.73  4943.4 1975.82  4949.5 1975.36  4958.2 1975.91
    4973 1971.66  4979.1 1971.66  4985.8 1973.58  4997.4 1974.71  4997.9 1971.66
  4998.1 1971.16  5001.9 1971.16  5002.2 1971.66  5009.4 1974.56  5067.5 1975.57
  5073.4 1977.48  5088.8 1977.61  5110.2 1978.83  5138.4 1982.98  5152.8  1984.2
  5196.9 1985.94    5211 1985.95    5242 1987.82  5321.5 1990.86  5390.2 1992.84
#Mann= 3 ,-1 , 0
  4747.5     .05       0  4997.9     .05       0  5002.2     .05       0
Bank Sta=4997.9,5002.2
XS Rating Curve= 0 ,0
Exp/Cntr=0.3,0.1

Type RM Length L Ch R = 1 ,96796   ,253,253,253
BEGIN DESCRIPTION:
Lytle Creek 96796.09
END DESCRIPTION:
XS GIS Cut Line= 3
      1628317.11      6791704.91      1628755.88      6791770.01
      1629150.83      6791857.06
#Sta/Elev= 30
  4556.1 1982.03  4744.2 1982.26  4786.5 1981.75  4847.1 1980.06  4917.9 1979.33
  4952.6 1978.16  4988.7 1972.66  4996.7 1970.89  4997.8 1970.02  4998.1 1969.52
  5001.9 1969.52  5002.2 1970.02  5019.3  1970.2  5039.7 1972.18  5057.6 1973.04
  5062.7 1972.93  5101.2  1976.1  5106.4 1977.12  5111.5  1977.1  5121.7 1978.76
  5150.1 1980.07  5155.2 1979.86  5172.9 1981.44  5193.3 1982.37  5204.1  1983.6
  5224.1 1984.86  5247.8 1985.75  5291.5 1988.79  5340.3 1989.93  5404.1 1993.05
#Mann= 3 ,-1 , 0
  4556.1     .05       0  4997.8     .05       0  5002.2     .05       0
Bank Sta=4997.8,5002.2
XS Rating Curve= 0 ,0
Exp/Cntr=0.3,0.1

Type RM Length L Ch R = 1 ,96543   ,136,136,136
BEGIN DESCRIPTION:
Lytle Creek 96542.94
END DESCRIPTION:
XS GIS Cut Line= 3
       1628363.3      6791912.45      1628757.88      6791991.89
      1629109.46      6792046.58
#Sta/Elev= 30
    4597 1979.65  4698.4 1979.88  4850.9  1976.8  4894.5 1976.48  4901.7 1977.16
  4914.9 1976.94  4945.6  1974.4  4952.6 1972.75  4957.7 1972.67  4976.2 1969.54
  4995.5 1967.72  4997.8  1966.7  4998.1  1966.2  5001.9  1966.2  5002.2  1966.7
  5009.2 1967.36  5016.8 1966.96  5026.9 1967.52  5037.1 1969.04  5057.3 1974.22
  5067.1 1975.34    5135 1978.56  5140.1  1978.1    5203 1981.04  5229.3 1983.91
  5259.7 1984.84  5265.9  1985.8  5290.1 1987.41  5328.8 1991.25  5355.3 1992.53
#Mann= 3 ,-1 , 0
    4597     .05       0  4997.8     .05       0  5002.2     .05       0
Bank Sta=4997.8,5002.2
XS Rating Curve= 0 ,0
Exp/Cntr=0.3,0.1

Type RM Length L Ch R = 1 ,96407   ,74,74,74
BEGIN DESCRIPTION:
Lytle Creek 96407
END DESCRIPTION:
XS GIS Cut Line= 3
      1628391.69      6792093.01      1628725.93      6792118.19
      1629008.01      6792133.81
#Sta/Elev= 30
  4665.3 1976.88  4728.8 1977.17    4789 1976.92  4869.2 1975.56  4909.3 1974.16
  4919.3 1974.35  4927.9 1974.12  4939.4 1973.11  4959.4 1972.16  4979.5 1968.26
  4989.5 1966.61  4997.8  1966.5  4998.1    1966  5001.9    1966  5002.2  1966.5
  5009.6 1966.51  5019.6 1967.03  5029.6 1968.54  5039.6  1970.7  5059.7 1972.58
  5069.7 1973.16  5091.1  1973.7  5149.8 1977.07  5179.8 1978.36  5239.9 1982.64
    5260 1983.57  5266.7 1984.19  5271.7 1984.09    5279 1984.88    5283 1984.88
#Mann= 3 ,-1 , 0
  4665.3     .05       0  4997.8     .05       0  5002.2     .05       0
Bank Sta=4997.8,5002.2
XS Rating Curve= 0 ,0
Exp/Cntr=0.3,0.1

Type RM Length L Ch R = 1 ,96333   ,202,202,202
BEGIN DESCRIPTION:
Lytle Creek 96332.97
END DESCRIPTION:
XS GIS Cut Line= 3
      1628314.45      6792168.53      1628700.76       6792185.9
       1629067.1      6792216.28
#Sta/Elev= 30
  4614.2  1975.3  4804.9 1976.27    4885 1974.93  4915.1 1974.89  4938.2 1974.08
  4955.1 1972.62  4975.1 1968.01  4985.1 1966.57  4997.8 1966.41  4998.1 1965.91
  5001.9 1965.91  5002.2 1966.41  5005.5 1967.21  5015.2 1968.31  5045.3 1970.28
  5065.4 1971.07  5083.6 1973.01  5088.7 1973.05  5095.5 1974.15  5105.5 1974.79
  5135.6 1975.94  5185.8 1978.65  5204.3 1979.77  5209.3 1980.93    5246 1982.69
  5266.1 1983.15  5286.1 1984.67  5306.2 1985.52  5316.2 1986.54  5368.5 1989.65
#Mann= 3 ,-1 , 0
  4614.2     .05       0  4997.8     .05       0  5002.2     .05       0
Bank Sta=4997.8,5002.2
XS Rating Curve= 0 ,0
Exp/Cntr=0.3,0.1

Type RM Length L Ch R = 1 ,96131   ,88,88,88
BEGIN DESCRIPTION:
Lytle Creek 96131.29
END DESCRIPTION:
XS GIS Cut Line= 3
        1628334.      6792282.33      1628653.45      6792372.61
      1628986.06      6792482.33
#Sta/Elev= 30
  4668.3 1973.87  4740.6 1974.45  4804.4 1973.86  4852.9 1972.51  4858.1    1972
    4926 1970.68  4949.9 1969.41  4965.2 1966.48  4997.8  1965.9  4998.1  1965.4
  5001.9  1965.4  5002.2  1965.9  5030.8 1970.68    5044 1971.11  5062.6 1972.55
  5107.2  1973.6  5117.7 1974.05  5126.1 1975.11  5131.4  1974.8  5157.8 1977.17
  5163.1 1976.85  5170.4 1978.17  5189.6 1979.63  5194.9 1979.23  5221.4 1982.44
  5226.6 1982.51  5233.6 1983.79  5265.1 1985.25  5307.3 1985.93  5350.5 1987.66
#Mann= 3 ,-1 , 0
  4668.3     .05       0  4997.8     .07       0  5002.2     .05       0
Bank Sta=4997.8,5002.2
XS Rating Curve= 0 ,0
Exp/Cntr=0.3,0.1

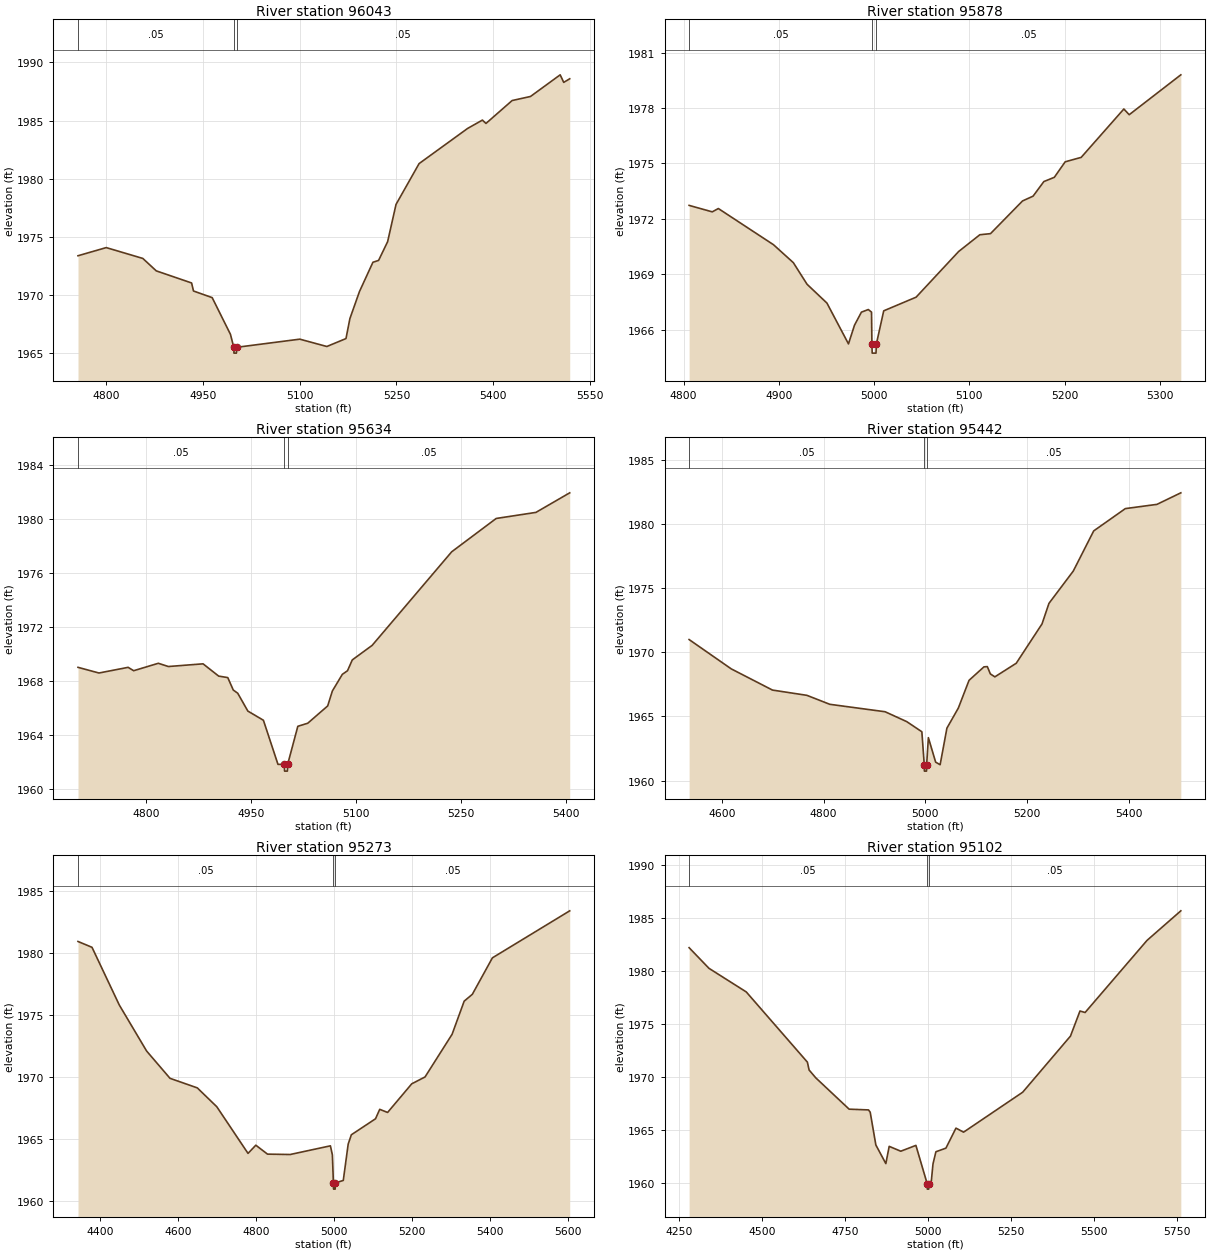
Type RM Length L Ch R = 1 ,96043   ,165,165,165
BEGIN DESCRIPTION:
Mapping XS f53f254b
END DESCRIPTION:
XS GIS Cut Line= 5
      1628358.83      6792320.08      1628525.52      6792370.44
      1628650.52      6792465.92      1628782.46      6792655.16
      1628964.79      6792738.51
#Sta/Elev= 30
  4756.2 1973.39    4800 1974.09  4856.7 1973.16  4877.6 1972.09  4932.4 1971.05
  4935.3 1970.36  4964.3 1969.79  4992.6 1966.64  4997.8 1965.52  4998.1 1965.02
  5001.9 1965.02  5002.2 1965.52  5100.2 1966.22  5142.1 1965.59  5171.8 1966.27
  5177.9 1967.99  5192.7 1970.31  5213.6 1972.83  5222.4 1972.99  5236.4  1974.6
  5249.4  1977.8  5285.2 1981.31  5360.4 1984.33  5383.4 1985.05  5388.9 1984.76
  5429.5 1986.73    5458 1987.08    5504 1988.94  5509.5 1988.29  5518.8  1988.6
#Mann= 3 ,-1 , 0
  4756.2     .05       0  4997.8     .05       0  5002.2     .05       0
Bank Sta=4997.8,5002.2
XS Rating Curve= 0 ,0
Exp/Cntr=0.3,0.1

Type RM Length L Ch R = 1 ,95878   ,244,244,244
BEGIN DESCRIPTION:
Lytle Creek 95878
END DESCRIPTION:
XS GIS Cut Line= 3
       1628343.8      6792375.39      1628463.13      6792528.34
      1628606.35      6792816.96
#Sta/Elev= 30
  4805.8 1972.73  4830.1 1972.38  4836.5 1972.56  4894.4  1970.6  4915.2 1969.63
  4929.6 1968.46  4950.5 1967.44  4973.1 1965.23  4979.4 1966.24  4986.7 1966.95
  4993.9 1967.09  4997.3 1966.95  4997.7 1965.23    4998 1964.73    5002 1964.73
  5002.4 1965.23  5010.1 1967.02  5044.1 1967.76  5088.7 1970.23    5111 1971.14
  5122.2  1971.2  5155.8 1972.97  5166.9 1973.23  5178.2 1974.02  5189.2 1974.25
  5200.6 1975.09  5217.4 1975.33  5262.2 1977.95  5267.8 1977.64    5322  1979.8
#Mann= 3 ,-1 , 0
  4805.8     .05       0  4997.7     .05       0  5002.4     .05       0
Bank Sta=4997.7,5002.4
XS Rating Curve= 0 ,0
Exp/Cntr=0.3,0.1

Type RM Length L Ch R = 1 ,95634   ,192,192,192
BEGIN DESCRIPTION:
Lytle Creek 95633.92
END DESCRIPTION:
XS GIS Cut Line= 3
      1628068.69      6792412.78      1628257.47      6792642.78
      1628554.79      6792916.23
#Sta/Elev= 30
  4703.3 1969.04  4733.2 1968.62  4774.8 1969.04  4782.7 1968.79  4817.9 1969.34
  4832.2  1969.1  4881.7  1969.3    4904 1968.39    4917 1968.28  4924.8 1967.36
  4931.2 1967.12  4945.6  1965.8  4967.8 1965.12  4988.6 1961.85  4997.7 1961.85
    4998 1961.35    5002 1961.35  5002.4 1961.85  5016.9 1964.67  5031.1  1964.9
  5059.5 1966.18  5066.2 1967.29  5080.4 1968.52  5087.8 1968.79  5094.6 1969.59
    5123 1970.67  5236.4  1977.6  5299.9 1980.07  5356.6 1980.52  5404.8 1981.97
#Mann= 3 ,-1 , 0
  4703.3     .05       0  4997.7     .05       0  5002.4     .05       0
Bank Sta=4997.7,5002.4
XS Rating Curve= 0 ,0
Exp/Cntr=0.3,0.1

Type RM Length L Ch R = 1 ,95442   ,169,169,169
BEGIN DESCRIPTION:
Mapping XS 38325b7c
END DESCRIPTION:
XS GIS Cut Line= 4
      1627831.74       6792376.4      1628000.13      6792674.98
      1628300.48      6792881.58      1628550.25      6792949.22
#Sta/Elev= 30
  4535.7    1971  4618.6 1968.71  4699.5 1967.06  4767.1 1966.65  4812.2 1965.95
  4920.8 1965.37  4963.3  1964.6    4993 1963.81  4997.7 1961.24    4998 1960.74
  5002.1 1960.74  5002.4 1961.24  5005.8 1963.35  5020.1 1961.44  5028.9 1961.24
  5042.2 1964.09  5064.7 1965.66  5085.7 1967.82    5115 1968.87  5121.6 1968.89
  5127.6 1968.32  5136.4 1968.09  5178.4 1969.15  5229.1 1972.22  5242.7 1973.82
  5290.5 1976.34  5330.6 1979.47  5392.8 1981.21  5454.9 1981.54  5501.8 1982.44
#Mann= 3 ,-1 , 0
  4535.7     .05       0  4997.7     .03       0  5002.4     .05       0
Bank Sta=4997.7,5002.4
XS Rating Curve= 0 ,0
Exp/Cntr=0.3,0.1

Type RM Length L Ch R = 1 ,95273   ,171,171,171
BEGIN DESCRIPTION:
Lytle Creek 95354.37
END DESCRIPTION:
XS GIS Cut Line= 3
      1627349.12      6792831.23      1627895.96      6792846.85
      1628586.89       6793027.4
#Sta/Elev= 30
  4342.5 1980.94  4378.4 1980.47  4448.4 1975.82  4518.5 1972.11  4578.5 1969.91
  4648.5 1969.14  4698.5 1967.62  4778.6 1963.86  4798.6 1964.52  4828.6  1963.8
  4886.6 1963.77  4989.9 1964.47    4995 1963.73  4997.6 1961.48    4998 1960.98
  5002.1 1960.98  5002.4 1961.48  5022.9 1961.68  5035.5 1964.61  5043.6 1965.36
  5105.6 1966.65  5116.4 1967.41  5136.6 1967.16  5198.6 1969.47  5232.6 1970.02
    5302 1973.46    5333 1976.13  5353.9 1976.68  5405.4 1979.62  5603.7 1983.41
#Mann= 3 ,-1 , 0
  4342.5     .05       0  4997.6     .05       0  5002.4     .05       0
Bank Sta=4997.6,5002.4
XS Rating Curve= 0 ,0
Exp/Cntr=0.3,0.1

Type RM Length L Ch R = 1 ,95102   ,206,206,206
BEGIN DESCRIPTION:
Lytle Creek 95413.9
END DESCRIPTION:
XS GIS Cut Line= 3
      1627175.44      6792924.97       1628316.1      6793047.37
      1628630.64      6793161.75
#Sta/Elev= 30
    4280 1982.23  4339.9 1980.28  4452.3 1978.05  4636.5 1971.42  4641.6 1970.68
  4661.7 1969.94  4762.3 1966.98  4820.7 1966.91  4825.8 1966.69  4842.8  1963.6
  4872.9 1961.84    4883 1963.47  4917.9 1963.01  4963.5 1963.56  4997.6 1959.93
    4998 1959.43  5002.1 1959.43  5002.4 1959.93    5010  1960.2    5015 1961.81
  5023.8 1962.96    5054  1963.3  5084.2 1965.19  5107.2 1964.81  5285.3 1968.58
  5429.3 1973.88    5458 1976.25  5473.4 1976.11  5660.1 1982.92  5761.9 1985.71
#Mann= 3 ,-1 , 0
    4280     .05       0  4997.6     .05       0  5002.4     .05       0
Bank Sta=4997.6,5002.4
XS Rating Curve= 0 ,0
Exp/Cntr=0.3,0.1

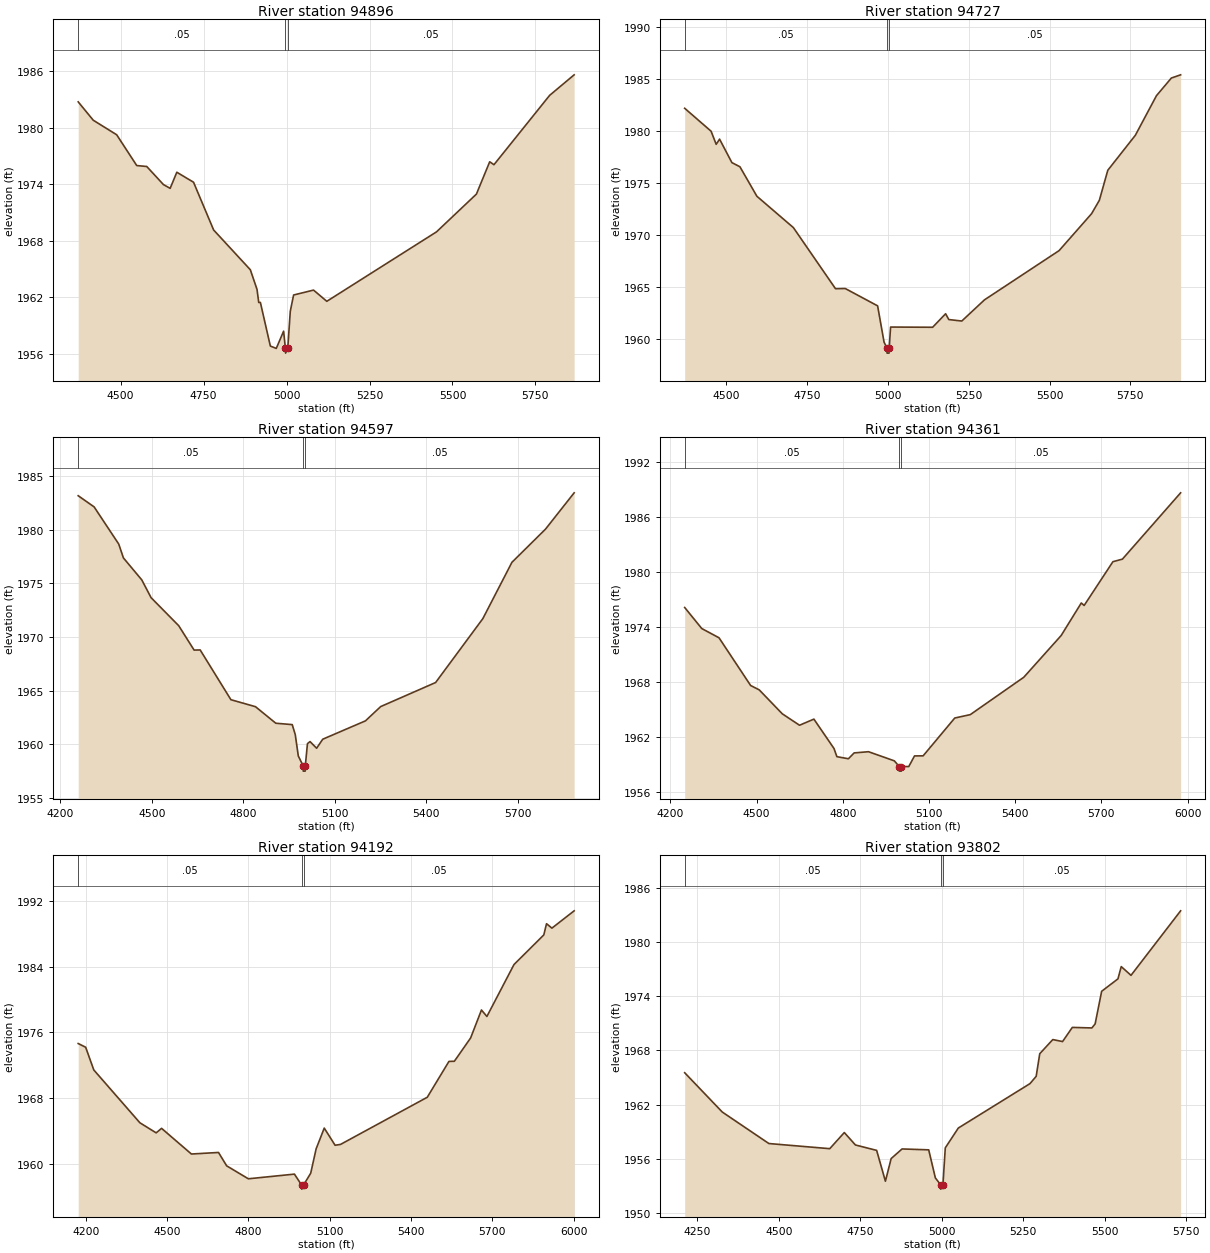
Type RM Length L Ch R = 1 ,94896   ,169,169,169
BEGIN DESCRIPTION:
Mapping XS 04d59858
END DESCRIPTION:
XS GIS Cut Line= 4
      1627129.91      6793054.75      1627670.27      6793119.86
      1628245.35      6793152.41      1628618.64      6793182.79
#Sta/Elev= 30
    4372 1982.74  4417.4 1980.79  4487.9 1979.25  4548.4 1975.98  4578.6 1975.88
  4628.9 1973.96  4649.1 1973.56  4669.2 1975.27  4719.6 1974.21  4780.2 1969.14
  4890.8 1964.92    4911 1962.83  4916.1 1961.45  4921.1 1961.45  4951.1 1956.82
    4969 1956.57  4991.1  1958.4  4996.5 1956.57    4997 1956.07  5003.6 1956.57
  5011.2 1960.51  5021.2 1962.24  5081.3 1962.76  5121.3 1961.57  5451.9 1968.94
  5572.2 1972.95  5612.3 1976.38  5625.1 1976.07  5792.9 1983.43  5866.8 1985.61
#Mann= 3 ,-1 , 0
    4372     .05       0  4996.5     .05       0  5003.6     .05       0
Bank Sta=4996.5,5003.6
XS Rating Curve= 0 ,0
Exp/Cntr=0.3,0.1

Type RM Length L Ch R = 1 ,94727   ,130,130,130
BEGIN DESCRIPTION:
Mapping XS 56ed5623
END DESCRIPTION:
XS GIS Cut Line= 4
      1627092.14      6793168.03      1627362.98      6793254.84
      1627928.95       6793291.3      1628609.48      6793230.54
#Sta/Elev= 30
  4370.6 1982.22  4452.4 1980.01  4468.1 1978.75  4478.6 1979.25  4516.7 1976.99
  4541.6 1976.59  4594.1 1973.75  4707.1 1970.73  4837.4 1964.85  4867.5 1964.87
  4967.7  1963.2  4987.7  1959.7  4996.5 1959.15    4997 1958.65  5003.1 1958.65
  5003.6 1959.15  5007.8 1961.16    5138 1961.14  5178.1 1962.44  5188.1 1961.88
  5228.2 1961.74  5298.5 1963.78  5529.4 1968.52  5629.8 1972.07  5653.9 1973.36
    5680 1976.25  5765.3 1979.62  5830.6 1983.43  5876.7 1985.13  5905.4 1985.44
#Mann= 3 ,-1 , 0
  4370.6     .05       0  4996.5     .05       0  5003.6     .05       0
Bank Sta=4996.5,5003.6
XS Rating Curve= 0 ,0
Exp/Cntr=0.3,0.1

Type RM Length L Ch R = 1 ,94597   ,236,236,236
BEGIN DESCRIPTION:
Lytle Creek 94789.65
END DESCRIPTION:
XS GIS Cut Line= 3
      1627017.78      6793306.59      1627662.33      6793386.89
      1628638.91      6793438.97
#Sta/Elev= 30
  4258.3 1983.15  4310.5 1982.11  4391.3 1978.65  4406.7 1977.36    4467 1975.31
  4497.4 1973.66  4588.1 1971.05  4638.6 1968.78  4658.6 1968.79  4759.4 1964.16
    4840 1963.51  4906.7 1961.97  4960.6 1961.84  4970.6 1960.91  4980.6 1958.92
  4996.4 1958.01  4996.9 1957.51  5003.1 1957.51  5003.6 1958.01  5010.6 1960.07
  5019.1 1960.26  5040.7 1959.64  5060.7 1960.48  5200.9 1962.19    5251 1963.52
  5431.2 1965.76  5586.2 1971.71  5681.6 1976.95  5791.8 1980.04  5885.8 1983.42
#Mann= 3 ,-1 , 0
  4258.3     .05       0  4996.4     .05       0  5003.6     .05       0
Bank Sta=4996.4,5003.6
XS Rating Curve= 0 ,0
Exp/Cntr=0.3,0.1

Type RM Length L Ch R = 1 ,94361   ,169,169,169
BEGIN DESCRIPTION:
Lytle Creek 94361.14
END DESCRIPTION:
XS GIS Cut Line= 3
      1627055.52      6793588.27      1627806.43      6793612.15
      1628780.44      6793575.27
#Sta/Elev= 30
  4249.7  1976.1  4309.2  1973.8  4369.2 1972.79  4479.3 1967.58  4509.3  1967.1
  4589.4 1964.49  4649.4 1963.24  4699.4 1963.91  4769.4  1960.7  4779.4 1959.81
  4819.5 1959.58  4839.5 1960.22  4889.5 1960.35  4979.5 1959.35  4996.4 1958.73
  4996.9 1958.23  5003.2 1958.23  5003.7 1958.73  5029.6 1958.73  5049.6 1959.89
  5079.6  1959.9  5189.7 1964.03  5243.7  1964.4  5429.9 1968.48    5560 1973.04
    5630 1976.59    5640 1976.32  5740.1  1981.1  5773.2 1981.38  5975.7 1988.62
#Mann= 3 ,-1 , 0
  4249.7     .05       0  4996.4     .05       0  5003.7     .05       0
Bank Sta=4996.4,5003.7
XS Rating Curve= 0 ,0
Exp/Cntr=0.3,0.1

Type RM Length L Ch R = 1 ,94192   ,390,390,390
BEGIN DESCRIPTION:
Lytle Creek 94191.93
END DESCRIPTION:
XS GIS Cut Line= 3
      1626927.52      6793792.27      1627754.35      6793766.23
      1628756.96      6793748.87
#Sta/Elev= 30
  4172.2 1974.65  4199.7  1974.2  4229.7 1971.43  4399.8 1964.99  4459.8 1963.76
  4479.8 1964.31  4589.9 1961.18  4689.9 1961.37    4720 1959.74    4800 1958.16
  4970.1 1958.73  4996.4  1957.4  4996.9  1956.9  5003.7  1957.4  5030.1 1958.84
  5050.1 1961.81  5080.1 1964.34  5120.1 1962.25  5140.1 1962.35  5460.2  1968.1
  5540.2 1972.47  5560.2 1972.49  5620.2 1975.33  5660.2 1978.74  5680.2 1977.95
  5780.2 1984.28  5890.2 1987.89  5900.2 1989.26  5920.2 1988.72  6002.2 1990.83
#Mann= 3 ,-1 , 0
  4172.2     .05       0  4996.4     .05       0  5003.7     .05       0
Bank Sta=4996.4,5003.7
XS Rating Curve= 0 ,0
Exp/Cntr=0.3,0.1

Type RM Length L Ch R = 1 ,93802   ,381,381,381
BEGIN DESCRIPTION:
Lytle Creek 93802.39
END DESCRIPTION:
XS GIS Cut Line= 3
      1626982.17      6793961.02       1627755.6      6794125.08
      1628487.34      6794119.87
#Sta/Elev= 30
  4210.9 1965.53  4326.2 1961.17  4469.4 1957.67  4656.3  1957.1  4700.9 1958.89
  4735.1 1957.51  4800.2 1956.91  4827.1 1953.49  4844.7    1956  4878.3 1957.07
    4960 1956.97  4980.5 1953.85  4996.3 1953.11  4996.8 1952.61  5003.7 1953.11
  5010.9 1957.19  5050.9 1959.39  5270.9 1964.32  5289.9 1965.13  5300.9 1967.64
  5340.9 1969.21  5370.9 1968.99  5400.9 1970.56  5460.9  1970.5  5470.9 1970.95
  5490.9 1974.57    5541 1975.95    5551 1977.31    5581 1976.34  5733.3  1983.5
#Mann= 3 ,-1 , 0
  4210.9     .05       0  4996.3     .05       0  5003.7     .05       0
Bank Sta=4996.3,5003.7
XS Rating Curve= 0 ,0
Exp/Cntr=0.3,0.1

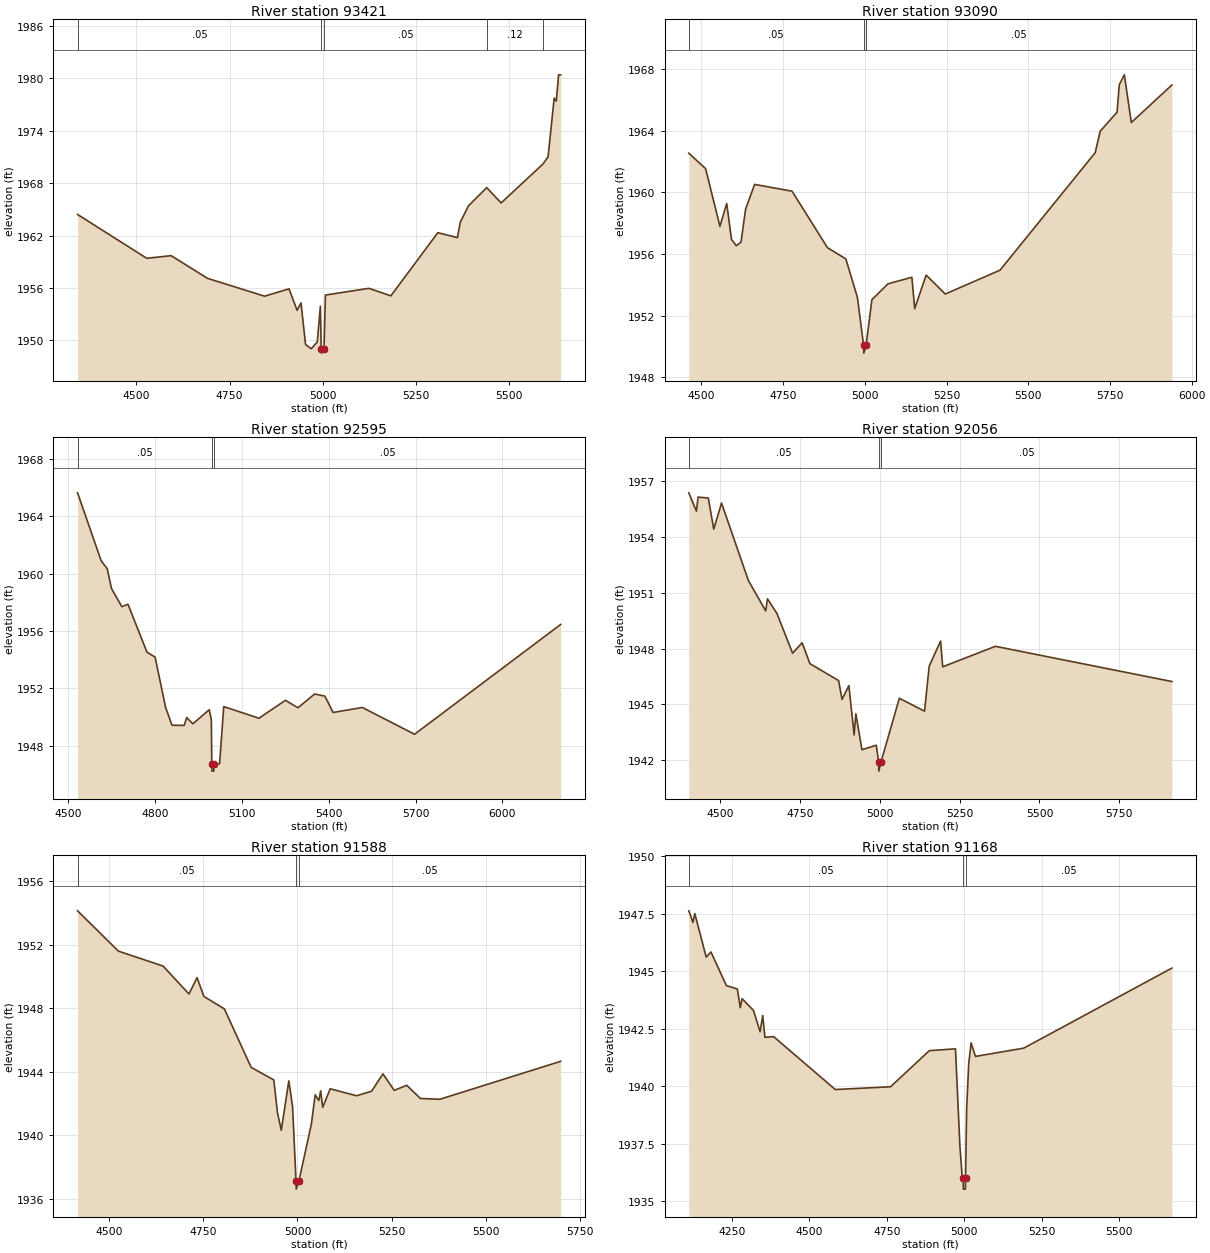
Type RM Length L Ch R = 1 ,93421   ,331,331,331
BEGIN DESCRIPTION:
Lytle Creek 93421.23
END DESCRIPTION:
XS GIS Cut Line= 3
      1626906.67      6794044.37      1627487.38      6794359.46
      1628049.84      6794658.92
#Sta/Elev= 30
  4341.7 1964.43  4527.5 1959.41  4593.1 1959.71    4691 1957.11  4844.1 1955.07
  4909.7 1955.91  4931.5 1953.45    4942  1954.3  4954.2 1949.54  4969.6 1949.05
  4985.7 1949.84    4994 1953.93  4996.3 1949.05  4996.8 1948.55  5003.7 1949.05
  5007.6  1955.2  5124.3 1955.97  5183.4 1955.11  5309.5 1962.34  5362.2 1961.78
  5369.8 1963.53  5391.7 1965.41  5440.9  1967.5  5479.6 1965.75  5592.4 1970.22
  5605.8 1971.04  5622.1 1977.75  5627.7 1977.41    5634 1980.42  5639.6 1980.42
#Mann= 5 ,-1 , 0
  4341.7     .05       0  4996.3     .05       0  5003.7     .05       0
  5440.9     .12       0  5592.4     .05       0
Bank Sta=4996.3,5003.7
XS Rating Curve= 0 ,0
Exp/Cntr=0.3,0.1

Type RM Length L Ch R = 1 ,93090   ,495,495,495
BEGIN DESCRIPTION:
Lytle Creek 93090.31
END DESCRIPTION:
XS GIS Cut Line= 3
      1626891.03      6794099.05      1627216.54      6794531.33
       1628018.6      6795015.69
#Sta/Elev= 30
  4461.4 1962.55    4513 1961.54  4556.7  1957.8  4577.5 1959.28  4592.1 1956.95
  4606.7 1956.54  4621.2 1956.77  4635.3 1958.92  4662.9 1960.52  4777.4 1960.08
  4885.7 1956.41  4941.9 1955.68  4977.3 1953.19  4996.3 1950.06  4996.8 1949.56
  5003.8 1950.06  5021.7 1953.03  5070.8 1954.06    5144 1954.49  5152.6 1952.45
  5187.6 1954.63  5246.1  1953.4  5413.7 1954.95  5704.8 1962.58  5720.3 1963.98
  5771.7 1965.21  5778.6    1967  5794.1 1967.64  5815.4 1964.54  5939.5 1966.98
#Mann= 3 ,-1 , 0
  4461.4     .05       0  4996.3     .05       0  5003.8     .05       0
Bank Sta=4996.3,5003.8
XS Rating Curve= 0 ,0
Exp/Cntr=0.3,0.1

Type RM Length L Ch R = 1 ,92595   ,539,539,539
BEGIN DESCRIPTION:
Lytle Creek 92595.09
END DESCRIPTION:
XS GIS Cut Line= 4
      1626492.98       6794257.4      1626760.37      6794646.33
      1627003.42      6794951.88      1627680.22       6795389.2
#Sta/Elev= 30
  4532.8 1965.63  4614.1  1960.9  4635.1 1960.34    4650 1958.95  4685.8 1957.69
  4706.8 1957.86  4772.4 1954.52  4800.5 1954.17  4836.9 1950.65    4859 1949.42
  4900.9 1949.41  4909.7 1949.96  4930.7 1949.52  4987.5  1950.5  4994.7  1949.8
  4996.3 1946.72  4996.8 1946.22  5003.3 1946.22  5003.8 1946.72  5023.2 1946.73
  5037.6 1950.72  5159.3 1949.91  5250.6 1951.16  5293.9 1950.64  5351.6  1951.6
  5386.8 1951.45  5415.3 1950.31  5516.1 1950.66  5696.4 1948.79    6201 1956.45
#Mann= 3 ,-1 , 0
  4532.8     .05       0  4996.3     .05       0  5003.8     .05       0
Bank Sta=4996.3,5003.8
XS Rating Curve= 0 ,0
Exp/Cntr=0.3,0.1

Type RM Length L Ch R = 1 ,92056   ,468,468,468
BEGIN DESCRIPTION:
Lytle Creek 92056
END DESCRIPTION:
XS GIS Cut Line= 3
       1626031.2      6794181.05      1626249.95      6794740.08
      1626784.65      6795479.62
#Sta/Elev= 30
  4401.7 1956.36  4425.6 1955.38  4430.9 1956.13  4462.9 1956.08  4479.9 1954.41
  4504.3 1955.81  4588.4 1951.65  4642.7 1950.02  4648.1 1950.67  4677.9 1949.88
  4726.8 1947.75  4756.7 1948.31  4781.1 1947.19  4870.9 1946.28  4881.7 1945.27
  4903.1 1946.01  4919.5 1943.36  4924.9  1944.5    4944 1942.57    4989 1942.81
  4996.2 1941.92  4996.7 1941.42  5003.8 1941.92  5061.1 1945.33    5140 1944.64
  5154.7 1947.06  5190.3  1948.4  5196.9 1947.02    5362 1948.12  5914.6 1946.23
#Mann= 3 ,-1 , 0
  4401.7     .05       0  4996.2     .03       0  5003.8     .05       0
Bank Sta=4996.2,5003.8
XS Rating Curve= 0 ,0
Exp/Cntr=0.3,0.1

Type RM Length L Ch R = 1 ,91588   ,420,420,420
BEGIN DESCRIPTION:
Mapping XS 2f5a3b62
END DESCRIPTION:
XS GIS Cut Line= 4
      1625730.16      6793971.85      1625842.14       6794378.1
      1625857.77      6794823.42      1626081.71      6795174.96
#Sta/Elev= 30
  4415.7 1954.13  4524.3 1951.59    4643 1950.65  4711.7 1948.89  4733.3 1949.92
  4751.3 1948.74  4805.9 1947.95    4877 1944.27  4937.1 1943.48  4947.1 1941.39
  4957.1 1940.31  4977.1 1943.42  4987.1 1941.78  4996.2  1937.1  4996.7  1936.6
  5003.8  1937.1  5037.1 1940.71  5047.1 1942.54  5056.7 1942.18  5061.7 1942.79
  5067.1 1941.75  5087.1 1942.92  5157.2 1942.48  5197.2 1942.77  5227.2 1943.86
  5257.3 1942.82  5290.4 1943.14  5326.8 1942.31  5378.5 1942.26  5699.5 1944.65
#Mann= 3 ,-1 , 0
  4415.7     .05       0  4996.2     .05       0  5003.8     .05       0
Bank Sta=4996.2,5003.8
XS Rating Curve= 0 ,0
Exp/Cntr=0.3,0.1

Type RM Length L Ch R = 1 ,91168   ,430,430,430
BEGIN DESCRIPTION:
Mapping XS 617cf102
END DESCRIPTION:
XS GIS Cut Line= 5
      1625001.01      6794224.48       1625191.1      6794534.35
      1625516.62      6794698.42      1625870.79      6795109.87
      1626091.04      6795296.44
#Sta/Elev= 30
  4110.3 1947.62  4123.9 1947.12  4129.8  1947.5  4166.5 1945.61  4181.9 1945.83
  4231.7 1944.37  4267.1 1944.22  4276.6 1943.41  4282.5  1943.8  4319.2 1943.29
  4340.5 1942.36  4349.1 1943.07    4356 1942.12  4384.3 1942.15  4583.3 1939.85
  4761.7 1939.97  4886.8 1941.54  4971.3 1941.62  4985.5 1937.41  4993.2 1936.02
  4996.2 1936.02  4996.7 1935.52  5003.3 1935.52  5003.8 1936.02  5007.4 1939.04
    5014 1940.97  5021.7 1941.88  5035.7 1941.29  5191.8 1941.65  5669.9 1945.13
#Mann= 3 ,-1 , 0
  4110.3     .05       0  4996.2     .05       0  5003.8     .05       0
Bank Sta=4996.2,5003.8
XS Rating Curve= 0 ,0
Exp/Cntr=0.3,0.1