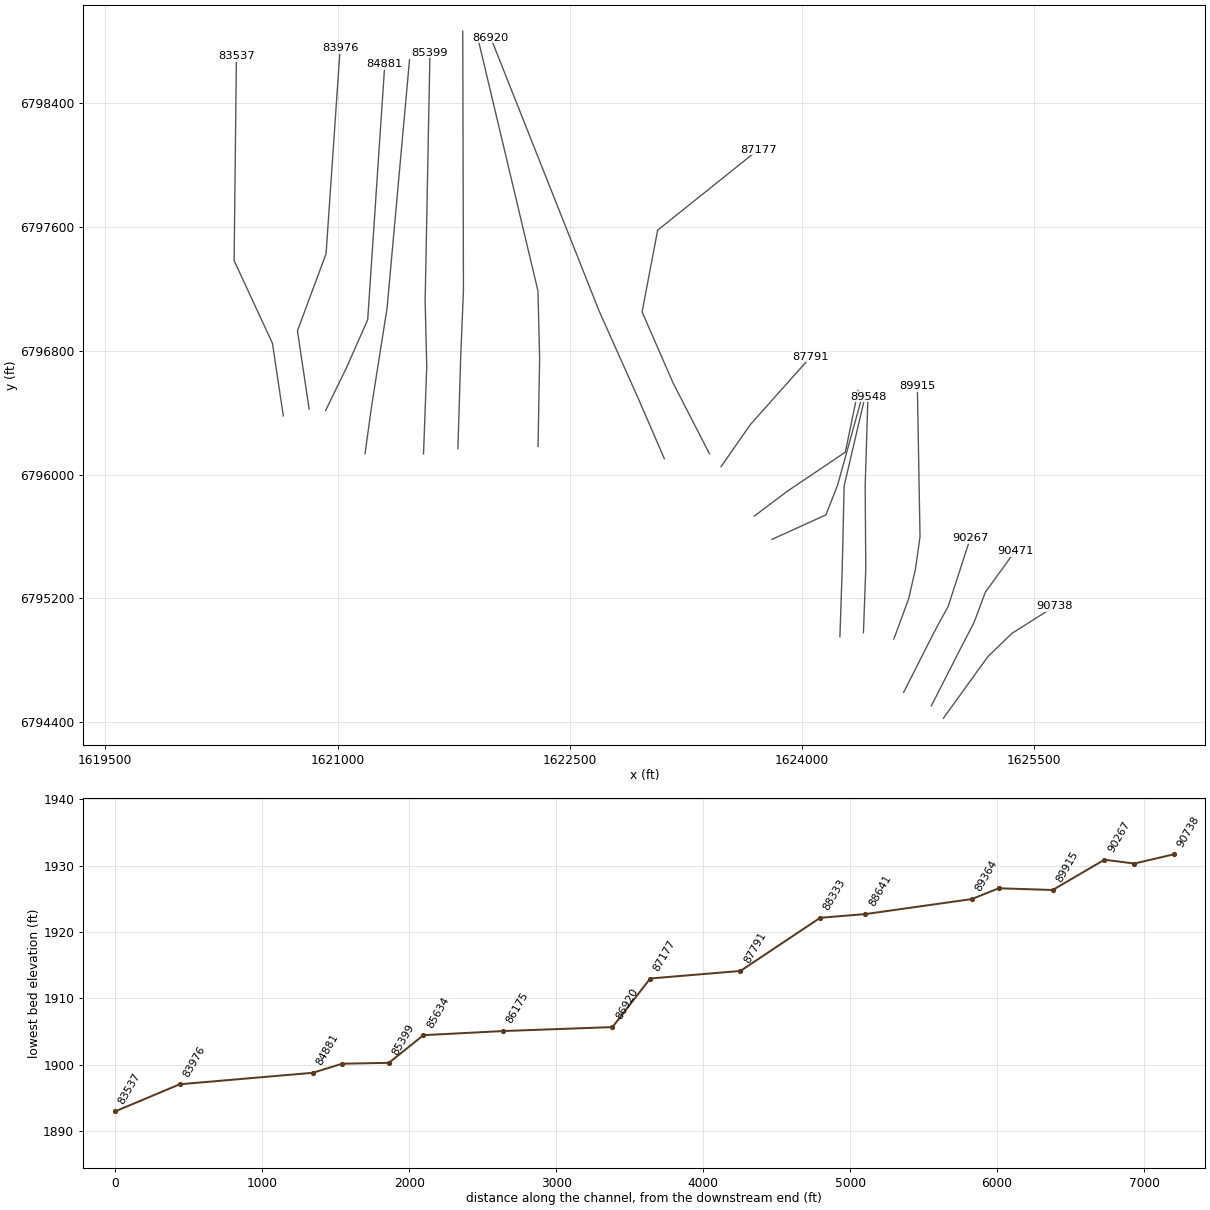
HEC-RAS study Lytle Creek.prj: Lytle Creek Base Level Engineering

--- Lytle Creek.g01 (geometry) --- (continued)

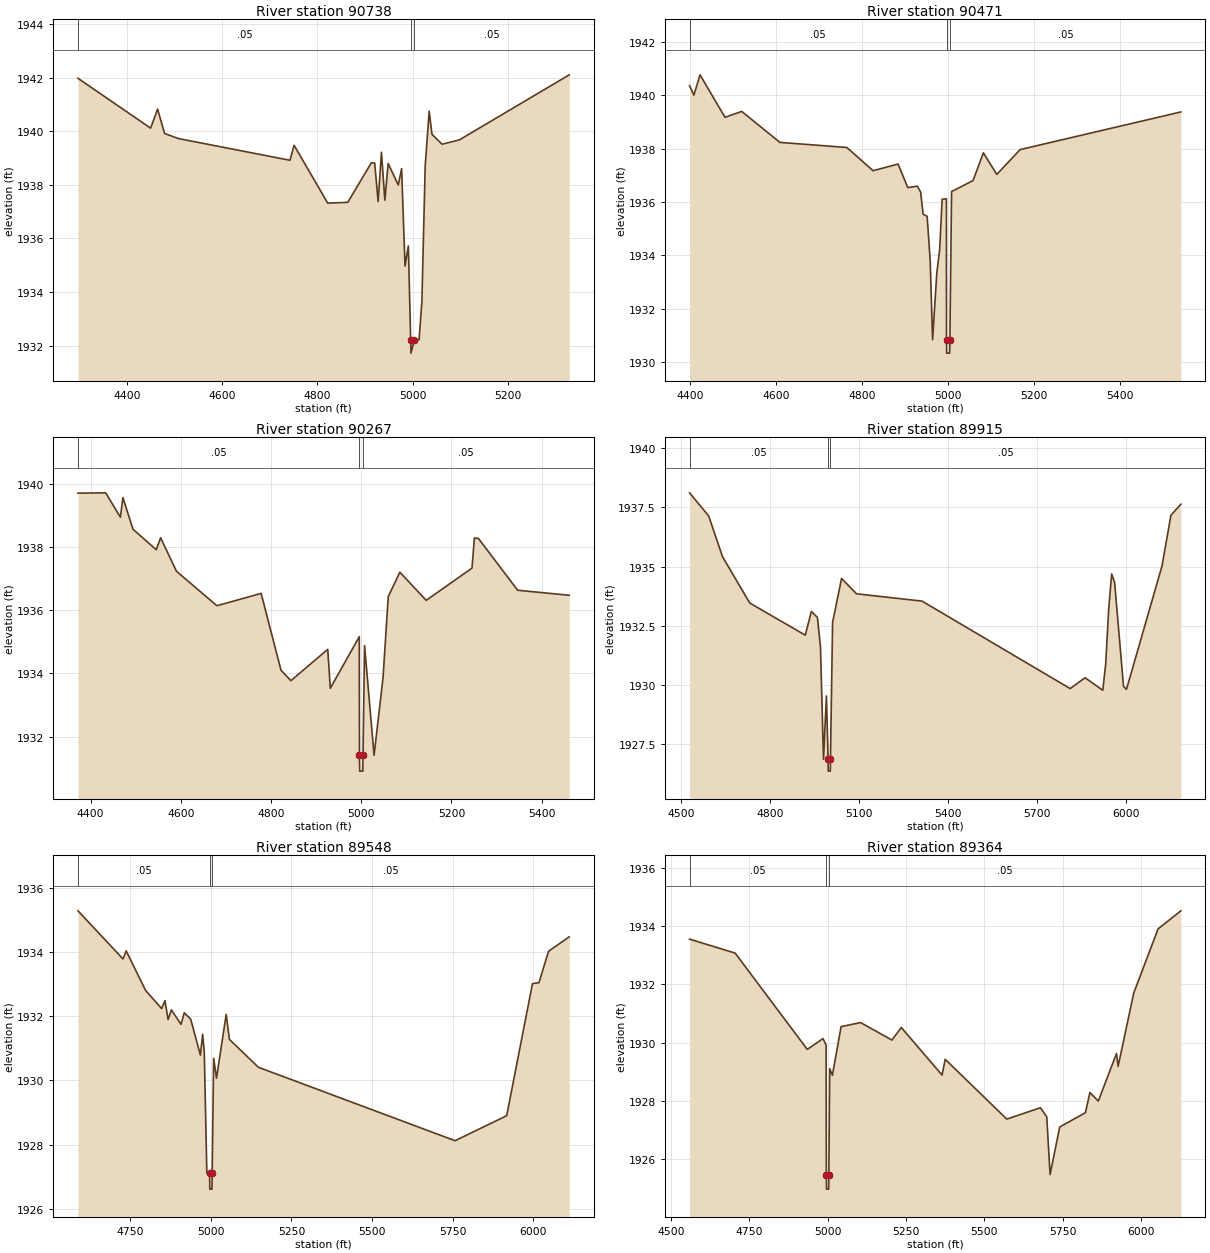
Type RM Length L Ch R = 1 ,90738   ,267,267,267
BEGIN DESCRIPTION:
Lytle Creek 90738.38
END DESCRIPTION:
XS GIS Cut Line= 4
      1624912.41      6794426.56       1625198.4      6794822.88
      1625354.36      6794974.18      1625631.09      6795149.29
#Sta/Elev= 30
  4296.2 1941.98    4449 1940.12  4463.7 1940.83  4478.4 1939.92  4507.6 1939.73
  4742.2 1938.92  4750.8 1939.48  4821.6 1937.32  4863.8 1937.35  4913.5 1938.83
  4920.4 1938.82  4927.6 1937.38  4934.6 1939.22  4941.8 1937.43  4948.7  1938.8
    4970    1938    4977 1938.61  4984.2 1934.97  4991.2 1935.72  4996.1 1932.22
  4996.6 1931.72    5004 1932.22  5013.8 1932.22  5019.7 1933.65  5026.6 1938.69
    5035 1940.75  5040.9 1939.89  5062.1 1939.52  5098.5 1939.68  5329.7 1942.11
#Mann= 3 ,-1 , 0
  4296.2     .05       0  4996.1     .03       0    5004     .05       0
Bank Sta=4996.1,5004
XS Rating Curve= 0 ,0
Exp/Cntr=0.3,0.1

Type RM Length L Ch R = 1 ,90471   ,204,204,204
BEGIN DESCRIPTION:
Lytle Creek 90470.76
END DESCRIPTION:
XS GIS Cut Line= 5
      1624834.25      6794506.37       1625033.3       6794896.5
      1625109.28      6795042.61      1625183.45      6795241.12
      1625375.91      6795506.38
#Sta/Elev= 30
  4398.7 1940.35  4408.8    1940    4423 1940.76    4481 1939.17  4519.9 1939.39
  4608.8 1938.23  4764.4 1938.04  4825.5 1937.17  4883.5 1937.42    4906 1936.54
  4928.5 1936.59    4936 1936.37  4941.7 1935.54  4951.1 1935.46  4958.1 1933.82
  4963.8 1930.84  4973.6 1933.35  4980.3 1934.23  4985.9  1936.1  4995.9 1936.12
  4996.1 1930.84  4996.6 1930.34  5003.5 1930.34    5004 1930.84  5007.9 1936.39
  5057.9  1936.8  5081.8 1937.84  5113.1 1937.03  5167.2 1937.96    5541 1939.37
#Mann= 3 ,-1 , 0
  4398.7     .05       0  4996.1     .05       0    5004     .05       0
Bank Sta=4996.1,5004
XS Rating Curve= 0 ,0
Exp/Cntr=0.3,0.1

Type RM Length L Ch R = 1 ,90267   ,352,352,352
BEGIN DESCRIPTION:
Lytle Creek 90266.99
END DESCRIPTION:
XS GIS Cut Line= 5
      1624655.44      6794593.21       1624850.4      6794978.34
      1624943.61      6795150.42      1625037.42      6795439.85
      1625085.97      6795589.66
#Sta/Elev= 30
  4372.1  1939.7  4433.5 1939.71  4466.1 1938.94  4471.7 1939.56    4494 1938.56
  4545.6 1937.91  4555.3 1938.29  4590.4 1937.23  4680.1 1936.14  4778.1 1936.53
  4822.2  1934.1  4844.1 1933.77  4925.8 1934.76  4931.5 1933.53  4995.7 1935.16
  4996.1 1931.41  4996.6 1930.91  5003.5 1930.91    5004 1931.41  5007.4 1934.88
  5028.5 1931.41  5048.4 1933.87    5060 1936.43  5085.7  1937.2  5144.1 1936.31
  5245.6 1937.33  5250.9 1938.28  5259.7 1938.27  5346.8 1936.63  5461.2 1936.47
#Mann= 3 ,-1 , 0
  4372.1     .05       0  4996.1     .05       0    5004     .05       0
Bank Sta=4996.1,5004
XS Rating Curve= 0 ,0
Exp/Cntr=0.3,0.1

Type RM Length L Ch R = 1 ,89915   ,367,367,367
BEGIN DESCRIPTION:
Lytle Creek 89915
END DESCRIPTION:
XS GIS Cut Line= 5
      1624592.06      6794937.34      1624688.25      6795198.63
      1624731.81        6795390.      1624761.34      6795599.28
      1624743.98      6796571.47
#Sta/Elev= 30
  4528.4 1938.12    4593 1937.14  4639.6 1935.42  4731.6 1933.46    4919  1932.1
  4939.5  1933.1    4960 1932.85  4970.3  1931.6  4980.5 1926.85  4990.3 1929.53
  4996.1 1926.85  4996.6 1926.35  5003.5 1926.35    5004 1926.85  5011.2 1932.64
  5041.5  1934.5    5092 1933.85  5313.2 1933.54  5813.3 1929.84  5863.3  1930.3
  5923.3 1929.77  5933.3 1930.91  5943.3 1933.22  5953.3 1934.69  5963.3 1934.32
  5993.3 1929.93  6003.3 1929.81  6123.3 1935.03  6153.3 1937.17  6186.8 1937.64
#Mann= 3 ,-1 , 0
  4528.4     .05       0  4996.1     .05       0    5004     .05       0
Bank Sta=4996.1,5004
XS Rating Curve= 0 ,0
Exp/Cntr=0.3,0.1

Type RM Length L Ch R = 1 ,89548   ,184,184,184
BEGIN DESCRIPTION:
Lytle Creek 89547.78
END DESCRIPTION:
XS GIS Cut Line= 4
      1624395.83      6794978.49      1624411.02      6795395.18
      1624407.04        6795927.      1624424.97      6796502.02
#Sta/Elev= 30
  4587.7 1935.29  4727.3 1933.79  4737.3 1934.04  4797.3 1932.81  4847.4 1932.24
  4857.4 1932.49  4867.4  1931.9  4877.4  1932.2  4907.4 1931.75  4917.4 1932.11
  4937.4 1931.91  4967.5 1930.79  4974.5 1931.44  4979.5 1930.89  4987.5 1927.11
  4996.1 1927.11  4996.6 1926.61  5003.5 1926.61    5004 1927.11  5008.6 1930.69
  5017.5 1930.07  5047.5 1932.06  5057.5 1931.28  5147.5 1930.41  5757.6 1928.12
  5917.7  1928.9  5997.7 1933.02  6017.7 1933.05  6047.7 1934.03  6111.8 1934.48
#Mann= 3 ,-1 , 0
  4587.7     .05       0  4996.1     .05       0    5004     .05       0
Bank Sta=4996.1,5004
XS Rating Curve= 0 ,0
Exp/Cntr=0.3,0.1

Type RM Length L Ch R = 1 ,89364   ,723,723,723
BEGIN DESCRIPTION:
Lytle Creek 89363.56
END DESCRIPTION:
XS GIS Cut Line= 4
      1624243.92      6794952.48      1624259.11      6795399.52
      1624271.08      6795925.99      1624406.39      6796504.47
#Sta/Elev= 30
  4559.5 1933.55  4705.1 1933.07  4935.2 1929.77  4985.3 1930.14  4995.3 1929.92
  4996.1 1925.48  4996.6 1924.98  5003.5 1924.98    5004 1925.48  5006.8 1929.11
  5015.3 1928.88  5043.1 1930.55  5105.3 1930.69  5205.3 1930.09  5235.3 1930.52
  5365.4 1928.89  5375.4 1929.43    5572 1927.38  5679.2 1927.77  5699.5 1927.46
  5710.1 1925.48  5740.9 1927.11    5823  1927.6  5837.2 1928.29  5864.1    1928
  5922.2 1929.63  5927.3 1929.19  5977.1  1931.7  6054.8  1933.9  6127.5 1934.52
#Mann= 3 ,-1 , 0
  4559.5     .05       0  4996.1     .03       0    5004     .05       0
Bank Sta=4996.1,5004
XS Rating Curve= 0 ,0
Exp/Cntr=0.3,0.1

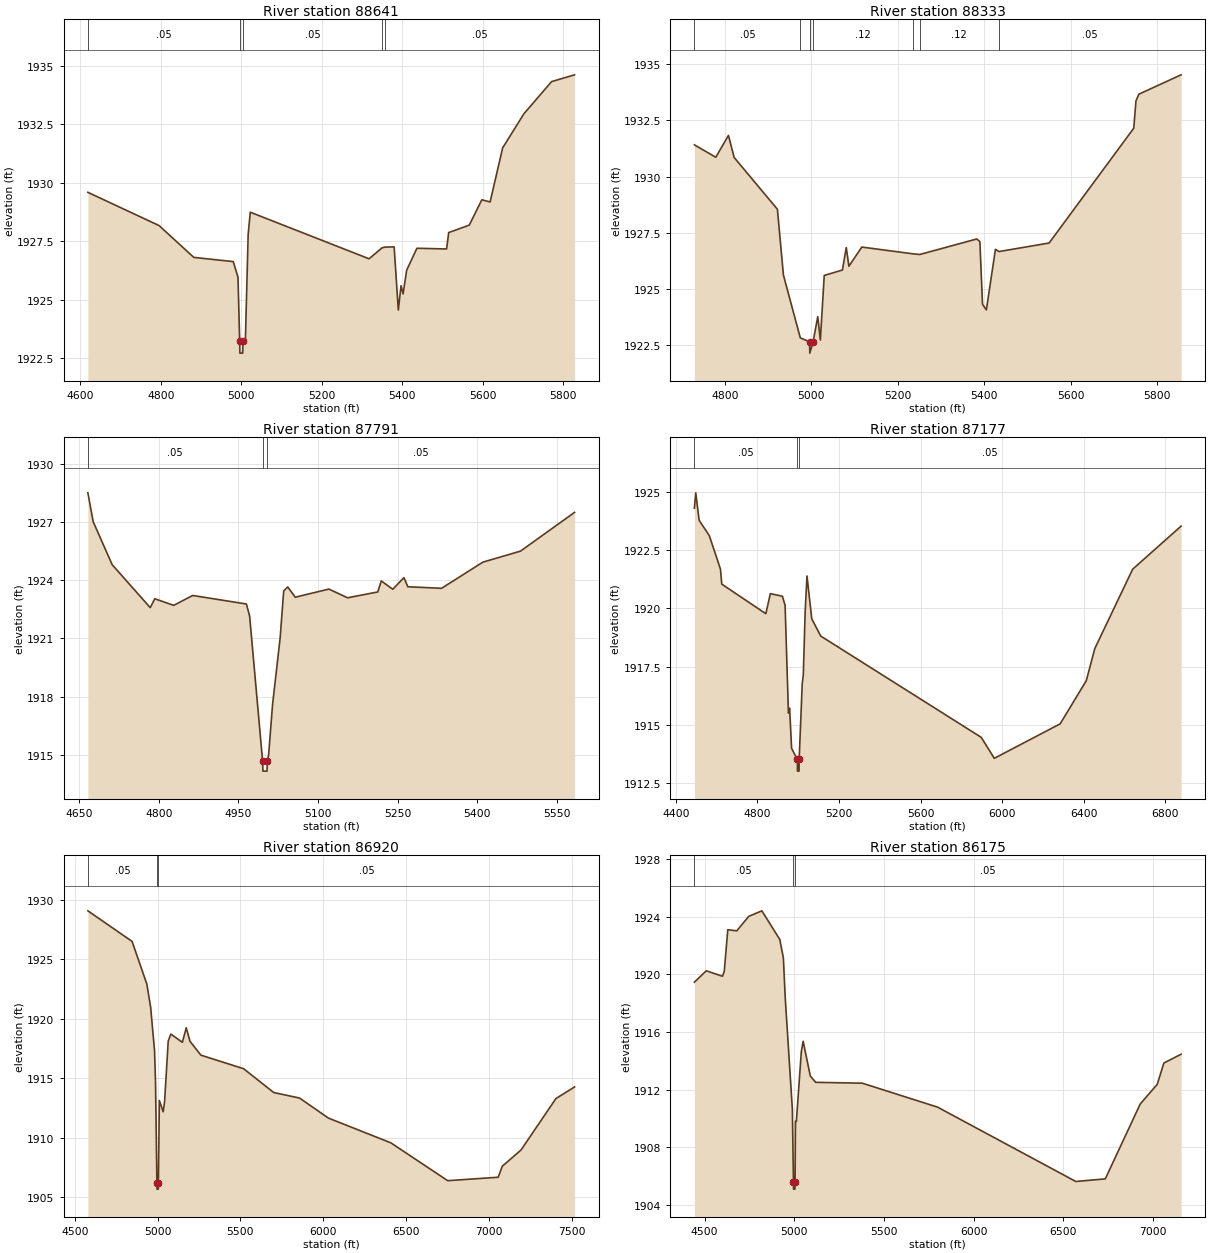
Type RM Length L Ch R = 1 ,88641   ,308,308,308
BEGIN DESCRIPTION:
Lytle Creek 88641.42
END DESCRIPTION:
XS GIS Cut Line= 4
      1623805.32      6795581.36      1624153.64      6795739.78
      1624229.55      6795933.46      1624394.59      6796530.28
#Sta/Elev= 30
  4618.6 1929.59  4795.6 1928.17  4881.9 1926.81  4980.1 1926.63  4991.8 1925.96
    4996 1923.22  4996.5 1922.72  5003.6 1922.72  5004.1 1923.22  5010.1 1923.22
  5017.1  1927.8  5022.4 1928.74  5317.7 1926.75  5350.1 1927.22    5358 1927.25
    5380 1927.26  5390.4 1924.56  5397.1  1925.6  5402.2 1925.25  5411.1 1926.26
  5436.6  1927.2  5510.4 1927.17  5515.6 1927.87  5566.8 1928.19  5597.9 1929.27
  5618.6 1929.18  5649.8 1931.49  5702.8 1932.95  5771.4 1934.32  5828.5 1934.61
#Mann= 5 ,-1 , 0
  4618.6     .05       0    4996     .05       0  5004.1     .05       0
  5350.1     .12       0    5358     .05       0
Bank Sta=4996,5004.1
XS Rating Curve= 0 ,0
Exp/Cntr=0.3,0.1

Type RM Length L Ch R = 1 ,88333   ,542,542,542
BEGIN DESCRIPTION:
Lytle Creek 88332.5
END DESCRIPTION:
XS GIS Cut Line= 4
      1623691.45      6795732.46      1623908.45      6795895.21
      1624278.94      6796144.69      1624361.48      6796543.54
#Sta/Elev= 30
  4729.7 1931.41  4779.2 1930.86  4808.4 1931.83  4821.6 1930.85  4921.6 1928.55
  4935.5 1925.63  4974.5 1922.84    4996 1922.66  4996.5 1922.16  5004.1 1922.66
  5014.9 1923.78  5020.9 1922.74  5029.9 1925.61  5071.9 1925.85  5080.8 1926.85
  5086.9 1926.02  5116.8 1926.87  5235.1 1926.57  5250.6 1926.54  5382.6 1927.23
  5389.7 1927.11  5395.8 1924.33  5404.7 1924.08  5425.7 1926.77  5433.8 1926.67
  5549.8 1927.05  5745.5 1932.15  5750.6 1933.36  5757.3 1933.66  5854.9 1934.52
#Mann= 7 ,-1 , 0
  4729.7     .05       0  4974.5     .12       0    4996     .07       0
  5004.1     .12       0  5235.1     .05       0  5250.6     .12       0
  5433.8     .05       0
Bank Sta=4996,5004.1
XS Rating Curve= 0 ,0
Exp/Cntr=0.3,0.1

Type RM Length L Ch R = 1 ,87791   ,614,614,614
BEGIN DESCRIPTION:
Lytle Creek 87790.86
END DESCRIPTION:
XS GIS Cut Line= 3
      1623476.61      6796051.48       1623665.4      6796322.73
        1624056.      6796761.07
#Sta/Elev= 30
  4666.1 1928.52  4676.1 1927.03  4711.9 1924.81  4783.7 1922.59  4792.2 1923.05
    4828 1922.71  4863.7 1923.22    4965 1922.78  4971.1 1922.15  4995.6 1914.65
  4996.1 1914.15  5003.9 1914.15  5004.4 1914.65  5006.9 1914.99  5014.4 1917.61
  5028.6 1921.02  5035.3 1923.45  5042.9 1923.66  5057.1 1923.13  5120.6 1923.55
  5155.7  1923.1  5212.6  1923.4  5219.3 1923.97    5241 1923.54  5261.9 1924.14
  5269.4 1923.67    5333 1923.59  5410.8 1924.94  5481.8 1925.51  5583.7 1927.51
#Mann= 3 ,-1 , 0
  4666.1     .05       0  4995.6     .05       0  5004.4     .05       0
Bank Sta=4995.6,5004.4
XS Rating Curve= 0 ,0
Exp/Cntr=0.3,0.1

Type RM Length L Ch R = 1 ,87177   ,257,257,257
BEGIN DESCRIPTION:
Lytle Creek 87176.58
END DESCRIPTION:
XS GIS Cut Line= 6
       1623401.6      6796134.29      1623167.21      6796590.06
      1623071.22      6796810.21      1622966.43      6797050.54
       1623066.9      6797578.44      1623717.96      6798099.29
#Sta/Elev= 30
  4490.8  1924.3  4497.5 1924.96    4514 1923.78    4564 1923.12  4618.7 1921.68
  4624.9 1921.04    4841 1919.77  4863.2 1920.63  4922.3 1920.52  4935.4 1920.13
  4951.9  1915.5  4957.6 1915.71  4967.3 1913.99  4995.6 1913.51  4996.1 1913.01
  5003.9 1913.01  5004.4 1913.51  5019.4 1916.75  5024.8 1917.15  5033.8 1919.85
  5042.8 1921.39  5066.2 1919.55  5110.2 1918.81  5897.1 1914.46  5961.1 1913.56
  6283.9 1915.04    6412 1916.89  6453.7 1918.27  6639.4 1921.68  6876.8 1923.53
#Mann= 3 ,-1 , 0
  4490.8     .05       0  4995.6     .05       0  5004.4     .05       0
Bank Sta=4995.6,5004.4
XS Rating Curve= 0 ,0
Exp/Cntr=0.3,0.1

Type RM Length L Ch R = 1 ,86920   ,745,745,745
BEGIN DESCRIPTION:
Lytle Creek 86919.68
END DESCRIPTION:
XS GIS Cut Line= 4
      1623109.94      6796103.03      1622940.65       6796493.7
      1622688.57       6797056.9       1621989.4      6798819.91
#Sta/Elev= 30
  4578.6 1929.08  4845.6 1926.51  4934.4 1922.94  4957.9 1920.96  4981.3 1917.31
  4987.3 1914.63  4995.6 1906.19  4996.1 1905.69  5003.9 1905.69  5004.4 1906.19
  5010.3 1913.14  5033.5 1912.19    5042 1913.05  5063.9 1918.13  5079.8 1918.72
  5149.4 1918.03  5172.6 1919.25  5195.3 1918.12  5261.1 1916.95  5519.3 1915.81
  5701.1 1913.81  5857.8 1913.34  6031.4 1911.66  6408.7 1909.58  6751.8  1906.4
    7057 1906.69  7081.3 1907.61  7194.7 1908.98  7405.4  1913.3    7518 1914.28
#Mann= 3 ,-1 , 0
  4578.6     .05       0  4995.6     .03       0  5004.4     .05       0
Bank Sta=4995.6,5004.4
XS Rating Curve= 0 ,0
Exp/Cntr=0.3,0.1

Type RM Length L Ch R = 1 ,86175   ,541,541,541
BEGIN DESCRIPTION:
Lytle Creek 86174.52
END DESCRIPTION:
XS GIS Cut Line= 4
      1622294.38      6796181.76      1622304.79      6796747.69
      1622293.84      6797186.07      1621898.49      6798849.29
#Sta/Elev= 30
  4443.1 1919.45  4509.4 1920.24  4599.4 1919.86  4609.4 1920.18  4629.4 1923.09
  4679.4 1923.01  4746.5 1924.02  4819.4  1924.4  4919.4 1922.41  4939.4 1921.12
  4949.4 1918.41  4989.4 1910.63  4995.6 1905.59  4996.1 1905.09    5004 1905.09
  5004.5 1905.59  5006.8 1909.79  5011.8 1909.79  5039.4 1914.63  5049.5 1915.35
  5089.5 1912.94  5119.5  1912.5  5379.6 1912.44  5799.1 1910.78    6570 1905.62
  6734.5  1905.8  6929.5    1911  7024.2 1912.36  7061.2 1913.84  7157.2 1914.45
#Mann= 3 ,-1 , 0
  4443.1     .05       0  4995.6     .05       0  5004.5     .05       0
Bank Sta=4995.6,5004.5
XS Rating Curve= 0 ,0
Exp/Cntr=0.3,0.1

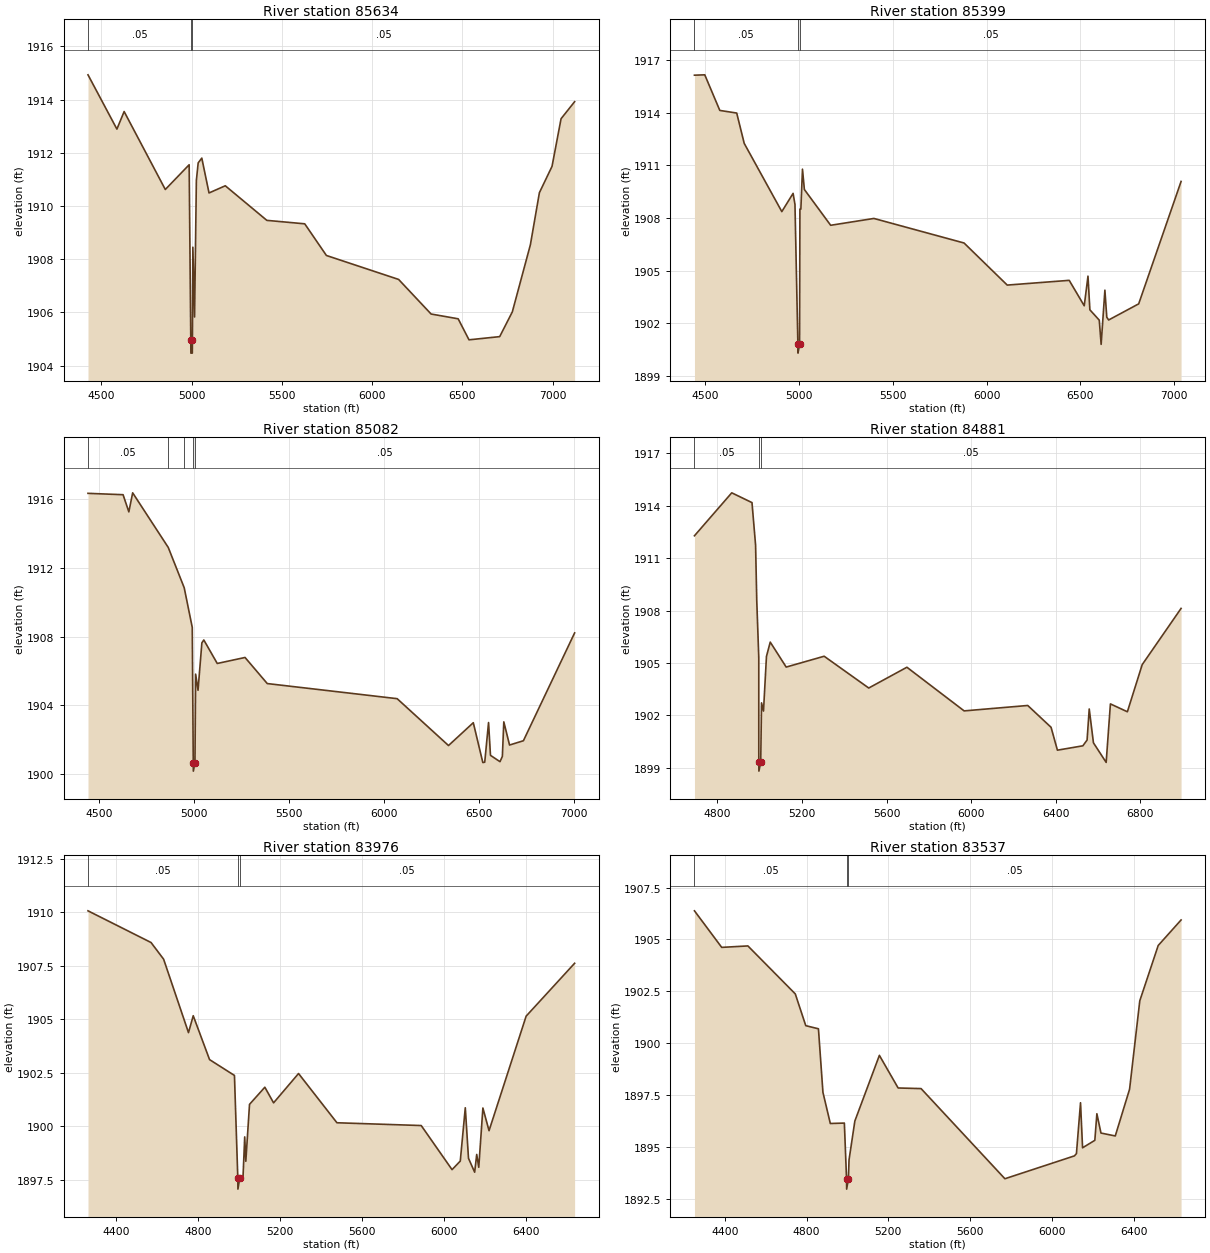
Type RM Length L Ch R = 1 ,85634   ,235,235,235
BEGIN DESCRIPTION:
Lytle Creek 85633.84
END DESCRIPTION:
XS GIS Cut Line= 4
      1621777.02      6796167.84      1621794.38      6796744.22
      1621812.68      6797189.66      1621808.22       6798863.1
#Sta/Elev= 30
  4426.1 1914.93  4586.3 1912.89  4626.3 1913.55  4854.4 1910.62  4986.5 1911.55
  4995.6 1904.97  4996.1 1904.47    5004 1904.47  5004.5 1904.97  5007.1 1908.45
  5016.5 1905.83  5026.5 1910.96  5036.5 1911.62  5056.6  1911.8  5096.6 1910.49
  5186.7 1910.76  5416.9 1909.46  5626.9 1909.33  5746.9 1908.14  6146.9 1907.24
  6326.9 1905.94  6476.9 1905.76  6536.9 1904.97  6706.9 1905.09  6776.9 1906.02
  6876.9 1908.54  6926.9  1910.5  6996.9 1911.49  7046.9 1913.28    7122 1913.92
#Mann= 3 ,-1 , 0
  4426.1     .05       0  4995.6     .05       0  5004.5     .05       0
Bank Sta=4995.6,5004.5
XS Rating Curve= 0 ,0
Exp/Cntr=0.3,0.1

Type RM Length L Ch R = 1 ,85399   ,317,317,317
BEGIN DESCRIPTION:
Lytle Creek 85399.18
END DESCRIPTION:
XS GIS Cut Line= 4
       1621554.8      6796133.14      1621575.63      6796695.61
      1621565.33       6797120.2       1621596.4      6798723.63
#Sta/Elev= 30
  4444.8 1916.15  4499.7 1916.17  4579.8 1914.14  4669.8 1913.99  4709.8 1912.26
    4910 1908.37    4970 1909.41    4980 1908.78  4995.6  1900.8  4996.1  1900.3
  5004.5  1900.8  5006.4 1908.51  5011.4 1908.51    5020 1910.79  5030.1 1909.63
  5170.1 1907.59  5400.2 1907.98  5880.3 1906.58  6110.3 1904.18  6440.4 1904.45
  6520.4    1903  6540.4 1904.69  6550.4 1902.77  6600.4 1902.18  6610.4  1900.8
  6630.4 1903.89  6640.4 1902.35  6650.4 1902.19  6810.4 1903.11  7036.1 1910.09
#Mann= 3 ,-1 , 0
  4444.8     .05       0  4995.6     .03       0  5004.5     .05       0
Bank Sta=4995.6,5004.5
XS Rating Curve= 0 ,0
Exp/Cntr=0.3,0.1

Type RM Length L Ch R = 1 ,85082   ,201,201,201
BEGIN DESCRIPTION:
Mapping XS dbb66543
END DESCRIPTION:
XS GIS Cut Line= 4
      1621177.21      6796135.02      1621218.88      6796437.13
      1621319.57      6797076.02      1621464.47      6798679.14
#Sta/Elev= 30
  4441.4 1916.35  4626.1 1916.27  4656.4 1915.27  4676.5 1916.38  4863.8  1913.2
  4947.9 1910.85  4990.2 1908.54  4995.5 1900.67    4996 1900.17  5004.5 1900.67
    5008 1905.82  5020.6 1904.88  5040.8 1907.64    5051 1907.81  5121.8 1906.44
    5268 1906.79    5385 1905.27  6068.7 1904.39    6339 1901.66  6469.5 1902.99
  6519.7 1900.67  6529.7 1900.69  6549.8    1903  6559.9 1901.09  6610.1 1900.72
  6622.5 1901.03  6630.1 1903.04  6660.3 1901.69  6733.3 1901.94  7002.8 1908.22
#Mann= 5 ,-1 , 0
  4441.4     .05       0  4863.8     .12       0  4947.9     .05       0
  4995.5     .05       0  5004.5     .05       0
Bank Sta=4995.5,5004.5
XS Rating Curve= 0 ,0
Exp/Cntr=0.3,0.1

Type RM Length L Ch R = 1 ,84881   ,905,905,905
BEGIN DESCRIPTION:
Lytle Creek 84881.32
END DESCRIPTION:
XS GIS Cut Line= 4
      1620922.84      6796414.33      1621058.27      6796692.14
      1621194.35      6797000.21      1621304.75      6798651.38
#Sta/Elev= 30
  4691.3 1912.28  4867.6 1914.74  4963.3 1914.18  4980.3 1911.74  4985.8 1908.58
  4995.3 1905.33  4995.5  1899.3    4996  1898.8  5004.5  1899.3  5008.4 1902.71
  5017.7 1902.24  5031.7 1905.37  5049.6 1906.19    5125 1904.76  5304.5 1905.38
  5515.3 1903.56  5695.7 1904.75  5966.3 1902.25    6267 1902.56  6377.3 1901.31
  6407.3    1900  6527.6 1900.25  6547.6 1900.58  6557.7 1902.36  6577.7 1900.42
  6637.8  1899.3  6657.9 1902.65  6738.1  1902.2  6808.2  1904.9    6992 1908.12
#Mann= 3 ,-1 , 0
  4691.3     .05       0  4995.5     .05       0  5004.5     .05       0
Bank Sta=4995.5,5004.5
XS Rating Curve= 0 ,0
Exp/Cntr=0.3,0.1

Type RM Length L Ch R = 1 ,83976   ,439,439,439
BEGIN DESCRIPTION:
Mapping XS f6a1cfaa
END DESCRIPTION:
XS GIS Cut Line= 4
       1620816.1      6796423.27      1620740.58      6796928.45
      1620925.48      6797425.85      1621016.47      6798754.29
#Sta/Elev= 30
  4264.9 1910.07  4572.3 1908.59  4633.7 1907.81    4755 1904.38  4778.1 1905.17
  4857.7 1903.12  4979.1 1902.38  4995.5 1897.57    4996 1897.07  5004.6 1897.57
  5020.6 1897.57  5029.1 1899.51  5034.5 1898.37  5052.6 1901.03  5127.3 1901.83
  5169.9  1901.1  5291.6 1902.47  5478.9 1900.17  5889.9 1900.04  6040.2 1897.98
  6080.3 1898.38  6104.8 1900.87  6120.4 1898.51  6150.5 1897.86  6160.5 1898.69
  6170.5 1898.09  6190.6 1900.86  6220.6  1899.8  6401.5 1905.15  6637.9 1907.62
#Mann= 3 ,-1 , 0
  4264.9     .05       0  4995.5     .05       0  5004.6     .05       0
Bank Sta=4995.5,5004.6
XS Rating Curve= 0 ,0
Exp/Cntr=0.3,0.1

Type RM Length L Ch R = 1 ,83537   ,720,720,720
BEGIN DESCRIPTION:
Mapping XS cd2165bb
END DESCRIPTION:
XS GIS Cut Line= 4
      1620649.44      6796378.95      1620579.12      6796847.72
      1620331.73      6797381.58      1620346.41      6798699.99
#Sta/Elev= 30
  4251.4 1906.38  4384.7 1904.62  4512.8 1904.69  4744.7 1902.38    4796 1900.85
    4858  1900.7    4880 1897.64  4916.1 1896.14  4984.8 1896.16  4995.5 1893.48
    4996 1892.98  5004.6 1893.48  5007.7 1894.39  5036.2 1896.26  5156.2 1899.42
  5247.9 1897.85  5360.2 1897.82  5770.3 1893.48  6110.3 1894.58  6120.3 1894.69
  6140.3 1897.14  6150.3 1894.97  6210.3 1895.33  6220.3 1896.61  6240.3 1895.68
  6310.3 1895.54  6380.3 1897.79  6430.3 1902.05  6520.3 1904.71  6632.3 1905.94
#Mann= 3 ,-1 , 0
  4251.4     .05       0  4995.5     .05       0  5004.6     .05       0
Bank Sta=4995.5,5004.6
XS Rating Curve= 0 ,0
Exp/Cntr=0.3,0.1