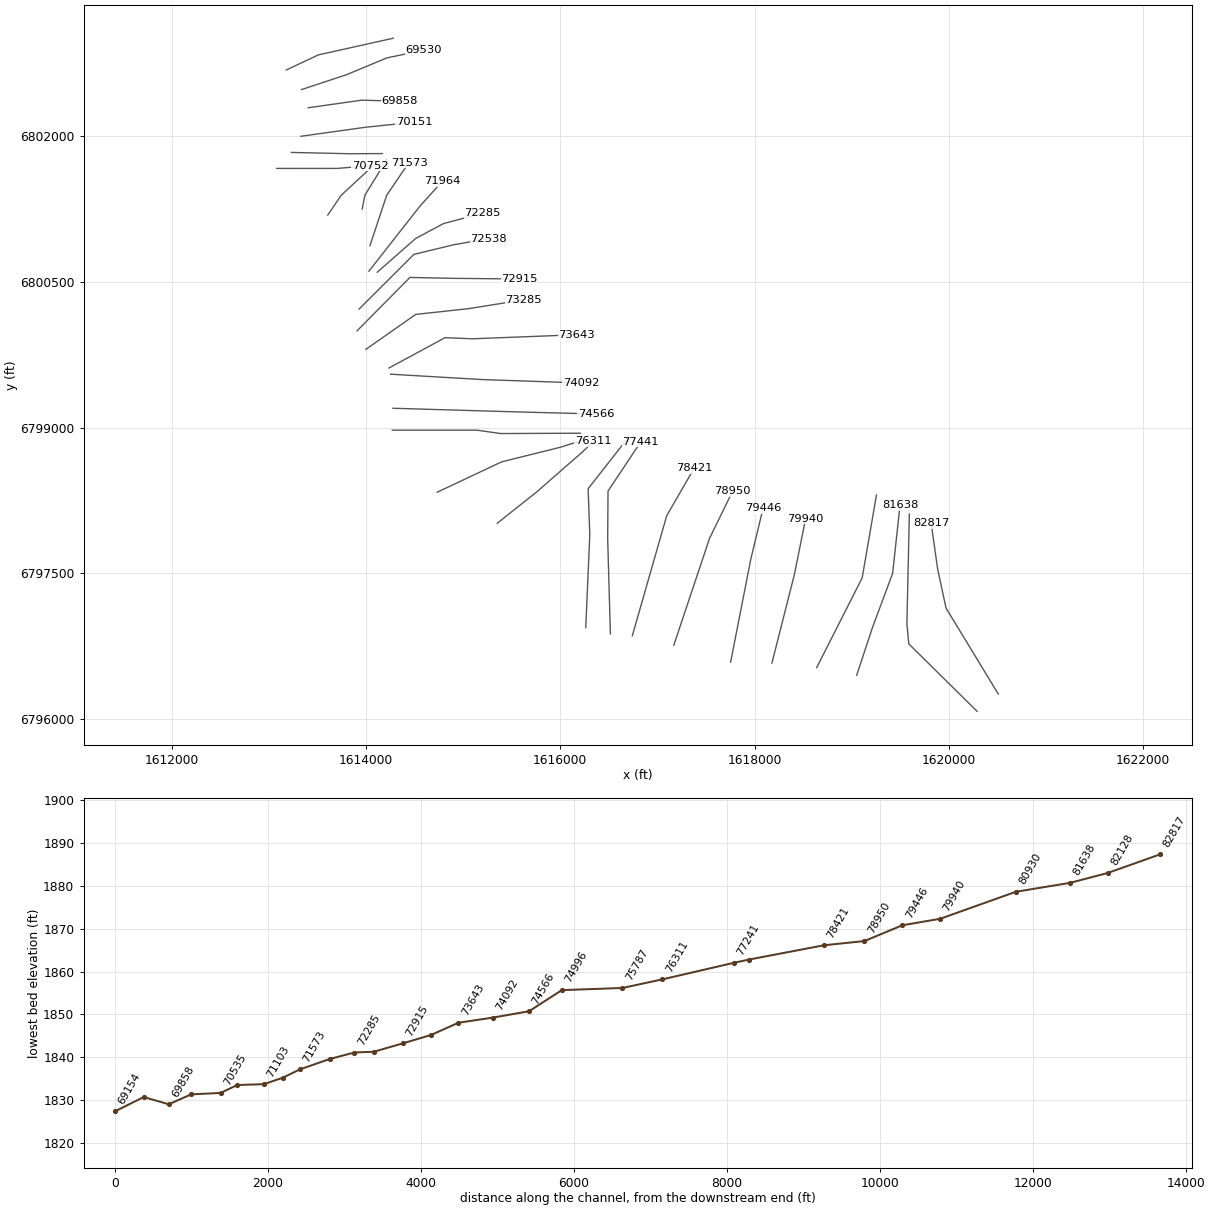
HEC-RAS study Lytle Creek.prj: Lytle Creek Base Level Engineering

--- Lytle Creek.g01 (geometry) --- (continued)

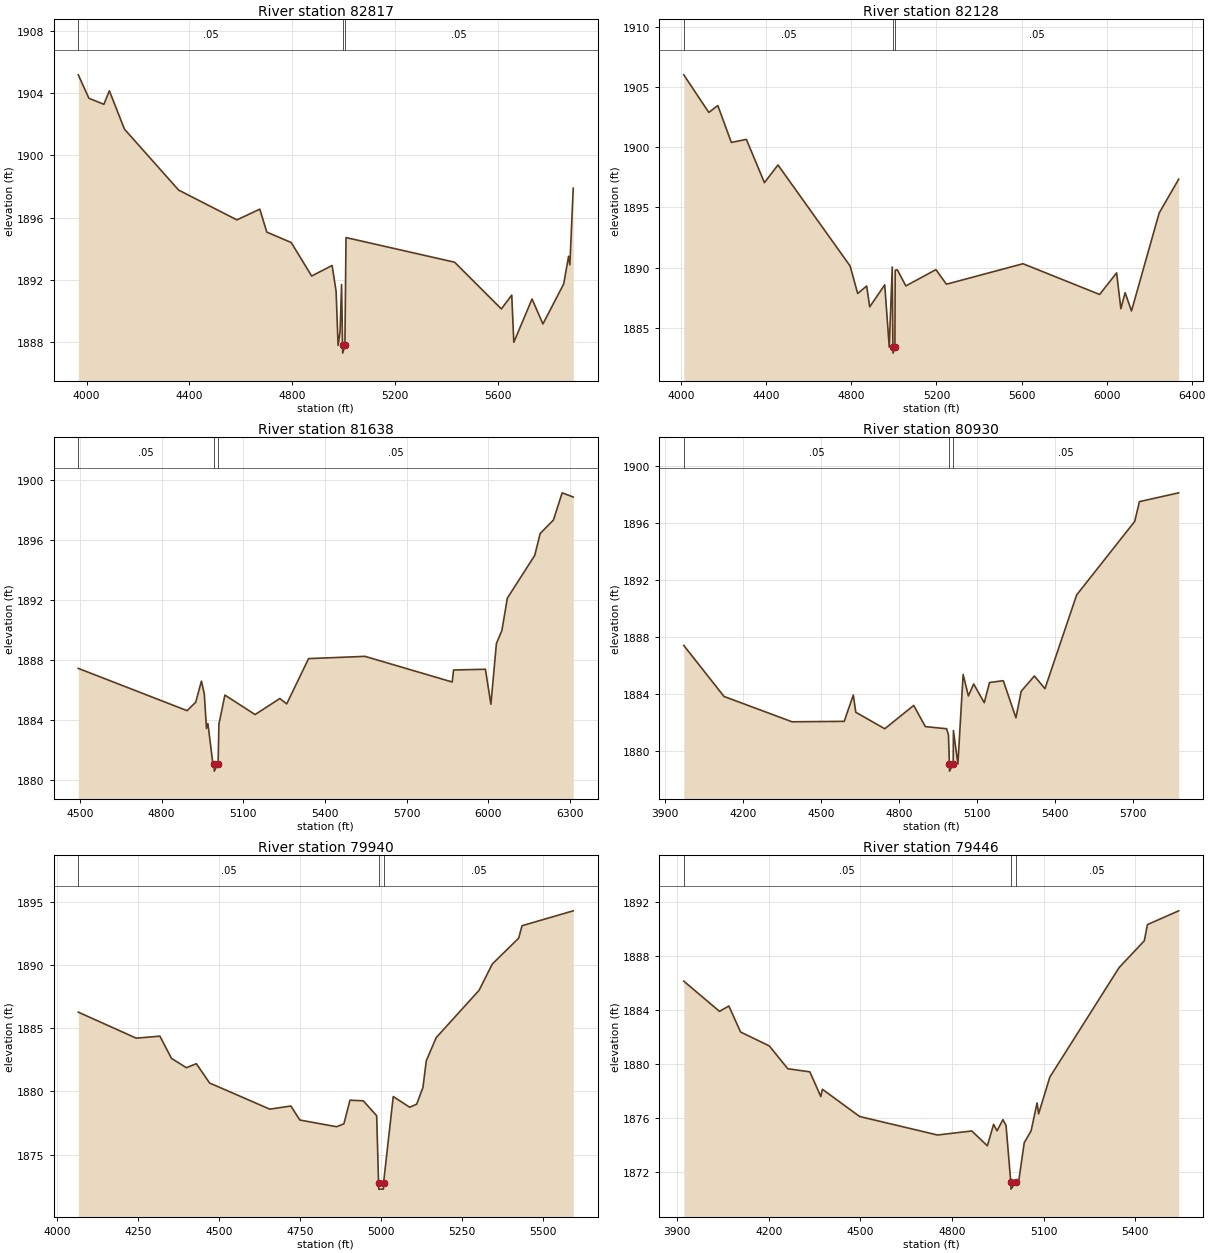
Type RM Length L Ch R = 1 ,82817   ,689,689,689
BEGIN DESCRIPTION:
Lytle Creek 82817.09
END DESCRIPTION:
XS GIS Cut Line= 4
      1620509.65      6796254.65      1619971.46      6797140.06
      1619885.29      6797539.56      1619817.99      6798014.59
#Sta/Elev= 30
  3967.8  1905.2  4009.1 1903.69  4067.3  1903.3  4088.7 1904.17  4147.3  1901.7
    4358 1897.77  4584.6 1895.85  4673.7 1896.54  4700.9 1895.06  4795.9 1894.39
  4875.3 1892.23  4954.8 1892.91  4970.3 1891.25  4978.1 1887.76  4985.7 1888.63
  4991.6 1891.68  4995.5 1887.76    4996 1887.26  5004.6 1887.76  5008.9 1894.71
  5431.3 1893.12    5613 1890.11  5653.4    1891  5661.4 1887.96  5732.3 1890.75
  5774.6 1889.14  5855.4 1891.72  5874.3  1893.5  5879.4 1892.95  5892.4 1897.89
#Mann= 3 ,-1 , 0
  3967.8     .05       0  4995.5     .03       0  5004.6     .05       0
Bank Sta=4995.5,5004.6
XS Rating Curve= 0 ,0
Exp/Cntr=0.3,0.1

Type RM Length L Ch R = 1 ,82128   ,490,490,490
BEGIN DESCRIPTION:
Lytle Creek 82245.587
END DESCRIPTION:
XS GIS Cut Line= 4
      1620290.92      6796077.54      1619587.94      6796771.92
      1619568.37      6796981.88      1619593.81      6798109.92
#Sta/Elev= 30
  4011.9 1906.01  4129.6 1902.89    4172 1903.46  4235.6  1900.4  4306.3 1900.65
  4391.2 1897.06  4454.9 1898.53  4794.2 1890.14  4829.6 1887.86    4872 1888.48
  4886.2 1886.75  4956.9 1888.58  4978.1 1883.41  4992.2 1890.06  4995.4 1883.41
  4995.9 1882.91  5004.6 1883.41  5006.1 1889.79  5016.2 1889.82  5056.3 1888.49
  5197.6 1889.84    5247 1888.63  5607.1 1890.33  5967.2 1887.78  6047.2 1889.57
  6067.2  1886.6  6087.2 1887.93  6117.2 1886.41  6247.3 1894.54  6339.2 1897.35
#Mann= 3 ,-1 , 0
  4011.9     .05       0  4995.4     .03       0  5004.6     .05       0
Bank Sta=4995.4,5004.6
XS Rating Curve= 0 ,0
Exp/Cntr=0.3,0.1

Type RM Length L Ch R = 1 ,81638   ,708,708,708
BEGIN DESCRIPTION:
Lytle Creek 81638.1
END DESCRIPTION:
XS GIS Cut Line= 4
      1619051.48      6796448.62      1619212.08      6796934.75
      1619421.65       6797498.7      1619497.46       6798198.5
#Sta/Elev= 30
  4493.9 1887.47  4893.4 1884.65    4925 1885.21  4946.1 1886.62  4956.6 1885.77
  4964.6 1883.47  4969.9 1883.79  4988.2 1881.12  4992.8 1881.12  4993.3 1880.62
  5007.3 1881.12  5010.3 1883.75  5032.3 1885.69  5143.1 1884.39  5234.1 1885.46
  5259.2  1885.1  5339.6 1888.12  5546.7 1888.27    5867 1886.56    5872 1887.36
    5989 1887.41  6009.1 1885.08  6029.3 1889.12  6049.4 1889.99  6069.5 1892.15
  6170.1    1895  6190.2 1896.46  6238.8 1897.36  6270.7 1899.17  6311.4 1898.89
#Mann= 3 ,-1 , 0
  4493.9     .05       0  4992.8     .05       0  5007.3     .05       0
Bank Sta=4992.8,5007.3
XS Rating Curve= 0 ,0
Exp/Cntr=0.3,0.1

Type RM Length L Ch R = 1 ,80930   ,990,990,990
BEGIN DESCRIPTION:
Lytle Creek 80930.44
END DESCRIPTION:
XS GIS Cut Line= 3
      1618639.17      6796526.78      1619107.91      6797451.25
      1619255.19      6798304.62
#Sta/Elev= 30
  3971.7 1887.39  4126.4  1883.8  4387.9 1882.02  4588.4 1882.05  4623.4  1883.9
  4632.9 1882.69  4744.3 1881.53  4855.6 1883.17  4900.2 1881.68  4982.1 1881.53
  4989.2 1881.09  4992.8 1879.05  4993.3 1878.55  5007.3 1879.05  5008.2 1881.41
  5025.4 1879.05  5045.5 1885.35  5065.8 1883.84  5086.1 1884.68  5126.7 1883.36
    5147 1884.78  5199.9 1884.91  5248.5  1882.3  5268.8 1884.17  5319.5 1885.24
  5360.1 1884.35  5481.9 1890.94  5705.1 1896.11  5723.2  1897.5  5874.2 1898.12
#Mann= 3 ,-1 , 0
  3971.7     .05       0  4992.8     .05       0  5007.3     .05       0
Bank Sta=4992.8,5007.3
XS Rating Curve= 0 ,0
Exp/Cntr=0.3,0.1

Type RM Length L Ch R = 1 ,79940   ,494,494,494
BEGIN DESCRIPTION:
Lytle Creek 79940.42
END DESCRIPTION:
XS GIS Cut Line= 3
      1618179.08      6796574.48      1618409.12      6797481.63
      1618526.28      6798063.08
#Sta/Elev= 30
  4064.6 1886.27  4243.6 1884.21  4316.7 1884.37  4352.5 1882.61  4398.7 1881.87
  4429.3 1882.19  4470.3 1880.66  4656.3 1878.59  4721.3 1878.84  4749.1 1877.73
  4862.6  1877.2  4885.2 1877.43  4903.9  1879.3  4945.1 1879.25  4986.4 1878.07
  4992.3 1872.76  4992.8 1872.26  5007.2 1872.26  5007.7 1872.76  5037.6 1879.59
  5088.6 1878.74  5110.1 1878.99  5129.4 1880.31  5139.6 1882.41  5170.2 1884.25
  5302.8    1888  5343.6 1890.08  5425.2 1892.13  5435.4 1893.11  5593.6 1894.29
#Mann= 3 ,-1 , 0
  4064.6     .05       0  4992.3     .05       0  5007.7     .05       0
Bank Sta=4992.3,5007.7
XS Rating Curve= 0 ,0
Exp/Cntr=0.3,0.1

Type RM Length L Ch R = 1 ,79446   ,496,496,496
BEGIN DESCRIPTION:
Lytle Creek 79445.51
END DESCRIPTION:
XS GIS Cut Line= 3
      1617753.75      6796583.23      1617962.08      6797646.56
      1618087.95      6798167.42
#Sta/Elev= 30
  3922.2 1886.17  4039.2 1883.93  4069.7 1884.33  4108.1  1882.4  4202.2 1881.37
  4262.5 1879.68  4334.7 1879.45  4370.6 1877.62  4375.7 1878.16  4497.7 1876.14
  4752.5 1874.77  4864.6 1875.07  4915.5 1873.97  4935.9 1875.56  4947.1 1875.08
  4966.5 1875.91  4976.6 1875.48  4992.3 1871.26  4992.8 1870.76  5007.7 1871.26
  5017.5 1871.26  5036.2  1874.2  5058.7 1875.08  5078.1 1877.15  5083.2 1876.34
  5119.9 1879.06  5346.7 1887.18    5429 1889.16  5439.3 1890.36  5541.6 1891.38
#Mann= 3 ,-1 , 0
  3922.2     .05       0  4992.3     .03       0  5007.7     .05       0
Bank Sta=4992.3,5007.7
XS Rating Curve= 0 ,0
Exp/Cntr=0.3,0.1

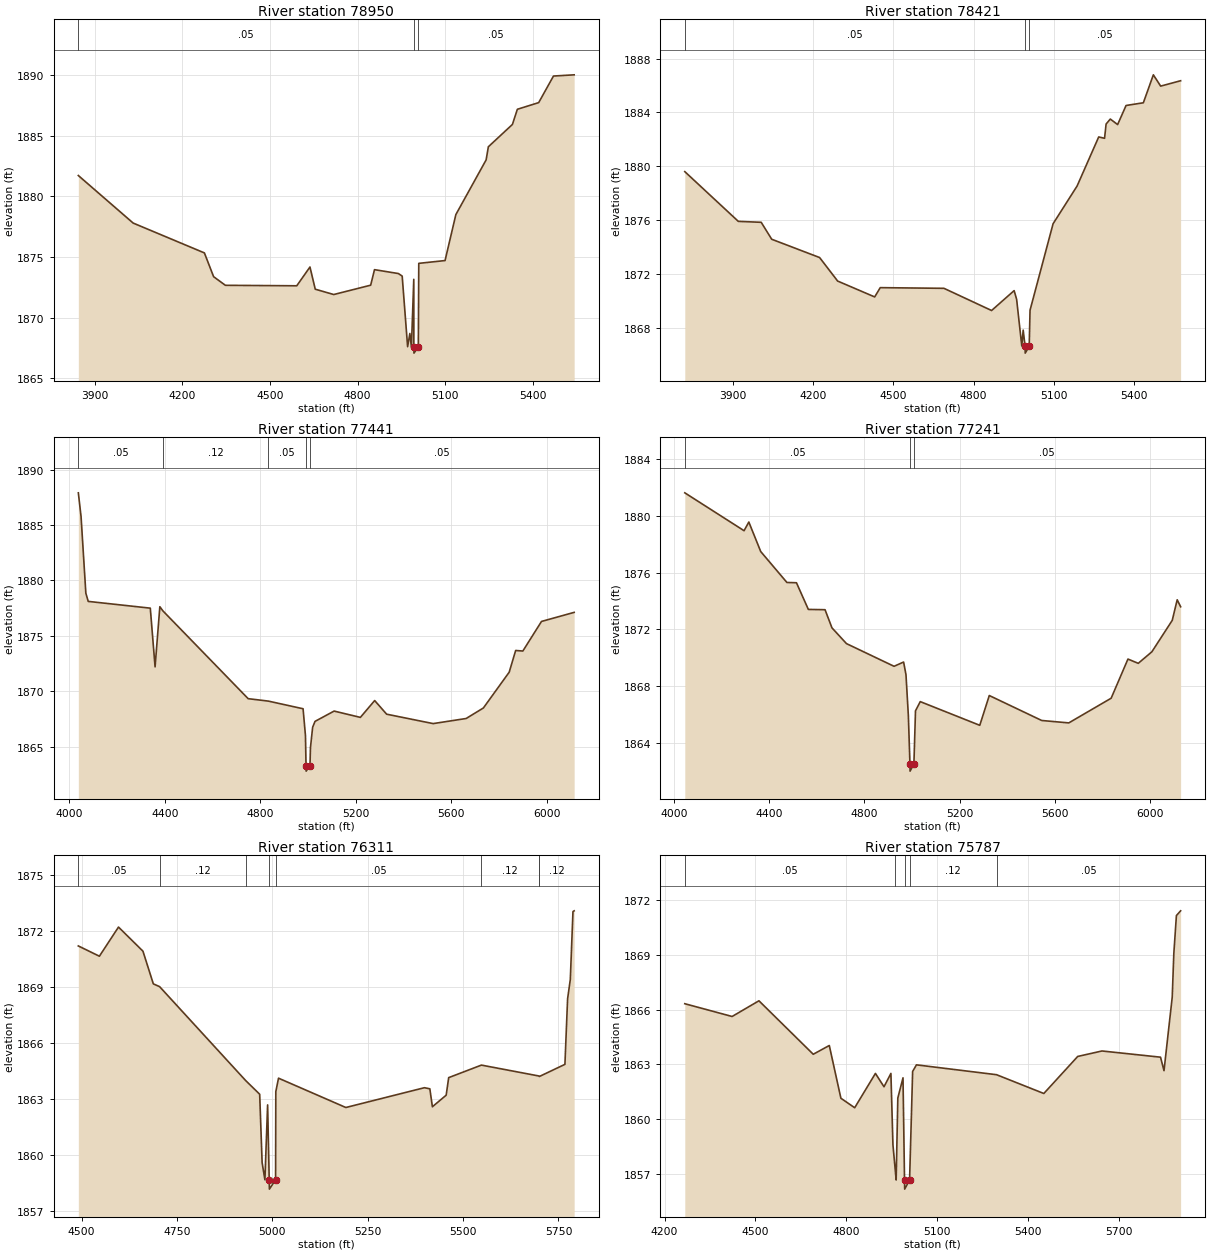
Type RM Length L Ch R = 1 ,78950   ,529,529,529
BEGIN DESCRIPTION:
Lytle Creek 78950.19
END DESCRIPTION:
XS GIS Cut Line= 3
       1617169.2      6796758.57      1617537.25      6797859.23
      1617773.38      6798341.91
#Sta/Elev= 30
  3843.4 1881.72  4031.2  1877.8  4275.1 1875.34  4306.7 1873.38    4347 1872.67
  4591.4 1872.63  4636.6 1874.18  4654.7 1872.35    4718 1871.91  4844.5 1872.68
  4857.6 1873.96  4939.4 1873.64  4952.4 1873.43    4971 1867.61  4978.7  1868.7
    4984 1867.58  4992.1 1873.16  4992.3 1867.58  4992.8 1867.08  5007.7 1867.58
  5009.2 1874.48  5099.2 1874.71  5136.2  1878.5  5239.9 1883.01  5247.5 1884.09
  5329.9 1885.93  5346.8 1887.18  5419.9 1887.73  5470.5 1889.92  5541.3 1890.02
#Mann= 3 ,-1 , 0
  3843.4     .05       0  4992.3     .05       0  5007.7     .05       0
Bank Sta=4992.3,5007.7
XS Rating Curve= 0 ,0
Exp/Cntr=0.3,0.1

Type RM Length L Ch R = 1 ,78421   ,980,980,980
BEGIN DESCRIPTION:
Lytle Creek 78421.47
END DESCRIPTION:
XS GIS Cut Line= 3
       1616742.1      6796855.73      1617096.28      6798091.87
      1617379.93      6798583.08
#Sta/Elev= 30
  3720.5  1879.6  3920.5  1875.9  4006.1 1875.83  4045.3 1874.57  4224.3 1873.21
  4291.8 1871.46  4430.2 1870.28    4451 1870.97  4689.1 1870.92  4867.1 1869.27
  4951.4 1870.75  4960.7  1870.1    4980 1866.63  4985.2 1867.81  4992.3  1866.6
  4992.8  1866.1  5007.7  1866.6  5010.8 1869.29  5096.9 1875.72  5186.7 1878.53
  5267.5 1882.18  5289.3 1882.08  5295.1 1883.14  5310.8 1883.51  5338.2  1883.1
  5369.7 1884.52  5434.3 1884.72  5471.7  1886.8    5499 1885.96  5573.6 1886.36
#Mann= 3 ,-1 , 0
  3720.5     .05       0  4992.3     .03       0  5007.7     .05       0
Bank Sta=4992.3,5007.7
XS Rating Curve= 0 ,0
Exp/Cntr=0.3,0.1

Type RM Length L Ch R = 1 ,77441   ,200,200,200
BEGIN DESCRIPTION:
Lytle Creek 77441.34
END DESCRIPTION:
XS GIS Cut Line= 4
      1616516.42      6796876.55      1616488.64      6797848.82
      1616492.11      6798345.34       1616828.9      6798852.26
#Sta/Elev= 30
  4037.5  1887.9    4049 1885.74    4069 1878.84    4079  1878.1  4339.1 1877.49
  4359.1 1872.19  4379.1 1877.62  4392.1 1877.24  4749.2 1869.32  4833.7  1869.1
  4979.3 1868.41  4989.3 1865.99  4991.7 1863.28  4992.2 1862.78  5008.3 1863.28
  5010.2 1864.89  5019.4 1866.74  5029.4 1867.27  5109.4  1868.2  5219.4 1867.63
  5279.4 1869.15  5329.4 1867.92  5524.4 1867.07  5662.7 1867.53  5734.9 1868.48
  5843.1 1871.71  5870.2 1873.67  5900.3 1873.62  5978.4 1876.29  6115.3 1877.11
#Mann= 5 ,-1 , 0
  4037.5     .05       0  4392.1     .12       0  4833.7     .05       0
  4991.7     .05       0  5008.3     .05       0
Bank Sta=4991.7,5008.3
XS Rating Curve= 0 ,0
Exp/Cntr=0.3,0.1

Type RM Length L Ch R = 1 ,77241   ,930,930,930
BEGIN DESCRIPTION:
Lytle Creek 77240.61
END DESCRIPTION:
XS GIS Cut Line= 4
      1616262.94      6796939.09      1616304.61      6797897.43
      1616287.25      6798369.65      1616689.77      6798883.22
#Sta/Elev= 30
  4045.2 1881.63  4294.3 1878.96  4314.4 1879.57  4364.4 1877.49  4474.5 1875.31
  4514.6 1875.29  4564.6 1873.41  4634.7 1873.39  4663.9 1872.11  4724.8    1871
  4924.9  1869.4    4965  1869.7    4975 1868.81    4985 1865.92  4991.7 1862.51
  4992.2 1862.01  5008.3 1862.51    5015 1866.26    5035 1866.91  5285.2 1865.24
  5325.2 1867.34  5545.5 1865.58  5659.4 1865.41  5837.5 1867.15  5908.1 1869.91
  5951.4 1869.61  6008.5 1870.42  6094.3 1872.64  6115.1 1874.09  6129.5  1873.6
#Mann= 3 ,-1 , 0
  4045.2     .05       0  4991.7     .05       0  5008.3     .05       0
Bank Sta=4991.7,5008.3
XS Rating Curve= 0 ,0
Exp/Cntr=0.3,0.1

Type RM Length L Ch R = 1 ,76311   ,524,524,524
BEGIN DESCRIPTION:
Lytle Creek 76311.12
END DESCRIPTION:
XS GIS Cut Line= 4
      1615351.78      6798014.21      1615754.55      6798333.65
      1616234.43      6798753.15      1616340.62      6798856.73
#Sta/Elev= 30
  4491.3  1871.2  4546.5 1870.65  4596.6 1872.21  4660.7 1870.92  4687.9 1869.17
  4704.4 1869.02  4930.1 1863.99  4966.7 1863.26  4973.1  1859.6  4980.4 1858.68
  4987.5 1862.69  4991.7 1858.68  4992.2 1858.18  5008.4 1858.68    5009  1863.4
  5016.1 1864.12  5192.6 1862.55  5398.6 1863.61  5412.8 1863.55  5419.5 1862.59
  5455.6 1863.21  5462.2 1864.15    5548 1864.82    5698 1864.24  5699.9 1864.21
  5766.9 1864.86  5773.9 1868.37    5781  1869.4    5788 1873.04  5791.1 1873.08
#Mann= 8 ,-1 , 0
  4491.3     .05       0  4704.4     .12       0  4930.1     .05       0
  4991.7     .05       0  5008.4     .05       0    5548     .12       0
    5698     .05       0  5699.9     .12       0
Bank Sta=4991.7,5008.4
XS Rating Curve= 0 ,0
Exp/Cntr=0.3,0.1

Type RM Length L Ch R = 1 ,75787   ,791,791,791
BEGIN DESCRIPTION:
Lytle Creek 75787.47
END DESCRIPTION:
XS GIS Cut Line= 4
      1614733.76      6798333.67      1615396.91      6798646.15
      1615999.72      6798796.15      1616268.24      6798880.73
#Sta/Elev= 30
  4266.8 1866.33  4422.9 1865.63  4511.4 1866.49  4690.6 1863.56  4743.5 1864.04
  4781.8 1861.15  4827.3 1860.63  4895.7 1862.51    4924 1861.78  4946.8 1862.51
  4953.5  1858.6  4961.6 1857.13  4964.1 1856.67  4969.6 1861.16  4986.7 1862.27
  4991.7 1856.67  4992.2 1856.17  5008.4 1856.67  5018.5 1862.62  5031.1 1862.98
  5295.3 1862.44  5451.3 1861.41  5563.1 1863.44  5643.1 1863.74  5836.3  1863.4
  5847.8 1862.66  5874.9 1866.69  5880.2 1869.09  5888.7 1871.16  5902.6 1871.42
#Mann= 5 ,-1 , 0
  4266.8     .05       0  4961.6     .12       0  4991.7     .07       0
  5008.4     .12       0  5295.3     .05       0
Bank Sta=4991.7,5008.4
XS Rating Curve= 0 ,0
Exp/Cntr=0.3,0.1

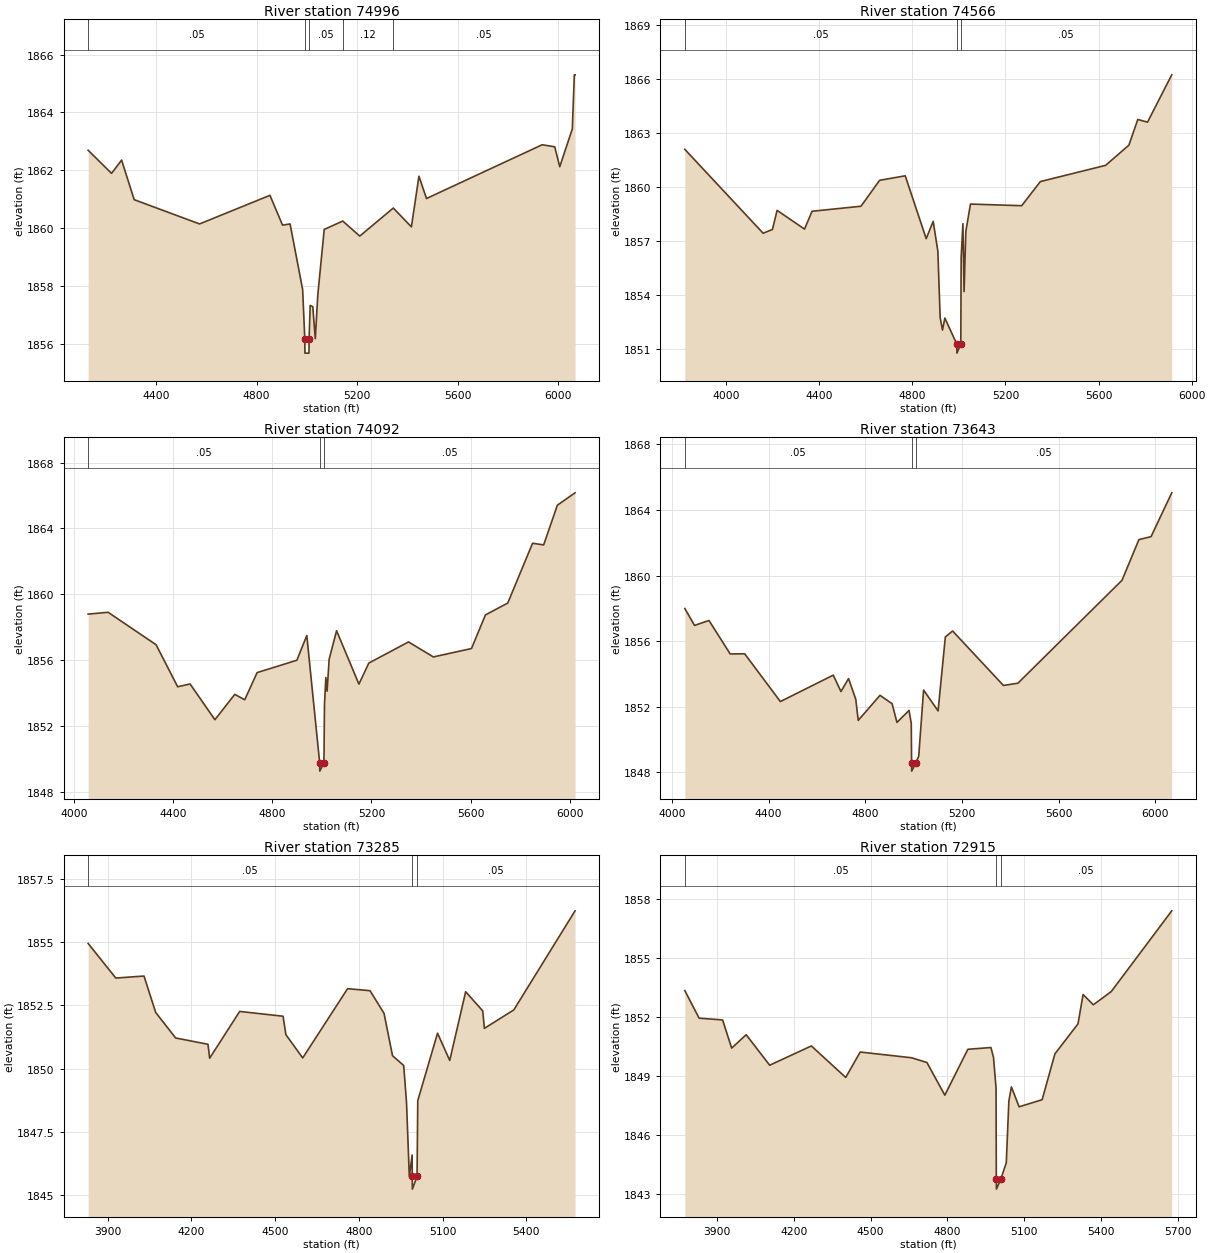
Type RM Length L Ch R = 1 ,74996   ,430,430,430
BEGIN DESCRIPTION:
Lytle Creek 74996.12
END DESCRIPTION:
XS GIS Cut Line= 4
      1614271.89      6798972.54      1615143.44      6798972.54
       1615386.5      6798937.82      1616205.92      6798941.29
#Sta/Elev= 30
  4129.9 1862.69    4223 1861.89    4263 1862.35    4313 1860.98    4573 1860.14
    4853 1861.13    4903  1860.1    4933 1860.14    4983 1857.87  4991.5 1856.17
    4992 1855.67  5008.1 1855.67  5008.6 1856.17  5013.1 1857.32  5023.2 1857.28
  5033.3 1856.17  5043.4  1857.7  5068.8 1859.95  5142.5 1860.24  5210.2 1859.72
  5343.5 1860.69  5415.5 1860.04  5445.5 1861.79  5475.5 1861.02  5935.5 1862.88
  5985.5 1862.81  6005.5 1862.12  6055.5 1863.43  6063.5  1865.3  6066.4  1865.3
#Mann= 5 ,-1 , 0
  4129.9     .05       0  4991.5     .03       0  5008.6     .05       0
  5142.5     .12       0  5343.5     .05       0
Bank Sta=4991.5,5008.6
XS Rating Curve= 0 ,0
Exp/Cntr=0.3,0.1

Type RM Length L Ch R = 1 ,74566   ,474,474,474
BEGIN DESCRIPTION:
Lytle Creek 74566.15
END DESCRIPTION:
XS GIS Cut Line= 3
      1614278.83      6799198.24      1615455.94      6799163.51
       1616369.1      6799139.21
#Sta/Elev= 30
  3823.4 1862.07  4159.7 1857.41  4199.7 1857.62  4219.7 1858.68  4337.5 1857.64
  4369.8 1858.63  4579.9 1858.91  4659.9 1860.35    4770  1860.6    4860 1857.11
    4890 1858.07    4910 1856.42    4920 1852.72    4930 1852.03  4940.1  1852.7
  4991.4 1851.25  4991.9 1850.75  5008.6 1851.25  5010.1 1856.06  5017.7 1857.94
  5022.7 1854.17  5030.1  1857.5  5050.1 1859.03  5270.2 1858.94  5350.2 1860.28
  5630.3 1861.18  5730.3  1862.3  5768.7 1863.73  5810.4 1863.58  5914.5 1866.21
#Mann= 3 ,-1 , 0
  3823.4     .05       0  4991.4     .05       0  5008.6     .05       0
Bank Sta=4991.4,5008.6
XS Rating Curve= 0 ,0
Exp/Cntr=0.3,0.1

Type RM Length L Ch R = 1 ,74092   ,449,449,449
BEGIN DESCRIPTION:
Lytle Creek 74091.63
END DESCRIPTION:
XS GIS Cut Line= 3
      1614254.53      6799548.93      1615202.47      6799493.38
      1616216.31      6799458.66
#Sta/Elev= 30
  4057.5  1858.8  4138.1 1858.91  4331.6 1856.94  4418.6 1854.39  4468.7 1854.56
  4568.8 1852.39    4649 1853.93  4689.1  1853.6  4739.1 1855.25  4899.4    1856
  4939.5  1857.5  4991.4 1849.77  4991.9 1849.27  5008.6 1849.77  5010.8 1853.32
  5016.3 1854.95  5021.3 1854.12  5029.6 1856.06  5059.6 1857.79  5149.7 1854.55
  5189.7 1855.83  5349.8 1857.11  5449.9  1856.2  5603.7 1856.71    5660 1858.75
    5750 1859.47  5850.1  1863.1  5894.8    1863  5950.1 1865.41  6021.5 1866.16
#Mann= 3 ,-1 , 0
  4057.5     .05       0  4991.4     .05       0  5008.6     .05       0
Bank Sta=4991.4,5008.6
XS Rating Curve= 0 ,0
Exp/Cntr=0.3,0.1

Type RM Length L Ch R = 1 ,73643   ,358,358,358
BEGIN DESCRIPTION:
Lytle Creek 73642.97
END DESCRIPTION:
XS GIS Cut Line= 4
      1614237.08      6799612.54      1614815.28      6799925.26
       1615098.3      6799913.51      1616170.57      6799955.16
#Sta/Elev= 30
  4053.6 1857.99  4093.8 1856.96  4153.6 1857.26  4241.3 1855.22  4301.2 1855.23
  4448.7 1852.32  4667.5 1853.93  4699.3 1852.93  4730.7 1853.72  4760.6 1852.46
  4770.7 1851.17  4860.8  1852.7  4910.8 1852.19  4930.9 1851.05  4980.9 1851.78
  4990.1 1850.98  4991.4 1848.58  4991.9 1848.08  5008.6 1848.58  5020.9 1848.99
    5041 1853.02    5101 1851.75    5131 1856.26    5161 1856.62  5371.2  1853.3
  5431.2 1853.44  5861.6 1859.71  5931.6 1862.19  5981.7 1862.37  6067.3 1865.04
#Mann= 3 ,-1 , 0
  4053.6     .05       0  4991.4     .05       0  5008.6     .05       0
Bank Sta=4991.4,5008.6
XS Rating Curve= 0 ,0
Exp/Cntr=0.3,0.1

Type RM Length L Ch R = 1 ,73285   ,370,370,370
BEGIN DESCRIPTION:
Lytle Creek 73285.23
END DESCRIPTION:
XS GIS Cut Line= 4
      1614000.02       6799805.2      1614513.08       6800164.6
      1615053.07      6800223.29      1615621.88      6800314.13
#Sta/Elev= 30
  3829.5 1854.95  3928.7 1853.58  4029.8 1853.66  4071.7 1852.22  4143.2 1851.21
  4259.1 1850.96  4265.2 1850.41  4372.8 1852.26  4528.3 1852.07  4538.5 1851.34
  4598.7 1850.42  4759.6 1853.16  4840.1 1853.08  4890.4 1852.18  4920.6 1850.51
  4960.8 1850.12  4970.9 1848.65  4980.9 1845.73    4991 1846.58  4991.4 1845.73
  4991.9 1845.23  5008.6 1845.73  5011.2 1848.73  5082.1  1851.4  5125.8 1850.32
  5182.9 1853.04  5244.1 1852.28    5250 1851.59  5355.5 1852.32  5575.1 1856.24
#Mann= 3 ,-1 , 0
  3829.5     .05       0  4991.4     .05       0  5008.6     .05       0
Bank Sta=4991.4,5008.6
XS Rating Curve= 0 ,0
Exp/Cntr=0.3,0.1

Type RM Length L Ch R = 1 ,72915   ,377,377,377
BEGIN DESCRIPTION:
Lytle Creek 72915.39
END DESCRIPTION:
XS GIS Cut Line= 4
      1613908.88      6799995.29      1614453.08      6800545.17
      1614901.16      6800535.79      1615581.31       6800529.3
#Sta/Elev= 30
  3774.6 1853.35  3830.4 1851.95  3922.2 1851.86  3957.6 1850.43  4014.2 1851.11
  4106.1 1849.56  4268.8 1850.54  4403.1 1848.94  4459.7 1850.23  4660.2 1849.94
  4720.2  1849.7  4790.2 1848.04  4880.2 1850.37  4970.3 1850.46  4980.3 1849.96
  4990.3  1848.4  4991.3 1843.77  4991.8 1843.27  5008.7 1843.77  5030.3 1844.61
  5040.3 1847.74  5050.3 1848.46  5080.3 1847.45  5170.3 1847.81  5220.3 1850.14
  5310.3 1851.66  5330.3 1853.15  5370.3 1852.63  5440.3  1853.3  5676.6  1857.4
#Mann= 3 ,-1 , 0
  3774.6     .05       0  4991.3     .05       0  5008.7     .05       0
Bank Sta=4991.3,5008.7
XS Rating Curve= 0 ,0
Exp/Cntr=0.3,0.1

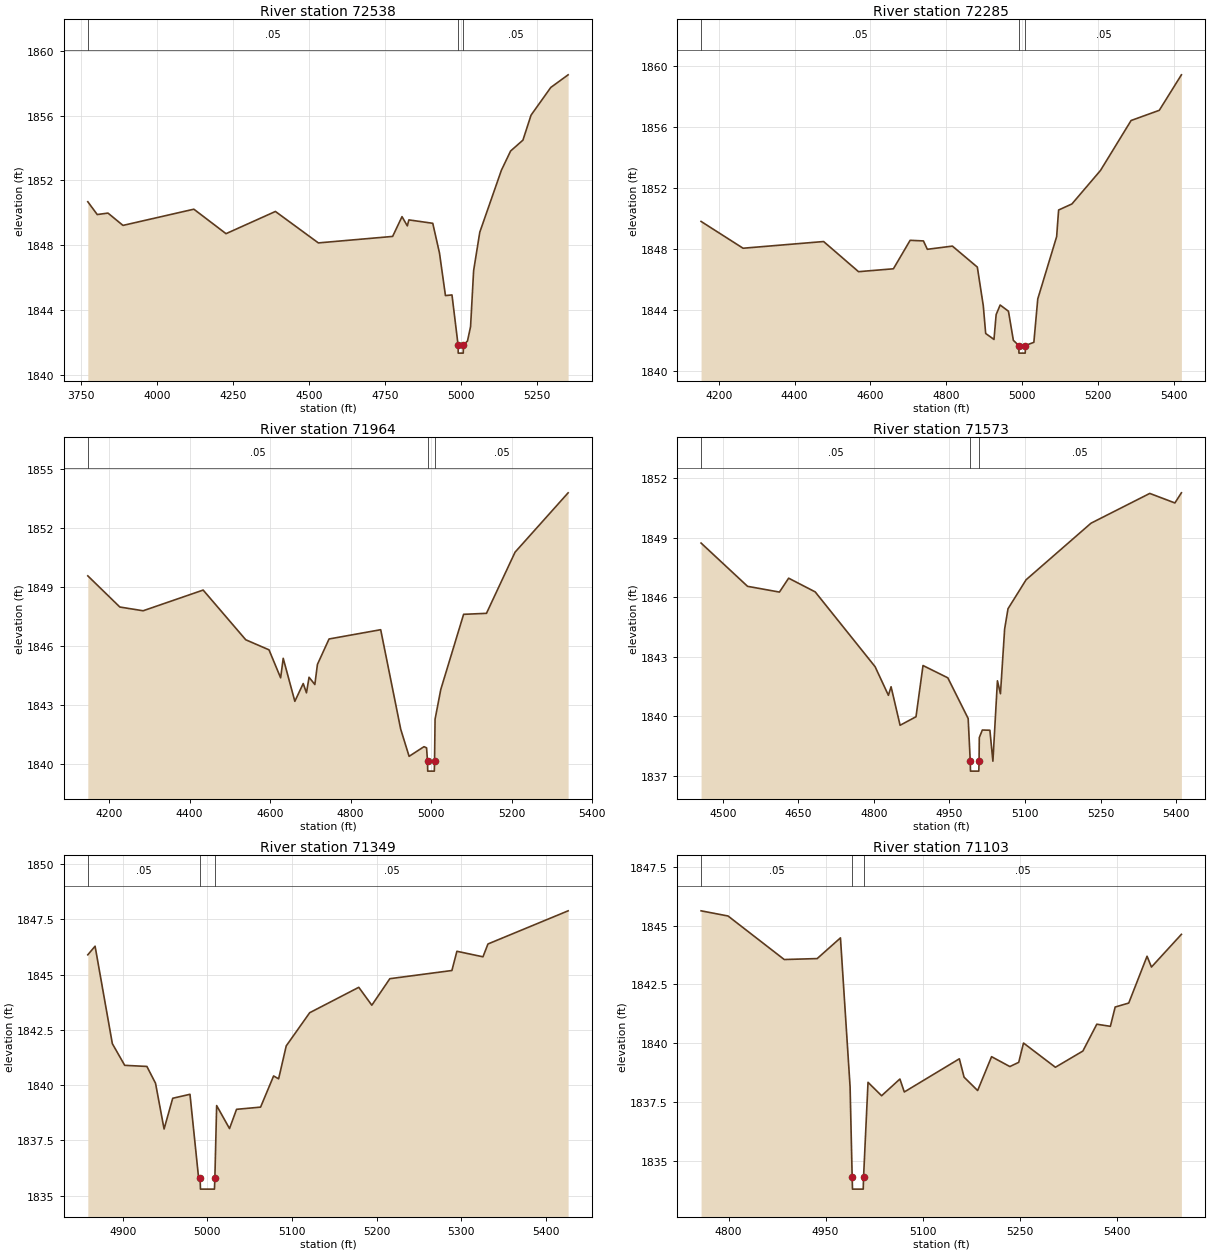
Type RM Length L Ch R = 1 ,72538   ,253,253,253
BEGIN DESCRIPTION:
Lytle Creek 72537.93
END DESCRIPTION:
XS GIS Cut Line= 4
      1613929.77      6800219.31      1614493.79      6800782.59
      1614909.84      6800883.02      1615261.76      6800943.47
#Sta/Elev= 30
  3771.6 1850.68  3802.7 1849.89    3838 1849.98  3887.5 1849.22  4120.9 1850.22
  4226.9 1848.71  4389.6 1850.08    4531 1848.14  4775.7 1848.54  4806.6 1849.76
  4824.1 1849.19  4829.2 1849.56  4907.9 1849.35    4930 1847.52  4949.7 1844.89
  4971.2 1844.93  4991.3 1841.84  4991.8 1841.34  5008.3 1841.34  5008.8 1841.84
  5022.3 1842.09  5032.4 1842.97  5042.5 1846.43  5062.8  1848.8  5133.9 1852.62
  5164.3 1853.81  5204.9 1854.48  5231.6 1856.02  5296.6 1857.73  5353.8 1858.51
#Mann= 3 ,-1 , 0
  3771.6     .05       0  4991.3     .05       0  5008.8     .05       0
Bank Sta=4991.3,5008.8
XS Rating Curve= 0 ,0
Exp/Cntr=0.3,0.1

Type RM Length L Ch R = 1 ,72285   ,321,321,321
BEGIN DESCRIPTION:
Lytle Creek 72285.29
END DESCRIPTION:
XS GIS Cut Line= 4
      1614117.25       6800599.5      1614512.28      6800946.47
      1614799.16      6801100.03      1615201.37      6801205.99
#Sta/Elev= 30
  4153.2 1849.81    4264 1848.05  4476.5 1848.49  4568.6 1846.51  4660.6  1846.7
  4704.7 1848.57  4739.8 1848.53  4750.1 1847.98  4816.2 1848.19    4882 1846.81
  4897.6 1844.29    4904 1842.45  4925.9 1842.06  4931.6 1843.69  4942.2 1844.32
  4964.1 1843.91    4977    1842  4991.3 1841.66  4991.8 1841.16  5008.3 1841.16
  5008.8 1841.66  5031.1 1841.87  5041.4 1844.72  5091.2 1848.81  5096.4 1850.56
  5131.6 1850.96  5206.9 1853.16  5287.6 1856.44    5362 1857.11  5420.3 1859.44
#Mann= 3 ,-1 , 0
  4153.2     .05       0  4991.3     .05       0  5008.8     .05       0
Bank Sta=4991.3,5008.8
XS Rating Curve= 0 ,0
Exp/Cntr=0.3,0.1

Type RM Length L Ch R = 1 ,71964   ,391,391,391
BEGIN DESCRIPTION:
Lytle Creek 71964.43
END DESCRIPTION:
XS GIS Cut Line= 3
      1614031.29      6800609.89      1614557.26      6801280.77
       1614785.9      6801533.66
#Sta/Elev= 30
  4147.3 1849.56  4226.9 1847.98  4284.7 1847.79  4433.9 1848.84  4539.7 1846.32
  4597.5 1845.81  4626.4 1844.39  4632.8 1845.38  4661.7  1843.2  4682.5  1844.1
  4690.6 1843.63    4697 1844.42  4711.4 1844.05  4717.8 1845.07  4746.7 1846.36
    4875 1846.83  4924.8 1841.78  4945.6 1840.41  4982.6  1840.9    4989 1840.84
  4991.3 1840.16  4991.8 1839.66  5008.3 1839.66  5008.8 1840.16  5010.1 1842.29
  5024.3  1843.8    5081 1847.61  5137.8 1847.66  5208.8 1850.76  5340.7 1853.77
#Mann= 3 ,-1 , 0
  4147.3     .05       0  4991.3     .05       0  5008.8     .05       0
Bank Sta=4991.3,5008.8
XS Rating Curve= 0 ,0
Exp/Cntr=0.3,0.1

Type RM Length L Ch R = 1 ,71573   ,224,224,224
BEGIN DESCRIPTION:
Lytle Creek 71572.9
END DESCRIPTION:
XS GIS Cut Line= 3
      1614041.73      6800872.93      1614213.51      6801390.14
      1614442.68      6801728.68
#Sta/Elev= 30
  4456.8 1848.73  4549.1 1846.55  4612.4 1846.26  4630.7 1846.96  4683.4 1846.27
  4802.4  1842.5  4828.8 1841.06  4834.1 1841.49    4852 1839.55  4883.6 1839.98
  4897.5 1842.56  4946.8 1841.94  4987.2 1839.89  4991.3 1837.74  4991.8 1837.24
  5008.3 1837.24  5008.8 1837.74  5009.3 1838.93  5015.3 1839.31  5030.3  1839.3
  5036.3 1837.74  5045.3 1841.79  5051.3 1841.14  5059.6  1844.4  5066.3 1845.42
  5102.2 1846.88  5231.1 1849.73  5347.8 1851.23  5397.7 1850.75  5410.6 1851.26
#Mann= 3 ,-1 , 0
  4456.8     .05       0  4991.3     .05       0  5008.8     .05       0
Bank Sta=4991.3,5008.8
XS Rating Curve= 0 ,0
Exp/Cntr=0.3,0.1

Type RM Length L Ch R = 1 ,71349   ,246,246,246
BEGIN DESCRIPTION:
Lytle Creek 71348.67
END DESCRIPTION:
XS GIS Cut Line= 3
      1613961.77      6801249.52      1613989.55      6801391.88
      1614210.91      6801751.58
#Sta/Elev= 30
  4858.7  1845.9  4867.3 1846.29  4887.7 1841.88  4902.3  1840.9  4928.5 1840.85
  4938.7 1840.09  4948.8 1838.02    4959 1839.41  4979.4 1839.59  4989.6  1835.8
  4991.3  1835.8  4991.8  1835.3  5008.3  1835.3  5008.8  1835.8  5010.9 1839.08
  5026.1 1838.04  5034.4 1838.91  5062.8 1839.01  5078.2 1840.42  5084.1 1840.29
  5093.1 1841.78  5120.8 1843.28  5178.8 1844.43  5194.2 1843.62  5215.5 1844.82
  5288.8 1845.19  5294.7 1846.06  5325.5 1845.81  5331.4 1846.39  5426.1 1847.89
#Mann= 3 ,-1 , 0
  4858.7     .05       0  4991.3     .05       0  5008.8     .05       0
Bank Sta=4991.3,5008.8
XS Rating Curve= 0 ,0
Exp/Cntr=0.3,0.1

Type RM Length L Ch R = 1 ,71103   ,351,351,351
BEGIN DESCRIPTION:
Lytle Creek 71103.1
END DESCRIPTION:
XS GIS Cut Line= 3
      1613607.62      6801187.04      1613744.76      6801390.14
      1614109.35      6801728.69
#Sta/Elev= 30
  4757.6 1845.63  4799.3 1845.41  4886.2 1843.56  4937.1  1843.6  4973.1 1844.48
    4988 1838.14  4991.2  1834.3  4991.7  1833.8  5008.3  1833.8  5008.8  1834.3
  5015.7 1838.34  5036.7 1837.77    5065 1838.48  5071.8 1837.93  5156.9 1839.34
  5164.2 1838.56  5185.2 1837.99  5206.7 1839.43    5235 1839.01  5248.7 1839.19
  5256.1 1840.01  5305.4 1838.98  5347.9 1839.67  5369.4 1840.81  5390.4 1840.72
  5397.8 1841.54  5418.8 1841.71  5447.1  1843.7  5453.9 1843.24  5500.2 1844.63
#Mann= 3 ,-1 , 0
  4757.6     .05       0  4991.2     .05       0  5008.8     .05       0
Bank Sta=4991.2,5008.8
XS Rating Curve= 0 ,0
Exp/Cntr=0.3,0.1

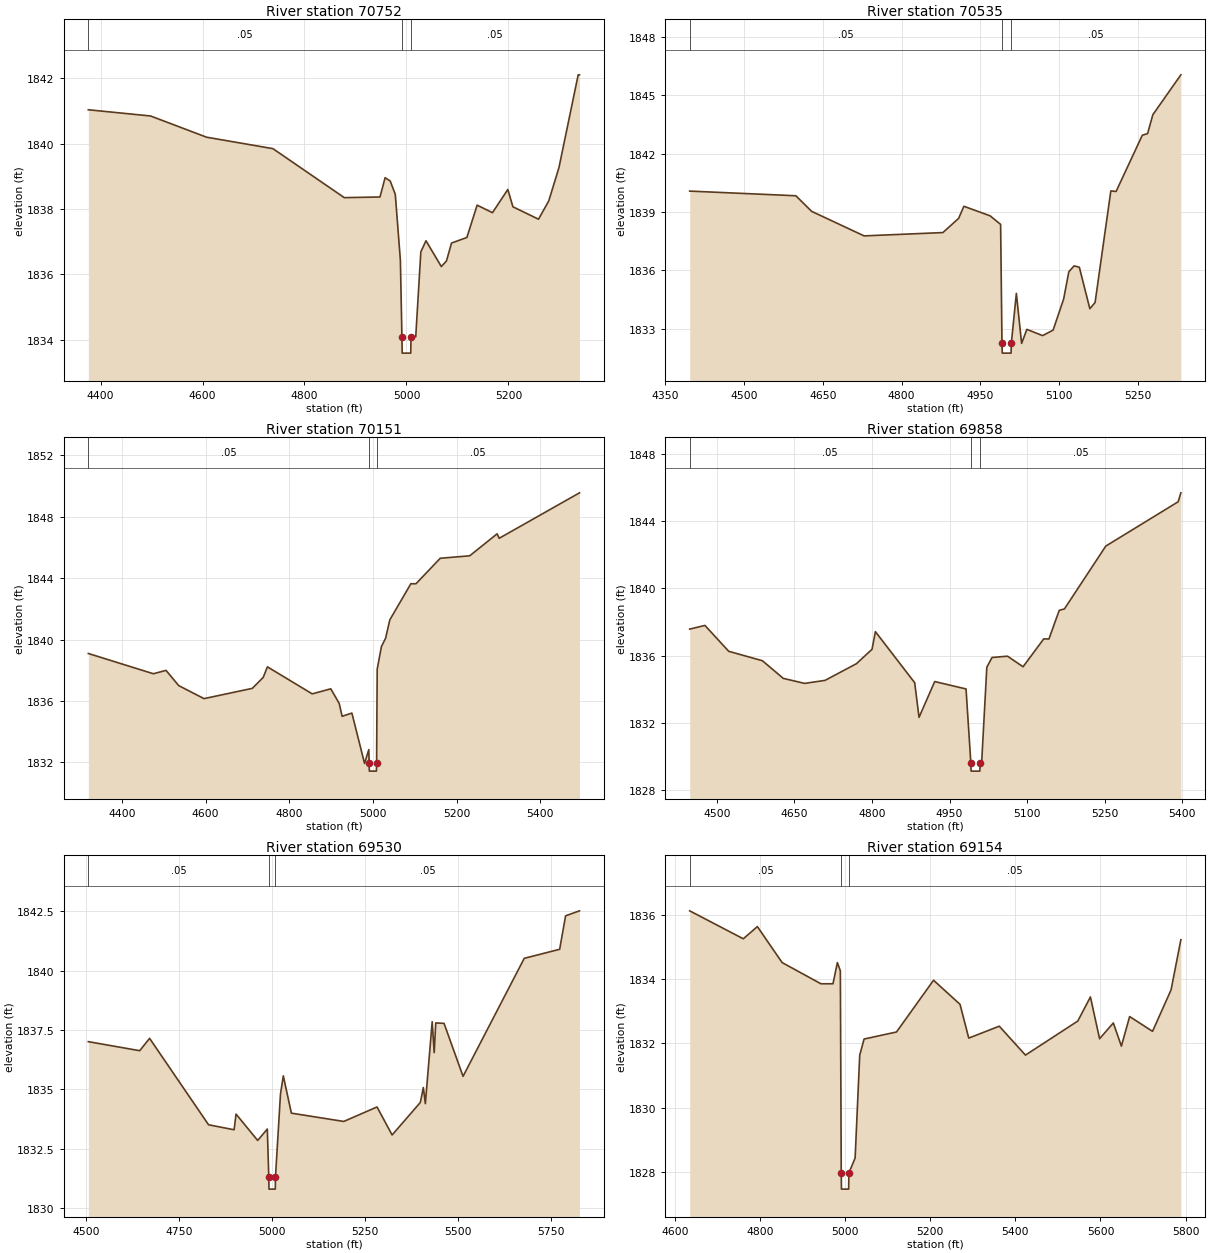
Type RM Length L Ch R = 1 ,70752   ,217,217,217
BEGIN DESCRIPTION:
Lytle Creek 70752.22
END DESCRIPTION:
XS GIS Cut Line= 3
      1613082.96      6801667.64      1613704.83      6801667.92
      1614045.13       6801695.7
#Sta/Elev= 30
  4376.1 1841.04  4498.1 1840.85  4608.1  1840.2  4738.1 1839.85  4878.1 1838.35
  4948.1 1838.37  4958.1 1838.96  4968.1 1838.86  4978.1 1838.45  4988.1 1836.43
  4991.1 1834.09  4991.6 1833.59  5008.4 1833.59  5008.9 1834.09  5018.2 1834.09
  5028.2 1836.69  5038.3 1837.03  5068.4 1836.24  5078.4 1836.41  5088.4 1836.96
  5118.5 1837.13  5138.6 1838.12  5168.7 1837.89  5198.8  1838.6  5208.8 1838.07
    5259 1837.69  5279.1 1838.25  5299.1 1839.27  5336.8 1842.11  5339.4 1842.11
#Mann= 3 ,-1 , 0
  4376.1     .05       0  4991.1     .05       0  5008.9     .05       0
Bank Sta=4991.1,5008.9
XS Rating Curve= 0 ,0
Exp/Cntr=0.3,0.1

Type RM Length L Ch R = 1 ,70535   ,384,384,384
BEGIN DESCRIPTION:
Lytle Creek 70535.33
END DESCRIPTION:
XS GIS Cut Line= 3
      1613232.74      6801832.57      1613838.51      6801818.96
      1614168.38       6801820.7
#Sta/Elev= 30
  4396.1 1840.07  4598.4 1839.83  4628.4 1839.03  4728.4 1837.77  4878.5 1837.94
  4908.5 1838.67  4918.5 1839.29  4968.5  1838.8  4988.5 1838.36  4991.1 1832.25
  4991.6 1831.75  5008.4 1831.75  5008.9 1832.25  5018.5 1834.82  5028.5 1832.25
  5038.5 1832.97  5068.5 1832.65  5088.5 1832.93  5108.5 1834.52  5118.5 1835.93
  5128.5 1836.23  5138.5 1836.16  5158.5 1834.03  5168.5 1834.35  5198.5 1840.08
  5208.5 1840.05  5258.5 1842.94  5268.5 1843.02  5278.5 1843.99  5331.9 1846.04
#Mann= 3 ,-1 , 0
  4396.1     .05       0  4991.1     .05       0  5008.9     .05       0
Bank Sta=4991.1,5008.9
XS Rating Curve= 0 ,0
Exp/Cntr=0.3,0.1

Type RM Length L Ch R = 1 ,70151   ,293,293,293
BEGIN DESCRIPTION:
Lytle Creek 70151.14
END DESCRIPTION:
XS GIS Cut Line= 3
      1613331.13       6801998.9      1614003.04      6802092.66
      1614496.06        6802143.
#Sta/Elev= 30
  4319.9 1839.09  4475.3 1837.77  4505.6 1837.99  4535.8    1837  4596.4 1836.15
  4711.9 1836.82  4737.8 1837.53  4747.9 1838.22    4855 1836.46  4899.3 1836.79
  4919.5 1835.84  4926.5    1835  4949.8 1835.21  4980.1 1831.93  4990.2 1832.83
  4991.1 1831.93  4991.6 1831.43  5008.4 1831.43  5008.9 1831.93  5010.3 1838.06
  5020.4 1839.54  5030.4 1840.08  5040.5 1841.28  5090.8 1843.63    5103 1843.63
  5161.1 1845.29  5231.5 1845.45  5296.9 1846.88  5301.9 1846.59  5493.9 1849.55
#Mann= 3 ,-1 , 0
  4319.9     .05       0  4991.1     .05       0  5008.9     .05       0
Bank Sta=4991.1,5008.9
XS Rating Curve= 0 ,0
Exp/Cntr=0.3,0.1

Type RM Length L Ch R = 1 ,69858   ,328,328,328
BEGIN DESCRIPTION:
Lytle Creek 69858.41
END DESCRIPTION:
XS GIS Cut Line= 3
       1613405.8      6802292.31      1613956.16      6802370.44
      1614350.14      6802360.02
#Sta/Elev= 30
  4447.3 1837.57  4476.8 1837.79  4522.8 1836.25  4587.9 1835.69  4628.3 1834.64
  4669.7 1834.34  4709.1 1834.52  4769.7 1835.51    4800 1836.37  4806.5 1837.42
  4882.5 1834.38  4890.9 1832.32  4921.2 1834.45  4981.8 1834.01  4991.1 1829.62
  4991.6 1829.12  5008.5 1829.12    5009 1829.62    5012 1829.62    5022  1835.3
    5032 1835.88    5062 1835.96  5092.1 1835.33  5132.1 1836.99  5142.1 1836.98
  5162.1 1838.69  5172.1 1838.77  5252.1 1842.51  5392.2 1845.15  5397.3 1845.68
#Mann= 3 ,-1 , 0
  4447.3     .05       0  4991.1     .05       0    5009     .05       0
Bank Sta=4991.1,5009
XS Rating Curve= 0 ,0
Exp/Cntr=0.3,0.1

Type RM Length L Ch R = 1 ,69530   ,376,376,376
BEGIN DESCRIPTION:
Lytle Creek 69530.3
END DESCRIPTION:
XS GIS Cut Line= 4
       1613338.1      6802479.81      1613805.12      6802634.33
      1614216.58       6802806.2      1614591.66      6802883.98
#Sta/Elev= 30
  4505.8 1837.01    4644 1836.63  4670.5 1837.15  4829.1 1833.51  4897.8  1833.3
    4903 1833.96  4961.2 1832.85  4987.1 1833.33  4991.1  1831.3  4991.6  1830.8
  5008.5  1830.8    5009  1831.3  5022.5  1834.8  5030.1 1835.57  5051.8    1834
  5192.7 1833.65  5282.2 1834.26  5322.7 1833.08  5398.6 1834.45  5406.7 1835.08
  5412.1  1834.4  5430.5 1837.85  5435.9 1836.55  5440.1  1837.8  5462.4 1837.78
  5513.5 1835.55  5678.1 1840.52  5773.3  1840.9  5789.3 1842.31  5826.7 1842.52
#Mann= 3 ,-1 , 0
  4505.8     .05       0  4991.1     .05       0    5009     .05       0
Bank Sta=4991.1,5009
XS Rating Curve= 0 ,0
Exp/Cntr=0.3,0.1

Type RM Length L Ch R = 1 ,69154   ,394,394,394
BEGIN DESCRIPTION:
Lytle Creek 69153.72
END DESCRIPTION:
XS GIS Cut Line= 3
       1613181.1      6802681.73       1613510.5      6802836.67
      1614281.32      6803008.25
#Sta/Elev= 30
  4635.1 1836.12    4761 1835.25  4794.1 1835.63  4852.2 1834.51  4943.4 1833.85
  4971.7 1833.85    4982 1834.51    4989 1834.25  4991.1 1827.96  4991.6 1827.46
  5008.5 1827.46    5009 1827.96  5023.7 1828.43  5034.5 1831.63  5044.7 1832.13
  5120.9 1832.35  5207.9 1833.96  5270.1 1833.21  5290.6 1832.16  5362.3 1832.53
  5423.8 1831.63  5546.7 1832.69  5576.4 1833.44  5597.9 1832.14  5630.2 1832.63
  5649.1 1831.91  5668.5 1832.83  5722.3 1832.37  5765.8 1833.66  5788.8 1835.22
#Mann= 3 ,-1 , 0
  4635.1     .05       0  4991.1     .05       0    5009     .05       0
Bank Sta=4991.1,5009
XS Rating Curve= 0 ,0
Exp/Cntr=0.3,0.1