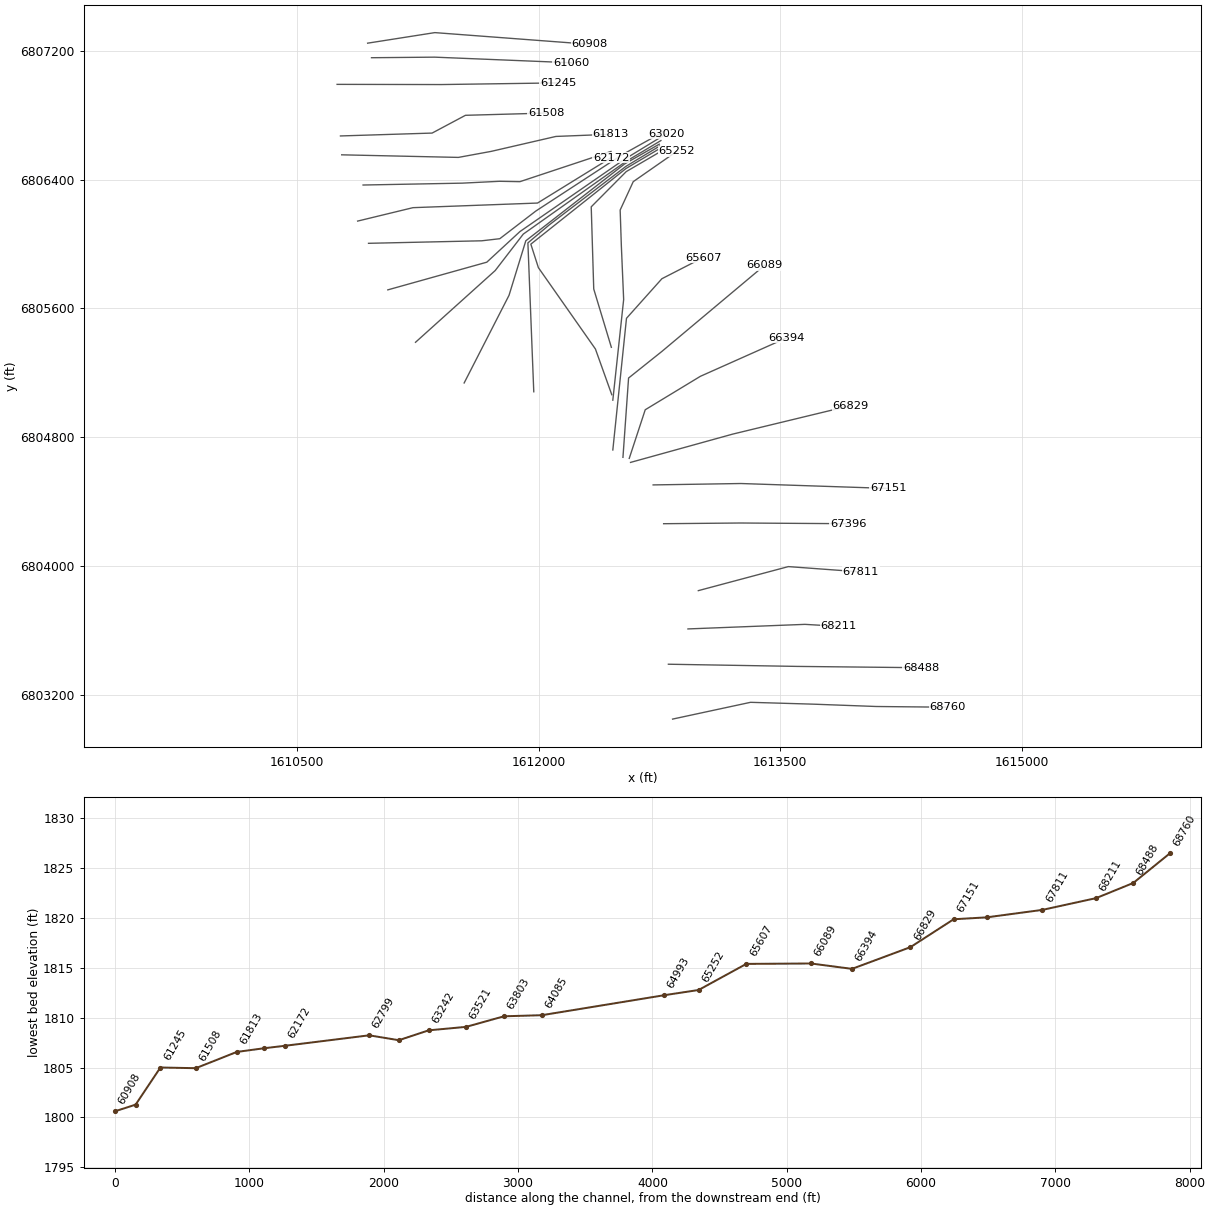
HEC-RAS study Lytle Creek.prj: Lytle Creek Base Level Engineering

--- Lytle Creek.g01 (geometry) --- (continued)

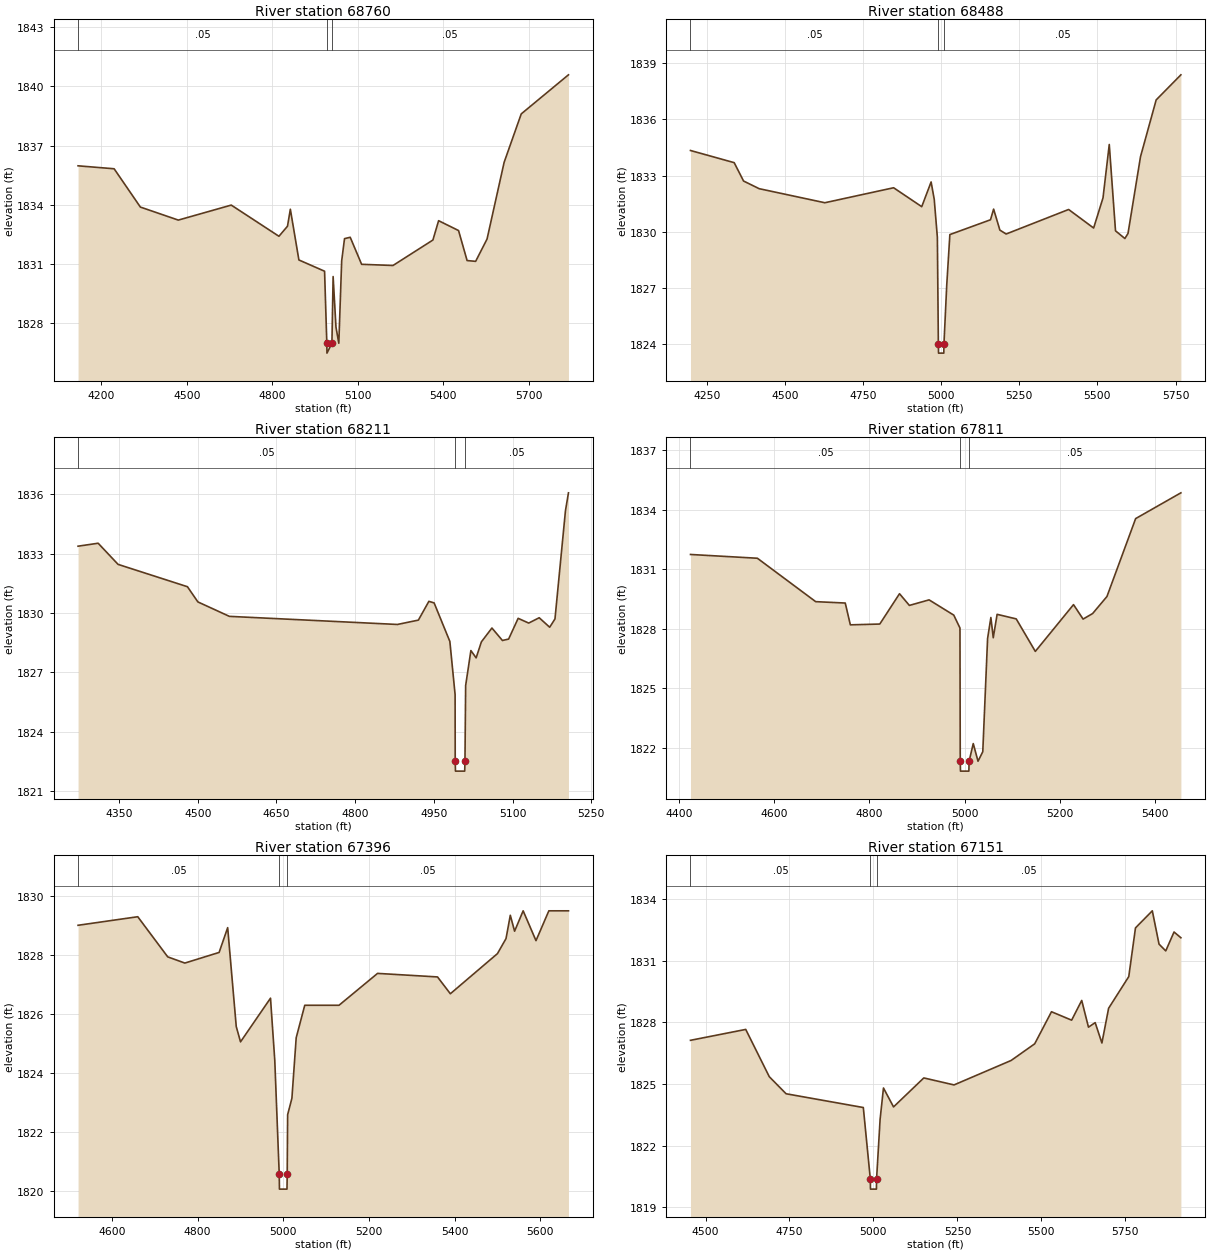
Type RM Length L Ch R = 1 ,68760   ,272,272,272
BEGIN DESCRIPTION:
Lytle Creek 68759.64
END DESCRIPTION:
XS GIS Cut Line= 5
      1612831.19      6803050.01      1613315.16      6803154.18
      1613702.95      6803142.79      1614096.25      6803128.22
      1614540.64      6803123.81
#Sta/Elev= 30
  4118.1 1835.98  4244.7 1835.83  4336.8 1833.89  4469.9 1833.23  4655.7 1833.99
  4823.1 1832.41  4853.1 1832.92  4863.1 1833.78  4893.1 1831.21  4983.2 1830.64
  4991.1 1826.99  4991.6 1826.49    5009 1826.99  5013.2 1830.37  5023.2 1827.81
  5033.2 1826.99  5043.2 1831.16  5053.2 1832.29  5073.2 1832.36  5113.2 1830.99
  5223.3 1830.93  5363.4 1832.22  5383.4  1833.2  5453.4  1832.7  5483.4 1831.18
  5513.4 1831.14  5553.4 1832.27  5613.4 1836.16  5673.4 1838.61  5839.1 1840.59
#Mann= 3 ,-1 , 0
  4118.1     .05       0  4991.1     .05       0    5009     .05       0
Bank Sta=4991.1,5009
XS Rating Curve= 0 ,0
Exp/Cntr=0.3,0.1

Type RM Length L Ch R = 1 ,68488   ,277,277,277
BEGIN DESCRIPTION:
Lytle Creek 68487.72
END DESCRIPTION:
XS GIS Cut Line= 3
       1612805.2      6803390.73       1613607.9      6803377.16
      1614374.14      6803369.02
#Sta/Elev= 30
    4198 1834.34  4337.8 1833.69  4367.8 1832.71  4417.8  1832.3  4627.9 1831.55
  4847.9 1832.35  4937.9 1831.34  4967.9 1832.66  4977.9 1831.73  4987.9  1829.7
  4991.1 1824.02  4991.6 1823.52  5008.5 1823.52    5009 1824.02  5017.9 1827.15
  5027.9 1829.85  5157.9 1830.64  5167.9 1831.21  5187.9 1830.09  5207.9 1829.88
  5407.9 1831.19  5487.9  1830.2  5517.9 1831.81  5537.9 1834.66  5557.9 1830.05
  5587.9 1829.64  5597.9 1829.91  5637.9 1834.01    5688 1837.04  5767.1 1838.38
#Mann= 3 ,-1 , 0
    4198     .05       0  4991.1     .05       0    5009     .05       0
Bank Sta=4991.1,5009
XS Rating Curve= 0 ,0
Exp/Cntr=0.3,0.1

Type RM Length L Ch R = 1 ,68211   ,400,400,400
BEGIN DESCRIPTION:
Lytle Creek 68211.11
END DESCRIPTION:
XS GIS Cut Line= 3
       1612926.7      6803609.91      1613653.12      6803638.28
      1613860.69      6803626.17
#Sta/Elev= 30
  4271.7 1833.38    4310 1833.53    4348 1832.46  4480.2 1831.33  4500.2 1830.56
  4560.2 1829.83  4880.5 1829.42  4920.5 1829.64  4940.5 1830.59  4950.5 1830.51
  4980.5 1828.56  4990.5 1825.87  4990.7  1822.5  4991.2    1822  5008.8    1822
  5009.3  1822.5  5010.6 1826.33  5020.6  1828.1  5030.6 1827.73  5040.6 1828.54
  5060.7 1829.24  5080.7 1828.61  5092.5 1828.68  5110.7 1829.73  5130.8 1829.49
  5150.8 1829.76  5170.8 1829.28  5180.9  1829.7  5200.9 1835.18  5206.6 1836.08
#Mann= 3 ,-1 , 0
  4271.7     .05       0  4990.7     .05       0  5009.3     .05       0
Bank Sta=4990.7,5009.3
XS Rating Curve= 0 ,0
Exp/Cntr=0.3,0.1

Type RM Length L Ch R = 1 ,67811   ,415,415,415
BEGIN DESCRIPTION:
Lytle Creek 67810.83
END DESCRIPTION:
XS GIS Cut Line= 3
      1612991.06      6803847.65      1613550.07      6803996.95
      1613999.75      6803963.96
#Sta/Elev= 30
  4424.4 1831.75  4564.8 1831.56  4687.2 1829.37  4749.3  1829.3    4760  1828.2
  4821.8 1828.24  4863.2 1829.77  4883.9 1829.18  4925.3 1829.46  4977.1 1828.69
  4990.1 1828.04  4990.7 1821.32  4991.2 1820.82  5008.8 1820.82  5009.3 1821.32
    5018 1822.21    5028 1821.32    5038  1821.8  5048.1 1827.51    5055 1828.57
    5060 1827.55  5068.1 1828.73  5108.2  1828.5  5148.3 1826.86  5228.5 1829.22
  5248.6 1828.49  5268.6 1828.77  5298.7 1829.63  5358.9 1833.56  5453.9 1834.86
#Mann= 3 ,-1 , 0
  4424.4     .05       0  4990.7     .05       0  5009.3     .05       0
Bank Sta=4990.7,5009.3
XS Rating Curve= 0 ,0
Exp/Cntr=0.3,0.1

Type RM Length L Ch R = 1 ,67396   ,245,245,245
BEGIN DESCRIPTION:
Lytle Creek 67396.37
END DESCRIPTION:
XS GIS Cut Line= 3
      1612775.61       6804263.3      1613253.05      6804267.64
      1613920.77       6804263.3
#Sta/Elev= 30
  4520.9 1829.01  4660.3  1829.3  4730.3 1827.94  4770.3 1827.73  4850.3 1828.09
  4870.3 1828.93  4890.3 1825.58  4900.3 1825.06  4970.3 1826.54  4980.3 1824.43
  4990.7 1820.57  4991.2 1820.07  5008.8 1820.07  5009.3 1820.57  5010.3 1822.59
  5020.3 1823.15  5030.3  1825.2  5050.3  1826.3  5130.3  1826.3  5220.3 1827.38
  5360.3 1827.26  5390.3 1826.69  5500.3 1828.05  5520.3 1828.56  5530.3 1829.35
  5540.3 1828.81  5560.3  1829.5  5590.3 1828.49  5620.3  1829.5  5666.1  1829.5
#Mann= 3 ,-1 , 0
  4520.9     .05       0  4990.7     .03       0  5009.3     .05       0
Bank Sta=4990.7,5009.3
XS Rating Curve= 0 ,0
Exp/Cntr=0.3,0.1

Type RM Length L Ch R = 1 ,67151   ,322,322,322
BEGIN DESCRIPTION:
Lytle Creek 66938.9
END DESCRIPTION:
XS GIS Cut Line= 3
      1612710.47      6804504.18       1613255.1      6804512.86
      1614170.09      6804482.31
#Sta/Elev= 30
  4455.3 1827.12  4619.8 1827.65  4689.9 1825.35  4739.9 1824.52  4969.9 1823.85
  4990.7 1820.38  4991.2 1819.88  5008.9 1819.88  5009.4 1820.38  5019.9 1823.28
  5029.9  1824.8  5059.9 1823.88    5150 1825.29    5240 1824.95  5410.1 1826.14
  5480.2 1826.95  5530.2 1828.51  5590.2  1828.1  5620.2 1829.06  5640.3 1827.76
  5660.3 1827.98  5680.3 1826.99  5700.3 1828.68  5760.3 1830.22  5780.3 1832.59
  5830.4 1833.42  5850.4  1831.8  5870.4 1831.47  5895.1 1832.39  5915.5 1832.11
#Mann= 3 ,-1 , 0
  4455.3     .05       0  4990.7     .05       0  5009.4     .05       0
Bank Sta=4990.7,5009.4
XS Rating Curve= 0 ,0
Exp/Cntr=0.3,0.1

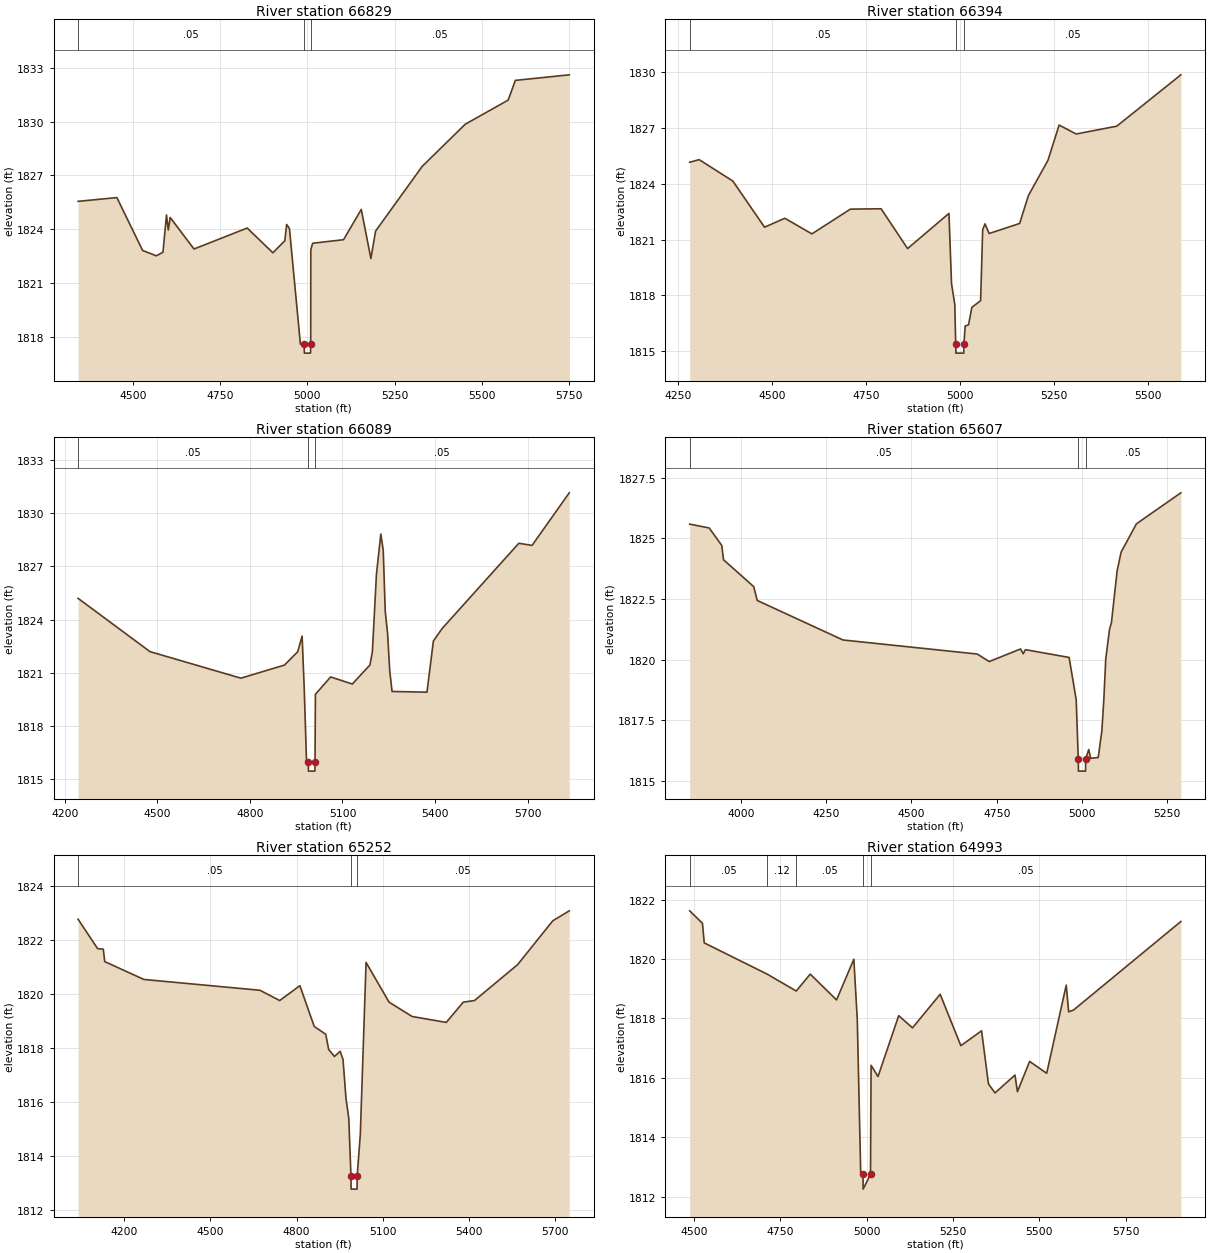
Type RM Length L Ch R = 1 ,66829   ,435,435,435
BEGIN DESCRIPTION:
Lytle Creek 67461.288
END DESCRIPTION:
XS GIS Cut Line= 3
      1612570.15      6804643.95      1613204.75      6804819.72
      1613935.49      6804996.44
#Sta/Elev= 30
  4341.5 1825.55  4452.9 1825.76  4526.7 1822.81  4566.2 1822.51  4585.2 1822.71
  4595.3 1824.79  4600.5 1823.95  4605.9 1824.65  4674.3 1822.89    4827 1824.06
  4900.8 1822.68  4935.1 1823.35  4940.3 1824.26  4948.4 1824.03  4979.8 1817.58
  4990.7 1817.58  4991.2 1817.08  5008.9 1817.08  5009.4 1817.58  5009.7 1822.84
  5014.8 1823.21  5103.7 1823.41  5154.6  1825.1  5182.2 1822.36  5195.7 1823.89
  5329.5  1827.5  5452.9 1829.85  5576.4  1831.2    5597  1832.3  5751.8 1832.61
#Mann= 3 ,-1 , 0
  4341.5     .05       0  4990.7     .05       0  5009.4     .05       0
Bank Sta=4990.7,5009.4
XS Rating Curve= 0 ,0
Exp/Cntr=0.3,0.1

Type RM Length L Ch R = 1 ,66394   ,305,305,305
BEGIN DESCRIPTION:
Lytle Creek 66393.781
END DESCRIPTION:
XS GIS Cut Line= 4
      1612562.13      6804668.97      1612661.33      6804970.84
       1613003.8      6805178.56      1613540.63      6805417.98
#Sta/Elev= 30
  4281.7 1825.16  4306.9  1825.3  4396.5 1824.15  4480.7 1821.67  4534.8 1822.15
  4606.6 1821.31    4709 1822.64  4790.7 1822.66  4861.1 1820.52  4971.1 1822.41
    4978 1818.63  4986.6 1817.53  4989.1  1815.4  4989.6  1814.9  5010.4  1814.9
  5010.9  1815.4  5014.3 1816.36  5023.2 1816.42  5032.1 1817.36  5055.3 1817.72
  5060.8 1821.53    5067 1821.85    5078 1821.33  5159.1 1821.87  5182.4 1823.37
  5234.3 1825.26  5264.1 1827.16  5309.4 1826.68  5417.4  1827.1  5587.8 1829.86
#Mann= 3 ,-1 , 0
  4281.7     .05       0  4989.1     .05       0  5010.9     .05       0
Bank Sta=4989.1,5010.9
XS Rating Curve= 0 ,0
Exp/Cntr=0.3,0.1

Type RM Length L Ch R = 1 ,66089   ,482,482,482
BEGIN DESCRIPTION:
Lytle Creek 66089.12
END DESCRIPTION:
XS GIS Cut Line= 4
      1612523.06      6804675.49      1612557.92       6805167.9
      1612764.86      6805333.15      1613404.11        6805869.
#Sta/Elev= 30
  4242.7  1825.2  4475.8 1822.19  4770.6 1820.69  4911.8 1821.43  4954.7 1822.18
  4969.1 1823.07  4975.7 1820.21  4983.5 1815.94  4989.1 1815.94  4989.6 1815.44
  5010.4 1815.44  5010.9 1815.94  5012.2 1819.78  5061.6 1820.76  5131.9 1820.36
  5189.1 1821.44  5196.9 1822.19  5210.1 1826.56  5224.3 1828.83  5232.1 1827.91
  5238.6 1824.47  5246.4 1823.19  5252.9 1821.17  5260.7 1819.94  5373.9  1819.9
  5394.7 1822.79  5423.3  1823.5  5671.8 1828.31  5714.7 1828.19  5835.3 1831.16
#Mann= 3 ,-1 , 0
  4242.7     .05       0  4989.1     .05       0  5010.9     .05       0
Bank Sta=4989.1,5010.9
XS Rating Curve= 0 ,0
Exp/Cntr=0.3,0.1

Type RM Length L Ch R = 1 ,65607   ,355,355,355
BEGIN DESCRIPTION:
Lytle Creek 65607.01
END DESCRIPTION:
XS GIS Cut Line= 4
      1612460.13      6804721.07      1612544.95      6805538.76
      1612764.86      6805784.54       1613020.9      6805916.02
#Sta/Elev= 30
  3850.1 1825.59  3907.3 1825.43  3944.1 1824.71  3949.2 1824.12  4037.8 1823.01
  4048.1 1822.44  4299.4 1820.81    4693 1820.23  4728.1 1819.92  4820.1 1820.44
  4827.6 1820.24  4834.3 1820.41  4962.2 1820.09  4983.1 1818.34  4989.1  1815.9
  4989.6  1815.4  5010.4  1815.4  5010.9  1815.9  5019.8 1816.29  5025.4 1815.93
  5047.6 1815.96  5058.3 1817.07  5064.1 1818.38  5069.7 1820.03  5080.7 1821.25
  5086.3 1821.52  5102.9 1823.65  5114.6 1824.43  5159.5  1825.6  5289.8 1826.88
#Mann= 3 ,-1 , 0
  3850.1     .05       0  4989.1     .05       0  5010.9     .05       0
Bank Sta=4989.1,5010.9
XS Rating Curve= 0 ,0
Exp/Cntr=0.3,0.1

Type RM Length L Ch R = 1 ,65252   ,259,259,259
BEGIN DESCRIPTION:
Lytle Creek 65251.55
END DESCRIPTION:
XS GIS Cut Line= 6
      1612460.12      6805030.46       1612527.4      6805655.48
      1612513.12      6805987.66       1612505.7      6806211.04
      1612586.86      6806387.25      1612857.28      6806575.64
#Sta/Elev= 30
  4040.2 1822.77  4108.1 1821.68  4127.8 1821.66  4132.9  1821.2  4269.1 1820.54
  4672.6 1820.14  4741.4 1819.76  4811.5 1820.31  4861.5  1818.8  4901.6 1818.51
  4911.6 1817.95  4931.6 1817.69  4951.6 1817.88  4961.6 1817.58  4971.6 1816.17
  4981.6 1815.39  4989.1 1813.28  4989.6 1812.78  5010.4 1812.78  5010.9 1813.28
  5021.7  1814.8  5041.7 1821.17  5121.7  1819.7  5201.8 1819.17  5320.6 1818.95
  5379.8  1819.7  5418.8 1819.76  5568.9 1821.09    5691 1822.71  5748.4 1823.08
#Mann= 3 ,-1 , 0
  4040.2     .05       0  4989.1     .05       0  5010.9     .05       0
Bank Sta=4989.1,5010.9
XS Rating Curve= 0 ,0
Exp/Cntr=0.3,0.1

Type RM Length L Ch R = 1 ,64993   ,908,908,908
BEGIN DESCRIPTION:
Mapping XS 26b83782
END DESCRIPTION:
XS GIS Cut Line= 5
        1612451.      6805358.65      1612341.64      6805720.59
      1612326.01        6806231.      1612543.46      6806449.75
      1612738.53      6806563.69
#Sta/Elev= 30
    4487 1821.62    4524  1821.2  4529.2 1820.54  4711.3 1819.49  4795.8 1818.92
  4836.2 1819.49  4912.5 1818.62  4962.6 1819.99  4972.6 1817.96  4982.6 1812.75
  4989.1 1812.75  4989.6 1812.25  5010.9 1812.75  5012.6 1816.42  5032.6 1816.04
  5092.6 1818.09  5132.6 1817.68  5212.7 1818.81  5272.7 1817.08  5332.7 1817.58
  5352.7 1815.79  5371.7 1815.49  5429.5 1816.09  5436.6 1815.53  5471.9 1816.55
  5521.4 1816.15    5578 1819.12    5585 1818.22  5599.2 1818.28  5910.1 1821.26
#Mann= 5 ,-1 , 0
    4487     .05       0  4711.3     .12       0  4795.8     .05       0
  4989.1     .05       0  5010.9     .05       0
Bank Sta=4989.1,5010.9
XS Rating Curve= 0 ,0
Exp/Cntr=0.3,0.1

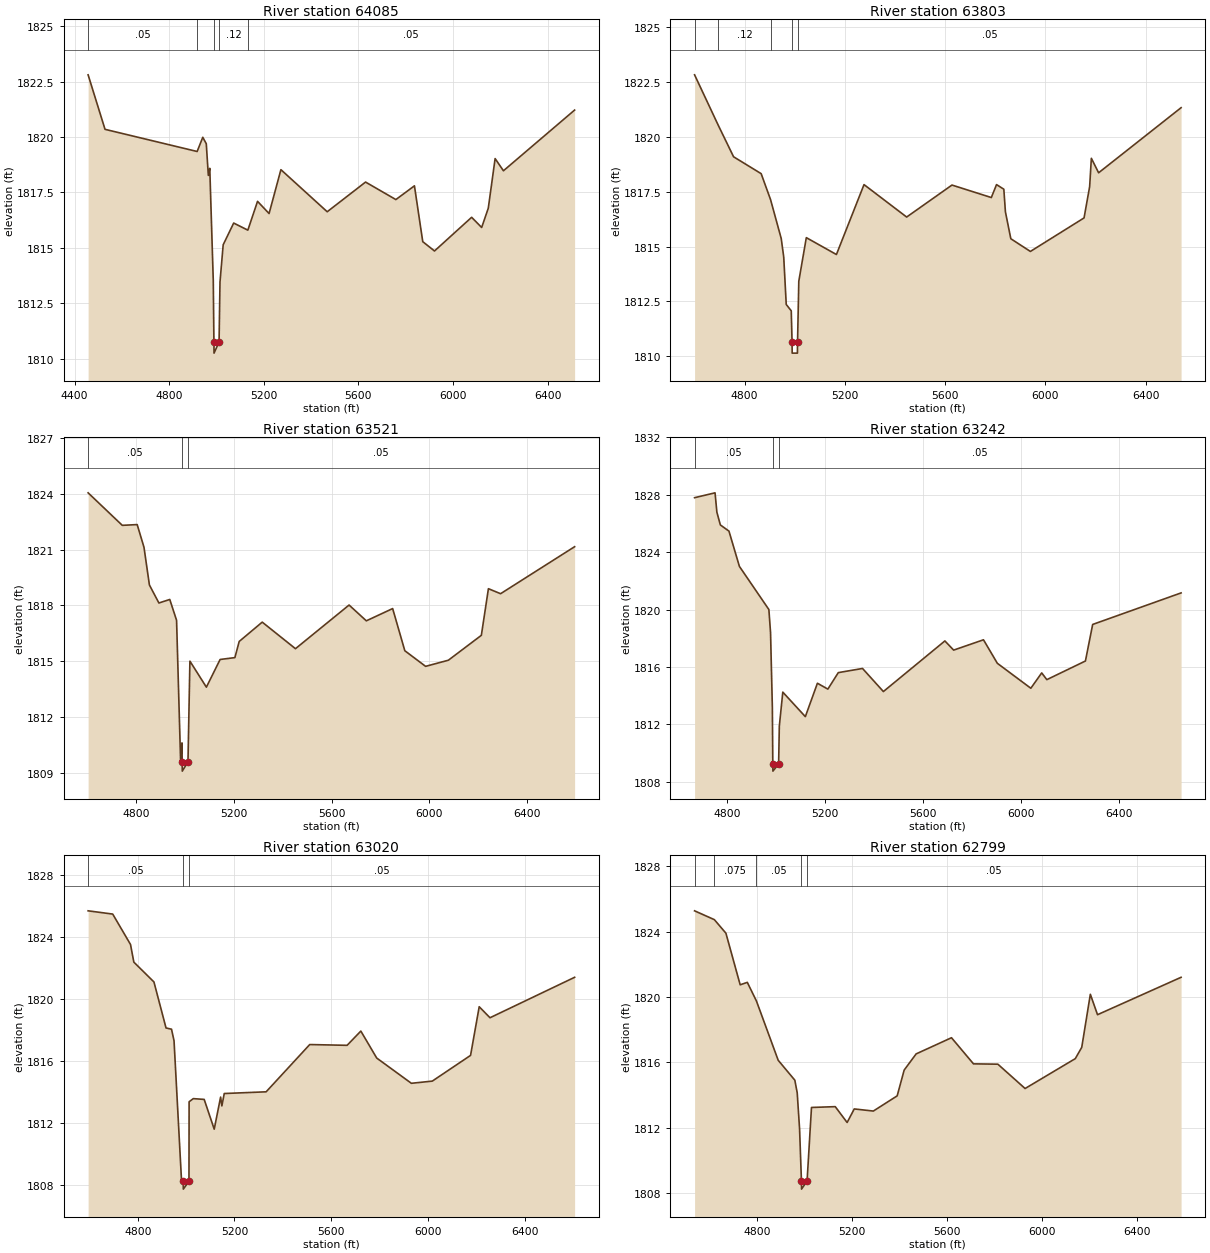
Type RM Length L Ch R = 1 ,64085   ,282,282,282
BEGIN DESCRIPTION:
Mapping XS cc1b6361
END DESCRIPTION:
XS GIS Cut Line= 6
      1612453.62      6805064.34      1612352.05      6805348.19
      1611997.89       6805853.4      1611951.01      6805999.23
      1612541.76       6806468.8      1612740.68      6806586.49
#Sta/Elev= 30
  4457.1 1822.81  4528.6 1820.35  4918.2 1819.35    4942 1819.99  4956.8  1819.7
  4965.5 1818.27  4971.6 1818.59  4986.4 1813.52  4989.1 1810.75  4989.6 1810.25
  5010.9 1810.75  5014.8 1813.46  5028.3 1815.14  5072.7 1816.12  5132.6  1815.8
  5173.6  1817.1  5222.4 1816.55  5272.4 1818.53  5468.2 1816.63  5630.4 1817.97
  5758.6 1817.18  5837.1  1817.8  5872.3 1815.28    5922 1814.86    6079 1816.38
  6121.4 1815.92  6149.4 1816.79  6178.3 1819.03  6213.5 1818.48  6514.5 1821.22
#Mann= 5 ,-1 , 0
  4457.1     .05       0  4918.2     .12       0  4989.1     .07       0
  5010.9     .12       0  5132.6     .05       0
Bank Sta=4989.1,5010.9
XS Rating Curve= 0 ,0
Exp/Cntr=0.3,0.1

Type RM Length L Ch R = 1 ,63803   ,282,282,282
BEGIN DESCRIPTION:
Mapping XS 94f33449
END DESCRIPTION:
XS GIS Cut Line= 5
      1611969.24      6805082.57      1611932.78      6806007.05
       1612065.6      6806119.02       1612541.9      6806482.52
      1612750.06      6806607.74
#Sta/Elev= 30
  4600.2 1822.84  4694.6 1820.54  4755.8  1819.1  4865.8 1818.33  4903.2 1817.15
  4945.9 1815.37  4955.9 1814.52  4965.9 1812.36  4985.9 1812.07  4989.1 1810.64
  4989.6 1810.14  5010.5 1810.14    5011 1810.64    5016 1813.42    5046 1815.41
  5166.1 1814.64  5276.2 1817.83  5446.3 1816.35  5627.1 1817.81  5784.1 1817.24
  5804.9 1817.83    5834 1817.62  5840.3 1816.59  5861.9 1815.36    5940 1814.78
  6154.1 1816.31  6176.4 1817.74  6183.2 1819.03  6212.2 1818.37  6541.2 1821.34
#Mann= 5 ,-1 , 0
  4600.2     .05       0  4694.6     .12       0  4903.2     .05       0
  4989.1     .05       0    5011     .05       0
Bank Sta=4989.1,5011
XS Rating Curve= 0 ,0
Exp/Cntr=0.3,0.1

Type RM Length L Ch R = 1 ,63521   ,279,279,279
BEGIN DESCRIPTION:
Mapping XS 31b3d0d7
END DESCRIPTION:
XS GIS Cut Line= 5
      1611536.95      6805137.25       1611815.6      6805681.52
      1611919.76      6806020.07      1612533.43      6806497.37
      1612748.35      6806619.91
#Sta/Elev= 30
  4603.3 1824.06  4743.1 1822.31  4804.1 1822.35  4831.9 1821.13  4854.1  1819.1
  4892.9 1818.13  4937.4 1818.32  4965.2  1817.2  4981.8 1809.58  4987.4  1810.6
  4988.1 1809.58  4988.6 1809.08  5011.9 1809.58  5019.8    1815  5087.2  1813.6
  5143.4 1815.09  5203.8 1815.19  5221.5 1816.06  5315.7  1817.1  5451.7 1815.67
    5671 1818.02  5741.6 1817.17  5849.3 1817.83  5899.1 1815.56  5984.1 1814.72
  6077.3 1815.05  6212.2 1816.39  6241.1  1818.9  6290.9 1818.63  6593.8 1821.16
#Mann= 3 ,-1 , 0
  4603.3     .05       0  4988.1     .05       0  5011.9     .05       0
Bank Sta=4988.1,5011.9
XS Rating Curve= 0 ,0
Exp/Cntr=0.3,0.1

Type RM Length L Ch R = 1 ,63242   ,222,222,222
BEGIN DESCRIPTION:
Mapping XS e7d49430
END DESCRIPTION:
XS GIS Cut Line= 5
       1611234.9      6805389.88      1611729.66      6805835.17
      1611904.14      6806061.73       1612536.2      6806509.23
      1612758.73      6806642.46
#Sta/Elev= 30
  4668.9  1827.8  4752.4 1828.14  4759.9 1826.79  4774.1  1825.9  4809.2 1825.47
  4851.8 1823.01  4972.1    1820  4978.9 1818.39  4986.3 1813.19  4988.1 1809.23
  4988.6 1808.73  5011.9 1809.23  5014.7 1811.86  5028.9 1814.24  5120.9 1812.53
  5170.2 1814.86  5212.8 1814.45  5255.4  1815.6  5354.3 1815.89  5439.4 1814.28
  5690.4 1817.81  5726.1 1817.17  5847.9 1817.89  5904.5 1816.25  6041.1 1814.51
  6085.5 1815.58  6106.4 1815.11  6263.9 1816.41  6293.5 1818.96  6654.3 1821.16
#Mann= 3 ,-1 , 0
  4668.9     .05       0  4988.1     .05       0  5011.9     .05       0
Bank Sta=4988.1,5011.9
XS Rating Curve= 0 ,0
Exp/Cntr=0.3,0.1

Type RM Length L Ch R = 1 ,63020   ,221,221,221
BEGIN DESCRIPTION:
Mapping XS be3d6582
END DESCRIPTION:
XS GIS Cut Line= 5
      1611062.95      6805715.37      1611677.58      6805887.25
       1611883.3      6806077.36      1612529.31      6806524.01
      1612791.72      6806684.13
#Sta/Elev= 30
    4595  1825.7  4696.7 1825.49  4770.2 1823.53    4784 1822.39  4867.1 1821.11
  4917.1 1818.14  4939.8 1818.06  4950.2 1817.31  4981.3 1808.24  4988.1 1808.24
  4988.6 1807.74  5011.9 1808.24  5012.5 1813.38  5029.9 1813.58  5074.8 1813.53
  5116.3 1811.61  5142.7 1813.68  5147.9 1813.11  5157.8 1813.91  5330.9 1814.02
  5511.1 1817.07  5665.6 1817.02  5722.4 1817.94    5788  1816.2  5931.2 1814.57
  6017.7 1814.71  6175.9 1816.37  6211.7 1819.51  6256.3  1818.8  6606.1 1821.41
#Mann= 3 ,-1 , 0
    4595     .05       0  4988.1     .05       0  5011.9     .05       0
Bank Sta=4988.1,5011.9
XS Rating Curve= 0 ,0
Exp/Cntr=0.3,0.1

Type RM Length L Ch R = 1 ,62799   ,627,627,627
BEGIN DESCRIPTION:
Mapping XS 973cb49e
END DESCRIPTION:
XS GIS Cut Line= 6
      1610943.17      6806004.44      1611646.33      6806020.07
       1611758.3      6806033.09      1611982.26      6806204.96
      1612513.64      6806551.73      1612788.24      6806704.95
#Sta/Elev= 30
  4538.4 1825.27  4621.6 1824.73  4670.3  1823.9  4730.3 1820.74  4760.3 1820.89
  4798.7 1819.75  4890.3 1816.12  4960.3  1814.9  4970.3 1814.13  4980.3 1811.91
  4988.1 1808.73  4988.6 1808.23  5011.9 1808.73  5030.4 1813.23  5130.4 1813.28
  5180.4 1812.31  5210.4 1813.14  5290.7 1813.01    5391 1813.94  5420.5 1815.52
  5470.9 1816.51  5619.6  1817.5  5712.2  1815.9  5814.8 1815.88  5929.4 1814.39
  6140.7 1816.22  6167.8 1816.91    6204 1820.16  6234.2 1818.91  6585.9  1821.2
#Mann= 5 ,-1 , 0
  4538.4     .05       0  4621.6    .075       0  4798.7     .05       0
  4988.1     .05       0  5011.9     .05       0
Bank Sta=4988.1,5011.9
XS Rating Curve= 0 ,0
Exp/Cntr=0.3,0.1

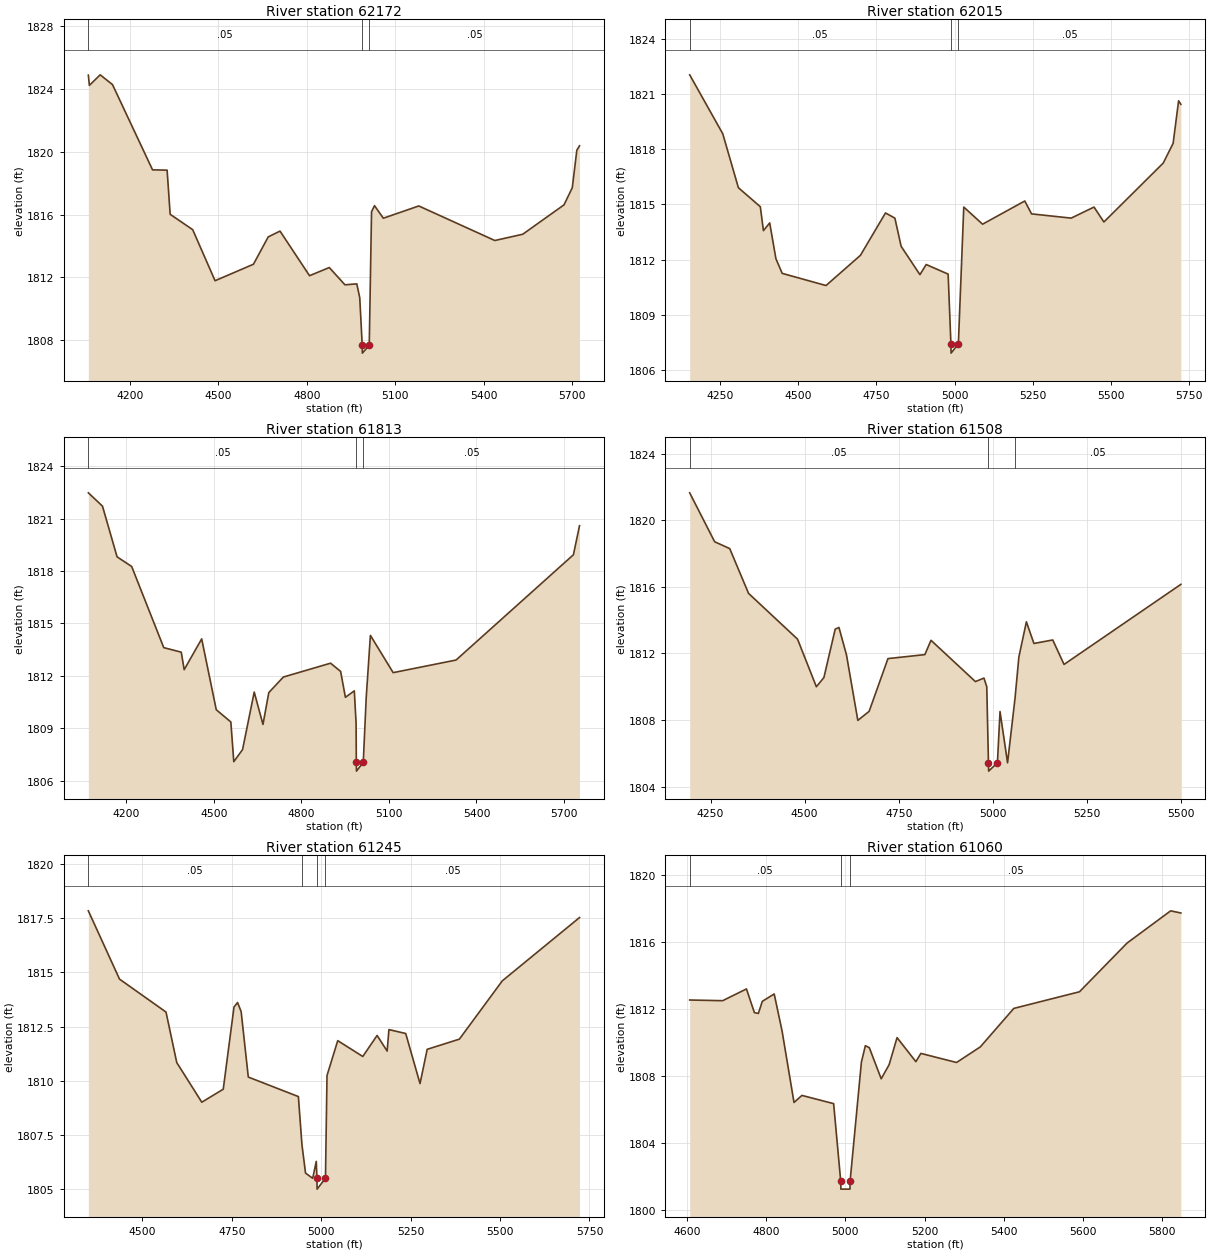
Type RM Length L Ch R = 1 ,62172   ,157,157,157
BEGIN DESCRIPTION:
Mapping XS 6360c2df
END DESCRIPTION:
XS GIS Cut Line= 4
      1610875.48      6806142.46      1611219.24       6806225.8
      1611992.68      6806254.44      1612449.73      6806536.57
#Sta/Elev= 30
  4059.8 1824.88  4063.3 1824.23  4099.9  1824.9  4141.6 1824.28  4277.4 1818.85
  4326.8 1818.83  4337.1 1816.02  4413.5 1815.04  4489.3 1811.79  4619.4 1812.84
  4669.5 1814.58  4709.5 1814.95  4809.5 1812.11  4876.5 1812.63  4929.6 1811.53
  4969.7 1811.59  4979.7 1810.71  4988.1 1807.68  4988.6 1807.18  5011.9 1807.68
  5019.7 1816.18  5029.7 1816.57  5059.7 1815.77  5179.8 1816.55  5437.6 1814.35
  5532.2 1814.75    5672 1816.62  5700.1 1817.71  5715.5  1820.1  5724.6 1820.38
#Mann= 3 ,-1 , 0
  4059.8     .05       0  4988.1     .05       0  5011.9     .05       0
Bank Sta=4988.1,5011.9
XS Rating Curve= 0 ,0
Exp/Cntr=0.3,0.1

Type RM Length L Ch R = 1 ,62015   ,202,202,202
BEGIN DESCRIPTION:
Lytle Creek 62014.58
END DESCRIPTION:
XS GIS Cut Line= 5
      1610909.35      6806366.42      1611524.26      6806378.02
      1611756.87      6806389.57       1611883.3      6806387.25
      1612448.44      6806574.76
#Sta/Elev= 30
  4153.2 1822.04  4258.9 1818.84  4308.9 1815.91  4378.9 1814.88  4388.9 1813.58
  4408.9    1814  4428.9 1812.05  4448.9 1811.26  4588.9  1810.6  4698.9 1812.24
    4779 1814.54    4809 1814.26    4829 1812.73  4889.1 1811.19  4909.1 1811.74
  4979.2 1811.22  4988.1 1807.43  4988.6 1806.93  5011.9 1807.43  5029.2 1814.86
  5089.3 1813.93  5224.2 1815.19  5245.8 1814.49  5372.5 1814.26  5445.4 1814.86
    5477 1814.05  5666.7 1817.25  5698.3 1818.32  5715.8 1820.63    5723 1820.44
#Mann= 3 ,-1 , 0
  4153.2     .05       0  4988.1     .05       0  5011.9     .05       0
Bank Sta=4988.1,5011.9
XS Rating Curve= 0 ,0
Exp/Cntr=0.3,0.1

Type RM Length L Ch R = 1 ,61813   ,305,305,305
BEGIN DESCRIPTION:
Lytle Creek 61813.44
END DESCRIPTION:
XS GIS Cut Line= 5
      1610776.57      6806553.92      1611501.05      6806537.88
      1611704.79      6806575.33      1612106.76       6806668.1
      1612445.85      6806681.53
#Sta/Elev= 30
  4069.5 1822.47  4117.9 1821.71    4168 1818.81    4218 1818.26    4328 1813.62
    4388 1813.36    4398 1812.36    4458 1814.12    4508 1810.07    4558 1809.37
  4568.1  1807.1  4598.1 1807.79  4638.1 1811.08  4668.1 1809.23  4688.1 1811.05
  4738.1 1811.94  4899.8 1812.73  4934.3 1812.26  4950.7 1810.78  4981.2 1811.15
  4987.3 1809.31  4988.1 1807.06  4988.6 1806.56  5011.9 1807.06  5022.1 1810.79
  5036.4 1814.32  5114.4 1812.19  5329.9 1812.91  5732.3 1818.93  5753.2 1820.59
#Mann= 3 ,-1 , 0
  4069.5     .05       0  4988.1     .04       0  5011.9     .05       0
Bank Sta=4988.1,5011.9
XS Rating Curve= 0 ,0
Exp/Cntr=0.3,0.1

Type RM Length L Ch R = 1 ,61508   ,263,263,263
BEGIN DESCRIPTION:
Lytle Creek 61507.84
END DESCRIPTION:
XS GIS Cut Line= 4
      1610768.77      6806671.11      1611338.01      6806688.97
      1611545.06      6806799.29      1612045.03      6806813.18
#Sta/Elev= 30
  4194.7 1821.65    4261 1818.71    4301  1818.3    4351 1815.61  4481.1 1812.86
  4531.1    1810  4551.1 1810.55  4581.1 1813.46  4591.1 1813.56  4611.1 1811.91
  4641.2 1807.98  4671.2 1808.52  4721.2 1811.69  4819.2 1811.93  4835.5 1812.79
  4953.4 1810.31  4976.1 1810.52  4983.6    1810  4988.1 1805.43  4988.6 1804.93
  5011.9 1805.43  5018.8 1808.51  5038.8 1805.43  5058.8 1809.34  5068.8 1811.78
  5088.8  1813.9  5108.8  1812.6  5158.8 1812.81  5188.8 1811.34    5499 1816.15
#Mann= 3 ,-1 , 0
  4194.7     .05       0  4988.1     .03       0  5058.8     .05       0
Bank Sta=4988.1,5011.9
XS Rating Curve= 0 ,0
Exp/Cntr=0.3,0.1

Type RM Length L Ch R = 1 ,61245   ,185,185,185
BEGIN DESCRIPTION:
Lytle Creek 61244.98
END DESCRIPTION:
XS GIS Cut Line= 3
      1610747.92      6806991.42      1611395.76      6806990.27
      1612120.75      6807000.67
#Sta/Elev= 30
  4349.2 1817.84  4436.3 1814.69  4566.3 1813.17  4596.3 1810.84  4666.3 1809.01
  4726.3 1809.61  4756.3  1813.4  4766.3 1813.61  4776.3 1813.19  4796.3 1810.17
  4936.3 1809.27  4946.3 1807.04  4956.3 1805.74  4976.3  1805.5  4986.3 1806.28
  4988.1  1805.5  4988.6    1805    5012  1805.5  5016.3 1810.24  5046.3 1811.85
  5116.3 1811.12  5156.3 1812.09  5184.4 1811.37  5189.4 1812.36  5236.3 1812.18
  5276.3 1809.87  5296.3 1811.45  5386.3 1811.92  5506.3 1814.61  5722.1 1817.53
#Mann= 4 ,-1 , 0
  4349.2     .05       0  4946.3     .03       0  4988.1     .03       0
    5012     .05       0
Bank Sta=4988.1,5012
XS Rating Curve= 0 ,0
Exp/Cntr=0.3,0.1

Type RM Length L Ch R = 1 ,61060   ,152,152,152
BEGIN DESCRIPTION:
Lytle Creek 61060.47
END DESCRIPTION:
XS GIS Cut Line= 3
      1610961.68      6807156.93      1611354.09       6807160.4
      1612200.66      6807125.71
#Sta/Elev= 30
    4607 1812.53  4690.3 1812.49  4750.3 1813.19  4770.3 1811.78  4780.3 1811.73
  4790.3 1812.45  4820.3 1812.89  4840.3 1810.67  4870.3 1806.43  4890.3 1806.85
  4970.3 1806.36  4988.1 1801.77  4988.6 1801.27  5011.5 1801.27    5012 1801.77
  5040.4 1808.83  5050.4 1809.81  5060.4 1809.69  5090.4 1807.84  5110.4 1808.68
  5130.4 1810.29  5177.9 1808.86  5190.5 1809.35  5280.6 1808.81  5340.6 1809.74
  5425.1 1812.03  5590.8 1813.02  5710.9 1815.92    5821 1817.84  5846.7 1817.71
#Mann= 3 ,-1 , 0
    4607     .05       0  4988.1     .04       0    5012     .05       0
Bank Sta=4988.1,5012
XS Rating Curve= 0 ,0
Exp/Cntr=0.3,0.1

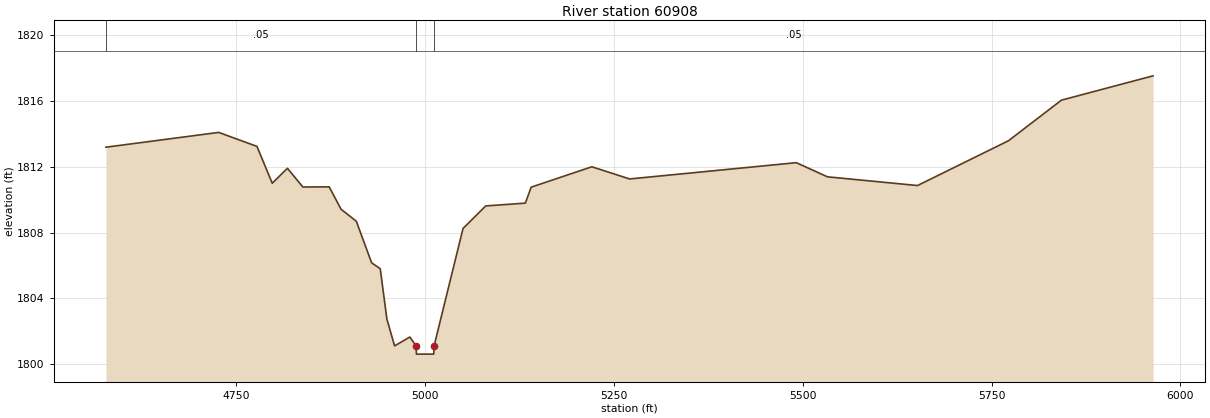
Type RM Length L Ch R = 1 ,60908   ,324,324,324
BEGIN DESCRIPTION:
Lytle Creek 61296.893
END DESCRIPTION:
XS GIS Cut Line= 3
      1610937.47      6807247.22      1611354.85      6807312.79
      1612315.92      6807240.26
#Sta/Elev= 30
  4577.5 1813.19  4726.8 1814.09  4777.5 1813.24  4797.7    1811  4817.9 1811.91
  4838.2 1810.77  4873.1 1810.78  4888.8 1809.42    4909 1808.69  4929.3 1806.16
  4940.7  1805.8  4949.5 1802.74  4959.7 1801.11  4979.9 1801.65  4988.1 1801.11
  4988.6 1800.61  5011.5 1800.61    5012 1801.11  5050.3 1808.25  5080.4 1809.62
  5132.8 1809.79  5140.5 1810.76  5220.8    1812  5270.9 1811.26  5491.5 1812.25
  5532.7 1811.39    5652 1810.86  5772.3 1813.58  5842.5 1816.05  5963.8 1817.53
#Mann= 3 ,-1 , 0
  4577.5     .05       0  4988.1     .05       0    5012     .05       0
Bank Sta=4988.1,5012
XS Rating Curve= 0 ,0
Exp/Cntr=0.3,0.1