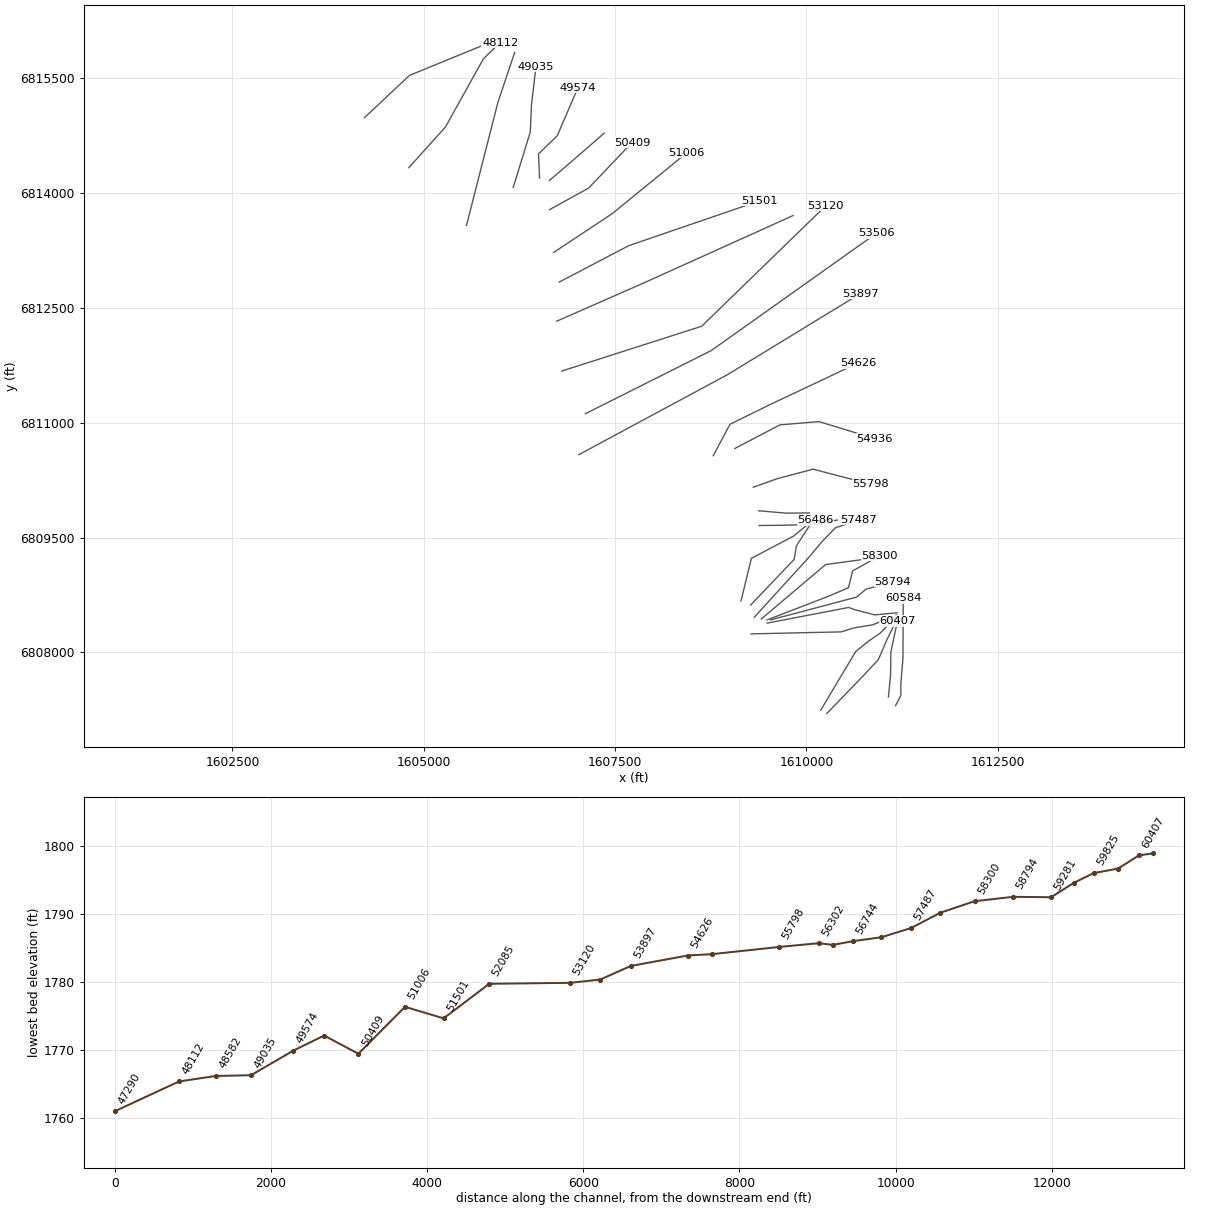
HEC-RAS study Lytle Creek.prj: Lytle Creek Base Level Engineering

--- Lytle Creek.g01 (geometry) --- (continued)

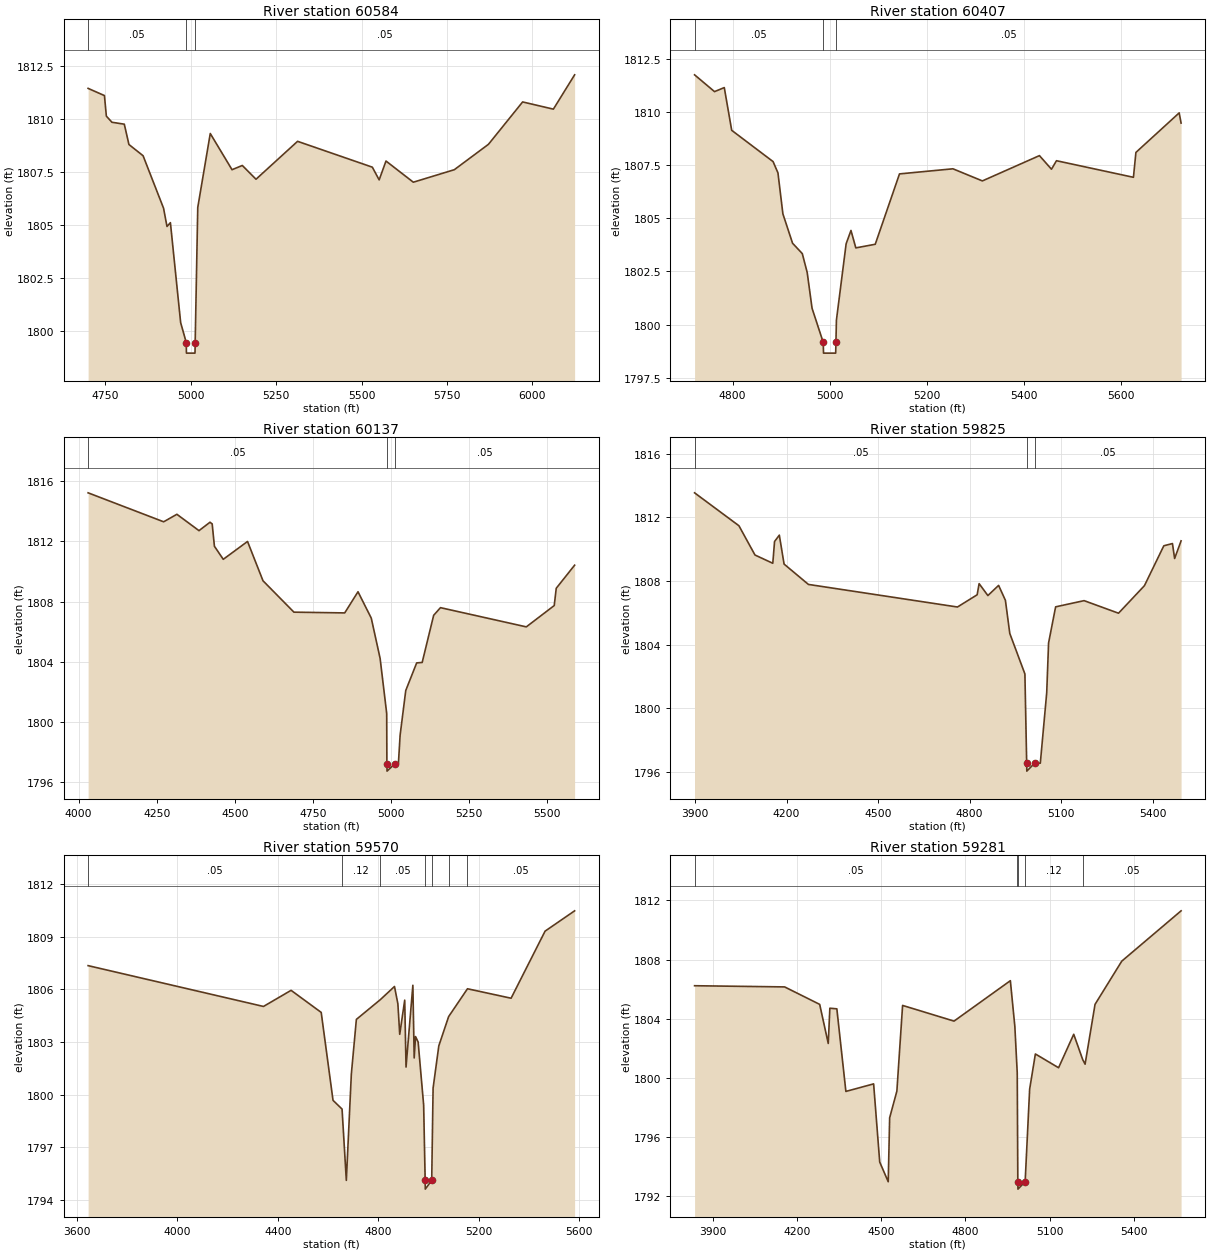
Type RM Length L Ch R = 1 ,60584   ,177,177,177
BEGIN DESCRIPTION:
Lytle Creek 60583.97
END DESCRIPTION:
XS GIS Cut Line= 5
      1611165.88      6807304.29      1611235.56       6807436.7
      1611235.56      6807590.65      1611262.68      6807928.99
      1611266.12      6808710.18
#Sta/Elev= 30
  4699.7 1811.44  4747.5  1811.1  4753.1 1810.13  4769.5 1809.84  4805.6 1809.75
  4819.2 1808.79  4860.6 1808.26  4920.6 1805.78  4930.6 1804.92  4940.6  1805.1
  4970.6 1800.38    4987 1799.44  4987.5 1798.94  5012.6 1798.94  5013.1 1799.44
  5020.7 1805.82  5057.3 1809.31    5121  1807.6  5151.1  1807.8  5191.2 1807.15
  5312.9 1808.94  5531.7 1807.72  5551.7 1807.12  5571.7 1808.01  5651.7 1807.01
  5771.7  1807.6  5871.7  1808.8  5971.7  1810.8  6061.7 1810.46  6123.9 1812.08
#Mann= 3 ,-1 , 0
  4699.7     .05       0    4987     .05       0  5013.1     .05       0
Bank Sta=4987,5013.1
XS Rating Curve= 0 ,0
Exp/Cntr=0.3,0.1

Type RM Length L Ch R = 1 ,60407   ,270,270,270
BEGIN DESCRIPTION:
Lytle Creek 60407.03
END DESCRIPTION:
XS GIS Cut Line= 4
      1611072.37      6807417.06      1611100.14      6807694.82
      1611104.59      6808004.37       1611190.3      6808409.27
#Sta/Elev= 30
  4721.8 1811.75  4762.9 1810.96    4783 1811.15  4798.3 1809.14  4883.5 1807.67
  4893.6 1807.14  4903.8 1805.21  4923.7 1803.83  4943.8 1803.34  4953.9 1802.45
  4963.9 1800.77    4987 1799.16  4987.5 1798.66  5012.6 1798.66  5013.1 1799.16
  5014.1 1800.21  5034.1  1803.8  5044.1 1804.43  5054.1 1803.61  5094.1 1803.78
  5144.1 1807.09  5254.2 1807.33  5314.9 1806.76  5432.5 1807.95  5457.3 1807.31
  5467.6 1807.71  5626.2 1806.93  5631.3  1808.1  5720.5 1809.96  5724.4 1809.48
#Mann= 3 ,-1 , 0
  4721.8     .05       0    4987     .04       0  5013.1     .05       0
Bank Sta=4987,5013.1
XS Rating Curve= 0 ,0
Exp/Cntr=0.3,0.1

Type RM Length L Ch R = 1 ,60137   ,312,312,312
BEGIN DESCRIPTION:
Lytle Creek 60136.79
END DESCRIPTION:
XS GIS Cut Line= 5
      1610268.73      6807202.36      1610738.38      6807688.48
      1610940.42      6807903.15      1611049.39      6808156.85
      1611185.38      6808436.72
#Sta/Elev= 30
  4030.2 1815.24  4272.1 1813.31  4314.5 1813.81  4385.3 1812.72  4420.5 1813.28
  4427.5 1813.17  4434.7 1811.68    4463 1810.81  4540.7    1812  4590.3 1809.38
  4689.3 1807.29    4852 1807.24  4894.5 1808.65    4937 1806.89  4965.3 1804.21
  4986.4 1800.54    4987  1797.2  4987.5  1796.7  5013.1  1797.2  5023.9  1797.2
  5029.3 1799.08  5047.4 1802.07  5082.4 1803.91    5100 1803.94  5136.8 1807.08
  5158.6 1807.59  5433.5 1806.31  5522.9 1807.73  5529.3 1808.88  5588.2 1810.42
#Mann= 3 ,-1 , 0
  4030.2     .05       0    4987     .05       0  5013.1     .05       0
Bank Sta=4987,5013.1
XS Rating Curve= 0 ,0
Exp/Cntr=0.3,0.1

Type RM Length L Ch R = 1 ,59825   ,255,255,255
BEGIN DESCRIPTION:
Lytle Creek 59825.13
END DESCRIPTION:
XS GIS Cut Line= 5
      1610187.98        6807244.      1610644.12      6808009.17
      1610807.52      6808142.53      1610962.51      6808249.09
      1611178.92      6808464.13
#Sta/Elev= 30
  3898.3 1813.54  4043.7 1811.47  4096.3 1809.63  4154.7 1809.11  4160.5 1810.48
  4176.1 1810.88  4191.7 1809.06  4271.5 1807.78  4760.1 1806.36  4824.7 1807.13
  4831.1 1807.83  4859.8 1807.08    4895 1807.72  4917.3 1806.78  4931.6  1804.7
  4981.2 1802.15    4987 1796.54  4987.5 1796.04  5013.1 1796.54  5031.7 1796.54
  5052.7 1800.97  5058.8  1804.1  5081.9 1806.37  5175.2 1806.76  5288.1 1805.97
    5373  1807.7  5436.6 1810.21  5464.9 1810.35    5472 1809.41  5493.2 1810.52
#Mann= 3 ,-1 , 0
  3898.3     .05       0    4987     .05       0  5013.1     .05       0
Bank Sta=4987,5013.1
XS Rating Curve= 0 ,0
Exp/Cntr=0.3,0.1

Type RM Length L Ch R = 1 ,59570   ,289,289,289
BEGIN DESCRIPTION:
Lytle Creek 59569.64
END DESCRIPTION:
XS GIS Cut Line= 5
      1609276.49      6808241.42      1610456.22      6808267.46
      1610621.41      6808319.12      1610867.94       6808359.6
      1611177.53       6808488.8
#Sta/Elev= 30
  3644.1 1807.36  4342.8 1805.03  4452.8 1805.95  4572.8 1804.69  4619.9 1799.67
  4655.9 1799.17  4672.9  1795.1  4692.9 1801.17  4712.9 1804.29  4808.5 1805.42
  4864.8 1806.17  4878.3 1805.18  4885.7 1803.44  4905.5 1805.39  4910.8 1801.57
    4938 1806.24  4943.3 1802.09  4948.6 1803.31    4959    1803    4981  1799.4
    4987  1795.1  4987.5  1794.6  5013.1  1795.1  5018.6 1800.37  5041.4 1802.78
  5080.5 1804.45  5155.6 1806.04  5329.4  1805.5  5464.8 1809.33  5582.5 1810.49
#Mann= 7 ,-1 , 0
  3644.1     .05       0  4655.9     .12       0  4808.5     .05       0
    4987     .05       0  5013.1     .05       0  5080.5     .12       0
  5155.6     .05       0
Bank Sta=4987,5013.1
XS Rating Curve= 0 ,0
Exp/Cntr=0.3,0.1

Type RM Length L Ch R = 1 ,59281   ,487,487,487
BEGIN DESCRIPTION:
Lytle Creek 59281.01
END DESCRIPTION:
XS GIS Cut Line= 5
      1609487.43      6808382.04      1610554.23      6808586.85
      1610623.58      6808560.01      1610895.12      6808489.41
      1611185.35      6808517.46
#Sta/Elev= 30
  3835.7 1806.23  4156.5 1806.15  4281.3 1804.97  4311.8 1802.33  4317.5 1804.71
  4342.4 1804.67  4374.6 1799.09  4473.4  1799.6  4495.1 1794.32  4525.4 1792.99
  4530.5 1797.31  4556.2 1799.11  4576.6  1804.9  4759.8 1803.84  4960.4 1806.57
  4976.4 1803.48  4984.9 1800.34  4985.6 1797.89    4987 1792.99  4987.5 1792.49
  5013.1 1792.99  5029.1 1799.24  5049.5 1801.62  5132.1 1800.69  5186.1 1802.95
  5218.3 1801.23  5226.6 1800.93    5262 1804.97  5357.2 1807.89  5568.5 1811.29
#Mann= 5 ,-1 , 0
  3835.7     .05       0  4985.6     .12       0    4987     .07       0
  5013.1     .12       0  5218.3     .05       0
Bank Sta=4987,5013.1
XS Rating Curve= 0 ,0
Exp/Cntr=0.3,0.1

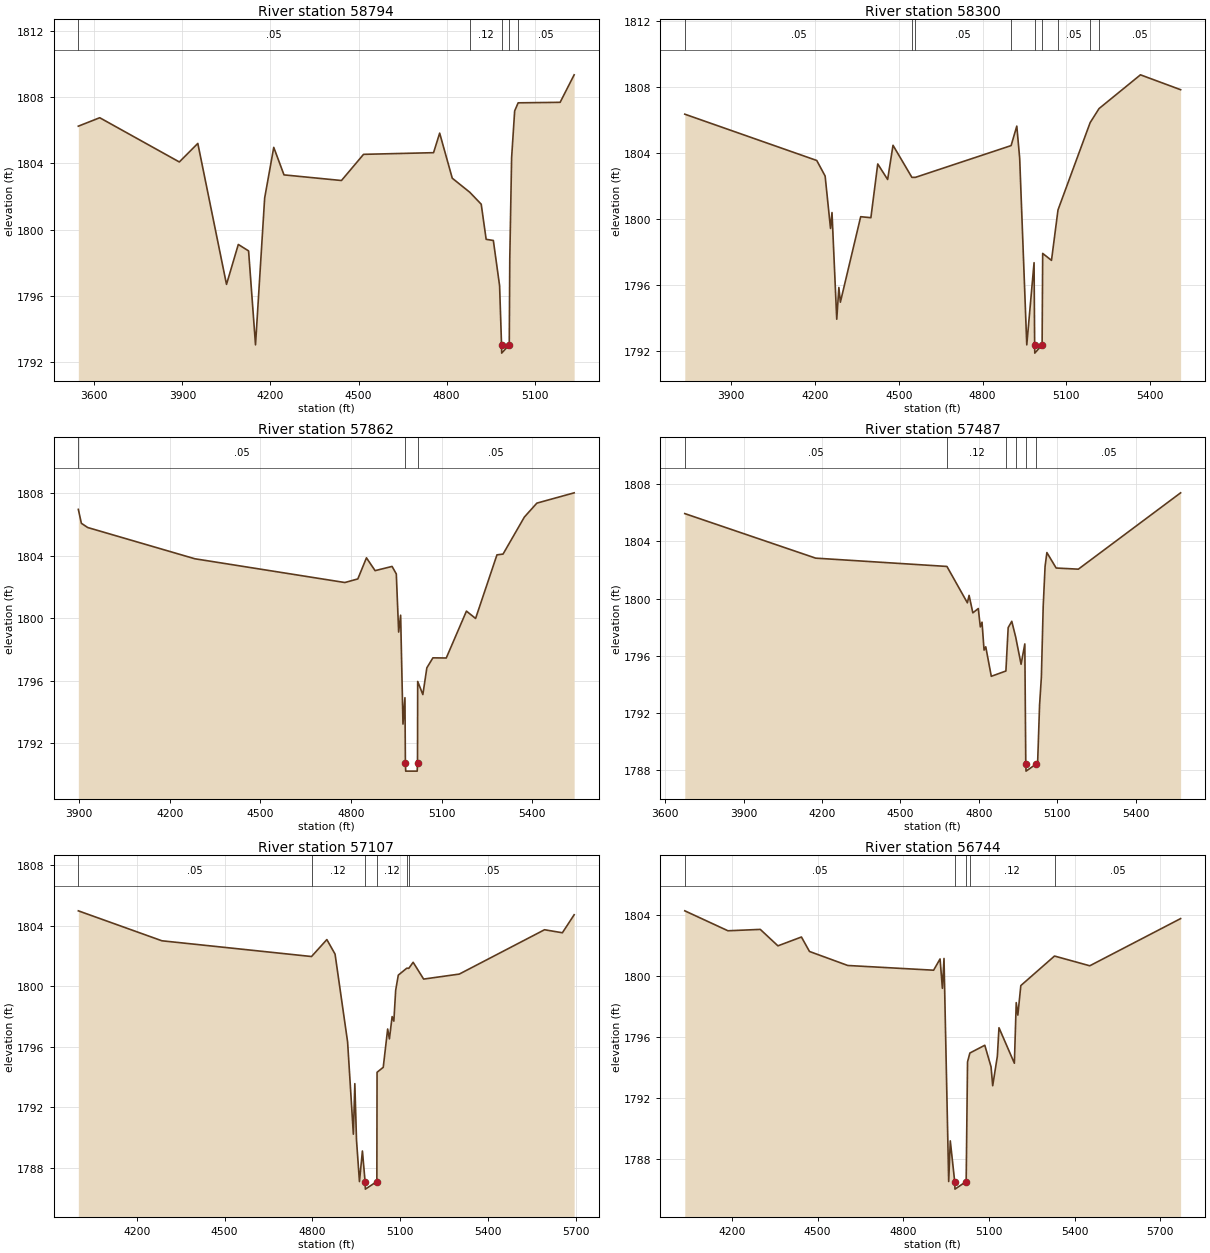
Type RM Length L Ch R = 1 ,58794   ,494,494,494
BEGIN DESCRIPTION:
Lytle Creek 58794.3
END DESCRIPTION:
XS GIS Cut Line= 5
      1609531.74      6808423.71       1610657.4      6808722.42
      1610781.74      6808827.36      1610905.26      6808859.16
      1611129.25      6808925.58
#Sta/Elev= 30
  3545.7 1806.25  3618.6 1806.76  3889.6 1804.09  3952.6 1805.21  4050.3  1796.7
  4090.5 1799.11  4125.5 1798.72  4149.1 1793.05  4180.2 1801.91  4211.2 1804.97
  4246.1 1803.31  4441.8 1802.97    4517 1804.55  4755.4 1804.65  4776.2 1805.83
  4819.1 1803.11  4878.8 1802.26  4917.7 1801.54  4934.5 1799.42    4959 1799.35
  4980.3 1796.62  4986.9 1793.05  4987.4 1792.55  5013.2 1793.05    5015 1798.26
  5021.2 1804.34  5031.6 1807.17  5043.5 1807.66  5186.4 1807.69  5234.2 1809.35
#Mann= 5 ,-1 , 0
  3545.7     .05       0  4878.8     .12       0  4986.9     .07       0
  5013.2     .12       0  5043.5     .05       0
Bank Sta=4986.9,5013.2
XS Rating Curve= 0 ,0
Exp/Cntr=0.3,0.1

Type RM Length L Ch R = 1 ,58300   ,438,438,438
BEGIN DESCRIPTION:
Lytle Creek 59575.975
END DESCRIPTION:
XS GIS Cut Line= 5
      1609487.43       6808423.7      1610284.35        6808731.
      1610551.05      6808844.69      1610604.66      6809064.34
      1610958.42      6809261.44
#Sta/Elev= 30
  3734.2 1806.35  4206.6 1803.55  4236.6 1802.61  4255.9 1799.44  4261.2  1800.4
  4278.2 1793.95  4285.8 1795.87  4291.2 1794.98  4363.9 1800.15  4400.4 1800.09
    4425 1803.34  4460.4  1802.4  4479.6 1804.47  4547.2 1802.53  4559.9 1802.53
  4902.4 1804.45  4922.8 1805.63  4933.1 1803.69  4958.5  1792.4  4984.6 1797.37
  4986.7  1792.4  4987.2  1791.9  5013.4  1792.4  5015.5 1797.93    5047 1797.51
  5070.3 1800.56  5185.4 1805.84  5217.3 1806.69  5365.5 1808.73  5509.3 1807.83
#Mann= 9 ,-1 , 0
  3734.2     .05       0  4547.2     .12       0  4559.9     .05       0
  4902.4     .12       0  4986.7     .07       0  5013.4     .12       0
  5070.3     .05       0  5185.4     .12       0  5217.3     .05       0
Bank Sta=4986.7,5013.4
XS Rating Curve= 0 ,0
Exp/Cntr=0.3,0.1

Type RM Length L Ch R = 1 ,57862   ,375,375,375
BEGIN DESCRIPTION:
Lytle Creek 57862.05
END DESCRIPTION:
XS GIS Cut Line= 3
      1609411.96      6808436.74      1610251.88      6809147.27
       1610788.3      6809220.18
#Sta/Elev= 30
  3897.2 1806.96  3907.3 1806.07  3928.2  1805.8    4283  1803.8  4779.6 1802.28
  4822.5 1802.51  4851.1 1803.86  4879.7 1803.04  4935.9 1803.31  4949.9 1802.83
  4957.7 1799.11  4964.2 1800.19    4972 1793.22  4978.5 1794.91    4980 1790.71
    4981 1790.21  5019.1 1790.21  5020.1 1790.71  5020.7 1795.95  5037.8 1795.11
    5051 1796.82  5071.1 1797.46  5115.3 1797.45  5182.1 1800.45  5212.4 1799.98
  5283.1 1804.05  5303.3  1804.1  5373.9 1806.47  5415.2 1807.36  5538.7 1808.02
#Mann= 3 ,-1 , 0
  3897.2     .05       0    4980     .05       0  5020.1     .05       0
Bank Sta=4980,5020.1
XS Rating Curve= 0 ,0
Exp/Cntr=0.3,0.1

Type RM Length L Ch R = 1 ,57487   ,380,380,380
BEGIN DESCRIPTION:
Lytle Creek 57486.78
END DESCRIPTION:
XS GIS Cut Line= 5
      1609318.21      6808457.57      1610021.99      6809229.61
       1610202.4      6809444.15      1610378.08      6809626.85
      1610680.08      6809730.97
#Sta/Elev= 30
  3674.7 1805.93  4175.6 1802.82  4678.1 1802.24  4756.4  1799.7  4762.9 1800.22
  4777.3    1799  4798.1  1799.3  4805.9 1798.02  4812.4 1798.35  4820.2  1796.4
  4826.7 1796.63  4847.9 1794.57  4903.8 1794.94  4912.5 1797.97  4926.3 1798.41
  4941.4  1797.3  4961.9 1795.41  4976.2 1796.83  4979.9 1788.45  4980.9 1787.95
  5020.1 1788.45  5025.5 1788.66  5032.7 1792.56  5039.6 1794.51  5046.6 1799.46
  5053.8 1802.25  5060.7 1803.21  5096.2 1802.13  5181.1 1802.05  5572.6 1807.38
#Mann= 6 ,-1 , 0
  3674.7     .05       0  4678.1     .12       0  4903.8     .05       0
  4941.4     .12       0  4979.9     .07       0  5020.1     .05       0
Bank Sta=4979.9,5020.1
XS Rating Curve= 0 ,0
Exp/Cntr=0.3,0.1

Type RM Length L Ch R = 1 ,57107   ,363,363,363
BEGIN DESCRIPTION:
Lytle Creek 57107.41
END DESCRIPTION:
XS GIS Cut Line= 5
      1609271.88       6808617.7      1609841.84      6809216.51
      1609869.06      6809389.46      1610048.21      6809665.44
      1610404.61      6809728.84
#Sta/Elev= 30
  4000.9 1804.99  4286.3 1803.01    4797 1801.97  4849.4 1803.09  4877.4 1802.13
  4920.2 1796.33  4939.9 1790.23  4944.9 1793.57  4950.6 1789.84  4960.7  1787.1
  4970.8 1789.12  4979.9  1787.1  4980.9  1786.6  5020.1  1787.1  5020.8 1794.32
  5041.9 1794.65    5057 1797.18    5063 1796.53  5072.2    1798  5078.1  1797.7
  5084.4 1799.75  5093.3 1800.74  5122.3  1801.2  5129.2 1801.19    5144 1801.59
  5179.8 1800.48  5301.6 1800.81  5592.5 1803.74  5653.5 1803.54  5693.7 1804.73
#Mann= 6 ,-1 , 0
  4000.9     .05       0    4797     .12       0  4979.9     .07       0
  5020.1     .12       0  5122.3     .12       0  5129.2     .05       0
Bank Sta=4979.9,5020.1
XS Rating Curve= 0 ,0
Exp/Cntr=0.3,0.1

Type RM Length L Ch R = 1 ,56744   ,258,258,258
BEGIN DESCRIPTION:
Mapping XS 555dad79
END DESCRIPTION:
XS GIS Cut Line= 5
      1609146.33      6808671.13      1609281.74       6809228.4
      1609833.83      6809520.07      1610036.95      6809686.73
      1610308.47      6809733.28
#Sta/Elev= 30
  4034.9  1804.3    4186 1802.99  4299.2 1803.08    4361    1802  4443.3 1802.58
  4471.5 1801.63  4605.6 1800.71  4906.1  1800.4  4928.7 1801.14  4936.9 1799.21
  4942.5 1801.17  4958.9 1786.52  4964.5 1789.19  4979.9 1786.52  4980.9 1786.02
  5020.1 1786.52  5024.9 1794.38  5033.1 1794.96  5085.3 1795.47  5107.3 1794.05
    5113 1792.81  5129.3 1794.75    5135 1796.62  5188.9 1794.29  5195.4 1798.27
    5201 1797.45  5211.5 1799.39  5329.4 1801.33  5452.9 1800.69    5771 1803.79
#Mann= 5 ,-1 , 0
  4034.9     .05       0  4979.9     .05       0  5020.1     .05       0
  5033.1     .12       0  5329.4     .05       0
Bank Sta=4979.9,5020.1
XS Rating Curve= 0 ,0
Exp/Cntr=0.3,0.1

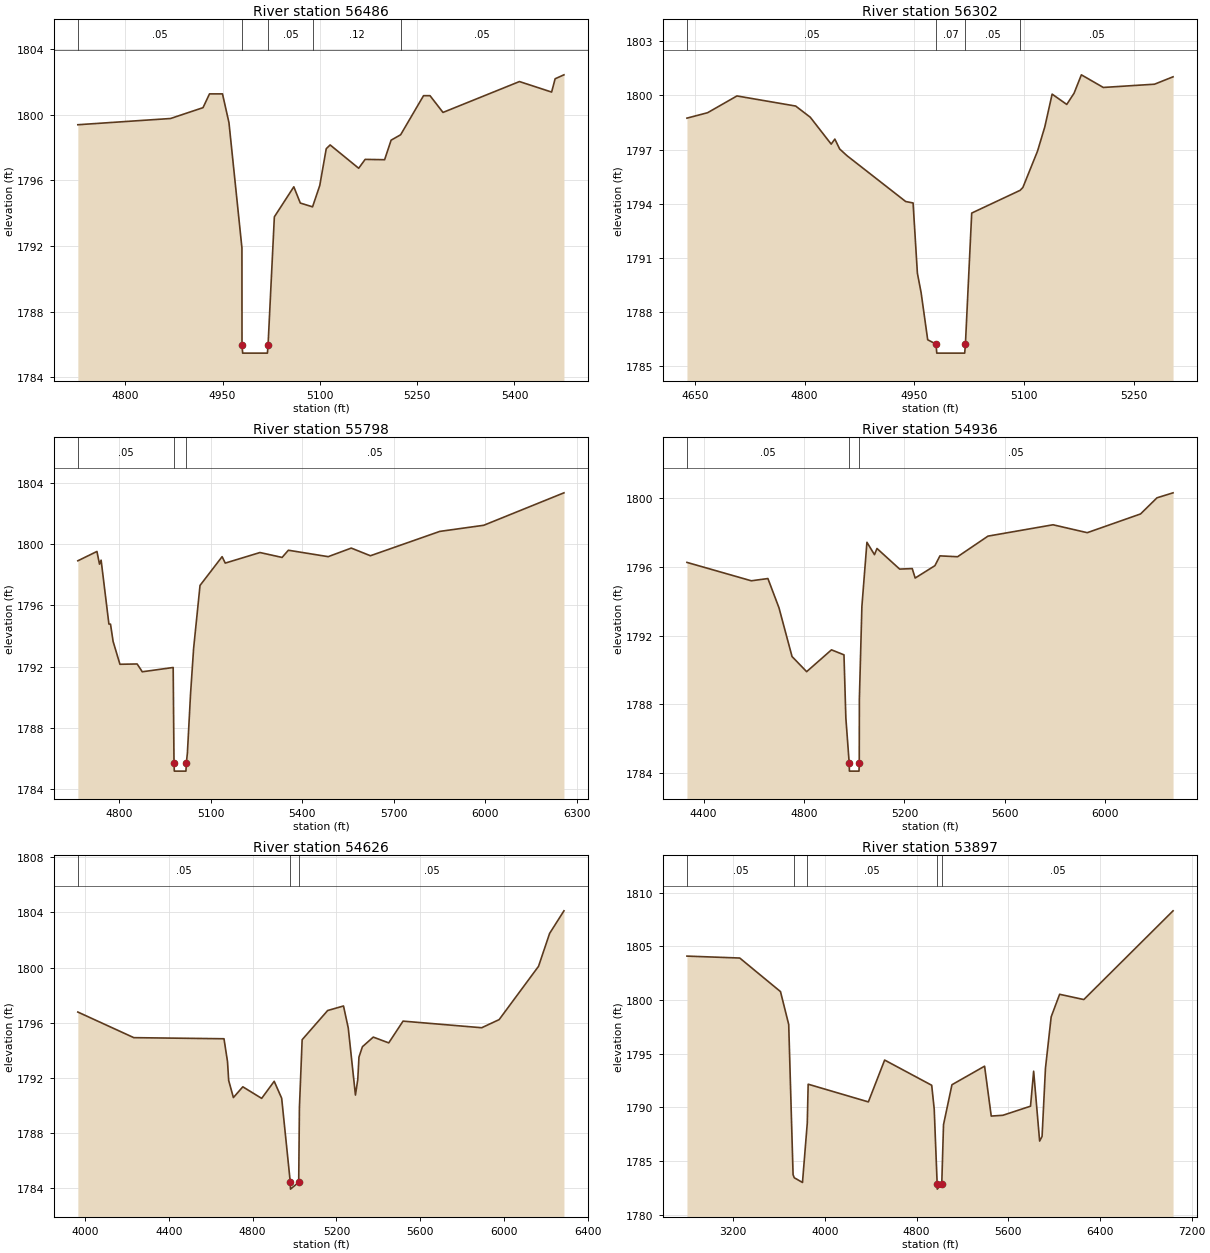
Type RM Length L Ch R = 1 ,56486   ,184,184,184
BEGIN DESCRIPTION:
Lytle Creek 56486.22
END DESCRIPTION:
XS GIS Cut Line= 4
      1609382.04      6809657.69      1609652.92      6809660.29
      1609957.64      6809667.22      1610120.18      6809728.79
#Sta/Elev= 30
  4726.8 1799.39  4869.8 1799.77  4919.8 1800.43  4929.8 1801.27  4949.8 1801.27
  4959.8 1799.52  4979.8 1791.89  4979.9 1785.98  4980.9 1785.48  5019.1 1785.48
  5020.1 1785.98  5029.8 1793.78  5059.8 1795.61  5069.8 1794.62  5088.7 1794.39
  5099.8 1795.69  5109.8 1797.93  5115.8 1798.16  5159.8 1796.74  5169.8 1797.28
  5199.8 1797.26  5209.8 1798.45  5224.5 1798.78  5259.8 1801.16  5269.8 1801.16
  5289.8 1800.14  5407.7 1802.02  5457.3 1801.38  5462.7 1802.19  5476.3 1802.43
#Mann= 5 ,-1 , 0
  4726.8     .05       0  4979.9     .05       0  5020.1     .05       0
  5088.7     .12       0  5224.5     .05       0
Bank Sta=4979.9,5020.1
XS Rating Curve= 0 ,0
Exp/Cntr=0.3,0.1

Type RM Length L Ch R = 1 ,56302   ,504,504,504
BEGIN DESCRIPTION:
Lytle Creek 56301.97
END DESCRIPTION:
XS GIS Cut Line= 3
      1609376.91      6809850.39      1609736.25      6809819.15
      1610040.44      6809821.75
#Sta/Elev= 30
  4639.2 1798.74  4667.4 1799.04  4707.6 1799.97  4787.9 1799.41  4807.9 1798.79
  4836.5  1797.3  4841.5 1797.58  4848.1 1797.03  4858.1 1796.66  4938.4 1794.12
  4948.5 1794.04  4954.4 1790.15  4959.5 1789.07  4968.5 1786.46  4979.9 1786.22
  4980.9 1785.72  5019.1 1785.72  5020.1 1786.22  5028.7 1793.48  5094.9 1794.74
  5098.7  1794.9  5118.7 1796.91  5128.7 1798.26  5138.7 1800.07  5158.7  1799.5
  5168.7 1800.12  5178.7 1801.14  5208.7 1800.44  5278.7 1800.62  5304.1 1801.03
#Mann= 4 ,-1 , 0
  4639.2     .05       0  4979.9     .07       0  5020.1     .05       0
  5094.9     .05       0
Bank Sta=4979.9,5020.1
XS Rating Curve= 0 ,0
Exp/Cntr=0.3,0.1

Type RM Length L Ch R = 1 ,55798   ,862,862,862
BEGIN DESCRIPTION:
Lytle Creek 55798.38
END DESCRIPTION:
XS GIS Cut Line= 4
      1609306.03       6810158.2      1609621.15      6810270.19
      1610088.41      6810394.01       1610838.7      6810197.55
#Sta/Elev= 30
  4664.7 1798.91  4727.3 1799.52  4735.7 1798.69    4741 1798.95  4766.5 1794.78
  4771.8 1794.77  4780.3 1793.64  4802.7 1792.15  4859.1 1792.17  4875.9 1791.66
  4977.2 1791.94  4979.9 1785.67  4980.9 1785.17  5019.1 1785.17  5020.1 1785.67
  5023.8 1786.35  5034.1  1790.2  5044.2 1793.19  5065.2  1797.3  5137.6 1799.18
  5147.9 1798.76  5261.7 1799.45  5334.2 1799.13  5354.8  1799.6  5485.3 1799.18
    5561 1799.74  5623.7 1799.24  5851.1 1800.83  5995.2 1801.23  6258.1 1803.35
#Mann= 3 ,-1 , 0
  4664.7     .05       0  4979.9     .03       0  5020.1     .05       0
Bank Sta=4979.9,5020.1
XS Rating Curve= 0 ,0
Exp/Cntr=0.3,0.1

Type RM Length L Ch R = 1 ,54936   ,310,310,310
BEGIN DESCRIPTION:
Lytle Creek 55595.381
END DESCRIPTION:
XS GIS Cut Line= 4
      1609063.89      6810663.44      1609654.48      6810972.78
       1610164.4      6811015.96      1610890.39      6810794.02
#Sta/Elev= 30
  4333.3 1796.26  4589.8 1795.19    4656 1795.32  4700.1 1793.62  4752.2 1790.78
  4810.4  1789.9  4909.4 1791.17  4959.2 1790.88  4966.7  1787.2  4979.9 1784.61
  4980.9 1784.11  5019.1 1784.11  5020.1 1784.61  5020.6 1788.31  5030.6 1793.69
  5050.7 1797.43  5080.8 1796.71  5090.8 1797.07  5181.2 1795.87  5231.3  1795.9
    5243 1795.35  5321.7 1796.07  5341.7 1796.64    5412 1796.59  5533.3 1797.79
  5792.5 1798.45  5928.9 1797.99  6141.3 1799.08  6206.9 1800.02  6270.9 1800.31
#Mann= 3 ,-1 , 0
  4333.3     .05       0  4979.9     .03       0  5020.1     .05       0
Bank Sta=4979.9,5020.1
XS Rating Curve= 0 ,0
Exp/Cntr=0.3,0.1

Type RM Length L Ch R = 1 ,54626   ,729,729,729
BEGIN DESCRIPTION:
Lytle Creek 54428.227
END DESCRIPTION:
XS GIS Cut Line= 4
      1608783.06      6810569.74      1609001.97      6810980.83
      1609511.97      6811231.46      1610674.69      6811780.89
#Sta/Elev= 30
    3966 1796.77  4233.2 1794.91  4663.5 1794.83  4680.3 1793.17  4685.9  1791.8
  4708.4 1790.56  4753.4 1791.34  4843.3  1790.5  4903.1 1791.74  4938.8 1790.51
  4979.9 1784.41  4980.9 1783.91  5020.1 1784.41  5023.5 1789.82  5036.5 1794.76
  5158.2 1796.88  5233.9 1797.21  5256.6 1795.61  5290.9 1790.74    5302 1791.87
  5307.7  1793.5  5324.1 1794.25    5376 1794.95  5449.8 1794.53  5518.1 1796.11
  5893.4 1795.63  5976.7 1796.22  6164.7 1800.09  6217.6 1802.48    6286 1804.12
#Mann= 3 ,-1 , 0
    3966     .05       0  4979.9     .03       0  5020.1     .05       0
Bank Sta=4979.9,5020.1
XS Rating Curve= 0 ,0
Exp/Cntr=0.3,0.1

Type RM Length L Ch R = 1 ,53897   ,391,391,391
BEGIN DESCRIPTION:
Lytle Creek 53829.901
END DESCRIPTION:
XS GIS Cut Line= 3
      1607026.61      6810583.49      1608965.91      6811626.96
      1610704.98      6812687.99
#Sta/Elev= 30
  2797.8 1804.09  3258.5 1803.91  3613.6 1800.78  3685.3 1797.72  3723.4 1783.71
  3733.8 1783.43  3805.4 1782.99  3847.3 1788.54  3854.9 1792.15  4379.9  1790.5
  4521.9  1794.4  4932.4 1792.05  4954.3 1789.82  4979.9 1782.87  4980.9 1782.37
  5020.1 1782.87  5035.4 1788.38  5108.9  1792.1  5393.5 1793.83  5451.6 1789.18
  5552.3 1789.25  5794.2  1790.1  5821.4 1793.36  5873.6 1786.85  5894.9 1787.28
  5924.4 1793.63  5974.3 1798.43  6047.9 1800.53  6258.9 1800.04  7037.2 1808.31
#Mann= 5 ,-1 , 0
  2797.8     .05       0  3733.8     .12       0  3847.3     .05       0
  4979.9     .03       0  5020.1     .05       0
Bank Sta=4979.9,5020.1
XS Rating Curve= 0 ,0
Exp/Cntr=0.3,0.1

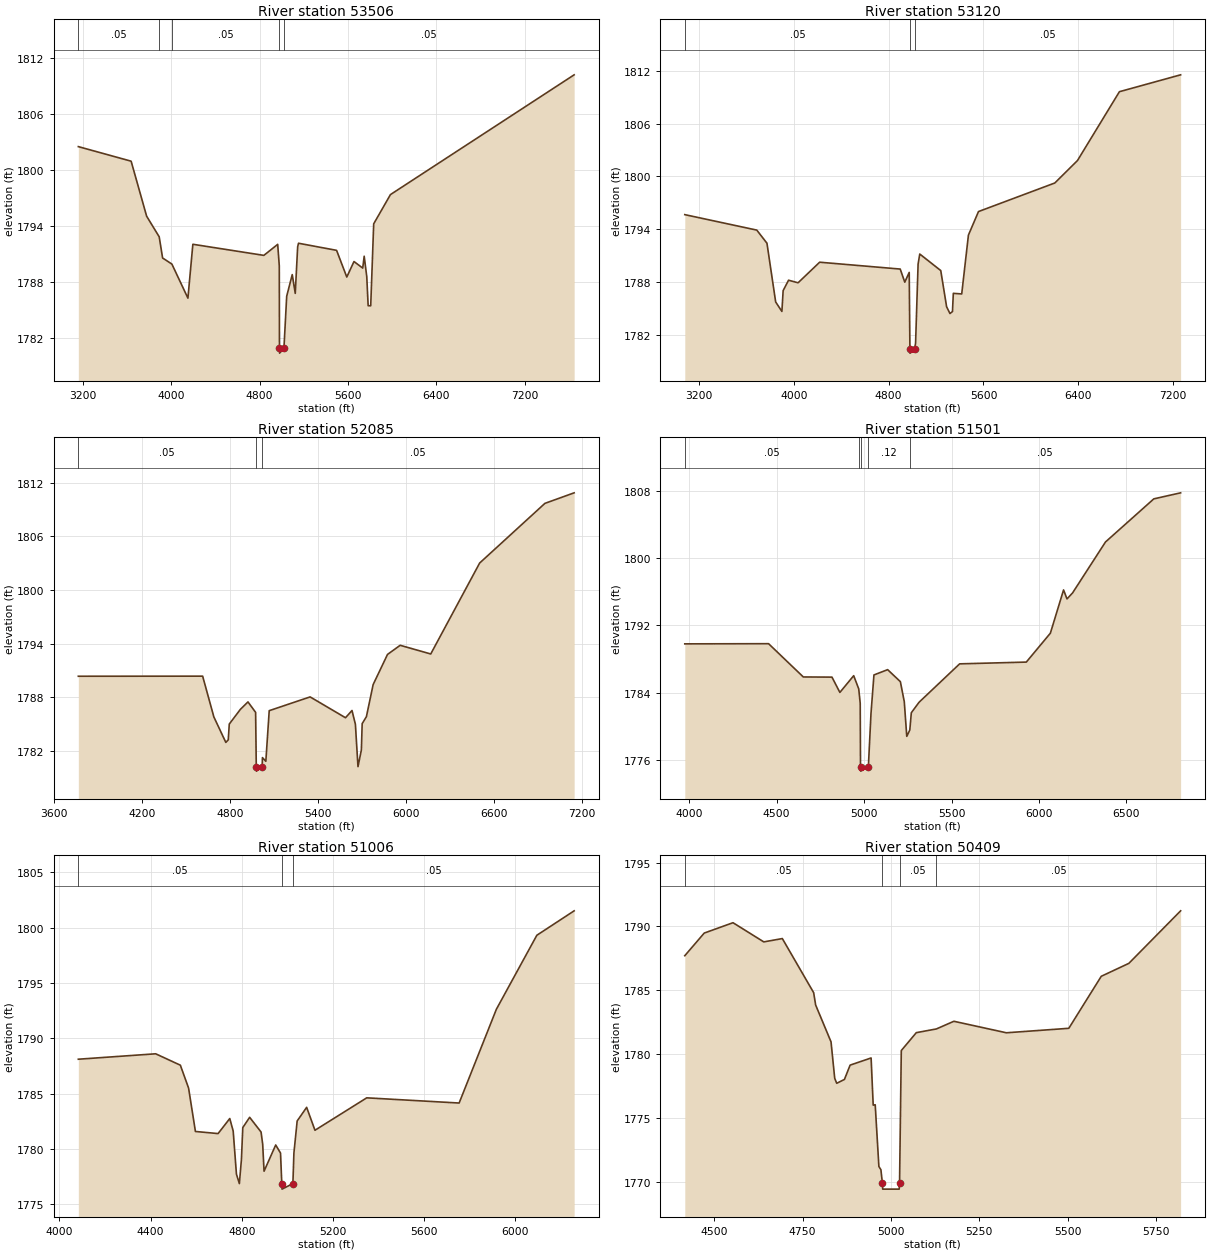
Type RM Length L Ch R = 1 ,53506   ,386,386,386
BEGIN DESCRIPTION:
Lytle Creek 53266.654
END DESCRIPTION:
XS GIS Cut Line= 3
      1607112.65      6811118.96      1608757.24      6811943.93
      1610914.75      6813475.74
#Sta/Elev= 30
  3160.1 1802.49  3637.8 1800.93    3778 1795.04  3891.7 1792.83  3922.6 1790.56
  4006.5 1789.91  4151.6 1786.26  4196.3 1792.03  4838.5 1790.84  4963.9 1792.02
  4978.2 1789.72  4979.9 1780.87  4980.9 1780.37  5020.2 1780.87  5045.2 1786.46
  5095.4 1788.78  5122.7 1786.77  5144.4 1791.75  5152.2 1792.14  5496.6 1791.38
  5588.9 1788.52  5654.1 1790.18  5733.1 1789.48  5746.3 1790.75  5769.7 1788.56
  5782.2 1785.45  5805.4 1785.44  5832.4 1794.22  5983.8 1797.35    7646 1810.18
#Mann= 5 ,-1 , 0
  3160.1     .05       0  3891.7     .12       0  4006.5     .05       0
  4979.9     .03       0  5020.2     .05       0
Bank Sta=4979.9,5020.2
XS Rating Curve= 0 ,0
Exp/Cntr=0.3,0.1

Type RM Length L Ch R = 1 ,53120   ,1035,1035,1035
BEGIN DESCRIPTION:
Lytle Creek 52677.451
END DESCRIPTION:
XS GIS Cut Line= 3
      1606805.27      6811676.81      1608631.99      6812261.77
      1610254.97      6813837.97
#Sta/Elev= 30
  3081.9 1795.64  3688.9 1793.88  3774.6 1792.39  3848.1 1785.71  3900.6 1784.63
  3911.1    1787  3956.6 1788.18  4037.1 1787.89    4219 1790.23  4898.2 1789.45
  4936.7 1787.96  4974.1 1789.07  4979.9 1780.39  4980.9 1779.89  5020.2 1780.39
  5027.8 1781.05  5048.9 1790.01    5063 1791.16    5240 1789.28  5289.4 1785.16
  5317.7 1784.39  5338.8 1784.62    5346 1786.69  5416.7 1786.62  5473.3 1793.31
  5558.2 1795.99  6201.8 1799.24  6392.6 1801.79  6746.3 1809.62  7262.4 1811.54
#Mann= 3 ,-1 , 0
  3081.9     .05       0  4979.9     .03       0  5020.2     .05       0
Bank Sta=4979.9,5020.2
XS Rating Curve= 0 ,0
Exp/Cntr=0.3,0.1

Type RM Length L Ch R = 1 ,52085   ,584,584,584
BEGIN DESCRIPTION:
Lytle Creek 52085.131
END DESCRIPTION:
XS GIS Cut Line= 3
      1606738.43      6812328.29       1607868.4      6812824.69
      1609826.93      6813708.47
#Sta/Elev= 30
  3765.8 1790.36    4614 1790.37  4690.5 1785.81  4772.2 1782.96  4788.8 1783.25
  4795.6 1785.01  4871.1 1786.65  4923.2 1787.49  4975.4 1786.32  4979.9 1780.25
  4980.9 1779.75  5020.2 1780.25  5021.9 1781.26  5045.1 1780.85  5068.2 1786.51
  5347.3 1788.05  5588.7 1785.72    5633 1786.53  5656.2 1784.99  5673.8 1780.25
  5696.9 1782.12  5702.4 1785.06  5731.3 1785.84  5777.3 1789.43  5875.3  1792.8
  5961.7 1793.82  6170.2 1792.85    6504 1803.02  6949.1 1809.69  7148.7 1810.87
#Mann= 3 ,-1 , 0
  3765.8     .05       0  4979.9     .05       0  5020.2     .05       0
Bank Sta=4979.9,5020.2
XS Rating Curve= 0 ,0
Exp/Cntr=0.3,0.1

Type RM Length L Ch R = 1 ,51501   ,495,495,495
BEGIN DESCRIPTION:
Lytle Creek 51500.99
END DESCRIPTION:
XS GIS Cut Line= 3
      1606769.64      6812838.68      1607677.77      6813314.43
      1609389.49      6813901.21
#Sta/Elev= 30
  3974.8 1789.81  4453.8 1789.83  4652.3 1785.87  4816.2 1785.85  4861.4 1784.03
  4940.4 1786.02  4969.2 1784.45  4977.7 1782.73  4979.4 1775.16  4980.4 1774.66
  5020.7 1775.16    5025 1775.48  5039.4 1781.55  5056.2 1786.11  5134.5 1786.74
  5207.3 1785.31  5229.6 1782.93  5243.9  1778.8  5261.2 1779.55  5269.9 1781.61
  5314.2 1782.86  5546.1 1787.43  5927.3 1787.64  6064.8 1791.08  6140.3 1796.23
  6159.9 1795.16  6191.6 1795.87    6380 1801.94  6656.2 1807.07  6809.5 1807.79
#Mann= 5 ,-1 , 0
  3974.8     .05       0  4969.2     .12       0  4979.4     .07       0
  5020.7     .12       0  5261.2     .05       0
Bank Sta=4979.4,5020.7
XS Rating Curve= 0 ,0
Exp/Cntr=0.3,0.1

Type RM Length L Ch R = 1 ,51006   ,597,597,597
BEGIN DESCRIPTION:
Lytle Creek 50902.465
END DESCRIPTION:
XS GIS Cut Line= 3
      1606696.74      6813226.01      1607461.08      6813732.08
      1608435.92      6814527.22
#Sta/Elev= 30
  4083.3  1788.1  4422.5 1788.59  4530.8 1787.56  4566.9 1785.49  4596.9 1781.57
  4696.3 1781.38  4747.5 1782.74  4762.5 1781.61  4776.8 1777.71  4789.6 1776.86
  4798.6 1779.03  4804.6 1781.92  4834.7 1782.85  4884.8 1781.52  4891.9 1780.42
  4897.9 1777.98    4949 1780.35  4970.1 1779.62  4975.7 1776.86  4976.7 1776.36
  5024.4 1776.86  5028.8 1779.61  5043.1 1782.52  5084.7 1783.75  5121.2 1781.68
  5348.3 1784.61  5753.5 1784.14    5917 1792.62  6094.3  1799.3    6258 1801.51
#Mann= 3 ,-1 , 0
  4083.3     .05       0  4975.7     .03       0  5024.4     .05       0
Bank Sta=4975.7,5024.4
XS Rating Curve= 0 ,0
Exp/Cntr=0.3,0.1

Type RM Length L Ch R = 1 ,50409   ,438,438,438
BEGIN DESCRIPTION:
Lytle Creek 50408.91
END DESCRIPTION:
XS GIS Cut Line= 3
      1606643.26      6813785.64      1607153.65      6814066.88
       1607719.6      6814660.61
#Sta/Elev= 30
  4416.7 1787.71  4471.7 1789.48  4553.1 1790.29  4640.2 1788.79  4692.7 1789.05
  4781.3 1784.82    4787 1783.85  4830.5 1780.97  4840.9 1778.12  4846.6 1777.73
  4868.4 1778.03  4884.5 1779.15  4943.9 1779.71  4949.8 1776.02  4955.5 1776.05
  4965.9 1771.22  4971.6 1770.97  4975.7 1769.95  4976.7 1769.45  5023.4 1769.45
  5024.4 1769.95  5029.3 1780.29  5071.8 1781.69  5128.6 1781.98  5178.1 1782.58
  5326.6 1781.68  5503.3 1782.03  5595.2  1786.1  5673.2 1787.11  5819.7 1791.22
#Mann= 4 ,-1 , 0
  4416.7     .05       0  4975.7     .07       0  5024.4     .05       0
  5128.6     .05       0
Bank Sta=4975.7,5024.4
XS Rating Curve= 0 ,0
Exp/Cntr=0.3,0.1

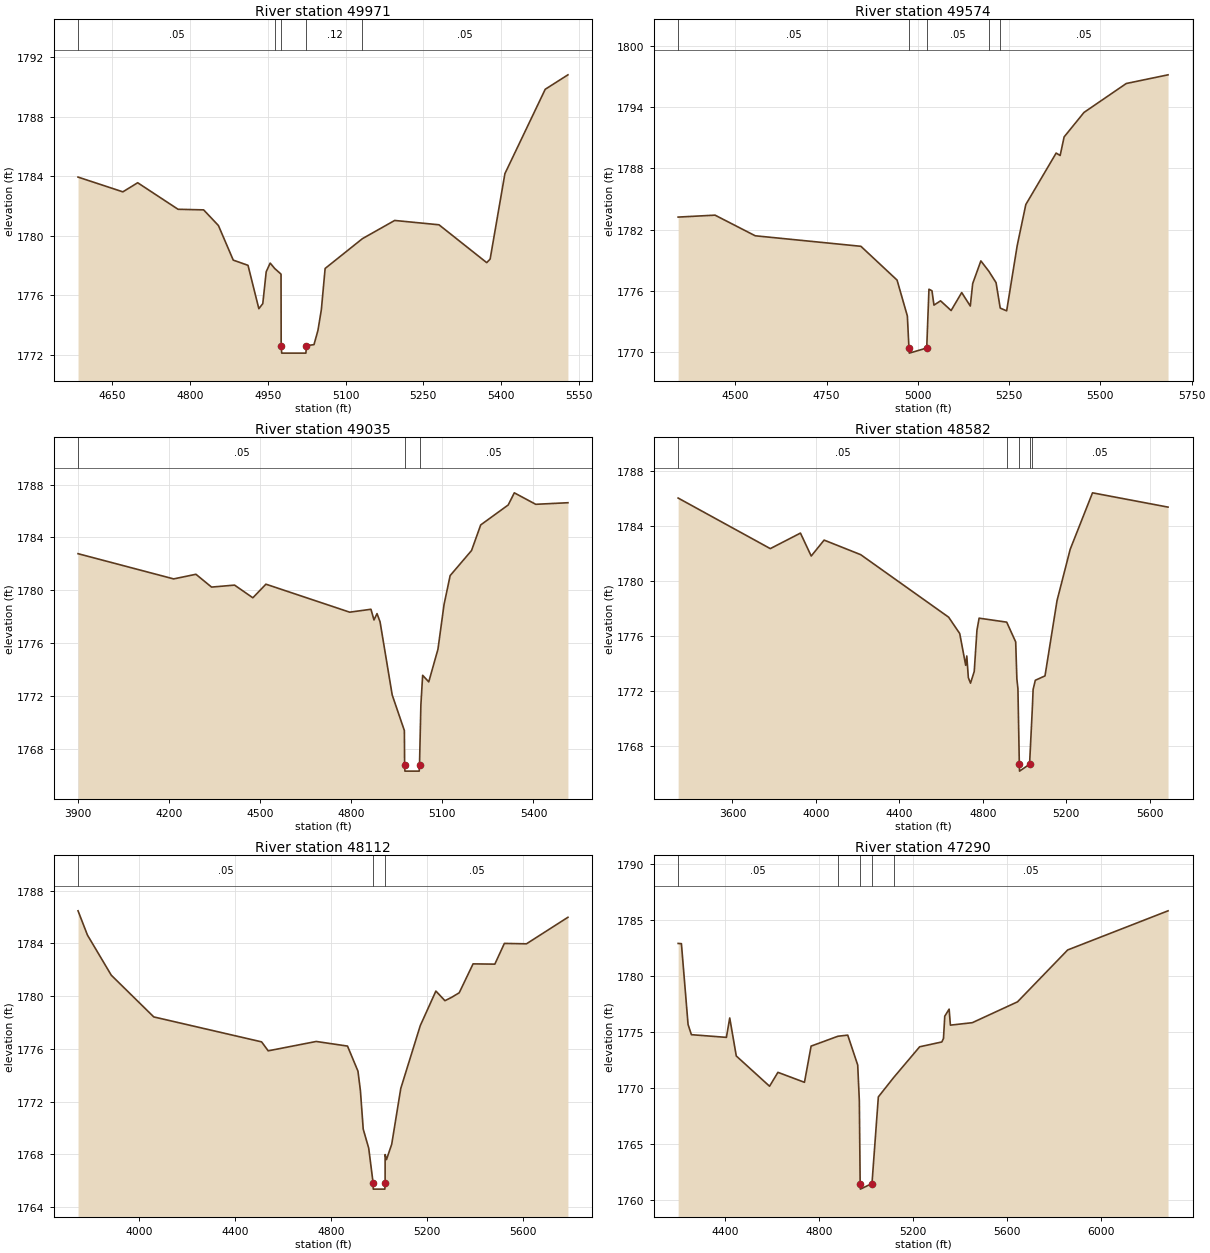
Type RM Length L Ch R = 1 ,49971   ,397,397,397
BEGIN DESCRIPTION:
Lytle Creek 49971.07
END DESCRIPTION:
XS GIS Cut Line= 3
      1606643.25      6814167.58      1606959.21      6814438.41
      1607358.51      6814785.63
#Sta/Elev= 30
  4583.7 1783.94  4670.2 1782.95  4698.8 1783.56  4776.7 1781.78  4826.1 1781.74
  4854.6 1780.69  4883.2 1778.37  4911.7 1778.02  4932.6 1775.11  4940.2 1775.45
  4946.8 1777.59  4954.5 1778.17  4963.4  1777.8  4975.4 1777.43  4975.7 1772.63
  4976.7 1772.13  5023.4 1772.13  5024.4 1772.63    5039  1772.7  5046.6 1773.65
  5053.2 1775.04  5060.5 1777.81  5132.5 1779.81  5194.7 1781.03  5280.2 1780.74
  5372.3  1778.2  5378.9 1778.44  5407.4 1784.17  5485.2 1789.83    5529  1790.8
#Mann= 5 ,-1 , 0
  4583.7     .05       0  4963.4     .12       0  4975.7     .07       0
  5024.4     .12       0  5132.5     .05       0
Bank Sta=4975.7,5024.4
XS Rating Curve= 0 ,0
Exp/Cntr=0.3,0.1

Type RM Length L Ch R = 1 ,49574   ,539,539,539
BEGIN DESCRIPTION:
Lytle Creek 49573.62
END DESCRIPTION:
XS GIS Cut Line= 4
      1606513.22      6814197.13      1606499.24      6814512.75
      1606743.93      6814750.91      1607014.75      6815379.35
#Sta/Elev= 30
  4343.6 1783.22  4444.6 1783.41  4554.7 1781.39  4844.1 1780.36  4943.2 1777.05
  4971.4 1773.53  4975.7  1770.4  4976.7  1769.9  5024.4  1770.4  5030.5 1776.16
  5038.8    1776  5044.2  1774.6  5062.3 1775.02  5091.2 1774.07  5120.2 1775.83
  5143.7 1774.51  5150.3 1776.71  5172.7 1778.93  5194.5 1777.92  5214.3  1776.8
  5225.7 1774.31  5243.3 1774.04  5272.2 1780.43  5295.8 1784.45  5378.9 1789.49
  5389.8 1789.25  5400.7 1791.07  5455.2 1793.47  5570.9  1796.3  5685.3 1797.15
#Mann= 5 ,-1 , 0
  4343.6     .05       0  4975.7     .05       0  5024.4     .05       0
  5194.5     .12       0  5225.7     .05       0
Bank Sta=4975.7,5024.4
XS Rating Curve= 0 ,0
Exp/Cntr=0.3,0.1

Type RM Length L Ch R = 1 ,49035   ,453,453,453
BEGIN DESCRIPTION:
Lytle Creek 49035.02
END DESCRIPTION:
XS GIS Cut Line= 4
       1606169.2      6814076.82      1606392.51       6814801.8
      1606407.12      6815146.74      1606466.12      6815653.37
#Sta/Elev= 30
  3899.6 1782.76  4214.7 1780.85    4288  1781.2  4339.5 1780.23  4415.3 1780.38
  4475.5 1779.42  4518.6 1780.45  4794.5 1778.33  4864.6 1778.55  4874.6 1777.74
  4884.6 1778.22  4894.6  1777.6  4934.6 1772.06  4974.7 1769.36  4975.5 1766.79
  4976.5 1766.29  5023.6 1766.29  5024.6 1766.79  5029.1 1771.31  5034.9 1773.55
    5055 1773.05  5085.3 1775.52  5105.4 1778.91  5125.5  1781.1    5196    1783
  5226.2 1784.94  5316.8 1786.45  5336.9 1787.37  5407.4  1786.5  5513.5 1786.62
#Mann= 3 ,-1 , 0
  3899.6     .05       0  4975.5     .05       0  5024.6     .05       0
Bank Sta=4975.5,5024.6
XS Rating Curve= 0 ,0
Exp/Cntr=0.3,0.1

Type RM Length L Ch R = 1 ,48582   ,470,470,470
BEGIN DESCRIPTION:
Lytle Creek 48676.464
END DESCRIPTION:
XS GIS Cut Line= 3
      1605558.51      6813579.82      1605968.89       6815188.6
      1606188.37      6815841.18
#Sta/Elev= 30
  3339.7 1786.05  3781.6 1782.37  3926.1  1783.5  3977.7 1781.83  4039.6 1782.99
    4215 1781.93  4636.7 1777.38  4689.8 1776.19  4718.4 1773.88  4723.6 1774.56
  4731.1 1772.98  4741.4 1772.58  4759.3 1773.43  4772.3 1776.43  4782.7 1777.31
    4915 1777.02  4958.1 1775.58  4963.7 1772.89  4968.8 1772.18  4975.5 1766.68
  4976.5 1766.18  5024.6 1766.68  5038.2 1770.85  5041.6 1772.12  5052.1 1772.79
  5098.6 1773.11  5156.3 1778.59  5219.4 1782.32  5326.4 1786.43  5688.5 1785.39
#Mann= 5 ,-1 , 0
  3339.7     .05       0    4915     .12       0  4975.5     .07       0
  5024.6     .12       0  5038.2     .05       0
Bank Sta=4975.5,5024.6
XS Rating Curve= 0 ,0
Exp/Cntr=0.3,0.1

Type RM Length L Ch R = 1 ,48112   ,822,822,822
BEGIN DESCRIPTION:
Mapping XS 1c9a4dce
END DESCRIPTION:
XS GIS Cut Line= 4
      1604803.91      6814333.63      1605283.05      6814864.85
      1605779.58      6815757.21      1605998.35      6815969.04
#Sta/Elev= 30
  3745.7 1786.46    3785 1784.62  3884.3 1781.58  4061.3 1778.42  4510.5 1776.53
  4538.1 1775.85  4738.2 1776.56  4868.5 1776.21    4912 1774.31  4922.3 1772.82
  4933.9 1769.92  4956.8 1768.47  4974.9 1765.87  4975.9 1765.37  5024.1 1765.37
  5025.1 1765.87  5025.2 1767.99  5030.9 1767.61  5052.6 1768.77  5090.4    1773
  5171.6 1777.76  5236.7 1780.38  5274.5 1779.65  5301.9  1779.9  5333.9 1780.25
  5391.6 1782.44  5482.3 1782.42    5522 1783.99  5614.1 1783.96  5786.8 1785.97
#Mann= 3 ,-1 , 0
  3745.7     .05       0  4974.9     .05       0  5025.1     .05       0
Bank Sta=4974.9,5025.1
XS Rating Curve= 0 ,0
Exp/Cntr=0.3,0.1

Type RM Length L Ch R = 1 ,47290   ,506,506,506
BEGIN DESCRIPTION:
Lytle Creek 47289.81
END DESCRIPTION:
XS GIS Cut Line= 3
      1604224.89      6814988.18      1604813.41      6815540.24
      1605995.71      6816024.62
#Sta/Elev= 30
  4200.4 1782.91  4214.3 1782.89  4242.6 1775.68  4256.8 1774.77  4405.7 1774.53
  4419.9 1776.26  4447.8 1772.87  4589.4 1770.17    4625 1771.41  4737.9 1770.52
  4766.2 1773.75  4880.3 1774.63    4922 1774.73  4964.5 1772.06  4971.4 1768.88
  4974.9 1761.49  4975.9 1760.99  5025.2 1761.49  5052.3 1769.22  5117.2 1770.94
  5228.1 1773.69  5322.4 1774.12  5329.5 1774.43  5334.9 1776.42  5353.5 1777.05
  5358.9 1775.62  5452.1 1775.84  5644.5  1777.7    5858 1782.33    6285 1785.82
#Mann= 5 ,-1 , 0
  4200.4     .05       0  4880.3     .12       0  4974.9     .07       0
  5025.2     .12       0  5117.2     .05       0
Bank Sta=4974.9,5025.2
XS Rating Curve= 0 ,0
Exp/Cntr=0.3,0.1