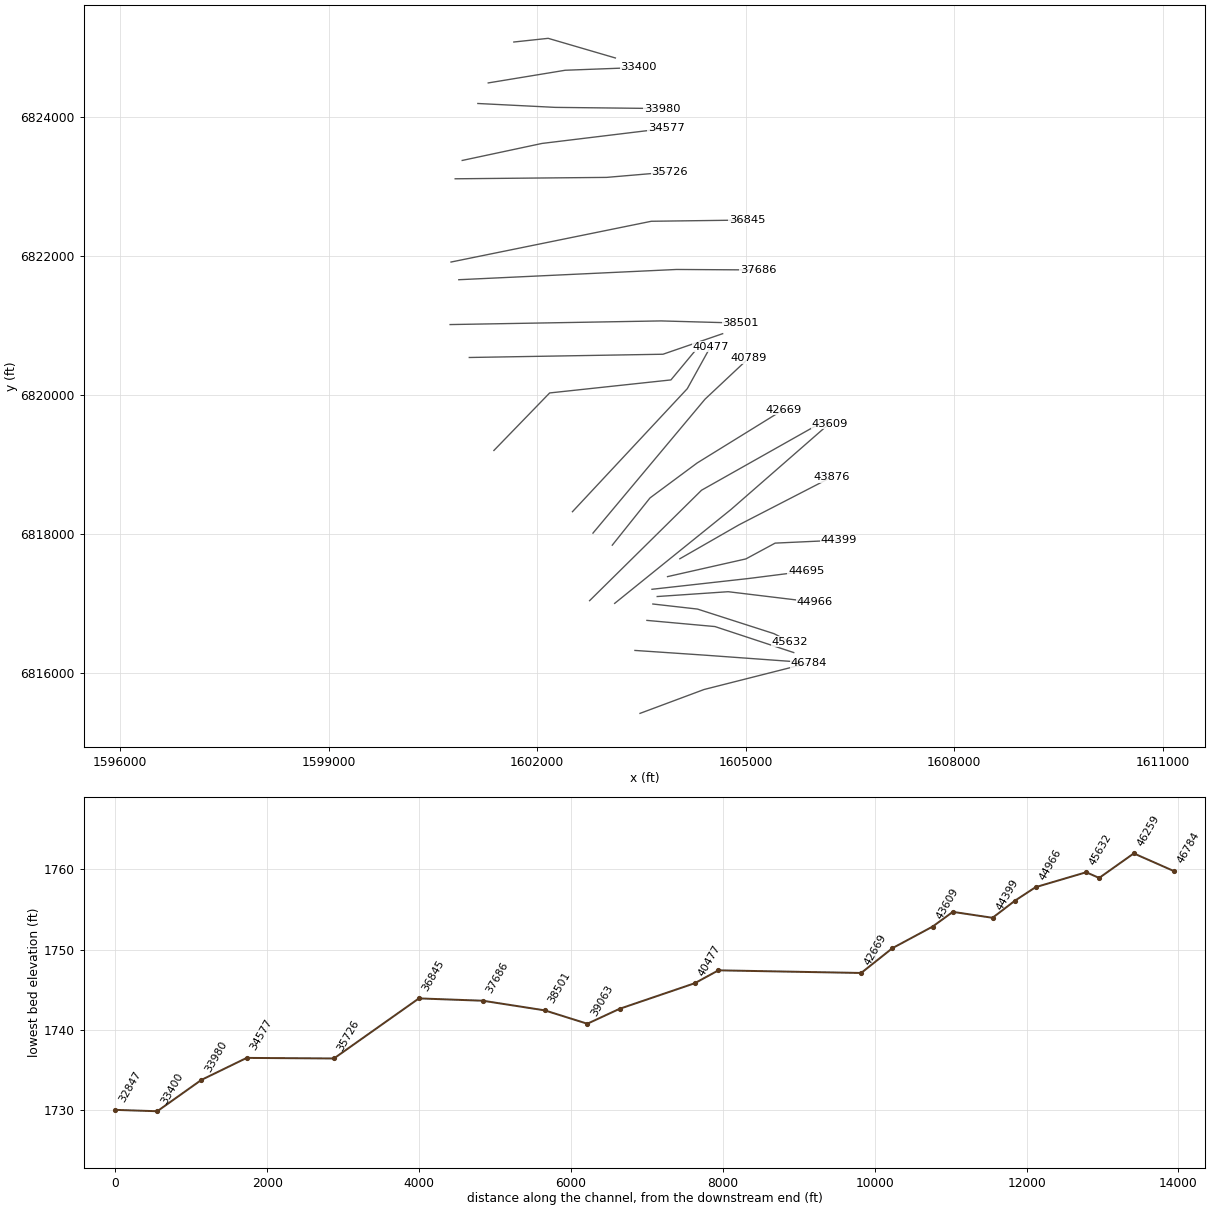
HEC-RAS study Lytle Creek.prj: Lytle Creek Base Level Engineering

--- Lytle Creek.g01 (geometry) --- (continued)

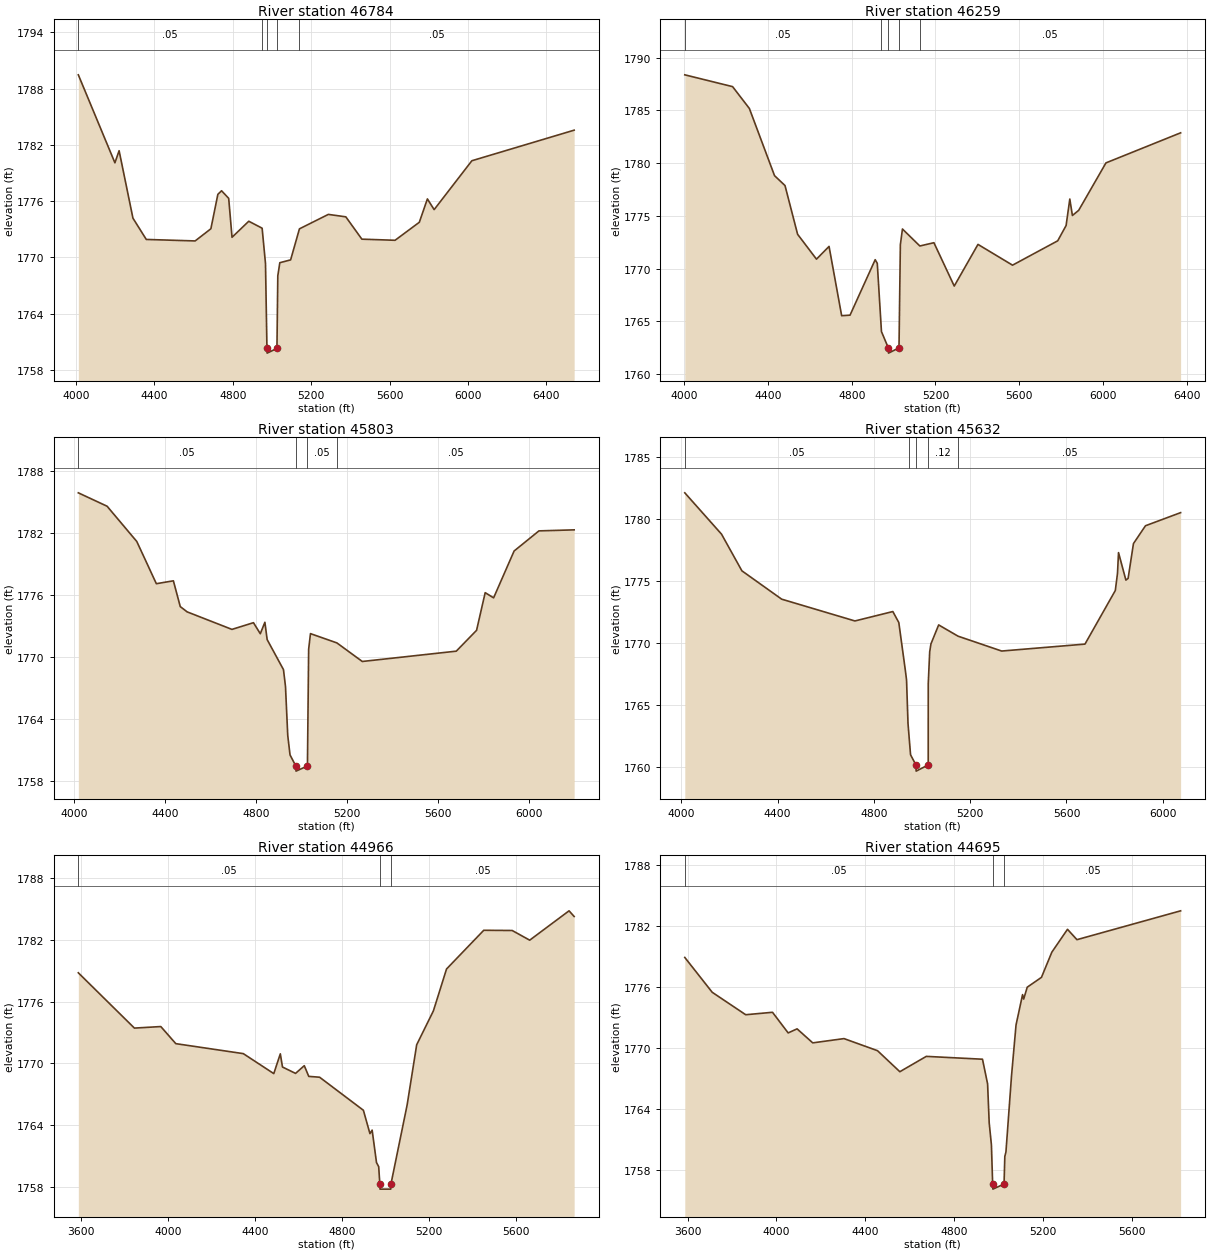
Type RM Length L Ch R = 1 ,46784   ,525,525,525
BEGIN DESCRIPTION:
Lytle Creek 46784.46
END DESCRIPTION:
XS GIS Cut Line= 3
      1603480.03      6815415.22      1604401.95      6815758.99
      1605901.02      6816138.96
#Sta/Elev= 30
  4011.9 1789.47  4198.6 1780.09    4220 1781.38  4290.6 1774.19  4358.7 1771.92
  4608.1 1771.76  4688.4 1773.06    4724 1776.73  4742.9 1777.11  4779.3  1776.3
  4796.3 1772.15  4881.7 1773.86  4949.9 1773.12  4967.1 1769.34  4974.5  1760.3
  4975.5  1759.8  5025.5  1760.3  5029.9 1768.04  5040.2 1769.44  5095.3 1769.74
  5140.3 1773.05  5287.8 1774.59    5377 1774.33  5458.9 1771.95  5628.3 1771.83
  5752.1 1773.75  5793.3 1776.24  5827.8  1775.1  6020.3 1780.31  6542.3 1783.57
#Mann= 5 ,-1 , 0
  4011.9     .05       0  4949.9     .12       0  4974.5     .07       0
  5025.5     .12       0  5140.3     .05       0
Bank Sta=4974.5,5025.5
XS Rating Curve= 0 ,0
Exp/Cntr=0.3,0.1

Type RM Length L Ch R = 1 ,46259   ,456,456,456
BEGIN DESCRIPTION:
Lytle Creek 46259.37
END DESCRIPTION:
XS GIS Cut Line= 3
      1603407.15      6816321.49      1604407.16      6816253.78
      1605770.88      6816154.88
#Sta/Elev= 30
  4001.9 1788.38  4230.3 1787.26  4310.5 1785.19  4430.7 1778.82  4480.8 1777.88
    4541 1773.26  4631.2  1770.9  4691.3 1772.11  4751.5 1765.54  4791.6 1765.59
  4911.8 1770.85  4921.8  1770.5  4941.8 1764.03  4974.5 1762.49  4975.5 1761.99
  5025.6 1762.49  5032.1 1772.26  5042.1 1773.76  5125.2 1772.15  5192.5 1772.46
  5289.6 1768.35  5403.1  1772.3  5568.2 1770.33  5784.1 1772.64  5824.2 1774.09
  5841.9  1776.6  5854.3 1775.04  5884.3 1775.53  6014.7 1780.03  6371.5 1782.88
#Mann= 5 ,-1 , 0
  4001.9     .05       0  4941.8     .12       0  4974.5     .07       0
  5025.6     .12       0  5125.2     .05       0
Bank Sta=4974.5,5025.6
XS Rating Curve= 0 ,0
Exp/Cntr=0.3,0.1

Type RM Length L Ch R = 1 ,45803   ,171,171,171
BEGIN DESCRIPTION:
Lytle Creek 45801.99
END DESCRIPTION:
XS GIS Cut Line= 3
      1603579.36      6816753.97       1604558.2      6816665.24
      1605691.81      6816290.83
#Sta/Elev= 30
  4019.8 1785.91  4146.1 1784.61  4276.5 1781.19  4362.3  1777.1  4437.1 1777.38
  4467.3 1774.88  4497.4 1774.37  4694.2 1772.67  4788.6 1773.32  4818.7 1772.25
  4838.8 1773.36  4848.8 1771.68  4920.4 1768.77  4929.2 1767.15  4939.2 1762.38
  4949.2  1760.5  4974.5 1759.43  4975.5 1758.93  5025.6 1759.43  5030.9 1770.74
  5038.9 1772.26  5154.9 1771.36  5266.4 1769.56    5679 1770.56  5768.1 1772.58
  5805.9 1776.23  5842.9 1775.73  5932.9 1780.27  6041.9 1782.22  6196.5 1782.32
#Mann= 4 ,-1 , 0
  4019.8     .05       0  4974.5     .05       0  5025.6     .05       0
  5154.9     .05       0
Bank Sta=4974.5,5025.6
XS Rating Curve= 0 ,0
Exp/Cntr=0.3,0.1

Type RM Length L Ch R = 1 ,45632   ,666,666,666
BEGIN DESCRIPTION:
Mapping XS 67b3d247
END DESCRIPTION:
XS GIS Cut Line= 4
      1603664.99      6816989.85      1604307.35      6816916.93
      1605408.05      6816562.77      1605637.17      6816444.73
#Sta/Elev= 30
    4014 1782.12  4166.7 1778.78  4251.3 1775.82  4416.6 1773.53    4721 1771.77
  4878.6 1772.53  4903.4 1771.64  4930.2 1767.83  4935.5 1767.01  4941.6 1763.49
  4945.9 1762.46  4952.2 1760.96  4974.5 1760.14  4975.5 1759.64  5025.6 1760.14
  5025.7  1766.7  5031.7 1769.27    5037 1769.92    5069 1771.45  5149.6 1770.54
  5330.9 1769.34    5677  1769.9  5803.1 1774.23  5812.2 1775.62  5816.4 1777.29
  5847.1 1775.07  5856.3 1775.21  5878.5 1778.02  5928.4 1779.46  6074.5 1780.52
#Mann= 5 ,-1 , 0
    4014     .05       0  4945.9     .12       0  4974.5     .07       0
  5025.6     .12       0  5149.6     .05       0
Bank Sta=4974.5,5025.6
XS Rating Curve= 0 ,0
Exp/Cntr=0.3,0.1

Type RM Length L Ch R = 1 ,44966   ,271,271,271
BEGIN DESCRIPTION:
Mapping XS 19fa8d52
END DESCRIPTION:
XS GIS Cut Line= 4
      1603727.47      6817097.49      1604748.33      6817166.93
      1605810.83      6817038.46      1605998.32      6817017.63
#Sta/Elev= 30
  3586.8 1778.79  3844.9 1773.42  3966.4 1773.57  4035.4 1771.91  4346.1 1770.94
  4486.4    1769  4516.5 1770.92  4526.5 1769.64  4586.6 1769.02  4626.8 1769.77
  4647.4 1768.73  4697.3 1768.65  4898.8 1765.44    4929 1763.17  4939.1 1763.51
  4959.2 1760.36  4969.3 1759.96  4974.4 1758.28  4975.4 1757.78  5024.7 1757.78
  5025.7 1758.28  5100.2 1765.96  5144.1  1771.8    5221 1775.09  5281.5 1779.16
  5452.8 1782.92  5583.7  1782.9  5664.3 1781.96  5845.4 1784.81  5868.9 1784.26
#Mann= 3 ,-1 , 0
  3586.8     .05       0  4974.4     .05       0  5025.7     .05       0
Bank Sta=4974.4,5025.7
XS Rating Curve= 0 ,0
Exp/Cntr=0.3,0.1

Type RM Length L Ch R = 1 ,44695   ,296,296,296
BEGIN DESCRIPTION:
Lytle Creek 44695.53
END DESCRIPTION:
XS GIS Cut Line= 3
       1603652.3      6817201.89       1605050.6      6817358.02
      1605870.51      6817462.24
#Sta/Elev= 30
  3587.6 1778.91  3711.1 1775.48    3862 1773.27  3982.7 1773.51  4053.2 1771.48
  4093.4 1771.88  4163.9  1770.5  4304.7 1770.92  4455.7 1769.73  4556.3 1767.66
  4675.5 1769.17  4928.6 1768.89  4951.6 1766.46  4958.8 1762.62  4968.8 1760.46
  4974.4  1756.6  4975.4  1756.1  5025.7  1756.6  5029.2 1759.32  5034.2 1759.75
  5059.5 1767.29  5079.7 1772.26  5109.1 1775.25  5114.2 1774.81  5130.1 1775.98
  5194.2 1776.95    5241 1779.43  5311.5 1781.68  5354.1 1780.66  5821.1  1783.5
#Mann= 3 ,-1 , 0
  3587.6     .05       0  4974.4     .05       0  5025.7     .05       0
Bank Sta=4974.4,5025.7
XS Rating Curve= 0 ,0
Exp/Cntr=0.3,0.1

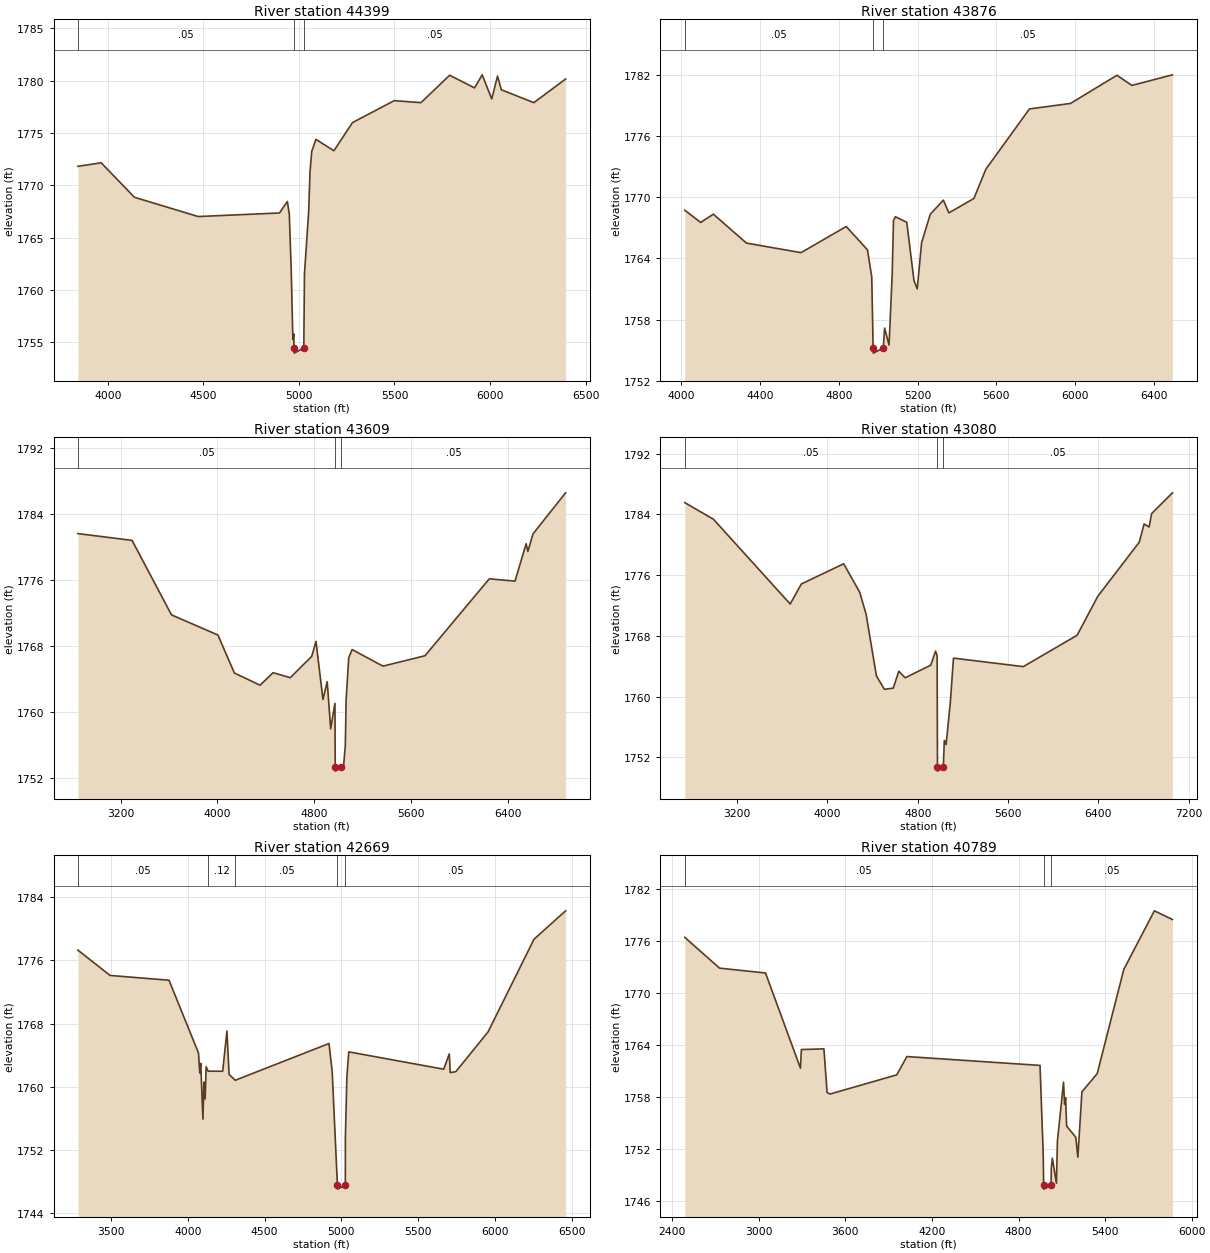
Type RM Length L Ch R = 1 ,44399   ,523,523,523
BEGIN DESCRIPTION:
Lytle Creek 44398.8
END DESCRIPTION:
XS GIS Cut Line= 4
      1603876.25      6817384.19      1605003.73      6817639.27
      1605424.16      6817866.57      1606340.87      6817908.91
#Sta/Elev= 30
  3843.8 1771.82  3965.5 1772.16  4139.8 1768.86    4473 1767.02  4898.5 1767.36
  4939.6 1768.46  4949.8 1767.24  4960.1 1761.77  4968.3 1755.26  4973.4 1755.79
  4974.4 1754.46  4975.4 1753.96  5025.7 1754.46  5029.1 1761.55    5051 1767.44
  5058.1 1771.26  5067.2 1773.25  5089.1  1774.4  5183.1 1773.31  5280.3    1776
  5498.6  1778.1  5638.7 1777.91  5788.9 1780.53    5919 1779.32  5959.1 1780.57
  6009.1 1778.26  6039.2 1780.45  6059.2 1779.14  6229.4 1777.91  6395.4 1780.17
#Mann= 3 ,-1 , 0
  3843.8     .05       0  4974.4     .05       0  5025.7     .05       0
Bank Sta=4974.4,5025.7
XS Rating Curve= 0 ,0
Exp/Cntr=0.3,0.1

Type RM Length L Ch R = 1 ,43876   ,267,267,267
BEGIN DESCRIPTION:
Lytle Creek 44192.169
END DESCRIPTION:
XS GIS Cut Line= 3
      1604052.98      6817641.21      1604905.73       6818130.8
      1606235.57      6818816.46
#Sta/Elev= 30
  4016.7 1768.74  4097.3 1767.54    4162 1768.35  4330.4 1765.51  4607.8 1764.57
  4837.7 1767.14  4945.7 1764.84  4967.3 1762.19  4974.4  1755.2  4975.4  1754.7
  5025.7  1755.2  5032.9 1757.16  5055.4  1755.5  5071.3 1762.44  5077.9 1767.73
  5087.8  1768.1  5145.4 1767.55  5182.1 1761.82  5198.6 1761.01  5220.8 1765.54
  5265.1 1768.35  5331.6 1769.73  5359.4 1768.48  5486.7 1769.89  5547.6 1772.77
  5769.2 1778.69    5978 1779.23  6214.3    1782  6289.8    1781  6496.2 1782.04
#Mann= 3 ,-1 , 0
  4016.7     .05       0  4974.4     .05       0  5025.7     .05       0
Bank Sta=4974.4,5025.7
XS Rating Curve= 0 ,0
Exp/Cntr=0.3,0.1

Type RM Length L Ch R = 1 ,43609   ,529,529,529
BEGIN DESCRIPTION:
Lytle Creek 43609.297
END DESCRIPTION:
XS GIS Cut Line= 3
      1603115.52      6816998.89      1604790.35      6818351.95
      1606205.02      6819588.02
#Sta/Elev= 30
  2846.9 1781.64  3294.4 1780.82  3620.6 1771.79  4004.4 1769.35  4140.3 1764.75
    4353 1763.27  4460.1 1764.79  4602.4 1764.18  4779.9 1766.77  4815.1 1768.58
  4872.7 1761.55  4907.9 1763.69  4936.6 1757.99  4971.8 1761.07  4974.2 1753.36
  4975.2 1752.86  5025.9 1753.36  5043.3 1753.49  5057.5 1755.94  5064.2 1761.54
  5085.8 1766.61  5113.5 1767.59  5368.9 1765.58  5716.3 1766.84  6247.8 1776.16
  6460.4 1775.88  6552.5 1780.41  6566.8 1779.48  6609.5 1781.61  6878.6 1786.58
#Mann= 3 ,-1 , 0
  2846.9     .05       0  4974.2     .05       0  5025.9     .05       0
Bank Sta=4974.2,5025.9
XS Rating Curve= 0 ,0
Exp/Cntr=0.3,0.1

Type RM Length L Ch R = 1 ,43080   ,411,411,411
BEGIN DESCRIPTION:
Lytle Creek 43080.136
END DESCRIPTION:
XS GIS Cut Line= 3
      1602754.99      6817037.99      1604365.51      6818628.19
      1606155.04      6819638.02
#Sta/Elev= 30
  2736.7 1785.55  2991.2 1783.35  3670.1 1772.19  3769.1 1774.83  4143.9 1777.49
  4285.3 1773.75  4341.9 1770.88  4433.8 1762.71  4504.5 1760.95  4582.3  1761.1
  4631.8 1763.33  4688.4 1762.47  4914.7 1764.13  4957.1 1765.98  4971.2 1765.39
  4974.2 1750.67  4975.2 1750.17  5025.9 1750.67  5034.9 1754.22  5050.8 1753.68
  5088.4 1759.26  5115.8 1765.06  5734.3 1763.94  6210.6 1768.07    6394 1773.21
  6760.8 1780.33  6804.1 1782.74  6848.1 1782.34    6871 1784.11  7054.8 1786.84
#Mann= 3 ,-1 , 0
  2736.7     .05       0  4974.2     .05       0  5025.9     .05       0
Bank Sta=4974.2,5025.9
XS Rating Curve= 0 ,0
Exp/Cntr=0.3,0.1

Type RM Length L Ch R = 1 ,42669   ,1880,1880,1880
BEGIN DESCRIPTION:
Lytle Creek 42668.9
END DESCRIPTION:
XS GIS Cut Line= 4
       1603081.2      6817837.14      1603624.27      6818517.52
      1604303.93      6819021.54      1605546.47      6819790.25
#Sta/Elev= 30
  3283.3 1777.31  3492.6 1774.11  3876.9  1773.5  4069.1 1764.29  4077.1 1761.76
  4083.5 1762.99  4097.9 1755.93  4104.3 1760.63  4112.3 1758.48  4118.7 1762.55
  4131.6    1762  4226.7 1761.99  4254.4 1767.08  4268.4 1761.59  4308.7 1760.85
  4919.5  1765.5  4940.3 1761.93  4974.2 1747.58  4975.2 1747.08  5025.9 1747.58
  5026.2 1753.62  5035.7 1761.19  5048.3 1764.44  5666.8 1762.25  5703.5 1764.19
  5709.4 1761.82    5746 1761.94  5956.4 1766.98  6255.4 1778.69  6461.1 1782.28
#Mann= 5 ,-1 , 0
  3283.3     .05       0  4131.6     .12       0  4308.7     .05       0
  4974.2     .05       0  5025.9     .05       0
Bank Sta=4974.2,5025.9
XS Rating Curve= 0 ,0
Exp/Cntr=0.3,0.1

Type RM Length L Ch R = 1 ,40789   ,312,312,312
BEGIN DESCRIPTION:
Lytle Creek 40789.027
END DESCRIPTION:
XS GIS Cut Line= 3
      1602803.38      6818010.71      1604415.44      6819939.04
       1605047.3      6820532.41
#Sta/Elev= 30
  2486.6 1776.45  2727.5  1772.9  3046.3 1772.34  3288.4 1761.36  3294.9 1763.51
    3451 1763.59  3473.2 1758.55    3494 1758.38  3955.9 1760.59  4026.2  1762.7
  4948.9 1761.68    4971 1751.54  4974.1 1747.91  4975.1 1747.41    5026 1747.91
    5027 1749.81  5034.4 1750.97  5062.7 1748.09  5069.5 1752.94    5112 1759.74
  5119.3 1757.18  5126.2 1757.96  5133.5 1754.68    5197 1753.39  5211.2  1751.1
  5239.5 1758.63  5345.5 1760.74  5529.6 1772.75  5741.6 1779.51  5866.8 1778.51
#Mann= 3 ,-1 , 0
  2486.6     .05       0  4974.1     .05       0    5026     .05       0
Bank Sta=4974.1,5026
XS Rating Curve= 0 ,0
Exp/Cntr=0.3,0.1

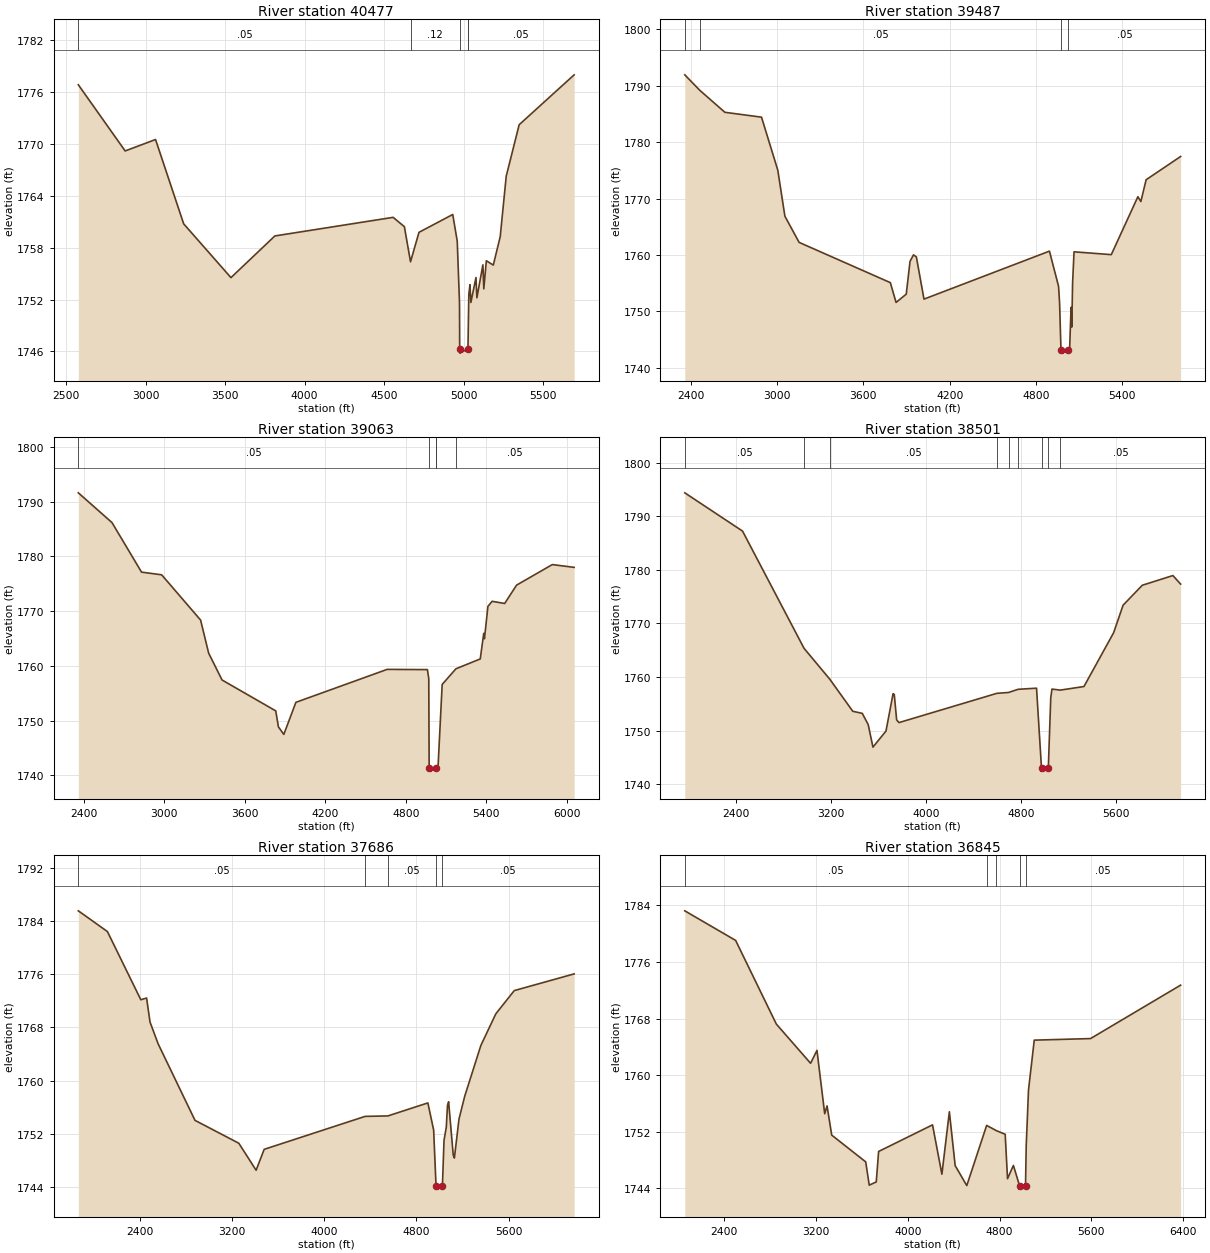
Type RM Length L Ch R = 1 ,40477   ,990,990,990
BEGIN DESCRIPTION:
Lytle Creek 40238.718
END DESCRIPTION:
XS GIS Cut Line= 3
      1602508.28      6818318.91      1604160.57      6820090.48
      1604496.13      6820697.39
#Sta/Elev= 30
  2577.5 1776.83  2871.8 1769.18  3062.8  1770.5  3239.6 1760.75  3536.7 1754.53
  3812.7 1759.35  4555.8  1761.5  4626.6 1760.42  4665.2 1756.36  4718.4 1759.77
  4930.5 1761.83  4958.8 1758.74    4973 1751.62  4974.1  1746.3  4975.1  1745.8
    5026  1746.3  5027.4  1747.9  5031.5 1752.58  5038.7 1753.71  5044.4 1751.66
  5076.5 1754.54  5082.2  1752.2    5120 1756.01  5125.7 1753.23  5141.7 1756.48
  5185.3 1755.98  5228.8 1759.26  5266.6 1766.26  5347.9 1772.21  5693.5 1777.98
#Mann= 5 ,-1 , 0
  2577.5     .05       0  4665.2     .12       0  4974.1     .07       0
    5026     .12       0  5027.4     .05       0
Bank Sta=4974.1,5026
XS Rating Curve= 0 ,0
Exp/Cntr=0.3,0.1

Type RM Length L Ch R = 1 ,39487   ,424,424,424
BEGIN DESCRIPTION:
Lytle Creek 39640.856
END DESCRIPTION:
XS GIS Cut Line= 4
      1601378.17       6819200.6      1602180.27      6820028.74
      1603925.06      6820216.24      1604269.63      6820631.84
#Sta/Elev= 30
  2358.4 1791.92  2462.6 1789.18  2637.1 1785.28  2891.8 1784.42    3005 1775.03
  3054.4 1766.87  3153.4 1762.23  3787.6  1755.1  3827.4 1751.59  3898.2 1753.06
  3924.5 1758.87  3948.5 1760.02  3968.6 1759.66  4021.5 1752.18  4893.9 1760.68
  4957.2 1754.46  4964.3  1751.6  4974.1 1743.11  4975.1 1742.61    5026 1743.11
  5034.8 1743.78  5044.2 1750.72  5049.2 1747.23  5054.9 1755.05  5064.9 1760.56
  5323.9 1760.06  5508.8 1770.32  5529.6 1769.47  5566.1 1773.33    5806 1777.45
#Mann= 4 ,-1 , 0
  2358.4     .12       0  2462.6     .05       0  4974.1     .05       0
    5026     .05       0
Bank Sta=4974.1,5026
XS Rating Curve= 0 ,0
Exp/Cntr=0.3,0.1

Type RM Length L Ch R = 1 ,39063   ,562,562,562
BEGIN DESCRIPTION:
Lytle Creek 39054.887
END DESCRIPTION:
XS GIS Cut Line= 3
      1601024.06      6820539.16      1603810.48      6820586.03
      1604668.93      6820881.84
#Sta/Elev= 30
  2359.8  1791.6  2610.8 1786.16  2830.8 1777.11  2980.8 1776.62  3270.9 1768.35
  3330.9 1762.31  3430.9  1757.4  3830.9 1751.76  3850.9 1748.83    3891 1747.46
    3981 1753.32  4661.1 1759.34  4961.1  1759.3  4971.2 1757.68  4974.1 1741.25
  4975.1 1740.75    5026 1741.25  5026.9 1741.25  5041.1 1741.88  5071.1 1756.59
  5173.6 1759.45  5354.9 1761.25  5380.8 1765.92  5386.1 1764.94    5412 1770.85
  5443.3 1771.78  5536.9 1771.38  5625.3 1774.73  5891.8 1778.49  6054.6 1777.98
#Mann= 5 ,-1 , 0
  2359.8     .05       0  4974.1     .05       0    5026     .05       0
  5026.9     .12       0  5173.6     .05       0
Bank Sta=4974.1,5026
XS Rating Curve= 0 ,0
Exp/Cntr=0.3,0.1

Type RM Length L Ch R = 1 ,38501   ,815,815,815
BEGIN DESCRIPTION:
Lytle Creek 38501.12
END DESCRIPTION:
XS GIS Cut Line= 3
      1600747.94      6821013.11      1603782.88      6821065.73
      1604930.14      6821033.95
#Sta/Elev= 30
  1964.6 1794.36  2451.7 1787.22  2970.7 1765.34  3188.1 1759.57  3381.9 1753.59
  3461.9  1753.2  3511.9 1751.11  3551.9  1746.9  3661.9  1749.9  3721.9 1756.88
  3731.9 1756.71  3751.9 1751.98  3771.9 1751.48  4597.6 1756.94  4696.1  1757.1
  4776.6 1757.69  4932.1  1757.9  4974.1 1742.92  4975.1 1742.42    5026 1742.92
  5032.1 1743.39  5052.1  1756.1  5062.1 1757.73  5132.7 1757.54  5332.2 1758.21
  5582.3 1768.24  5662.4 1773.39  5824.2 1777.11  6082.5 1778.92  6147.7 1777.33
#Mann= 9 ,-1 , 0
  1964.6     .05       0  2970.7     .12       0  3188.1     .05       0
  4597.6     .12       0  4696.1     .05       0  4776.6     .12       0
  4974.1     .07       0    5026     .12       0  5132.7     .05       0
Bank Sta=4974.1,5026
XS Rating Curve= 0 ,0
Exp/Cntr=0.3,0.1

Type RM Length L Ch R = 1 ,37686   ,841,841,841
BEGIN DESCRIPTION:
Lytle Creek 37390.876
END DESCRIPTION:
XS GIS Cut Line= 3
      1600872.94      6821658.95      1604005.07      6821806.48
      1605175.05      6821799.57
#Sta/Elev= 30
  1864.4 1785.59  2116.7 1782.47  2407.1 1772.18  2457.1 1772.44  2487.1 1768.81
  2557.2 1765.54  2877.6 1753.99    3258 1750.54  3408.2 1746.47  3478.2 1749.62
  4354.8 1754.59  4552.7 1754.66  4899.8 1756.62  4949.9 1752.52  4969.9 1744.41
    4974 1744.12    4975 1743.62    5026 1744.12  5039.9 1750.97  5059.9 1752.98
  5069.9 1756.24  5079.9 1756.79  5119.9 1748.77  5129.9 1748.31  5169.9 1754.18
  5219.9 1757.64  5359.9 1765.29  5489.9 1770.06  5649.9 1773.56    6170 1776.08
#Mann= 5 ,-1 , 0
  1864.4     .05       0  4354.8     .12       0  4552.7     .05       0
    4974     .05       0    5026     .05       0
Bank Sta=4974,5026
XS Rating Curve= 0 ,0
Exp/Cntr=0.3,0.1

Type RM Length L Ch R = 1 ,36845   ,1119,1119,1119
BEGIN DESCRIPTION:
Lytle Creek 36844.86
END DESCRIPTION:
XS GIS Cut Line= 3
       1600761.2      6821913.45      1603642.93      6822500.43
      1605019.51      6822518.32
#Sta/Elev= 30
  2059.1 1783.23  2501.8 1779.05  2856.2 1767.23  3154.5 1761.69  3210.1 1763.51
  3277.4 1754.56  3297.8 1755.67  3338.6 1751.54  3634.6 1747.76  3665.2 1744.47
  3726.4 1744.93  3746.9 1749.23  4216.3 1752.99  4297.9 1746.02  4362.9 1754.84
  4413.5 1747.23  4514.6 1744.41  4687.6 1752.91  4772.6 1752.17    4849 1751.66
  4869.4 1745.38  4920.5 1747.26    4974 1744.41    4975 1743.91  5026.1 1744.41
  5032.1 1750.02  5052.1  1757.9  5102.1 1764.96  5592.1 1765.18  6376.7 1772.73
#Mann= 5 ,-1 , 0
  2059.1     .05       0  4687.6     .12       0  4772.6     .05       0
    4974     .05       0  5026.1     .05       0
Bank Sta=4974,5026.1
XS Rating Curve= 0 ,0
Exp/Cntr=0.3,0.1

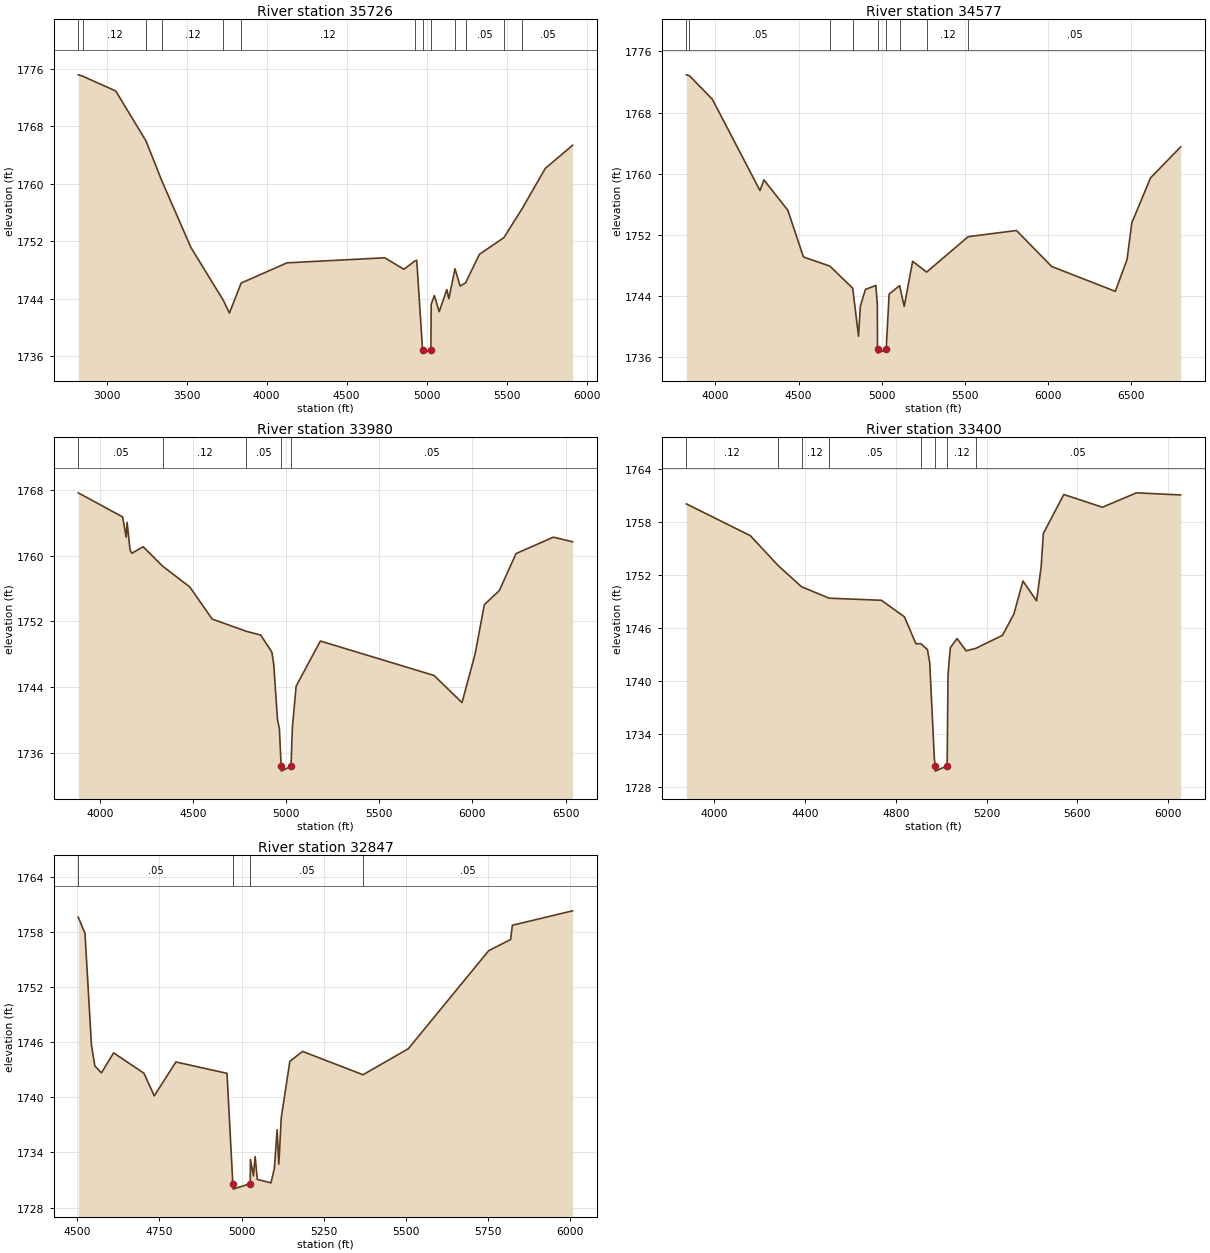
Type RM Length L Ch R = 1 ,35726   ,1149,1149,1149
BEGIN DESCRIPTION:
Lytle Creek 35725.689
END DESCRIPTION:
XS GIS Cut Line= 3
      1600820.86      6823112.07      1602997.26      6823132.09
      1603905.18      6823209.34
#Sta/Elev= 30
  2823.5 1775.19  2851.2    1775  3057.7 1772.94  3247.1 1765.96  3346.1 1760.39
  3527.7 1751.12  3729.8 1743.77  3767.7    1742  3840.9 1746.18  4127.7    1749
  4737.7  1749.7  4857.7  1748.1    4927 1749.27  4937.7 1749.36    4974 1736.92
    4975 1736.42  5026.1 1736.92  5027.8 1743.22  5047.9 1744.44    5078  1742.2
  5125.9 1745.27  5138.2    1744  5176.7 1748.17  5208.5 1745.77  5242.3 1746.19
  5328.9 1750.18    5482 1752.51  5597.8 1756.61  5740.4 1762.15  5911.2 1765.38
#Mann= 13 ,-1 , 0
  2823.5     .05       0  2851.2     .12       0  3247.1     .05       0
  3346.1     .12       0  3729.8     .05       0  3840.9     .12       0
    4927     .05       0    4974     .05       0  5026.1     .05       0
  5176.7     .12       0  5242.3     .05       0    5482     .12       0
  5597.8     .05       0
Bank Sta=4974,5026.1
XS Rating Curve= 0 ,0
Exp/Cntr=0.3,0.1

Type RM Length L Ch R = 1 ,34577   ,597,597,597
BEGIN DESCRIPTION:
Lytle Creek 34576.911
END DESCRIPTION:
XS GIS Cut Line= 3
      1600922.19      6823376.07      1602071.43      6823621.23
        1603855.        6823838.
#Sta/Elev= 30
  3824.9 1772.94  3843.2 1772.83  3981.2 1769.74  4267.5 1757.78  4291.3 1759.18
  4434.7 1755.21  4528.7 1749.09  4688.2 1747.88  4824.9 1744.99    4860 1738.71
  4870.7 1742.62  4901.4 1744.83  4964.2 1745.36    4973 1742.76    4974 1736.99
    4975 1736.49  5026.1 1736.99  5043.9 1744.22  5106.8 1745.33  5134.6 1742.61
  5185.2 1748.52  5269.2  1747.1  5518.9 1751.74  5809.5 1752.55    6021 1747.84
  6403.8 1744.58  6474.3 1748.77  6503.1 1753.57  6615.4 1759.44  6796.7 1763.51
#Mann= 9 ,-1 , 0
  3824.9     .12       0  3843.2     .05       0  4688.2     .12       0
  4824.9     .05       0    4974     .07       0  5026.1     .05       0
  5106.8     .05       0  5269.2     .12       0  5518.9     .05       0
Bank Sta=4974,5026.1
XS Rating Curve= 0 ,0
Exp/Cntr=0.3,0.1

Type RM Length L Ch R = 1 ,33980   ,580,580,580
BEGIN DESCRIPTION:
Lytle Creek 33980.178
END DESCRIPTION:
XS GIS Cut Line= 3
      1601147.34      6824196.13      1602261.14      6824140.17
      1603798.34      6824123.21
#Sta/Elev= 30
  3884.8 1767.69  4122.8 1764.75  4142.1 1762.28  4147.1 1764.09  4162.8 1760.69
  4172.8 1760.32  4232.9 1761.12  4337.7 1758.74  4483.2 1756.21  4603.4 1752.29
  4786.5  1750.8  4863.7 1750.34  4923.8 1748.25  4933.8 1746.76  4953.8 1740.04
  4963.8 1738.97  4973.6 1734.34  4974.6 1733.74  5026.5 1734.34  5033.9 1739.11
  5053.9 1744.11  5183.9 1749.61  5793.9 1745.41  5943.9  1742.1  6013.9 1748.01
  6063.9 1754.05  6143.9 1755.76  6233.9 1760.28  6433.9 1762.28  6537.3 1761.72
#Mann= 5 ,-1 , 0
  3884.8     .05       0  4337.7     .12       0  4786.5     .05       0
  4973.6     .03       0  5026.5     .05       0
Bank Sta=4973.6,5026.5
XS Rating Curve= 0 ,0
Exp/Cntr=0.3,0.1

Type RM Length L Ch R = 1 ,33400   ,553,553,553
BEGIN DESCRIPTION:
Lytle Creek 33399.804
END DESCRIPTION:
XS GIS Cut Line= 3
      1601296.66      6824492.31      1602404.63       6824674.8
      1603459.78      6824714.53
#Sta/Elev= 30
  3877.1 1760.08  4159.2 1756.48  4281.7  1753.1  4384.8  1750.7  4506.5 1749.41
  4736.9 1749.17  4838.2  1747.3  4888.9 1744.25  4910.4 1744.26  4939.6  1743.6
  4949.7 1742.12    4970 1731.36  4973.6 1730.44  4974.6 1729.84  5026.5 1730.44
  5030.4 1740.72  5040.4  1743.8  5070.4 1744.84  5110.4 1743.45  5152.6 1743.73
  5270.6 1745.21  5320.6 1747.61  5360.6 1751.35  5420.7 1749.11  5440.7 1752.92
  5450.7 1756.74  5540.8 1761.14  5710.9  1759.7    5861 1761.33  6055.9 1761.09
#Mann= 8 ,-1 , 0
  3877.1     .12       0  4281.7     .05       0  4384.8     .12       0
  4506.5     .05       0  4910.4     .12       0  4973.6     .07       0
  5026.5     .12       0  5152.6     .05       0
Bank Sta=4973.6,5026.5
XS Rating Curve= 0 ,0
Exp/Cntr=0.3,0.1

Type RM Length L Ch R = 1 ,32847   ,525,525,525
BEGIN DESCRIPTION:
Lytle Creek 32846.541
END DESCRIPTION:
XS GIS Cut Line= 3
        1601665.      6825081.31      1602158.97      6825134.26
      1603125.77      6824851.49
#Sta/Elev= 30
  4503.2 1759.61  4523.7 1757.85  4543.4 1745.66  4553.5 1743.44  4573.6 1742.66
  4610.8 1744.84    4703 1742.63  4734.5 1740.16  4800.2 1743.85  4955.8 1742.61
  4973.5 1730.61  4974.6 1730.01  5026.5 1730.61  5027.1 1733.22  5036.2 1731.46
  5041.4 1733.55    5048 1731.07  5089.6 1730.69    5100 1732.29  5108.3 1736.47
  5113.5 1732.74  5120.9 1737.79    5147 1743.92  5185.6    1745  5369.6 1742.46
  5507.4 1745.29  5751.9 1755.96  5818.8 1757.18    5824 1758.73  6007.3  1760.3
#Mann= 4 ,-1 , 0
  4503.2     .05       0  4973.5     .05       0  5026.5     .05       0
  5369.6     .05       0
Bank Sta=4973.5,5026.5
XS Rating Curve= 0 ,0
Exp/Cntr=0.3,0.1