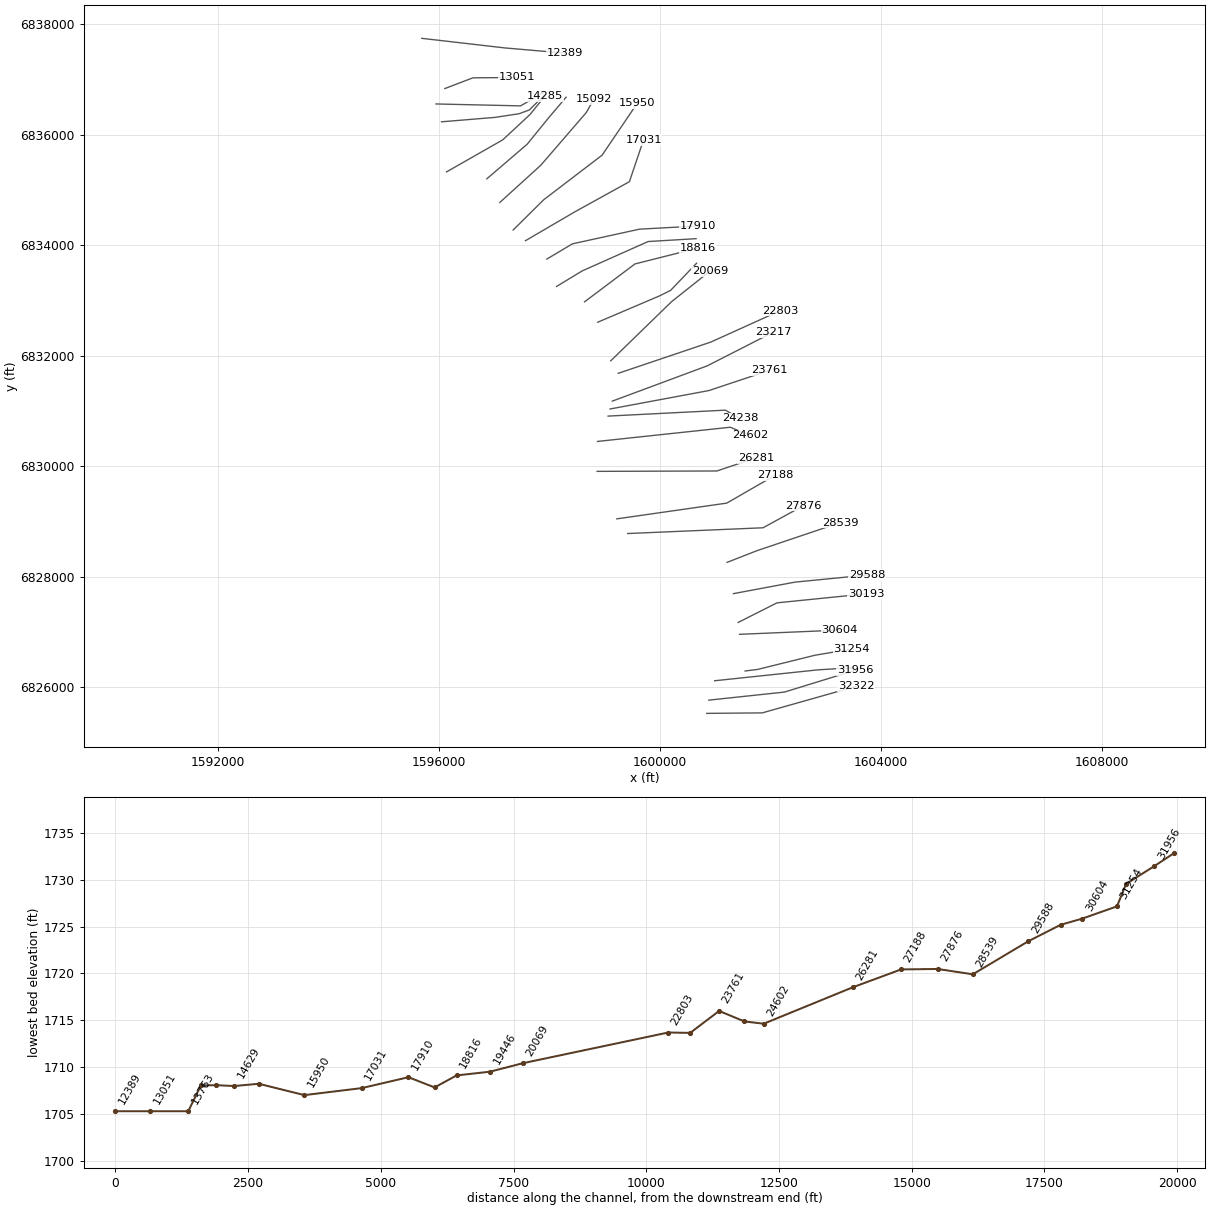
HEC-RAS study Lytle Creek.prj: Lytle Creek Base Level Engineering

--- Lytle Creek.g01 (geometry) --- (continued)

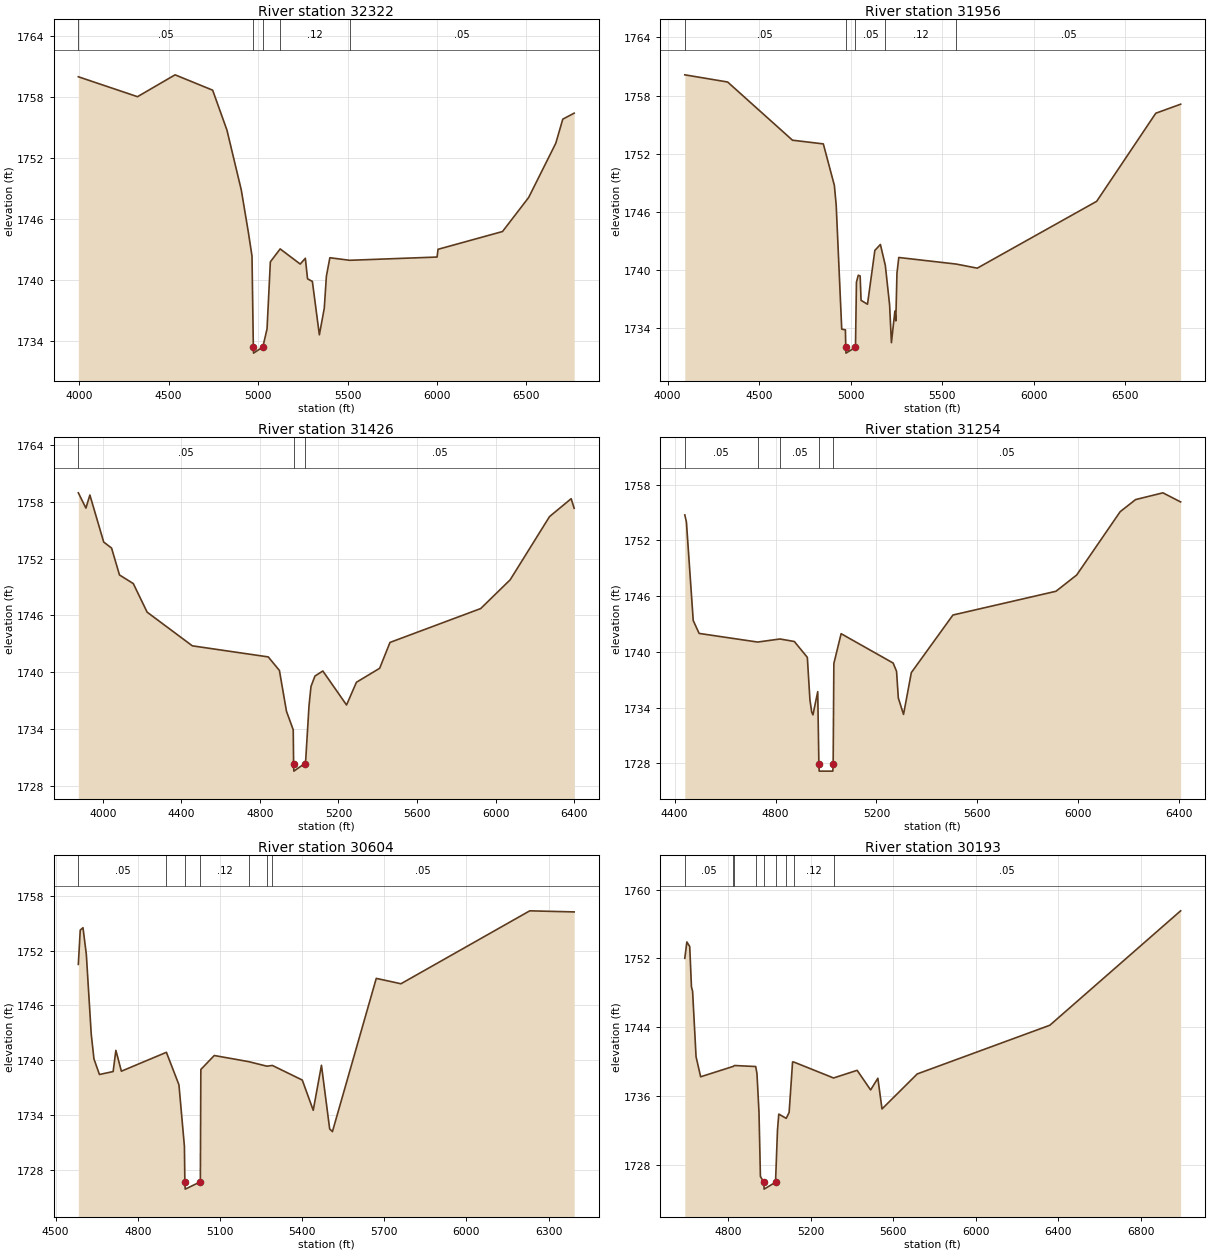
Type RM Length L Ch R = 1 ,32322   ,366,366,366
BEGIN DESCRIPTION:
Lytle Creek 32322.286
END DESCRIPTION:
XS GIS Cut Line= 3
      1600844.22      6825531.33      1601848.88      6825540.18
      1603549.03      6826020.91
#Sta/Elev= 30
  3995.3 1759.99  4326.1 1758.03  4536.1 1760.18  4746.1 1758.67  4826.1 1754.74
  4906.1 1748.86  4946.1 1744.65  4966.1 1742.35  4973.5 1733.41  4974.6 1732.81
  5026.5 1733.41  5050.1 1735.19  5068.7 1741.79  5123.5 1743.06  5235.5 1741.57
  5264.3 1742.14  5276.5 1740.12  5303.5 1739.86  5342.6 1734.61  5370.1 1737.23
  5381.8 1740.37  5401.3 1742.19  5512.6 1741.94  6000.7 1742.26  6005.9 1743.02
  6366.4 1744.77  6512.6 1748.12  6664.1 1753.45  6703.2 1755.82  6766.8 1756.41
#Mann= 5 ,-1 , 0
  3995.3     .05       0  4973.5     .05       0  5026.5     .05       0
  5123.5     .12       0  5512.6     .05       0
Bank Sta=4973.5,5026.5
XS Rating Curve= 0 ,0
Exp/Cntr=0.3,0.1

Type RM Length L Ch R = 1 ,31956   ,530,530,530
BEGIN DESCRIPTION:
Lytle Creek 31167.796
END DESCRIPTION:
XS GIS Cut Line= 3
      1600882.34      6825770.91      1602250.42      6825916.75
      1603524.75      6826309.11
#Sta/Elev= 30
  4093.9 1760.14  4327.9  1759.4  4682.3  1753.4  4850.8 1753.02  4911.2 1748.74
  4921.2 1746.69  4951.4 1733.92  4971.5 1733.85  4973.5 1732.05  4974.6 1731.45
  5026.5 1732.05  5031.8 1738.76  5041.9 1739.48    5052  1739.4    5057 1736.89
  5092.2 1736.49  5132.4 1742.04  5162.6 1742.65  5189.6 1740.49  5212.9 1736.44
  5222.9 1732.53  5241.9 1735.79  5246.9 1734.77  5253.1 1739.68  5263.1 1741.31
  5577.3 1740.63    5692 1740.21  6344.4  1747.1  6667.3 1756.18  6803.1 1757.11
#Mann= 5 ,-1 , 0
  4093.9     .05       0  4973.5     .05       0  5026.5     .05       0
  5189.6     .12       0  5577.3     .05       0
Bank Sta=4973.5,5026.5
XS Rating Curve= 0 ,0
Exp/Cntr=0.3,0.1

Type RM Length L Ch R = 1 ,31426   ,172,172,172
BEGIN DESCRIPTION:
Mapping XS 7648e034
END DESCRIPTION:
XS GIS Cut Line= 3
      1600986.55      6826121.61      1602861.54      6826319.52
       1603500.2      6826357.71
#Sta/Elev= 30
  3875.4 1758.96  3914.1 1757.35  3934.2 1758.73  4004.6 1753.76  4044.8 1753.12
    4085 1750.28  4155.4 1749.37  4225.8 1746.35  4456.1 1742.79  4842.7 1741.62
  4899.5 1740.19  4935.6 1735.86  4969.9 1733.92  4971.7 1730.35    4973 1729.55
  5028.3 1730.35  5033.5 1730.74  5050.3 1736.48  5060.4  1738.5  5080.5  1739.6
  5120.7 1740.13  5241.4 1736.54  5291.7 1738.94  5410.1 1740.42  5462.6 1743.15
  5924.6 1746.73  6074.8 1749.77  6275.2 1756.45  6385.4 1758.34  6400.6 1757.33
#Mann= 3 ,-1 , 0
  3875.4     .05       0  4971.7     .05       0  5028.3     .05       0
Bank Sta=4971.7,5028.3
XS Rating Curve= 0 ,0
Exp/Cntr=0.3,0.1

Type RM Length L Ch R = 1 ,31254   ,650,650,650
BEGIN DESCRIPTION:
Mapping XS e18eeca7
END DESCRIPTION:
XS GIS Cut Line= 4
      1601538.66       6826298.7      1601764.31      6826326.47
      1602802.51      6826583.41      1603461.16      6826694.34
#Sta/Elev= 30
  4440.4 1754.75  4446.8 1753.99  4473.8 1743.38  4497.2 1741.99    4729 1741.06
  4817.7 1741.39  4874.5 1741.12    4926 1739.41  4936.3 1734.83  4943.1 1733.55
  4948.2 1733.22  4967.2 1735.72  4971.7 1727.96    4973 1727.16    5027 1727.16
  5028.3 1727.96  5031.1 1738.75  5059.9 1741.96    5266  1738.8  5279.5 1737.91
  5286.6 1735.03  5307.2 1733.27  5338.1 1737.77  5502.9 1743.97  5911.3 1746.53
  5993.3 1748.28  6165.7  1755.1  6226.6  1756.4    6335 1757.13  6405.2 1756.15
#Mann= 5 ,-1 , 0
  4440.4     .05       0    4729     .12       0  4817.7     .05       0
  4971.7     .05       0  5028.3     .05       0
Bank Sta=4971.7,5028.3
XS Rating Curve= 0 ,0
Exp/Cntr=0.3,0.1

Type RM Length L Ch R = 1 ,30604   ,411,411,411
BEGIN DESCRIPTION:
Mapping XS 778433d1
END DESCRIPTION:
XS GIS Cut Line= 2
      1601437.97      6826961.89      1603246.96      6827038.27
#Sta/Elev= 30
  4582.7 1750.48  4589.7 1754.24  4599.7  1754.5  4611.9 1751.58  4629.8 1742.85
  4639.8 1740.12  4659.8 1738.42  4709.8 1738.74  4719.8 1741.06  4739.9 1738.78
  4904.3 1740.85  4950.1 1737.29  4970.1 1730.55  4971.7 1726.66    4973 1725.86
  5028.3 1726.66  5030.1 1738.97  5079.1  1740.5  5204.1 1739.83  5271.4 1739.33
  5291.3 1739.41  5400.5 1737.81  5440.5  1734.5  5470.5 1739.43  5500.5 1732.46
  5510.6 1732.16  5670.7 1748.95  5760.8 1748.36  6231.2 1756.35  6393.3 1756.23
#Mann= 7 ,-1 , 0
  4582.7     .05       0  4904.3     .12       0  4971.7     .07       0
  5028.3     .12       0  5204.1     .05       0  5271.4     .12       0
  5291.3     .05       0
Bank Sta=4971.7,5028.3
XS Rating Curve= 0 ,0
Exp/Cntr=0.3,0.1

Type RM Length L Ch R = 1 ,30193   ,605,605,605
BEGIN DESCRIPTION:
Mapping XS 8268765c
END DESCRIPTION:
XS GIS Cut Line= 3
      1601413.63      6827177.17      1602115.01      6827531.33
      1603726.14      6827694.53
#Sta/Elev= 30
  4588.2 1752.02  4598.2 1753.92  4612.1 1753.39  4620.5 1748.71  4626.1 1748.17
  4642.8 1740.58  4665.1 1738.25  4823.7 1739.46  4828.9 1739.56  4932.1 1739.44
  4938.3 1738.62  4948.2 1734.06    4955 1726.66  4971.7 1725.99    4973 1725.19
  5028.3 1725.99  5037.8 1732.06  5044.1 1733.91  5080.1 1733.42  5094.3 1734.11
    5111 1739.98  5119.5 1739.94  5309.8 1738.11  5424.2    1739  5489.6 1736.72
  5524.7 1738.08  5544.8 1734.51  5715.7 1738.58  6358.9 1744.24  6993.3 1757.54
#Mann= 9 ,-1 , 0
  4588.2     .05       0  4823.7     .12       0  4828.9     .05       0
  4932.1     .12       0  4971.7     .07       0  5028.3     .12       0
  5080.1     .05       0  5119.5     .12       0  5309.8     .05       0
Bank Sta=4971.7,5028.3
XS Rating Curve= 0 ,0
Exp/Cntr=0.3,0.1

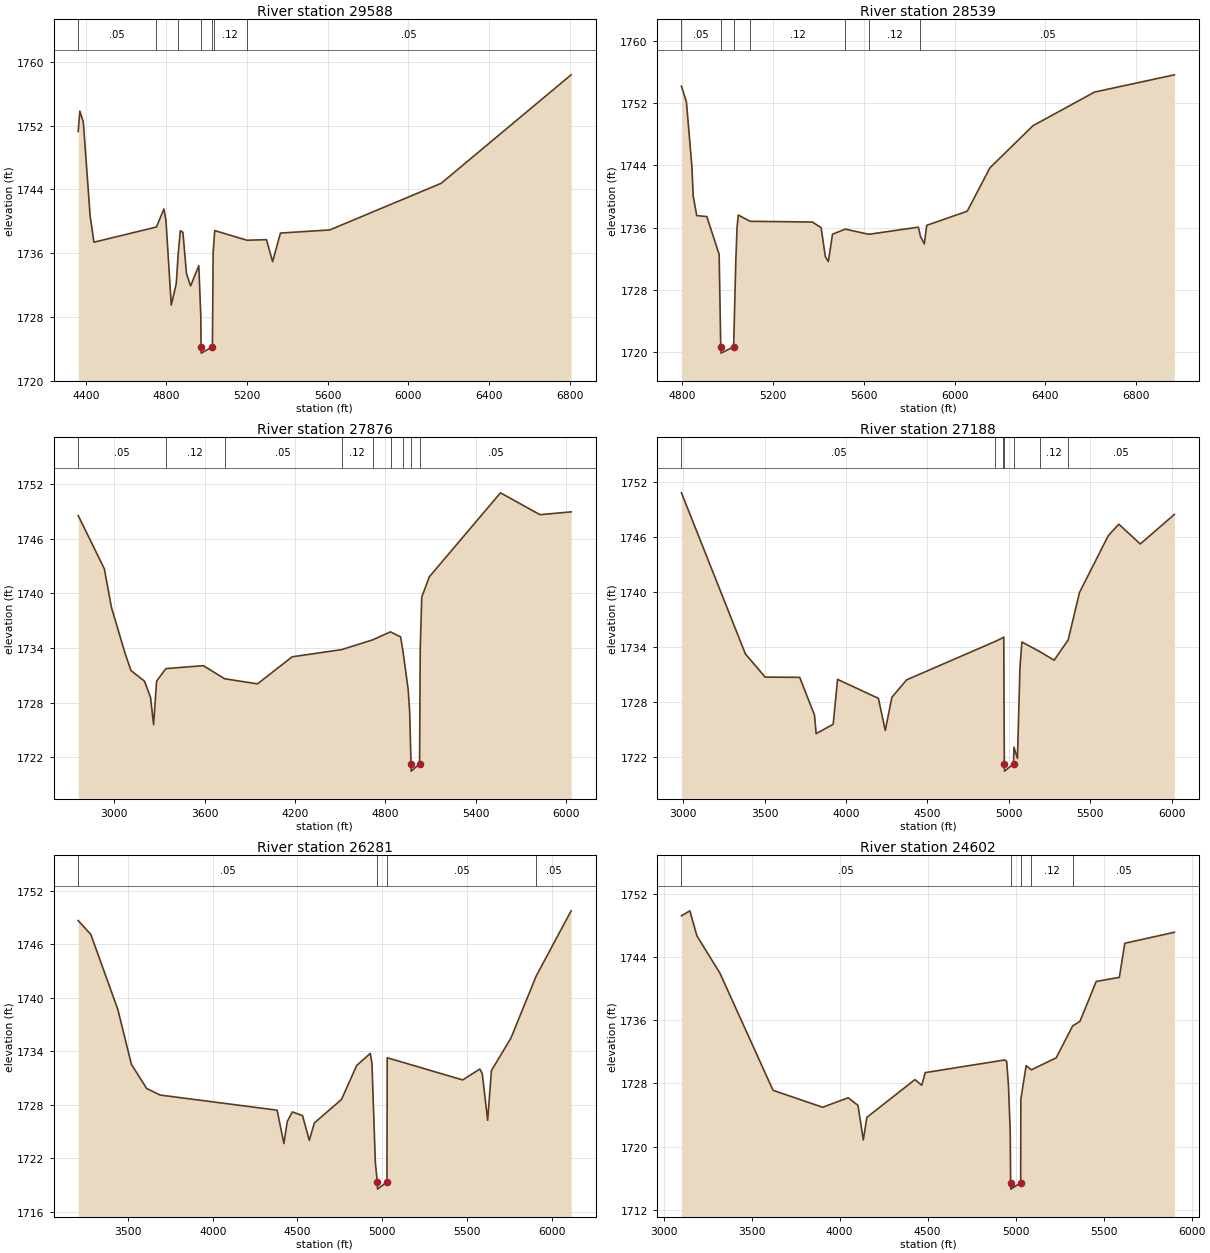
Type RM Length L Ch R = 1 ,29588   ,1049,1049,1049
BEGIN DESCRIPTION:
Mapping XS cfcc106c
END DESCRIPTION:
XS GIS Cut Line= 3
      1601326.81        6827698.       1602441.4      6827906.33
       1603746.9       6828034.8
#Sta/Elev= 30
  4362.3 1751.27  4370.6 1753.82  4387.7 1752.47  4421.5  1740.7  4440.4 1737.37
  4750.5 1739.28  4787.7 1741.55  4797.9 1740.06  4824.1 1729.49  4848.8 1732.15
  4858.5 1735.91  4869.1 1738.81  4881.9 1738.61  4899.6 1733.45    4920 1731.88
  4960.7 1734.42  4970.8 1728.07  4971.7 1724.25    4973 1723.45  5028.3 1724.25
  5031.9  1736.1  5034.3 1736.93  5039.8 1738.83  5199.4 1737.62  5296.4 1737.69
  5326.9 1734.94  5365.9 1738.52  5610.3 1738.91    6163 1744.76    6808 1758.38
#Mann= 7 ,-1 , 0
  4362.3     .05       0  4750.5     .12       0  4858.5     .05       0
  4971.7     .05       0  5028.3     .05       0  5034.3     .12       0
  5199.4     .05       0
Bank Sta=4971.7,5028.3
XS Rating Curve= 0 ,0
Exp/Cntr=0.3,0.1

Type RM Length L Ch R = 1 ,28539   ,663,663,663
BEGIN DESCRIPTION:
Mapping XS 4e40e666
END DESCRIPTION:
XS GIS Cut Line= 3
      1601212.22      6828263.97       1601753.9      6828475.77
      1603257.41      6828982.73
#Sta/Elev= 30
  4798.9 1754.17  4820.8 1752.13  4844.8 1743.84  4850.7 1740.04  4866.3 1737.56
  4910.4 1737.44  4964.7 1732.58  4971.7 1720.71    4973 1719.91  5028.3 1720.71
  5038.1 1731.86  5043.4 1736.03  5048.8 1737.63    5101 1736.83  5374.6 1736.74
  5413.3 1736.01  5431.8  1732.3    5445 1731.67  5463.3 1735.17  5519.3 1735.83
  5622.8 1735.16    5841 1736.08  5850.3 1734.89  5867.1 1733.93  5877.8 1736.31
  6056.1 1738.13  6155.8 1743.69  6344.7 1749.09  6616.4 1753.42  6967.2 1755.63
#Mann= 7 ,-1 , 0
  4798.9     .05       0  4971.7     .03       0  5028.3     .05       0
    5101     .12       0  5519.3     .05       0  5622.8     .12       0
  5850.3     .05       0
Bank Sta=4971.7,5028.3
XS Rating Curve= 0 ,0
Exp/Cntr=0.3,0.1

Type RM Length L Ch R = 1 ,27876   ,688,688,688
BEGIN DESCRIPTION:
Lytle Creek 27783.321
END DESCRIPTION:
XS GIS Cut Line= 3
      1599414.49      6828785.67       1601862.4      6828889.84
      1602586.33      6829285.65
#Sta/Elev= 30
  2760.1 1748.54  2934.1 1742.68  2980.8 1738.47  3070.9 1733.45  3110.9 1731.52
    3201 1730.35    3241 1728.56  3261.1 1725.59  3281.1 1730.36  3342.7 1731.73
  3591.4 1732.06  3733.3 1730.62  3951.7 1730.06  4181.9 1733.03  4511.2 1733.82
  4717.1 1734.89  4835.3 1735.77  4902.5 1735.21  4918.5 1733.58  4952.6 1729.46
  4962.6    1727  4971.6 1721.28  4972.9 1720.48  5028.5 1721.28  5032.7 1733.81
  5042.7 1739.57  5092.7  1741.8    5566 1751.03  5828.6 1748.63  6035.3 1748.94
#Mann= 9 ,-1 , 0
  2760.1     .05       0  3342.7     .12       0  3733.3     .05       0
  4511.2     .12       0  4717.1     .05       0  4835.3     .12       0
  4918.5     .05       0  4971.6     .05       0  5028.5     .05       0
Bank Sta=4971.6,5028.5
XS Rating Curve= 0 ,0
Exp/Cntr=0.3,0.1

Type RM Length L Ch R = 1 ,27188   ,907,907,907
BEGIN DESCRIPTION:
Lytle Creek 27188.48
END DESCRIPTION:
XS GIS Cut Line= 3
      1599216.53      6829051.29      1601206.35      6829336.08
       1602086.4      6829842.98
#Sta/Elev= 30
  2989.9 1750.79  3382.3 1733.22  3503.6 1730.69  3715.7 1730.66  3806.6 1726.54
  3816.7 1724.52  3921.2 1725.54    3948 1730.44  4198.7 1728.37    4241 1724.87
  4281.4 1728.48  4372.3 1730.39  4916.1 1734.58  4964.7    1735  4968.3 1735.06
  4971.6 1721.23  4972.9 1720.43  5028.5 1721.23  5030.6 1723.04  5052.2 1721.82
  5067.7 1731.72  5079.5 1734.52  5187.9 1733.48  5277.7 1732.53  5363.8 1734.75
  5432.9 1739.91  5609.6 1746.11  5674.3 1747.37  5806.3 1745.21  6015.6 1748.44
#Mann= 7 ,-1 , 0
  2989.9     .05       0  4916.1     .12       0  4964.7     .05       0
  4971.6     .05       0  5028.5     .05       0  5187.9     .12       0
  5363.8     .05       0
Bank Sta=4971.6,5028.5
XS Rating Curve= 0 ,0
Exp/Cntr=0.3,0.1

Type RM Length L Ch R = 1 ,26281   ,1679,1679,1679
BEGIN DESCRIPTION:
Lytle Creek 26661.68
END DESCRIPTION:
XS GIS Cut Line= 3
      1598860.62      6829910.67      1601027.33      6829917.61
      1601732.22      6830153.73
#Sta/Elev= 30
  3205.6 1748.66    3280 1747.11    3440 1738.67    3520 1732.52    3610 1729.82
    3690 1729.08    4380 1727.39    4420 1723.65    4440 1726.12    4470 1727.19
    4530 1726.78    4570 1724.01    4600 1725.96    4760 1728.58    4850 1732.41
    4930 1733.75    4940 1732.63    4960 1721.48  4971.6 1719.33  4972.9 1718.53
  5028.5 1719.33    5030 1733.27  5475.3 1730.78  5576.8    1732  5591.3 1731.47
    5623 1726.25  5645.2 1731.83  5760.1 1735.46    5909 1742.41  6115.7 1749.75
#Mann= 4 ,-1 , 0
  3205.6     .05       0  4971.6     .05       0  5028.5     .05       0
    5909     .05       0
Bank Sta=4971.6,5028.5
XS Rating Curve= 0 ,0
Exp/Cntr=0.3,0.1

Type RM Length L Ch R = 1 ,24602   ,364,364,364
BEGIN DESCRIPTION:
Lytle Creek 24387.649
END DESCRIPTION:
XS GIS Cut Line= 3
      1598867.58      6830452.33      1601270.39      6830709.28
      1601624.59      6830559.96
#Sta/Elev= 30
    3101 1749.19  3148.7 1749.82  3188.9 1746.65  3319.7 1741.94  3621.4 1727.13
    3903 1724.99  4048.3 1726.19  4104.1 1725.22  4134.3 1720.86  4154.4 1723.71
  4427.4 1728.48  4466.2 1727.78  4486.3 1729.37  4938.8 1730.97  4948.9 1730.78
    4959 1727.79    4969 1721.93  4971.5 1715.44  4972.8 1714.64  5028.5 1715.44
  5029.4 1726.01  5059.5 1730.25  5089.3 1729.72  5230.5 1731.24    5324 1735.28
  5365.3 1735.84  5457.6 1740.89  5589.1 1741.41  5620.2 1745.72  5901.9 1747.11
#Mann= 5 ,-1 , 0
    3101     .05       0  4971.5     .05       0  5028.5     .05       0
  5089.3     .12       0    5324     .05       0
Bank Sta=4971.5,5028.5
XS Rating Curve= 0 ,0
Exp/Cntr=0.3,0.1

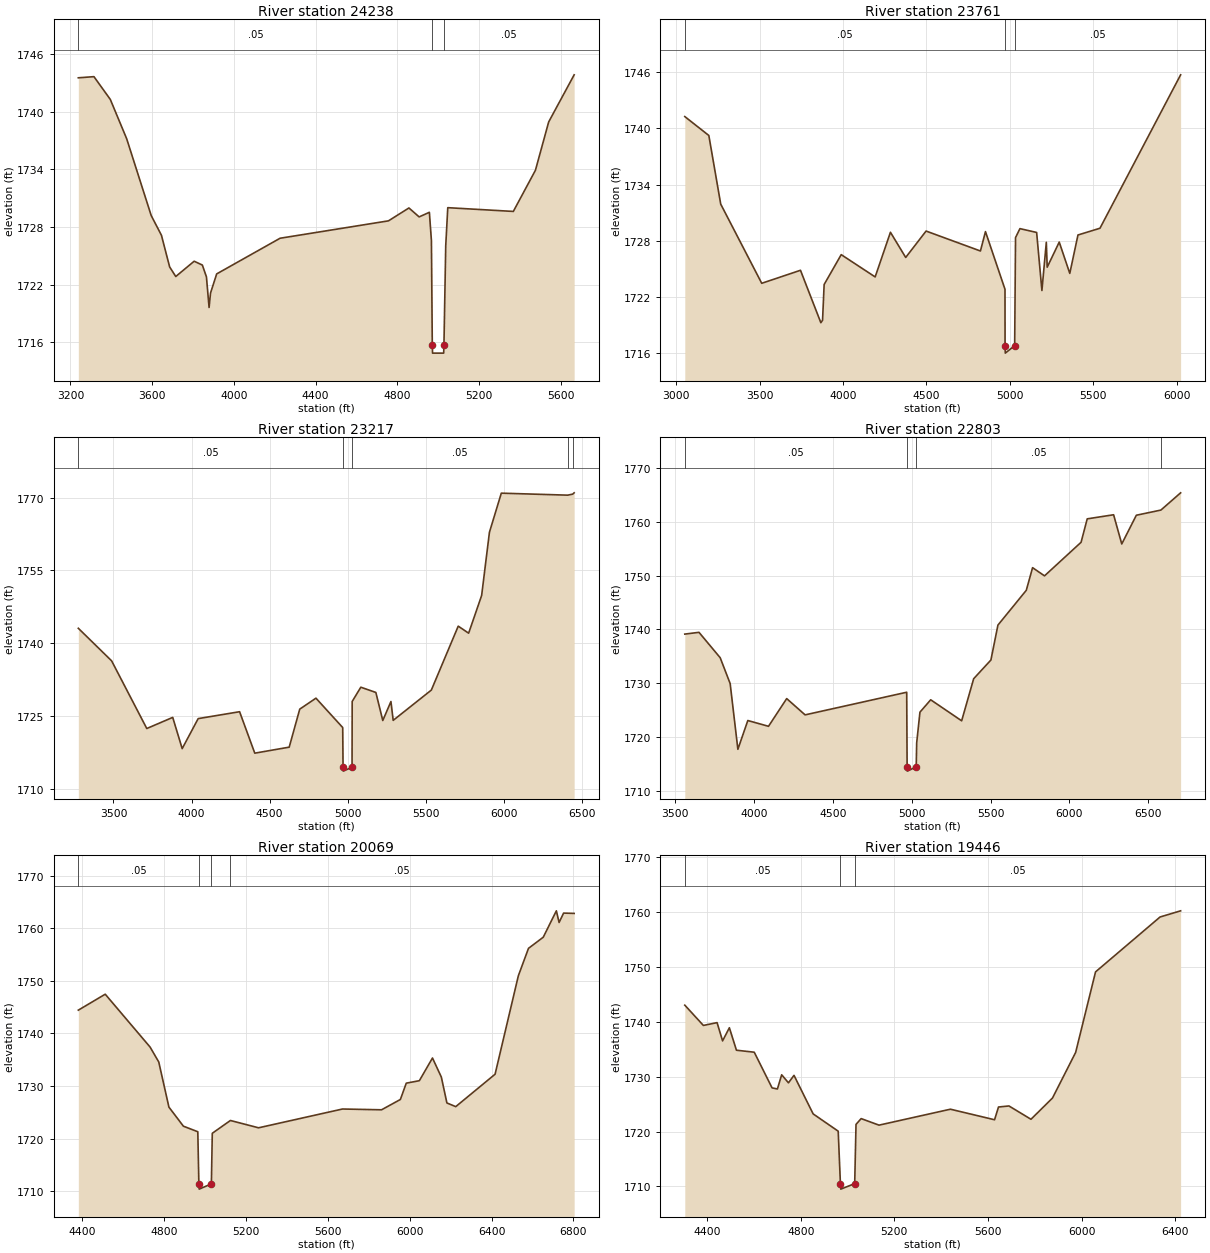
Type RM Length L Ch R = 1 ,24238   ,477,477,477
BEGIN DESCRIPTION:
Lytle Creek 23884.878
END DESCRIPTION:
XS GIS Cut Line= 3
      1599058.61      6830910.67      1601180.11      6831018.31
      1601443.97      6830869.02
#Sta/Elev= 30
  3238.6 1743.52  3315.1 1743.64  3395.2 1741.27  3475.3 1737.18  3595.4 1729.19
  3645.5 1727.14  3685.6 1723.85  3715.6 1722.85  3805.7 1724.44  3845.8 1724.04
  3865.8 1722.81  3878.7 1719.63  3885.8 1721.13  3915.9 1723.12  4226.3 1726.83
  4756.9 1728.64  4857.1 1729.98  4907.1 1729.05  4957.2 1729.53  4967.2 1726.59
  4971.5 1715.68  4972.8 1714.88  5027.2 1714.88  5028.5 1715.68  5037.3 1726.05
  5047.3 1730.01  5368.2 1729.62  5476.4  1733.9  5541.3 1738.93    5666 1743.83
#Mann= 3 ,-1 , 0
  3238.6     .05       0  4971.5     .05       0  5028.5     .05       0
Bank Sta=4971.5,5028.5
XS Rating Curve= 0 ,0
Exp/Cntr=0.3,0.1

Type RM Length L Ch R = 1 ,23761   ,544,544,544
BEGIN DESCRIPTION:
Lytle Creek 23335.647
END DESCRIPTION:
XS GIS Cut Line= 3
       1599093.3      6831039.14       1600881.5      6831372.48
      1601975.23      6831737.05
#Sta/Elev= 30
  3051.6 1741.27  3195.7 1739.25  3266.9 1731.92  3512.7 1723.46    3745 1724.85
  3867.1 1719.25  3877.3 1719.51  3886.8 1723.33  3989.2 1726.52  4192.6 1724.14
  4284.2 1728.91  4375.7 1726.22  4497.8 1729.04  4823.6 1726.91  4853.8 1728.98
  4970.8 1722.82  4971.2  1716.8  4972.6    1716  5028.8  1716.8    5034 1728.34
  5060.4  1729.3  5160.5 1728.89  5192.1 1722.69  5218.5 1727.84  5223.8 1725.18
  5295.9 1727.86  5359.2 1724.52  5408.2 1728.62    5540 1729.34  6023.5 1745.73
#Mann= 3 ,-1 , 0
  3051.6     .05       0  4971.2     .05       0  5028.8     .05       0
Bank Sta=4971.2,5028.8
XS Rating Curve= 0 ,0
Exp/Cntr=0.3,0.1

Type RM Length L Ch R = 1 ,23217   ,414,414,414
BEGIN DESCRIPTION:
Lytle Creek 22765.807
END DESCRIPTION:
XS GIS Cut Line= 3
      1599135.01      6831181.52      1600853.72      6831820.39
      1602050.84       6832431.1
#Sta/Elev= 30
  3274.7 1743.09  3488.1 1736.38  3713.4 1722.44  3879.6 1724.73  3940.3  1718.3
  4042.8 1724.48  4308.2  1725.9  4405.5 1717.36  4626.1  1718.6  4693.6 1726.43
  4797.5 1728.69    4969 1722.64  4971.2 1714.46  4972.6 1713.66  5028.8 1714.46
  5029.7 1728.01    5085 1730.95  5181.4 1729.87  5225.8 1724.09  5278.1    1728
  5292.5 1724.12    5537 1730.36  5709.3 1743.53    5776 1742.08  5859.3 1749.85
  5909.3 1762.88  5985.4 1770.93  6410.9 1770.52  6442.9 1770.73  6452.2    1771
#Mann= 5 ,-1 , 0
  3274.7     .05       0  4971.2     .03       0  5028.8     .05       0
  6410.9     .12       0  6442.9     .05       0
Bank Sta=4971.2,5028.8
XS Rating Curve= 0 ,0
Exp/Cntr=0.3,0.1

Type RM Length L Ch R = 1 ,22803   ,2734,2734,2734
BEGIN DESCRIPTION:
Lytle Creek 22183.167
END DESCRIPTION:
XS GIS Cut Line= 3
      1599242.59      6831684.97       1600919.7      6832250.95
       1602169.7      6832816.92
#Sta/Elev= 30
  3562.3 1739.13  3652.3 1739.46  3786.5 1734.75  3849.8 1729.95  3898.7 1717.75
  3961.7 1723.09  4092.8 1722.02  4208.1 1727.16  4324.7 1724.14  4968.6 1728.34
  4971.2  1714.5  4972.6  1713.7  5028.8  1714.5  5031.9 1718.95  5052.5 1724.64
  5120.7 1726.94  5316.8 1723.04    5393 1730.85  5502.2 1734.32  5546.7  1740.8
  5726.5 1747.26  5766.3 1751.46    5842 1749.94  6073.6 1756.17  6112.6 1760.52
  6279.8 1761.28  6331.5 1755.86  6423.9 1761.19  6579.6 1762.15  6704.5 1765.35
#Mann= 4 ,-1 , 0
  3562.3     .05       0  4971.2     .03       0  5028.8     .05       0
  6579.6     .12       0
Bank Sta=4971.2,5028.8
XS Rating Curve= 0 ,0
Exp/Cntr=0.3,0.1

Type RM Length L Ch R = 1 ,20069   ,623,623,623
BEGIN DESCRIPTION:
Mapping XS ea394c71
END DESCRIPTION:
XS GIS Cut Line= 3
      1599106.33      6831910.67      1600204.42      6832978.38
      1600902.64      6833533.49
#Sta/Elev= 30
  4380.3 1744.43  4511.8 1747.46    4731 1737.42  4773.5 1734.58  4823.1 1726.01
  4893.8 1722.39  4964.3 1721.33  4969.5 1711.43    4971 1710.43  5030.6 1711.43
  5035.1 1721.04  5123.7 1723.47  5261.4 1722.08  5671.6 1725.65  5862.5  1725.5
  5954.4 1727.46  5983.3 1730.56  6047.3 1731.03  6111.4 1735.34  6154.7 1731.72
  6181.9  1726.8  6225.1  1726.1  6417.4 1732.26  6531.1 1750.96  6580.7 1756.17
  6652.9 1758.29  6716.9  1763.3  6730.3 1761.09  6752.2 1762.87  6803.9 1762.81
#Mann= 4 ,-1 , 0
  4380.3     .05       0  4969.5     .03       0  5030.6     .05       0
  5123.7     .05       0
Bank Sta=4969.5,5030.6
XS Rating Curve= 0 ,0
Exp/Cntr=0.3,0.1

Type RM Length L Ch R = 1 ,19446   ,630,630,630
BEGIN DESCRIPTION:
Mapping XS 5db95189
END DESCRIPTION:
XS GIS Cut Line= 4
      1598871.95      6832609.45      1599991.74      6833086.89
       1600191.4      6833186.71      1600660.09      6833677.11
#Sta/Elev= 30
  4304.5 1742.99  4383.9  1739.3  4442.4 1739.81    4466 1736.49    4495 1738.88
  4525.2 1734.79  4601.3 1734.43  4677.4 1727.94  4700.3 1727.74  4718.5 1730.32
  4747.5 1728.86  4771.2 1730.22  4852.9 1723.21  4960.1 1720.06  4969.5 1710.52
    4971 1709.52  5030.6 1710.52  5036.2  1721.3  5058.2 1722.35  5134.5 1721.16
  5439.6 1724.06  5628.3 1722.14  5645.1 1724.46  5689.8 1724.65  5783.9 1722.23
  5875.8 1726.09  5974.8 1734.39  6059.8 1749.04  6335.6 1759.03  6423.4 1760.15
#Mann= 3 ,-1 , 0
  4304.5     .05       0  4969.5     .03       0  5030.6     .05       0
Bank Sta=4969.5,5030.6
XS Rating Curve= 0 ,0
Exp/Cntr=0.3,0.1

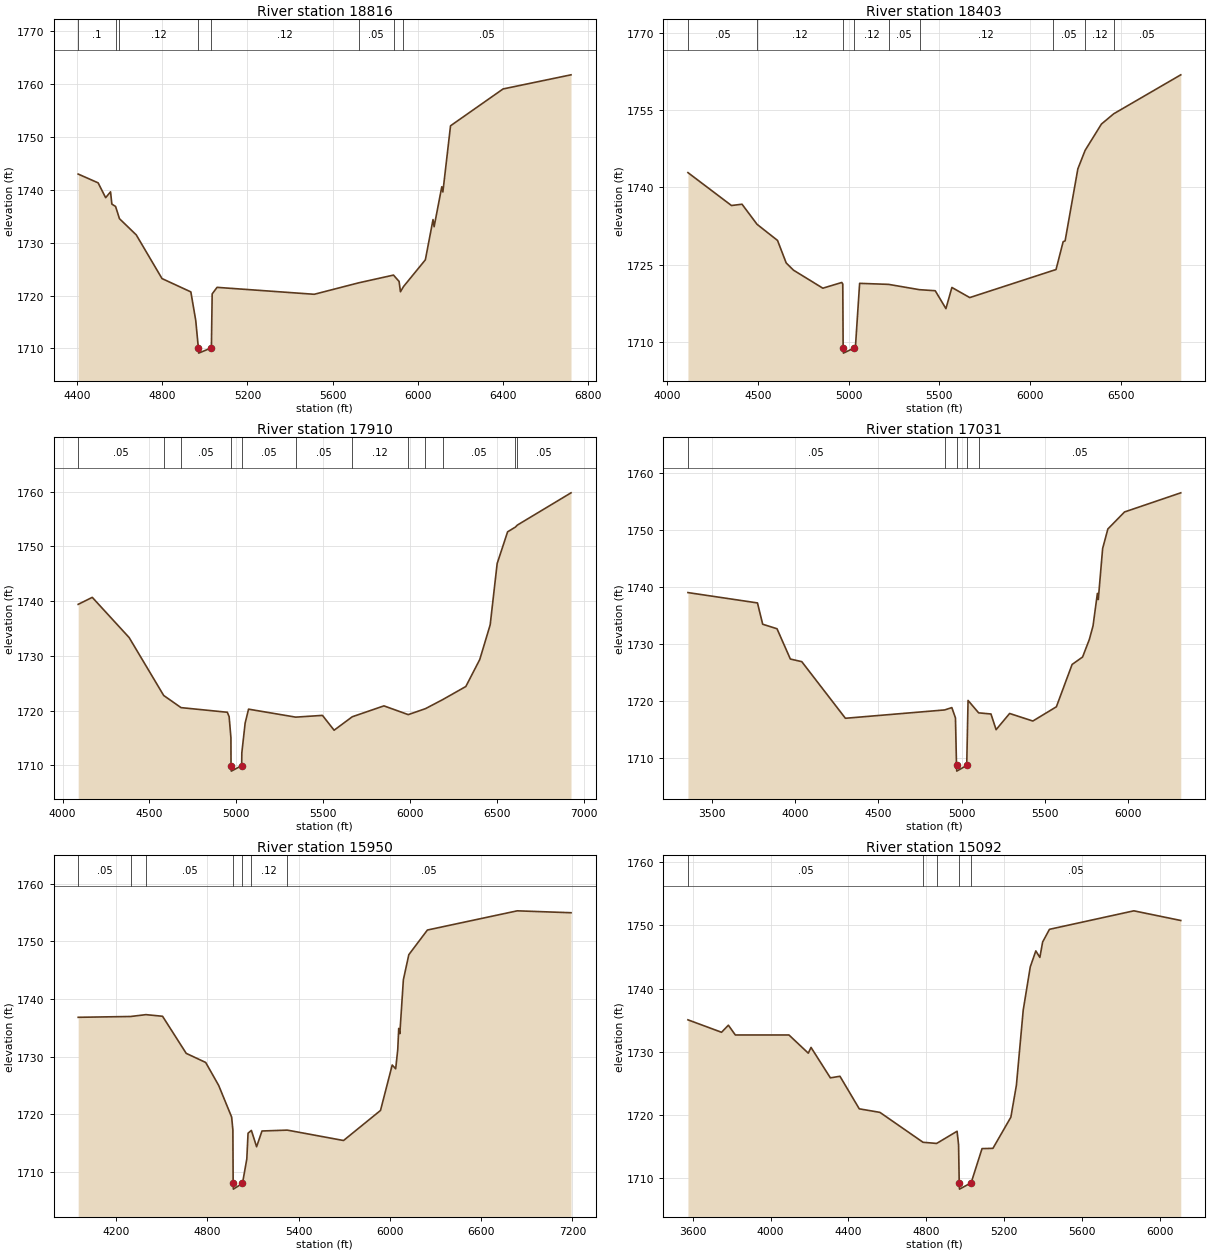
Type RM Length L Ch R = 1 ,18816   ,413,413,413
BEGIN DESCRIPTION:
Mapping XS 94faf59f
END DESCRIPTION:
XS GIS Cut Line= 3
      1598633.21      6832978.36       1599544.7      6833664.14
      1600680.93      6833950.37
#Sta/Elev= 30
  4405.6 1742.99  4499.1 1741.33  4534.5 1738.52  4557.4 1739.63  4563.6 1737.31
  4581.1 1736.86  4599.3 1734.55  4678.2 1731.48    4799 1723.22  4934.3  1720.7
  4957.2  1715.3  4969.5 1710.12    4971 1709.12  5030.6 1710.12  5034.3 1720.32
  5057.2 1721.56  5513.2 1720.25  5722.1 1722.42  5885.1 1723.88  5911.3 1722.68
  5917.8 1720.73  5931.9  1721.7  6034.6 1726.77  6070.6 1734.38  6075.7 1733.03
  6111.7 1740.59  6116.8  1739.6  6152.7 1752.12  6399.3 1759.09    6718 1761.76
#Mann= 8 ,-1 , 0
  4405.6      .1       0  4581.1     .05       0  4599.3     .12       0
  4969.5     .07       0  5030.6     .12       0  5722.1     .05       0
  5885.1     .12       0  5931.9     .05       0
Bank Sta=4969.5,5030.6
XS Rating Curve= 0 ,0
Exp/Cntr=0.3,0.1

Type RM Length L Ch R = 1 ,18403   ,493,493,493
BEGIN DESCRIPTION:
Mapping XS 08cbe365
END DESCRIPTION:
XS GIS Cut Line= 4
       1598127.2      6833257.05       1598590.7      6833538.27
      1599783.41      6834069.52      1600651.63      6834121.51
#Sta/Elev= 30
  4113.7 1742.84  4353.7 1736.46  4411.9 1736.71  4494.9 1732.81  4607.7 1729.69
  4655.4 1725.33  4695.5 1723.93  4857.6 1720.43    4962 1721.54  4967.5 1721.23
  4969.5 1708.84    4971 1707.84  5030.6 1708.84  5037.2 1708.99  5060.4 1721.37
  5219.9 1721.17  5390.9 1720.14  5477.3 1719.94  5536.3 1716.47  5569.2 1720.57
  5667.7 1718.61  6124.9 1723.84  6143.4 1724.04  6182.7 1729.45  6193.5  1729.6
  6263.7 1743.56  6303.9 1747.16  6393.9 1752.26  6461.7 1754.25  6831.3  1761.8
#Mann= 9 ,-1 , 0
  4113.7     .05       0  4494.9     .12       0  4969.5     .07       0
  5030.6     .12       0  5219.9     .05       0  5390.9     .12       0
  6124.9     .05       0  6303.9     .12       0  6461.7     .05       0
Bank Sta=4969.5,5030.6
XS Rating Curve= 0 ,0
Exp/Cntr=0.3,0.1

Type RM Length L Ch R = 1 ,17910   ,879,879,879
BEGIN DESCRIPTION:
Mapping XS 22398246
END DESCRIPTION:
XS GIS Cut Line= 4
      1597950.05       6833751.8      1598413.62      6834027.86
      1599627.16      6834293.48      1600679.29      6834350.78
#Sta/Elev= 30
    4090 1739.42    4171  1740.7  4383.2 1733.35    4582 1722.76  4681.7 1720.54
  4948.3 1719.69  4958.5 1718.88  4968.8 1715.04  4969.4 1709.93  4970.9 1708.93
  5030.6 1709.93  5031.5 1712.27  5050.7 1717.73  5070.3 1720.26  5341.5  1718.8
  5495.4 1719.12  5562.5 1716.41    5667 1718.87  5849.1 1720.86    5989 1719.26
    6088 1720.35    6187    1722  6320.3  1724.4  6400.4 1729.33  6460.5 1735.68
  6500.6 1746.88  6560.7 1752.68  6605.7 1753.55  6616.2  1753.9  6925.5 1759.81
#Mann= 12 ,-1 , 0
    4090     .05       0    4582     .12       0  4681.7     .05       0
  4969.4     .07       0  5030.6     .05       0  5341.5     .05       0
    5667     .12       0    5989     .05       0    6088     .12       0
    6187     .05       0  6605.7     .12       0  6616.2     .05       0
Bank Sta=4969.4,5030.6
XS Rating Curve= 0 ,0
Exp/Cntr=0.3,0.1

Type RM Length L Ch R = 1 ,17031   ,1081,1081,1081
BEGIN DESCRIPTION:
Mapping XS 42768128
END DESCRIPTION:
XS GIS Cut Line= 4
      1597564.63      6834085.13      1598455.29      6834605.98
      1599444.87      6835152.86      1599700.05        6835908.
#Sta/Elev= 30
  3356.6 1739.02  3774.1 1737.21  3805.5 1733.48  3891.5 1732.69  3971.6 1727.39
  4040.2 1726.93  4302.2 1717.02  4898.3 1718.48  4941.3 1718.89  4963.1 1717.08
  4969.4 1708.77  4970.9 1707.77  5030.7 1708.77  5038.7 1720.14  5102.3 1717.97
  5176.4 1717.77  5207.1 1715.03  5288.4 1717.86  5427.8 1716.54  5569.1 1719.03
  5663.5 1726.44  5726.4 1727.74  5767.2 1730.83  5789.3 1733.21  5815.4 1738.88
  5820.7  1737.8  5846.9 1746.74  5878.3 1750.15  5978.3 1753.13  6316.1 1756.48
#Mann= 5 ,-1 , 0
  3356.6     .05       0  4898.3     .12       0  4969.4     .07       0
  5030.7     .12       0  5102.3     .05       0
Bank Sta=4969.4,5030.7
XS Rating Curve= 0 ,0
Exp/Cntr=0.3,0.1

Type RM Length L Ch R = 1 ,15950   ,858,858,858
BEGIN DESCRIPTION:
Mapping XS e763e8b1
END DESCRIPTION:
XS GIS Cut Line= 4
      1597340.71      6834277.86      1597892.79      6834824.73
      1598950.08      6835632.02       1599585.5      6836569.54
#Sta/Elev= 30
  3950.6 1736.81  4295.4 1736.95  4396.1 1737.27  4505.3 1736.99  4660.8 1730.56
  4788.9 1728.98  4874.1 1725.01  4959.4 1719.52  4967.6 1717.31  4969.4 1708.02
  4970.9 1707.02  5030.7 1708.02  5059.1 1712.24  5067.4 1716.72  5089.3  1717.2
  5123.5 1714.37  5158.9  1717.1  5325.7 1717.25    5695 1715.45  5938.1 1720.66
  6015.1 1728.54  6037.9 1727.88  6051.6 1731.25  6057.9 1734.88  6065.2 1733.98
  6088.4 1743.32  6124.3 1747.67  6246.4 1751.94  6837.2 1755.27  7190.5 1754.94
#Mann= 7 ,-1 , 0
  3950.6     .05       0  4295.4     .12       0  4396.1     .05       0
  4969.4     .05       0  5030.7     .05       0  5089.3     .12       0
  5325.7     .05       0
Bank Sta=4969.4,5030.7
XS Rating Curve= 0 ,0
Exp/Cntr=0.3,0.1

Type RM Length L Ch R = 1 ,15092   ,463,463,463
BEGIN DESCRIPTION:
Mapping XS 8fef07ec
END DESCRIPTION:
XS GIS Cut Line= 4
      1597101.14      6834777.87       1597840.7      6835449.73
      1598663.62      6836402.86      1598799.03      6836642.44
#Sta/Elev= 30
  3574.8 1735.05  3747.5 1733.08  3782.7  1734.2  3818.4 1732.65  4094.1 1732.65
  4193.5 1729.77  4207.6 1730.68    4307 1725.86  4356.3 1726.11  4455.6 1720.95
  4561.7 1720.39  4783.5 1715.65  4853.4 1715.47  4958.4  1717.4  4966.1 1715.27
  4969.4 1709.23  4970.9 1708.23  5030.7 1709.23  5086.7 1714.65  5142.7 1714.69
  5234.9 1719.63  5263.4 1724.69  5298.5 1736.61  5334.7 1743.44  5363.2 1745.97
    5384 1744.94  5398.3 1747.39  5433.4 1749.39  5867.2 1752.32  6108.4 1750.79
#Mann= 5 ,-1 , 0
  3574.8     .05       0  4783.5      .1       0  4853.4     .12       0
  4969.4     .07       0  5030.7     .05       0
Bank Sta=4969.4,5030.7
XS Rating Curve= 0 ,0
Exp/Cntr=0.3,0.1

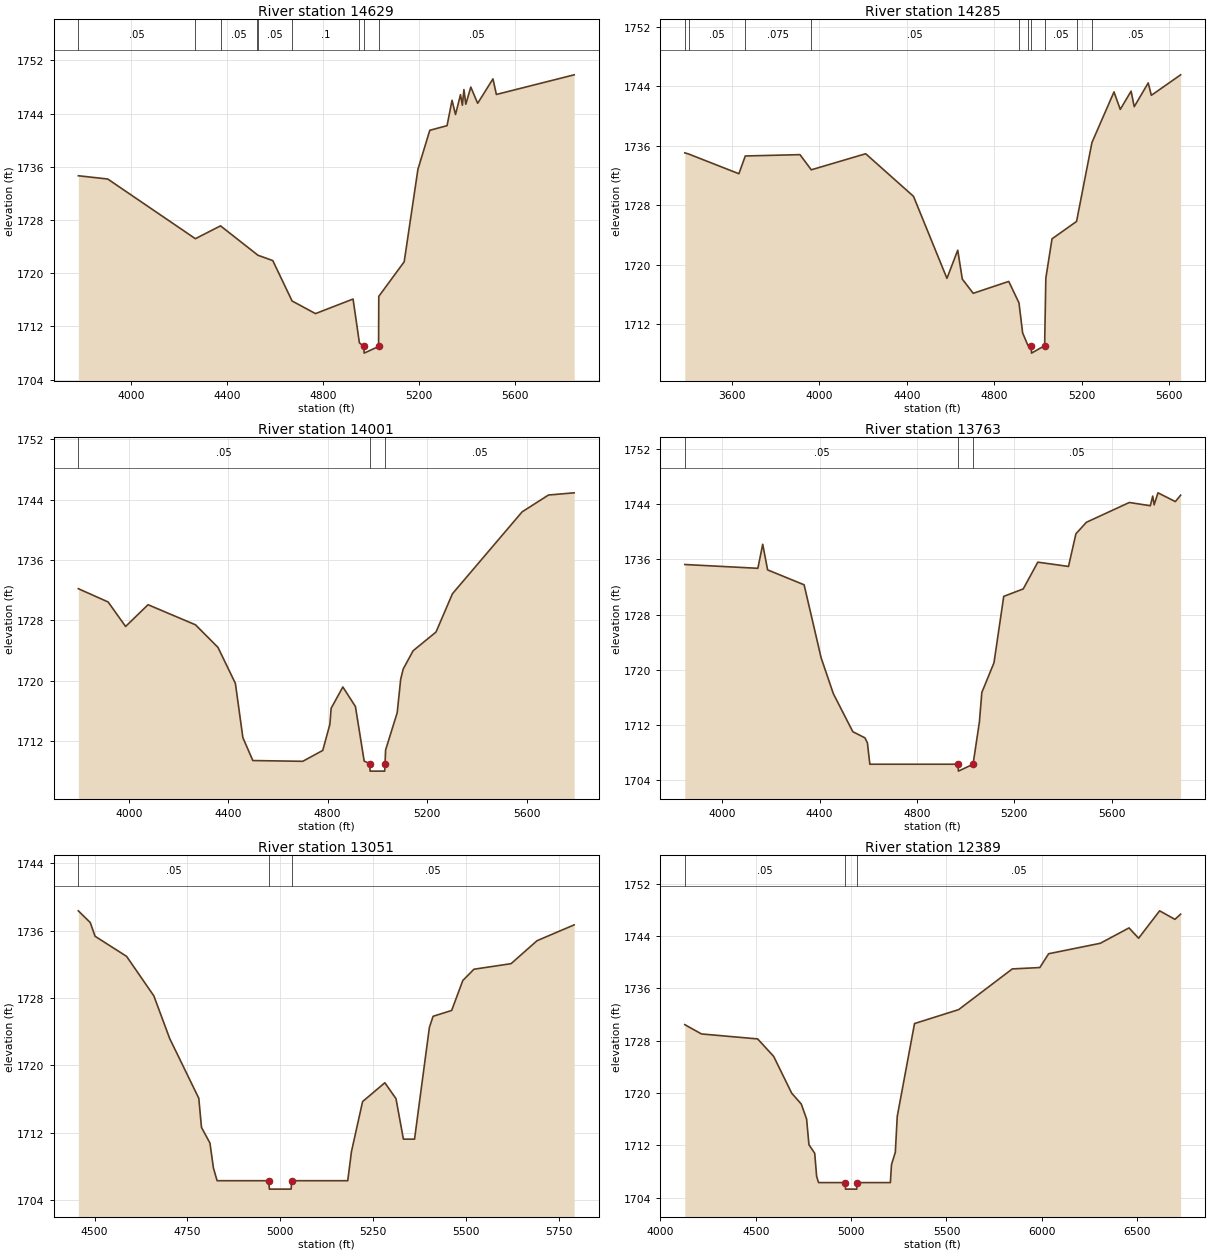
Type RM Length L Ch R = 1 ,14629   ,344,344,344
BEGIN DESCRIPTION:
Mapping XS f29a74ee
END DESCRIPTION:
XS GIS Cut Line= 4
      1596865.04      6835204.97      1597594.17      6835829.94
      1597986.54      6836312.58      1598299.06      6836680.67
#Sta/Elev= 30
  3780.2 1734.65  3902.7 1734.16  4267.8 1725.19  4372.4 1727.12  4522.5 1722.87
  4527.7 1722.71  4590.2  1721.9  4670.5 1715.83  4767.9 1713.93  4924.5 1716.12
  4950.9 1709.54  4969.2 1708.99  4970.7 1707.99  5030.8 1708.99  5031.6 1716.52
  5137.5 1721.72  5194.6 1735.61  5244.1 1741.48    5316 1742.18  5336.8 1745.99
  5351.2 1743.85    5372 1746.84  5379.8 1745.26  5386.3  1747.6  5394.1  1745.4
  5414.9 1747.98  5443.5 1745.54  5507.2 1749.21  5521.4 1746.87  5845.4 1749.82
#Mann= 9 ,-1 , 0
  3780.2     .05       0  4267.8     .12       0  4372.4     .05       0
  4522.5     .12       0  4527.7     .05       0  4670.5      .1       0
  4950.9     .05       0  4969.2     .05       0  5030.8     .05       0
Bank Sta=4969.2,5030.8
XS Rating Curve= 0 ,0
Exp/Cntr=0.3,0.1

Type RM Length L Ch R = 1 ,14285   ,284,284,284
BEGIN DESCRIPTION:
Mapping XS 96a4ea7a
END DESCRIPTION:
XS GIS Cut Line= 4
      1596135.82      6835329.93       1597153.2       6835909.8
      1597642.79      6836364.66      1597913.62        6836698.
#Sta/Elev= 30
  3384.2 1735.03  3402.2 1734.87  3631.7 1732.22    3661 1734.61  3911.2 1734.79
    3963 1732.75    4212 1734.91  4430.7 1729.18  4583.7 1718.14  4633.1 1721.93
  4654.1 1718.04  4703.9 1716.13  4866.6 1717.73  4913.4 1714.84  4930.1  1710.8
  4954.3 1709.12  4969.2 1709.08  4970.7 1708.08  5030.8 1709.08  5036.2 1718.16
  5064.5 1723.46  5176.8  1725.8  5247.2 1736.42  5348.1 1743.23  5376.8 1740.88
  5426.4 1743.33  5440.7 1741.24  5504.7 1744.44    5519 1742.77    5653 1745.53
#Mann= 10 ,-1 , 0
  3384.2      .1       0  3402.2     .05       0    3661    .075       0
    3963     .05       0  4913.4    .075       0  4954.3     .05       0
  4969.2     .03       0  5030.8     .05       0  5176.8    .075       0
  5247.2     .05       0
Bank Sta=4969.2,5030.8
XS Rating Curve= 0 ,0
Exp/Cntr=0.3,0.1

Type RM Length L Ch R = 1 ,14001   ,238,238,238
BEGIN DESCRIPTION:
Mapping XS ac820d99
END DESCRIPTION:
XS GIS Cut Line= 5
      1596045.55      6836236.19      1597010.84      6836316.05
      1597448.34      6836382.02      1597635.84      6836451.47
      1597906.67       6836722.3
#Sta/Elev= 30
  3797.4  1732.2  3917.3 1730.44  3987.5  1727.2  4077.8 1730.08  4268.5 1727.42
  4358.8 1724.44    4429 1719.67  4459.1 1712.49  4499.2 1709.45  4699.9 1709.35
  4780.3 1710.79  4809.1 1714.25  4814.1 1716.37  4861.2 1719.19  4911.8  1716.6
    4947 1709.37  4969.2 1709.05  4970.7 1708.05  5029.4 1708.05  5030.9 1709.05
  5033.1 1710.85  5079.8 1715.79  5093.8 1720.22  5103.9 1721.56  5143.6 1723.98
  5235.8 1726.46  5301.9 1731.53  5582.1 1742.37  5688.2  1744.6  5791.4 1744.89
#Mann= 3 ,-1 , 0
  3797.4     .05       0  4969.2     .03       0  5030.9     .05       0
Bank Sta=4969.2,5030.9
XS Rating Curve= 0 ,0
Exp/Cntr=0.3,0.1

Type RM Length L Ch R = 1 ,13763   ,712,712,712
BEGIN DESCRIPTION:
Mapping XS d7a37edd
END DESCRIPTION:
XS GIS Cut Line= 3
       1595944.9      6836559.11      1597476.12      6836524.39
      1597913.59      6836777.84
#Sta/Elev= 30
  3846.5 1735.25  4146.7  1734.7  4166.7 1738.18  4186.7 1734.47  4336.7 1732.31
  4406.7 1721.72  4456.8 1716.53  4536.8 1711.02  4586.8 1710.12  4596.8 1709.39
  4606.8  1706.3  4969.2  1706.3  4970.7  1705.3  5030.9  1706.3  5056.9 1712.42
  5066.9  1716.7  5116.9 1721.01  5156.9 1730.63    5237 1731.71    5297 1735.59
    5423 1734.97  5453.5  1739.7  5496.6 1741.37    5673 1744.24  5759.2 1743.77
  5769.1 1745.17  5774.9  1743.9  5790.7 1745.64  5862.2 1744.37  5883.7  1745.3
#Mann= 3 ,-1 , 0
  3846.5     .05       0  4969.2     .03       0  5030.9     .05       0
Bank Sta=4969.2,5030.9
XS Rating Curve= 0 ,0
Exp/Cntr=0.3,0.1

Type RM Length L Ch R = 1 ,13051   ,662,662,662
BEGIN DESCRIPTION:
Lytle Creek 13051.031
END DESCRIPTION:
XS GIS Cut Line= 3
        1596105.        6836838.      1596613.14      6837031.94
      1597405.02        6837038.
#Sta/Elev= 30
  4456.1 1738.37  4488.2 1736.98  4501.2 1735.35  4586.1 1732.96  4659.5 1728.27
  4702.3 1723.19  4780.6  1716.1  4787.9 1712.64  4810.7 1710.77    4820 1707.82
    4830  1706.3  4969.2  1706.3  4970.7  1705.3  5029.4  1705.3  5030.9  1706.3
  5181.9  1706.3  5191.9 1709.75  5221.9  1715.7  5281.9 1717.94  5311.9 1716.05
  5331.9 1711.24  5361.9 1711.24  5401.9 1724.52  5411.9 1725.84  5461.9 1726.53
  5491.9 1730.09  5521.9 1731.43  5621.9 1732.09  5691.9 1734.82  5791.9  1736.7
#Mann= 3 ,-1 , 0
  4456.1     .05       0  4969.2     .03       0  5030.9     .05       0
Bank Sta=4969.2,5030.9
XS Rating Curve= 0 ,0
Exp/Cntr=0.3,0.1

Type RM Length L Ch R = 1 ,12389   ,492,492,492
BEGIN DESCRIPTION:
Mapping XS bc94589d
END DESCRIPTION:
XS GIS Cut Line= 3
      1595687.96       6837746.6       1597191.4        6837573.
      1598274.72      6837479.25
#Sta/Elev= 30
  4127.5 1730.44  4215.1 1729.02  4509.8 1728.26  4593.7 1725.59  4688.2 1719.97
  4738.6  1718.3  4766.4 1716.01  4778.8 1712.09    4809 1710.78  4819.1 1707.24
  4829.2  1706.3  4969.2  1706.3  4970.7  1705.3  5029.4  1705.3  5030.9  1706.3
  5205.8  1706.3  5211.7 1709.05  5231.8 1710.93  5241.9 1716.42  5332.5 1730.61
    5564 1732.74  5845.3 1738.96  5989.8 1739.17    6036 1741.28    6307 1742.88
  6457.7 1745.23  6507.8 1743.65  6618.2 1747.84  6698.5 1746.54  6728.3 1747.33
#Mann= 3 ,-1 , 0
  4127.5     .05       0  4969.2     .03       0  5030.9     .05       0
Bank Sta=4969.2,5030.9
XS Rating Curve= 0 ,0
Exp/Cntr=0.3,0.1