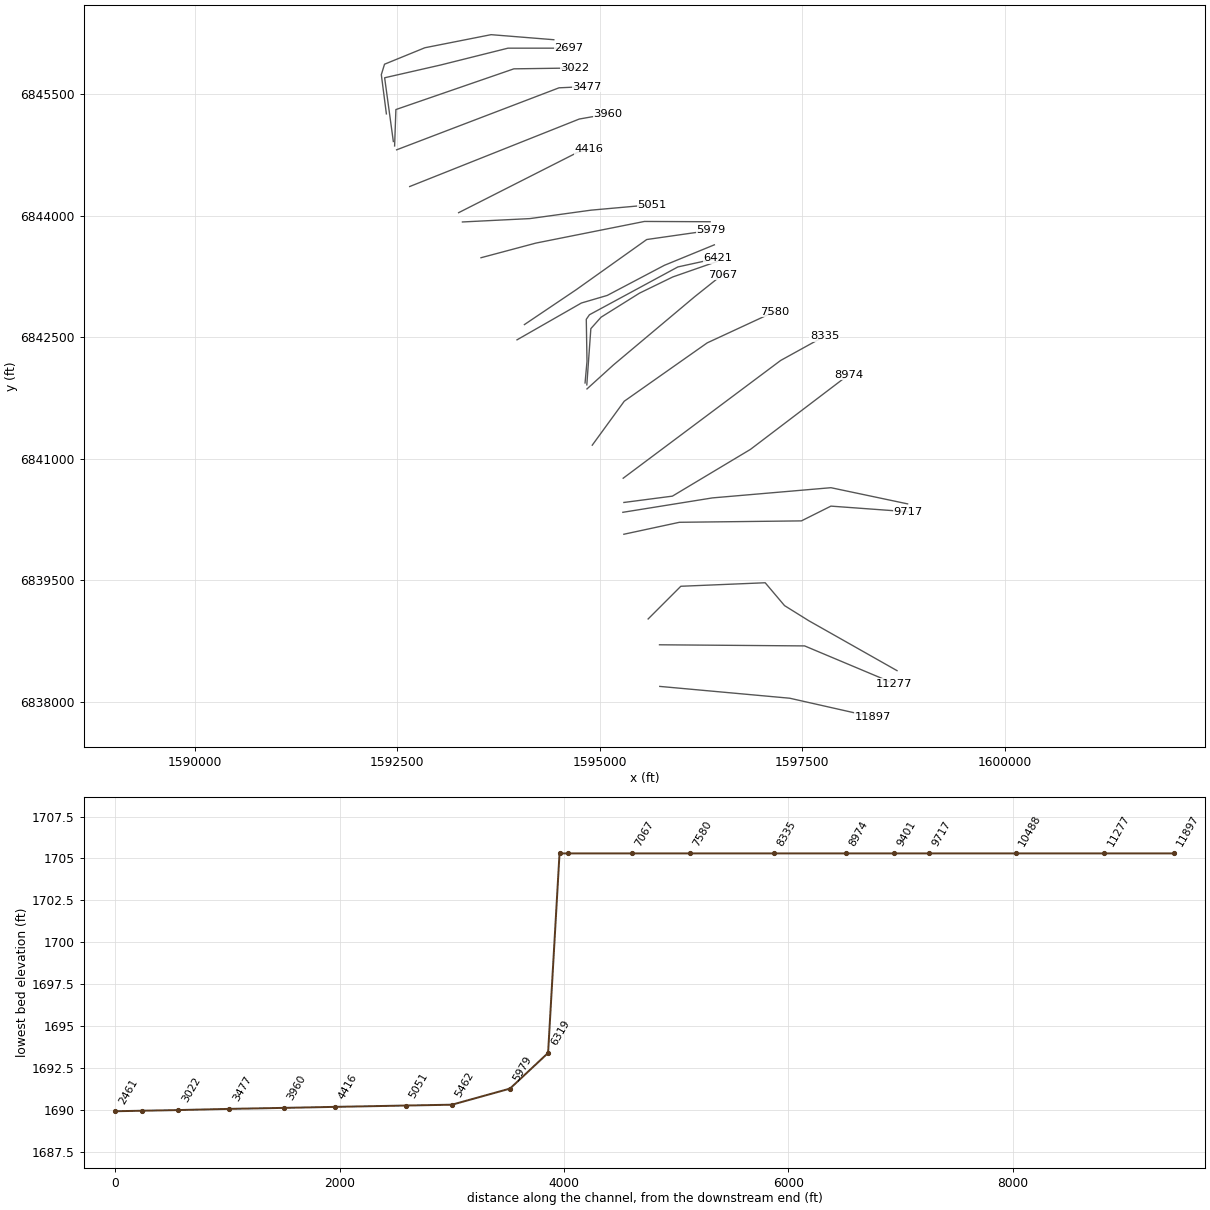
HEC-RAS study Lytle Creek.prj: Lytle Creek Base Level Engineering

--- Lytle Creek.g01 (geometry) --- (continued)

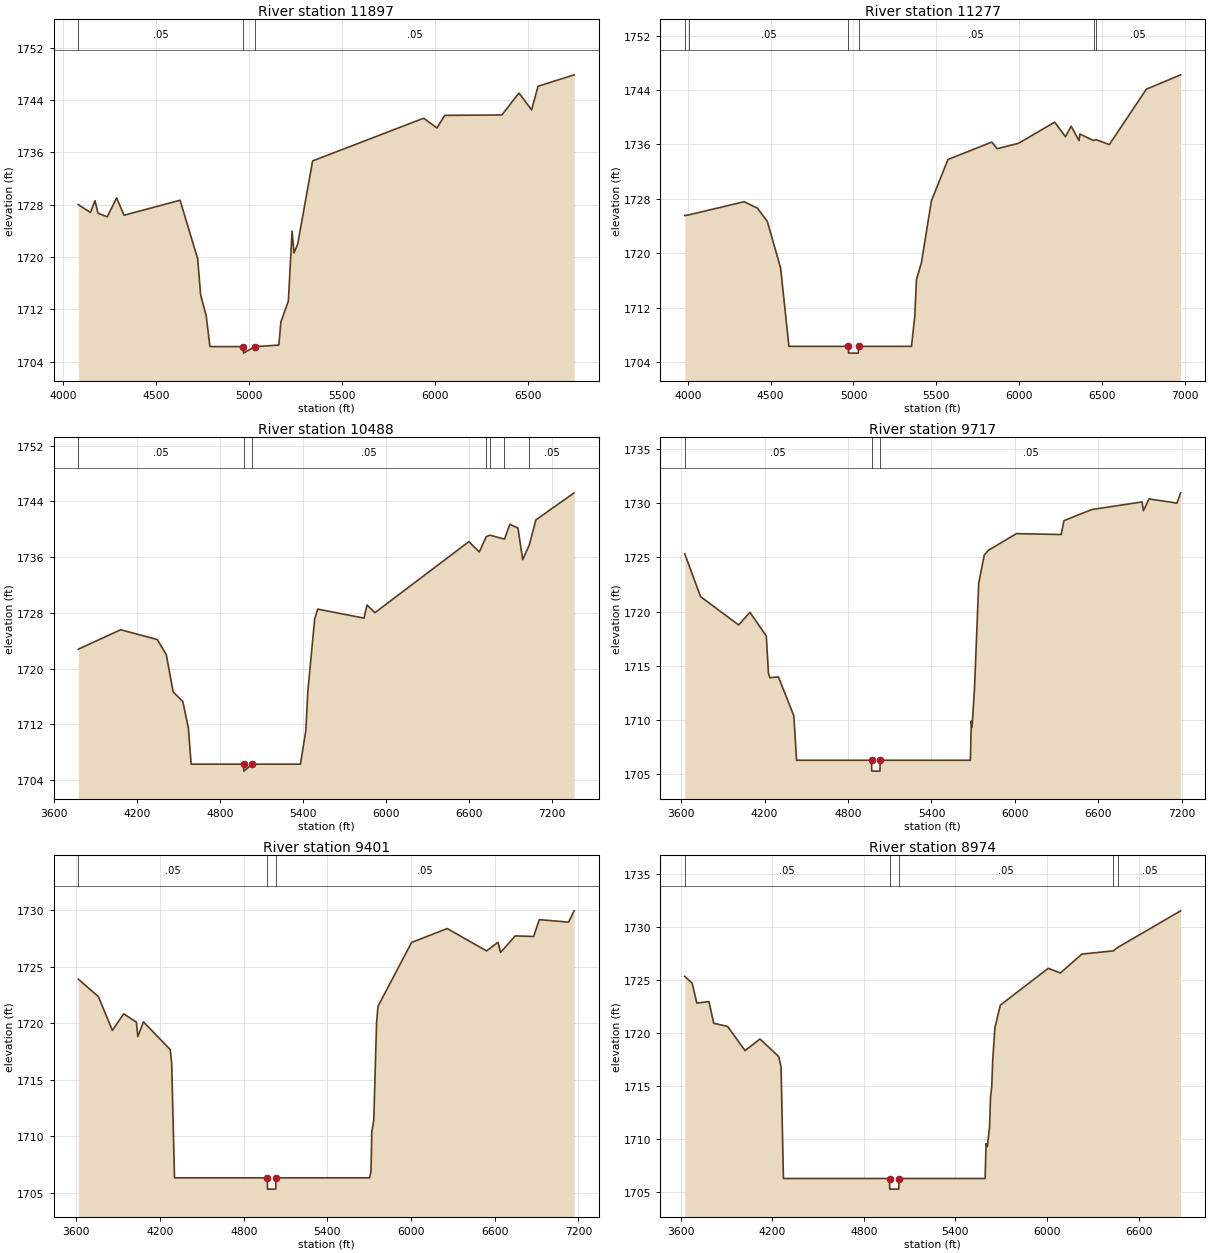
Type RM Length L Ch R = 1 ,11897   ,620,620,620
BEGIN DESCRIPTION:
Mapping XS fcdb02d6
END DESCRIPTION:
XS GIS Cut Line= 3
      1595739.98      6838191.05      1597344.17      6838045.22
      1598374.47      6837812.79
#Sta/Elev= 30
  4081.9 1728.02  4147.2 1726.82  4171.6 1728.63  4187.4 1726.71  4237.6 1726.16
  4287.8 1729.05  4327.9  1726.4  4629.2 1728.69  4723.8 1719.74  4739.6 1714.23
  4769.7 1711.01  4789.8  1706.3  4969.2  1706.3  4970.7  1705.3  5030.9  1706.3
  5160.6 1706.53  5171.4 1710.08  5211.6 1713.26  5231.6 1723.97  5241.7 1720.62
  5261.8 1721.97  5342.1 1734.71  5939.6 1741.24  6011.3 1739.75  6052.4 1741.68
  6359.9 1741.74  6452.2 1745.09  6519.8 1742.52  6554.7 1746.13  6748.9 1747.88
#Mann= 3 ,-1 , 0
  4081.9     .05       0  4969.2     .03       0  5030.9     .05       0
Bank Sta=4969.2,5030.9
XS Rating Curve= 0 ,0
Exp/Cntr=0.3,0.1

Type RM Length L Ch R = 1 ,11277   ,789,789,789
BEGIN DESCRIPTION:
Mapping XS 984a383e
END DESCRIPTION:
XS GIS Cut Line= 3
       1595736.5      6838704.94       1597528.2      6838691.05
      1598635.88      6838225.76
#Sta/Elev= 30
  3981.8 1725.55  4005.7 1725.64  4340.3 1727.58  4420.3 1726.63  4480.3 1724.66
  4560.3 1717.82  4610.3  1706.3  4969.2  1706.3  4970.7  1705.3  5029.4  1705.3
  5030.9  1706.3  5350.3  1706.3  5370.3 1710.76  5380.3 1716.11  5410.3 1718.61
  5470.3 1727.68  5570.4 1733.79  5835.2 1736.36    5867 1735.37  5996.7 1736.18
  6214.8 1739.29  6279.7 1737.15  6314.3 1738.68  6361.8 1736.56  6367.2 1737.54
  6449.9 1736.57  6462.7 1736.73  6544.4 1735.98    6768 1744.13    6975 1746.25
#Mann= 6 ,-1 , 0
  3981.8    .075       0  4005.7     .05       0  4969.2     .03       0
  5030.9     .05       0  6449.9    .075       0  6462.7     .05       0
Bank Sta=4969.2,5030.9
XS Rating Curve= 0 ,0
Exp/Cntr=0.3,0.1

Type RM Length L Ch R = 1 ,10488   ,771,771,771
BEGIN DESCRIPTION:
Mapping XS 10ce9f81
END DESCRIPTION:
XS GIS Cut Line= 6
      1595596.12      6839023.72      1595999.77      6839427.38
      1597041.44      6839470.78      1597280.16      6839188.67
      1597579.63      6839002.03      1598669.02      6838385.73
#Sta/Elev= 30
  3773.3  1722.8  4079.6 1725.59  4344.2 1724.19  4409.4 1722.04  4459.5 1716.67
  4529.5 1715.28  4569.6 1711.47  4589.6  1706.3  4969.2  1706.3  4970.7  1705.3
  5030.9  1706.3  5380.3  1706.3  5419.3  1711.1  5433.6 1716.66    5483 1727.07
    5505 1728.55  5840.6 1727.26  5861.8 1729.14  5919.7 1728.04  6599.1 1738.24
  6674.2 1736.75  6724.4 1738.94  6751.4 1739.16  6856.7  1738.6  6895.1 1740.72
  6954.1 1740.19  6988.5 1735.64  7036.3 1737.77  7084.1 1741.36  7360.8 1745.24
#Mann= 7 ,-1 , 0
  3773.3     .05       0  4969.2     .03       0  5030.9     .05       0
  6724.4    .075       0  6751.4     .05       0  6856.7    .075       0
  7036.3     .05       0
Bank Sta=4969.2,5030.9
XS Rating Curve= 0 ,0
Exp/Cntr=0.3,0.1

Type RM Length L Ch R = 1 ,9717    ,316,316,316
BEGIN DESCRIPTION:
Mapping XS c2292043
END DESCRIPTION:
XS GIS Cut Line= 5
      1595296.64      6840069.74      1595982.41      6840217.31
      1597488.49      6840234.67      1597853.07      6840416.96
      1598801.78      6840347.65
#Sta/Elev= 30
  3625.9 1725.32  3739.2 1721.38  4012.9 1718.77  4094.7 1719.93  4212.1 1717.75
  4227.7  1714.3    4238 1713.91  4299.3 1713.98    4410 1710.41    4430  1706.3
  4968.9  1706.3  4970.4  1705.3  5029.6  1705.3  5031.1  1706.3    5680  1706.3
  5686.8 1709.91  5691.8 1709.35    5710 1712.95    5740 1722.62  5780.1 1725.21
  5810.1 1725.65  6011.4 1727.18  6333.3  1727.1  6353.4 1728.38  6553.9  1729.4
  6914.9  1730.1  6924.9 1729.29    6965 1730.38  7165.5 1729.99  7192.4 1730.94
#Mann= 3 ,-1 , 0
  3625.9     .05       0  4968.9     .03       0  5031.1     .05       0
Bank Sta=4968.9,5031.1
XS Rating Curve= 0 ,0
Exp/Cntr=0.3,0.1

Type RM Length L Ch R = 1 ,9401    ,427,427,427
BEGIN DESCRIPTION:
Mapping XS 3c507853
END DESCRIPTION:
XS GIS Cut Line= 4
      1595283.99      6840340.62      1596390.72      6840518.56
       1597853.4      6840644.43      1598799.54      6840444.79
#Sta/Elev= 30
  3613.8 1723.89  3758.2 1722.34  3857.9 1719.35  3938.8 1720.82  4030.1 1720.09
  4040.2  1718.8  4080.7 1720.11  4273.2 1717.65  4283.3 1716.43  4303.6  1706.3
  4968.9  1706.3  4970.4  1705.3  5029.6  1705.3  5031.1  1706.3  5702.6  1706.3
  5712.6 1706.83  5718.6 1710.33  5732.7 1711.42  5752.8 1720.04  5762.8 1721.48
  6003.7 1727.14  6259.4 1728.37  6541.7 1726.39  6623.5 1727.15  6642.2 1726.26
  6746.9 1727.72    6879 1727.67  6919.9 1729.16  7129.7 1728.94  7169.8 1729.94
#Mann= 3 ,-1 , 0
  3613.8     .05       0  4968.9     .03       0  5031.1     .05       0
Bank Sta=4968.9,5031.1
XS Rating Curve= 0 ,0
Exp/Cntr=0.3,0.1

Type RM Length L Ch R = 1 ,8974    ,639,639,639
BEGIN DESCRIPTION:
Mapping XS f694fd06
END DESCRIPTION:
XS GIS Cut Line= 4
      1595296.92      6840462.13      1595895.93      6840540.26
      1596859.47      6841117.52       1598070.2       6842037.5
#Sta/Elev= 30
  3627.8 1725.32  3676.3 1724.67  3706.5 1722.81  3785.7 1722.95  3817.5 1720.91
  3908.2 1720.61  4022.6 1718.33    4120 1719.43  4242.7 1717.78  4258.3 1716.83
  4273.9  1706.3  4968.8  1706.3  4970.3  1705.3  5029.7  1705.3  5031.2  1706.3
    5595  1706.3  5601.3 1709.59  5609.5 1709.29  5624.1 1711.16  5630.3 1713.92
  5638.4 1714.94  5644.9 1717.47  5659.4 1720.51  5694.8 1722.62  6008.8 1726.08
  6087.8 1725.64  6229.3 1727.42  6434.2 1727.72  6465.7 1728.06  6875.7 1731.49
#Mann= 5 ,-1 , 0
  3627.8     .05       0  4968.8     .03       0  5031.2     .05       0
  6434.2    .075       0  6465.7     .05       0
Bank Sta=4968.8,5031.2
XS Rating Curve= 0 ,0
Exp/Cntr=0.3,0.1

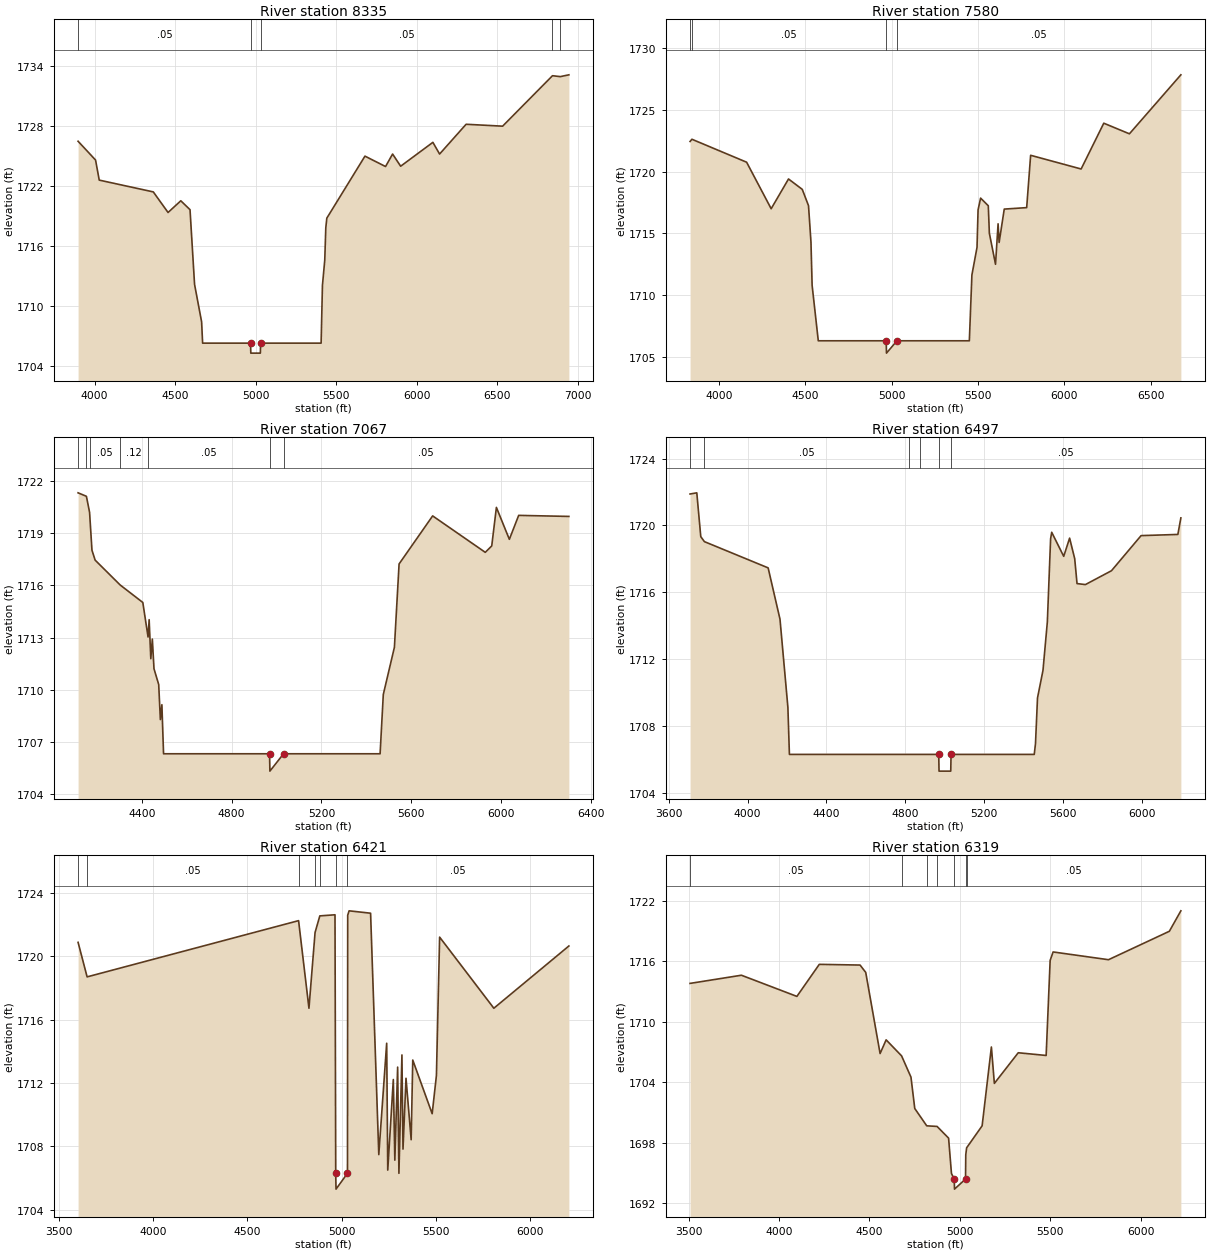
Type RM Length L Ch R = 1 ,8335    ,755,755,755
BEGIN DESCRIPTION:
Mapping XS 9461dd3d
END DESCRIPTION:
XS GIS Cut Line= 3
      1595288.33      6840761.64      1597232.74      6842215.61
      1597775.26      6842515.08
#Sta/Elev= 30
  3897.8 1726.51  4006.3 1724.63  4029.2 1722.62  4364.8 1721.44  4456.5 1719.38
  4535.7 1720.55  4592.9 1719.66  4621.1 1712.18  4664.9 1708.43  4671.1  1706.3
  4968.8  1706.3  4970.3  1705.3  5029.7  1705.3  5031.2  1706.3  5406.9  1706.3
  5415.2 1712.09  5429.5  1714.6    5436 1717.85  5442.3 1718.81  5679.2 1725.02
    5807 1723.98  5850.8 1725.23  5900.8 1724.01  6100.9  1726.4  6142.6 1725.23
  6307.2 1728.21  6533.9 1728.02  6843.5 1733.07  6892.3 1732.98  6945.4 1733.16
#Mann= 5 ,-1 , 0
  3897.8     .05       0  4968.8     .03       0  5031.2     .05       0
  6843.5    .075       0  6892.3     .05       0
Bank Sta=4968.8,5031.2
XS Rating Curve= 0 ,0
Exp/Cntr=0.3,0.1

Type RM Length L Ch R = 1 ,7580    ,513,513,513
BEGIN DESCRIPTION:
Mapping XS 5a191e74
END DESCRIPTION:
XS GIS Cut Line= 4
      1594906.37      6841169.63      1595301.31      6841712.14
      1596325.62      6842432.62      1597158.98      6842818.92
#Sta/Elev= 30
  3833.1 1722.45  3843.8 1722.63  4160.5 1720.77  4302.7    1717  4403.1 1719.41
  4482.7 1718.57  4518.9 1717.25  4533.1 1714.31  4539.8 1710.79  4575.5  1706.3
  4968.8  1706.3  4970.3  1705.3  5031.2  1706.3  5450.2  1706.3    5465 1711.63
  5494.6 1713.87  5500.7 1716.91  5515.5 1717.86  5559.9 1717.24  5566.1 1715.01
  5601.8  1712.5  5616.6 1715.78  5622.7 1714.27  5652.3 1716.97  5782.2 1717.09
  5805.1 1721.33  6097.5 1720.22  6228.6 1723.93  6377.1 1723.07    6675 1727.85
#Mann= 4 ,-1 , 0
  3833.1    .075       0  3843.8     .05       0  4968.8     .03       0
  5031.2     .05       0
Bank Sta=4968.8,5031.2
XS Rating Curve= 0 ,0
Exp/Cntr=0.3,0.1

Type RM Length L Ch R = 1 ,7067    ,570,570,570
BEGIN DESCRIPTION:
Mapping XS 61d46f32
END DESCRIPTION:
XS GIS Cut Line= 4
      1594841.24      6841864.04      1595166.77      6842159.19
      1596169.37       6843001.2      1596512.22      6843274.61
#Sta/Elev= 30
  4115.5 1721.34  4152.6 1721.14  4166.7 1720.22  4177.4 1718.03  4191.6 1717.46
  4302.9 1716.03    4404 1715.02  4427.4 1713.03  4432.2 1714.03  4439.6 1711.78
  4446.4 1712.91  4453.8  1711.2  4474.8 1710.29  4482.2 1708.27    4489 1709.13
  4496.4  1706.3  4968.8  1706.3  4970.3  1705.3  5031.2  1706.3  5461.4  1706.3
  5475.7 1709.72  5525.2 1712.44    5546 1717.24  5695.6 1720.01  5930.1 1717.91
  5958.9 1718.28  5979.7  1720.5  6037.4 1718.66    6079 1720.04  6302.7 1719.98
#Mann= 7 ,-1 , 0
  4115.5     .05       0  4152.6     .12       0  4166.7     .05       0
  4302.9     .12       0  4427.4     .05       0  4968.8     .03       0
  5031.2     .05       0
Bank Sta=4968.8,5031.2
XS Rating Curve= 0 ,0
Exp/Cntr=0.3,0.1

Type RM Length L Ch R = 1 ,6497    ,76,76,76
BEGIN DESCRIPTION:
Mapping XS e246b9a7
END DESCRIPTION:
XS GIS Cut Line= 6
      1594839.08        6841914.      1594888.99      6842608.41
      1595014.86      6842749.47      1595490.12      6843046.77
      1595900.27      6843246.43      1596451.84      6843438.93
#Sta/Elev= 30
  3708.7 1721.88  3742.8 1721.95  3762.9 1719.33  3781.3 1719.03  4104.3 1717.46
  4164.4 1714.39  4204.4 1709.12  4212.1  1706.3  4815.9  1706.3  4875.4  1706.3
  4968.8  1706.3  4970.3  1705.3  5029.7  1705.3  5031.2  1706.3  5452.8  1706.3
  5459.2 1706.96  5469.3 1709.68  5497.1 1711.33  5519.2 1714.23  5535.7  1719.2
  5541.3 1719.59  5602.1 1718.15    5632 1719.24  5657.8 1718.01  5669.6 1716.52
  5711.9 1716.46  5844.2 1717.29  5994.2 1719.39  6180.5 1719.46  6195.8 1720.45
#Mann= 6 ,-1 , 0
  3708.7     .12       0  3781.3     .05       0  4815.9     .12       0
  4875.4     .05       0  4968.8     .03       0  5031.2     .05       0
Bank Sta=4968.8,5031.2
XS Rating Curve= 0 ,0
Exp/Cntr=0.3,0.1

Type RM Length L Ch R = 1 ,6421    ,102,102,102
BEGIN DESCRIPTION:
Mapping XS 61c250d7
END DESCRIPTION:
XS GIS Cut Line= 6
      1594817.37      6841937.79      1594841.24      6842202.59
      1594832.56      6842723.42      1594871.63      6842779.85
      1595963.21      6843370.12      1596457.98      6843478.63
#Sta/Elev= 30
  3600.4 1720.88  3648.4  1718.7  4771.5 1722.25  4826.6 1716.72    4859  1721.5
  4884.3 1722.55  4964.9 1722.62  4968.8  1706.3  4970.3  1705.3  5031.2  1706.3
  5032.4 1722.59  5039.8 1722.87  5153.9 1722.72  5197.5 1707.48  5239.4 1714.51
  5245.1  1706.5  5274.7 1712.22  5282.7 1707.13  5297.6    1713  5304.4  1706.3
  5320.4 1713.77  5326.1 1707.83    5342  1712.3  5369.4 1708.42  5377.9 1713.45
    5481 1710.06  5503.6 1712.48  5520.6 1721.21  5808.6 1716.72  6207.1 1720.65
#Mann= 7 ,-1 , 0
  3600.4     .12       0  3648.4     .05       0  4771.5     .12       0
    4859     .05       0  4884.3     .12       0  4968.8     .05       0
  5031.2     .05       0
Bank Sta=4968.8,5031.2
XS Rating Curve= 0 ,0
Exp/Cntr=0.3,0.1

Type RM Length L Ch R = 1 ,6319    ,340,340,340
BEGIN DESCRIPTION:
Mapping XS b8d173da
END DESCRIPTION:
XS GIS Cut Line= 5
      1593977.12      6842469.97      1594772.23      6842924.81
      1595091.68      6843018.56      1595796.54      6843390.09
      1596413.92      6843643.28
#Sta/Elev= 30
  3508.6  1713.8  3792.5 1714.61  4099.1 1712.51  4222.9 1715.69  4448.3 1715.62
  4479.6 1714.89    4559 1706.84  4592.4  1708.2  4677.8 1706.61  4729.7  1704.5
  4750.6 1701.39  4816.8 1699.67    4874 1699.61  4937.6 1698.45  4953.5 1694.94
  4968.8 1694.39  4970.3 1693.39  5031.2 1694.39  5032.6  1696.8  5037.4 1697.49
    5123 1699.67  5174.2 1707.49  5190.6 1703.88  5322.7 1706.92  5476.9 1706.65
    5499 1716.08  5515.3 1716.92  5821.5 1716.15  6157.9 1718.97  6221.6    1721
#Mann= 7 ,-1 , 0
  3508.6     .05       0  4677.8     .12       0  4816.8     .05       0
    4874     .12       0  4968.8     .07       0  5031.2     .12       0
  5037.4     .05       0
Bank Sta=4968.8,5031.2
XS Rating Curve= 0 ,0
Exp/Cntr=0.3,0.1

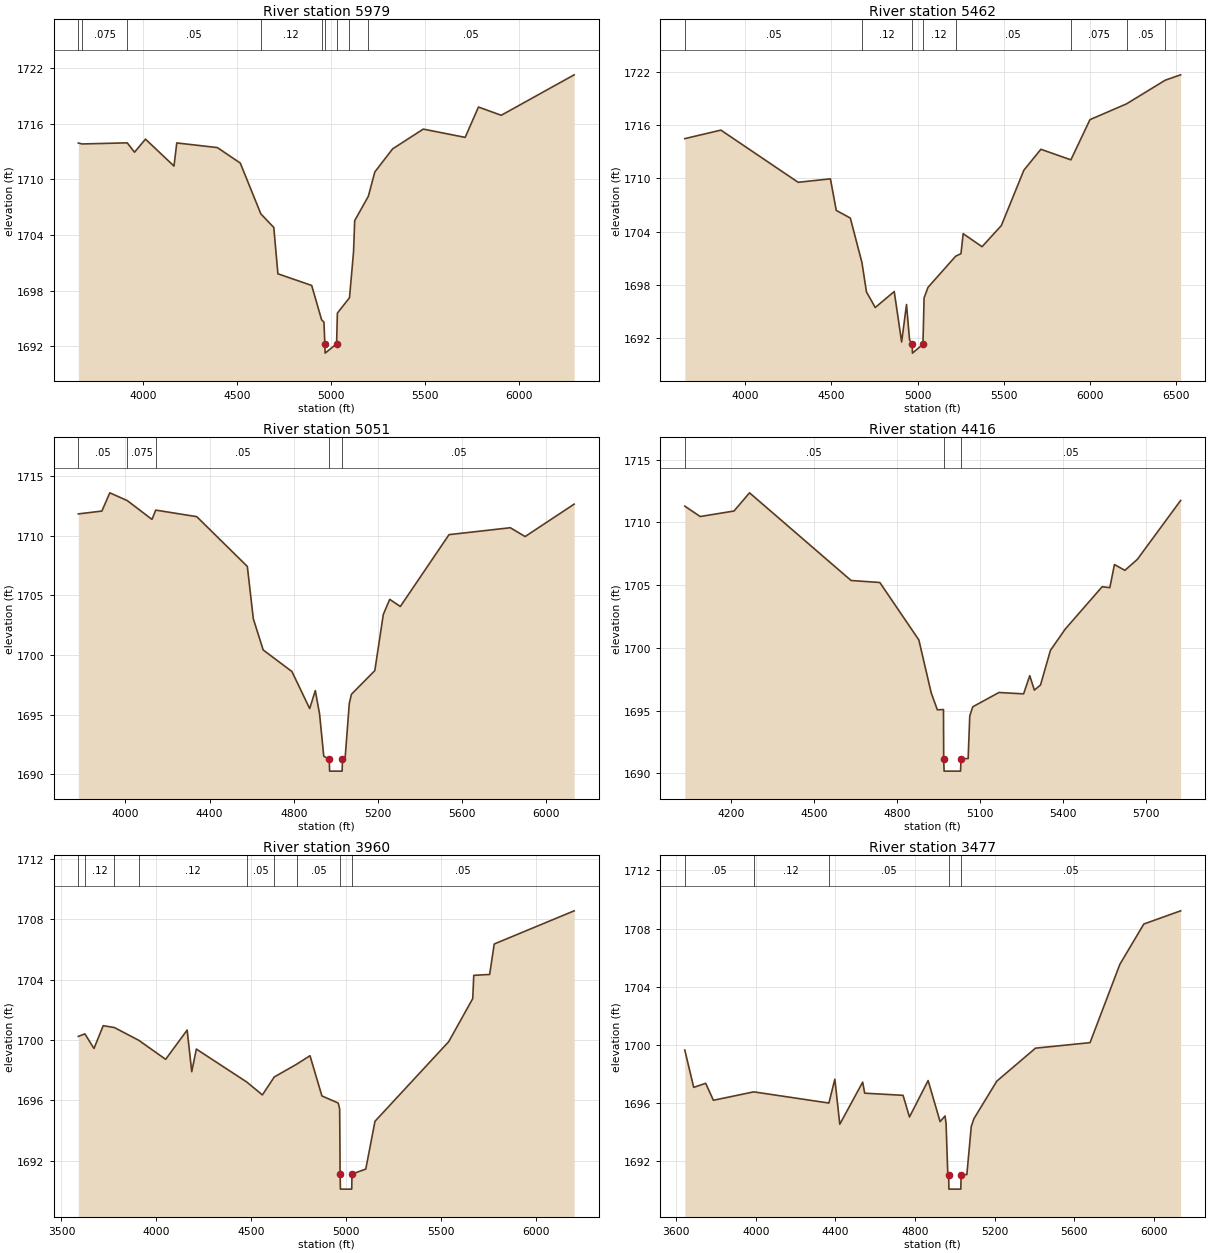
Type RM Length L Ch R = 1 ,5979    ,517,517,517
BEGIN DESCRIPTION:
Mapping XS 37e76429
END DESCRIPTION:
XS GIS Cut Line= 4
      1594068.66      6842658.31       1594706.7      6843088.01
      1595579.09      6843708.67      1596368.99      6843821.51
#Sta/Elev= 30
  3657.3  1713.9  3677.7  1713.8  3917.4 1713.92  3956.2 1712.91  4014.6 1714.32
  4166.1 1711.42  4181.1 1713.91    4397 1713.41  4518.9 1711.74  4628.2 1706.27
  4697.2  1704.8    4719 1699.81  4898.9 1698.55  4951.5 1694.85  4964.1  1694.6
  4968.8 1692.26  4970.3 1691.26  5031.3 1692.26  5035.4 1695.57  5099.9 1697.23
  5121.5 1702.19  5127.6 1705.54  5200.1 1708.16  5234.6 1710.78  5329.3 1713.27
  5492.3  1715.4  5715.3 1714.51    5786 1717.78  5907.2 1716.89  6295.1 1721.25
#Mann= 9 ,-1 , 0
  3657.3     .05       0  3677.7    .075       0  3917.4     .05       0
  4628.2     .12       0  4951.5     .05       0  4968.8     .03       0
  5031.3     .05       0  5099.9     .12       0  5200.1     .05       0
Bank Sta=4968.8,5031.3
XS Rating Curve= 0 ,0
Exp/Cntr=0.3,0.1

Type RM Length L Ch R = 1 ,5462    ,411,411,411
BEGIN DESCRIPTION:
Mapping XS 6eee6da3
END DESCRIPTION:
XS GIS Cut Line= 4
      1593532.65      6843483.84      1594209.73       6843664.4
      1595550.01      6843931.76      1596361.28      6843928.29
#Sta/Elev= 30
  3648.6 1714.47    3858 1715.43  4306.7 1709.55    4494 1709.94  4528.1 1706.38
  4609.6 1705.52    4677 1700.51  4703.3  1697.2  4754.3 1695.44  4864.6 1697.24
  4907.5 1691.56  4935.9 1695.78  4953.4  1691.8  4968.8  1691.3  4970.3  1690.3
  5031.3  1691.3  5037.9 1696.52  5060.6 1697.71    5221 1701.22  5252.1 1701.51
  5264.8 1703.76  5374.4 1702.29  5486.6 1704.68  5617.1 1710.91    5716 1713.27
  5890.2 1712.08    6001 1716.61  6213.4 1718.39  6438.4 1721.06  6527.3 1721.66
#Mann= 8 ,-1 , 0
  3648.6     .05       0    4677     .12       0  4968.8     .07       0
  5031.3     .12       0    5221     .05       0  5890.2    .075       0
  6213.4     .05       0  6438.4    .075       0
Bank Sta=4968.8,5031.3
XS Rating Curve= 0 ,0
Exp/Cntr=0.3,0.1

Type RM Length L Ch R = 1 ,5051    ,635,635,635
BEGIN DESCRIPTION:
Mapping XS a91f2043
END DESCRIPTION:
XS GIS Cut Line= 4
      1593303.26      6843925.41      1594136.57      6843967.07
      1594891.78      6844071.24      1595646.94      6844138.94
#Sta/Elev= 30
  3776.8 1711.84  3888.7 1712.08  3926.3 1713.61  4009.1 1712.96  4126.5 1711.38
  4144.5 1712.16  4339.2 1711.61  4579.5 1707.43  4607.9 1703.04  4654.8 1700.42
  4791.3 1698.61  4875.6  1695.5  4902.3 1697.01  4922.5 1695.06  4942.5  1691.5
  4968.7 1691.25  4970.2 1690.25  5029.8 1690.25  5031.3 1691.25  5043.6 1691.28
  5063.8 1695.94  5073.9  1696.7    5185 1698.69  5225.3  1703.4  5255.6 1704.67
  5306.1 1704.07  5537.4  1710.1  5828.5 1710.68  5898.8 1709.94  6131.7 1712.66
#Mann= 5 ,-1 , 0
  3776.8     .05       0  4009.1    .075       0  4144.5     .05       0
  4968.7     .05       0  5031.3     .05       0
Bank Sta=4968.7,5031.3
XS Rating Curve= 0 ,0
Exp/Cntr=0.3,0.1

Type RM Length L Ch R = 1 ,4416    ,456,456,456
BEGIN DESCRIPTION:
Mapping XS 28d35157
END DESCRIPTION:
XS GIS Cut Line= 3
      1593256.33      6844039.97      1594725.11      6844784.78
      1594865.73      6844821.24
#Sta/Elev= 30
    4033  1711.3  4088.6 1710.47  4210.9 1710.91    4267 1712.36    4634 1705.37
  4737.9 1705.21    4879 1700.63  4923.5 1696.42  4945.8 1695.06    4968 1695.08
  4968.7 1691.17  4970.2 1690.17  5029.8 1690.17  5031.3 1691.17  5057.1 1691.17
    5063 1694.57  5073.8  1695.3  5168.5 1696.44  5257.5 1696.33  5279.8 1697.78
  5296.5 1696.63  5318.7 1697.04  5354.6  1699.8  5407.8 1701.49  5541.4 1704.87
  5569.3  1704.8  5585.9 1706.64  5623.7 1706.18  5668.5 1707.05  5825.1 1711.75
#Mann= 3 ,-1 , 0
    4033     .05       0  4968.7     .05       0  5031.3     .05       0
Bank Sta=4968.7,5031.3
XS Rating Curve= 0 ,0
Exp/Cntr=0.3,0.1

Type RM Length L Ch R = 1 ,3960    ,483,483,483
BEGIN DESCRIPTION:
Mapping XS e9e981e6
END DESCRIPTION:
XS GIS Cut Line= 3
      1592652.22      6844362.91      1594745.95      6845196.24
       1595100.1      6845258.74
#Sta/Elev= 30
    3589 1700.24  3623.5 1700.41  3671.5 1699.44  3720.1 1700.95  3778.7 1700.83
  3907.7 1699.98  4049.2 1698.72  4162.5 1700.66  4186.7  1697.9    4211  1699.4
    4476 1697.22    4559 1696.36  4621.7 1697.55  4738.9 1698.39  4809.9 1698.96
  4872.8 1696.29  4958.9 1695.82  4966.3 1695.41  4968.7 1691.11  4970.2 1690.11
  5029.8 1690.11  5031.3 1691.11  5103.9 1691.44  5152.5 1694.61  5540.9 1699.89
  5667.7 1702.75    5673 1704.29  5756.7 1704.35  5780.9 1706.37  6202.1 1708.57
#Mann= 9 ,-1 , 0
    3589     .05       0  3623.5     .12       0  3778.7    .075       0
  3907.7     .12       0    4476     .05       0  4621.7     .12       0
  4738.9     .05       0  4968.7     .05       0  5031.3     .05       0
Bank Sta=4968.7,5031.3
XS Rating Curve= 0 ,0
Exp/Cntr=0.3,0.1

Type RM Length L Ch R = 1 ,3477    ,455,455,455
BEGIN DESCRIPTION:
Mapping XS 03b72a6c
END DESCRIPTION:
XS GIS Cut Line= 3
      1592490.76      6844816.04      1594495.95      6845581.66
      1594839.71      6845597.28
#Sta/Elev= 30
  3643.5 1699.63  3688.3 1697.06  3748.4 1697.34  3787.2 1696.17  3989.8 1696.75
  4367.2 1695.98  4397.3 1697.62    4422 1694.52    4537 1697.42  4547.2 1696.66
  4739.9 1696.51    4772 1695.02  4865.7 1697.53  4925.9  1694.7  4950.6 1695.09
  4955.9 1694.57  4964.6 1691.05  4968.7 1691.05  4970.2 1690.05  5029.9 1690.05
  5031.4 1691.05  5060.2 1691.05  5082.4 1694.36  5095.6  1694.9  5210.8 1697.49
    5405 1699.76    5679 1700.14    5829 1705.54  5949.1 1708.31    6134 1709.22
#Mann= 5 ,-1 , 0
  3643.5     .05       0  3989.8     .12       0  4367.2     .05       0
  4968.7     .03       0  5031.4     .05       0
Bank Sta=4968.7,5031.4
XS Rating Curve= 0 ,0
Exp/Cntr=0.3,0.1

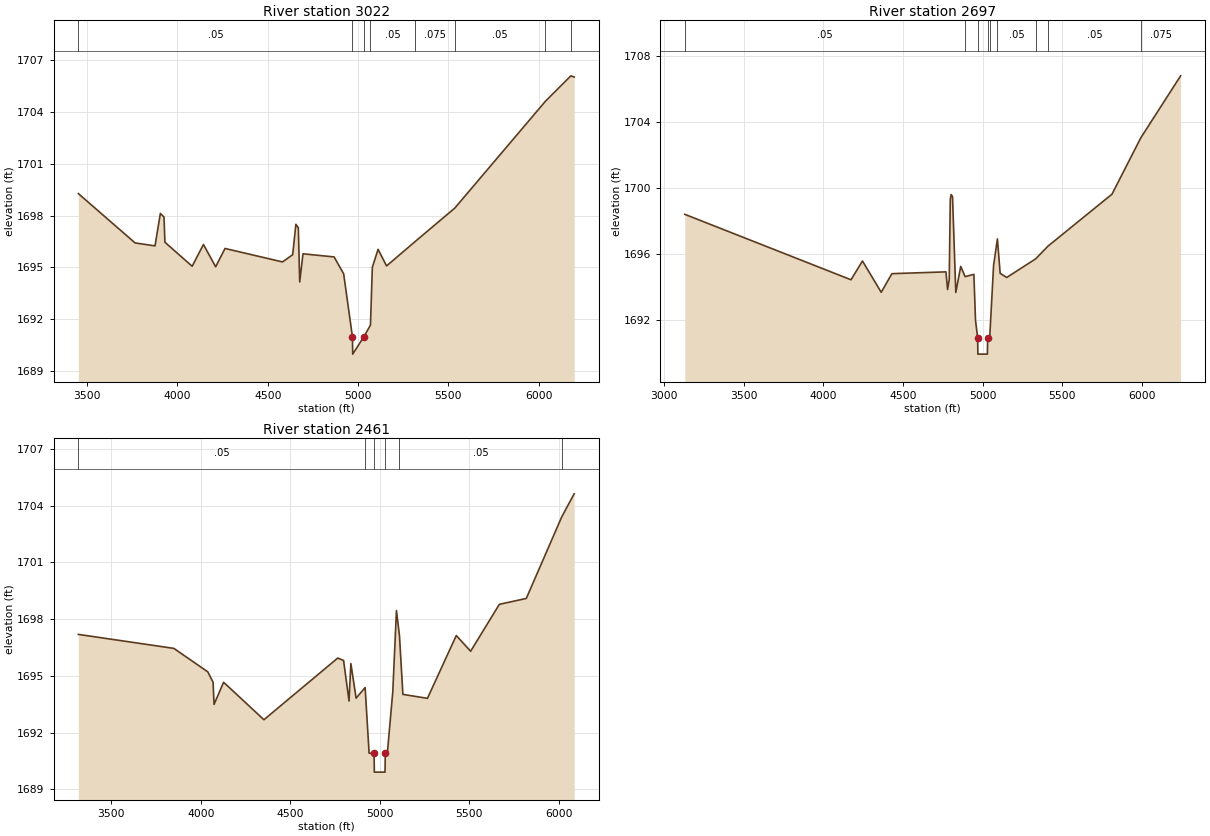
Type RM Length L Ch R = 1 ,3022    ,325,325,325
BEGIN DESCRIPTION:
Mapping XS 52a88089
END DESCRIPTION:
XS GIS Cut Line= 4
      1592465.97       6844863.9      1592481.97      6845313.37
      1593938.66      6845816.03      1594691.95      6845826.42
#Sta/Elev= 30
  3451.7 1699.28    3766 1696.42  3876.1 1696.25  3905.7 1698.13  3925.8 1697.92
    3931 1696.46  4081.7 1695.07  4144.1 1696.33  4211.8 1695.04  4263.6  1696.1
  4581.7 1695.32    4638 1695.74  4655.7  1697.5  4669.2  1697.3  4676.9 1694.16
  4695.1 1695.79  4867.3 1695.61  4920.2 1694.63  4968.7 1690.98  4970.2 1689.98
  5031.4 1690.98  5068.5 1691.66  5078.9 1695.01  5110.6 1696.05  5157.7 1695.09
  5316.7 1696.51  5535.3 1698.44  6036.2 1704.62  6177.5  1706.1  6195.8 1706.03
#Mann= 8 ,-1 , 0
  3451.7     .05       0  4968.7     .07       0  5031.4     .05       0
  5068.5     .05       0  5316.7    .075       0  5535.3     .05       0
  6036.2    .075       0  6177.5      .1       0
Bank Sta=4968.7,5031.4
XS Rating Curve= 0 ,0
Exp/Cntr=0.3,0.1

Type RM Length L Ch R = 1 ,2697    ,236,236,236
BEGIN DESCRIPTION:
Mapping XS 53d90626
END DESCRIPTION:
XS GIS Cut Line= 5
      1592450.35      6844918.58      1592342.84      6845705.72
      1593032.41      6845862.91      1593865.74      6846071.24
      1594615.74      6846071.24
#Sta/Elev= 30
  3131.5 1698.42  4174.3 1694.45  4246.1 1695.59  4363.9 1693.69  4430.7 1694.82
  4769.9 1694.93  4780.2 1693.86  4790.5 1694.46  4797.1 1699.32  4802.2 1699.62
  4811.1  1699.5  4831.7 1693.68  4862.7 1695.26  4890.2 1694.64  4945.1 1694.78
  4955.4 1691.99  4968.7 1690.94  4970.2 1689.94  5029.9 1689.94  5031.4 1690.94
  5044.4 1690.94  5068.8 1695.32  5092.8 1696.93    5110 1694.84  5151.3 1694.59
  5333.1 1695.72  5410.1 1696.49  5811.5 1699.64    5993 1703.07  6242.2 1706.82
#Mann= 9 ,-1 , 0
  3131.5     .05       0  4890.2     .12       0  4968.7     .05       0
  5031.4     .12       0  5044.4     .12       0  5092.8     .05       0
  5333.1    .075       0  5410.1     .05       0    5993    .075       0
Bank Sta=4968.7,5031.4
XS Rating Curve= 0 ,0
Exp/Cntr=0.3,0.1

Type RM Length L Ch R = 1 ,2461    ,213,213,213
BEGIN DESCRIPTION:
Mapping XS e7afadb7
END DESCRIPTION:
XS GIS Cut Line= 6
       1592364.4       6845259.8      1592301.91      6845744.14
      1592341.48       6845873.1       1592839.7      6846076.45
      1593657.41      6846237.91      1594431.75      6846175.54
#Sta/Elev= 30
  3315.5 1697.19  3849.7 1696.45  4039.3 1695.21  4068.8 1694.66  4074.2 1693.49
  4127.6 1694.66    4353 1692.68  4765.7 1695.94  4798.2 1695.81  4828.8 1693.67
    4839 1695.65  4868.3 1693.82  4918.7 1694.38    4941 1690.91  4968.7 1690.91
  4970.2 1689.91  5029.9 1689.91  5031.4 1690.91  5042.9 1690.91  5073.4 1694.17
  5093.8 1698.45  5110.8 1697.11  5129.8 1694.02  5267.1 1693.81  5428.3 1697.13
  5508.6  1696.3  5669.1 1698.78  5819.6 1699.09  6018.7 1703.42  6087.2 1704.62
#Mann= 6 ,-1 , 0
  3315.5     .05       0  4918.7     .12       0  4968.7     .07       0
  5031.4     .12       0  5110.8     .05       0  6018.7    .075       0
Bank Sta=4968.7,5031.4
XS Rating Curve= 0 ,0
Exp/Cntr=0.3,0.1