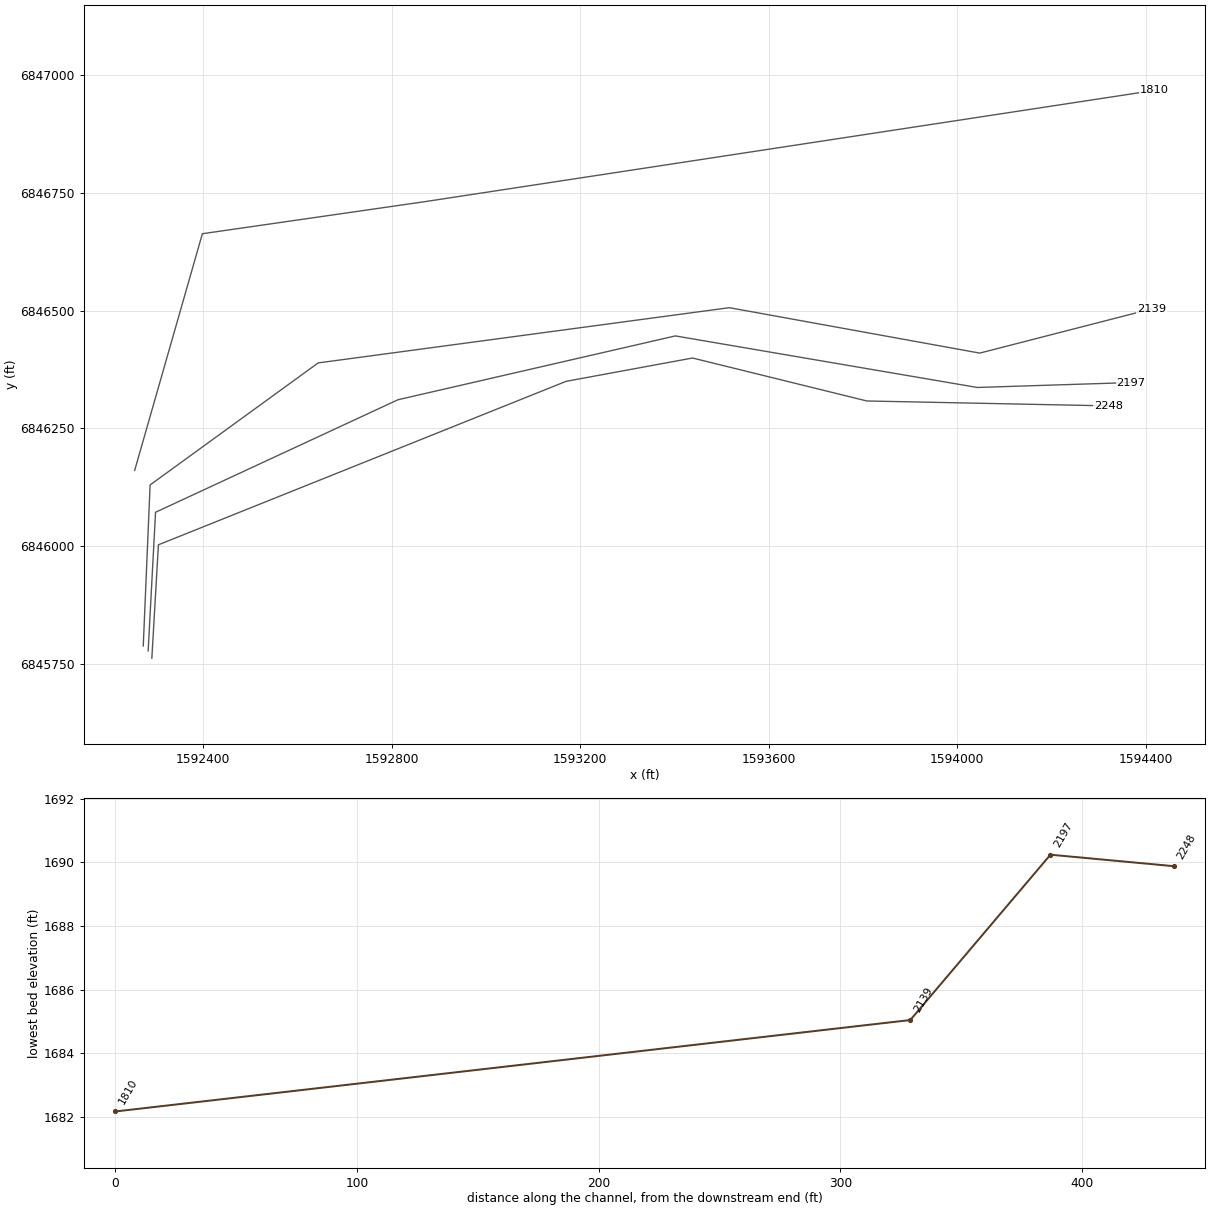
HEC-RAS study Lytle Creek.prj: Lytle Creek Base Level Engineering

--- Lytle Creek.g01 (geometry) --- (continued)

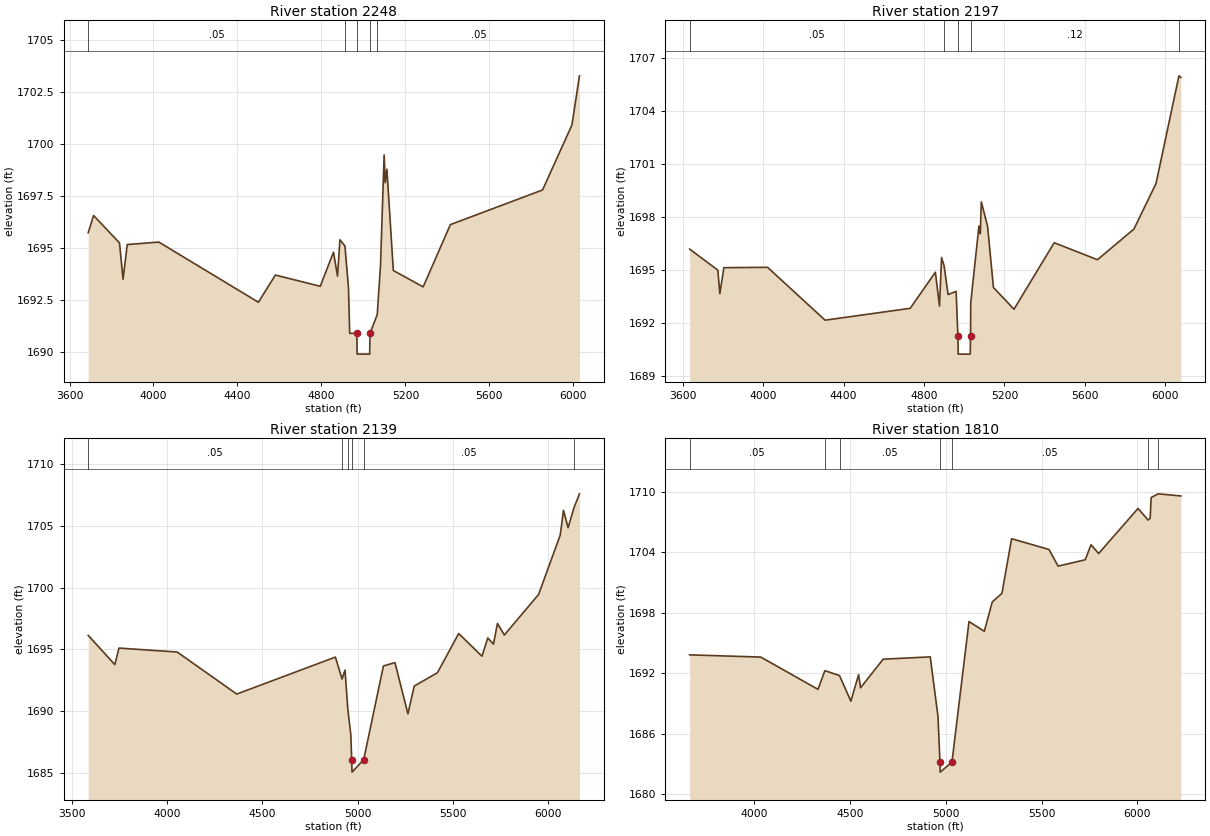
Type RM Length L Ch R = 1 ,2248    ,51,51,51
BEGIN DESCRIPTION:
Mapping XS 97d56949
END DESCRIPTION:
XS GIS Cut Line= 6
       1592291.5      6845762.42      1592305.45      6846003.09
      1593170.43      6846349.88      1593438.66      6846399.36
      1593808.45      6846308.22      1594320.76      6846297.82
#Sta/Elev= 30
  3689.1 1695.73  3714.7 1696.56    3838 1695.24    3855 1693.49    3875 1695.16
  4025.5 1695.28  4499.8 1692.38  4580.6 1693.69  4794.5 1693.15  4857.6 1694.79
  4876.7 1693.64  4888.3 1695.39  4912.1 1695.09  4928.9 1693.09  4934.8 1690.88
  4968.7 1690.88  4970.2 1689.88  5029.9 1689.88  5031.4 1690.88  5065.9 1691.78
  5081.5 1694.14  5098.8 1699.48  5103.9 1698.14    5112 1698.79  5142.6 1693.91
  5284.8 1693.12  5414.4 1696.12  5853.5 1697.79  5993.5 1700.92  6029.3 1703.29
#Mann= 5 ,-1 , 0
  3689.1     .05       0  4912.1     .12       0  4968.7     .07       0
  5031.4     .12       0  5065.9     .05       0
Bank Sta=4968.7,5031.4
XS Rating Curve= 0 ,0
Exp/Cntr=0.3,0.1

Type RM Length L Ch R = 1 ,2197    ,58,58,58
BEGIN DESCRIPTION:
Mapping XS ff393b14
END DESCRIPTION:
XS GIS Cut Line= 6
      1592283.68      6845778.03      1592299.37      6846072.13
      1592813.66      6846310.82       1593402.2      6846446.24
      1594042.82      6846336.86      1594368.34      6846347.28
#Sta/Elev= 30
  3635.1 1696.18  3775.3 1694.99  3785.3 1693.66  3805.3 1695.13  4022.6 1695.15
  4308.4 1692.16  4731.4 1692.83  4856.7 1694.87  4877.2 1692.96  4887.5  1695.7
  4899.9 1695.24  4919.9 1693.61  4959.9 1693.79  4968.7 1691.24  4970.2 1690.24
  5029.9 1690.24  5031.4 1691.24  5032.6 1693.16  5073.2 1697.48    5080 1697.05
  5085.1 1698.85  5116.2 1697.47  5145.2 1694.01  5247.5 1692.78  5447.3 1696.54
  5662.3 1695.58  5843.4 1697.31  5953.5 1699.89  6067.4 1705.98  6076.9 1705.89
#Mann= 5 ,-1 , 0
  3635.1     .05       0  4899.9     .12       0  4968.7     .03       0
  5031.4     .12       0  6067.4    .075       0
Bank Sta=4968.7,5031.4
XS Rating Curve= 0 ,0
Exp/Cntr=0.3,0.1

Type RM Length L Ch R = 1 ,2139    ,329,329,329
BEGIN DESCRIPTION:
Mapping XS eb4e3603
END DESCRIPTION:
XS GIS Cut Line= 6
      1592273.27      6845788.46      1592287.81      6846130.06
      1592644.38      6846388.95      1593516.78      6846506.13
      1594048.03      6846409.78      1594412.64      6846503.54
#Sta/Elev= 30
  3585.2 1696.14  3724.9 1693.77  3746.7 1695.11  4052.3 1694.79  4365.1 1691.38
    4883 1694.38  4917.9  1692.6  4933.4 1693.33  4948.1 1690.18  4963.7 1688.11
  4968.7 1686.05  4970.2 1685.05  5031.4 1686.05  5135.2 1693.66  5195.7 1693.93
  5263.8 1689.78  5296.9 1692.03  5418.8 1693.11  5530.4 1696.29  5652.5 1694.45
    5683 1695.93  5712.9 1695.43  5733.9 1697.11  5770.1 1696.17    5950 1699.46
  6063.6 1704.28  6080.5 1706.28  6104.9 1704.87  6135.7  1706.5  6164.4 1707.62
#Mann= 6 ,-1 , 0
  3585.2     .05       0  4917.9     .12       0  4948.1     .05       0
  4968.7     .03       0  5031.4     .05       0  6135.7      .1       0
Bank Sta=4968.7,5031.4
XS Rating Curve= 0 ,0
Exp/Cntr=0.3,0.1

Type RM Length L Ch R = 1 ,1810    ,0,0,0
BEGIN DESCRIPTION:
Lytle Creek 5095.985
END DESCRIPTION:
XS GIS Cut Line= 4
      1592255.03       6846160.8      1592398.69      6846663.03
      1592870.08      6846730.96      1594418.65      6846967.07
#Sta/Elev= 30
  3661.5 1693.81    4033 1693.59  4331.7 1690.39  4367.7 1692.24  4444.1 1691.76
  4503.4 1689.22  4543.9 1691.84    4554 1690.54  4671.9 1693.38    4918 1693.61
  4958.5 1687.69  4968.6 1683.18  4970.1 1682.18  5031.4 1683.18  5120.3 1697.11
  5200.3 1696.15  5241.7 1699.05  5292.3 1699.91  5342.8 1705.33  5538.1 1704.26
  5585.6 1702.61  5727.2 1703.24  5757.6 1704.73  5797.3 1703.86    6003 1708.33
  6055.7 1707.18  6066.5 1707.36  6071.6 1709.41    6108 1709.78  6226.6 1709.57
#Mann= 7 ,-1 , 0
  3661.5     .05       0  4367.7    .075       0  4444.1     .05       0
  4968.6     .03       0  5031.4     .05       0  6055.7    .075       0
    6108     .05       0
Bank Sta=4968.6,5031.4
XS Rating Curve= 0 ,0
Exp/Cntr=0.3,0.1

Chan Stop Cuts=-1
Use User Specified Reach Order=0
Composite Channel Slope=5