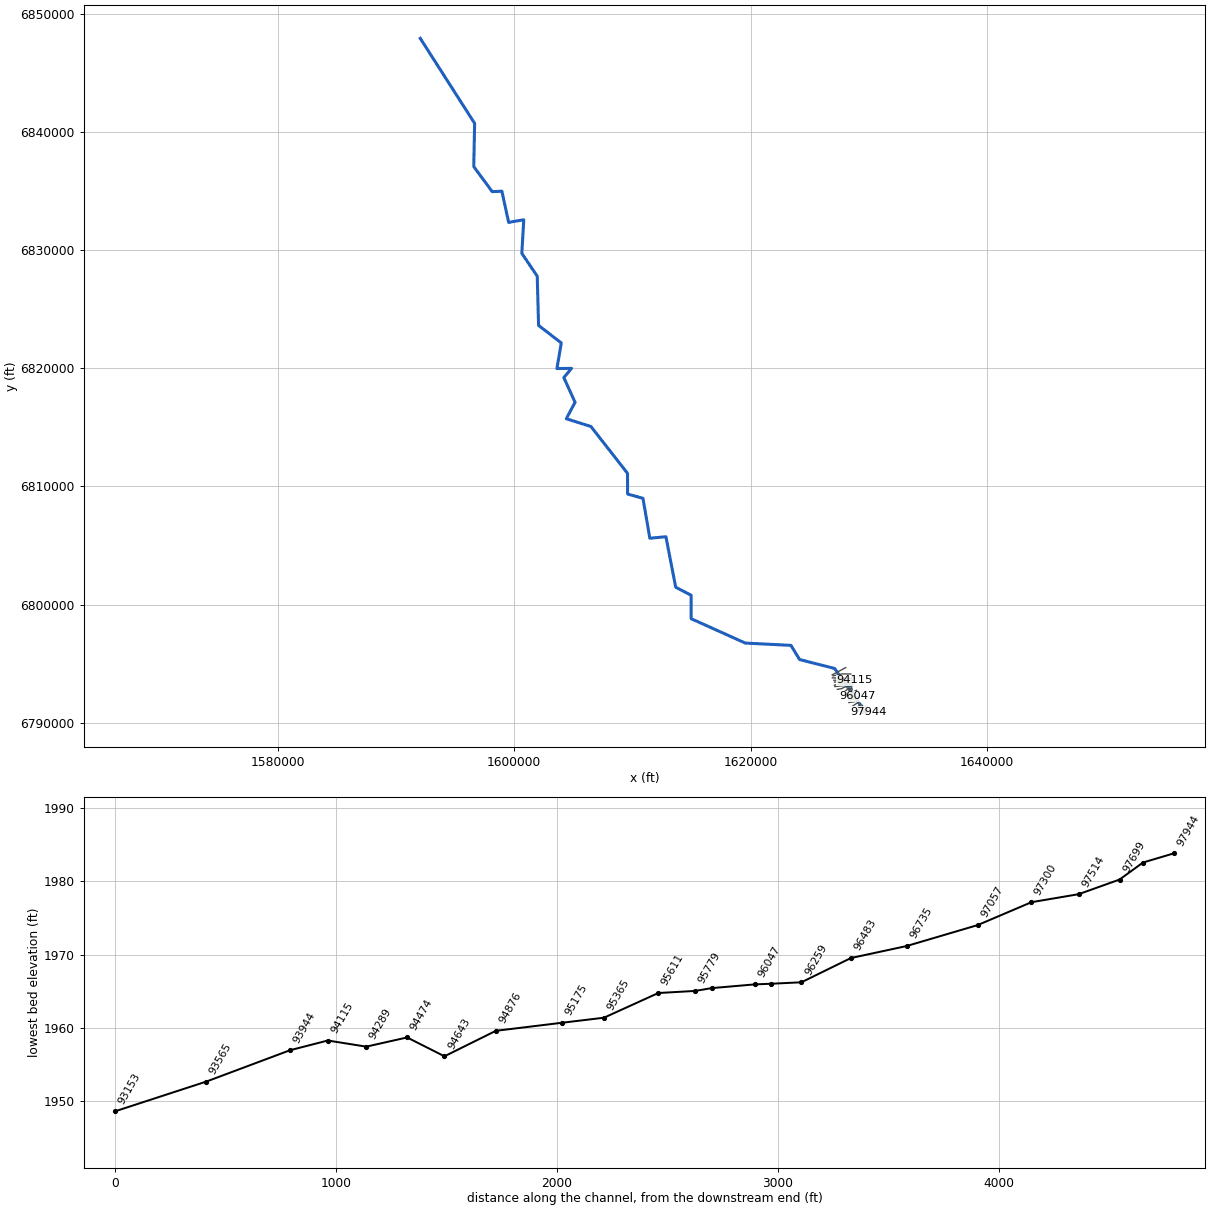
--- Lytle Creek.prj (project) ---

Proj Title=Lytle Creek Base Level Engineering
Current Plan=p02
Default Exp/Contr=0.3,0.1
English Units
Geom File=g01
Geom File=g02
Flow File=f01
Plan File=p01
Plan File=p02
Y Axis Title=Elevation
X Axis Title(PF)=Main Channel Distance
X Axis Title(XS)=Station
BEGIN DESCRIPTION:
Lytle Creek
END DESCRIPTION:
DSS Export Rating Curves= 0
DSS Export Rating Curve Sorted= 0
DSS Export Volume Flow Curves= 0
DXF OffsetX= 0
DXF OffsetY= 0
DXF ScaleX= 1
DXF ScaleY= 10

--- Lytle Creek.p02 (plan) ---

Plan Title=ohrlord
Program Version=4.10
Short Identifier=ohlord
Geom File=g02
Flow File=f01
Subcritical Flow
K Sum by GR= 0
Std Step Tol= 0.01
Critical Tol= 0.01
Num of Std Step Trials= 20
Max Error Tol= 0.3
Flow Tol Ratio= 0.001
Split Flow NTrial= 30
Split Flow Tol= 0.02
Split Flow Ratio= 0.02
Log Output Level= 0
Friction Slope Method= 1
Unsteady Friction Slope Method= 2
Unsteady Bridges Friction Slope Method= 1
Parabolic Critical Depth
Global Vel Dist= 1 , 1 , 1
Global Log Level= 0
CheckData=True
Encroach Param=-1 ,0,0, 0
BEGIN DESCRIPTION:
Multiple Run
END DESCRIPTION:
Computation Interval=1HOUR
Output Interval=1HOUR
Run HTab= 0
Run UNet= 0
Run PostProcess= 0
Run WQNet= 0
UNET Theta= 1
UNET Theta Warmup= 1
UNET ZTol= 0.02
UNET ZSATol= 0.05
UNET MxIter= 20
UNET MaxInSteps= 0
UNET DtIC= 0
UNET DtMin= 0
UNET MaxCRTS= 20
UNET WFStab= 2
UNET SFStab= 1
UNET WFX= 1
UNET SFX= 1
UNET DSS MLevel= 4
UNET DZMax Abort= 100
UNET Convert EG Bridges= 0
UNET Use Existing IB Tables=-1
UNET Froude Reduction=False
UNET Froude Limit= 1
UNET Froude Power= 10
UNET Time Slicing=0,0, 5
UNET Junction Losses=0
Instantaneous Interval=1HOUR
Write IC File= 0
Write IC File at Sim End=0
Echo Input=False
Echo Parameters=False
Echo Output=False
Write Detailed= 0
WQ AD Non Conservative
WQ ULTIMATE=-1
WQ Max Comp Step=1HOUR
WQ Output Interval=15MIN
WQ Output Selected Increments= 0
WQ Output face flow=0
WQ Output face velocity=0
WQ Output face area=0
WQ Output face dispersion=0
WQ Output cell volume=0
WQ Output cell surface area=0
WQ Output cell continuity=0
WQ Output cumulative cell continuity=0
WQ Output face conc=0
WQ Output face dconc_dx=0
WQ Output face courant=0
WQ Output face peclet=0
WQ Output face adv mass=0
WQ Output face disp mass=0
WQ Output cell mass=0
WQ Output cell source sink temp=0
WQ Output cell source sink nsm=0
WQ Output MaxMinRange=-1
WQ Daily Max Min Mean=-1
WQ Daily Range=0
WQ Daily Time=0
WQ Create Restart=0
WQ Fixed Restart=0
WQ System Summary=0
WQ Use Fixed Temperature=0
Sorting and Armoring Iterations= 10
XS Update Threshold= 0.02
Hydraulics Update Threshold= 0.02
Energy Slope Method= 1
Volume Change Method= 0
XS Weighting Method= 0
Number of US Weighted Cross Sections= 1
Number of DS Weighted Cross Sections= 1
Upstream XS Weight=0.25
Main XS Weight=0.5
Downstream XS Weight=0.25
Number of DS XS's Weighted with US Boundary= 1
Upstream Boundary Weight= 1
Weight of XSs Associated with US Boundary= 0
Number of US XS's Weighted with DS Boundary= 1
Downstream Boundary Weight= 0.5
Weight of XSs Associated with DS Boundary= 0.5
Sediment Output Level= 4
Mass or Volume Output= 0
Output Increment Type= 1
Profile and TS Output Increment= 10
XS Output Flag= 0
XS Output Increment= 10
Disregard all LS=0
Disregard all Conn=0
Disregard all Breaches=0
Disregard all Pumps=0

--- Lytle Creek.f01 (steady flow) ---

Flow Title=Multiple
Program Version=4.10
Number of Profiles= 7
Profile Names=10-year,25-year,50-year,1pct_min,100-year,1pct_plu,500-year
River Rch & RM=Lytle Creek,Reach-1         ,97944
     293     415     518     323     644    1286    1008
River Rch & RM=Lytle Creek,Reach-1         ,97699
     386     554     698     438     874    1744    1390
River Rch & RM=Lytle Creek,Reach-1         ,94876
     584     845    1071     674    1345    2684    2152
River Rch & RM=Lytle Creek,Reach-1         ,81295
     934    1387    1786    1141    2277    4544    3756
River Rch & RM=Lytle Creek,Reach-1         ,76774
     966    1430    1838    1172    2338    4665    3838
River Rch & RM=Lytle Creek,Reach-1         ,70093
    1017    1506    1936    1234    2463    4914    4041
River Rch & RM=Lytle Creek,Reach-1         ,66503
    1254    1873    2421    1551    3095    6176    5131
River Rch & RM=Lytle Creek,Reach-1         ,62780
    1360    2034    2632    1688    3368    6720    5592
River Rch & RM=Lytle Creek,Reach-1         ,59952
    1502    2253    2920    1875    3741    7465    6229
River Rch & RM=Lytle Creek,Reach-1         ,58923
    2081    3136    4080    2627    5241   10457    8769
River Rch & RM=Lytle Creek,Reach-1         ,52412
    2533    3836    5008    3234    6452   12874   10856
River Rch & RM=Lytle Creek,Reach-1         ,47505
    2610    3951    5156    3328    6639   13247   11162
River Rch & RM=Lytle Creek,Reach-1         ,43111
    2605    3932    5120    3297    6578   13125   11008
River Rch & RM=Lytle Creek,Reach-1         ,31068
    2739    4129    5373    3457    6898   13762   11520
River Rch & RM=Lytle Creek,Reach-1         ,25857
    2742    4130    5371    3453    6891   13749   11493
River Rch & RM=Lytle Creek,Reach-1         ,21642
    2976    4488    5843    3759    7501   14967   12530
River Rch & RM=Lytle Creek,Reach-1         ,16664
    2964    4460    5797    3724    7430   14825   12370
River Rch & RM=Lytle Creek,Reach-1         ,9206
    3000    4512    5864    3766    7514   14993   12505
River Rch & RM=Lytle Creek,Reach-1         ,8140
    2998    4507    5854    3758    7498   14961   12466
River Rch & RM=Lytle Creek,Reach-1         ,6872
    2942    4407    5711    3657    7297   14560   12072
Boundary for River Rch & Prof#=Lytle Creek,Reach-1         , 1
Up Type= 0
Dn Type= 3
Dn Slope=0.005
Boundary for River Rch & Prof#=Lytle Creek,Reach-1         , 2
Up Type= 0
Dn Type= 3
Dn Slope=0.005
Boundary for River Rch & Prof#=Lytle Creek,Reach-1         , 3
Up Type= 0
Dn Type= 3
Dn Slope=0.005
Boundary for River Rch & Prof#=Lytle Creek,Reach-1         , 4
Up Type= 0
Dn Type= 3
Dn Slope=0.005
Boundary for River Rch & Prof#=Lytle Creek,Reach-1         , 5
Up Type= 0
Dn Type= 3
Dn Slope=0.005
Boundary for River Rch & Prof#=Lytle Creek,Reach-1         , 6
Up Type= 0
Dn Type= 3
Dn Slope=0.005
Boundary for River Rch & Prof#=Lytle Creek,Reach-1         , 7
Up Type= 0
Dn Type= 3
Dn Slope=0.005
DSS Import GetInterval= 0
DSS Import GetPeak= 0
DSS Import FillOption= 0

--- Lytle Creek.g02 (geometry) ---

Geom Title=LytleCr
Program Version=4.10

River Reach=Lytle Creek     ,Reach-1
Reach XY= 30
        1629755.        6790838.      1627115.27      6794587.07
      1624152.71      6795343.06      1623415.83       6796543.7
        1619555.        6796738.      1614975.92       6798801.4
      1614975.47      6800784.73      1613668.54      6801467.32
      1612839.15      6805741.73      1611479.42      6805612.96
      1610897.33      6808994.53      1609596.61        6809358.
      1609591.01      6811110.25      1606495.05      6815073.23
      1604411.21      6815731.98      1605152.76      6817123.51
      1604202.73      6819217.06      1604858.01      6819996.63
      1603614.74      6819981.16      1603987.33       6822147.3
      1602064.68      6823633.74      1601952.32      6827795.59
      1600648.55      6829737.42      1600811.52      6832579.42
      1599533.31      6832355.87      1598960.46      6834996.74
      1598143.39      6834955.85      1596580.79      6837076.55
        1596655.        6840738.        1592055.        6847938.

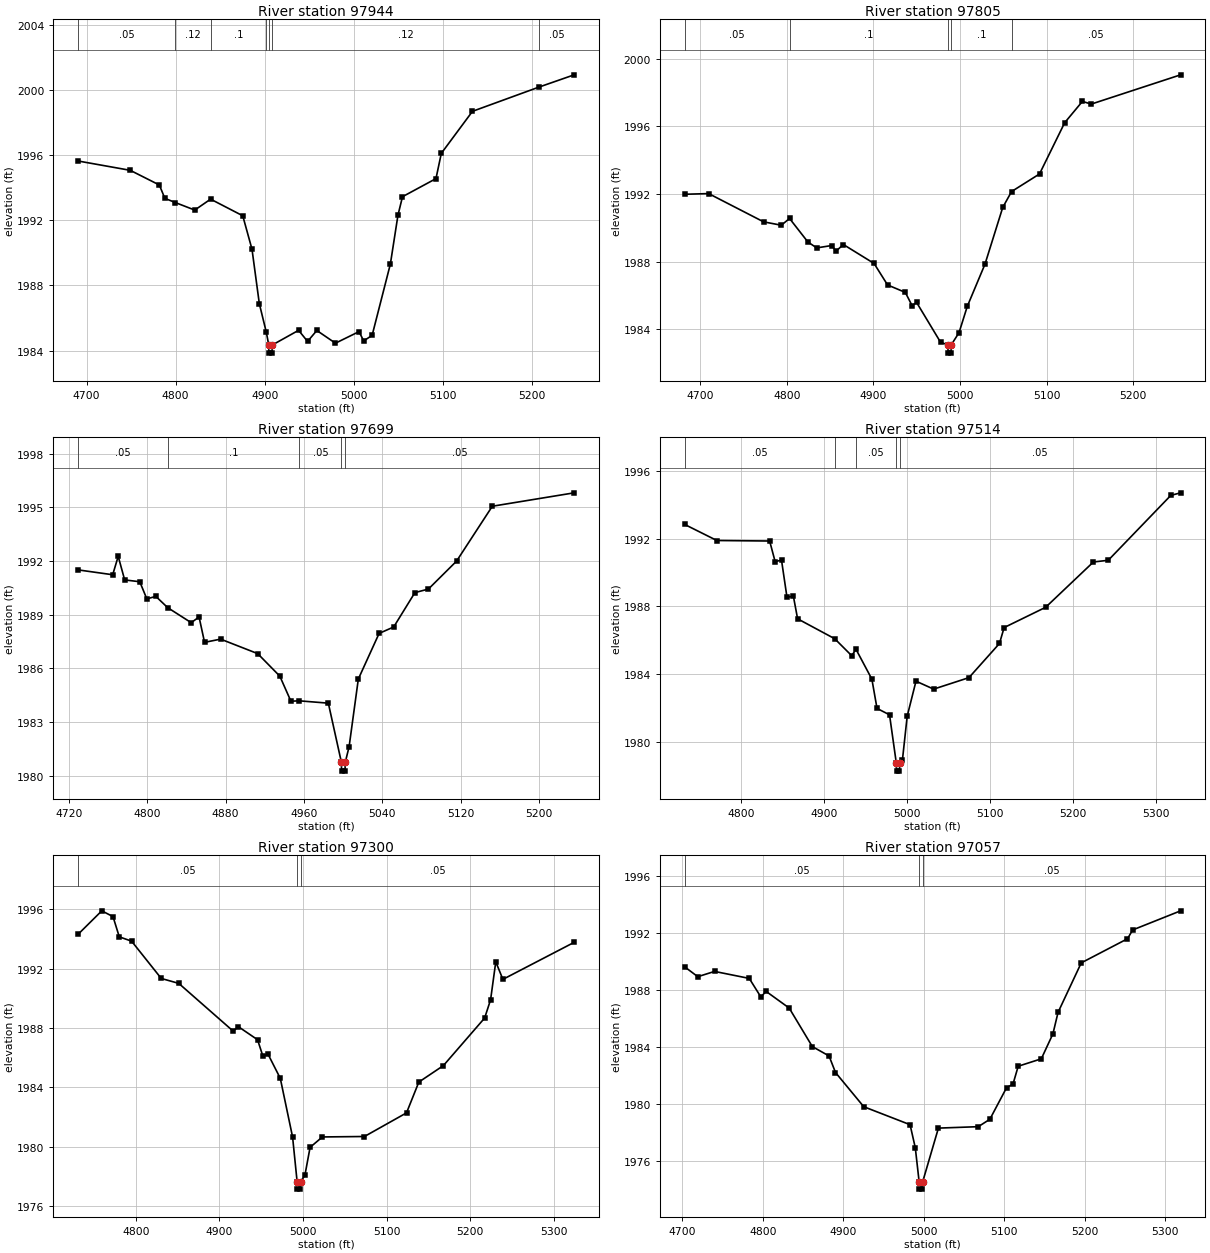
Type RM Length L Ch R = 1 ,97944   ,139,139,139
BEGIN DESCRIPTION:
Lytle Creek 98308.404
END DESCRIPTION:
XS GIS Cut Line= 3
      1629457.47      6790785.77      1629754.74      6790871.55
      1629996.49      6790925.08
#Sta/Elev= 30
  4690.6 1995.63    4749 1995.06  4781.7 1994.16  4787.9 1993.34  4799.7 1993.08
  4821.5 1992.62  4839.3 1993.29  4875.4 1992.27  4885.8 1990.21    4894 1986.88
  4901.9 1985.11  4904.6 1984.34  4904.8 1983.84  4908.3 1983.84  4908.6 1984.34
  4938.1 1985.24  4948.2 1984.56  4958.6 1985.23  4979.5 1984.45    5006 1985.16
  5011.2 1984.59  5020.7 1984.93  5041.2 1989.31  5049.7  1992.3  5054.8 1993.44
  5092.4 1994.55  5098.4  1996.1  5133.4 1998.68  5207.7 2000.16  5247.6 2000.92
#Mann= 7 ,-1 , 0
  4690.6     .05       0  4799.7     .12       0  4839.3      .1       0
  4901.9     .12       0  4904.6     .07       0  4908.6     .12       0
  5207.7     .05       0
Bank Sta=4904.6,4908.6
XS Rating Curve= 0 ,0
Exp/Cntr=0.3,0.1

Type RM Length L Ch R = 1 ,97805   ,106,106,106
BEGIN DESCRIPTION:
Lytle Creek 98184.62
END DESCRIPTION:
XS GIS Cut Line= 2
      1629385.85      6790926.46      1629945.92      6791048.44
#Sta/Elev= 30
  4681.8 1991.98  4709.5 1992.02    4773 1990.35  4793.5 1990.15    4803 1990.55
  4824.2 1989.16  4834.4 1988.81  4851.7 1988.95  4856.8 1988.62  4865.2 1989.01
  4900.7 1987.89  4916.3 1986.62  4936.8 1986.18  4944.7 1985.39  4949.8 1985.59
  4977.7 1983.22    4986 1983.09  4986.2 1982.59  4989.7 1982.59    4990 1983.09
  4998.9  1983.8  5008.4 1985.35  5028.9 1987.85  5049.4  1991.2  5059.6 1992.14
  5091.9 1993.18    5121 1996.21  5141.5 1997.47  5151.7 1997.31    5255 1999.04
#Mann= 5 ,-1 , 0
  4681.8     .05       0    4803      .1       0    4986     .07       0
    4990      .1       0  5059.6     .05       0
Bank Sta=4986,4990
XS Rating Curve= 0 ,0
Exp/Cntr=0.3,0.1

Type RM Length L Ch R = 1 ,97699   ,185,185,185
BEGIN DESCRIPTION:
Lytle Creek 98062.36
END DESCRIPTION:
XS GIS Cut Line= 3
      1629403.05      6790954.42       1629621.5      6791069.62
      1629840.98       6791207.2
#Sta/Elev= 30
  4729.7 1991.51  4764.9 1991.24  4770.5 1992.27  4777.1 1990.95  4792.5 1990.85
  4799.7 1989.89  4808.9 1990.03    4821  1989.4    4845 1988.56    4853 1988.88
  4858.6 1987.46    4875 1987.64  4912.8 1986.83  4935.4 1985.57  4946.7 1984.17
  4955.3 1984.19  4984.9 1984.06  4998.2 1980.76  4998.4 1980.26  5001.9 1980.26
  5002.2 1980.76  5006.1 1981.63  5015.5 1985.41  5036.7 1987.96  5051.6 1988.32
  5073.2 1990.24    5087 1990.44  5115.7    1992  5152.2 1995.07  5235.7 1995.82
#Mann= 5 ,-1 , 0
  4729.7     .05       0    4821      .1       0  4955.3     .05       0
  4998.2     .05       0  5002.2     .05       0
Bank Sta=4998.2,5002.2
XS Rating Curve= 0 ,0
Exp/Cntr=0.3,0.1

Type RM Length L Ch R = 1 ,97514   ,214,214,214
BEGIN DESCRIPTION:
Mapping XS cb8f6ab7
END DESCRIPTION:
XS GIS Cut Line= 4
      1629332.16      6790936.41      1629437.68       6791025.6
      1629523.83      6791262.77      1629713.95      6791346.39
#Sta/Elev= 30
  4731.7 1992.85  4770.5  1991.9  4834.2 1991.87  4840.8 1990.65  4848.5 1990.74
  4855.1 1988.54  4862.8 1988.61  4867.9 1987.27  4912.7 1986.09  4933.1 1985.09
  4938.4 1985.46  4957.5  1983.7  4963.7 1981.97  4978.8 1981.59  4986.9 1978.76
  4987.2 1978.26  4990.8 1978.26  4991.1 1978.76  4994.3  1978.9  5000.1 1981.51
  5010.7 1983.58    5032 1983.11  5074.6 1983.79  5111.4 1985.81    5117 1986.75
  5167.1 1987.95  5224.7 1990.63  5242.6 1990.73  5318.1 1994.57  5329.9 1994.72
#Mann= 5 ,-1 , 0
  4731.7     .05       0  4912.7      .1       0  4938.4     .05       0
  4986.9     .05       0  4991.1     .05       0
Bank Sta=4986.9,4991.1
XS Rating Curve= 0 ,0
Exp/Cntr=0.3,0.1

Type RM Length L Ch R = 1 ,97300   ,243,243,243
BEGIN DESCRIPTION:
Lytle Creek 97631.83
END DESCRIPTION:
XS GIS Cut Line= 2
      1629120.45      6790984.32      1629468.03      6791464.65
#Sta/Elev= 30
  4731.2 1994.31  4759.4 1995.88  4772.8 1995.49  4780.3 1994.13    4795 1993.84
  4830.5 1991.33  4851.4    1991  4916.4 1987.79  4922.6 1988.09  4945.6 1987.21
    4952  1986.1  4958.1 1986.24  4972.8 1984.61  4987.5 1980.66  4992.9 1977.66
  4993.2 1977.16  4996.8 1977.16  4997.1 1977.66  5002.2 1978.09  5008.4 1979.97
  5023.1 1980.67  5073.4  1980.7  5123.7 1982.29  5138.4 1984.36  5167.8 1985.47
  5217.1 1988.67  5224.2  1989.9  5230.4 1992.45  5238.9 1991.27  5324.1 1993.76
#Mann= 3 ,-1 , 0
  4731.2     .05       0  4992.9     .05       0  4997.1     .05       0
Bank Sta=4992.9,4997.1
XS Rating Curve= 0 ,0
Exp/Cntr=0.3,0.1

Type RM Length L Ch R = 1 ,97057   ,322,322,322
BEGIN DESCRIPTION:
Lytle Creek 97411.86
END DESCRIPTION:
XS GIS Cut Line= 2
      1628909.55      6791130.53      1629298.36      6791608.19
#Sta/Elev= 30
    4703 1989.62  4719.3 1988.93  4740.1  1989.3  4783.2 1988.81  4797.6 1987.51
  4804.1  1987.9  4832.8 1986.73  4861.5 1984.03  4882.3 1983.37  4890.3 1982.21
  4925.4 1979.81  4982.9 1978.55  4989.4 1976.93  4994.2 1974.53  4994.5 1974.03
  4998.1 1974.03  4998.5 1974.53  5018.1 1978.31  5067.6 1978.41    5082 1978.93
  5102.8 1981.15  5110.7 1981.39  5117.2 1982.65  5145.9 1983.17  5160.3 1984.92
  5166.7 1986.43  5195.5  1989.9  5252.9 1991.59  5259.4 1992.21  5318.9 1993.55
#Mann= 3 ,-1 , 0
    4703     .05       0  4994.2     .05       0  4998.5     .05       0
Bank Sta=4994.2,4998.5
XS Rating Curve= 0 ,0
Exp/Cntr=0.3,0.1

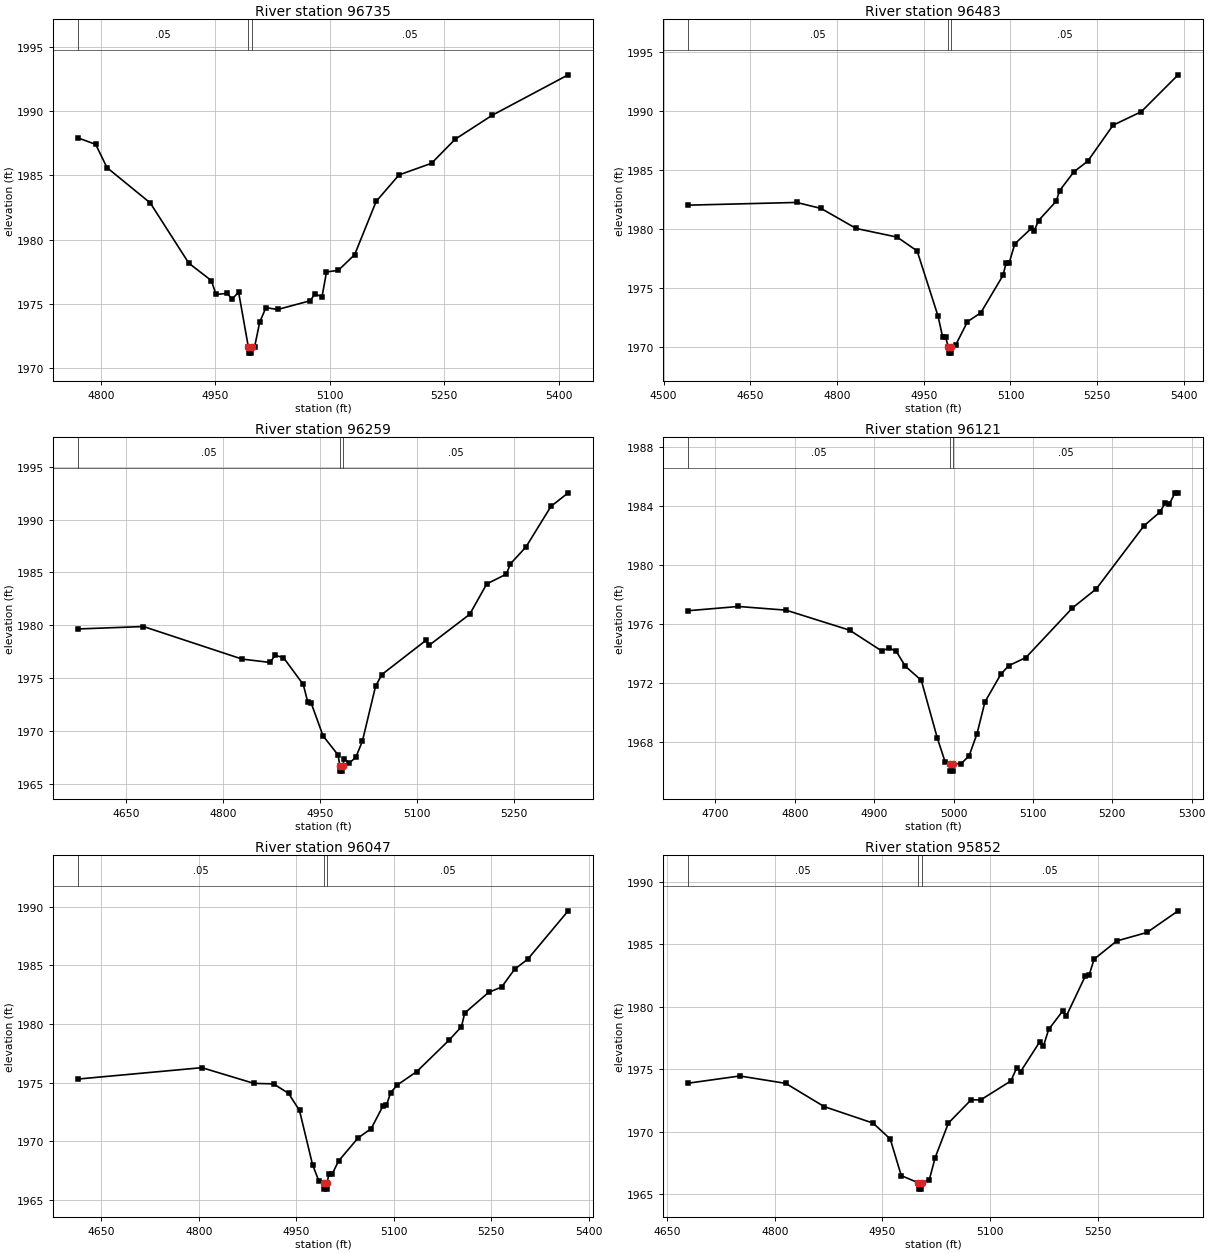
Type RM Length L Ch R = 1 ,96735   ,252,252,252
BEGIN DESCRIPTION:
Lytle Creek 97066.38
END DESCRIPTION:
XS GIS Cut Line= 3
      1628640.03      6791400.24      1628845.72      6791544.75
      1629180.15      6791747.75
#Sta/Elev= 30
  4769.7 1987.93    4793 1987.42  4807.8 1985.61  4864.5 1982.86    4915 1978.17
  4944.6 1976.81  4950.7 1975.73  4965.5 1975.82  4971.6 1975.36  4980.3 1975.91
    4993 1971.66  4993.3 1971.16  4996.9 1971.16  4997.3 1971.66  5001.3 1971.66
    5008 1973.58  5016.1  1974.7  5031.5 1974.56  5074.2 1975.24    5080 1975.75
  5089.7 1975.57  5095.5 1977.48    5111 1977.61  5132.4 1978.83  5160.6 1982.98
  5190.5 1985.04  5233.2 1985.95  5264.1 1987.82  5312.7 1989.69  5412.3 1992.84
#Mann= 3 ,-1 , 0
  4769.7     .05       0    4993     .05       0  4997.3     .05       0
Bank Sta=4993,4997.3
XS Rating Curve= 0 ,0
Exp/Cntr=0.3,0.1

Type RM Length L Ch R = 1 ,96483   ,224,224,224
BEGIN DESCRIPTION:
Lytle Creek 96796.09
END DESCRIPTION:
XS GIS Cut Line= 3
      1628317.03       6791704.9      1628755.88      6791770.01
      1629150.85      6791857.06
#Sta/Elev= 30
    4542 1982.03  4730.2 1982.26  4772.5 1981.75  4833.1 1980.06  4903.9 1979.33
  4938.6 1978.16  4974.7 1972.66  4982.7 1970.89  4987.8 1970.89  4992.5 1970.02
  4992.9 1969.52  4996.5 1969.52  4996.9 1970.02  5005.2  1970.2  5025.7 1972.18
  5048.7 1972.93  5087.2  1976.1  5092.4 1977.12  5097.5  1977.1  5107.6 1978.76
  5136.1 1980.07  5141.2 1979.86  5148.6 1980.73  5179.3 1982.37  5184.9 1983.25
    5210 1984.86  5233.7 1985.75  5277.5 1988.79  5326.3 1989.93  5390.1 1993.05
#Mann= 3 ,-1 , 0
    4542     .05       0  4992.5     .05       0  4996.9     .05       0
Bank Sta=4992.5,4996.9
XS Rating Curve= 0 ,0
Exp/Cntr=0.3,0.1

Type RM Length L Ch R = 1 ,96259   ,138,138,138
BEGIN DESCRIPTION:
Lytle Creek 96542.94
END DESCRIPTION:
XS GIS Cut Line= 3
      1628363.33      6791912.45      1628757.88      6791991.89
      1629109.48      6792046.58
#Sta/Elev= 30
  4575.7 1979.65  4677.1 1979.88  4829.6  1976.8  4873.2 1976.48  4880.4 1977.16
  4893.6 1976.94  4924.2  1974.4  4931.2 1972.75  4936.3 1972.67  4954.8 1969.54
  4978.2 1967.72  4980.7  1966.7  4981.1  1966.2  4984.7  1966.2  4985.1  1966.7
  4987.9 1967.36  4995.5 1966.96  5005.6 1967.52  5015.7 1969.04    5036 1974.22
  5045.8 1975.34  5113.7 1978.56  5118.8  1978.1  5181.7 1981.04    5208 1983.91
  5238.4 1984.84  5244.5  1985.8  5268.7 1987.41  5307.4 1991.25    5334 1992.53
#Mann= 3 ,-1 , 0
  4575.7     .05       0  4980.7     .05       0  4985.1     .05       0
Bank Sta=4980.7,4985.1
XS Rating Curve= 0 ,0
Exp/Cntr=0.3,0.1

Type RM Length L Ch R = 1 ,96121   ,74,74,74
BEGIN DESCRIPTION:
Lytle Creek 96407
END DESCRIPTION:
XS GIS Cut Line= 3
      1628391.69      6792093.01      1628725.93      6792118.19
      1629008.01      6792133.81
#Sta/Elev= 30
  4665.3 1976.88  4728.8 1977.17    4789 1976.92  4869.2 1975.56  4909.3 1974.16
  4919.3 1974.35  4927.9 1974.12  4939.4 1973.11  4959.4 1972.16  4979.5 1968.26
  4989.5 1966.61  4995.3  1966.5  4995.7    1966  4999.3    1966  4999.7  1966.5
  5009.6 1966.51  5019.6 1967.03  5029.6 1968.54  5039.6  1970.7  5059.7 1972.58
  5069.7 1973.16  5091.1  1973.7  5149.8 1977.07  5179.8 1978.36  5239.9 1982.64
    5260 1983.57  5266.7 1984.19  5271.7 1984.09    5279 1984.88    5283 1984.88
#Mann= 3 ,-1 , 0
  4665.3     .05       0  4995.3     .05       0  4999.7     .05       0
Bank Sta=4995.3,4999.7
XS Rating Curve= 0 ,0
Exp/Cntr=0.3,0.1

Type RM Length L Ch R = 1 ,96047   ,195,195,195
BEGIN DESCRIPTION:
Lytle Creek 96332.97
END DESCRIPTION:
XS GIS Cut Line= 3
      1628314.45      6792168.53      1628700.76       6792185.9
       1629067.1      6792216.28
#Sta/Elev= 30
  4614.2  1975.3  4804.9 1976.27    4885 1974.93  4915.1 1974.89  4938.2 1974.08
  4955.1 1972.62  4975.1 1968.01  4985.1 1966.57  4992.9 1966.41  4993.3 1965.91
  4996.9 1965.91  4997.3 1966.41  5000.5 1967.21  5005.5 1967.21  5015.2 1968.31
  5045.3 1970.28  5065.4 1971.07  5083.6 1973.01  5088.7 1973.05  5095.5 1974.15
  5105.5 1974.79  5135.6 1975.94  5185.8 1978.65  5204.3 1979.77  5209.3 1980.93
    5246 1982.69  5266.1 1983.15  5286.1 1984.67  5306.2 1985.52  5368.5 1989.65
#Mann= 3 ,-1 , 0
  4614.2     .05       0  4992.9     .05       0  4997.3     .05       0
Bank Sta=4992.9,4997.3
XS Rating Curve= 0 ,0
Exp/Cntr=0.3,0.1

Type RM Length L Ch R = 1 ,95852   ,73,73,73
BEGIN DESCRIPTION:
Lytle Creek 96131.29
END DESCRIPTION:
XS GIS Cut Line= 3
      1628334.04      6792282.35      1628653.45      6792372.61
       1628986.1      6792482.34
#Sta/Elev= 30
  4679.2 1973.87  4751.4 1974.45  4815.3 1973.86  4868.9    1972  4936.9 1970.68
  4960.8 1969.41  4976.1 1966.48  5000.1  1965.9  5000.5  1965.4  5004.1  1965.4
  5004.5  1965.9  5015.2 1966.16  5023.3 1967.92  5041.7 1970.68  5073.4 1972.55
  5086.5 1972.53  5128.6 1974.05  5136.9 1975.11  5142.2  1974.8  5168.7 1977.17
    5174 1976.85  5181.2 1978.17  5200.5 1979.63  5205.7 1979.23  5232.2 1982.44
  5237.5 1982.51  5244.4 1983.79    5276 1985.25  5318.1 1985.93  5361.4 1987.66
#Mann= 3 ,-1 , 0
  4679.2     .05       0  5000.1     .05       0  5004.5     .05       0
Bank Sta=5000.1,5004.5
XS Rating Curve= 0 ,0
Exp/Cntr=0.3,0.1

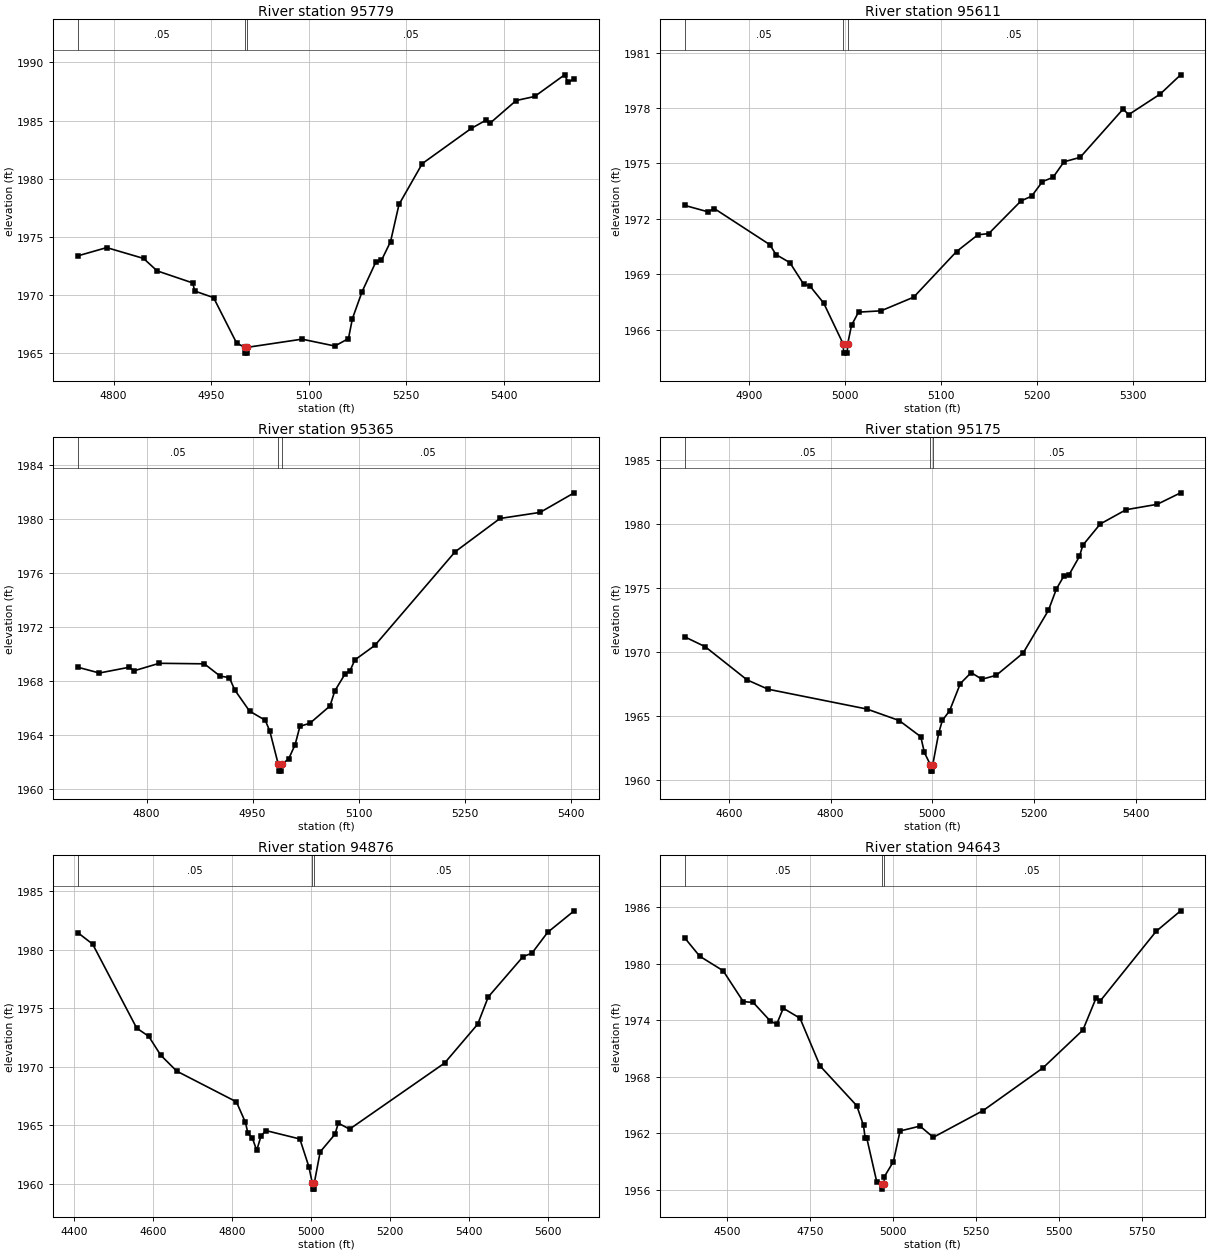
Type RM Length L Ch R = 1 ,95779   ,168,168,168
BEGIN DESCRIPTION:
Mapping XS f53f254b
END DESCRIPTION:
XS GIS Cut Line= 5
      1628358.85      6792320.09      1628525.52      6792370.44
      1628650.52      6792465.92      1628782.46      6792655.16
      1628964.72      6792738.48
#Sta/Elev= 30
  4745.6 1973.39  4789.4 1974.09    4846 1973.16  4866.9 1972.09  4921.8 1971.05
  4924.6 1970.36  4953.7 1969.79    4989  1965.9  5001.4 1965.52  5001.8 1965.02
  5005.4 1965.02  5005.8 1965.52  5089.6 1966.22  5140.2 1965.63  5161.1 1966.27
  5167.2 1967.99  5182.1 1970.31    5203 1972.83  5211.8 1972.99  5225.8  1974.6
  5238.8  1977.8  5274.6 1981.31  5349.8 1984.33  5372.8 1985.05  5378.3 1984.76
  5418.9 1986.73  5447.4 1987.08  5493.4 1988.94  5498.9 1988.29  5508.1  1988.6
#Mann= 3 ,-1 , 0
  4745.6     .05       0  5001.4     .05       0  5005.8     .05       0
Bank Sta=5001.4,5005.8
XS Rating Curve= 0 ,0
Exp/Cntr=0.3,0.1

Type RM Length L Ch R = 1 ,95611   ,246,246,246
BEGIN DESCRIPTION:
Lytle Creek 95878
END DESCRIPTION:
XS GIS Cut Line= 3
      1628343.74      6792375.31      1628463.13      6792528.34
      1628606.36      6792816.97
#Sta/Elev= 30
    4833 1972.73  4857.4 1972.38  4863.8 1972.56  4921.7  1970.6    4928 1970.07
  4942.5 1969.63  4956.9 1968.46  4963.3 1968.37  4977.7 1967.44    4998 1965.23
  4998.5 1964.73  5002.2 1964.73  5002.7 1965.23  5006.7 1966.24    5014 1966.95
  5037.4 1967.02  5071.4 1967.76    5116 1970.23  5138.3 1971.14  5149.5  1971.2
  5183.1 1972.97  5194.2 1973.23  5205.5 1974.02  5216.5 1974.25  5227.9 1975.09
  5244.7 1975.33  5289.5 1977.95  5295.1 1977.64  5328.1 1978.76  5349.3  1979.8
#Mann= 3 ,-1 , 0
    4833     .05       0    4998     .05       0  5002.7     .05       0
Bank Sta=4998,5002.7
XS Rating Curve= 0 ,0
Exp/Cntr=0.3,0.1

Type RM Length L Ch R = 1 ,95365   ,190,190,190
BEGIN DESCRIPTION:
Lytle Creek 95633.92
END DESCRIPTION:
XS GIS Cut Line= 3
      1628068.69      6792412.78      1628257.47      6792642.78
      1628554.79      6792916.23
#Sta/Elev= 30
  4703.3 1969.04  4733.2 1968.62  4774.8 1969.04  4782.7 1968.79  4817.9 1969.34
  4881.7  1969.3    4904 1968.39    4917 1968.28  4924.8 1967.36  4945.6  1965.8
  4967.8 1965.12  4974.3 1964.32  4986.3 1961.85  4986.8 1961.35  4990.5 1961.35
    4991 1961.85  5000.9 1962.25  5010.1 1963.31  5016.9 1964.67  5031.1  1964.9
  5059.5 1966.18  5066.2 1967.29  5080.4 1968.52  5087.8 1968.79  5094.6 1969.59
    5123 1970.67  5236.4  1977.6  5299.9 1980.07  5356.6 1980.52  5404.8 1981.97
#Mann= 3 ,-1 , 0
  4703.3     .05       0  4986.3     .05       0    4991     .05       0
Bank Sta=4986.3,4991
XS Rating Curve= 0 ,0
Exp/Cntr=0.3,0.1

Type RM Length L Ch R = 1 ,95175   ,299,299,299
BEGIN DESCRIPTION:
Mapping XS 38325b7c
END DESCRIPTION:
XS GIS Cut Line= 4
      1627923.27      6792338.96      1628003.08      6792656.72
      1628242.29      6792889.69      1628550.24      6792949.24
#Sta/Elev= 30
    4513 1971.17  4553.3  1970.4  4635.7  1967.8    4677 1967.07  4871.2 1965.52
  4934.8 1964.62  4977.3 1963.35  4984.3 1962.12  4996.1 1961.16  4996.6 1960.66
  5000.3 1960.66  5000.8 1961.16  5012.5 1963.64  5019.7 1964.63  5033.9 1965.38
    5055 1967.51  5076.3 1968.37  5097.4 1967.85  5125.7 1968.16  5178.5  1969.9
  5228.2 1973.24  5244.1 1974.93  5258.8 1975.94    5269 1976.04  5289.3 1977.47
  5295.9 1978.34  5330.1    1980    5381 1981.12  5442.1 1981.54  5488.2 1982.44
#Mann= 3 ,-1 , 0
    4513     .05       0  4996.1     .03       0  5000.8     .05       0
Bank Sta=4996.1,5000.8
XS Rating Curve= 0 ,0
Exp/Cntr=0.3,0.1

Type RM Length L Ch R = 1 ,94876   ,233,233,233
BEGIN DESCRIPTION:
Lytle Creek 95413.9
END DESCRIPTION:
XS GIS Cut Line= 4
      1627348.95      6792821.16      1627675.96      6792874.85
      1628032.09      6793039.06      1628561.67      6793083.56
#Sta/Elev= 30
  4410.7 1981.42  4447.2 1980.47  4558.7  1973.3  4589.1  1972.6  4619.5 1970.99
    4660 1969.63    4811 1967.01  4833.9 1965.25  4840.1 1964.33  4851.1 1963.94
  4862.4 1962.87  4873.2 1964.08  4885.3 1964.56  4971.6 1963.84  4994.3 1961.48
  5003.2 1960.06  5003.7 1959.56  5007.4 1959.56    5008 1960.06    5023 1962.74
  5060.4 1964.24  5068.9 1965.19  5097.4 1964.68  5337.9 1970.32  5421.7 1973.64
  5448.3 1975.96  5536.6 1979.41  5558.7 1979.69  5598.8 1981.48  5665.7 1983.31
#Mann= 3 ,-1 , 0
  4410.7     .05       0  5003.2     .05       0    5008     .05       0
Bank Sta=5003.2,5008
XS Rating Curve= 0 ,0
Exp/Cntr=0.3,0.1

Type RM Length L Ch R = 1 ,94643   ,169,169,169
BEGIN DESCRIPTION:
Mapping XS 04d59858
END DESCRIPTION:
XS GIS Cut Line= 4
      1627129.91      6793054.75      1627670.27      6793119.86
      1628245.35      6793152.41      1628618.64      6793182.79
#Sta/Elev= 30
    4372 1982.74  4417.4 1980.79  4487.9 1979.25  4548.4 1975.98  4578.6 1975.88
  4628.9 1973.96  4649.1 1973.56  4669.2 1975.27  4719.6 1974.21  4780.2 1969.14
  4890.8 1964.92    4911 1962.83  4916.1 1961.45  4921.1 1961.45  4951.1 1956.82
  4965.4 1956.57  4966.5 1956.07  4972.5 1956.57    4974  1957.4  5001.1 1958.99
  5021.2 1962.24  5081.3 1962.76  5121.3 1961.57  5271.6 1964.41  5451.9 1968.94
  5572.2 1972.95  5612.3 1976.38  5625.1 1976.07  5792.9 1983.43  5866.8 1985.61
#Mann= 3 ,-1 , 0
    4372     .05       0  4965.4     .05       0  4972.5     .05       0
Bank Sta=4965.4,4972.5
XS Rating Curve= 0 ,0
Exp/Cntr=0.3,0.1

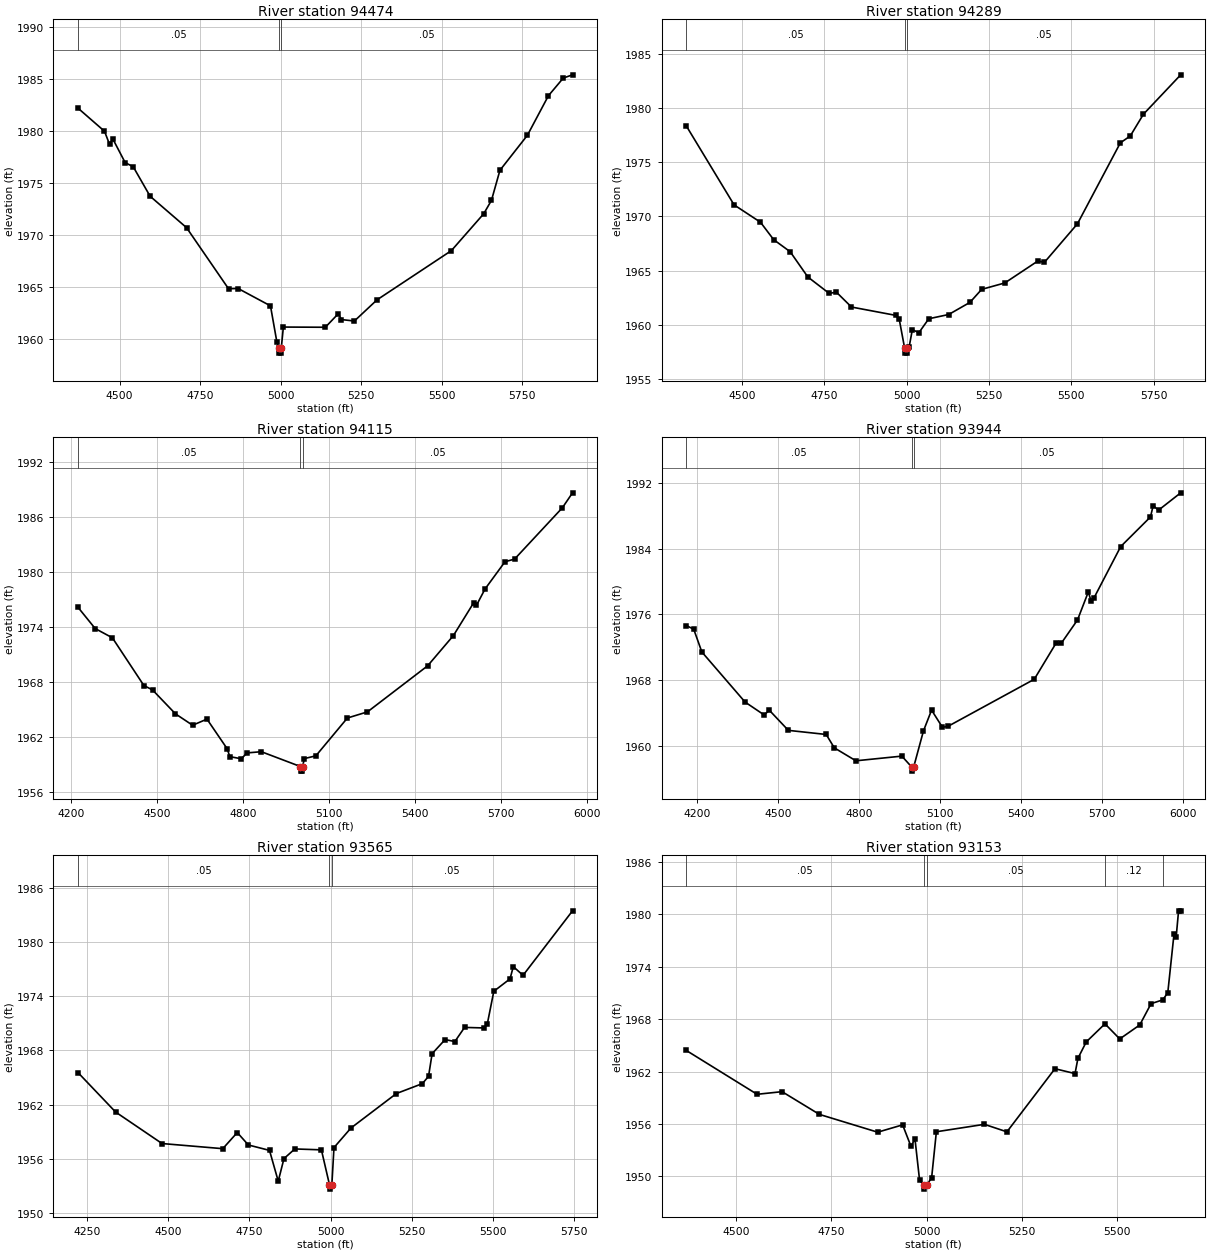
Type RM Length L Ch R = 1 ,94474   ,185,185,185
BEGIN DESCRIPTION:
Mapping XS 56ed5623
END DESCRIPTION:
XS GIS Cut Line= 4
      1627092.17      6793168.04      1627362.98      6793254.84
      1627928.95       6793291.3      1628609.52      6793230.53
#Sta/Elev= 30
  4371.1 1982.22  4452.9 1980.01  4468.6 1978.75  4479.1 1979.25  4517.1 1976.99
  4542.1 1976.59  4594.6 1973.75  4707.6 1970.73  4837.9 1964.85  4867.9 1964.87
  4968.2  1963.2  4988.2  1959.7  4994.7 1959.15  4995.8 1958.65  5000.7 1958.65
  5001.8 1959.15  5008.2 1961.16  5138.5 1961.14  5178.6 1962.44  5188.6 1961.88
  5228.7 1961.74    5299 1963.78  5529.9 1968.52  5630.3 1972.07  5654.3 1973.36
  5680.5 1976.25  5765.8 1979.62  5831.1 1983.43  5877.2 1985.13  5905.9 1985.44
#Mann= 3 ,-1 , 0
  4371.1     .05       0  4994.7     .05       0  5001.8     .05       0
Bank Sta=4994.7,5001.8
XS Rating Curve= 0 ,0
Exp/Cntr=0.3,0.1

Type RM Length L Ch R = 1 ,94289   ,174,174,174
BEGIN DESCRIPTION:
Lytle Creek 94789.65
END DESCRIPTION:
XS GIS Cut Line= 3
      1627100.25      6793434.09      1627536.24      6793468.46
      1628597.77      6793379.41
#Sta/Elev= 30
    4330 1978.34  4475.2 1971.06  4555.4 1969.46  4595.6 1967.85  4645.7 1966.74
  4699.4 1964.41  4764.2  1962.9  4786.2 1963.01    4832 1961.64  4966.8 1960.87
  4976.8 1960.57  4993.3 1957.89  4994.5 1957.39  4999.4 1957.39  5000.5 1957.89
  5006.9 1957.91    5017 1959.55    5037 1959.28    5067 1960.56  5127.4 1960.95
  5192.1 1962.07  5227.7 1963.27    5298 1963.86  5398.3 1965.88  5418.4 1965.76
  5518.7 1969.31  5649.2 1976.78  5679.3 1977.41  5719.4 1979.42  5832.6 1983.05
#Mann= 3 ,-1 , 0
    4330     .05       0  4993.3     .05       0  5000.5     .05       0
Bank Sta=4993.3,5000.5
XS Rating Curve= 0 ,0
Exp/Cntr=0.3,0.1

Type RM Length L Ch R = 1 ,94115   ,171,171,171
BEGIN DESCRIPTION:
Lytle Creek 94361.14
END DESCRIPTION:
XS GIS Cut Line= 3
      1627055.58      6793588.28      1627806.43      6793612.15
       1628780.4      6793575.27
#Sta/Elev= 30
    4224  1976.1  4283.5  1973.8  4343.5 1972.79  4453.5 1967.58  4483.6  1967.1
  4563.6 1964.49  4623.6 1963.24  4673.7 1963.91  4743.7  1960.7  4753.7 1959.81
  4793.7 1959.58  4813.7 1960.22  4863.7 1960.35  5000.2 1958.73  5001.3 1958.23
  5006.3 1958.23  5007.5 1958.73  5013.8  1959.6  5053.9  1959.9  5163.9 1964.03
    5234  1964.7  5444.1 1969.73  5534.2 1973.04  5604.3 1976.59  5614.3 1976.32
  5644.3 1978.11  5714.3  1981.1  5747.5 1981.38  5914.5 1986.99  5949.9 1988.62
#Mann= 3 ,-1 , 0
    4224     .05       0  5000.2     .05       0  5007.5     .05       0
Bank Sta=5000.2,5007.5
XS Rating Curve= 0 ,0
Exp/Cntr=0.3,0.1

Type RM Length L Ch R = 1 ,93944   ,379,379,379
BEGIN DESCRIPTION:
Lytle Creek 94191.93
END DESCRIPTION:
XS GIS Cut Line= 3
      1626927.48      6793792.27      1627754.35      6793766.23
      1628756.92      6793748.87
#Sta/Elev= 30
  4161.3 1974.65  4188.8  1974.2  4218.8 1971.43  4378.9 1965.32    4449 1963.76
    4469 1964.31    4539 1961.87  4679.1 1961.37  4709.1 1959.74  4789.1 1958.16
  4959.2 1958.73  4995.6  1957.4  4996.7  1956.9  5002.9  1957.4  5039.2 1961.81
  5069.2 1964.34  5109.2 1962.25  5129.3 1962.35  5449.3  1968.1  5529.3 1972.47
  5549.3 1972.49  5609.3 1975.33  5649.3 1978.74  5659.3 1977.67  5669.3 1977.95
  5769.3 1984.28  5879.4 1987.89  5889.4 1989.26  5909.4 1988.72  5991.3 1990.83
#Mann= 3 ,-1 , 0
  4161.3     .05       0  4995.6     .05       0  5002.9     .05       0
Bank Sta=4995.6,5002.9
XS Rating Curve= 0 ,0
Exp/Cntr=0.3,0.1

Type RM Length L Ch R = 1 ,93565   ,412,412,412
BEGIN DESCRIPTION:
Lytle Creek 93802.39
END DESCRIPTION:
XS GIS Cut Line= 3
      1626982.18      6793961.02       1627755.6      6794125.08
      1628487.35      6794119.87
#Sta/Elev= 30
  4222.4 1965.53  4337.7 1961.17  4480.8 1957.67  4667.8  1957.1  4712.4 1958.89
  4746.6 1957.51  4811.7 1956.91  4838.6 1953.49  4856.2    1956  4889.7 1957.07
  4971.5 1956.97  4996.3 1953.11  4997.5 1952.61  5003.7 1953.11  5010.2 1957.22
  5062.4 1959.39  5202.4 1963.22  5282.4 1964.32  5301.4 1965.13  5312.4 1967.64
  5352.4 1969.21  5382.4 1968.99  5412.4 1970.56  5472.4  1970.5  5482.4 1970.95
  5502.4 1974.57  5552.4 1975.95  5562.4 1977.31  5592.4 1976.34  5744.8  1983.5
#Mann= 3 ,-1 , 0
  4222.4     .05       0  4996.3     .05       0  5003.7     .05       0
Bank Sta=4996.3,5003.7
XS Rating Curve= 0 ,0
Exp/Cntr=0.3,0.1

Type RM Length L Ch R = 1 ,93153   ,310,310,310
BEGIN DESCRIPTION:
Lytle Creek 93421.23
END DESCRIPTION:
XS GIS Cut Line= 3
      1626906.69      6794044.37      1627487.38      6794359.46
      1628049.86      6794658.93
#Sta/Elev= 30
  4369.2 1964.43    4555 1959.41  4620.6 1959.71  4718.5 1957.11  4871.6 1955.07
  4937.1 1955.91    4959 1953.45  4969.5  1954.3  4981.7 1949.54  4993.3 1949.05
  4994.5 1948.55  5000.7 1949.05  5013.2 1949.84  5025.7 1955.12  5151.8 1955.97
  5210.9 1955.11    5337 1962.34  5389.7 1961.78  5397.3 1963.53  5419.2 1965.41
  5468.3 1967.48  5507.1 1965.75  5559.6 1967.35  5589.3 1969.79  5619.9 1970.22
  5633.2 1971.04  5649.5 1977.75  5655.2 1977.41  5661.5 1980.42  5667.1 1980.42
#Mann= 5 ,-1 , 0
  4369.2     .05       0  4993.3     .05       0  5000.7     .05       0
  5468.3     .12       0  5619.9     .05       0
Bank Sta=4993.3,5000.7
XS Rating Curve= 0 ,0
Exp/Cntr=0.3,0.1