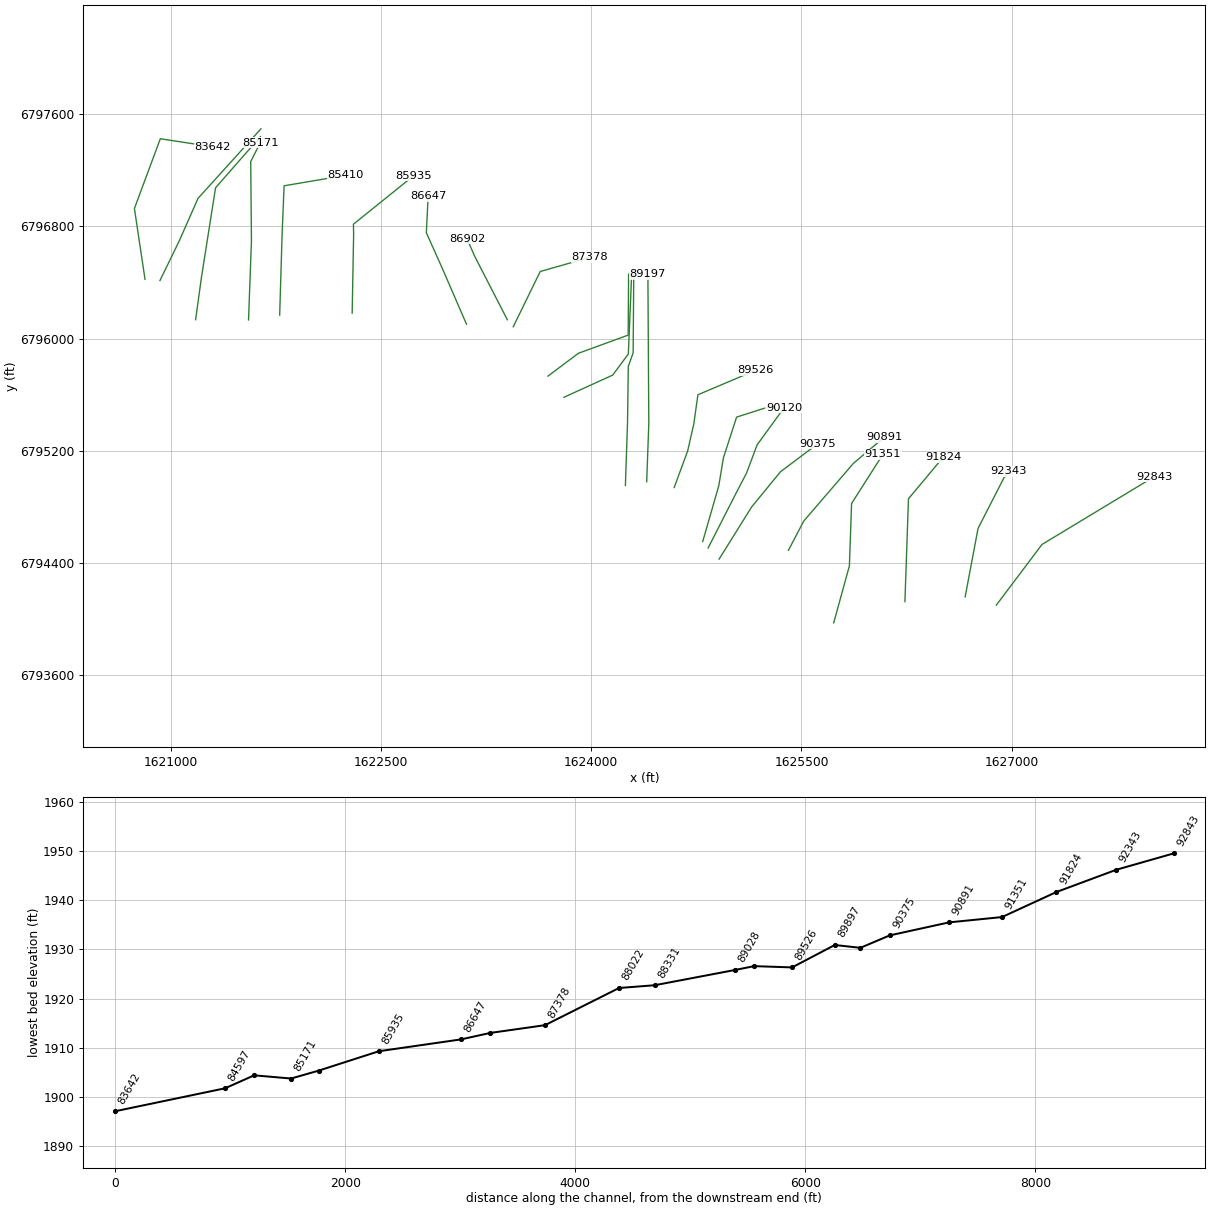
HEC-RAS study Lytle Creek.prj: Lytle Creek Base Level Engineering

--- Lytle Creek.g02 (geometry) --- (continued)

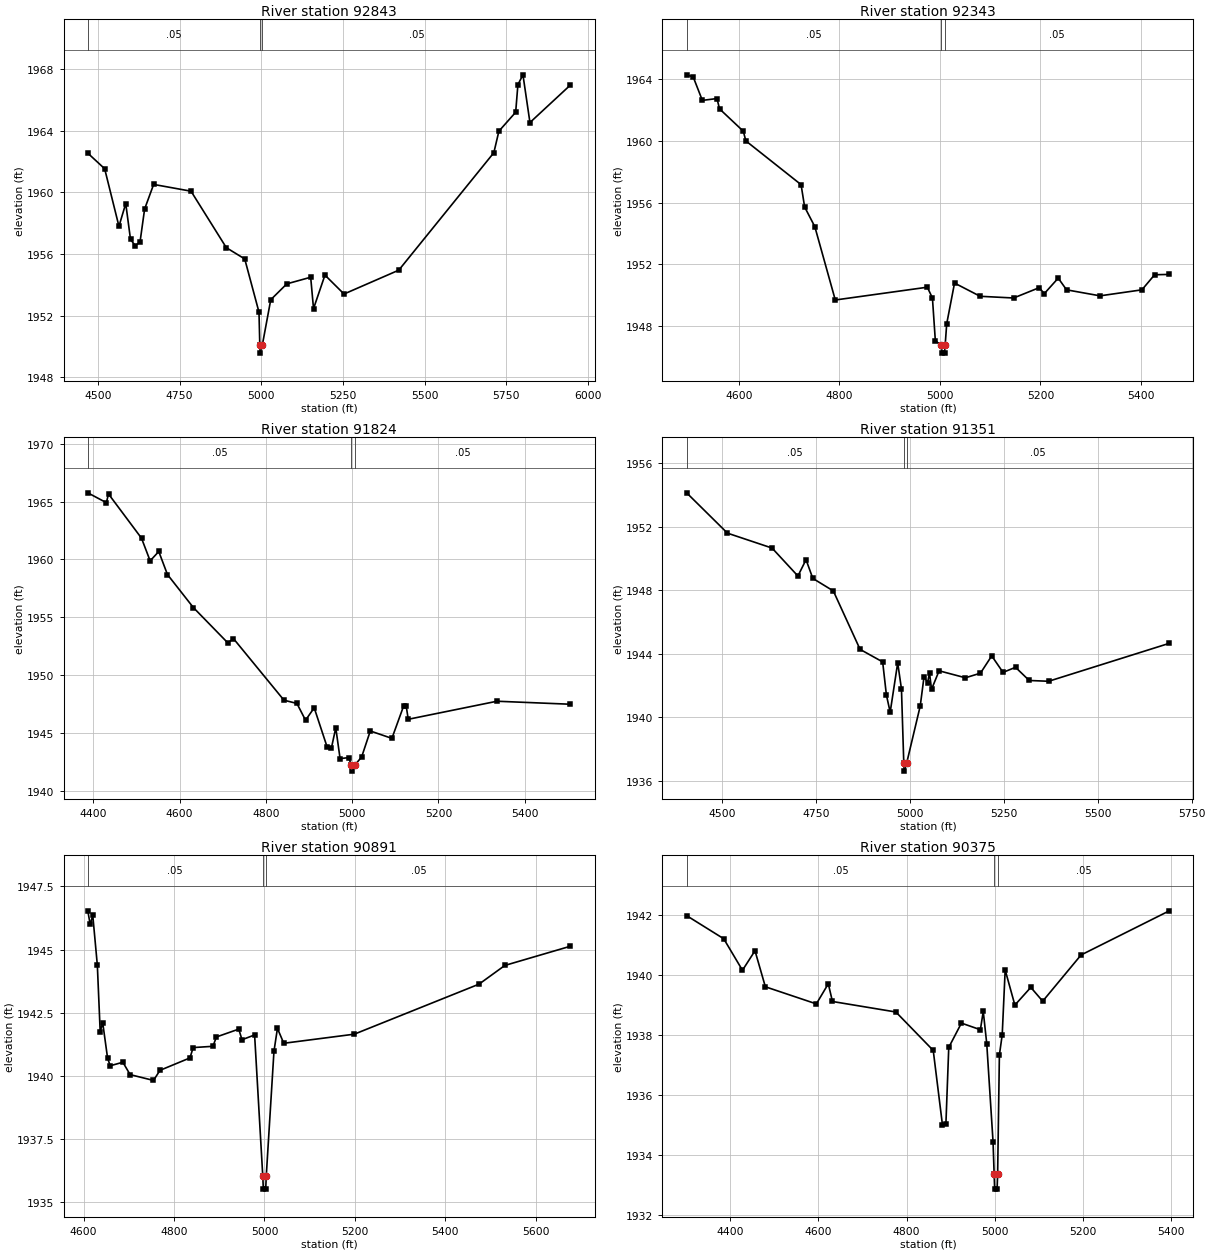
Type RM Length L Ch R = 1 ,92843   ,500,500,500
BEGIN DESCRIPTION:
Lytle Creek 93090.31
END DESCRIPTION:
XS GIS Cut Line= 3
      1626890.99        6794099.      1627216.54      6794531.33
      1628018.64      6795015.71
#Sta/Elev= 30
  4468.7 1962.55  4520.3 1961.54  4564.1  1957.8  4584.9 1959.28  4599.5 1956.95
    4614 1956.54  4628.6 1956.77  4642.7 1958.92  4670.3 1960.52  4784.8 1960.08
    4893 1956.41  4949.3 1955.68    4993 1952.22  4995.5 1950.06  4996.6 1949.56
    5003 1950.06    5029 1953.03  5078.2 1954.06  5151.3 1954.49    5160 1952.45
    5195 1954.63  5253.4  1953.4  5421.1 1954.95  5712.2 1962.58  5727.7 1963.98
  5779.1 1965.21  5785.9    1967  5801.4 1967.64  5822.8 1964.54  5946.9 1966.98
#Mann= 3 ,-1 , 0
  4468.7     .05       0  4995.5     .05       0    5003     .05       0
Bank Sta=4995.5,5003
XS Rating Curve= 0 ,0
Exp/Cntr=0.3,0.1

Type RM Length L Ch R = 1 ,92343   ,519,519,519
BEGIN DESCRIPTION:
Lytle Creek 92595.09
END DESCRIPTION:
XS GIS Cut Line= 4
      1626668.15       6794157.2      1626760.37      6794646.33
      1626944.71      6795006.11      1626979.71      6795053.35
#Sta/Elev= 30
  4495.7 1964.29  4508.7 1964.16    4527 1962.63  4556.1 1962.75  4561.2 1962.08
  4608.5 1960.63  4613.6    1960  4723.5 1957.16  4730.6 1955.71  4750.9 1954.43
  4791.6 1949.67  4974.8  1950.5    4985  1949.8  4990.8 1947.02  5002.8 1946.72
    5004 1946.22  5009.2 1946.22  5010.3 1946.72  5013.4 1948.12    5029 1950.77
    5080 1949.91  5146.6  1949.8  5197.6 1950.47  5207.6 1950.08  5235.4 1951.09
    5252 1950.33  5318.6 1949.94    5402 1950.33  5427.3 1951.31  5456.5 1951.33
#Mann= 3 ,-1 , 0
  4495.7     .05       0  5002.8     .05       0  5010.3     .05       0
Bank Sta=5002.8,5010.3
XS Rating Curve= 0 ,0
Exp/Cntr=0.3,0.1

Type RM Length L Ch R = 1 ,91824   ,473,473,473
BEGIN DESCRIPTION:
Lytle Creek 92056
END DESCRIPTION:
XS GIS Cut Line= 3
      1626238.39      6794123.56      1626263.78      6794857.45
      1626510.57      6795152.25
#Sta/Elev= 30
  4387.1 1965.75  4430.1  1964.9  4435.1 1965.65  4511.6 1961.83  4531.6 1959.87
  4551.6 1960.68  4571.7 1958.69  4631.7 1955.84  4711.7 1952.78  4724.8 1953.15
  4841.8 1947.83  4871.8 1947.55  4891.8  1946.1  4911.9 1947.17  4941.9 1943.78
  4951.9 1943.72  4961.9 1945.44  4971.9 1942.78  4991.9 1942.87  4998.1  1942.2
  4999.3  1941.7  5005.7  1942.2  5021.9 1942.93  5041.9 1945.17    5092 1944.53
  5119.2 1947.33  5125.1 1947.33  5129.9 1946.18  5335.5 1947.74  5505.9 1947.48
#Mann= 3 ,-1 , 0
  4387.1     .05       0  4998.1     .03       0  5005.7     .05       0
Bank Sta=4998.1,5005.7
XS Rating Curve= 0 ,0
Exp/Cntr=0.3,0.1

Type RM Length L Ch R = 1 ,91351   ,460,460,460
BEGIN DESCRIPTION:
Mapping XS 2f5a3b62
END DESCRIPTION:
XS GIS Cut Line= 4
      1625730.16      6793971.84      1625842.14       6794378.1
      1625857.77      6794823.42      1626081.71      6795174.95
#Sta/Elev= 30
  4406.7 1954.13  4515.3 1951.59    4634 1950.65  4702.7 1948.89  4724.3 1949.92
  4742.3 1948.74  4796.9 1947.95    4868 1944.27  4928.1 1943.48  4938.1 1941.39
  4948.1 1940.31  4968.1 1943.42  4978.1 1941.78  4984.3  1937.1  4985.5  1936.6
  4991.9  1937.1  5028.1 1940.71  5038.1 1942.54  5047.7 1942.18  5052.7 1942.79
  5058.1 1941.75  5078.2 1942.92  5148.2 1942.48  5188.2 1942.77  5218.2 1943.86
  5248.3 1942.82  5281.5 1943.14  5317.9 1942.31  5369.5 1942.26  5690.5 1944.65
#Mann= 3 ,-1 , 0
  4406.7     .05       0  4984.3     .05       0  4991.9     .05       0
Bank Sta=4984.3,4991.9
XS Rating Curve= 0 ,0
Exp/Cntr=0.3,0.1

Type RM Length L Ch R = 1 ,90891   ,516,516,516
BEGIN DESCRIPTION:
Mapping XS 617cf102
END DESCRIPTION:
XS GIS Cut Line= 4
      1625406.98      6794489.31      1625516.62      6794698.42
      1625870.79      6795109.87      1626091.08      6795296.47
#Sta/Elev= 30
  4609.2 1946.53  4614.5 1945.99  4620.2 1946.35  4630.3 1944.38  4636.6 1941.75
  4642.2  1942.1  4652.9 1940.71  4658.7  1940.4  4686.8 1940.54  4702.8 1940.05
  4754.5 1939.82  4768.9 1940.22  4835.1 1940.71  4842.3 1941.12    4886 1941.17
  4893.7 1941.54  4943.1 1941.85  4950.3 1941.43  4978.2 1941.62  4996.3 1936.02
  4997.5 1935.52  5002.8 1935.52  5003.9 1936.02    5021 1940.97  5028.7 1941.88
  5042.7 1941.29  5198.7 1941.65  5474.7 1943.63  5531.8 1944.37  5676.9 1945.13
#Mann= 3 ,-1 , 0
  4609.2     .05       0  4996.3     .05       0  5003.9     .05       0
Bank Sta=4996.3,5003.9
XS Rating Curve= 0 ,0
Exp/Cntr=0.3,0.1

Type RM Length L Ch R = 1 ,90375   ,255,255,255
BEGIN DESCRIPTION:
Lytle Creek 90738.38
END DESCRIPTION:
XS GIS Cut Line= 4
       1624912.4      6794426.55      1625145.59      6794800.01
      1625351.17      6795050.62      1625614.99      6795248.66
#Sta/Elev= 30
  4301.3 1941.98  4385.4 1941.21  4427.9 1940.16  4456.3 1940.81  4479.8 1939.61
  4595.4 1939.04  4622.5 1939.71  4631.9 1939.12  4775.7 1938.77  4860.4 1937.49
  4881.3 1935.01  4889.1 1935.03  4895.6 1937.59  4924.3  1938.4  4967.3 1938.18
  4973.8 1938.79  4981.7 1937.72    4996 1934.45  4998.5 1933.37  4999.7 1932.87
  5005.2 1932.87  5006.4 1933.37  5010.4 1937.34  5016.8 1938.01  5023.5 1940.17
  5045.5    1939  5081.6 1939.59  5108.6 1939.13  5195.6 1940.67  5395.6 1942.14
#Mann= 3 ,-1 , 0
  4301.3     .05       0  4998.5     .03       0  5006.4     .05       0
Bank Sta=4998.5,5006.4
XS Rating Curve= 0 ,0
Exp/Cntr=0.3,0.1

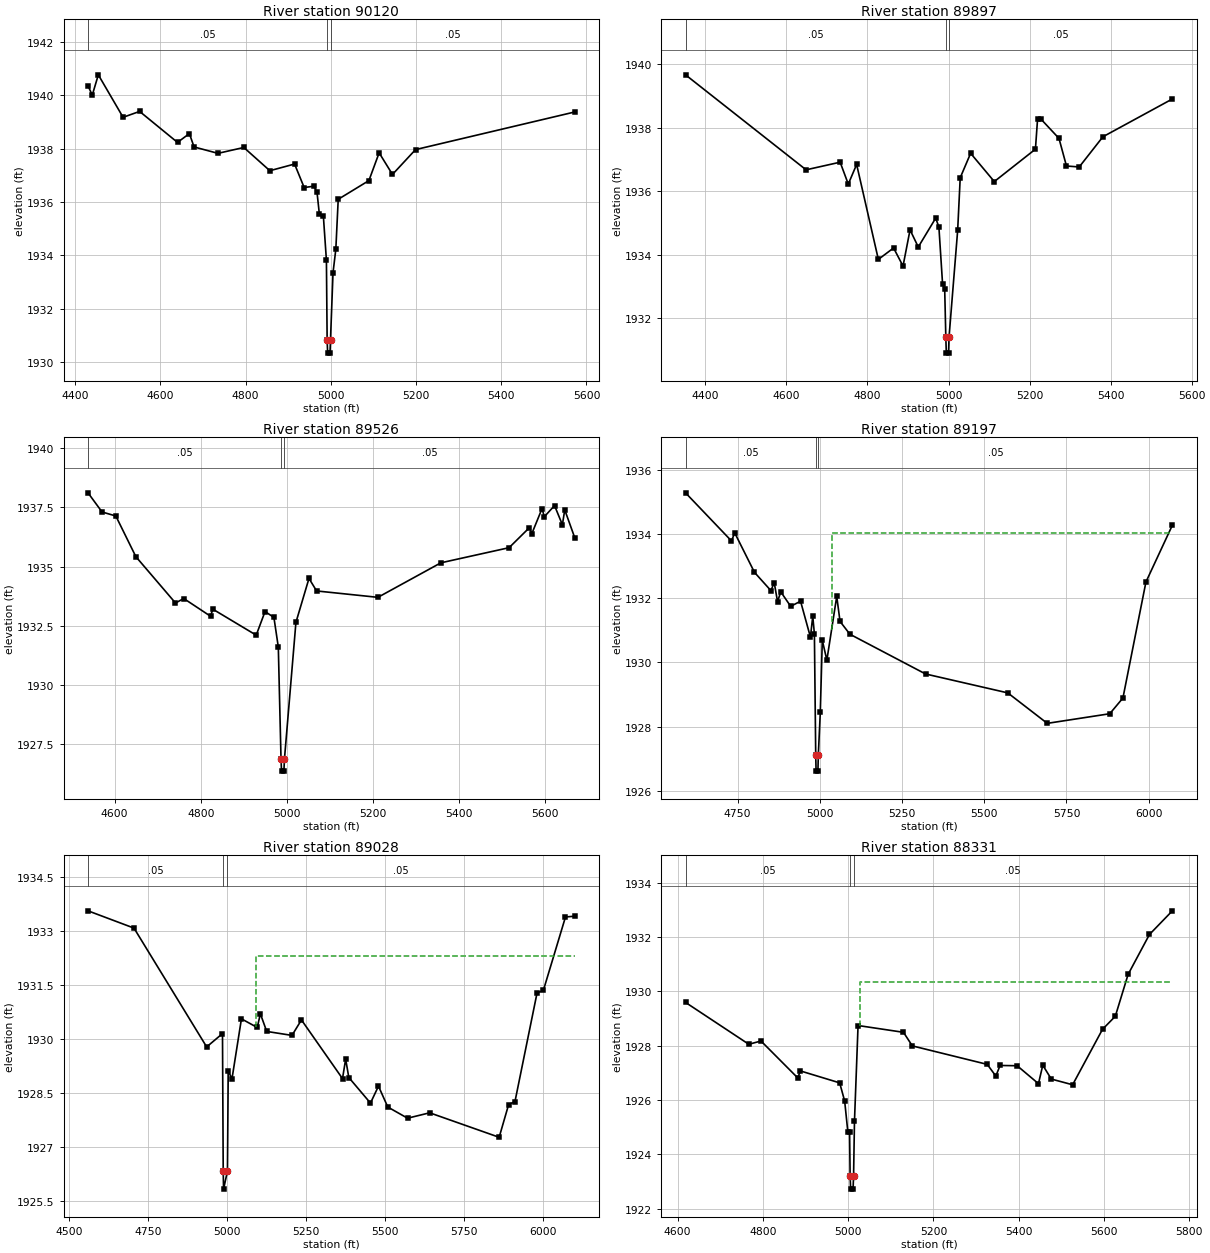
Type RM Length L Ch R = 1 ,90120   ,223,223,223
BEGIN DESCRIPTION:
Lytle Creek 90470.76
END DESCRIPTION:
XS GIS Cut Line= 5
      1624834.27      6794506.42       1625033.3       6794896.5
      1625109.28      6795042.61      1625183.45      6795241.12
      1625375.95      6795506.42
#Sta/Elev= 30
  4430.4 1940.35  4440.4    1940  4454.6 1940.76  4512.7 1939.17  4551.5 1939.39
  4640.4 1938.23  4668.3 1938.56  4679.2 1938.06  4735.3 1937.82    4796 1938.04
  4857.1 1937.17  4915.1 1937.42  4937.6 1936.54  4960.2 1936.59  4967.7 1936.37
  4973.3 1935.54  4982.7 1935.46  4989.8 1933.82  4991.5 1930.84  4992.7 1930.34
  4998.2 1930.34  4999.4 1930.84  5005.3 1933.35  5011.9 1934.23  5017.5  1936.1
  5089.5  1936.8  5113.5 1937.84  5144.8 1937.03  5198.9 1937.96  5572.7 1939.37
#Mann= 3 ,-1 , 0
  4430.4     .05       0  4991.5     .05       0  4999.4     .05       0
Bank Sta=4991.5,4999.4
XS Rating Curve= 0 ,0
Exp/Cntr=0.3,0.1

Type RM Length L Ch R = 1 ,89897   ,371,371,371
BEGIN DESCRIPTION:
Lytle Creek 90266.99
END DESCRIPTION:
XS GIS Cut Line= 5
      1624795.56       6794552.1      1624910.04      6794949.07
      1624943.61      6795150.42      1625037.42      6795439.85
      1625303.95      6795524.92
#Sta/Elev= 30
  4351.1 1939.67  4648.6 1936.68  4732.6 1936.92  4752.7 1936.23  4773.3 1936.85
  4826.9 1933.86  4864.5 1934.22  4887.8 1933.65  4905.1 1934.79  4925.4 1934.25
  4968.4 1935.16  4976.3 1934.88  4985.3  1933.1  4990.6 1932.93  4993.4 1931.41
  4994.6 1930.91  5000.1 1930.91  5001.3 1931.41  5022.6 1934.77  5028.9 1936.43
  5054.6  1937.2    5113 1936.31  5214.5 1937.33  5219.8 1938.28  5228.6 1938.27
  5272.6 1937.67  5291.1  1936.8  5322.6 1936.77    5381 1937.72  5552.4 1938.91
#Mann= 3 ,-1 , 0
  4351.1     .05       0  4993.4     .05       0  5001.3     .05       0
Bank Sta=4993.4,5001.3
XS Rating Curve= 0 ,0
Exp/Cntr=0.3,0.1

Type RM Length L Ch R = 1 ,89526   ,329,329,329
BEGIN DESCRIPTION:
Lytle Creek 89915
END DESCRIPTION:
XS GIS Cut Line= 5
      1624592.08      6794937.41      1624688.25      6795198.63
      1624731.81        6795390.      1624761.34      6795599.28
      1625170.32      6795772.68
#Sta/Elev= 30
  4538.2 1938.12  4570.8 1937.31  4602.8 1937.14  4649.3 1935.42  4741.3 1933.46
  4760.5 1933.65  4822.7  1932.9  4827.9  1933.2  4928.7  1932.1  4949.2  1933.1
  4969.8 1932.85    4980  1931.6  4986.3 1926.85  4987.5 1926.35    4993 1926.35
  4994.2 1926.85  5020.9 1932.64  5051.2  1934.5  5068.9 1933.97  5211.2  1933.7
  5357.4 1935.16  5515.8  1935.8  5563.1 1936.65  5568.5 1936.39  5592.2 1937.45
  5597.6 1937.11  5621.3 1937.58  5639.5 1936.77    5645  1937.4  5668.4 1936.21
#Mann= 3 ,-1 , 0
  4538.2     .05       0  4986.3     .05       0  4994.2     .05       0
Bank Sta=4986.3,4994.2
XS Rating Curve= 0 ,0
Exp/Cntr=0.3,0.1

Type RM Length L Ch R = 1 ,89197   ,169,169,169
BEGIN DESCRIPTION:
Lytle Creek 89547.78
END DESCRIPTION:
XS GIS Cut Line= 4
      1624395.83      6794978.53      1624411.02      6795395.18
        1624410.       6795531.4      1624404.48      6796458.33
#Sta/Elev= 30
  4591.8 1935.29  4731.4 1933.79  4741.4 1934.04  4801.4 1932.81  4851.4 1932.24
  4861.4 1932.49  4871.5  1931.9  4881.5  1932.2  4911.5 1931.75  4941.5 1931.91
  4971.5 1930.79  4978.6 1931.44  4983.6 1930.89  4987.6 1927.11  4988.7 1926.61
  4994.3 1926.61  4995.5 1927.11  5001.5 1928.44  5007.6 1930.69  5021.5 1930.07
  5051.5 1932.06  5061.5 1931.28  5091.5 1930.88  5321.6 1929.64  5571.6 1929.05
  5691.6  1928.1  5881.6  1928.4  5921.6 1928.89  5991.6 1932.51  6071.9 1934.28
#Mann= 3 ,-1 , 0
  4591.8     .05       0  4987.6     .05       0  4995.5     .05       0
#XS Ineff= 2 , 0
       0                  5035.8       0 1934.04
Permanent Ineff=
       F       F
Bank Sta=4987.6,4995.5
XS Rating Curve= 0 ,0
Exp/Cntr=0.3,0.1

Type RM Length L Ch R = 1 ,89028   ,697,697,697
BEGIN DESCRIPTION:
Lytle Creek 89363.56
END DESCRIPTION:
XS GIS Cut Line= 5
      1624243.92      6794952.48      1624259.11      6795399.52
      1624264.58      6795801.57      1624299.15      6795898.07
       1624303.7      6796487.56
#Sta/Elev= 30
  4559.5 1933.55  4705.1 1933.07  4935.2 1929.77  4985.3 1930.14  4987.6 1926.32
  4988.7 1925.82    5001 1926.32  5003.5 1929.11  5015.3 1928.88  5045.3 1930.55
  5095.3 1930.31  5105.3 1930.69  5125.3  1930.2  5205.3 1930.09  5235.3 1930.52
  5365.3 1928.89  5375.3 1929.43  5385.3 1928.92  5453.8 1928.21  5479.2 1928.68
  5508.7  1928.1  5571.3 1927.79  5641.3 1927.94  5861.3 1927.26  5891.3 1928.17
  5911.3 1928.25  5981.3 1931.27  6001.3 1931.34  6071.3 1933.38  6100.9  1933.4
#Mann= 3 ,-1 , 0
  4559.5     .05       0  4987.6     .05       0    5001     .05       0
#XS Ineff= 2 , 0
       0                    5091       0  1932.3
Permanent Ineff=
       F       F
Bank Sta=4987.6,5001
XS Rating Curve= 0 ,0
Exp/Cntr=0.3,0.1

Type RM Length L Ch R = 1 ,88331   ,309,309,309
BEGIN DESCRIPTION:
Lytle Creek 88641.42
END DESCRIPTION:
XS GIS Cut Line= 4
      1623805.32      6795581.36      1624153.64      6795739.78
      1624264.81      6795890.07      1624288.72      6796461.68
#Sta/Elev= 30
  4618.6 1929.59    4767 1928.05  4795.6 1928.17  4881.9 1926.81  4887.8 1927.07
  4980.1 1926.63  4991.8 1925.96  4999.3 1924.82  5003.3 1924.82  5004.6 1923.22
  5005.8 1922.72  5011.5 1922.72  5012.7 1923.22  5014.8 1925.22  5023.2 1928.74
  5129.7 1928.49  5150.5 1927.99  5326.2 1927.31  5346.3 1926.88  5356.3 1927.27
  5396.3 1927.26  5446.3  1926.6  5456.4 1927.28  5476.4 1926.77  5526.4 1926.56
  5596.5  1928.6  5626.5 1929.08  5656.5 1930.62  5706.6 1932.09  5760.3 1932.96
#Mann= 3 ,-1 , 0
  4618.6     .05       0  5004.6     .05       0  5012.7     .05       0
#XS Ineff= 2 , 0
       0                  5028.3       0 1930.35
Permanent Ineff=
       F       F
Bank Sta=5004.6,5012.7
XS Rating Curve= 0 ,0
Exp/Cntr=0.3,0.1

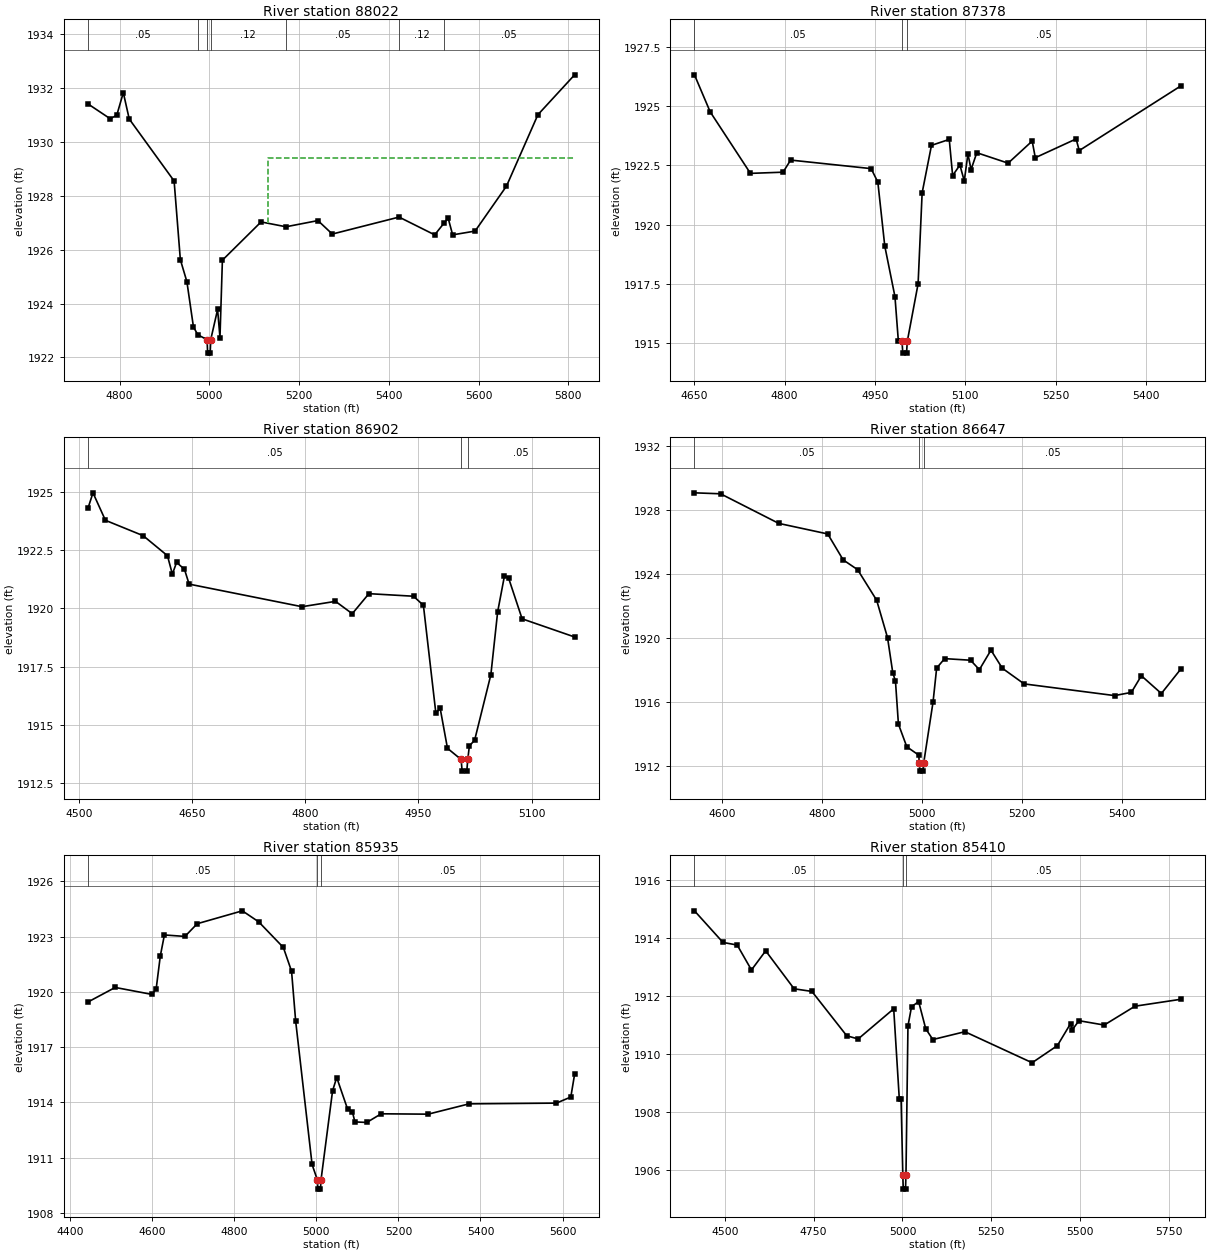
Type RM Length L Ch R = 1 ,88022   ,644,644,644
BEGIN DESCRIPTION:
Lytle Creek 88332.5
END DESCRIPTION:
XS GIS Cut Line= 4
      1623691.45      6795732.46      1623908.45      6795895.21
      1624263.83      6796024.92      1624266.64      6796459.75
#Sta/Elev= 30
  4729.7 1931.41  4779.2 1930.86  4793.8 1930.99  4808.4 1931.83  4821.6 1930.85
  4921.6 1928.55  4935.5 1925.63  4950.1 1924.81  4964.7 1923.13  4974.5 1922.84
  4995.1 1922.66  4996.3 1922.16    5002 1922.16  5003.2 1922.66  5018.5 1923.78
  5023.8 1922.74  5029.2 1925.61  5115.4 1927.03  5170.9 1926.85  5242.1 1927.08
  5274.1 1926.58  5422.9 1927.21  5502.3 1926.55  5522.8 1926.98  5532.3 1927.17
  5542.3 1926.55  5592.3 1926.69  5662.3 1928.36  5732.3 1931.01  5814.1 1932.49
#Mann= 7 ,-1 , 0
  4729.7     .05       0  4974.5     .12       0  4995.1     .07       0
  5003.2     .12       0  5170.9     .05       0  5422.9     .12       0
  5522.8     .05       0
#XS Ineff= 2 , 0
       0  4868.3 1929.42  5131.7       0 1929.42
Permanent Ineff=
       F       F
Bank Sta=4995.1,5003.2
XS Rating Curve= 0 ,0
Exp/Cntr=0.3,0.1

Type RM Length L Ch R = 1 ,87378   ,476,476,476
BEGIN DESCRIPTION:
Lytle Creek 87790.86
END DESCRIPTION:
XS GIS Cut Line= 3
      1623443.73      6796084.55      1623636.15      6796478.55
      1623991.01      6796579.83
#Sta/Elev= 30
  4650.4 1926.31  4676.5 1924.75  4743.3 1922.16  4797.4 1922.21    4810 1922.72
  4943.6 1922.36  4954.7 1921.79  4966.2  1919.1  4983.1 1916.97  4988.7 1915.11
  4994.8 1915.09  4996.1 1914.59  5002.3 1914.59  5003.6 1915.09  5021.5 1917.51
  5028.2 1921.34  5043.7 1923.34  5073.2 1923.59  5078.8 1922.07  5090.9 1922.51
  5098.1 1921.84  5104.2 1922.98  5109.4 1922.32  5118.9 1923.03  5170.9 1922.59
  5210.8 1923.52    5216 1922.82  5283.7 1923.61  5288.9 1923.12  5457.9 1925.85
#Mann= 3 ,-1 , 0
  4650.4     .05       0  4994.8     .05       0  5003.6     .05       0
Bank Sta=4994.8,5003.6
XS Rating Curve= 0 ,0
Exp/Cntr=0.3,0.1

Type RM Length L Ch R = 1 ,86902   ,255,255,255
BEGIN DESCRIPTION:
Lytle Creek 87176.58
END DESCRIPTION:
XS GIS Cut Line= 3
      1623401.56      6796134.37      1623167.21      6796590.06
      1623114.26       6796711.5
#Sta/Elev= 30
  4512.1  1924.3  4518.7 1924.96  4535.2 1923.78  4585.2 1923.12  4617.4 1922.26
  4623.9 1921.47  4629.5 1921.97  4639.9 1921.68  4646.1 1921.04  4795.7 1920.07
  4840.1  1920.3  4862.3 1919.77  4884.4 1920.63  4943.5 1920.52  4956.6 1920.13
  4973.1  1915.5  4978.8 1915.71  4988.5 1913.99  5006.6 1913.51  5007.9 1913.01
  5014.1 1913.01  5015.4 1913.51  5017.5 1914.09  5024.5 1914.34    5046 1917.15
    5055 1919.85    5064 1921.39  5069.5  1921.3  5087.4 1919.55    5157 1918.77
#Mann= 3 ,-1 , 0
  4512.1     .05       0  5006.6     .05       0  5015.4     .05       0
Bank Sta=5006.6,5015.4
XS Rating Curve= 0 ,0
Exp/Cntr=0.3,0.1

Type RM Length L Ch R = 1 ,86647   ,712,712,712
BEGIN DESCRIPTION:
Lytle Creek 86919.68
END DESCRIPTION:
XS GIS Cut Line= 4
      1623109.93      6796103.05      1622940.65       6796493.7
      1622823.46      6796755.51      1622836.59      6797017.49
#Sta/Elev= 30
  4544.4 1929.08  4596.7 1929.02  4713.3 1927.17  4811.4 1926.51  4842.3 1924.89
  4871.2 1924.28  4909.4 1922.37  4931.2 1920.03  4941.7 1917.84  4947.1 1917.31
    4953 1914.63  4969.8 1913.21  4993.8 1912.69  4994.8 1912.19  4996.1 1911.69
  5002.4 1911.69  5003.6 1912.19  5022.4 1916.01  5029.6 1918.13  5045.6 1918.72
  5097.5 1918.62  5115.2 1918.03  5138.4 1919.25  5161.1 1918.12  5204.9 1917.14
  5386.1 1916.41  5419.7 1916.61  5439.7 1917.65  5479.8 1916.54  5519.3 1918.09
#Mann= 3 ,-1 , 0
  4544.4     .05       0  4994.8     .03       0  5003.6     .05       0
Bank Sta=4994.8,5003.6
XS Rating Curve= 0 ,0
Exp/Cntr=0.3,0.1

Type RM Length L Ch R = 1 ,85935   ,525,525,525
BEGIN DESCRIPTION:
Lytle Creek 86174.52
END DESCRIPTION:
XS GIS Cut Line= 4
      1622294.38      6796181.76      1622304.79      6796747.69
      1622303.09      6796815.98       1622733.2      6797162.07
#Sta/Elev= 30
  4443.1 1919.45  4509.4 1920.24  4599.4 1919.86  4609.4 1920.18  4619.4 1921.95
  4629.4 1923.09  4679.4 1923.01  4709.4  1923.7  4819.4  1924.4  4859.4  1923.8
  4919.4 1922.41  4939.4 1921.12  4949.4 1918.41  4989.4 1910.63  5002.3 1909.79
  5003.6 1909.29  5009.9 1909.29  5011.2 1909.79  5039.4 1914.63  5049.5 1915.35
  5075.9 1913.64  5087.5  1913.5  5093.9 1912.94  5122.7 1912.91  5157.9 1913.38
  5272.4 1913.36  5372.2 1913.92    5585 1913.96  5620.2 1914.29  5629.5 1915.53
#Mann= 3 ,-1 , 0
  4443.1     .05       0  5002.3     .05       0  5011.2     .05       0
Bank Sta=5002.3,5011.2
XS Rating Curve= 0 ,0
Exp/Cntr=0.3,0.1

Type RM Length L Ch R = 1 ,85410   ,239,239,239
BEGIN DESCRIPTION:
Lytle Creek 85633.84
END DESCRIPTION:
XS GIS Cut Line= 4
      1621777.02      6796167.81      1621794.38      6796744.22
      1621808.59      6797090.17      1622248.12      6797164.64
#Sta/Elev= 30
  4414.9 1914.93  4495.1 1913.84  4535.1 1913.75  4575.2 1912.89  4615.2 1913.55
  4695.2 1912.24  4745.2 1912.15  4843.2 1910.62  4875.3 1910.51  4975.3 1911.55
    4991 1908.45    4996 1908.45  5000.9 1905.83  5002.2 1905.33  5008.5 1905.33
  5009.8 1905.83  5015.4 1910.96  5025.4 1911.62  5045.4  1911.8  5065.4 1910.86
  5085.4 1910.49  5175.5 1910.76  5364.6 1909.69  5435.6 1910.28  5472.8 1911.04
  5477.8 1910.83  5496.4 1911.14  5567.4 1910.99  5653.9 1911.64  5783.6 1911.88
#Mann= 3 ,-1 , 0
  4414.9     .05       0  5000.9     .05       0  5009.8     .05       0
Bank Sta=5000.9,5009.8
XS Rating Curve= 0 ,0
Exp/Cntr=0.3,0.1

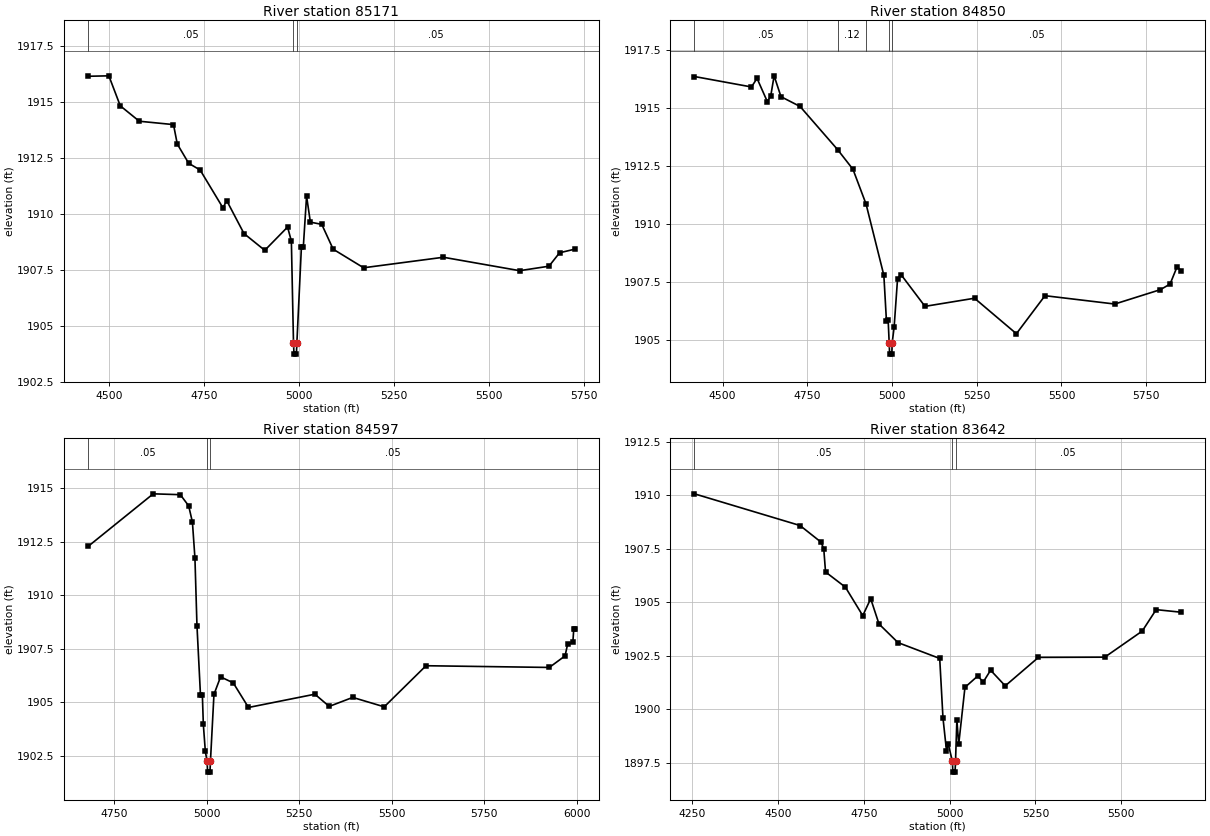
Type RM Length L Ch R = 1 ,85171   ,321,321,321
BEGIN DESCRIPTION:
Lytle Creek 85399.18
END DESCRIPTION:
XS GIS Cut Line= 4
       1621554.8      6796133.14      1621575.63      6796695.61
      1621570.54      6797262.98      1621638.62      6797397.03
#Sta/Elev= 30
  4444.8 1916.15  4499.7 1916.17  4529.7 1914.83  4579.8 1914.14  4669.8 1913.99
  4679.8 1913.12  4709.8 1912.26  4739.9 1911.96  4799.9 1910.27  4809.9 1910.59
  4855.3 1909.12    4910 1908.37    4970 1909.41    4980 1908.78  4985.6 1904.23
  4986.9 1903.73  4993.2 1903.73  4994.5 1904.23  5006.4 1908.51  5011.4 1908.51
    5020 1910.79    5030 1909.63    5060 1909.53    5090 1908.42  5170.1 1907.59
  5380.1 1908.06  5580.7 1907.46  5657.9 1907.66  5685.8 1908.26  5725.4 1908.42
#Mann= 3 ,-1 , 0
  4444.8     .05       0  4985.6     .03       0  4994.5     .05       0
Bank Sta=4985.6,4994.5
XS Rating Curve= 0 ,0
Exp/Cntr=0.3,0.1

Type RM Length L Ch R = 1 ,84850   ,253,253,253
BEGIN DESCRIPTION:
Mapping XS dbb66543
END DESCRIPTION:
XS GIS Cut Line= 4
       1621177.2        6796135.      1621218.88      6796437.13
      1621319.57      6797076.02      1621639.07      6797440.29
#Sta/Elev= 30
  4416.8 1916.35    4585  1915.9  4601.5 1916.27  4631.8 1915.27  4641.9 1915.51
  4651.9 1916.38  4672.2 1915.48  4728.4 1915.06  4839.2  1913.2  4884.6 1912.35
  4923.3 1910.85  4975.8 1907.78  4983.4 1905.82  4988.4 1905.87  4991.5 1904.88
  4992.8 1904.38  4999.2 1904.38  5000.5 1904.88  5006.1 1905.54  5016.3 1907.64
  5026.4 1907.81  5097.2 1906.44  5243.4 1906.79    5367 1905.26  5451.4  1906.9
  5657.3 1906.54    5792 1907.16  5820.5  1907.4  5841.4 1908.15  5853.1 1907.98
#Mann= 5 ,-1 , 0
  4416.8     .05       0  4839.2     .12       0  4923.3     .05       0
  4991.5     .05       0  5000.5     .05       0
Bank Sta=4991.5,5000.5
XS Rating Curve= 0 ,0
Exp/Cntr=0.3,0.1

Type RM Length L Ch R = 1 ,84597   ,955,955,955
BEGIN DESCRIPTION:
Lytle Creek 84881.32
END DESCRIPTION:
XS GIS Cut Line= 4
      1620922.84      6796414.33      1621058.27      6796692.14
      1621194.35      6797000.21      1621643.34       6797496.5
#Sta/Elev= 30
  4679.4 1912.28  4855.7 1914.74  4928.9  1914.7  4951.4 1914.18  4961.6 1913.42
  4968.4 1911.74  4973.9 1908.58  4983.4 1905.33  4988.5 1905.33  4991.1 1903.97
  4996.5 1902.71  5001.3 1902.24  5002.6 1901.74    5009 1901.74  5010.3 1902.24
  5019.8 1905.37  5037.7 1906.19  5071.9 1905.91  5113.1 1904.76  5292.6 1905.38
  5331.3 1904.81  5394.9 1905.23    5480 1904.79  5592.9 1906.71  5926.1 1906.63
  5968.7 1907.17  5975.5 1907.71  5989.7  1907.8  5992.2 1908.43  5994.5 1908.43
#Mann= 3 ,-1 , 0
  4679.4     .05       0  5001.3     .05       0  5010.3     .05       0
Bank Sta=5001.3,5010.3
XS Rating Curve= 0 ,0
Exp/Cntr=0.3,0.1

Type RM Length L Ch R = 1 ,83642   ,431,431,431
BEGIN DESCRIPTION:
Mapping XS f6a1cfaa
END DESCRIPTION:
XS GIS Cut Line= 4
      1620816.09      6796423.29      1620740.58      6796928.45
      1620925.48      6797425.85       1621296.8      6797368.84
#Sta/Elev= 30
  4257.2 1910.07  4564.6 1908.59    4626 1907.81  4633.8 1907.49  4638.9 1906.42
  4696.7 1905.71  4747.3 1904.38  4770.4 1905.17  4794.6 1903.99    4850 1903.12
  4971.4 1902.38  4980.9  1899.6  4991.1 1898.08  4996.4 1898.38  5008.3 1897.57
  5009.6 1897.07  5016.1 1897.07  5017.4 1897.57  5021.4 1899.51  5026.7 1898.37
  5044.9 1901.03  5082.1 1901.56  5098.2 1901.28  5119.6 1901.83  5162.2  1901.1
  5258.9 1902.43  5452.1 1902.44  5561.2 1903.66  5601.7 1904.66  5674.3 1904.54
#Mann= 3 ,-1 , 0
  4257.2     .05       0  5008.3     .05       0  5017.4     .05       0
Bank Sta=5008.3,5017.4
XS Rating Curve= 0 ,0
Exp/Cntr=0.3,0.1