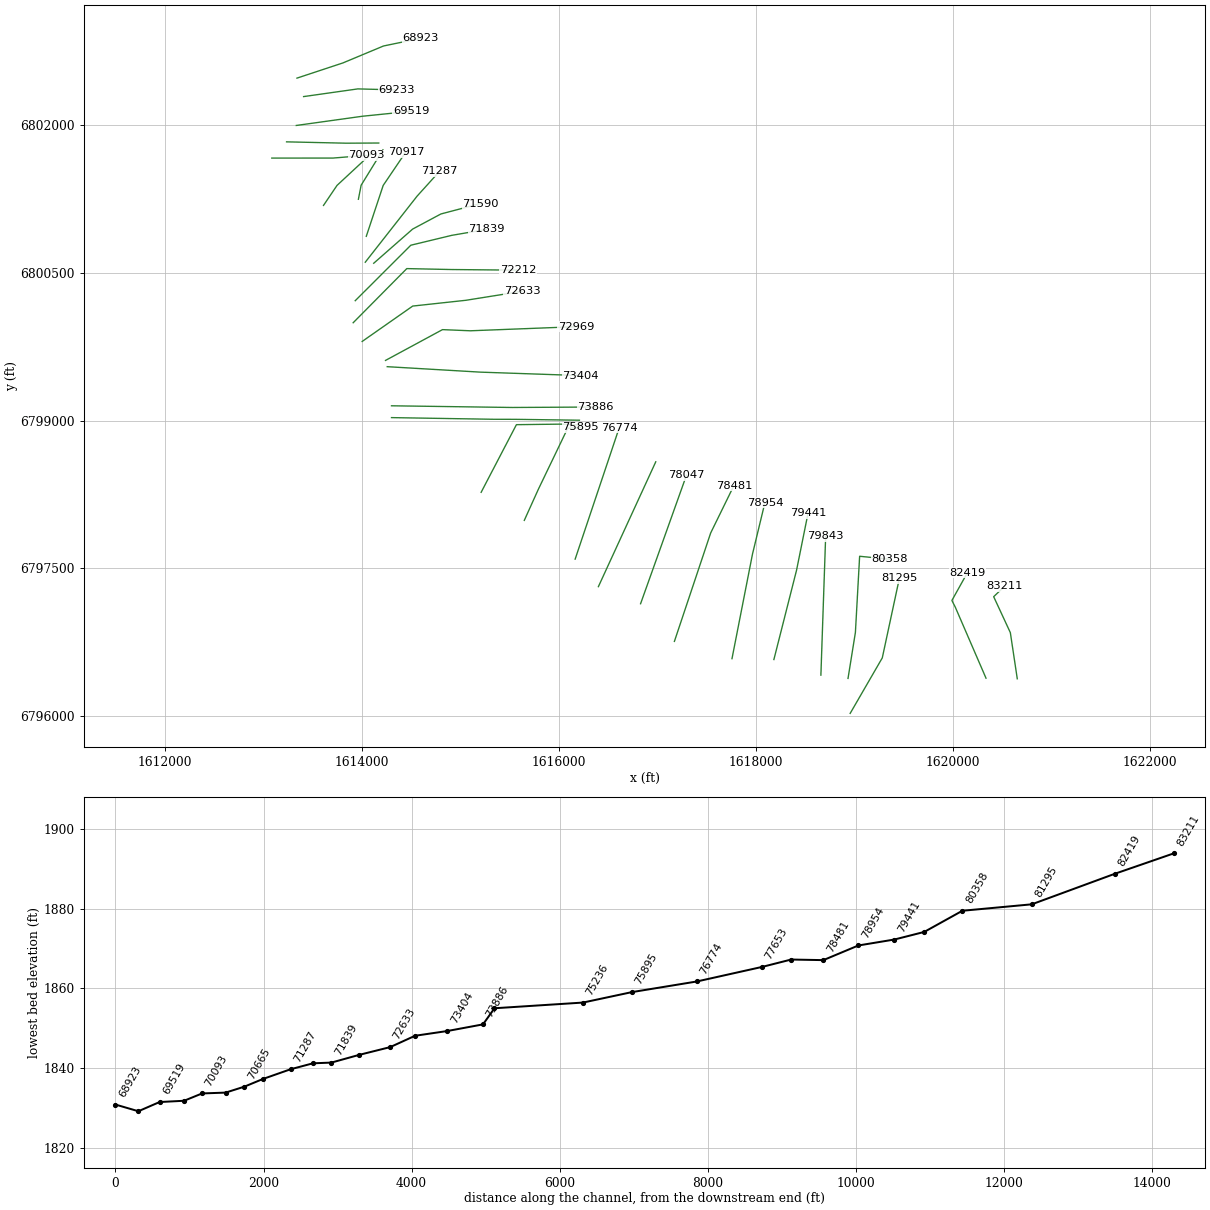
HEC-RAS study Lytle Creek.prj: Lytle Creek Base Level Engineering

--- Lytle Creek.g02 (geometry) --- (continued)

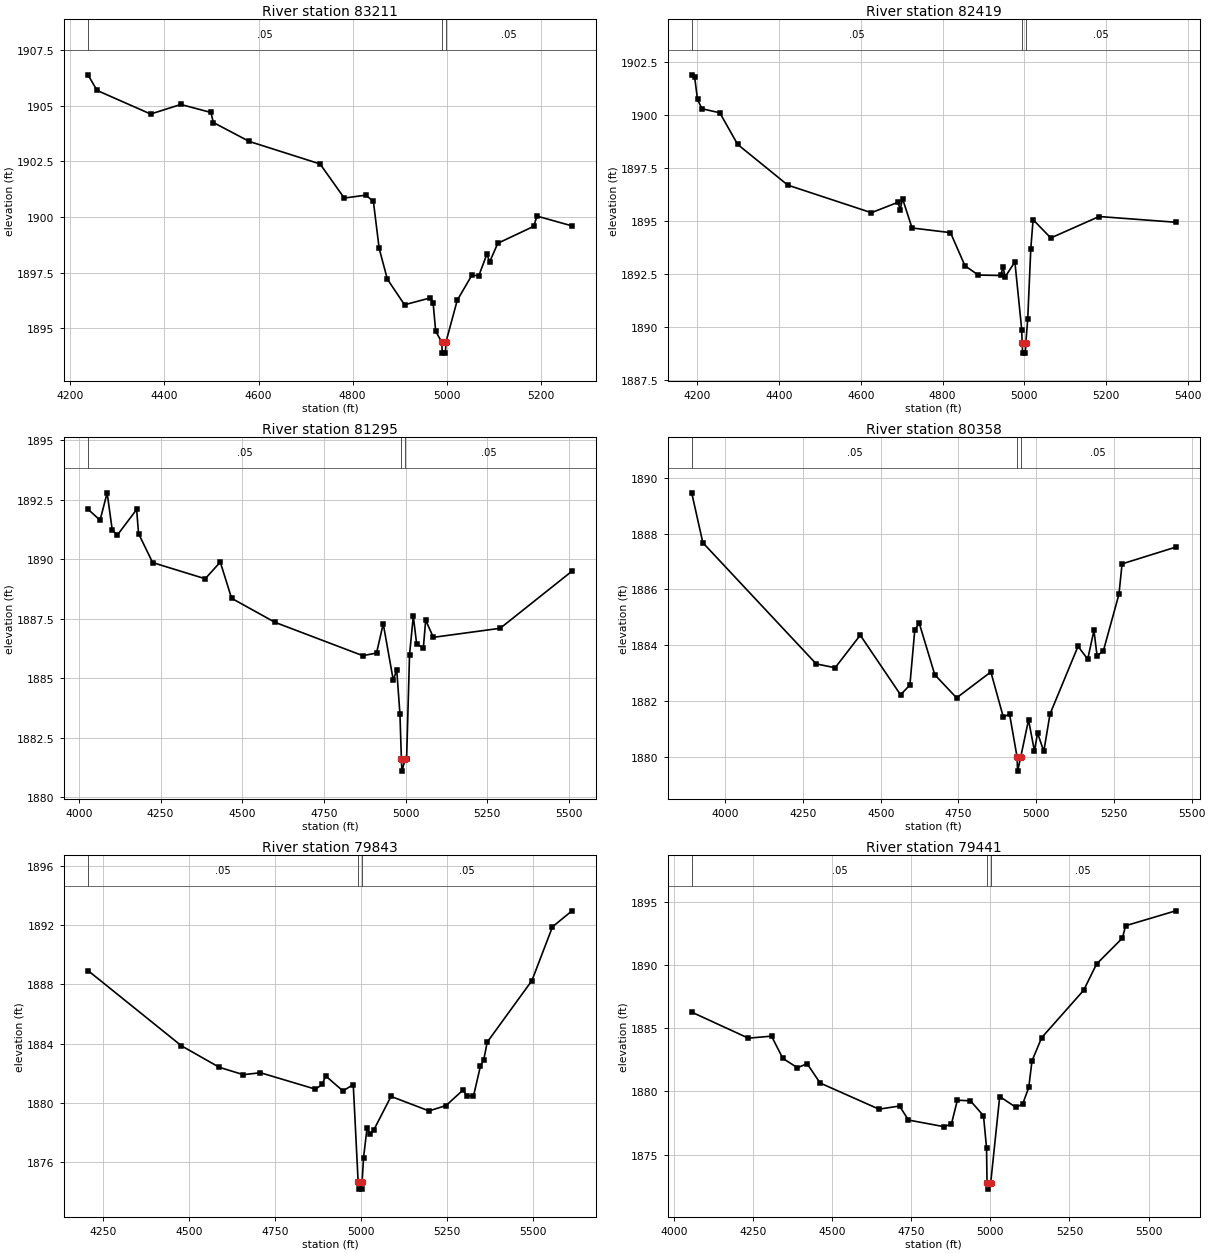
Type RM Length L Ch R = 1 ,83211   ,792,792,792
BEGIN DESCRIPTION:
Mapping XS cd2165bb
END DESCRIPTION:
XS GIS Cut Line= 4
      1620649.43      6796379.01      1620579.12      6796847.72
      1620409.97      6797212.73      1620520.14      6797317.95
#Sta/Elev= 30
  4237.5 1906.38  4256.7 1905.68  4370.7 1904.62  4434.8 1905.05  4498.8 1904.69
  4503.9 1904.24  4580.3 1903.39  4730.7 1902.38  4782.1 1900.85  4827.9 1900.98
    4844  1900.7  4856.3 1898.59  4873.7 1897.21  4910.2 1896.06  4965.3 1896.37
  4970.9 1896.16  4976.4 1894.87  4989.2 1894.39  4990.5 1893.89    4997 1893.89
  4998.3 1894.39  5022.2 1896.26  5053.4 1897.39    5068 1897.36  5085.4 1898.34
    5091 1897.98  5108.4 1898.82  5184.7 1899.58  5191.7 1900.04  5266.1  1899.6
#Mann= 3 ,-1 , 0
  4237.5     .05       0  4989.2     .05       0  4998.3     .05       0
Bank Sta=4989.2,4998.3
XS Rating Curve= 0 ,0
Exp/Cntr=0.3,0.1

Type RM Length L Ch R = 1 ,82419   ,1124,1124,1124
BEGIN DESCRIPTION:
Lytle Creek 82817.09
END DESCRIPTION:
XS GIS Cut Line= 4
      1620332.13      6796384.92      1620020.07       6797106.8
      1619985.89      6797174.29      1620142.21      6797454.66
#Sta/Elev= 30
  4186.7 1901.91  4193.8 1901.82  4200.9 1900.75  4211.8 1900.31  4255.4 1900.12
    4299 1898.63  4421.6 1896.71  4625.9 1895.41  4690.9  1895.9  4696.4 1895.55
  4702.1 1896.07  4725.3 1894.69  4819.3 1894.47  4854.6 1892.91  4887.3 1892.47
  4941.8 1892.45  4947.7 1892.83  4953.1 1892.39  4976.7 1893.09  4993.4  1889.9
  4994.4 1889.29  4995.7 1888.79  5002.2 1888.79  5003.5 1889.29  5008.1  1890.4
  5015.6 1893.72  5021.2 1895.08  5064.5 1894.22  5182.6 1895.23  5369.8 1894.96
#Mann= 3 ,-1 , 0
  4186.7     .05       0  4994.4     .03       0  5003.5     .05       0
Bank Sta=4994.4,5003.5
XS Rating Curve= 0 ,0
Exp/Cntr=0.3,0.1

Type RM Length L Ch R = 1 ,81295   ,937,937,937
BEGIN DESCRIPTION:
Lytle Creek 82245.587
END DESCRIPTION:
XS GIS Cut Line= 3
      1618953.45       6796027.5      1619279.32      6796591.01
      1619453.47      6797402.89
#Sta/Elev= 30
  4027.8  1892.1  4064.8 1891.64  4086.4 1892.79  4102.1 1891.22  4117.9 1891.02
  4176.7 1892.09  4182.5 1891.08  4225.6 1889.86  4386.5 1889.18  4432.7 1889.88
  4467.3 1888.36  4600.2 1887.35  4868.8 1885.95  4910.9 1886.06  4931.4 1887.29
    4962 1884.93  4972.7 1885.35  4982.5 1883.51    4987  1881.6  4988.5  1881.1
  4998.5  1881.6  5002.9  1881.6  5011.9 1885.99  5023.4 1887.61  5033.6 1886.45
  5054.1 1886.27  5061.3 1887.44  5084.8 1886.72  5289.3  1887.1  5509.1  1889.5
#Mann= 3 ,-1 , 0
  4027.8     .05       0    4987     .05       0  4998.5     .05       0
Bank Sta=4987,4998.5
XS Rating Curve= 0 ,0
Exp/Cntr=0.3,0.1

Type RM Length L Ch R = 1 ,80358   ,515,515,515
BEGIN DESCRIPTION:
Lytle Creek 81638.1
END DESCRIPTION:
XS GIS Cut Line= 4
      1618931.52      6796382.61      1619006.39      6796849.33
      1619049.34      6797623.26      1619356.64      6797592.99
#Sta/Elev= 30
  3892.1 1889.47  3927.9 1887.68  4292.5 1883.33  4353.3 1883.19  4434.2 1884.36
  4563.8 1882.22  4593.8 1882.57  4609.6 1884.55  4623.9 1884.79  4673.9 1882.94
    4744 1882.11  4854.2 1883.04  4894.3 1881.42  4914.3 1881.53  4938.6 1879.98
  4940.1 1879.48  4950.2 1879.98  4975.4 1881.32  4994.4  1880.2  5004.4 1880.85
  5024.5 1880.19  5044.5 1881.53  5134.6 1883.96  5165.7  1883.5  5185.8 1884.53
  5195.8 1883.62  5215.9 1883.79  5266.2 1885.83  5276.2 1886.92  5448.7 1887.52
#Mann= 3 ,-1 , 0
  3892.1     .05       0  4938.6     .05       0  4950.2     .05       0
Bank Sta=4938.6,4950.2
XS Rating Curve= 0 ,0
Exp/Cntr=0.3,0.1

Type RM Length L Ch R = 1 ,79843   ,402,402,402
BEGIN DESCRIPTION:
Lytle Creek 80930.44
END DESCRIPTION:
XS GIS Cut Line= 2
      1618656.17      6796415.88       1618704.4      6797824.76
#Sta/Elev= 30
  4204.9 1888.94  4477.2 1883.85  4587.2  1882.4  4657.3  1881.9  4707.3 1882.03
  4867.4 1880.92  4887.4 1881.24  4896.9 1881.82  4947.5  1880.8  4977.5 1881.23
  4991.7 1874.66  4993.2 1874.16  5001.8 1874.16  5003.3 1874.66  5007.5 1876.29
  5017.5 1878.26  5027.5 1877.89  5037.5 1878.17  5087.5 1880.43  5198.1 1879.45
  5247.6 1879.81  5297.7 1880.87  5307.7 1880.48  5327.7 1880.45  5347.7 1882.46
  5357.7 1882.92  5367.7  1884.1  5497.8 1888.26  5557.8  1891.9  5614.6 1892.98
#Mann= 3 ,-1 , 0
  4204.9     .05       0  4991.7     .05       0  5003.3     .05       0
Bank Sta=4991.7,5003.3
XS Rating Curve= 0 ,0
Exp/Cntr=0.3,0.1

Type RM Length L Ch R = 1 ,79441   ,487,487,487
BEGIN DESCRIPTION:
Lytle Creek 79940.42
END DESCRIPTION:
XS GIS Cut Line= 3
      1618179.08      6796574.47      1618409.12      6797481.63
      1618526.28      6798063.07
#Sta/Elev= 30
  4056.7 1886.27  4235.7 1884.21  4308.8 1884.37  4344.6 1882.61  4390.8 1881.87
  4421.4 1882.19  4462.4 1880.66  4648.4 1878.59  4713.4 1878.84  4741.2 1877.73
  4854.7  1877.2  4877.3 1877.43    4896  1879.3  4937.2 1879.25  4978.5 1878.07
  4988.1 1875.53  4989.7 1872.76  4991.2 1872.26  5001.3 1872.76  5029.7 1879.59
  5080.7 1878.74  5102.2 1878.99  5121.5 1880.31  5131.7 1882.41  5162.3 1884.25
  5294.9    1888  5335.7 1890.08  5417.3 1892.13  5427.5 1893.11  5585.7 1894.29
#Mann= 3 ,-1 , 0
  4056.7     .05       0  4989.7     .05       0  5001.3     .05       0
Bank Sta=4989.7,5001.3
XS Rating Curve= 0 ,0
Exp/Cntr=0.3,0.1

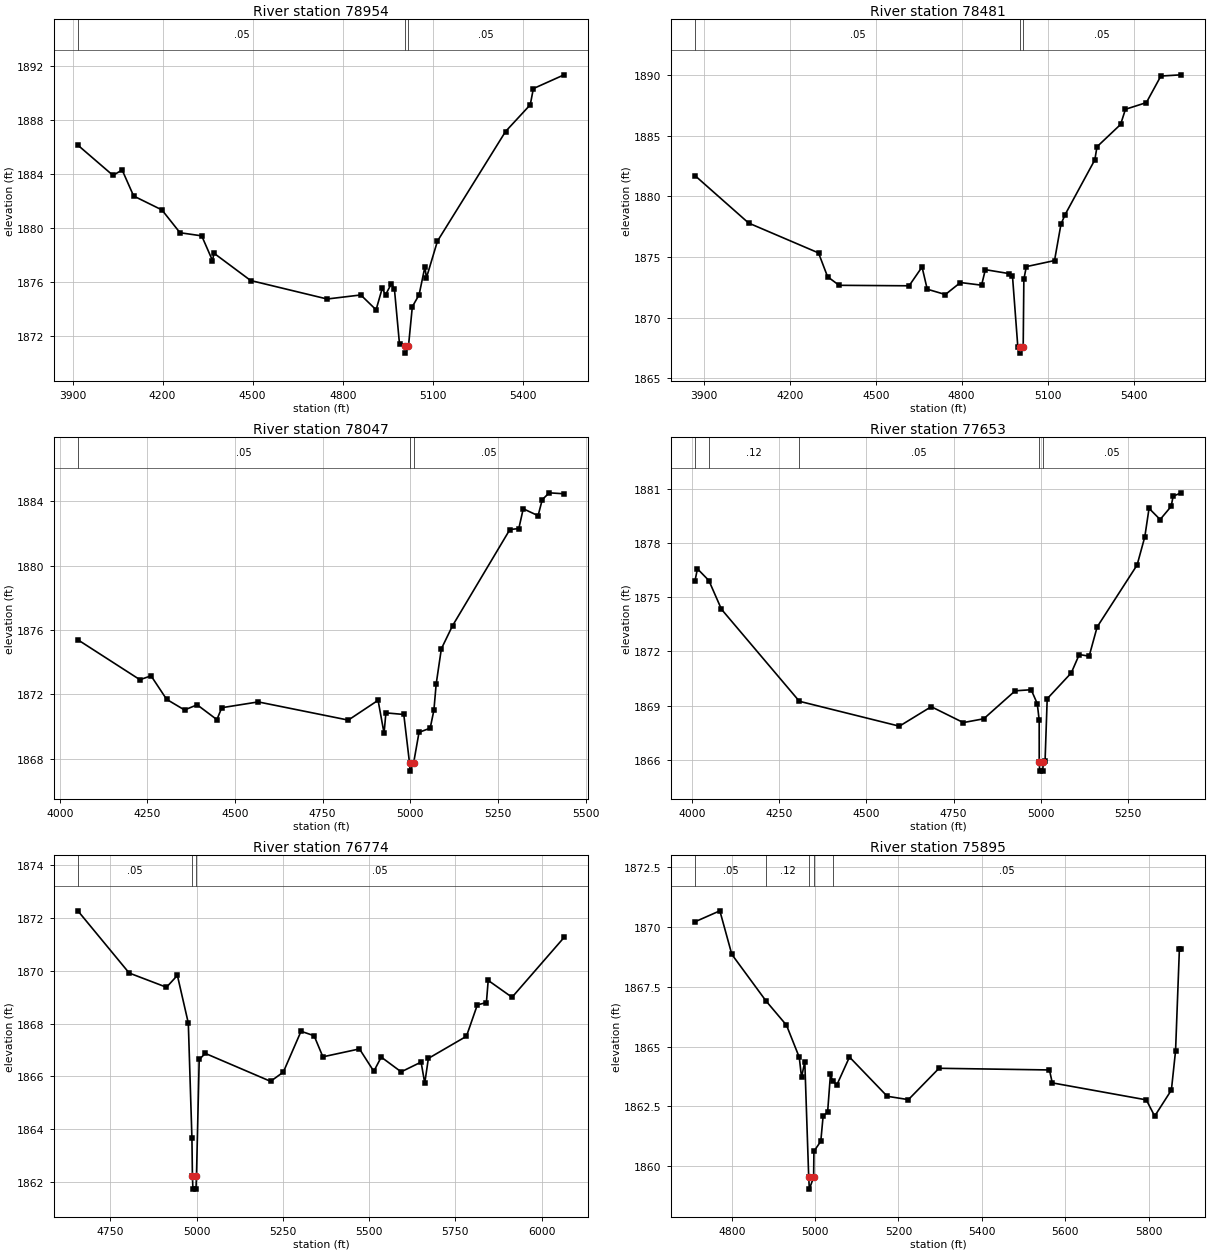
Type RM Length L Ch R = 1 ,78954   ,473,473,473
BEGIN DESCRIPTION:
Lytle Creek 79445.51
END DESCRIPTION:
XS GIS Cut Line= 3
      1617753.75      6796583.22      1617962.08      6797646.56
      1618087.95      6798167.41
#Sta/Elev= 30
  3917.7 1886.17  4034.7 1883.93  4065.2 1884.33  4103.6  1882.4  4197.7 1881.37
    4258 1879.68  4330.2 1879.45  4366.1 1877.62  4371.2 1878.16  4493.2 1876.14
    4748 1874.77  4860.1 1875.07    4911 1873.97  4931.4 1875.56  4942.6 1875.08
    4962 1875.91  4972.2 1875.48    4989 1871.43  5007.2 1871.26  5008.7 1870.76
  5018.8 1871.26  5031.7  1874.2  5054.2 1875.08  5073.6 1877.15  5078.7 1876.34
  5115.4 1879.06  5342.2 1887.18  5424.5 1889.16  5434.8 1890.36  5537.1 1891.38
#Mann= 3 ,-1 , 0
  3917.7     .05       0  5007.2     .03       0  5018.8     .05       0
Bank Sta=5007.2,5018.8
XS Rating Curve= 0 ,0
Exp/Cntr=0.3,0.1

Type RM Length L Ch R = 1 ,78481   ,434,434,434
BEGIN DESCRIPTION:
Lytle Creek 78950.19
END DESCRIPTION:
XS GIS Cut Line= 3
      1617169.21      6796758.58      1617537.25      6797859.23
      1617773.34      6798341.83
#Sta/Elev= 30
  3868.4 1881.72  4056.2  1877.8  4300.1 1875.34  4331.7 1873.38    4372 1872.67
  4616.4 1872.63  4661.6 1874.18  4679.7 1872.35    4743 1871.91  4795.7  1872.9
  4869.5 1872.68  4882.6 1873.96  4964.4 1873.64  4977.4 1873.43    4996 1867.61
  5003.2 1867.58  5004.7 1867.08  5014.8 1867.58  5017.1 1873.16  5025.7 1874.21
  5124.2 1874.71  5146.7 1877.71  5161.2  1878.5  5264.9 1883.01  5272.5 1884.09
  5354.9 1885.93  5371.8 1887.18  5444.9 1887.73  5495.5 1889.92  5566.2 1890.02
#Mann= 3 ,-1 , 0
  3868.4     .05       0  5003.2     .05       0  5014.8     .05       0
Bank Sta=5003.2,5014.8
XS Rating Curve= 0 ,0
Exp/Cntr=0.3,0.1

Type RM Length L Ch R = 1 ,78047   ,394,394,394
BEGIN DESCRIPTION:
Lytle Creek 78421.47
END DESCRIPTION:
XS GIS Cut Line= 2
        1616826.      6797141.27      1617292.28      6798447.75
#Sta/Elev= 30
  4051.6 1875.39  4228.6 1872.91  4260.5 1873.15  4304.9 1871.69  4355.9 1871.03
    4392 1871.35  4448.3 1870.43  4462.2 1871.17  4566.2 1871.53  4823.2  1870.4
  4908.2 1871.63  4925.2 1869.58  4930.5 1870.85  4981.5 1870.75  4997.9 1867.73
  4999.4 1867.23  5009.5 1867.73    5025 1869.64  5056.8  1869.9  5067.4 1871.01
  5073.9 1872.64  5088.7 1874.83  5120.5 1876.26  5284.2 1882.24  5309.7  1882.3
  5322.3 1883.53  5364.7  1883.1  5376.6  1884.1  5396.6 1884.52  5438.8 1884.46
#Mann= 3 ,-1 , 0
  4051.6     .05       0  4997.9     .03       0  5009.5     .05       0
Bank Sta=4997.9,5009.5
XS Rating Curve= 0 ,0
Exp/Cntr=0.3,0.1

Type RM Length L Ch R = 1 ,77653   ,879,879,879
BEGIN DESCRIPTION:
Lytle Creek 77441.34
END DESCRIPTION:
XS GIS Cut Line= 2
      1616397.77      6797314.67      1616980.14      6798582.73
#Sta/Elev= 30
  4007.6 1875.89  4014.9 1876.58  4047.7 1875.93  4083.8 1874.34  4307.4 1869.24
  4594.5 1867.86  4685.9 1868.94  4777.9 1868.06  4836.6 1868.27  4926.8 1869.82
  4972.7 1869.88  4990.2 1869.11  4995.7 1868.19  4995.8 1865.87  4997.3 1865.37
  5005.9 1865.37  5007.4 1865.87  5012.6 1865.95  5018.7 1869.38  5087.7 1870.81
  5110.7 1871.83  5139.1 1871.74  5162.1 1873.36  5276.7 1876.79  5298.8 1878.35
    5311 1879.93  5342.8 1879.31  5374.5 1880.04    5380  1880.6    5403 1880.79
#Mann= 5 ,-1 , 0
  4007.6     .05       0  4047.7     .12       0  4307.4     .05       0
  4995.8     .05       0  5007.4     .05       0
Bank Sta=4995.8,5007.4
XS Rating Curve= 0 ,0
Exp/Cntr=0.3,0.1

Type RM Length L Ch R = 1 ,76774   ,879,879,879
BEGIN DESCRIPTION:
Lytle Creek 77240.61
END DESCRIPTION:
XS GIS Cut Line= 2
      1616161.89      6797594.32      1616610.08      6798931.09
#Sta/Elev= 30
  4655.4 1872.28  4804.2 1869.92  4912.4 1869.38    4944 1869.83  4975.7 1868.02
  4986.2 1863.65  4987.6 1862.22  4989.1 1861.72  4997.9 1861.72  4999.4 1862.22
  5007.3 1866.64    5025 1866.87  5214.3 1865.81  5251.2 1866.16  5302.6 1867.71
  5340.5 1867.54  5365.9 1866.74    5472 1867.04  5513.6 1866.19  5535.1 1866.73
  5592.9 1866.17  5650.7 1866.54  5661.3 1865.74  5671.8 1866.68  5782.2 1867.52
  5813.8 1868.71  5840.1  1868.8  5845.3 1869.64  5914.4    1869  6065.3 1871.27
#Mann= 3 ,-1 , 0
  4655.4     .05       0  4987.6     .05       0  4999.4     .05       0
Bank Sta=4987.6,4999.4
XS Rating Curve= 0 ,0
Exp/Cntr=0.3,0.1

Type RM Length L Ch R = 1 ,75895   ,659,659,659
BEGIN DESCRIPTION:
Lytle Creek 76311.12
END DESCRIPTION:
XS GIS Cut Line= 4
      1615645.63      6797987.71      1615788.02      6798303.04
      1616085.88      6798923.11      1616218.29      6798932.06
#Sta/Elev= 30
  4711.6 1870.21  4771.5 1870.67  4800.2 1868.85  4882.4  1866.9  4931.4 1865.89
    4962 1864.55  4967.5 1863.71  4975.3 1864.37  4984.7 1859.54  4986.2 1859.04
  4996.5 1859.54  4997.2 1860.62  5013.7 1861.04  5019.2 1862.08  5030.1 1862.27
  5036.9 1863.84  5041.9 1863.57  5052.1 1863.39  5082.5 1864.56  5173.1 1862.92
  5223.9 1862.78  5297.4 1864.09  5562.3 1864.02  5569.1 1863.48  5794.7 1862.77
  5814.8 1862.09  5854.9 1863.18  5864.9 1864.82  5874.1 1869.07  5878.2 1869.07
#Mann= 5 ,-1 , 0
  4711.6     .05       0  4882.4     .12       0  4984.7     .07       0
  4996.5     .12       0  5041.9     .05       0
Bank Sta=4984.7,4996.5
XS Rating Curve= 0 ,0
Exp/Cntr=0.3,0.1

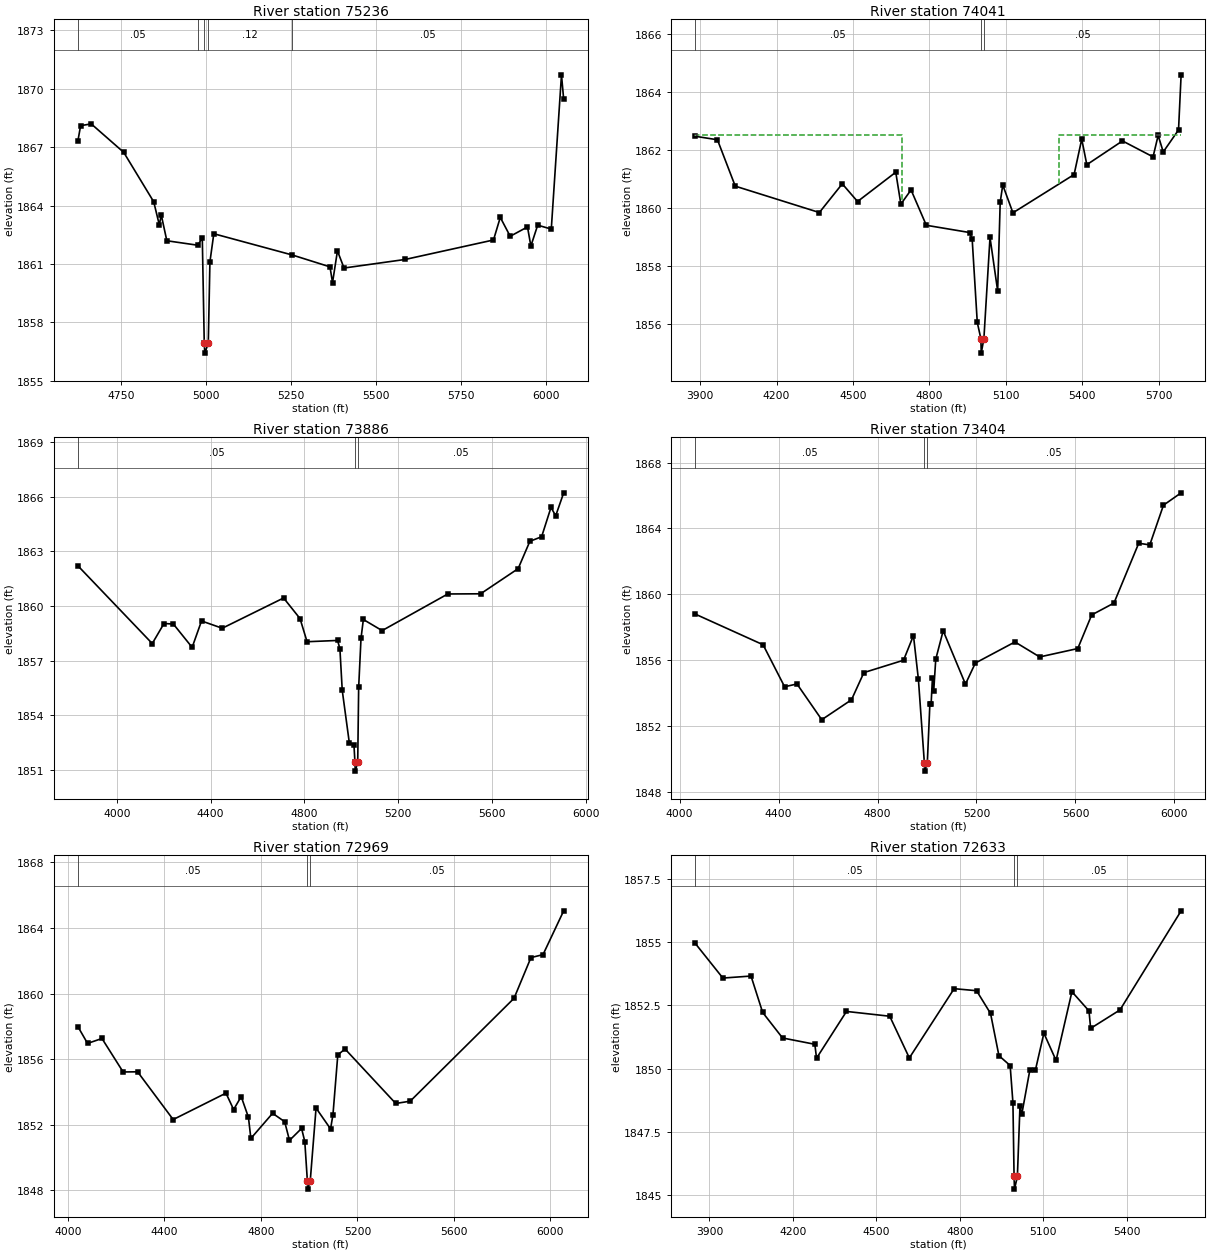
Type RM Length L Ch R = 1 ,75236   ,1195,1195,1195
BEGIN DESCRIPTION:
Lytle Creek 75787.47
END DESCRIPTION:
XS GIS Cut Line= 4
      1615207.63      6798272.98      1615565.79      6798959.93
      1616020.18      6798965.38       1616221.5      6798955.46
#Sta/Elev= 30
    4622  1867.3  4630.2  1868.1  4661.5 1868.19  4757.1 1866.73  4845.5 1864.19
    4862    1863  4867.6 1863.52  4884.1 1862.19  4975.3 1861.96  4988.5 1862.34
  4994.3 1856.92  4995.8 1856.42  5006.1 1856.92    5011 1861.11  5022.4 1862.55
  5253.3 1861.46  5364.5 1860.85    5372 1860.04  5386.5 1861.67  5405.9 1860.79
  5585.9 1861.23    5846 1862.23    5866 1863.39  5895.2 1862.42  5946.1  1862.9
  5956.1 1861.92  5976.1 1862.99  6016.2 1862.79  6046.2 1870.71  6052.7 1869.45
#Mann= 5 ,-1 , 0
    4622     .05       0  4975.3     .12       0  4994.3     .07       0
  5006.1     .12       0  5253.3     .05       0
Bank Sta=4994.3,5006.1
XS Rating Curve= 0 ,0
Exp/Cntr=0.3,0.1

Type RM Length L Ch R = 1 ,74041   ,155,155,155
BEGIN DESCRIPTION:
Lytle Creek 74996.12
END DESCRIPTION:
XS GIS Cut Line= 4
        1614298.      6799031.63      1615331.17      6799014.75
      1615554.08       6799014.2       1616205.2      6799005.25
#Sta/Elev= 30
  3880.7 1862.47  3967.7 1862.35  4037.7 1860.75  4367.8 1859.84  4457.8 1860.83
  4517.8 1860.22  4667.8 1861.23  4687.8 1860.13  4727.8 1860.62  4787.8  1859.4
  4957.8 1859.15  4967.8 1858.92  4987.8 1856.05  5001.9 1855.49  5003.4 1854.99
  5013.8 1855.49  5037.8 1858.98  5067.8 1857.14  5077.8 1860.19  5087.8 1860.79
  5127.8 1859.83  5367.9 1861.15  5397.9 1862.37  5417.9 1861.49  5557.9 1862.31
  5677.9 1861.76  5697.9  1862.5  5717.9 1861.93  5777.9 1862.69  5788.1 1864.59
#Mann= 3 ,-1 , 0
  3880.7     .05       0  5001.9     .05       0  5013.8     .05       0
#XS Ineff= 2 , 0
       0    4693 1862.52    5307       0 1862.52
Permanent Ineff=
       F       F
Bank Sta=5001.9,5013.8
XS Rating Curve= 0 ,0
Exp/Cntr=0.3,0.1

Type RM Length L Ch R = 1 ,73886   ,482,482,482
BEGIN DESCRIPTION:
Lytle Creek 74566.15
END DESCRIPTION:
XS GIS Cut Line= 3
      1614297.68      6799151.64      1615525.14      6799134.52
      1616369.15      6799139.21
#Sta/Elev= 30
  3833.6 1862.21  4150.9 1857.94    4201 1859.04    4241 1859.01    4321 1857.73
    4361 1859.18  4449.4 1858.78    4711 1860.44    4781 1859.31    4811 1858.04
    4941 1858.11    4951 1857.66    4961 1855.37    4991 1852.51    5011 1852.36
  5015.1 1851.44  5016.6 1850.94    5027 1851.44    5031 1855.53    5041 1858.22
    5051 1859.26    5131 1858.65    5411 1860.66    5551 1860.67    5711 1862.05
    5761 1863.55  5811.1  1863.8  5851.1 1865.41  5871.1 1864.95  5905.2 1866.21
#Mann= 3 ,-1 , 0
  3833.6     .05       0  5015.1     .05       0    5027     .05       0
Bank Sta=5015.1,5027
XS Rating Curve= 0 ,0
Exp/Cntr=0.3,0.1

Type RM Length L Ch R = 1 ,73404   ,435,435,435
BEGIN DESCRIPTION:
Lytle Creek 74091.63
END DESCRIPTION:
XS GIS Cut Line= 3
      1614254.54      6799548.93      1615202.47      6799493.38
      1616216.32      6799458.65
#Sta/Elev= 30
  4063.2  1858.8  4337.3 1856.94  4424.3 1854.39  4474.4 1854.56  4574.5 1852.39
  4694.7  1853.6  4744.8 1855.25  4905.1    1856  4945.2  1857.5  4965.2 1854.84
  4989.3 1849.77  4990.8 1849.27  5001.2 1849.77  5011.5 1853.32  5016.5 1853.32
    5022 1854.95    5027 1854.12  5035.3 1856.06  5065.3 1857.79  5155.4 1854.55
  5195.4 1855.83  5355.5 1857.11  5455.5  1856.2  5609.4 1856.71  5665.7 1858.75
  5755.7 1859.47  5855.8  1863.1  5900.5    1863  5955.8 1865.41  6027.2 1866.16
#Mann= 3 ,-1 , 0
  4063.2     .05       0  4989.3     .05       0  5001.2     .05       0
Bank Sta=4989.3,5001.2
XS Rating Curve= 0 ,0
Exp/Cntr=0.3,0.1

Type RM Length L Ch R = 1 ,72969   ,336,336,336
BEGIN DESCRIPTION:
Lytle Creek 73642.97
END DESCRIPTION:
XS GIS Cut Line= 4
      1614237.03      6799612.51      1614815.28      6799925.26
       1615098.3      6799913.51      1616170.62      6799955.16
#Sta/Elev= 30
    4041 1857.99  4081.3 1856.96    4141 1857.26  4228.7 1855.22  4288.7 1855.23
  4436.2 1852.32    4655 1853.93  4686.7 1852.93  4718.1 1853.72  4748.1 1852.46
  4758.2 1851.17  4848.3  1852.7  4898.3 1852.19  4918.3 1851.05  4968.4 1851.78
  4981.7 1850.98  4992.4 1848.58  4993.9 1848.08  5004.3 1848.58  5028.4 1853.02
  5088.5 1851.75  5098.5 1852.62  5118.5 1856.26  5148.5 1856.62  5358.7  1853.3
  5418.7 1853.44    5849 1859.71  5919.1 1862.19  5969.1 1862.37  6054.8 1865.04
#Mann= 3 ,-1 , 0
    4041     .05       0  4992.4     .05       0  5004.3     .05       0
Bank Sta=4992.4,5004.3
XS Rating Curve= 0 ,0
Exp/Cntr=0.3,0.1

Type RM Length L Ch R = 1 ,72633   ,421,421,421
BEGIN DESCRIPTION:
Lytle Creek 73285.23
END DESCRIPTION:
XS GIS Cut Line= 4
      1614000.04      6799805.21      1614513.08       6800164.6
      1615053.07      6800223.29       1615621.9      6800314.14
#Sta/Elev= 30
  3849.1 1854.95  3948.3 1853.58  4049.4 1853.66  4091.2 1852.22  4162.7 1851.21
  4278.7 1850.96  4284.8 1850.41  4392.4 1852.26  4547.8 1852.07  4618.2 1850.42
  4779.2 1853.16  4859.7 1853.08    4910 1852.18  4940.1 1850.51  4980.4 1850.12
  4990.4 1848.65  4994.5 1845.73    4996 1845.23  5006.4 1845.73  5015.7 1848.52
  5022.2 1848.19    5051 1849.93  5071.2 1849.94  5101.6  1851.4  5145.4 1850.32
  5202.4 1853.04  5263.7 1852.28  5269.6 1851.59  5375.1 1852.32  5594.7 1856.24
#Mann= 3 ,-1 , 0
  3849.1     .05       0  4994.5     .05       0  5006.4     .05       0
Bank Sta=4994.5,5006.4
XS Rating Curve= 0 ,0
Exp/Cntr=0.3,0.1

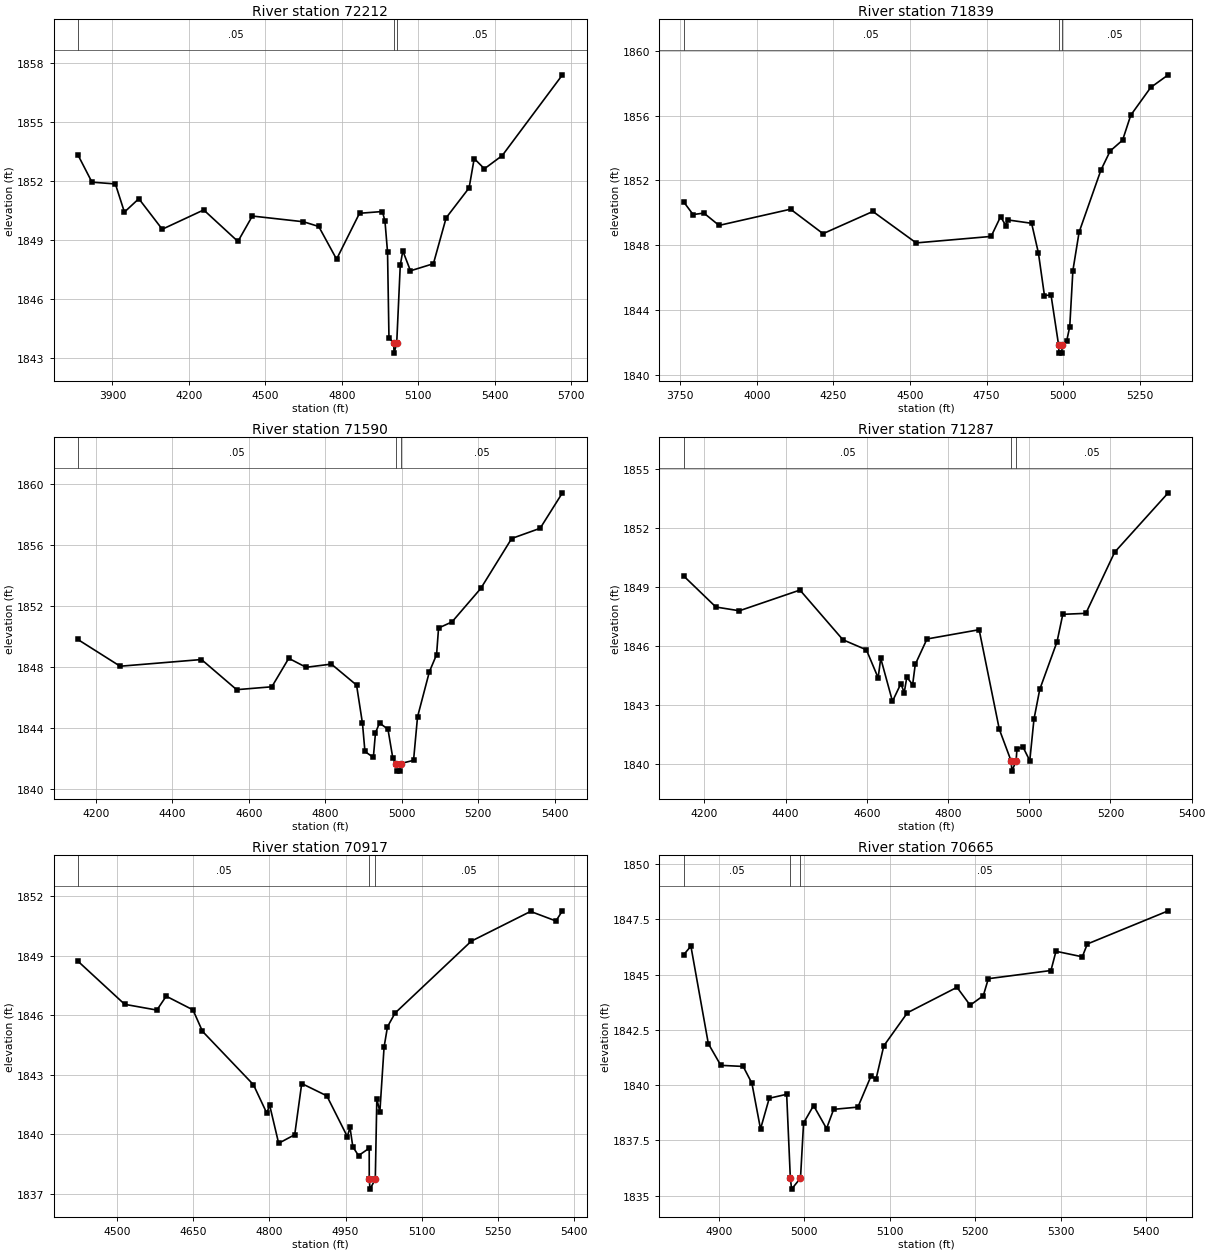
Type RM Length L Ch R = 1 ,72212   ,373,373,373
BEGIN DESCRIPTION:
Lytle Creek 72915.39
END DESCRIPTION:
XS GIS Cut Line= 4
      1613908.89      6799995.31      1614453.08      6800545.17
      1614901.16      6800535.79      1615581.33       6800529.3
#Sta/Elev= 30
  3764.1 1853.35  3819.8 1851.95  3911.7 1851.86  3947.1 1850.43  4003.7 1851.11
  4095.6 1849.56  4258.3 1850.54  4392.6 1848.94  4449.1 1850.23  4649.7 1849.94
  4709.7  1849.7  4779.7 1848.04  4869.7 1850.37  4959.7 1850.46  4969.7 1849.96
  4979.7  1848.4  4985.3 1844.05  5003.8 1843.77  5005.3 1843.27  5015.7 1843.77
  5029.7 1847.74  5039.7 1848.46  5069.7 1847.45  5159.7 1847.81  5209.7 1850.14
  5299.8 1851.66  5319.8 1853.15  5359.8 1852.63  5429.8  1853.3  5666.1  1857.4
#Mann= 3 ,-1 , 0
  3764.1     .05       0  5003.8     .05       0  5015.7     .05       0
Bank Sta=5003.8,5015.7
XS Rating Curve= 0 ,0
Exp/Cntr=0.3,0.1

Type RM Length L Ch R = 1 ,71839   ,249,249,249
BEGIN DESCRIPTION:
Lytle Creek 72537.93
END DESCRIPTION:
XS GIS Cut Line= 4
      1613929.75      6800219.28      1614493.79      6800782.59
      1614909.84      6800883.02      1615261.83      6800943.48
#Sta/Elev= 30
  3760.9 1850.68    3792 1849.89  3827.3 1849.98  3876.8 1849.22  4110.2 1850.22
  4216.3 1848.71  4378.9 1850.08  4520.3 1848.14    4765 1848.54  4795.9 1849.76
  4813.4 1849.19  4818.6 1849.56  4897.2 1849.35  4919.4 1847.52  4939.1 1844.89
  4960.5 1844.93  4985.3 1841.84  4986.8 1841.34  4995.7 1841.34  4997.2 1841.84
  5011.6 1842.09  5021.7 1842.97  5031.9 1846.43  5052.2  1848.8  5123.2 1852.62
  5153.6 1853.81  5194.2 1854.48  5220.9 1856.02    5286 1857.73  5343.2 1858.51
#Mann= 3 ,-1 , 0
  3760.9     .05       0  4985.3     .05       0  4997.2     .05       0
Bank Sta=4985.3,4997.2
XS Rating Curve= 0 ,0
Exp/Cntr=0.3,0.1

Type RM Length L Ch R = 1 ,71590   ,303,303,303
BEGIN DESCRIPTION:
Lytle Creek 72285.29
END DESCRIPTION:
XS GIS Cut Line= 4
      1614117.22      6800599.47      1614512.28      6800946.47
      1614799.16      6801100.03      1615201.42        6801206.
#Sta/Elev= 30
  4152.7 1849.81  4263.5 1848.05  4476.1 1848.49  4568.1 1846.51  4660.1  1846.7
  4704.3 1848.57  4749.7 1847.98  4815.8 1848.19  4881.6 1846.81  4897.1 1844.29
  4903.5 1842.45  4925.5 1842.06  4931.1 1843.69  4941.7 1844.32  4963.7 1843.91
  4976.5    1842  4985.3 1841.66  4986.8 1841.16  4995.7 1841.16  4997.2 1841.66
  5030.6 1841.87    5041 1844.72    5072 1847.69  5090.8 1848.81    5096 1850.56
  5131.1 1850.96  5206.4 1853.16  5287.2 1856.44  5361.6 1857.11  5419.9 1859.44
#Mann= 3 ,-1 , 0
  4152.7     .05       0  4985.3     .05       0  4997.2     .05       0
Bank Sta=4985.3,4997.2
XS Rating Curve= 0 ,0
Exp/Cntr=0.3,0.1

Type RM Length L Ch R = 1 ,71287   ,370,370,370
BEGIN DESCRIPTION:
Lytle Creek 71964.43
END DESCRIPTION:
XS GIS Cut Line= 3
      1614031.28      6800609.87      1614557.26      6801280.77
      1614785.89      6801533.64
#Sta/Elev= 30
  4148.9 1849.56  4228.5 1847.98  4286.3 1847.79  4435.5 1848.84  4541.3 1846.32
  4599.1 1845.81    4628 1844.39  4634.4 1845.38  4663.3  1843.2  4684.1  1844.1
  4692.2 1843.63  4698.6 1844.42    4713 1844.05  4719.4 1845.07  4748.3 1846.36
  4876.7 1846.83  4926.4 1841.78  4955.7 1840.16  4957.2 1839.66  4967.6 1840.16
  4969.8 1840.77  4984.2  1840.9  5001.4 1840.19  5011.7 1842.29  5025.9  1843.8
  5068.5 1846.22  5082.7 1847.61  5139.5 1847.66  5210.4 1850.76  5342.3 1853.77
#Mann= 3 ,-1 , 0
  4148.9     .05       0  4955.7     .05       0  4967.6     .05       0
Bank Sta=4955.7,4967.6
XS Rating Curve= 0 ,0
Exp/Cntr=0.3,0.1

Type RM Length L Ch R = 1 ,70917   ,252,252,252
BEGIN DESCRIPTION:
Lytle Creek 71572.9
END DESCRIPTION:
XS GIS Cut Line= 3
      1614041.71       6800872.9      1614213.51      6801390.14
      1614442.65      6801728.65
#Sta/Elev= 30
    4423 1848.73  4515.3 1846.55  4578.7 1846.26    4597 1846.96  4649.7 1846.27
  4668.4 1845.19  4768.7  1842.5  4795.1 1841.06  4800.4 1841.49  4818.3 1839.55
  4849.9 1839.98  4863.7 1842.56  4913.1 1841.94  4953.4 1839.89  4958.7 1840.35
  4964.3 1839.37  4975.5 1838.93  4996.5  1839.3  4996.6 1837.74  4998.1 1837.24
  5008.5 1837.74  5011.5 1841.79  5017.5 1841.14  5025.8  1844.4  5032.5 1845.42
  5047.4 1846.11  5197.3 1849.73  5314.1 1851.23  5363.9 1850.75  5376.8 1851.26
#Mann= 3 ,-1 , 0
    4423     .05       0  4996.6     .05       0  5008.5     .05       0
Bank Sta=4996.6,5008.5
XS Rating Curve= 0 ,0
Exp/Cntr=0.3,0.1

Type RM Length L Ch R = 1 ,70665   ,254,254,254
BEGIN DESCRIPTION:
Lytle Creek 71348.67
END DESCRIPTION:
XS GIS Cut Line= 3
      1613961.77      6801249.52      1613989.55      6801391.88
      1614210.91      6801751.58
#Sta/Elev= 30
  4858.7  1845.9  4867.3 1846.29  4887.7 1841.88  4902.3  1840.9  4928.5 1840.85
  4938.7 1840.09  4948.8 1838.02    4959 1839.41  4979.4 1839.59  4983.7  1835.8
  4985.2  1835.3  4995.6  1835.8  4999.2 1838.29  5010.9 1839.08  5026.1 1838.04
  5034.4 1838.91  5062.8 1839.01  5078.2 1840.42  5084.1 1840.29  5093.1 1841.78
  5120.8 1843.28  5178.8 1844.43  5194.2 1843.62  5209.6 1844.05  5215.5 1844.82
  5288.8 1845.19  5294.7 1846.06  5325.5 1845.81  5331.4 1846.39  5426.1 1847.89
#Mann= 3 ,-1 , 0
  4858.7     .05       0  4983.7     .05       0  4995.6     .05       0
Bank Sta=4983.7,4995.6
XS Rating Curve= 0 ,0
Exp/Cntr=0.3,0.1

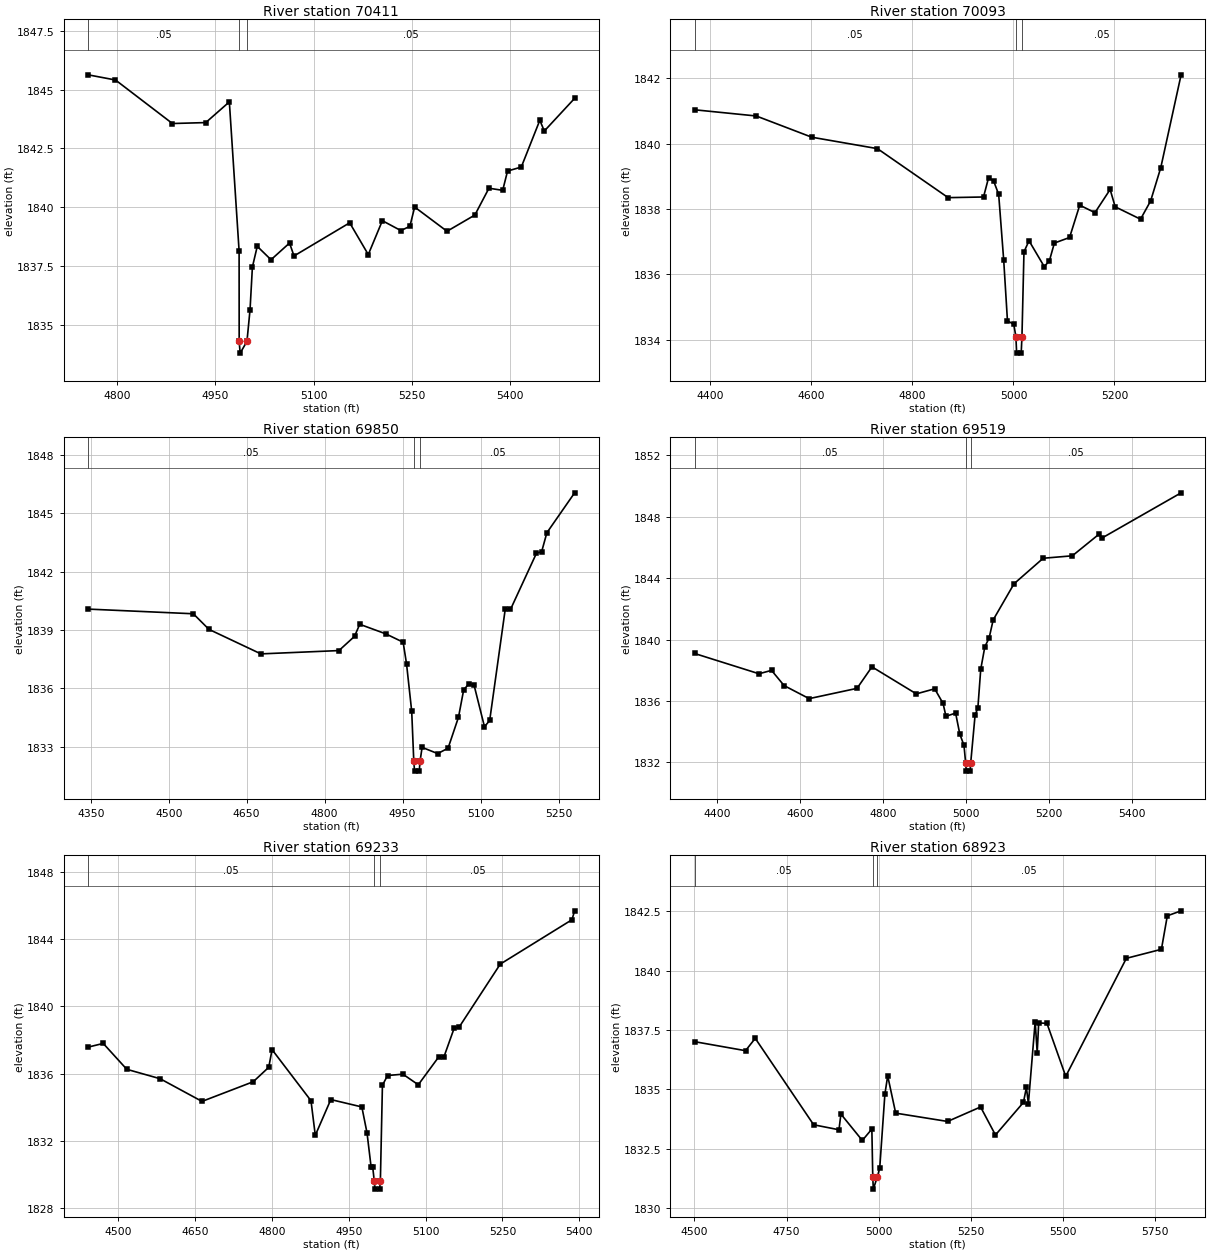
Type RM Length L Ch R = 1 ,70411   ,318,318,318
BEGIN DESCRIPTION:
Lytle Creek 71103.1
END DESCRIPTION:
XS GIS Cut Line= 3
      1613607.59      6801186.98      1613744.76      6801390.14
      1614109.37      6801728.71
#Sta/Elev= 30
  4755.8 1845.63  4797.6 1845.41  4884.5 1843.56  4935.4  1843.6  4971.4 1844.48
  4986.3 1838.14  4986.4  1834.3  4987.9  1833.8  4998.3  1834.3    5003 1835.65
  5006.6 1837.46    5014 1838.34    5035 1837.77  5063.3 1838.48  5070.1 1837.93
  5155.1 1839.34  5183.5 1837.99    5205 1839.43  5233.2 1839.01    5247 1839.19
  5254.3 1840.01  5303.7 1838.98  5346.2 1839.67  5367.7 1840.81  5388.7 1840.72
  5396.1 1841.54  5417.1 1841.71  5445.4  1843.7  5452.2 1843.24  5498.5 1844.63
#Mann= 3 ,-1 , 0
  4755.8     .05       0  4986.4     .05       0  4998.3     .05       0
Bank Sta=4986.4,4998.3
XS Rating Curve= 0 ,0
Exp/Cntr=0.3,0.1

Type RM Length L Ch R = 1 ,70093   ,243,243,243
BEGIN DESCRIPTION:
Lytle Creek 70752.22
END DESCRIPTION:
XS GIS Cut Line= 3
      1613082.91      6801667.64      1613704.83      6801667.92
      1614045.08       6801695.7
#Sta/Elev= 30
  4368.6 1841.04  4490.7 1840.85  4600.7  1840.2  4730.7 1839.85  4870.7 1838.35
  4940.7 1838.37  4950.7 1838.96  4960.7 1838.86  4970.7 1838.45  4980.7 1836.43
  4988.1 1834.58  5000.7 1834.47  5004.8 1834.09  5006.3 1833.59  5015.3 1833.59
  5016.8 1834.09  5020.8 1836.69  5030.8 1837.03  5060.9 1836.24    5071 1836.41
    5081 1836.96  5111.1 1837.13  5131.2 1838.12  5161.3 1837.89  5191.4  1838.6
  5201.4 1838.07  5251.6 1837.69  5271.6 1838.25  5291.7 1839.27  5331.9 1842.11
#Mann= 3 ,-1 , 0
  4368.6     .05       0  5004.8     .05       0  5016.8     .05       0
Bank Sta=5004.8,5016.8
XS Rating Curve= 0 ,0
Exp/Cntr=0.3,0.1

Type RM Length L Ch R = 1 ,69850   ,331,331,331
BEGIN DESCRIPTION:
Lytle Creek 70535.33
END DESCRIPTION:
XS GIS Cut Line= 3
      1613232.66      6801832.57      1613838.51      6801818.96
       1614168.4       6801820.7
#Sta/Elev= 30
    4345 1840.07  4547.4 1839.83  4577.4 1839.03  4677.4 1837.77  4827.5 1837.94
  4857.5 1838.67  4867.5 1839.29  4917.5  1838.8    4951 1838.37  4957.5 1837.27
  4967.5 1834.82  4971.5 1832.25    4973 1831.75    4982 1831.75  4983.5 1832.25
  4987.5 1832.97  5017.5 1832.65  5037.5 1832.93  5057.5 1834.52  5067.5 1835.93
  5077.5 1836.23  5087.5 1836.16  5107.5 1834.03  5117.5 1834.35  5147.5 1840.08
  5157.5 1840.05  5207.5 1842.94  5217.5 1843.02  5227.5 1843.99  5280.9 1846.04
#Mann= 3 ,-1 , 0
    4345     .05       0  4971.5     .05       0  4983.5     .05       0
Bank Sta=4971.5,4983.5
XS Rating Curve= 0 ,0
Exp/Cntr=0.3,0.1

Type RM Length L Ch R = 1 ,69519   ,286,286,286
BEGIN DESCRIPTION:
Lytle Creek 70151.14
END DESCRIPTION:
XS GIS Cut Line= 3
      1613331.12       6801998.9      1614003.04      6802092.66
      1614496.04        6802143.
#Sta/Elev= 30
  4345.3 1839.09  4500.7 1837.77    4531 1837.99  4561.3    1837  4621.8 1836.15
  4737.3 1836.82  4773.3 1838.22  4880.4 1836.46  4924.7 1836.79  4944.9 1835.84
  4951.9    1835  4975.2 1835.21  4985.3 1833.84  4995.4 1833.11  4999.5 1831.93
    5001 1831.43    5010 1831.43  5011.5 1831.93  5022.2 1835.08  5028.9 1835.54
  5035.8 1838.06  5045.8 1839.54  5055.9 1840.08  5065.9 1841.28  5116.2 1843.63
  5186.5 1845.29  5256.9 1845.45  5322.3 1846.88  5327.3 1846.59  5519.3 1849.55
#Mann= 3 ,-1 , 0
  4345.3     .05       0  4999.5     .05       0  5011.5     .05       0
Bank Sta=4999.5,5011.5
XS Rating Curve= 0 ,0
Exp/Cntr=0.3,0.1

Type RM Length L Ch R = 1 ,69233   ,310,310,310
BEGIN DESCRIPTION:
Lytle Creek 69858.41
END DESCRIPTION:
XS GIS Cut Line= 3
      1613405.83      6802292.31      1613956.16      6802370.44
      1614350.18      6802360.02
#Sta/Elev= 30
  4440.9 1837.57  4470.4 1837.79  4516.4 1836.25  4581.5 1835.69  4663.3 1834.34
  4763.3 1835.51  4793.6 1836.37  4800.1 1837.42  4876.1 1834.38  4884.5 1832.32
  4914.8 1834.45  4975.4 1834.01  4985.5 1832.47  4993.6 1830.41  4996.7 1830.41
  4999.6 1829.62  5001.1 1829.12  5010.1 1829.12  5011.6 1829.62  5015.6  1835.3
  5025.6 1835.88  5055.6 1835.96  5085.6 1835.33  5125.6 1836.99  5135.6 1836.98
  5155.6 1838.69  5165.6 1838.77  5245.7 1842.51  5385.7 1845.15  5390.9 1845.68
#Mann= 3 ,-1 , 0
  4440.9     .05       0  4999.6     .05       0  5011.6     .05       0
Bank Sta=4999.6,5011.6
XS Rating Curve= 0 ,0
Exp/Cntr=0.3,0.1

Type RM Length L Ch R = 1 ,68923   ,397,397,397
BEGIN DESCRIPTION:
Lytle Creek 69530.3
END DESCRIPTION:
XS GIS Cut Line= 4
      1613338.07       6802479.8      1613805.12      6802634.33
      1614216.58       6802806.2      1614591.63      6802883.98
#Sta/Elev= 30
  4500.4 1837.01  4638.7 1836.63  4665.1 1837.15  4823.7 1833.51  4892.4  1833.3
  4897.7 1833.96  4955.8 1832.85  4981.7 1833.33  4984.2  1831.3  4985.7  1830.8
  4996.2  1831.3  5003.1 1831.69  5017.1  1834.8  5024.7 1835.57  5046.4    1834
  5187.3 1833.65  5276.9 1834.26  5317.3 1833.08  5393.2 1834.45  5401.3 1835.08
  5406.7  1834.4  5425.1 1837.85  5430.6 1836.55  5434.7  1837.8  5457.1 1837.78
  5508.1 1835.55  5672.7 1840.52  5767.9  1840.9  5783.9 1842.31  5821.3 1842.52
#Mann= 3 ,-1 , 0
  4500.4     .05       0  4984.2     .05       0  4996.2     .05       0
Bank Sta=4984.2,4996.2
XS Rating Curve= 0 ,0
Exp/Cntr=0.3,0.1