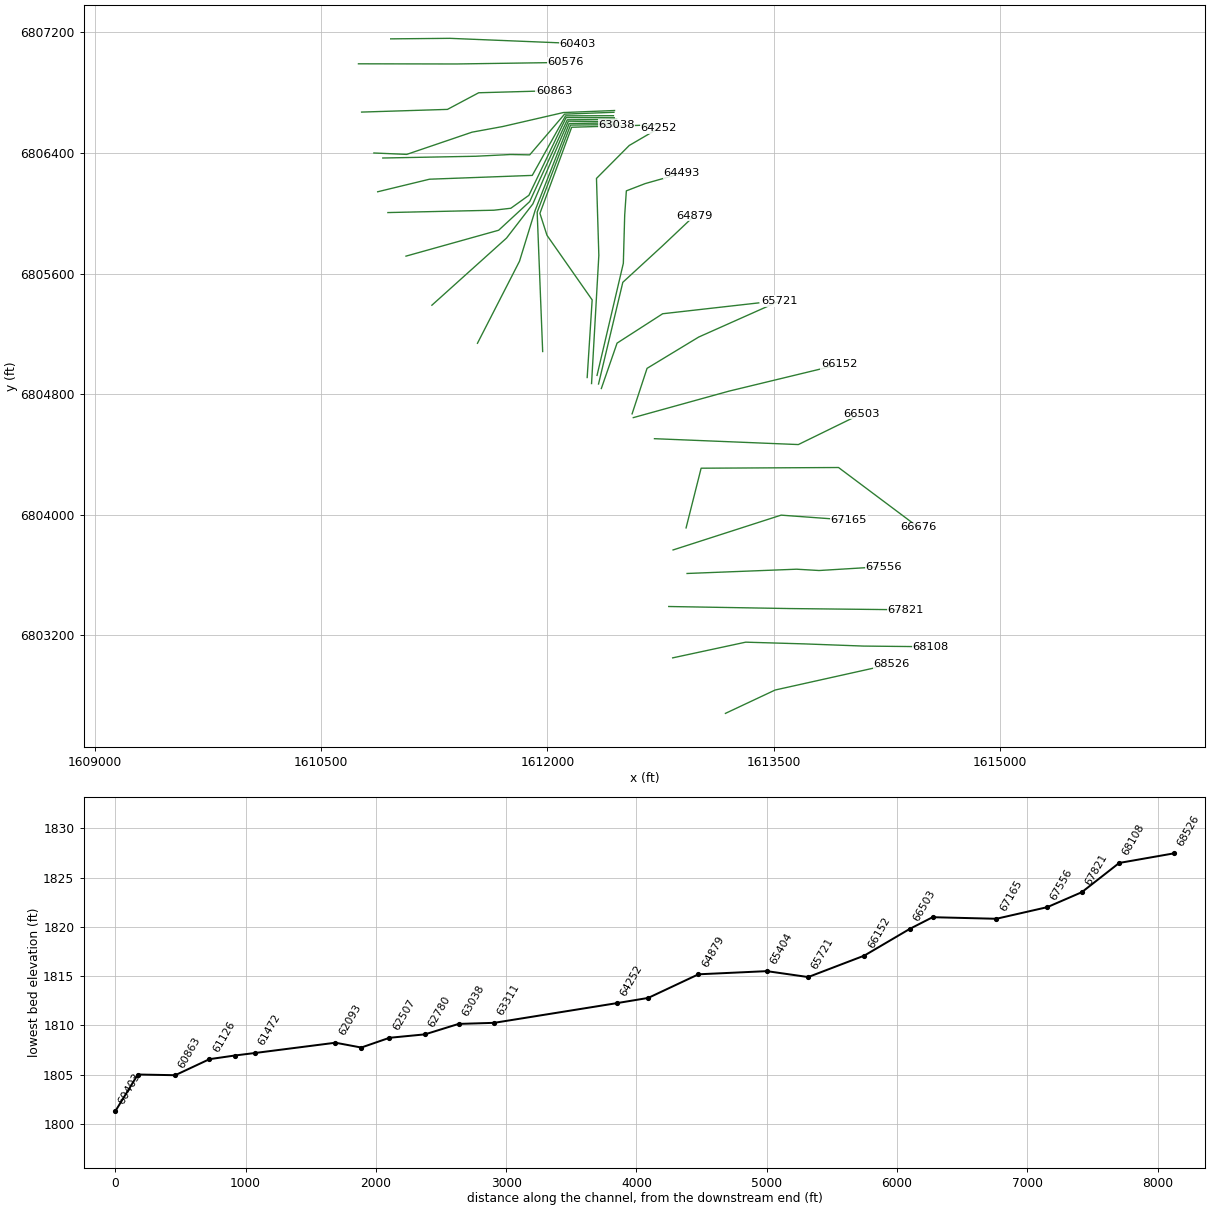
HEC-RAS study Lytle Creek.prj: Lytle Creek Base Level Engineering

--- Lytle Creek.g02 (geometry) --- (continued)

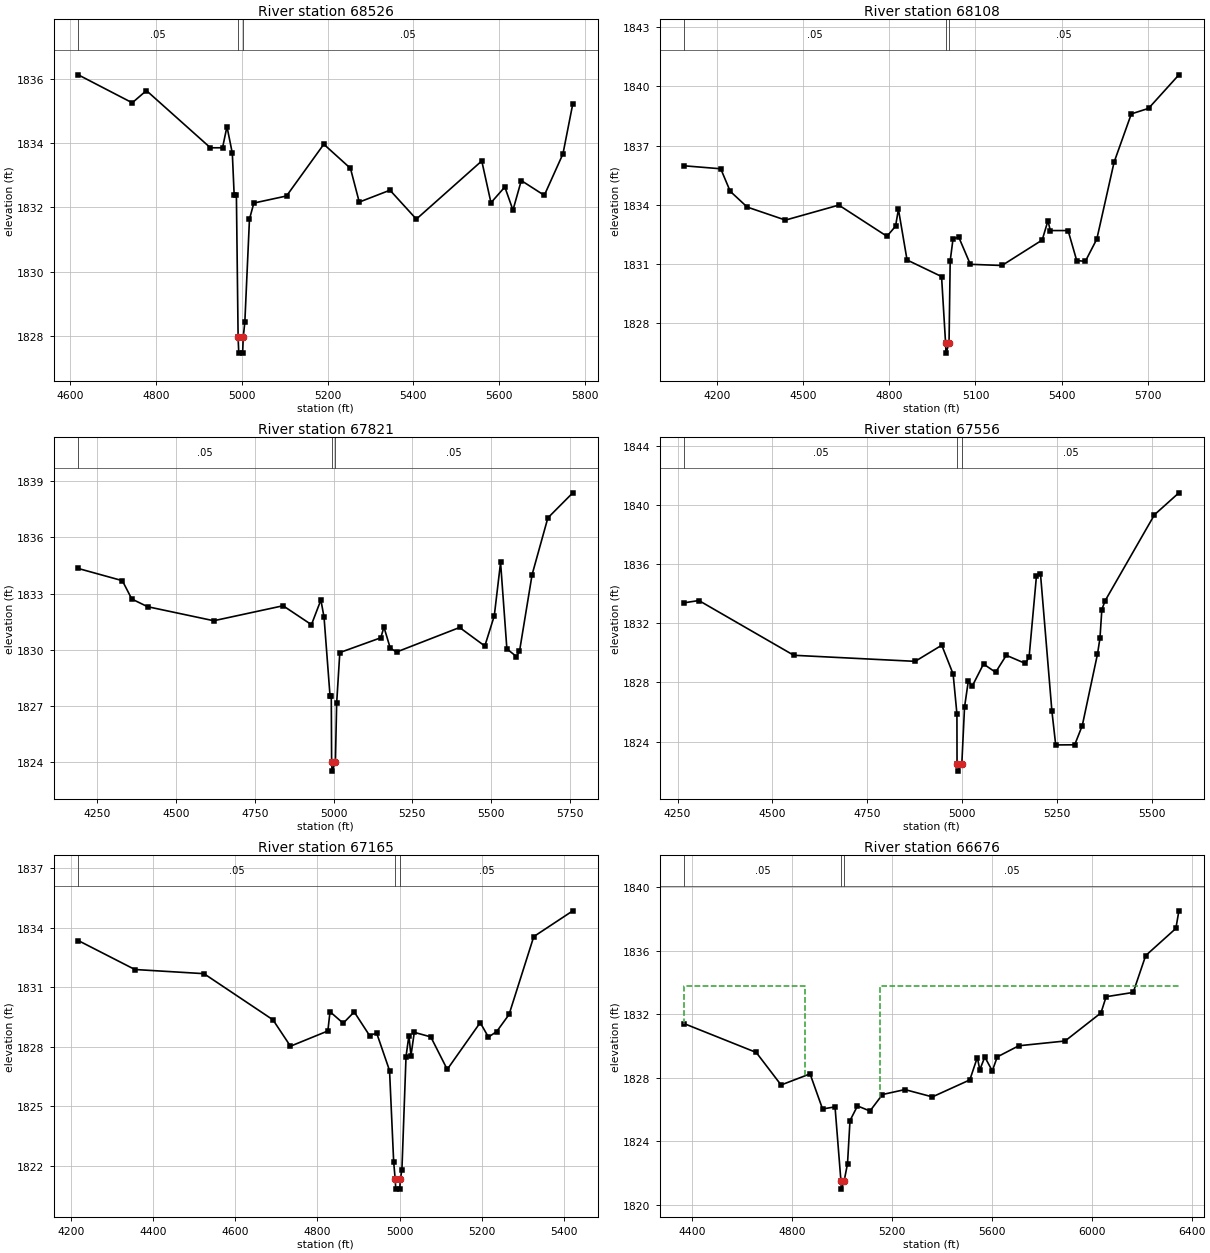
Type RM Length L Ch R = 1 ,68526   ,418,418,418
BEGIN DESCRIPTION:
Lytle Creek 69153.72
END DESCRIPTION:
XS GIS Cut Line= 3
       1613181.1      6802681.73       1613510.5      6802836.67
      1614281.31      6803008.25
#Sta/Elev= 30
  4618.4 1836.12  4744.3 1835.25  4777.4 1835.63  4926.7 1833.85    4955 1833.85
  4965.3 1834.51  4977.8 1833.68  4982.1 1832.37  4987.3 1832.37  4991.3 1827.96
  4992.8 1827.46  5001.8 1827.46  5003.3 1827.96    5007 1828.43  5017.8 1831.63
    5028 1832.13  5104.2 1832.35  5191.2 1833.96  5253.4 1833.21  5273.9 1832.16
  5345.6 1832.53  5407.1 1831.63  5559.7 1833.44  5581.2 1832.14  5613.5 1832.63
  5632.5 1831.91  5651.9 1832.83  5705.6 1832.37  5749.1 1833.66  5772.1 1835.22
#Mann= 3 ,-1 , 0
  4618.4     .05       0  4991.3     .05       0  5003.3     .05       0
Bank Sta=4991.3,5003.3
XS Rating Curve= 0 ,0
Exp/Cntr=0.3,0.1

Type RM Length L Ch R = 1 ,68108   ,287,287,287
BEGIN DESCRIPTION:
Lytle Creek 68759.64
END DESCRIPTION:
XS GIS Cut Line= 5
      1612831.26      6803050.02      1613315.16      6803154.18
      1613702.95      6803142.79      1614096.25      6803128.22
      1614540.62      6803123.81
#Sta/Elev= 30
  4087.1 1835.98  4213.7 1835.83  4246.6 1834.69  4305.7 1833.89  4438.9 1833.23
  4624.6 1833.99    4792 1832.41    4822 1832.92    4832 1833.78    4862 1831.21
  4982.1 1830.37  4996.1 1826.99  4997.6 1826.49  5008.1 1826.99  5012.1 1831.16
  5022.1 1832.29  5042.1 1832.36  5082.2 1830.99  5192.2 1830.93  5332.3 1832.22
  5352.3  1833.2  5360.5  1832.7  5422.4  1832.7  5452.4 1831.18  5482.4 1831.14
  5522.4 1832.27  5582.4 1836.16  5642.4 1838.61  5702.4 1838.89    5808 1840.59
#Mann= 3 ,-1 , 0
  4087.1     .05       0  4996.1     .05       0  5008.1     .05       0
Bank Sta=4996.1,5008.1
XS Rating Curve= 0 ,0
Exp/Cntr=0.3,0.1

Type RM Length L Ch R = 1 ,67821   ,265,265,265
BEGIN DESCRIPTION:
Lytle Creek 68487.72
END DESCRIPTION:
XS GIS Cut Line= 3
      1612805.18      6803390.73       1613607.9      6803377.16
      1614374.22      6803369.02
#Sta/Elev= 30
  4190.1 1834.34  4329.9 1833.69  4359.9 1832.71    4410  1832.3    4620 1831.55
    4840 1832.35    4930 1831.34    4960 1832.66    4970 1831.73    4989 1827.53
  4992.9 1827.53    4994 1824.02  4995.5 1823.52    5006 1824.02    5010 1827.15
    5020 1829.85    5150 1830.64    5160 1831.21    5180 1830.09    5200 1829.88
  5400.1 1831.19  5480.1  1830.2  5510.1 1831.81  5530.1 1834.66  5550.1 1830.05
  5580.1 1829.64  5590.1 1829.91  5630.1 1834.01  5680.1 1837.04  5759.3 1838.38
#Mann= 3 ,-1 , 0
  4190.1     .05       0    4994     .05       0    5006     .05       0
Bank Sta=4994,5006
XS Rating Curve= 0 ,0
Exp/Cntr=0.3,0.1

Type RM Length L Ch R = 1 ,67556   ,391,391,391
BEGIN DESCRIPTION:
Lytle Creek 68211.11
END DESCRIPTION:
XS GIS Cut Line= 4
      1612926.72      6803609.91      1613653.12      6803638.28
      1613802.37      6803629.57      1614229.33      6803655.56
#Sta/Elev= 30
    4268 1833.38  4306.3 1833.53  4556.5 1829.83  4876.7 1829.42  4946.8 1830.51
  4976.8 1828.56  4986.8 1825.87  4987.1  1822.5  4988.6    1822  4999.7  1822.5
  5006.9 1826.33  5016.9  1828.1  5026.9 1827.73  5056.9 1829.24  5088.8 1828.68
    5117 1829.83  5167.1 1829.28  5177.1  1829.7  5196.5 1835.18  5207.2 1835.32
  5237.3 1826.05  5247.3 1823.77  5297.4 1823.78  5317.4 1825.08  5357.5 1829.91
    5364 1830.98    5369 1832.92  5377.5 1833.51  5507.8 1839.33  5572.2 1840.81
#Mann= 3 ,-1 , 0
    4268     .05       0  4987.1     .05       0  4999.7     .05       0
Bank Sta=4987.1,4999.7
XS Rating Curve= 0 ,0
Exp/Cntr=0.3,0.1

Type RM Length L Ch R = 1 ,67165   ,489,489,489
BEGIN DESCRIPTION:
Lytle Creek 67810.83
END DESCRIPTION:
XS GIS Cut Line= 3
      1612833.92      6803766.06      1613550.07      6803996.95
      1613999.71      6803963.96
#Sta/Elev= 30
  4218.1 1833.36  4355.8  1831.9  4523.9 1831.69  4691.9 1829.36  4734.4 1828.03
  4825.4  1828.8  4830.6 1829.77  4862.7 1829.19  4889.5 1829.76  4926.8 1828.57
  4944.2 1828.69  4975.5  1826.8  4985.5 1822.21  4989.2 1821.32  4990.7 1820.82
  5000.3 1820.82  5001.8 1821.32  5005.6  1821.8  5015.6 1827.51  5022.6 1828.57
  5027.6 1827.55  5035.7 1828.73  5075.8  1828.5  5115.9 1826.86  5196.1 1829.22
  5216.1 1828.49  5236.2 1828.77  5266.3 1829.63  5326.4 1833.56  5421.4 1834.86
#Mann= 3 ,-1 , 0
  4218.1     .05       0  4989.2     .05       0  5001.8     .05       0
Bank Sta=4989.2,5001.8
XS Rating Curve= 0 ,0
Exp/Cntr=0.3,0.1

Type RM Length L Ch R = 1 ,66676   ,173,173,173
BEGIN DESCRIPTION:
Lytle Creek 67396.37
END DESCRIPTION:
XS GIS Cut Line= 4
      1612920.04      6803912.28      1613019.85      6804308.34
      1613930.77      6804312.93      1614460.48      6803916.17
#Sta/Elev= 30
  4367.9  1831.4  4655.8 1829.59  4755.4 1827.54  4871.5 1828.24  4921.5 1826.03
  4971.5 1826.16  4995.2 1821.48  4996.7 1820.98  5007.8 1821.48  5021.5 1822.58
  5031.5  1825.3  5061.5 1826.22  5111.5  1825.9  5161.5 1826.94  5251.5 1827.25
  5361.5 1826.79  5511.5 1827.86  5541.5 1829.27  5551.5  1828.5  5571.5  1829.3
  5601.5 1828.43  5621.5 1829.31  5707.6 1830.01    5893 1830.31  6036.8 1832.08
  6057.6  1833.1    6166 1833.37    6216 1835.69  6336.9  1837.4  6349.1 1838.51
#Mann= 3 ,-1 , 0
  4367.9     .05       0  4995.2     .05       0  5007.8     .05       0
#XS Ineff= 2 , 0
       0  4849.9 1833.75  5150.1       0 1833.75
Permanent Ineff=
       F       F
Bank Sta=4995.2,5007.8
XS Rating Curve= 0 ,0
Exp/Cntr=0.3,0.1

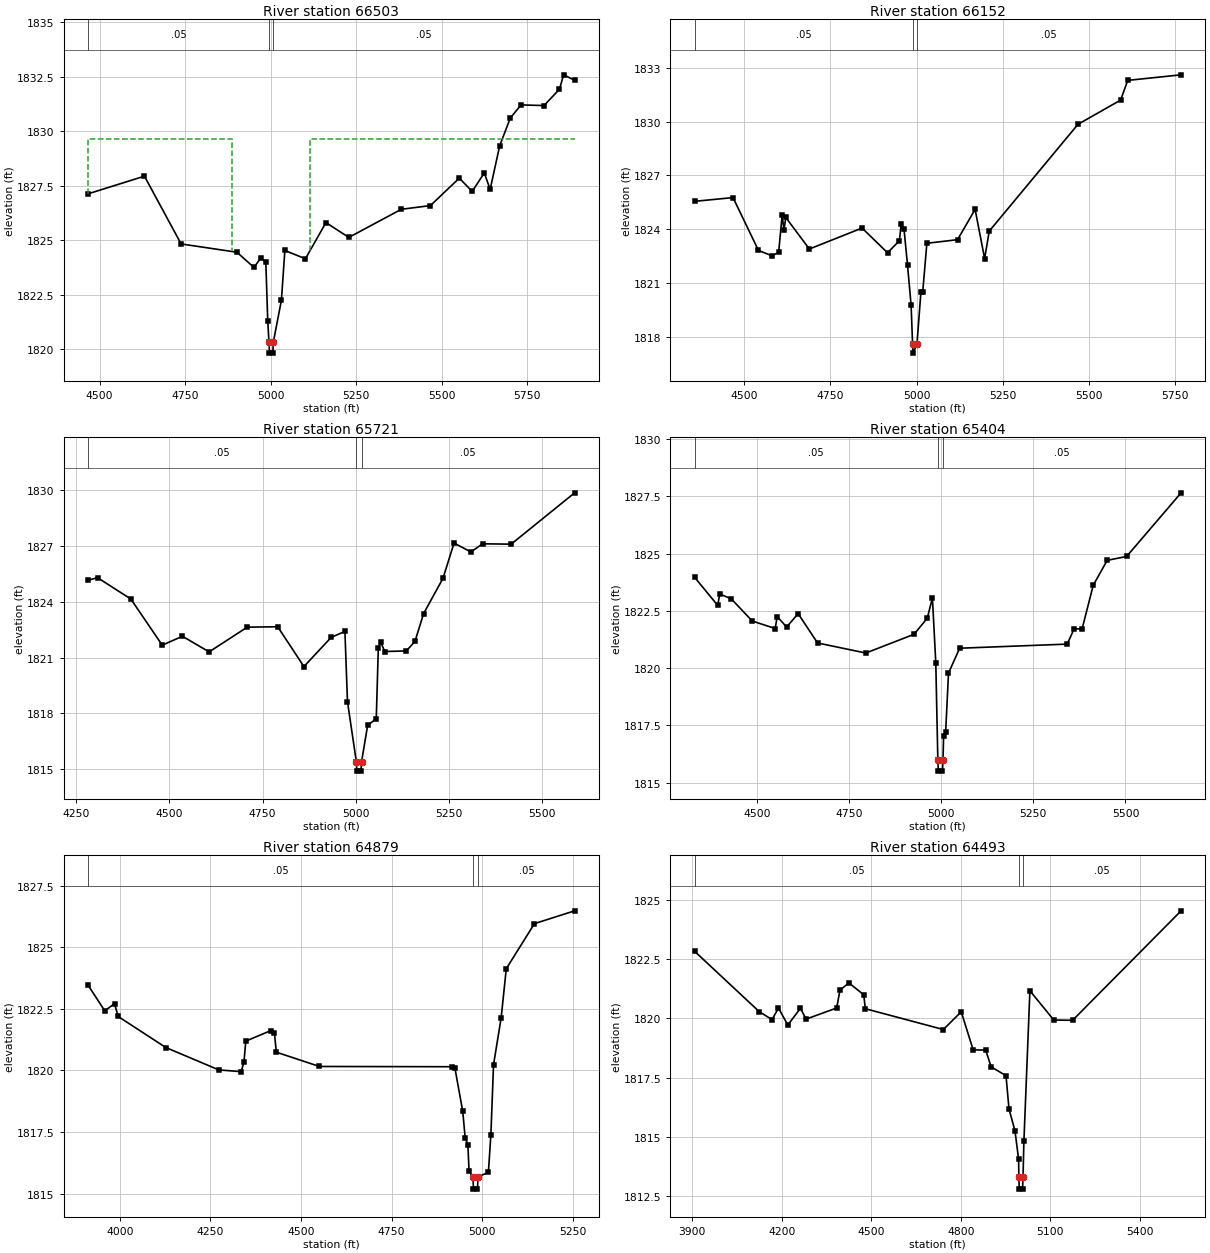
Type RM Length L Ch R = 1 ,66503   ,351,351,351
BEGIN DESCRIPTION:
Lytle Creek 66938.9
END DESCRIPTION:
XS GIS Cut Line= 3
      1612710.55      6804504.18      1613664.35      6804465.21
      1614083.94      6804670.47
#Sta/Elev= 30
  4466.3 1827.12  4630.9 1827.93  4738.1 1824.82  4901.1 1824.44  4951.2 1823.74
  4971.2 1824.19  4985.6 1823.98  4991.2  1821.3  4994.8 1820.31  4996.3 1819.81
    5006 1819.81  5007.5 1820.31  5031.2 1822.24  5041.2 1824.52  5101.3 1824.14
  5161.3  1825.8  5228.2 1825.12  5381.5 1826.41  5466.6 1826.58    5551 1827.84
  5588.6 1827.23  5624.1 1828.08  5641.1 1827.32  5669.1 1829.33  5699.9 1830.59
  5731.1  1831.2  5798.6 1831.17  5843.7 1831.92  5855.8 1832.58    5888 1832.33
#Mann= 3 ,-1 , 0
  4466.3     .05       0  4994.8     .05       0  5007.5     .05       0
#XS Ineff= 2 , 0
       0  4885.5 1829.64  5114.5       0 1829.64
Permanent Ineff=
       F       F
Bank Sta=4994.8,5007.5
XS Rating Curve= 0 ,0
Exp/Cntr=0.3,0.1

Type RM Length L Ch R = 1 ,66152   ,431,431,431
BEGIN DESCRIPTION:
Lytle Creek 67461.288
END DESCRIPTION:
XS GIS Cut Line= 3
      1612570.16      6804643.95      1613204.75      6804819.72
       1613935.4      6804996.42
#Sta/Elev= 30
  4356.5 1825.55  4467.9 1825.76  4541.7 1822.81  4581.2 1822.51  4600.2 1822.71
  4610.3 1824.79  4615.5 1823.95  4620.9 1824.65  4689.2 1822.89    4842 1824.06
  4915.8 1822.68  4950.1 1823.35  4955.3 1824.26  4963.4 1824.03  4973.7    1822
  4984.1 1819.76  4988.4 1817.58  4989.9 1817.08  5001.1 1817.58  5012.5 1820.48
  5017.7 1820.48  5029.8 1823.21  5118.7 1823.41  5169.6  1825.1  5197.2 1822.36
  5210.7 1823.89  5467.9 1829.85  5591.4  1831.2    5612  1832.3  5766.7 1832.61
#Mann= 3 ,-1 , 0
  4356.5     .05       0  4988.4     .05       0  5001.1     .05       0
Bank Sta=4988.4,5001.1
XS Rating Curve= 0 ,0
Exp/Cntr=0.3,0.1

Type RM Length L Ch R = 1 ,65721   ,317,317,317
BEGIN DESCRIPTION:
Lytle Creek 66393.781
END DESCRIPTION:
XS GIS Cut Line= 4
      1612562.13      6804668.97      1612661.33      6804970.84
       1613003.8      6805178.56      1613540.63      6805417.98
#Sta/Elev= 30
  4281.7 1825.16  4306.9  1825.3  4396.5 1824.15  4480.7 1821.67  4534.8 1822.15
  4606.6 1821.31    4709 1822.64  4790.7 1822.66  4861.1 1820.52  4934.2 1822.09
  4971.1 1822.41    4978 1818.63  5001.8  1815.4  5003.3  1814.9  5014.3  1814.9
  5015.8  1815.4  5032.1 1817.36  5055.3 1817.72  5060.8 1821.53    5067 1821.85
    5078 1821.33  5135.9 1821.36  5159.1 1821.87  5182.4 1823.37  5234.3 1825.26
  5264.1 1827.16  5309.4 1826.68  5340.7 1827.12  5417.4  1827.1  5587.8 1829.86
#Mann= 3 ,-1 , 0
  4281.7     .05       0  5001.8     .05       0  5015.8     .05       0
Bank Sta=5001.8,5015.8
XS Rating Curve= 0 ,0
Exp/Cntr=0.3,0.1

Type RM Length L Ch R = 1 ,65404   ,525,525,525
BEGIN DESCRIPTION:
Lytle Creek 66089.12
END DESCRIPTION:
XS GIS Cut Line= 4
      1612358.23      6804837.11      1612462.52      6805138.25
      1612764.86      6805333.15       1613401.8      6805405.22
#Sta/Elev= 30
  4331.4 1823.97  4394.2 1822.74  4399.5 1823.24  4430.7 1823.03  4487.7 1822.06
    4550 1821.73  4555.3 1822.25  4581.1  1821.8  4612.3 1822.38  4664.9  1821.1
  4795.8 1820.66  4926.7 1821.48  4962.4 1822.18  4976.4 1823.07  4985.6 1820.21
  4991.1    1816  4992.6  1815.5  5003.6  1815.5  5005.1    1816  5006.8 1817.05
  5012.4 1817.23    5020 1819.78  5050.2 1820.87    5342 1821.05  5360.7 1821.72
  5382.3 1821.71  5412.5 1823.62  5450.4 1824.71  5503.1 1824.88  5650.8 1827.66
#Mann= 3 ,-1 , 0
  4331.4     .05       0  4991.1     .05       0  5005.1     .05       0
Bank Sta=4991.1,5005.1
XS Rating Curve= 0 ,0
Exp/Cntr=0.3,0.1

Type RM Length L Ch R = 1 ,64879   ,386,386,386
BEGIN DESCRIPTION:
Lytle Creek 65607.01
END DESCRIPTION:
XS GIS Cut Line= 4
      1612339.63      6804867.07       1612500.6       6805541.7
      1612764.86      6805784.54      1612975.62      6805983.94
#Sta/Elev= 30
  3912.4 1823.46  3958.3 1822.42  3985.3 1822.71  3995.3 1822.19  4126.8 1820.93
  4273.2 1820.02  4334.9 1819.95  4342.4 1820.34  4347.6 1821.19  4417.1 1821.62
  4426.6 1821.51  4431.8 1820.74  4550.8 1820.16  4917.9 1820.15  4924.7 1820.09
  4946.2 1818.34    4953 1817.26  4960.4 1816.99  4963.7  1815.9  4974.4 1815.68
  4975.9 1815.18  4986.9 1815.18  4988.4 1815.68    5017 1815.86  5023.9 1817.39
  5031.2 1820.23  5052.2 1822.13  5066.4 1824.13  5144.1 1825.96    5255 1826.48
#Mann= 3 ,-1 , 0
  3912.4     .05       0  4974.4     .05       0  4988.4     .05       0
Bank Sta=4974.4,4988.4
XS Rating Curve= 0 ,0
Exp/Cntr=0.3,0.1

Type RM Length L Ch R = 1 ,64493   ,241,241,241
BEGIN DESCRIPTION:
Lytle Creek 65251.55
END DESCRIPTION:
XS GIS Cut Line= 6
      1612329.75      6804924.19      1612504.09      6805668.02
      1612513.12      6805987.66      1612524.09      6806148.48
      1612648.73      6806196.66      1612891.73      6806265.33
#Sta/Elev= 30
  3907.8 1822.84  4125.1 1820.28  4167.6 1819.95    4189 1820.44  4220.3 1819.72
  4262.8 1820.43  4281.5 1819.97  4384.2 1820.44  4395.3  1821.2  4425.3  1821.5
    4475    1821  4480.2 1820.41  4741.8 1819.53  4801.8 1820.28  4841.8 1818.67
  4883.9 1818.66  4901.9 1817.95  4951.9 1817.58  4961.9 1816.17  4981.9 1815.25
  4994.2 1814.04  4994.9 1813.28  4996.4 1812.78  5007.4 1812.78  5008.9 1813.28
  5011.9  1814.8    5032 1821.17  5112.2 1819.93  5175.2 1819.92  5538.9 1824.55
#Mann= 3 ,-1 , 0
  3907.8     .05       0  4994.9     .05       0  5008.9     .05       0
Bank Sta=4994.9,5008.9
XS Rating Curve= 0 ,0
Exp/Cntr=0.3,0.1

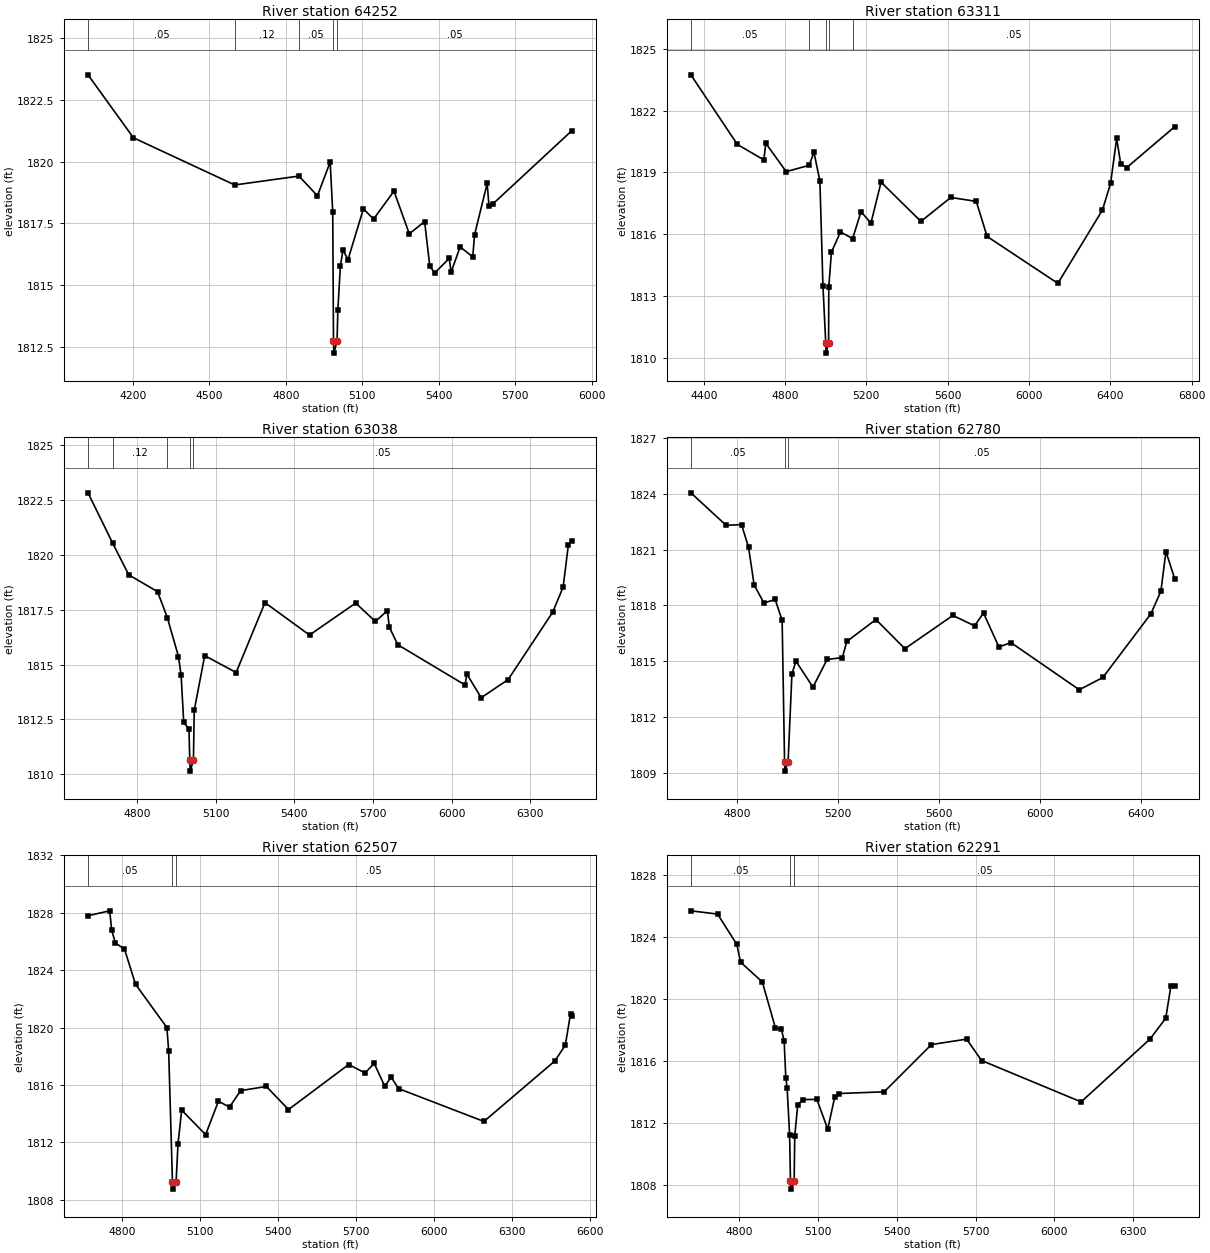
Type RM Length L Ch R = 1 ,64252   ,941,941,941
BEGIN DESCRIPTION:
Mapping XS 26b83782
END DESCRIPTION:
XS GIS Cut Line= 5
      1612293.38        6804870.      1612341.64      6805720.59
      1612326.01        6806231.      1612543.46      6806449.75
      1612738.48      6806563.66
#Sta/Elev= 30
  4024.8 1823.52  4203.1 1820.97    4600 1819.06  4851.9 1819.42  4924.2 1818.62
  4974.2 1819.99  4984.2 1817.96  4987.2 1812.75  4988.7 1812.25  5001.2 1812.75
  5004.2 1813.98  5014.2 1815.78  5024.2 1816.42  5044.2 1816.04  5104.3 1818.09
  5144.3 1817.68  5224.3 1818.81  5284.4 1817.08  5344.4 1817.58  5364.4 1815.79
  5383.4 1815.49  5441.1 1816.09  5448.2 1815.53  5483.6 1816.55  5533.1 1816.15
  5540.1 1817.04  5589.6 1819.12  5596.7 1818.22  5610.8 1818.28  5921.7 1821.26
#Mann= 5 ,-1 , 0
  4024.8     .05       0    4600     .12       0  4851.9     .05       0
  4987.2     .05       0  5001.2     .05       0
Bank Sta=4987.2,5001.2
XS Rating Curve= 0 ,0
Exp/Cntr=0.3,0.1

Type RM Length L Ch R = 1 ,63311   ,273,273,273
BEGIN DESCRIPTION:
Mapping XS cc1b6361
END DESCRIPTION:
XS GIS Cut Line= 6
      1612264.37      6804910.01      1612297.37        6805425.
      1611997.89       6805853.4      1611951.01      6805999.23
      1612161.63      6806570.52      1612740.69      6806586.89
#Sta/Elev= 30
  4336.9 1823.73  4565.4 1820.36  4695.6 1819.61  4705.6 1820.41  4805.9 1819.04
  4919.5 1819.35    4942 1819.99  4971.5 1818.59  4986.4 1813.52  5000.3 1810.75
  5001.8 1810.25  5014.3 1810.75  5015.2 1813.46  5028.2 1815.14  5072.7 1816.12
  5132.5  1815.8  5173.8  1817.1  5222.6 1816.55  5272.4 1818.53  5468.3 1816.63
  5615.4 1817.79  5740.7  1817.6    5794  1815.9  6141.9 1813.63  6361.2 1817.18
  6401.2 1818.47  6431.2 1820.65  6451.2 1819.41  6481.2 1819.24    6717 1821.22
#Mann= 5 ,-1 , 0
  4336.9     .05       0  4919.5     .12       0  5000.3     .07       0
  5014.3     .12       0  5132.5     .05       0
Bank Sta=5000.3,5014.3
XS Rating Curve= 0 ,0
Exp/Cntr=0.3,0.1

Type RM Length L Ch R = 1 ,63038   ,258,258,258
BEGIN DESCRIPTION:
Mapping XS 94f33449
END DESCRIPTION:
XS GIS Cut Line= 4
      1611969.24      6805082.56      1611932.78      6806007.05
      1612154.07      6806584.89      1612458.38      6806588.04
#Sta/Elev= 30
  4611.5 1822.84  4705.9 1820.54  4767.1  1819.1  4877.1 1818.33  4914.5 1817.15
  4957.2 1815.37  4967.2 1814.52  4977.2 1812.36  4997.2 1812.07  5000.3 1810.64
  5001.8 1810.14  5014.3 1810.64  5017.3 1812.91  5057.3 1815.41  5177.4 1814.64
  5287.5 1817.83  5457.6 1816.35  5634.1 1817.81  5709.1 1816.97  5754.9 1817.46
  5762.6 1816.71  5794.7 1815.91  6051.7 1814.07  6058.6 1814.57  6113.4 1813.49
  6216.4 1814.32  6386.4 1817.39  6426.4 1818.54  6446.4 1820.47  6459.8 1820.63
#Mann= 5 ,-1 , 0
  4611.5     .05       0  4705.9     .12       0  4914.5     .05       0
  5000.3     .05       0  5014.3     .05       0
Bank Sta=5000.3,5014.3
XS Rating Curve= 0 ,0
Exp/Cntr=0.3,0.1

Type RM Length L Ch R = 1 ,62780   ,273,273,273
BEGIN DESCRIPTION:
Mapping XS 31b3d0d7
END DESCRIPTION:
XS GIS Cut Line= 5
      1611536.96      6805137.27       1611815.6      6805681.52
      1611919.76      6806020.07      1612145.36      6806595.37
      1612480.05      6806599.45
#Sta/Elev= 30
  4615.3 1824.06  4755.1 1822.31  4816.1 1822.35  4843.9 1821.13  4866.1  1819.1
  4904.9 1818.13  4949.3 1818.32  4977.1  1817.2  4986.7 1809.58  4988.2 1809.08
  5000.7 1809.58  5015.9 1814.31  5031.8    1815  5099.2  1813.6  5155.4 1815.09
  5215.8 1815.19  5233.5 1816.06  5348.8 1817.24  5463.7 1815.67  5653.9 1817.46
  5739.8  1816.9  5775.4 1817.59  5836.5 1815.76  5883.9    1816  6155.1 1813.46
  6248.5 1814.12  6438.5 1817.54  6478.5 1818.76  6498.6  1820.9  6533.6 1819.42
#Mann= 3 ,-1 , 0
  4615.3     .05       0  4986.7     .05       0  5000.7     .05       0
Bank Sta=4986.7,5000.7
XS Rating Curve= 0 ,0
Exp/Cntr=0.3,0.1

Type RM Length L Ch R = 1 ,62507   ,216,216,216
BEGIN DESCRIPTION:
Mapping XS e7d49430
END DESCRIPTION:
XS GIS Cut Line= 5
       1611234.9      6805389.88      1611729.66      6805835.17
      1611904.14      6806061.73      1612139.88      6806610.79
      1612450.32      6806606.25
#Sta/Elev= 30
  4668.9  1827.8  4752.4 1828.14  4759.9 1826.79  4774.1  1825.9  4809.2 1825.47
  4851.8 1823.01  4972.1    1820  4978.9 1818.39  4993.5 1809.23    4995 1808.73
  5007.5 1809.23  5014.7 1811.86  5028.9 1814.24  5120.9 1812.53  5170.2 1814.86
  5212.8 1814.45  5255.4  1815.6  5354.3 1815.89  5439.4 1814.28  5670.8 1817.42
  5733.7 1816.83  5768.8  1817.5  5809.8 1815.89  5833.4 1816.55  5862.4 1815.74
  6190.4 1813.45  6463.2 1817.67  6503.2 1818.77  6523.2 1820.95  6528.5 1820.82
#Mann= 3 ,-1 , 0
  4668.9     .05       0  4993.5     .05       0  5007.5     .05       0
Bank Sta=4993.5,5007.5
XS Rating Curve= 0 ,0
Exp/Cntr=0.3,0.1

Type RM Length L Ch R = 1 ,62291   ,198,198,198
BEGIN DESCRIPTION:
Mapping XS be3d6582
END DESCRIPTION:
XS GIS Cut Line= 5
      1611063.02      6805715.39      1611677.58      6805887.25
       1611883.3      6806077.36      1612132.29      6806619.94
      1612459.45      6806622.02
#Sta/Elev= 30
    4616  1825.7  4717.6 1825.49  4791.1 1823.53    4805 1822.39    4888 1821.11
    4938 1818.14  4960.7 1818.06  4971.1 1817.31  4977.4 1814.94  4982.6 1814.24
  4991.9 1811.24  4995.2 1808.24  4996.7 1807.74  5009.2 1808.24  5011.5 1811.18
    5023  1813.2  5043.8 1813.52  5095.7 1813.53  5137.2 1811.61  5163.6 1813.68
  5178.8 1813.91  5351.9 1814.02    5532 1817.07  5665.8 1817.42  5722.8 1816.04
  6101.7 1813.37  6363.9 1817.42    6424 1818.77    6444 1820.88  6458.4 1820.86
#Mann= 3 ,-1 , 0
    4616     .05       0  4995.2     .05       0  5009.2     .05       0
Bank Sta=4995.2,5009.2
XS Rating Curve= 0 ,0
Exp/Cntr=0.3,0.1

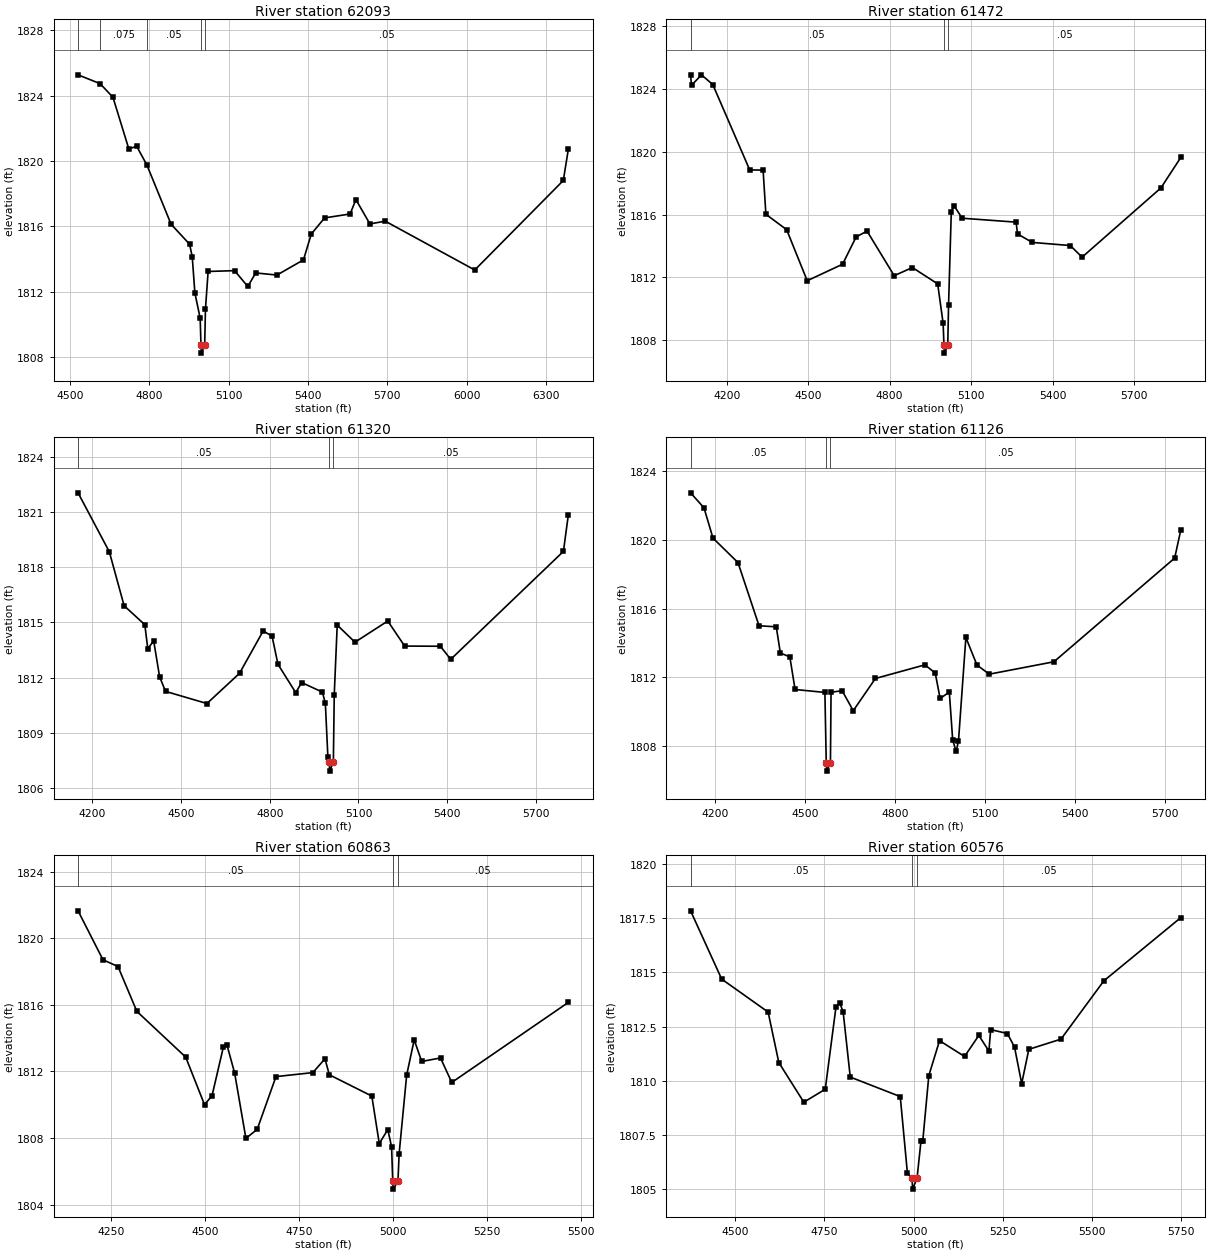
Type RM Length L Ch R = 1 ,62093   ,621,621,621
BEGIN DESCRIPTION:
Mapping XS 973cb49e
END DESCRIPTION:
XS GIS Cut Line= 6
      1610943.18      6806004.44      1611646.33      6806020.07
       1611758.3      6806033.09       1611878.1      6806119.02
      1612124.75      6806634.76      1612444.18      6806633.52
#Sta/Elev= 30
  4530.6 1825.27  4613.8 1824.73  4662.5  1823.9  4722.5 1820.74  4752.5 1820.89
  4790.9 1819.75  4882.5 1816.12  4952.5  1814.9  4962.5 1814.13  4972.5 1811.91
  4992.5 1810.37  4995.5 1808.73    4997 1808.23  5009.5 1808.73  5012.5 1810.93
  5022.5 1813.23  5122.6 1813.28  5172.6 1812.31  5202.6 1813.14  5282.9 1813.01
  5383.2 1813.94  5412.7 1815.52  5463.1 1816.51  5559.5 1816.75  5581.6 1817.63
  5634.5 1816.14  5692.5 1816.31  6031.1 1813.32    6366  1818.8  6385.2 1820.73
#Mann= 5 ,-1 , 0
  4530.6     .05       0  4613.8    .075       0  4790.9     .05       0
  4995.5     .05       0  5009.5     .05       0
Bank Sta=4995.5,5009.5
XS Rating Curve= 0 ,0
Exp/Cntr=0.3,0.1

Type RM Length L Ch R = 1 ,61472   ,152,152,152
BEGIN DESCRIPTION:
Mapping XS 6360c2df
END DESCRIPTION:
XS GIS Cut Line= 5
      1610875.49      6806142.46      1611219.24       6806225.8
      1611900.24      6806251.02      1612121.03      6806646.13
      1612438.53      6806647.18
#Sta/Elev= 30
    4067 1824.88  4070.5 1824.23  4107.1  1824.9  4148.8 1824.28  4284.6 1818.85
    4334 1818.83  4344.3 1816.02  4420.7 1815.04  4496.5 1811.79  4626.6 1812.84
  4676.6 1814.58  4716.7 1814.95  4816.7 1812.11  4883.7 1812.63  4976.8 1811.59
  4996.9 1809.07  4999.9 1807.68  5001.4 1807.18  5013.9 1807.68  5016.9 1810.27
  5026.9 1816.18  5036.9 1816.57  5066.9 1815.77  5265.3 1815.52    5271 1814.77
  5324.6 1814.23  5465.1 1814.03  5508.5 1813.29  5798.8  1817.7  5872.3 1819.65
#Mann= 3 ,-1 , 0
    4067     .05       0  4999.9     .05       0  5013.9     .05       0
Bank Sta=4999.9,5013.9
XS Rating Curve= 0 ,0
Exp/Cntr=0.3,0.1

Type RM Length L Ch R = 1 ,61320   ,194,194,194
BEGIN DESCRIPTION:
Lytle Creek 62014.58
END DESCRIPTION:
XS GIS Cut Line= 6
      1610909.34      6806366.42      1611524.26      6806378.02
      1611756.87      6806389.57       1611883.3      6806387.25
      1612114.42      6806657.54      1612441.79      6806669.72
#Sta/Elev= 30
    4152 1822.04  4257.7 1818.84  4307.7 1815.91  4377.7 1814.88  4387.7 1813.58
  4407.7    1814  4427.7 1812.05  4447.7 1811.26  4587.7  1810.6  4697.8 1812.24
  4777.8 1814.54  4807.8 1814.26  4827.8 1812.73  4887.9 1811.19  4907.9 1811.74
    4978 1811.22    4988 1810.61  4996.5 1807.72  5001.1 1807.43  5002.6 1806.93
  5015.1 1807.43  5018.1 1811.08  5028.1 1814.86  5088.1 1813.93    5199 1815.08
  5256.1 1813.72  5376.8 1813.71  5411.9    1813  5792.8 1818.86  5809.6 1820.86
#Mann= 3 ,-1 , 0
    4152     .05       0  5001.1     .05       0  5015.1     .05       0
Bank Sta=5001.1,5015.1
XS Rating Curve= 0 ,0
Exp/Cntr=0.3,0.1

Type RM Length L Ch R = 1 ,61126   ,263,263,263
BEGIN DESCRIPTION:
Lytle Creek 61813.44
END DESCRIPTION:
XS GIS Cut Line= 6
      1610850.36      6806399.69      1611067.82      6806390.37
      1611501.05      6806537.88      1611704.79      6806575.33
      1612106.76       6806668.1      1612445.79      6806681.52
#Sta/Elev= 30
  4119.4 1822.72  4164.1 1821.85  4194.1 1820.09  4277.4 1818.67  4347.6    1815
    4405 1814.94  4418.6 1813.42  4450.3 1813.19  4467.7  1811.3  4567.1 1811.13
  4571.6 1807.06  4573.1 1806.56  4585.6 1807.06  4587.6 1811.14  4624.5 1811.23
  4661.6 1810.07  4735.5 1811.94  4900.4 1812.73  4934.8 1812.26  4951.2 1810.78
  4981.8 1811.15    4993 1808.38  5004.5  1807.7  5012.4 1808.31    5037 1814.32
  5073.9 1812.72    5115 1812.19  5330.5 1812.91  5732.9 1818.93  5753.7 1820.59
#Mann= 3 ,-1 , 0
  4119.4     .05       0  4571.6     .05       0  4585.6     .05       0
Bank Sta=4571.6,4585.6
XS Rating Curve= 0 ,0
Exp/Cntr=0.3,0.1

Type RM Length L Ch R = 1 ,60863   ,287,287,287
BEGIN DESCRIPTION:
Lytle Creek 61507.84
END DESCRIPTION:
XS GIS Cut Line= 4
      1610768.71      6806671.11      1611338.01      6806688.97
      1611545.06      6806799.29      1612045.08      6806813.18
#Sta/Elev= 30
  4162.1 1821.65  4228.4 1818.71  4268.4  1818.3  4318.5 1815.61  4448.5 1812.86
  4498.6    1810  4518.6 1810.55  4548.6 1813.46  4558.6 1813.56  4578.6 1811.91
  4608.6 1807.98  4638.6 1808.52  4688.6 1811.69  4786.7 1811.93  4818.9 1812.76
  4830.6  1811.8  4943.6 1810.52  4963.4 1807.67  4986.2 1808.51  4996.2 1807.46
  4999.2 1805.43  5000.7 1804.93  5013.2 1805.43  5016.2 1807.05  5036.3 1811.78
  5056.3  1813.9  5076.3  1812.6  5126.3 1812.81  5156.3 1811.34  5466.5 1816.15
#Mann= 3 ,-1 , 0
  4162.1     .05       0  4999.2     .05       0  5013.2     .05       0
Bank Sta=4999.2,5013.2
XS Rating Curve= 0 ,0
Exp/Cntr=0.3,0.1

Type RM Length L Ch R = 1 ,60576   ,173,173,173
BEGIN DESCRIPTION:
Lytle Creek 61244.98
END DESCRIPTION:
XS GIS Cut Line= 3
      1610747.89      6806991.42      1611395.76      6806990.27
      1612120.72      6807000.67
#Sta/Elev= 30
  4375.6 1817.84  4462.7 1814.69  4592.7 1813.17  4622.7 1810.84  4692.7 1809.01
  4752.7 1809.61  4782.7  1813.4  4792.7 1813.61  4802.7 1813.19  4822.7 1810.17
  4962.7 1809.27  4982.7 1805.74  4995.7  1805.5  4997.2    1805  5009.7  1805.5
  5020.6  1807.2  5025.6  1807.2  5042.7 1810.24  5072.7 1811.85  5142.7 1811.12
  5182.7 1812.09  5210.9 1811.37  5215.9 1812.36  5262.7 1812.18  5282.7 1811.55
  5302.7 1809.87  5322.7 1811.45  5412.7 1811.92  5532.8 1814.61  5748.5 1817.53
#Mann= 3 ,-1 , 0
  4375.6     .05       0  4995.7     .05       0  5009.7     .05       0
Bank Sta=4995.7,5009.7
XS Rating Curve= 0 ,0
Exp/Cntr=0.3,0.1

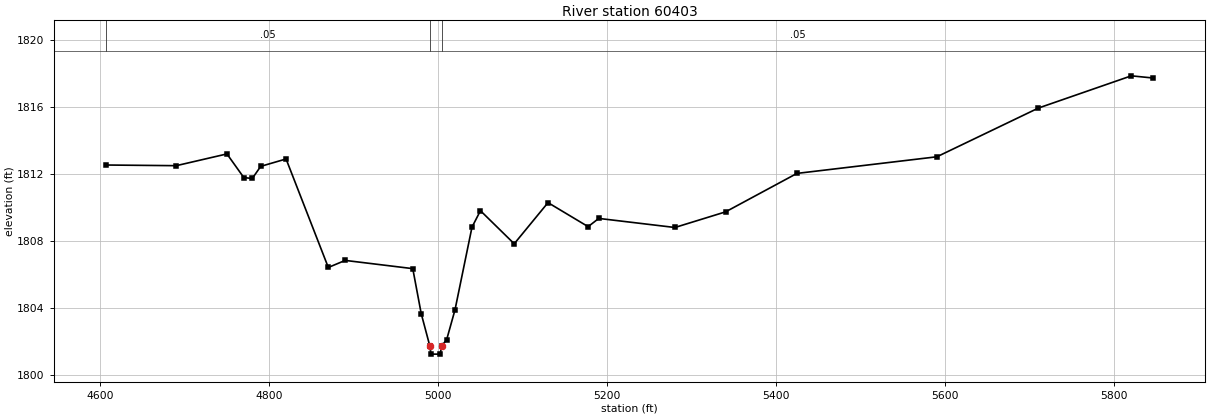
Type RM Length L Ch R = 1 ,60403   ,153,153,153
BEGIN DESCRIPTION:
Lytle Creek 61060.47
END DESCRIPTION:
XS GIS Cut Line= 3
      1610961.68      6807156.93      1611354.09       6807160.4
      1612200.66      6807125.71
#Sta/Elev= 30
    4607 1812.53  4690.3 1812.49  4750.3 1813.19  4770.3 1811.78  4780.3 1811.73
  4790.3 1812.45  4820.3 1812.89  4870.3 1806.43  4890.3 1806.85  4970.3 1806.36
  4980.3 1803.68  4990.4 1801.77  4991.9 1801.27  5002.9 1801.27  5004.4 1801.77
  5010.3 1802.11  5020.3 1803.91  5040.4 1808.83  5050.4 1809.81  5090.4 1807.84
  5130.4 1810.29  5177.9 1808.86  5190.5 1809.35  5280.6 1808.81  5340.6 1809.74
  5425.1 1812.03  5590.8 1813.02  5710.9 1815.92    5821 1817.84  5846.7 1817.71
#Mann= 3 ,-1 , 0
    4607     .05       0  4990.4     .03       0  5004.4     .05       0
Bank Sta=4990.4,5004.4
XS Rating Curve= 0 ,0
Exp/Cntr=0.3,0.1