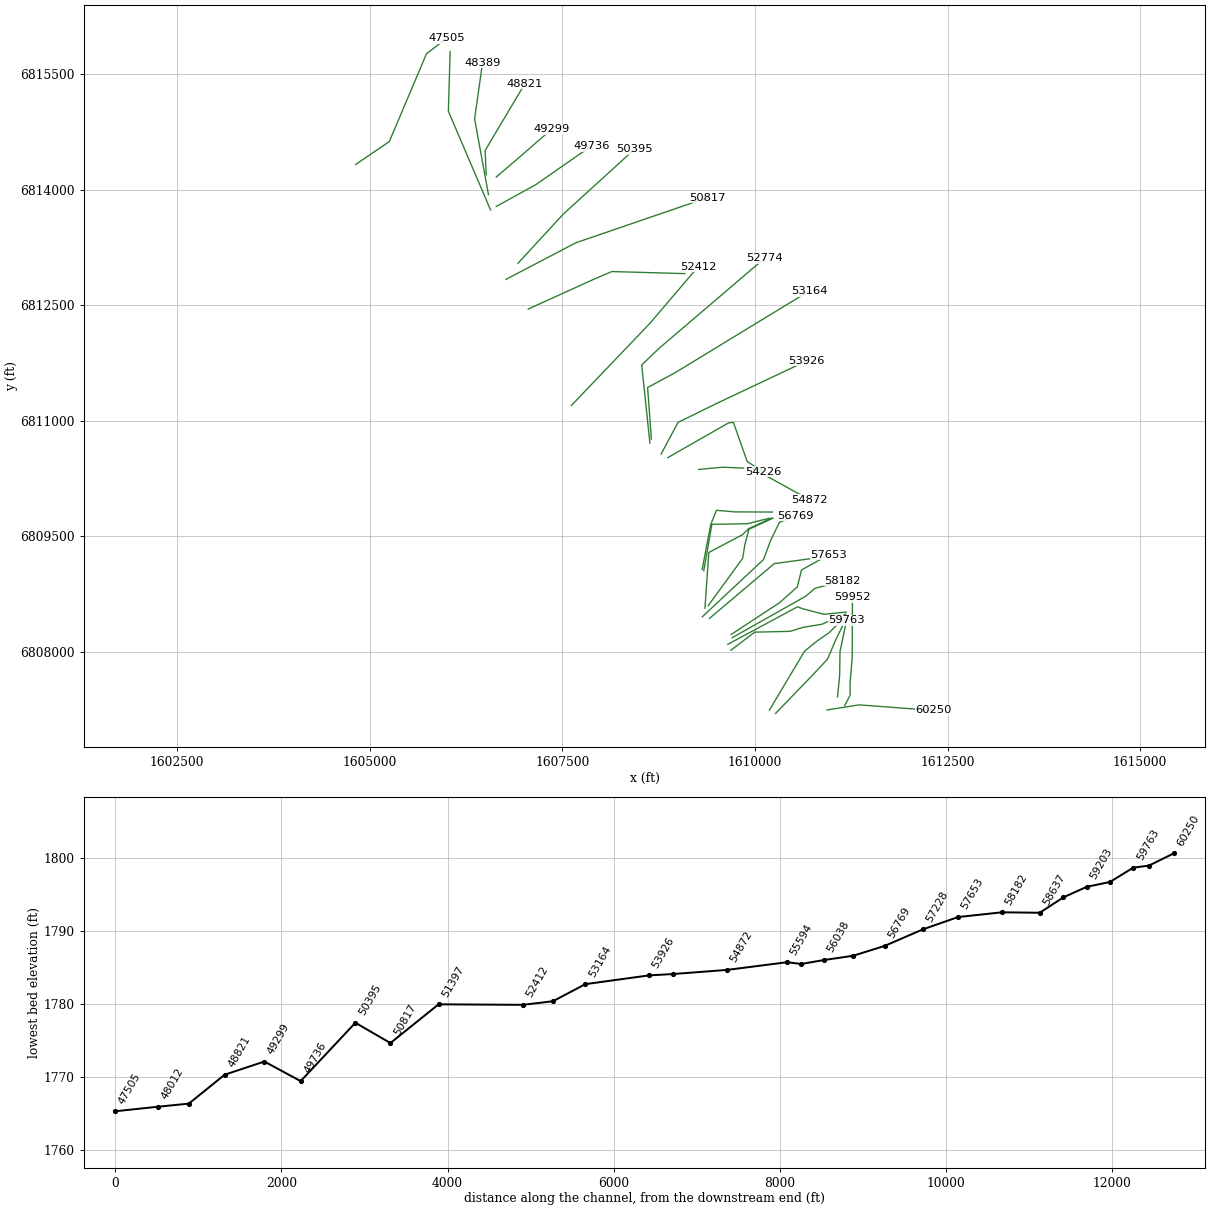
HEC-RAS study Lytle Creek.prj: Lytle Creek Base Level Engineering

--- Lytle Creek.g02 (geometry) --- (continued)

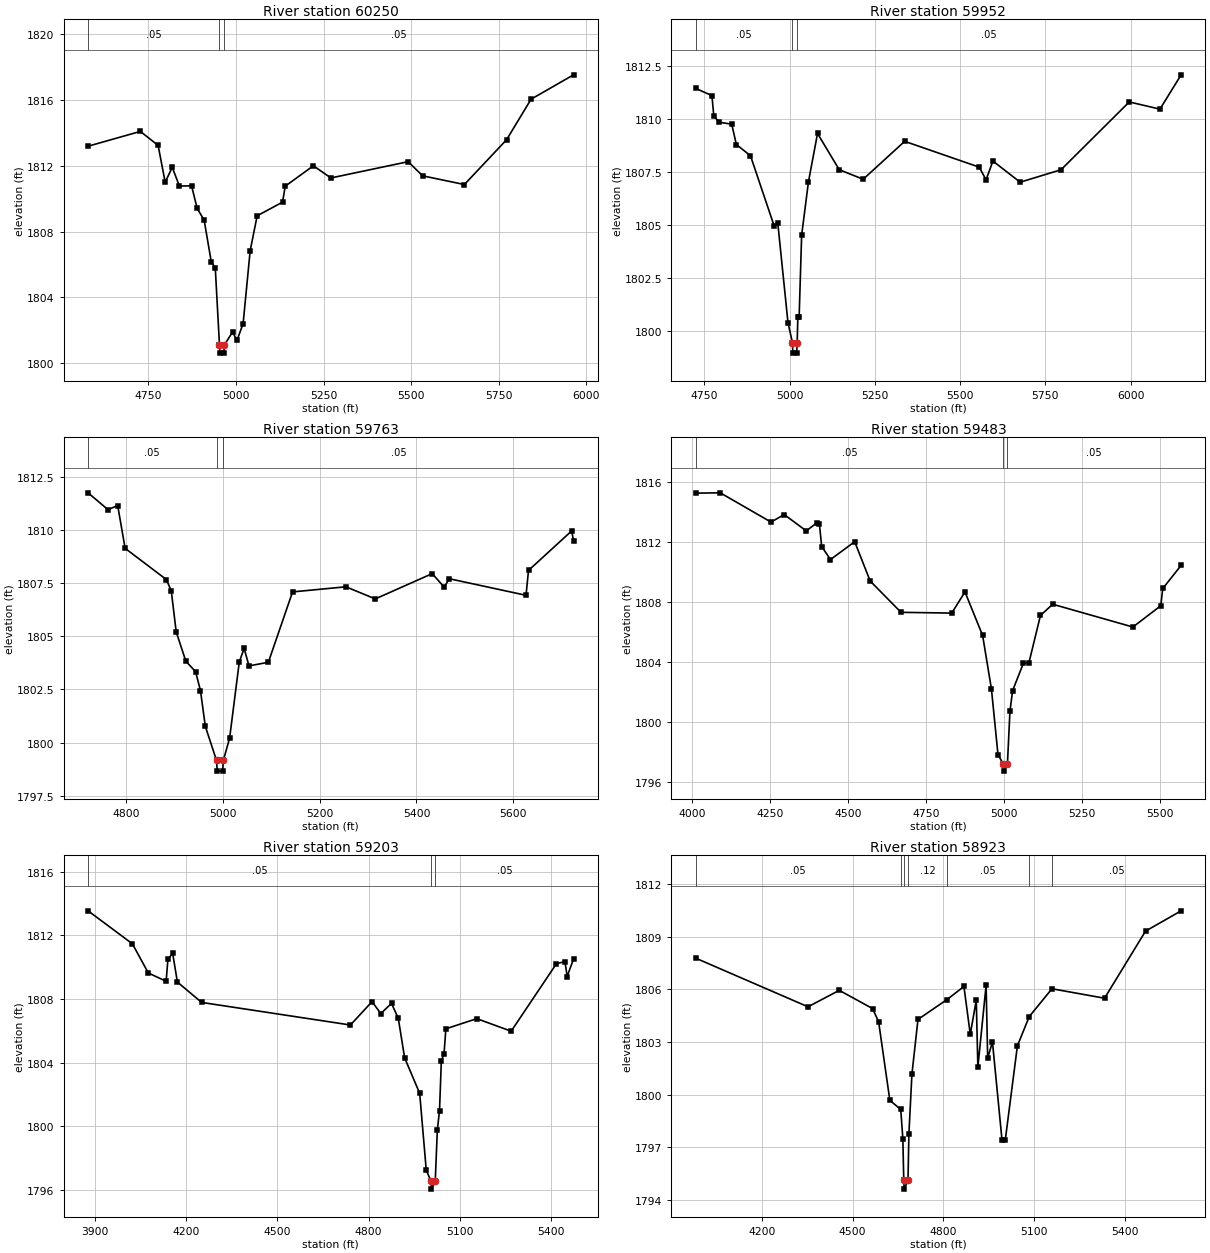
Type RM Length L Ch R = 1 ,60250   ,298,298,298
BEGIN DESCRIPTION:
Lytle Creek 61296.893
END DESCRIPTION:
XS GIS Cut Line= 3
      1610937.47      6807247.22      1611354.85      6807312.79
      1612315.92      6807240.26
#Sta/Elev= 30
  4577.5 1813.19  4726.8 1814.09  4777.5 1813.24  4797.7    1811  4817.9 1811.91
  4838.2 1810.77  4873.1 1810.78  4888.8 1809.42    4909 1808.69  4929.3 1806.16
  4940.7  1805.8  4952.7 1801.11  4954.2 1800.61  4965.2 1800.61  4966.7 1801.11
    4990 1801.89  5002.6 1801.38  5020.2  1802.4  5040.3 1806.83  5060.3 1808.96
  5132.8 1809.79  5140.5 1810.76  5220.8    1812  5270.9 1811.26  5491.5 1812.25
  5532.7 1811.39    5652 1810.86  5772.3 1813.58  5842.5 1816.05  5963.8 1817.53
#Mann= 3 ,-1 , 0
  4577.5     .05       0  4952.7     .05       0  4966.7     .05       0
Bank Sta=4952.7,4966.7
XS Rating Curve= 0 ,0
Exp/Cntr=0.3,0.1

Type RM Length L Ch R = 1 ,59952   ,189,189,189
BEGIN DESCRIPTION:
Lytle Creek 60583.97
END DESCRIPTION:
XS GIS Cut Line= 5
      1611165.87      6807304.29      1611235.56       6807436.7
      1611235.56      6807590.65      1611262.68      6807928.99
      1611266.12      6808710.18
#Sta/Elev= 30
    4724 1811.44  4771.8  1811.1  4777.4 1810.13  4793.8 1809.84  4829.9 1809.75
  4843.5 1808.79  4884.9 1808.26  4954.9 1804.92  4964.9  1805.1  4994.9 1800.38
  5007.9 1799.44  5009.4 1798.94  5020.4 1798.94  5021.9 1799.44  5023.8 1800.63
  5027.6 1800.63    5035 1804.51    5055 1807.03  5081.6 1809.31  5145.3  1807.6
  5215.5 1807.15  5337.2 1808.94    5556 1807.72    5576 1807.12    5596 1808.01
    5676 1807.01    5796  1807.6    5996  1810.8    6086 1810.46  6148.2 1812.08
#Mann= 3 ,-1 , 0
    4724     .05       0  5007.9     .03       0  5021.9     .05       0
Bank Sta=5007.9,5021.9
XS Rating Curve= 0 ,0
Exp/Cntr=0.3,0.1

Type RM Length L Ch R = 1 ,59763   ,280,280,280
BEGIN DESCRIPTION:
Lytle Creek 60407.03
END DESCRIPTION:
XS GIS Cut Line= 4
      1611072.37      6807417.06      1611100.14      6807694.82
      1611104.59      6808004.37       1611190.3      6808409.27
#Sta/Elev= 30
  4721.8 1811.75  4762.9 1810.96    4783 1811.15  4798.3 1809.14  4883.5 1807.67
  4893.6 1807.14  4903.8 1805.21  4923.7 1803.83  4943.8 1803.34  4953.9 1802.45
  4963.9 1800.77  4987.1 1799.16  4988.6 1798.66  4999.6 1798.66  5001.1 1799.16
  5014.1 1800.21  5034.1  1803.8  5044.1 1804.43  5054.1 1803.61  5094.1 1803.78
  5144.1 1807.09  5254.2 1807.33  5314.9 1806.76  5432.5 1807.95  5457.3 1807.31
  5467.6 1807.71  5626.2 1806.93  5631.3  1808.1  5720.5 1809.96  5724.4 1809.48
#Mann= 3 ,-1 , 0
  4721.8     .05       0  4987.1     .03       0  5001.1     .05       0
Bank Sta=4987.1,5001.1
XS Rating Curve= 0 ,0
Exp/Cntr=0.3,0.1

Type RM Length L Ch R = 1 ,59483   ,280,280,280
BEGIN DESCRIPTION:
Lytle Creek 60136.79
END DESCRIPTION:
XS GIS Cut Line= 5
       1610268.7      6807202.33      1610738.38      6807688.48
      1610940.42      6807903.15      1611049.39      6808156.85
      1611185.41      6808436.77
#Sta/Elev= 30
  4010.7 1815.24  4089.8 1815.26  4252.6 1813.31  4295.1 1813.81  4365.8 1812.72
  4401.1 1813.28    4408 1813.17  4415.2 1811.68  4443.5 1810.81  4521.2    1812
  4570.8 1809.38  4669.9 1807.29  4832.6 1807.24  4875.1 1808.65  4931.7 1805.75
    4960 1802.18  4981.1 1797.79  4997.4  1797.2  4998.9  1796.7  5011.4  1797.2
  5019.4 1800.69    5028 1802.07  5062.9 1803.91  5080.5 1803.94  5117.3 1807.08
  5156.6 1807.83    5414 1806.31  5503.5 1807.73  5509.8 1808.88  5568.8 1810.42
#Mann= 3 ,-1 , 0
  4010.7     .05       0  4997.4     .05       0  5011.4     .05       0
Bank Sta=4997.4,5011.4
XS Rating Curve= 0 ,0
Exp/Cntr=0.3,0.1

Type RM Length L Ch R = 1 ,59203   ,280,280,280
BEGIN DESCRIPTION:
Lytle Creek 59825.13
END DESCRIPTION:
XS GIS Cut Line= 5
      1610187.99      6807244.02      1610644.12      6808009.17
      1610807.52      6808142.53      1610962.51      6808249.09
      1611178.86      6808464.07
#Sta/Elev= 30
  3878.7 1813.54  4024.1 1811.47  4076.7 1809.63  4135.1 1809.11  4140.9 1810.48
  4156.5 1810.88  4172.1 1809.06  4251.9 1807.78  4740.5 1806.36  4811.5 1807.83
  4840.2 1807.08  4875.4 1807.72  4897.7 1806.78  4918.5  1804.3    4968 1802.06
  4989.5 1797.24  5005.1 1796.54  5006.6 1796.04  5019.1 1796.54  5025.9 1799.75
  5033.1 1800.97  5039.1  1804.1    5048 1804.56    5054 1806.12  5155.5 1806.76
  5268.5 1805.97    5417 1810.21  5445.3 1810.35  5452.3 1809.41  5473.5 1810.52
#Mann= 3 ,-1 , 0
  3878.7     .05       0  5005.1     .05       0  5019.1     .05       0
Bank Sta=5005.1,5019.1
XS Rating Curve= 0 ,0
Exp/Cntr=0.3,0.1

Type RM Length L Ch R = 1 ,58923   ,286,286,286
BEGIN DESCRIPTION:
Lytle Creek 59569.64
END DESCRIPTION:
XS GIS Cut Line= 6
      1609689.42      6808022.75      1609997.74      6808257.34
      1610456.22      6808267.46      1610621.41      6808319.12
      1610867.94       6808359.6      1611177.54       6808488.8
#Sta/Elev= 30
  3981.5 1807.79  4352.9 1805.01  4456.2 1805.95  4566.2 1804.91  4586.2 1804.16
  4623.3 1799.67  4659.3 1799.15  4666.3 1797.48  4669.3  1795.1  4670.8  1794.6
  4683.3  1795.1  4686.3 1797.75  4696.3 1801.17  4716.3 1804.29  4811.9 1805.42
  4868.1 1806.17  4889.1 1803.44  4908.9 1805.39  4914.2 1801.57  4941.4 1806.24
  4946.6 1802.09  4962.4    1803  4993.9 1797.41  5004.9 1797.42  5044.8 1802.78
  5083.9 1804.45    5159 1806.04  5332.8  1805.5  5468.2 1809.33  5585.9 1810.49
#Mann= 7 ,-1 , 0
  3981.5     .05       0  4659.3     .12       0  4669.3     .05       0
  4683.3     .12       0  4811.9     .05       0  5083.9     .12       0
    5159     .05       0
Bank Sta=4669.3,4683.3
XS Rating Curve= 0 ,0
Exp/Cntr=0.3,0.1

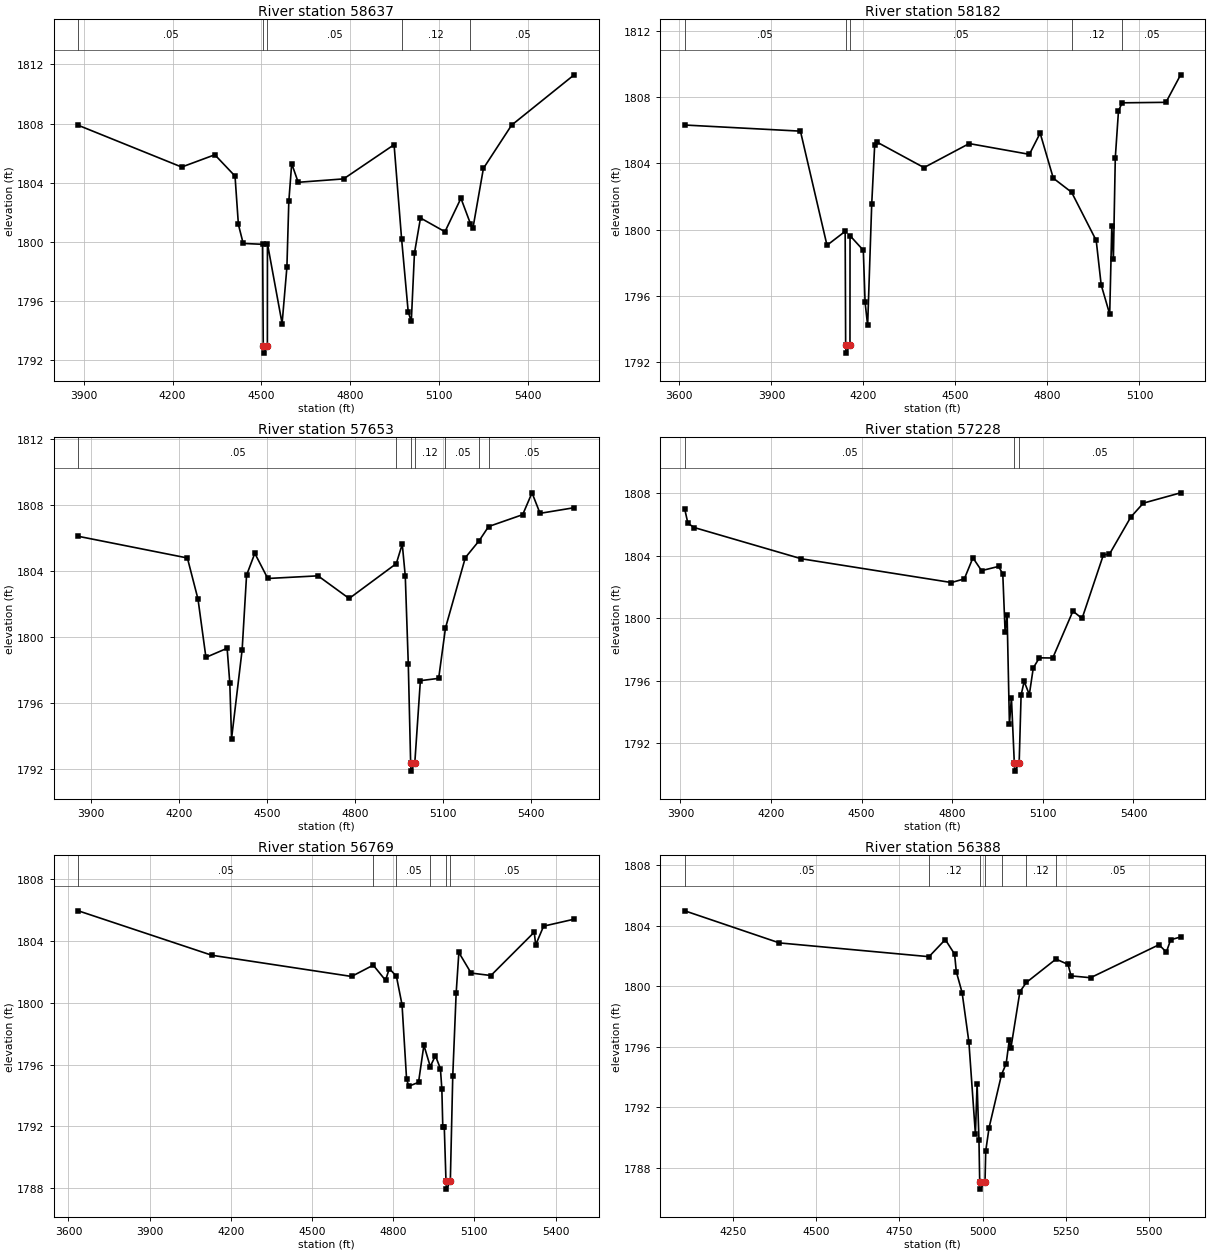
Type RM Length L Ch R = 1 ,58637   ,455,455,455
BEGIN DESCRIPTION:
Lytle Creek 59281.01
END DESCRIPTION:
XS GIS Cut Line= 5
      1609649.09      6808099.36      1610554.23      6808586.85
      1610623.58      6808560.01      1610895.12      6808489.41
      1611185.37      6808517.46
#Sta/Elev= 30
  3881.8 1807.88  4230.9 1805.06  4342.8 1805.89    4411 1804.45  4422.4 1801.18
  4438.6  1799.9  4504.3 1799.84  4506.3 1792.99  4507.8 1792.49  4520.3 1792.99
  4520.5 1799.89    4570 1794.49  4586.2 1798.29  4592.7 1802.74  4602.4 1805.29
  4624.4 1804.03  4777.7 1804.26  4948.2 1806.57  4973.5 1800.23    4996 1795.26
  5006.4 1794.64    5017 1799.24  5037.4 1801.62    5120 1800.69    5174 1802.95
  5206.2 1801.23  5214.5 1800.93  5249.9 1804.97  5345.1 1807.89  5556.4 1811.29
#Mann= 5 ,-1 , 0
  3881.8     .05       0  4506.3     .07       0  4520.3     .05       0
  4973.5     .12       0  5206.2     .05       0
Bank Sta=4506.3,4520.3
XS Rating Curve= 0 ,0
Exp/Cntr=0.3,0.1

Type RM Length L Ch R = 1 ,58182   ,529,529,529
BEGIN DESCRIPTION:
Lytle Creek 58794.3
END DESCRIPTION:
XS GIS Cut Line= 5
      1609705.92      6808185.31       1610657.4      6808722.42
      1610781.74      6808827.36      1610905.26      6808859.16
      1611129.25      6808925.58
#Sta/Elev= 30
  3617.7 1806.32  3994.7 1805.95  4081.3 1799.06  4140.5  1799.9  4142.1 1793.05
  4143.6 1792.55  4156.2 1793.05  4156.4 1799.64  4199.7 1798.76  4205.5 1795.61
  4213.8 1794.22  4227.1 1801.55  4236.7 1805.09  4243.1  1805.3  4397.5 1803.75
  4544.9  1805.2  4741.1 1804.55  4776.2 1805.83  4819.1 1803.11  4878.8 1802.26
    4959 1799.35  4975.2 1796.67    5003  1794.9  5009.8 1800.23    5015 1798.26
  5021.2 1804.34  5031.6 1807.17  5043.5 1807.66  5186.4 1807.69  5234.2 1809.35
#Mann= 5 ,-1 , 0
  3617.7     .05       0  4142.1     .07       0  4156.2     .05       0
  4878.8     .12       0  5043.5     .05       0
Bank Sta=4142.1,4156.2
XS Rating Curve= 0 ,0
Exp/Cntr=0.3,0.1

Type RM Length L Ch R = 1 ,57653   ,425,425,425
BEGIN DESCRIPTION:
Lytle Creek 59575.975
END DESCRIPTION:
XS GIS Cut Line= 5
      1609691.65      6808227.01      1610319.43      6808639.07
      1610551.05      6808844.69      1610604.66      6809064.34
      1610958.41      6809261.43
#Sta/Elev= 30
  3856.4  1806.1  4228.5 1804.79  4264.7  1802.3  4291.7 1798.78  4364.1 1799.33
  4373.2 1797.22  4379.2 1793.87  4415.3 1799.24  4430.4 1803.75  4458.5 1805.07
  4502.8 1803.55  4674.2 1803.71  4780.4 1802.34  4941.3 1804.45  4961.6 1805.63
  4971.9 1803.69  4982.2 1798.36  4990.2  1792.4  4991.7  1791.9  5004.4  1792.4
  5023.4 1797.37  5085.8 1797.51  5109.1 1800.56  5176.8 1804.81  5224.2 1805.84
  5256.1 1806.69  5372.5 1807.41  5404.3 1808.73  5431.7 1807.49  5548.1 1807.83
#Mann= 7 ,-1 , 0
  3856.4     .05       0  4941.3     .12       0  4990.2     .07       0
  5004.4     .12       0  5109.1     .05       0  5224.2     .12       0
  5256.1     .05       0
Bank Sta=4990.2,5004.4
XS Rating Curve= 0 ,0
Exp/Cntr=0.3,0.1

Type RM Length L Ch R = 1 ,57228   ,459,459,459
BEGIN DESCRIPTION:
Lytle Creek 57862.05
END DESCRIPTION:
XS GIS Cut Line= 3
      1609411.92      6808436.71      1610251.88      6809147.27
      1610788.35      6809220.19
#Sta/Elev= 30
  3914.5 1806.96  3924.7 1806.07  3945.5  1805.8  4300.4  1803.8    4797 1802.28
  4839.9 1802.51  4868.4 1803.86    4897 1803.04  4953.3 1803.31  4967.3 1802.83
    4975 1799.11  4981.6 1800.19  4989.3 1793.22  4995.9 1794.91  5005.5 1790.71
    5007 1790.21  5021.5 1790.71  5027.9 1795.07    5038 1795.95  5055.2 1795.11
  5068.3 1796.82  5088.5 1797.46  5132.7 1797.45  5199.5 1800.45  5229.8 1799.98
  5300.4 1804.05  5320.6  1804.1  5391.2 1806.47  5432.6 1807.36  5556.1 1808.02
#Mann= 3 ,-1 , 0
  3914.5     .05       0  5005.5     .05       0  5021.5     .05       0
Bank Sta=5005.5,5021.5
XS Rating Curve= 0 ,0
Exp/Cntr=0.3,0.1

Type RM Length L Ch R = 1 ,56769   ,381,381,381
BEGIN DESCRIPTION:
Lytle Creek 57486.78
END DESCRIPTION:
XS GIS Cut Line= 5
      1609318.17      6808457.54      1610113.45      6809201.79
       1610202.4      6809444.15      1610318.99      6809684.41
      1610520.03      6809768.11
#Sta/Elev= 30
  3636.5 1805.93  4129.8 1803.06  4646.1 1801.69  4726.3 1802.42  4771.7 1801.44
  4785.6  1802.2  4811.9  1801.7  4832.7 1799.86  4849.5 1795.04  4857.8  1794.6
  4893.6 1794.85  4913.4 1797.25    4937 1795.87    4956 1796.57  4974.5 1795.73
  4979.8 1794.41  4983.3 1791.94  4988.8 1791.94  4995.1 1788.45  4996.6 1787.95
  5011.1 1788.45  5020.1 1795.26  5032.6 1800.59  5042.6 1803.24  5087.8 1801.91
    5161 1801.75  5321.2 1804.55  5326.6 1803.73  5355.8 1804.94  5468.7 1805.39
#Mann= 6 ,-1 , 0
  3636.5     .05       0  4726.3     .12       0  4811.9     .05       0
    4937     .12       0  4995.1     .07       0  5011.1     .05       0
Bank Sta=4995.1,5011.1
XS Rating Curve= 0 ,0
Exp/Cntr=0.3,0.1

Type RM Length L Ch R = 1 ,56388   ,350,350,350
BEGIN DESCRIPTION:
Lytle Creek 57107.41
END DESCRIPTION:
XS GIS Cut Line= 5
      1609394.43      6808601.22      1609841.84      6809216.51
      1609869.06      6809389.46      1609923.19      6809594.01
      1610233.94        6809737.
#Sta/Elev= 30
  4105.6 1804.99  4389.7 1802.87  4839.2 1801.96  4888.1 1803.09  4916.1 1802.13
  4921.2 1800.97  4938.7 1799.58    4959 1796.33  4978.6 1790.23  4983.7 1793.57
  4989.3 1789.84  4991.5  1787.1    4993  1786.6  5007.5  1787.1  5009.6 1789.12
  5019.7 1790.66  5057.1 1794.17    5071 1794.89  5080.2 1796.43  5085.3 1795.93
  5112.3 1799.65  5131.9 1800.26  5220.6  1801.8  5256.8 1801.45    5266 1800.69
  5324.5 1800.57  5530.2 1802.75  5552.2 1802.26  5565.2 1803.08  5595.1 1803.26
#Mann= 7 ,-1 , 0
  4105.6     .05       0  4839.2     .12       0  4991.5     .07       0
  5007.5     .12       0  5057.1     .05       0  5131.9     .12       0
  5220.6     .05       0
Bank Sta=4991.5,5007.5
XS Rating Curve= 0 ,0
Exp/Cntr=0.3,0.1

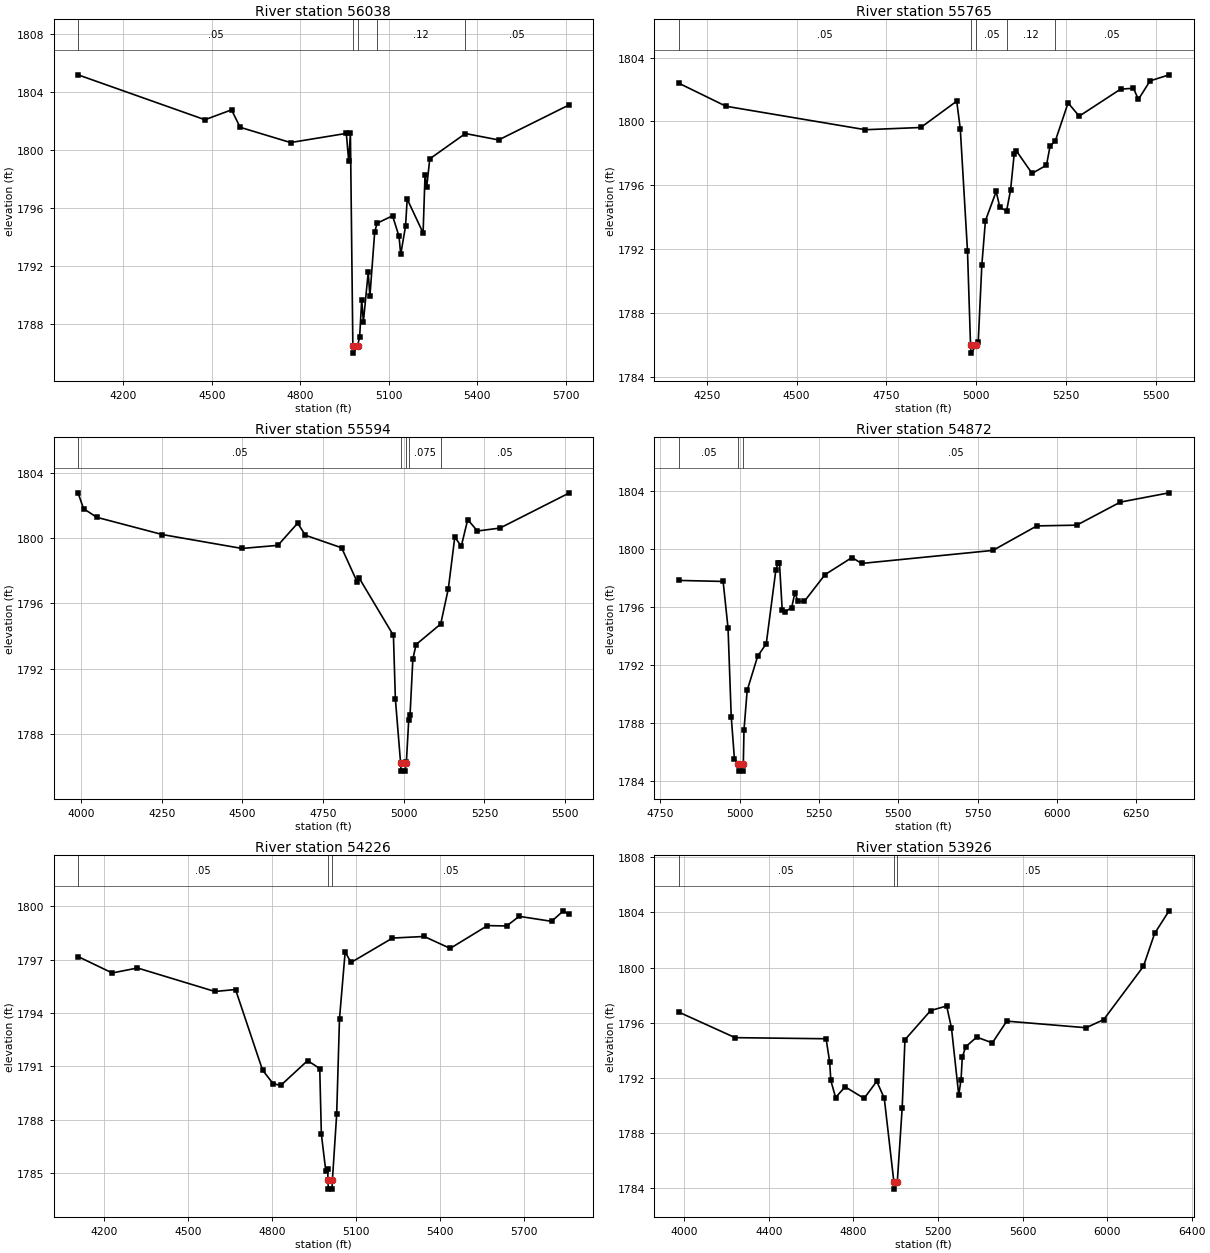
Type RM Length L Ch R = 1 ,56038   ,273,273,273
BEGIN DESCRIPTION:
Mapping XS 555dad79
END DESCRIPTION:
XS GIS Cut Line= 5
      1609351.83      6808569.23      1609401.84      6809291.85
      1609833.83      6809520.07       1609921.3      6809602.31
      1610219.82      6809739.93
#Sta/Elev= 30
  4047.2 1805.17    4477 1802.08  4567.2 1802.76  4596.2 1801.56  4767.1 1800.51
  4956.1 1801.14  4964.2 1799.21  4969.9 1801.17  4978.2 1786.52  4979.7 1786.02
  4994.2 1786.52  5001.3 1787.16  5008.2 1789.69  5013.9 1788.18  5030.3  1791.6
  5035.9 1789.92  5052.3 1794.38  5060.5 1794.96  5112.7 1795.47  5134.7 1794.05
  5140.3 1792.81  5156.7 1794.75  5162.3 1796.62  5216.2 1794.29  5222.7 1798.27
  5228.4 1797.45  5238.8 1799.39  5359.5 1801.13  5472.1 1800.69  5708.9 1803.08
#Mann= 5 ,-1 , 0
  4047.2     .05       0  4978.2     .05       0  4994.2     .05       0
  5060.5     .12       0  5359.5     .05       0
Bank Sta=4978.2,4994.2
XS Rating Curve= 0 ,0
Exp/Cntr=0.3,0.1

Type RM Length L Ch R = 1 ,55765   ,171,171,171
BEGIN DESCRIPTION:
Lytle Creek 56486.22
END DESCRIPTION:
XS GIS Cut Line= 5
       1609336.8      6809055.48      1609442.13      6809658.26
      1609652.92      6809660.29       1609906.1      6809666.05
      1610187.89      6809736.79
#Sta/Elev= 30
  4171.3  1802.4  4303.4 1800.95  4691.6 1799.48  4846.1 1799.62  4946.1 1801.27
  4956.1 1799.52  4976.1 1791.89  4984.6 1785.98  4986.1 1785.48  5000.6 1785.98
  5006.1  1786.2  5016.1 1791.01  5026.1 1793.78  5056.1 1795.61  5066.1 1794.62
    5085 1794.39  5096.1 1795.69  5106.1 1797.93  5112.2 1798.16  5156.1 1796.74
  5196.2 1797.26  5206.2 1798.45  5220.8 1798.78  5256.4 1801.16  5287.4 1800.33
  5402.5 1802.02  5438.5 1802.08  5452.3 1801.38  5484.8 1802.54  5537.8 1802.92
#Mann= 5 ,-1 , 0
  4171.3     .05       0  4984.6     .05       0  5000.6     .05       0
    5085     .12       0  5220.8     .05       0
Bank Sta=4984.6,5000.6
XS Rating Curve= 0 ,0
Exp/Cntr=0.3,0.1

Type RM Length L Ch R = 1 ,55594   ,722,722,722
BEGIN DESCRIPTION:
Lytle Creek 56301.97
END DESCRIPTION:
XS GIS Cut Line= 5
      1609315.97      6809071.02      1609426.48      6809653.98
      1609502.01      6809839.51      1609736.25      6809819.15
      1610227.36      6809817.01
#Sta/Elev= 30
  3990.8 1802.78  4007.7 1801.81  4048.8 1801.28  4252.4 1800.22  4498.7 1799.37
  4610.1 1799.56  4671.3 1800.92  4695.3 1800.18  4807.5 1799.41  4856.2  1797.3
  4861.2 1797.58  4968.1 1794.04  4974.1 1790.15  4990.3 1786.22  4991.8 1785.72
  5004.8 1785.72  5006.3 1786.22  5008.3 1786.31  5015.6 1788.88  5019.6 1789.16
  5028.3 1792.59  5038.3 1793.48  5114.6 1794.74  5138.3 1796.91  5158.3 1800.07
  5178.3  1799.5  5198.3 1801.14  5228.3 1800.44  5298.3 1800.62  5510.7 1802.75
#Mann= 5 ,-1 , 0
  3990.8     .05       0  4990.3     .03       0  5006.3     .05       0
  5015.6    .075       0  5114.6     .05       0
Bank Sta=4990.3,5006.3
XS Rating Curve= 0 ,0
Exp/Cntr=0.3,0.1

Type RM Length L Ch R = 1 ,54872   ,646,646,646
BEGIN DESCRIPTION:
Lytle Creek 55798.38
END DESCRIPTION:
XS GIS Cut Line= 4
      1609269.83      6810369.96      1609583.17       6810399.3
      1609975.54      6810382.47      1610709.79      6809975.97
#Sta/Elev= 30
  4807.3 1797.82  4947.6 1797.75  4963.1 1794.54  4973.2 1788.43  4983.2 1785.53
  4995.3 1785.17  4996.8 1784.67  5009.8 1784.67  5011.3 1785.17  5013.4 1787.49
  5023.4 1790.23  5056.5 1792.59  5083.7 1793.46  5113.8 1798.52  5120.4 1798.99
  5125.4 1798.99  5133.9 1795.79  5143.9 1795.67  5163.9 1795.95  5173.9 1796.97
  5183.9 1796.37  5203.9 1796.38    5269 1798.22  5354.1  1799.4  5384.1 1798.99
  5798.4 1799.89    5937 1801.58  6062.8 1801.63  6200.3 1803.22    6354 1803.86
#Mann= 3 ,-1 , 0
  4807.3     .05       0  4995.3     .03       0  5011.3     .05       0
Bank Sta=4995.3,5011.3
XS Rating Curve= 0 ,0
Exp/Cntr=0.3,0.1

Type RM Length L Ch R = 1 ,54226   ,300,300,300
BEGIN DESCRIPTION:
Lytle Creek 55595.381
END DESCRIPTION:
XS GIS Cut Line= 5
       1608870.7      6810524.27      1609654.48      6810972.78
      1609720.92      6810982.35      1609900.61      6810472.27
      1610103.31      6810341.85
#Sta/Elev= 30
  4106.4 1797.17  4228.5 1796.25  4318.7 1796.53  4595.3 1795.21  4668.9 1795.32
  4765.3  1790.8  4802.6 1790.04  4830.1 1789.93  4926.5 1791.33  4969.7 1790.88
  4975.5  1787.2  4991.2 1785.14  4998.5 1785.22  4998.9 1784.61  5000.4 1784.11
  5013.4 1784.11  5014.9 1784.61  5030.2 1788.31  5040.3 1793.69  5060.5 1797.43
  5081.5 1796.84  5229.6 1798.21  5342.8  1798.3  5435.7 1797.63  5568.9 1798.91
  5637.5 1798.89    5682 1799.43  5797.9 1799.15  5840.2 1799.74  5858.4 1799.54
#Mann= 3 ,-1 , 0
  4106.4     .05       0  4998.9    .035       0  5014.9     .05       0
Bank Sta=4998.9,5014.9
XS Rating Curve= 0 ,0
Exp/Cntr=0.3,0.1

Type RM Length L Ch R = 1 ,53926   ,762,762,762
BEGIN DESCRIPTION:
Lytle Creek 54428.227
END DESCRIPTION:
XS GIS Cut Line= 4
      1608783.04      6810569.69      1609001.97      6810980.83
      1609511.97      6811231.46      1610674.64      6811780.87
#Sta/Elev= 30
  3973.2 1796.77  4240.4 1794.91  4670.7 1794.83  4687.5 1793.17  4693.2  1791.8
  4715.7 1790.56  4760.6 1791.34  4850.6  1790.5  4910.4 1791.74    4946 1790.51
  4991.5 1784.41    4993 1783.91  5007.5 1784.41  5030.7 1789.82  5043.8 1794.76
  5165.5 1796.88  5241.1 1797.21  5263.9 1795.61  5298.2 1790.74  5309.2 1791.87
    5315  1793.5  5331.4 1794.25  5383.2 1794.95  5457.1 1794.53  5525.4 1796.11
  5900.6 1795.63  5983.9 1796.22  6171.9 1800.09  6224.8 1802.48  6293.2 1804.12
#Mann= 3 ,-1 , 0
  3973.2     .05       0  4991.5    .035       0  5007.5     .05       0
Bank Sta=4991.5,5007.5
XS Rating Curve= 0 ,0
Exp/Cntr=0.3,0.1

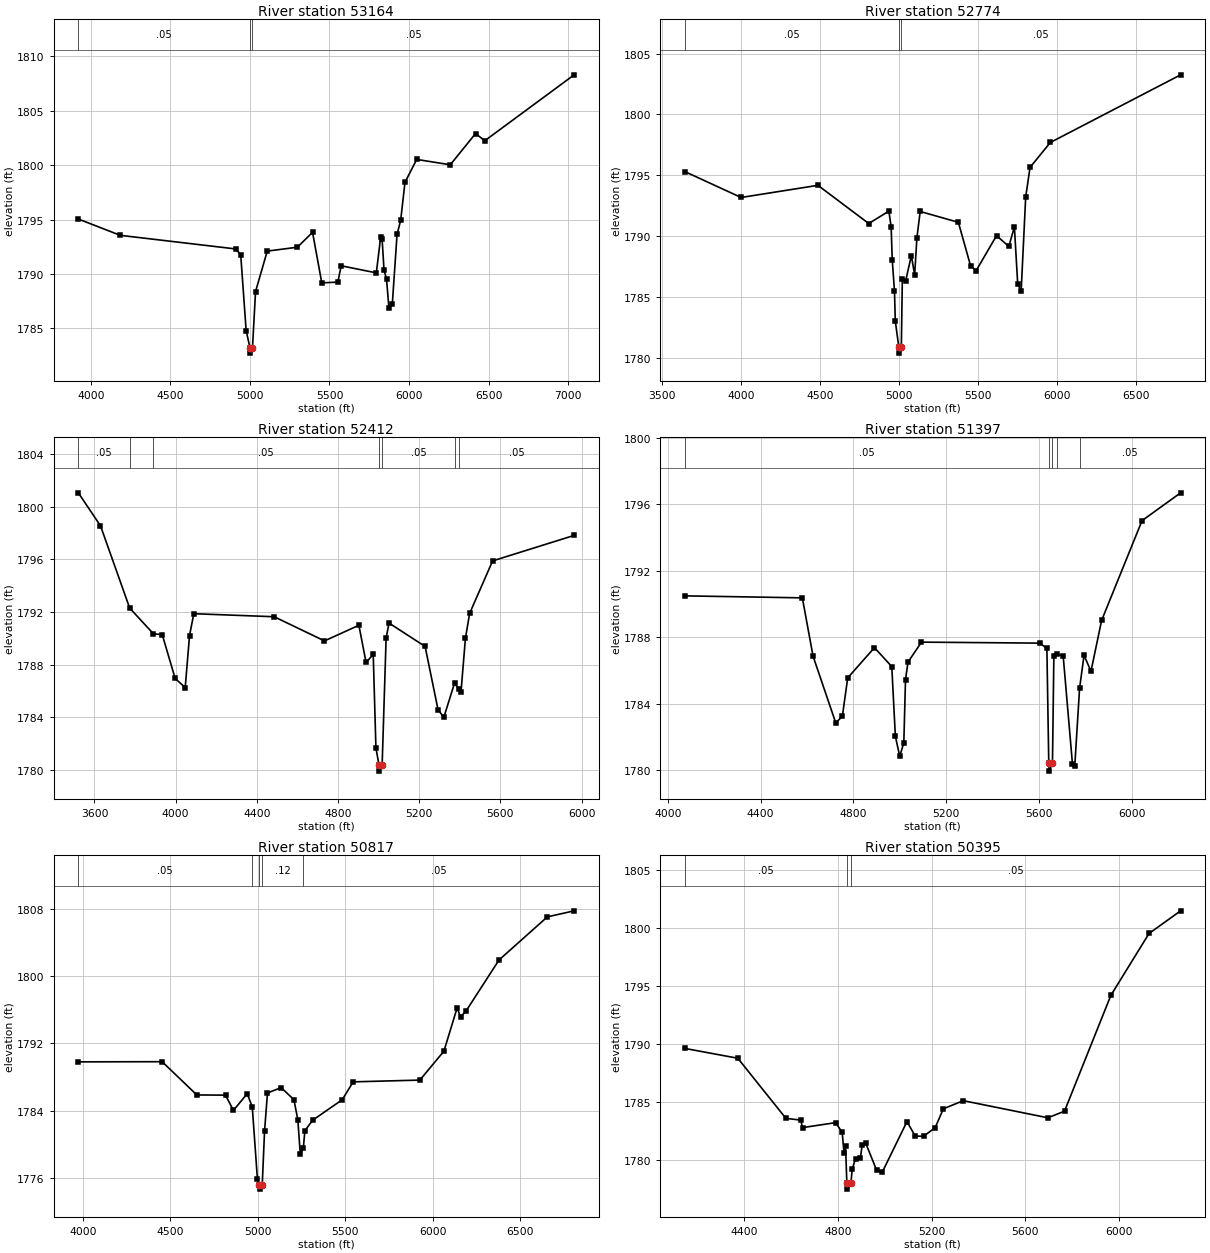
Type RM Length L Ch R = 1 ,53164   ,390,390,390
BEGIN DESCRIPTION:
Lytle Creek 53829.901
END DESCRIPTION:
XS GIS Cut Line= 4
      1608656.59      6810764.74      1608607.73      6811434.22
      1608965.91      6811626.96      1610704.98      6812687.99
#Sta/Elev= 30
    3922 1795.05    4186 1793.55  4910.5  1792.3  4942.2 1791.77  4976.3  1784.8
  5000.2 1783.22  5001.7 1782.72  5016.2 1783.22  5035.4 1788.38  5108.9  1792.1
  5298.6 1792.46  5393.5 1793.83  5451.6 1789.18  5552.3 1789.25  5573.6 1790.75
  5794.2  1790.1  5821.4 1793.36  5830.7 1793.18  5842.7 1790.33  5858.2 1789.55
  5873.6 1786.85  5894.9 1787.28  5924.4 1793.63  5947.2 1794.93  5974.3 1798.43
  6047.9 1800.53  6258.9 1800.04  6417.7 1802.91  6475.8 1802.25  7037.2 1808.31
#Mann= 3 ,-1 , 0
    3922     .05       0  5000.2    .035       0  5016.2     .05       0
Bank Sta=5000.2,5016.2
XS Rating Curve= 0 ,0
Exp/Cntr=0.3,0.1

Type RM Length L Ch R = 1 ,52774   ,362,362,362
BEGIN DESCRIPTION:
Lytle Creek 53266.654
END DESCRIPTION:
XS GIS Cut Line= 4
      1608637.64      6810713.04      1608531.31      6811727.05
      1608757.24      6811943.93      1610130.15      6813115.98
#Sta/Elev= 30
    3645  1795.3  4001.4 1793.17  4487.5 1794.17  4809.2 1791.03  4936.5 1792.05
  4950.7 1790.78  4957.9 1788.03  4972.1 1785.46  4977.1 1783.02  4999.4 1780.88
  5000.9 1780.38  5015.4 1780.88  5021.7 1786.46  5042.5 1786.31  5078.8 1788.39
  5099.6  1786.8  5113.9 1789.86  5134.7 1792.02  5376.3 1791.13  5454.2 1787.53
  5489.4 1787.17  5617.8 1790.03  5695.8 1789.15  5730.9 1790.76  5751.8 1786.07
  5773.7 1785.48  5802.3 1793.19  5829.7 1795.64  5958.2 1797.69  6782.9 1803.25
#Mann= 3 ,-1 , 0
    3645     .05       0  4999.4    .035       0  5015.4     .05       0
Bank Sta=4999.4,5015.4
XS Rating Curve= 0 ,0
Exp/Cntr=0.3,0.1

Type RM Length L Ch R = 1 ,52412   ,1015,1015,1015
BEGIN DESCRIPTION:
Lytle Creek 52677.451
END DESCRIPTION:
XS GIS Cut Line= 3
      1607617.91      6811200.49      1608631.99      6812261.77
      1609265.01      6813003.76
#Sta/Elev= 30
  3520.5 1801.07  3629.7 1798.56  3773.5  1792.3  3890.6 1790.34  3933.9 1790.28
  3997.7 1786.94  4047.1 1786.25  4068.5 1790.21  4089.5 1791.87  4485.5 1791.64
  4733.4  1789.8  4902.9 1790.99  4938.4 1788.16  4973.6 1788.77  4986.9 1781.66
  5001.6 1780.39  5003.1 1779.89  5017.6 1780.39  5037.1 1790.01  5051.3 1791.16
  5229.2 1789.38  5292.9 1784.57  5321.4 1783.98  5374.1 1786.58  5396.6 1786.11
    5406 1785.89  5427.9    1790  5448.8  1791.9  5561.9 1795.89  5963.7 1797.83
#Mann= 7 ,-1 , 0
  3520.5     .05       0  3773.5     .12       0  3890.6     .05       0
  5001.6    .035       0  5017.6     .05       0  5374.1     .12       0
  5396.6     .05       0
Bank Sta=5001.6,5017.6
XS Rating Curve= 0 ,0
Exp/Cntr=0.3,0.1

Type RM Length L Ch R = 1 ,51397   ,580,580,580
BEGIN DESCRIPTION:
Lytle Creek 52085.131
END DESCRIPTION:
XS GIS Cut Line= 4
      1607058.67      6812453.32      1607904.32      6812837.79
      1608143.83      6812940.44      1609091.22      6812913.24
#Sta/Elev= 30
  4073.2 1790.49  4579.9 1790.37    4626 1786.87  4723.8 1782.86  4752.3 1783.25
  4775.4 1785.56  4890.7 1787.38  4965.4 1786.24  4980.9 1782.05  4999.8 1780.85
  5017.3 1781.67  5024.6 1785.46  5035.4 1786.51  5093.4 1787.71    5604 1787.65
    5634 1787.33  5642.1 1780.46  5643.6 1779.96  5658.1 1780.46  5664.1  1786.9
  5675.8 1786.99  5704.1  1786.9  5744.1 1780.41  5754.1 1780.25  5774.9 1784.93
  5794.1 1786.92  5824.1 1785.96  5869.8 1789.01  6044.2 1795.01  6210.5 1796.68
#Mann= 5 ,-1 , 0
  4073.2     .05       0  5642.1     .05       0  5658.1     .05       0
  5675.8     .12       0  5774.9     .05       0
Bank Sta=5642.1,5658.1
XS Rating Curve= 0 ,0
Exp/Cntr=0.3,0.1

Type RM Length L Ch R = 1 ,50817   ,422,422,422
BEGIN DESCRIPTION:
Lytle Creek 51500.99
END DESCRIPTION:
XS GIS Cut Line= 3
      1606769.64      6812838.68      1607677.77      6813314.43
      1609389.49      6813901.21
#Sta/Elev= 30
  3974.8 1789.81  4453.8 1789.83  4652.3 1785.87  4816.2 1785.85  4861.4 1784.03
  4940.4 1786.02  4969.2 1784.45  4998.5  1775.9  5010.2 1775.16  5011.7 1774.66
  5026.2 1775.16  5039.4 1781.55  5056.2 1786.11  5134.5 1786.74  5207.3 1785.31
  5229.6 1782.93  5243.9  1778.8  5261.2 1779.55  5269.9 1781.61  5314.2 1782.86
  5483.4  1785.3  5546.1 1787.43  5927.3 1787.64  6064.8 1791.08  6140.3 1796.23
  6159.9 1795.16  6191.6 1795.87    6380 1801.94  6656.2 1807.07  6809.5 1807.79
#Mann= 5 ,-1 , 0
  3974.8     .05       0  4969.2     .12       0  5010.2     .07       0
  5026.2     .12       0  5261.2     .05       0
Bank Sta=5010.2,5026.2
XS Rating Curve= 0 ,0
Exp/Cntr=0.3,0.1

Type RM Length L Ch R = 1 ,50395   ,659,659,659
BEGIN DESCRIPTION:
Lytle Creek 50902.465
END DESCRIPTION:
XS GIS Cut Line= 3
      1606925.66      6813047.83      1607513.26       6813686.2
      1608435.94      6814527.23
#Sta/Elev= 30
    4147 1789.61  4373.2 1788.76  4578.5 1783.56    4642 1783.41  4649.4 1782.76
  4790.6 1783.19  4818.9 1782.35  4826.3 1780.57  4833.1 1781.19  4838.6 1777.94
  4840.1 1777.44  4855.9 1777.94  4861.5 1779.17  4875.6 1780.08  4896.6 1780.14
    4904 1781.29  4918.2 1781.47  4965.5 1779.08  4989.1 1778.88  5095.2 1783.28
  5130.3 1782.03  5165.8 1782.01  5215.4 1782.75  5250.6 1784.39  5335.7 1785.09
  5696.5 1783.61  5767.5 1784.18  5965.4  1794.2  6128.3 1799.55  6263.1 1801.51
#Mann= 3 ,-1 , 0
    4147     .05       0  4838.6     .05       0  4855.9     .05       0
Bank Sta=4838.6,4855.9
XS Rating Curve= 0 ,0
Exp/Cntr=0.3,0.1

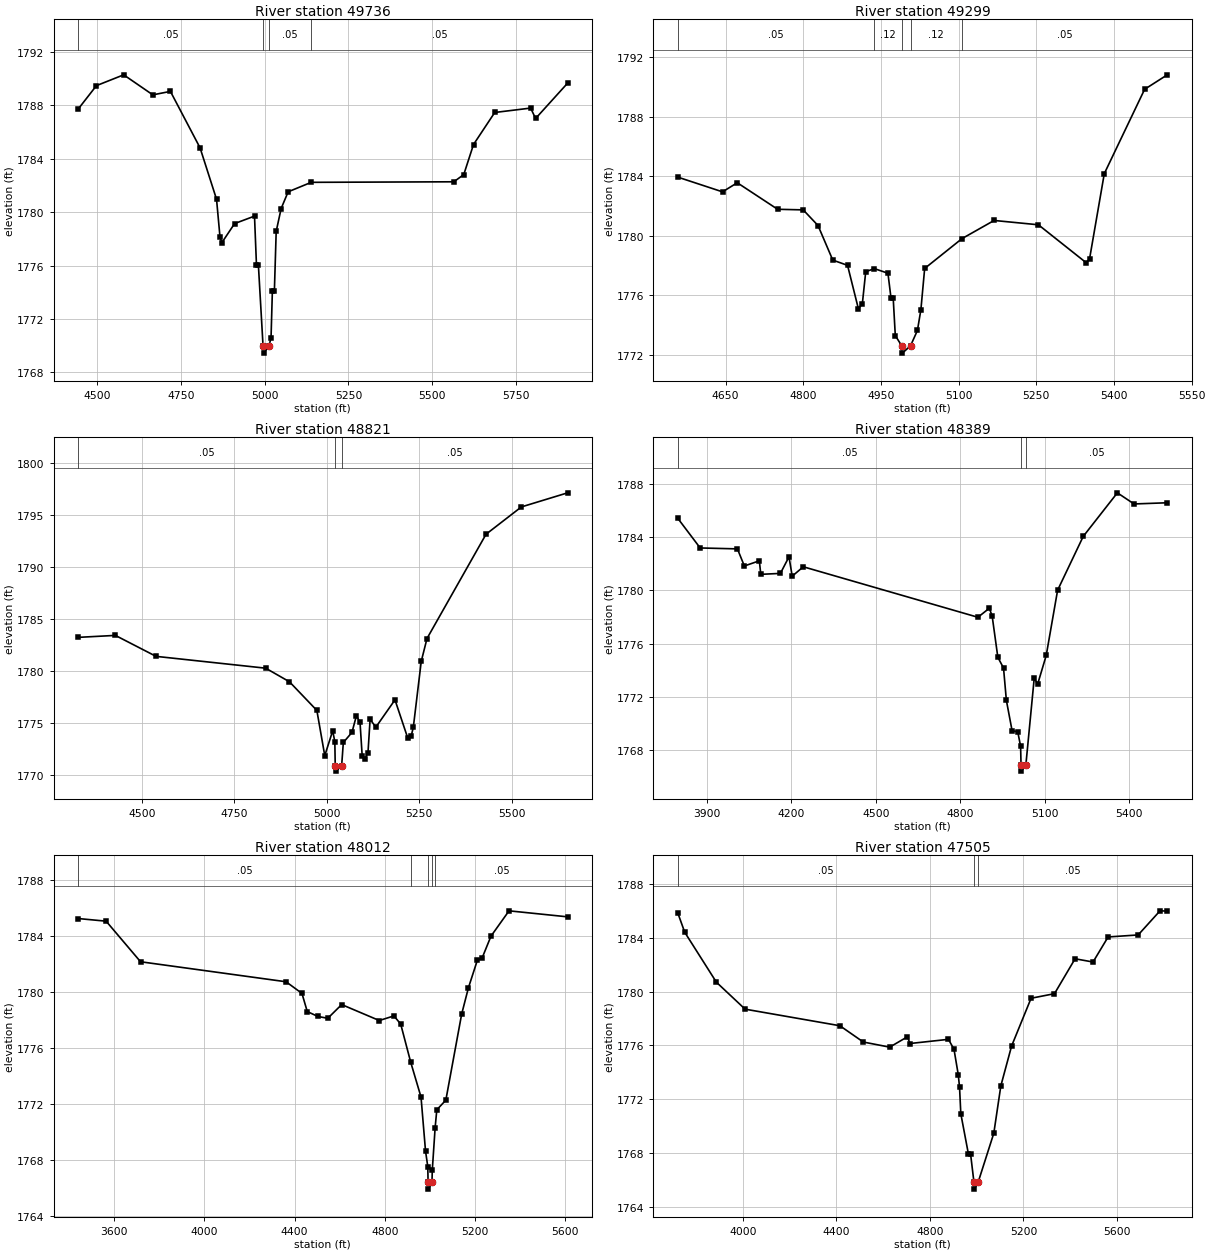
Type RM Length L Ch R = 1 ,49736   ,437,437,437
BEGIN DESCRIPTION:
Lytle Creek 50408.91
END DESCRIPTION:
XS GIS Cut Line= 3
      1606643.27      6813785.65      1607153.65      6814066.88
      1607875.81      6814569.52
#Sta/Elev= 30
  4442.2 1787.71  4497.2 1789.48  4578.6 1790.29  4665.7 1788.79  4718.2 1789.05
  4806.8 1784.82    4856 1780.97  4866.4 1778.12  4872.1 1777.73  4909.9 1779.15
  4969.4 1779.71  4975.3 1776.02    4981 1776.05    4995 1769.95  4996.5 1769.45
  5012.3 1769.95  5018.8 1770.61  5022.8 1774.12  5028.8 1774.12  5034.2 1778.57
    5049 1780.28  5069.9 1781.53  5138.9 1782.24  5564.8 1782.28  5594.5 1782.82
  5623.6 1785.07    5687 1787.47  5794.3  1787.8  5809.1 1787.02  5904.8 1789.67
#Mann= 4 ,-1 , 0
  4442.2     .05       0    4995    .035       0  5012.3     .05       0
  5138.9     .05       0
Bank Sta=4995,5012.3
XS Rating Curve= 0 ,0
Exp/Cntr=0.3,0.1

Type RM Length L Ch R = 1 ,49299   ,478,478,478
BEGIN DESCRIPTION:
Lytle Creek 49971.07
END DESCRIPTION:
XS GIS Cut Line= 3
      1606643.23      6814167.57      1606959.21      6814438.41
      1607358.49      6814785.61
#Sta/Elev= 30
  4557.6 1783.94  4644.2 1782.95  4672.7 1783.56  4750.6 1781.78    4800 1781.74
  4828.6 1780.69  4857.1 1778.37  4885.6 1778.02  4906.5 1775.11  4914.2 1775.45
  4920.7 1777.59  4937.3  1777.8  4963.6 1777.49  4969.6  1775.8  4973.8  1775.8
  4977.8 1773.31    4990 1772.63  4991.5 1772.13  5007.3 1772.63  5020.5 1773.65
  5027.2 1775.04  5034.5 1777.81  5106.5 1779.81  5168.6 1781.03  5254.1 1780.74
  5346.2  1778.2  5352.8 1778.44  5381.3 1784.17  5459.2 1789.83  5502.9  1790.8
#Mann= 5 ,-1 , 0
  4557.6     .05       0  4937.3     .12       0    4990     .07       0
  5007.3     .12       0  5106.5     .05       0
Bank Sta=4990,5007.3
XS Rating Curve= 0 ,0
Exp/Cntr=0.3,0.1

Type RM Length L Ch R = 1 ,48821   ,432,432,432
BEGIN DESCRIPTION:
Lytle Creek 49573.62
END DESCRIPTION:
XS GIS Cut Line= 3
      1606513.22      6814197.15      1606499.24      6814512.75
      1607014.77      6815379.39
#Sta/Elev= 30
  4327.4 1783.22  4428.4 1783.41  4538.5 1781.39  4835.1 1780.25  4899.3 1778.94
  4973.4 1776.18  4994.8 1771.82  5016.2 1774.22    5022 1773.17  5023.1 1770.83
  5024.6 1770.33  5040.4 1770.83    5045 1773.09  5068.3 1774.06  5080.4 1775.67
  5090.2 1775.02    5096 1771.79  5103.2 1771.54  5111.6 1772.06  5117.4 1775.32
    5133 1774.57  5184.7  1777.2  5219.6 1773.48  5228.5 1773.71  5234.3 1774.55
  5255.7  1780.9  5271.3 1783.11    5431 1793.16  5526.5 1795.79  5651.7 1797.15
#Mann= 3 ,-1 , 0
  4327.4     .05       0  5023.1     .05       0  5040.4     .05       0
Bank Sta=5023.1,5040.4
XS Rating Curve= 0 ,0
Exp/Cntr=0.3,0.1

Type RM Length L Ch R = 1 ,48389   ,377,377,377
BEGIN DESCRIPTION:
Lytle Creek 49035.02
END DESCRIPTION:
XS GIS Cut Line= 3
      1606542.45      6813939.37      1606362.38      6814924.01
       1606466.1       6815653.3
#Sta/Elev= 30
    3797 1785.46  3876.9 1783.21  4009.1 1783.14  4033.7 1781.85  4086.9 1782.24
    4092 1781.22  4161.6 1781.29  4192.1 1782.54  4203.5 1781.08  4242.9 1781.79
  4862.6 1777.98    4903 1778.66  4913.1 1778.08  4933.3 1774.96  4953.5 1774.15
  4963.6 1771.71  4983.8 1769.43    5004 1769.33  5014.1 1768.25  5015.6 1766.87
  5017.1 1766.37  5032.9 1766.87  5062.4 1773.38  5074.7 1772.94    5105  1775.1
  5145.4 1780.02  5236.3 1784.08  5357.5 1787.37  5416.7 1786.53  5534.6 1786.62
#Mann= 3 ,-1 , 0
    3797     .05       0  5015.6     .05       0  5032.9     .05       0
Bank Sta=5015.6,5032.9
XS Rating Curve= 0 ,0
Exp/Cntr=0.3,0.1

Type RM Length L Ch R = 1 ,48012   ,507,507,507
BEGIN DESCRIPTION:
Lytle Creek 48676.464
END DESCRIPTION:
XS GIS Cut Line= 3
      1606569.59      6813740.04       1606021.8      6815023.04
      1606045.15      6815797.54
#Sta/Elev= 30
  3440.2 1785.28  3564.8 1785.09  3717.3 1782.19  4362.2 1780.76  4432.6 1779.93
  4456.2 1778.63  4503.4 1778.28  4547.1 1778.15  4608.7 1779.13  4775.4 1777.99
  4840.2 1778.32  4870.2 1777.74  4914.8    1775  4960.3 1772.52  4980.3 1768.66
  4990.3 1767.55  4991.6 1766.44  4993.1 1765.94  5008.9 1766.44  5010.3 1767.31
  5022.9 1770.34  5030.3 1771.61  5070.3  1772.3  5140.3 1778.44  5170.4 1780.33
  5210.4 1782.32  5230.4 1782.43  5270.4 1784.02  5350.4 1785.83  5610.1  1785.4
#Mann= 5 ,-1 , 0
  3440.2     .05       0  4914.8     .12       0  4991.6     .07       0
  5008.9     .12       0  5022.9     .05       0
Bank Sta=4991.6,5008.9
XS Rating Curve= 0 ,0
Exp/Cntr=0.3,0.1

Type RM Length L Ch R = 1 ,47505   ,807,807,807
BEGIN DESCRIPTION:
Mapping XS 1c9a4dce
END DESCRIPTION:
XS GIS Cut Line= 4
      1604820.01      6814331.81      1605255.39      6814628.19
      1605738.43      6815768.98      1605998.33      6815969.02
#Sta/Elev= 30
  3721.3 1785.86  3751.5  1784.4    3887 1780.69  4009.7 1778.69  4414.9 1777.46
  4515.1 1776.25  4627.9 1775.87  4703.9 1776.64  4714.7 1776.14  4879.2 1776.45
  4902.9 1775.71  4921.1 1773.83  4926.6  1772.9    4932 1770.93  4964.5 1767.94
  4973.9 1767.92  4988.3 1765.83  4989.8 1765.33  5005.9 1765.83  5073.1 1769.48
  5103.2    1773  5149.1 1775.95  5232.5  1779.5  5332.6 1779.84  5420.6 1782.43
  5497.4 1782.19  5561.8 1784.05  5690.4  1784.2  5783.8 1785.99  5814.8 1785.97
#Mann= 3 ,-1 , 0
  3721.3     .05       0  4988.3     .05       0  5005.9     .05       0
Bank Sta=4988.3,5005.9
XS Rating Curve= 0 ,0
Exp/Cntr=0.3,0.1