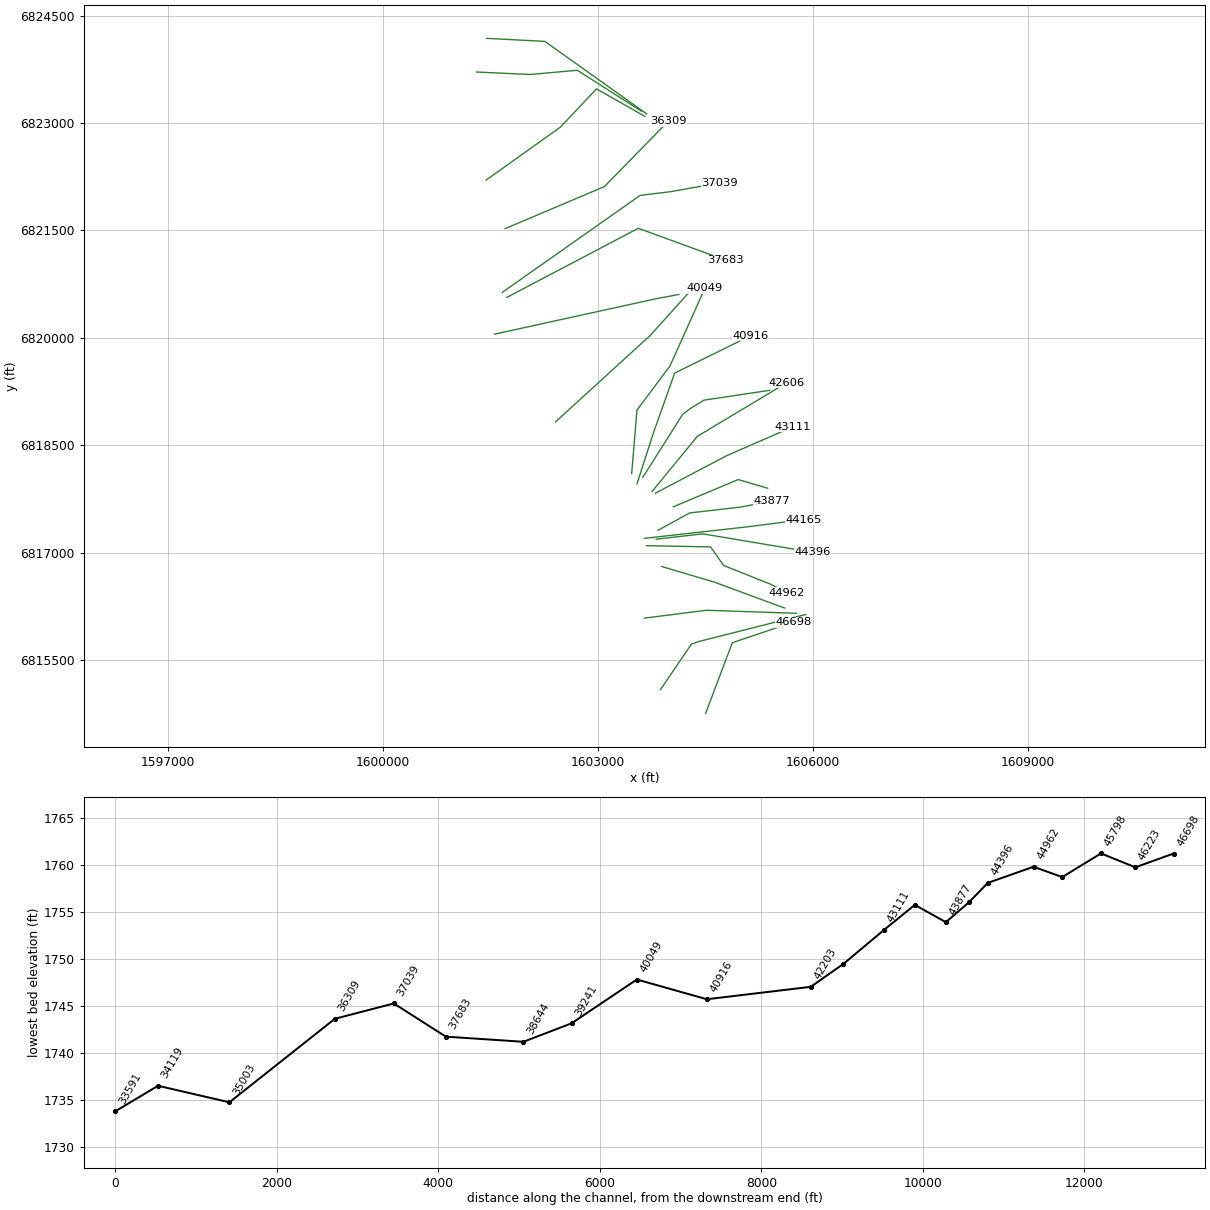
HEC-RAS study Lytle Creek.prj: Lytle Creek Base Level Engineering

--- Lytle Creek.g02 (geometry) --- (continued)

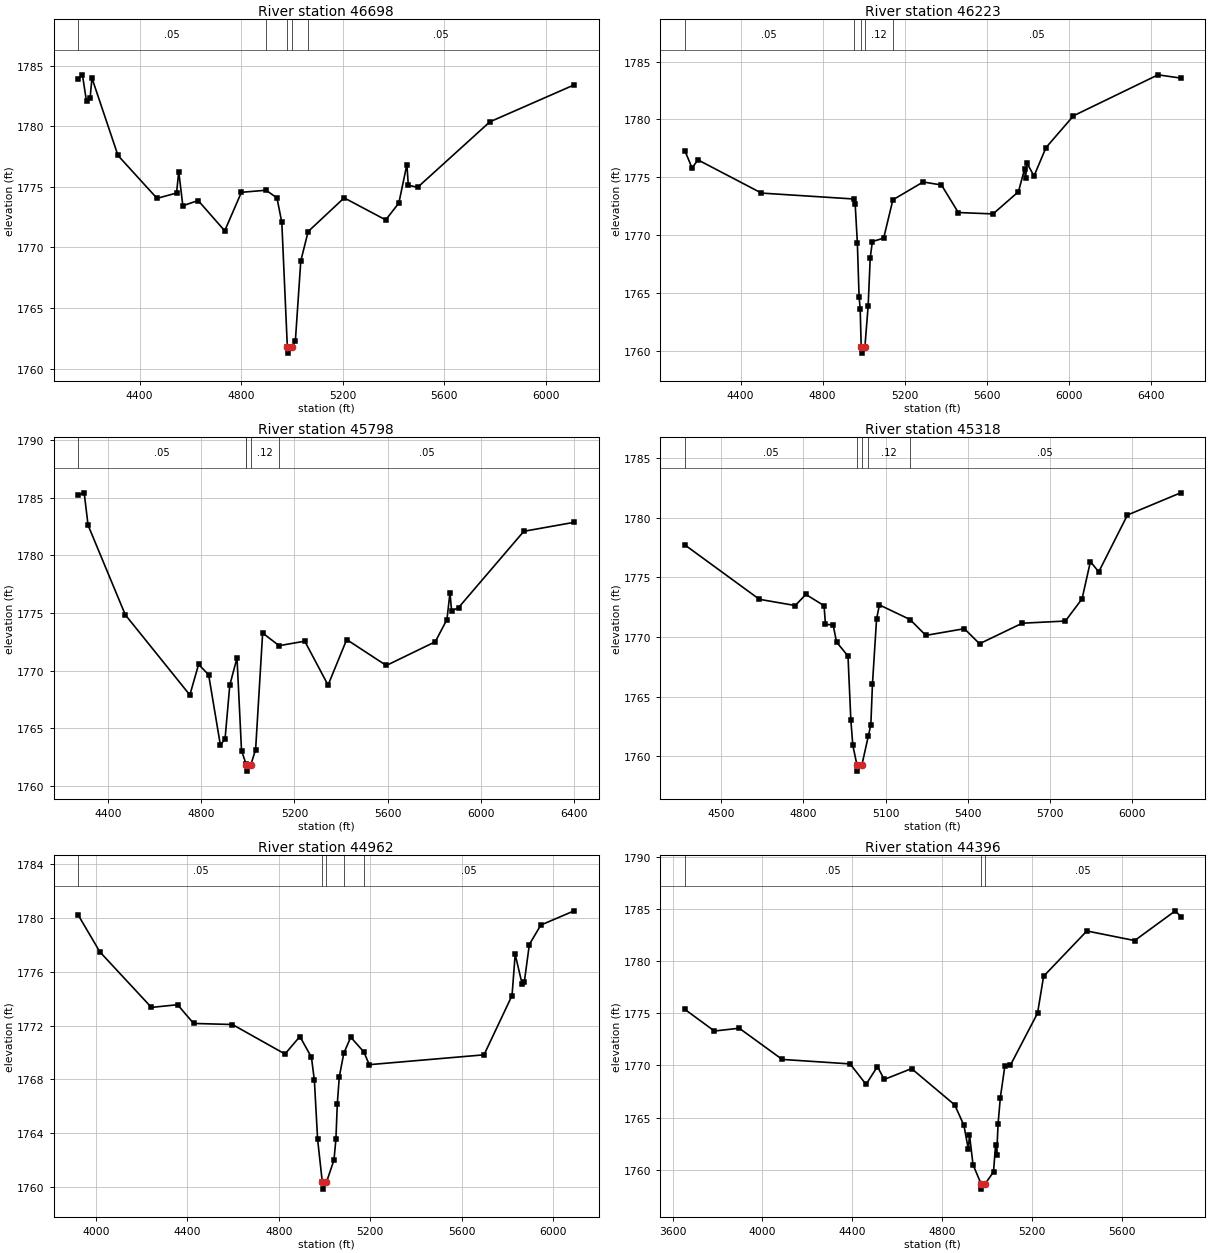
Type RM Length L Ch R = 1 ,46698   ,475,475,475
BEGIN DESCRIPTION:
Lytle Creek 47289.81
END DESCRIPTION:
XS GIS Cut Line= 3
      1604504.39      6814757.78      1604876.98        6815744.
      1605729.62      6816032.26
#Sta/Elev= 30
  4158.4 1783.94  4174.5 1784.25  4190.7 1782.05  4204.7 1782.31  4212.1 1783.98
  4314.7 1777.59  4468.6 1774.05  4545.5 1774.49  4554.2 1776.25  4570.3 1773.44
  4630.7 1773.87  4735.4 1771.37  4801.1 1774.55  4898.3 1774.72  4941.3 1774.09
  4960.4 1772.06  4982.2 1761.77  4983.7 1761.27  4999.8 1761.77  5013.8 1762.26
  5035.2 1768.88  5064.2 1771.31  5206.2 1774.09  5369.9 1772.27  5421.7 1773.66
  5453.4 1776.84    5459 1775.14  5495.7 1774.96  5780.6 1780.37  6112.7 1783.42
#Mann= 5 ,-1 , 0
  4158.4     .05       0  4898.3     .12       0  4982.2     .07       0
  4999.8     .12       0  5064.2     .05       0
Bank Sta=4982.2,4999.8
XS Rating Curve= 0 ,0
Exp/Cntr=0.3,0.1

Type RM Length L Ch R = 1 ,46223   ,425,425,425
BEGIN DESCRIPTION:
Lytle Creek 46784.46
END DESCRIPTION:
XS GIS Cut Line= 4
      1603874.69      6815088.92      1604305.57      6815723.05
      1604401.95      6815758.99      1605901.02      6816138.96
#Sta/Elev= 30
  4128.3 1777.31  4163.5  1775.8  4192.4  1776.5    4502 1773.63  4951.9 1773.12
  4958.4  1772.7  4969.1 1769.34  4977.5 1764.68  4982.9 1763.63  4987.9  1760.3
  4989.4  1759.8  5005.7  1760.3  5021.6 1763.85  5031.9 1768.04  5042.2 1769.44
  5097.3 1769.74  5142.3 1773.05  5289.8 1774.59    5379 1774.33  5460.9 1771.95
  5630.3 1771.83  5754.1 1773.75  5783.7  1775.7  5788.8 1774.92  5795.3 1776.24
  5829.8  1775.1  5888.2 1777.56  6022.3 1780.31  6434.2 1783.85  6544.3 1783.57
#Mann= 5 ,-1 , 0
  4128.3     .05       0  4951.9     .12       0  4987.9     .07       0
  5005.7     .12       0  5142.3     .05       0
Bank Sta=4987.9,5005.7
XS Rating Curve= 0 ,0
Exp/Cntr=0.3,0.1

Type RM Length L Ch R = 1 ,45798   ,480,480,480
BEGIN DESCRIPTION:
Lytle Creek 46259.37
END DESCRIPTION:
XS GIS Cut Line= 3
      1603650.13      6816087.52      1604514.03      6816197.52
      1605770.83      6816154.85
#Sta/Elev= 30
  4272.3 1785.25  4297.4 1785.44  4314.1 1782.63  4473.9 1774.85    4751 1767.89
  4788.5 1770.54  4831.6 1769.65  4882.1 1763.53  4902.2  1764.1  4922.4 1768.74
  4953.4 1771.11  4972.8 1763.06  4991.6 1761.94  4994.1 1761.78  4995.6 1761.28
  5011.9 1761.78  5033.3 1763.15  5063.5 1773.27  5134.1 1772.17  5244.2 1772.56
  5344.3 1768.75  5424.3  1772.7  5594.4 1770.45  5804.5 1772.51  5854.6 1774.44
  5867.7 1776.77  5874.6 1775.18  5904.6 1775.48  6184.7  1782.1  6400.7 1782.88
#Mann= 5 ,-1 , 0
  4272.3     .05       0  4991.6     .12       0  4994.1     .07       0
  5011.9     .12       0  5134.1     .05       0
Bank Sta=4994.1,5011.9
XS Rating Curve= 0 ,0
Exp/Cntr=0.3,0.1

Type RM Length L Ch R = 1 ,45318   ,356,356,356
BEGIN DESCRIPTION:
Lytle Creek 45801.99
END DESCRIPTION:
XS GIS Cut Line= 3
      1603894.01      6816807.53      1604623.89      6816591.54
      1605607.03       6816228.2
#Sta/Elev= 30
  4367.1 1777.71  4639.3 1773.15  4770.2 1772.63  4808.7 1773.56  4875.2 1772.62
  4880.4 1771.05  4908.4 1771.01  4920.8 1769.57  4962.6  1768.4    4973 1763.05
  4980.2 1760.93  4995.4 1759.26  4996.9 1758.76  5013.2 1759.26  5036.7 1761.69
    5046 1762.66  5051.9 1766.06  5066.9 1771.51  5077.3 1772.68  5188.8 1771.46
  5246.7 1770.13  5387.2 1770.69  5442.7 1769.43  5598.5 1771.15  5755.9 1771.33
  5816.7 1773.19  5847.2 1776.31  5877.6 1775.45  5982.3 1780.21  6176.4 1782.07
#Mann= 5 ,-1 , 0
  4367.1     .05       0  4995.4     .05       0  5013.2     .05       0
  5036.7     .12       0  5188.8     .05       0
Bank Sta=4995.4,5013.2
XS Rating Curve= 0 ,0
Exp/Cntr=0.3,0.1

Type RM Length L Ch R = 1 ,44962   ,566,566,566
BEGIN DESCRIPTION:
Mapping XS 67b3d247
END DESCRIPTION:
XS GIS Cut Line= 5
      1603680.72      6817099.03       1604573.8      6817082.22
      1604756.84      6816822.69      1605408.05      6816562.77
      1605637.23       6816444.7
#Sta/Elev= 30
  3923.1 1780.19  4017.4 1777.47    4243 1773.35  4357.5 1773.55  4427.5 1772.16
  4597.5 1772.08  4827.4 1769.89  4892.7 1771.19  4943.2 1769.65  4956.1 1767.93
  4970.2 1763.56  4990.9 1760.36  4992.4 1759.86  5008.7 1760.36  5041.8 1762.02
  5050.3 1763.56  5056.4  1766.2  5065.1 1768.19  5084.8 1769.95  5115.2 1771.14
  5172.2 1770.05  5196.5  1769.1  5698.4 1769.83    5821 1774.23  5834.8 1777.29
  5865.4 1775.07  5874.6 1775.21  5896.8 1778.02  5946.8 1779.46  6092.9 1780.52
#Mann= 5 ,-1 , 0
  3923.1     .05       0  4990.9     .05       0  5008.7     .05       0
  5084.8     .12       0  5172.2     .05       0
Bank Sta=4990.9,5008.7
XS Rating Curve= 0 ,0
Exp/Cntr=0.3,0.1

Type RM Length L Ch R = 1 ,44396   ,231,231,231
BEGIN DESCRIPTION:
Mapping XS 19fa8d52
END DESCRIPTION:
XS GIS Cut Line= 4
        1603814.      6817190.13      1604466.58      6817264.11
      1605810.83      6817038.46      1605998.36      6817017.63
#Sta/Elev= 30
  3654.3 1775.37  3786.1 1773.29  3896.8 1773.56  4088.1 1770.57  4390.6 1770.14
  4461.6 1768.18  4512.3 1769.88  4542.7 1768.65  4664.3 1769.69  4856.7 1766.21
  4897.6 1764.25  4917.3 1761.96  4922.4 1763.35  4938.1 1760.48  4974.1 1758.64
  4975.6 1758.14  4991.9 1758.64  5029.4 1759.79  5038.5 1762.39  5043.6 1761.44
  5049.7 1764.41  5059.8 1766.91  5080.1 1769.97  5104.2    1770  5225.5    1775
  5252.5 1778.54  5445.1 1782.88  5658.1 1781.96  5839.3 1784.81  5862.8 1784.26
#Mann= 3 ,-1 , 0
  3654.3     .05       0  4974.1     .05       0  4991.9     .05       0
Bank Sta=4974.1,4991.9
XS Rating Curve= 0 ,0
Exp/Cntr=0.3,0.1

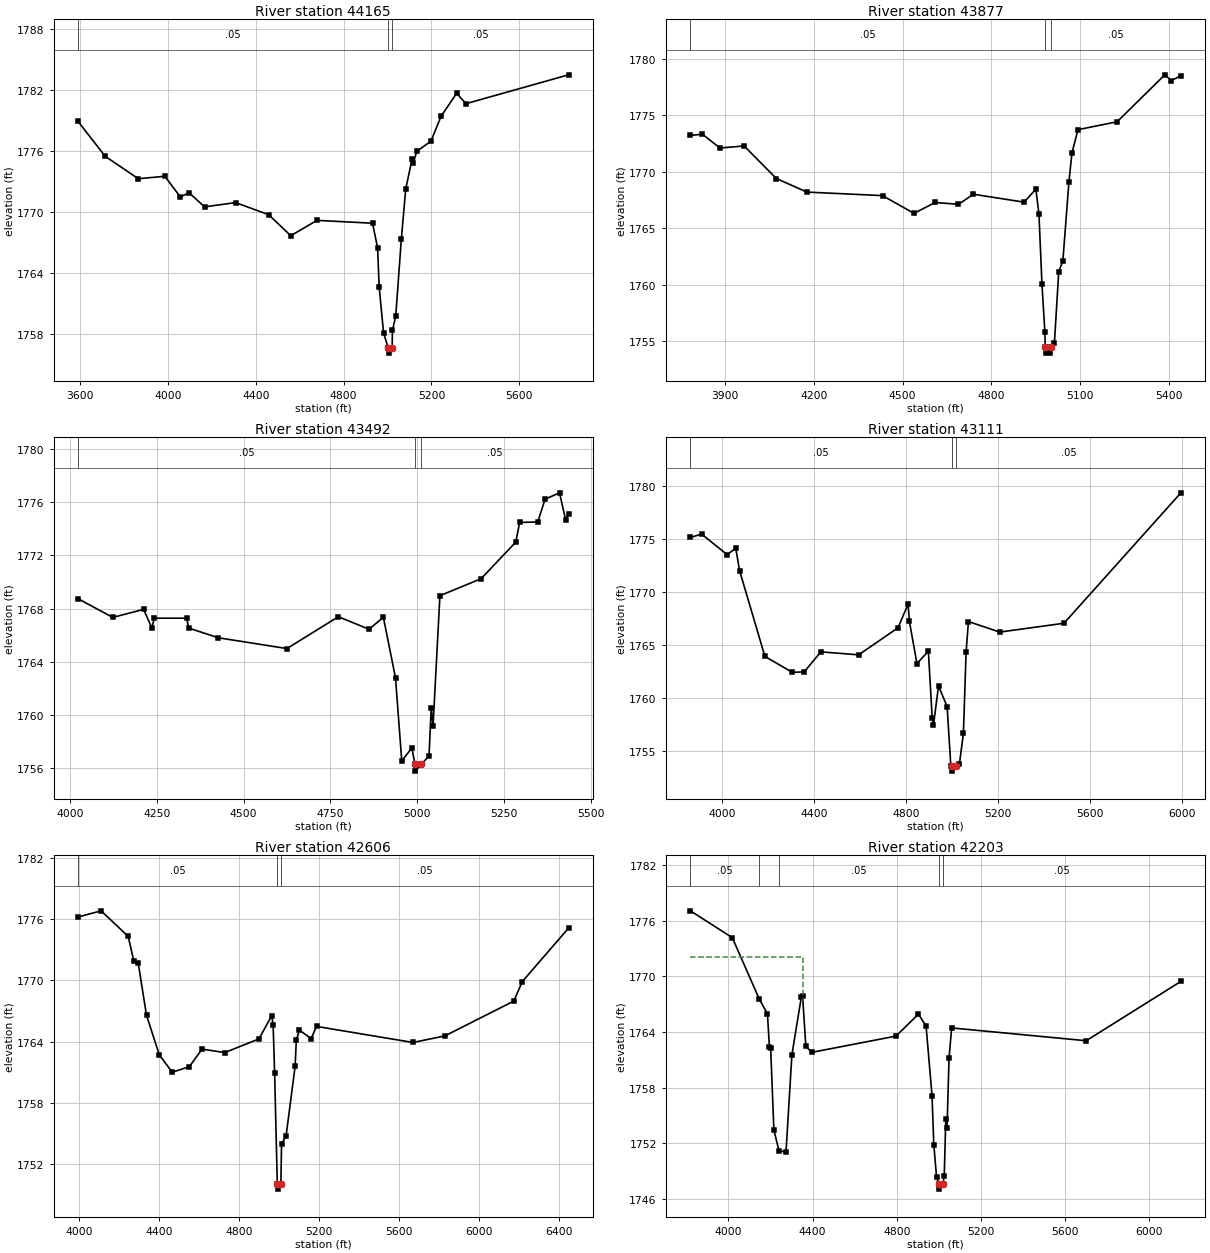
Type RM Length L Ch R = 1 ,44165   ,288,288,288
BEGIN DESCRIPTION:
Lytle Creek 44695.53
END DESCRIPTION:
XS GIS Cut Line= 3
      1603652.26      6817201.89       1605050.6      6817358.02
      1605870.47      6817462.24
#Sta/Elev= 30
    3591 1778.91  3714.5 1775.48  3865.4 1773.27  3986.2 1773.51  4056.6 1771.48
  4096.9 1771.88  4167.3  1770.5  4308.2 1770.92  4459.1 1769.73  4559.7 1767.66
  4678.9 1769.17    4932 1768.89    4955 1766.46  4962.2 1762.62  4982.3 1758.08
  5003.6  1756.6  5005.1  1756.1  5021.4  1756.6  5022.6 1758.34  5037.7 1759.75
    5063 1767.29  5083.1 1772.26  5112.6 1775.25  5117.6 1774.81  5133.5 1775.98
  5197.6 1776.95  5244.4 1779.43    5315 1781.68  5357.5 1780.66  5824.5  1783.5
#Mann= 3 ,-1 , 0
    3591     .05       0  5003.6     .05       0  5021.4     .05       0
Bank Sta=5003.6,5021.4
XS Rating Curve= 0 ,0
Exp/Cntr=0.3,0.1

Type RM Length L Ch R = 1 ,43877   ,385,385,385
BEGIN DESCRIPTION:
Lytle Creek 44398.8
END DESCRIPTION:
XS GIS Cut Line= 4
      1603842.25        6817315.      1604282.96      6817556.21
      1605003.73      6817639.27      1605426.59      6817722.97
#Sta/Elev= 30
  3782.6 1773.21  3822.9 1773.32  3882.6  1772.1  3964.2 1772.28  4073.2  1769.4
  4176.6  1768.2  4432.3 1767.89  4538.7 1766.32  4610.3 1767.28  4689.2 1767.12
    4740 1768.01  4911.2 1767.31  4951.1 1768.46  4961.5 1766.24  4971.6 1760.09
  4981.6 1755.79  4982.8 1754.46  4984.3 1753.96  4999.1 1753.96  5000.6 1754.46
  5013.7 1754.82  5028.4 1761.16  5042.4 1762.13  5062.8 1769.08    5073 1771.64
  5093.4 1773.72  5225.9 1774.42  5387.1 1778.57  5409.4 1778.06  5441.6  1778.5
#Mann= 3 ,-1 , 0
  3782.6     .05       0  4982.8     .05       0  5000.6     .05       0
Bank Sta=4982.8,5000.6
XS Rating Curve= 0 ,0
Exp/Cntr=0.3,0.1

Type RM Length L Ch R = 1 ,43492   ,381,381,381
BEGIN DESCRIPTION:
Lytle Creek 44192.169
END DESCRIPTION:
XS GIS Cut Line= 3
      1604052.97      6817641.21      1604959.74      6818022.54
      1605369.84      6817901.08
#Sta/Elev= 30
  4023.6 1768.74  4123.4 1767.34  4212.2 1767.94    4236 1766.54  4242.8 1767.28
  4336.4 1767.28  4341.8 1766.54  4427.2 1765.81  4624.7    1765  4772.6 1767.39
  4861.1 1766.45  4902.2 1767.35  4937.1  1762.8  4955.1 1756.57  4984.3 1757.54
  4993.1  1756.3  4994.6  1755.8  5010.9  1756.3  5033.6 1756.94  5039.9 1760.56
  5045.1 1759.15  5064.9 1768.97  5183.3 1770.24  5283.1 1772.99  5294.4 1774.47
  5346.5  1774.5  5367.4 1776.21  5409.1 1776.69  5426.5 1774.68    5435 1775.07
#Mann= 3 ,-1 , 0
  4023.6     .05       0  4993.1     .05       0  5010.9     .05       0
Bank Sta=4993.1,5010.9
XS Rating Curve= 0 ,0
Exp/Cntr=0.3,0.1

Type RM Length L Ch R = 1 ,43111   ,505,505,505
BEGIN DESCRIPTION:
Lytle Creek 43609.297
END DESCRIPTION:
XS GIS Cut Line= 3
      1603804.11       6817832.1      1604790.35      6818351.95
      1605720.51      6818758.28
#Sta/Elev= 30
  3863.7 1775.12    3912 1775.44    4023 1773.51  4060.6  1774.1    4077 1772.01
  4187.1 1763.93  4305.6 1762.44  4357.7 1762.47  4429.9 1764.36  4594.3 1764.08
  4764.9 1766.62  4808.9 1768.85  4814.6 1767.23  4847.3 1763.26    4897 1764.42
  4913.4 1758.18  4919.1 1757.46  4941.1 1761.16  4978.4  1759.2  4994.5 1753.64
  4999.6 1753.64  5001.1 1753.14  5017.5 1753.64  5031.9 1753.81  5049.1 1756.69
  5060.8 1764.33  5070.9 1767.21  5206.7 1766.22  5485.9 1767.05  5993.6 1779.32
#Mann= 3 ,-1 , 0
  3863.7     .05       0  4999.6     .05       0  5017.5     .05       0
Bank Sta=4999.6,5017.5
XS Rating Curve= 0 ,0
Exp/Cntr=0.3,0.1

Type RM Length L Ch R = 1 ,42606   ,403,403,403
BEGIN DESCRIPTION:
Lytle Creek 43080.136
END DESCRIPTION:
XS GIS Cut Line= 3
      1603756.59      6817854.29      1604389.76      6818626.28
      1605635.22      6819373.59
#Sta/Elev= 30
  3994.8 1776.23    4110 1776.84  4245.3 1774.33    4273 1771.94  4295.2 1771.75
  4336.8 1766.58  4400.7  1762.7  4465.2 1760.99  4550.7 1761.53  4614.5 1763.26
  4727.9 1762.92  4898.7 1764.26  4962.6 1766.55  4969.6  1765.6    4977 1760.96
  4990.4 1750.01  4991.9 1749.51  5008.3 1750.01  5011.6 1753.95  5034.3 1754.73
  5079.6 1761.59  5085.4 1764.15    5101 1765.13  5159.3 1764.29  5186.5 1765.49
  5668.5 1763.91  5827.9 1764.56  6171.9 1767.97  6214.7 1769.89  6445.7 1775.14
#Mann= 3 ,-1 , 0
  3994.8     .05       0  4990.4     .05       0  5008.3     .05       0
Bank Sta=4990.4,5008.3
XS Rating Curve= 0 ,0
Exp/Cntr=0.3,0.1

Type RM Length L Ch R = 1 ,42203   ,1287,1287,1287
BEGIN DESCRIPTION:
Lytle Creek 42668.9
END DESCRIPTION:
XS GIS Cut Line= 5
      1603626.54      6818050.53      1604184.22      6818932.76
      1604303.93      6819021.54      1604480.59      6819130.83
      1605399.85      6819268.56
#Sta/Elev= 30
  3819.7 1777.05  4018.5 1774.16  4146.9 1767.54  4185.6 1765.94  4194.9 1762.37
  4200.8 1762.28  4216.1 1753.44  4240.9 1751.17  4273.8 1751.11  4301.7 1761.54
  4346.7  1767.8  4352.6 1767.86  4367.9 1762.46  4396.4 1761.81    4796 1763.56
  4902.7 1765.92  4939.1 1764.66  4967.4 1757.13  4975.8 1751.87  4988.9  1748.4
  5001.1 1747.58  5002.6 1747.08    5019 1747.58  5025.5 1748.53  5032.8 1754.67
  5038.7 1753.62  5048.2 1761.19  5060.7 1764.44  5699.9 1763.06  6149.7 1769.45
#Mann= 5 ,-1 , 0
  3819.7     .05       0  4146.9     .12       0  4240.9     .05       0
  5001.1     .05       0    5019     .05       0
#XS Ineff= 2 , 0
       0    4354 1772.09               0
Permanent Ineff=
       F       F
Bank Sta=5001.1,5019
XS Rating Curve= 0 ,0
Exp/Cntr=0.3,0.1

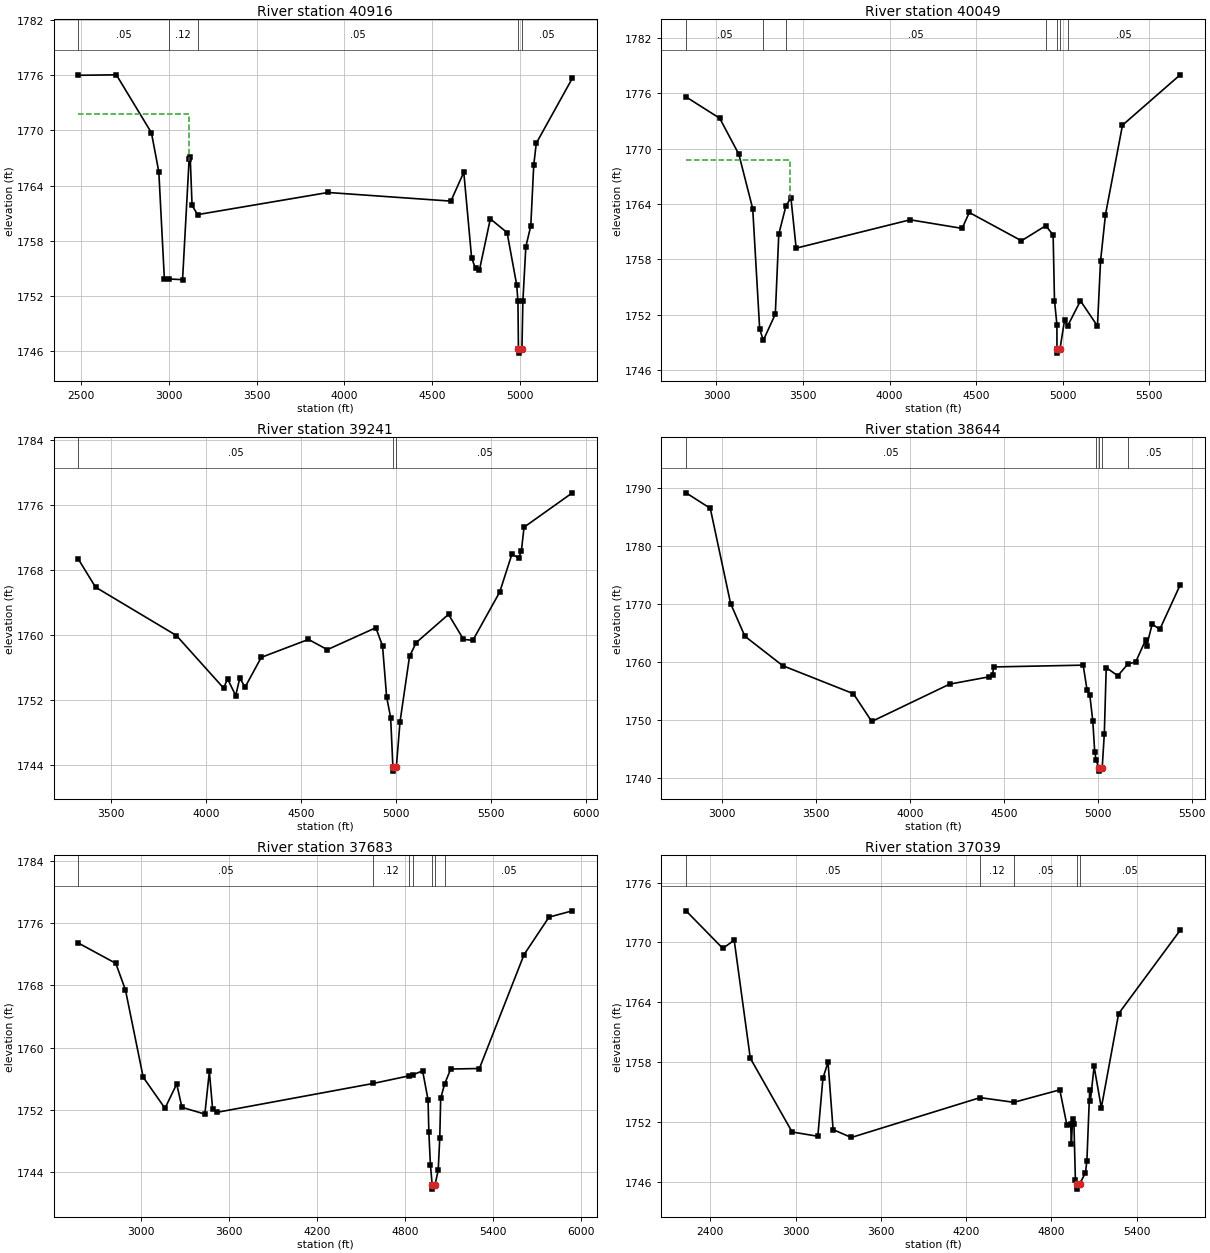
Type RM Length L Ch R = 1 ,40916   ,867,867,867
BEGIN DESCRIPTION:
Lytle Creek 40789.027
END DESCRIPTION:
XS GIS Cut Line= 4
       1603546.7      6817961.58      1603778.14      6818679.26
      1604072.72      6819508.53      1605129.21       6820029.1
#Sta/Elev= 30
    2485 1776.01  2701.9 1776.06  2901.5 1769.75  2943.6 1765.49  2975.1 1753.85
  3002.2 1753.83  3078.6 1753.76  3115.9 1766.85  3122.2 1767.06  3132.7 1761.85
    3164 1760.84  3906.7 1763.25  4605.5 1762.31  4679.1 1765.45  4723.7 1756.11
  4745.9 1754.99  4768.3 1754.82  4830.1 1760.38  4925.5 1758.88  4980.1 1753.19
  4987.3  1751.4    4990 1746.26    4992 1745.76    5010 1746.26  5015.3 1751.41
  5032.2 1757.35  5060.3 1759.61  5077.1 1766.21  5091.5 1768.61  5296.9 1775.69
#Mann= 5 ,-1 , 0
    2485     .05       0  3002.2     .12       0    3164     .05       0
    4990     .05       0    5010     .05       0
#XS Ineff= 2 , 0
       0  3115.3 1771.78               0
Permanent Ineff=
       F       F
Bank Sta=4990,5010
XS Rating Curve= 0 ,0
Exp/Cntr=0.3,0.1

Type RM Length L Ch R = 1 ,40049   ,808,808,808
BEGIN DESCRIPTION:
Lytle Creek 40238.718
END DESCRIPTION:
XS GIS Cut Line= 4
      1603472.83      6818104.19      1603547.41      6818993.46
      1604007.72      6819608.81      1604496.13       6820697.4
#Sta/Elev= 30
  2824.1 1775.59  3018.6 1773.28    3129 1769.39  3209.3 1763.48  3249.4 1750.47
  3270.5 1749.25  3339.7 1752.08  3359.8 1760.73  3401.6 1763.83    3430 1764.65
  3460.1 1759.22  4118.5 1762.29  4418.6 1761.36  4460.3 1763.08  4761.4 1760.02
  4901.8 1761.65  4944.4 1760.65  4952.3 1753.54  4966.3 1750.94  4966.5 1748.36
    4968 1747.86  4984.5 1748.36  5010.2 1751.42  5028.1  1750.8  5102.3 1753.52
  5200.5 1750.79  5218.2 1757.81  5246.8 1762.85    5345 1772.53  5678.1 1777.98
#Mann= 7 ,-1 , 0
  2824.1     .05       0  3270.5     .12       0  3401.6     .05       0
  4901.8     .12       0  4966.5     .07       0  4984.5     .12       0
  5028.1     .05       0
#XS Ineff= 2 , 0
       0  3424.4 1768.73  6575.6       0 1768.73
Permanent Ineff=
       F       F
Bank Sta=4966.5,4984.5
XS Rating Curve= 0 ,0
Exp/Cntr=0.3,0.1

Type RM Length L Ch R = 1 ,39241   ,597,597,597
BEGIN DESCRIPTION:
Lytle Creek 39640.856
END DESCRIPTION:
XS GIS Cut Line= 3
      1602408.27      6818826.06      1603733.34       6820036.1
      1604269.62      6820631.84
#Sta/Elev= 30
  3329.8 1769.31  3420.6 1765.84  3845.5 1759.89  4093.5 1753.42  4114.4 1754.55
    4157  1752.5  4178.5 1754.64  4206.3 1753.54  4291.4  1757.2  4539.3 1759.41
  4638.6 1758.15  4893.4 1760.85  4928.5 1758.61  4950.1 1752.32  4971.1 1749.79
    4983  1743.7  4984.5  1743.2    5001  1743.7  5020.4 1749.28  5070.4 1757.33
  5105.5 1759.02  5275.1 1762.49  5353.6 1759.42  5402.9 1759.29  5544.2 1765.24
  5608.5 1769.92  5643.6 1769.44  5657.8 1770.27    5672 1773.22  5925.8 1777.45
#Mann= 3 ,-1 , 0
  3329.8     .05       0    4983     .05       0    5001     .05       0
Bank Sta=4983,5001
XS Rating Curve= 0 ,0
Exp/Cntr=0.3,0.1

Type RM Length L Ch R = 1 ,38644   ,961,961,961
BEGIN DESCRIPTION:
Lytle Creek 39054.887
END DESCRIPTION:
XS GIS Cut Line= 3
      1601558.89      6820051.98      1603813.71      6820547.04
      1604131.36      6820607.03
#Sta/Elev= 30
  2807.2  1789.1  2936.3 1786.43  3044.5 1770.06  3120.6 1764.43  3322.6 1759.36
  3698.5 1754.55  3796.3 1749.77  4210.9 1756.19  4420.9 1757.45  4440.1 1757.79
  4445.3 1759.15  4922.5 1759.46    4943 1755.21  4957.7 1754.34  4973.7 1749.86
    4984 1744.51  4991.7 1743.17  5005.7 1741.73  5007.2 1741.23  5023.7 1741.73
  5035.1 1747.67  5045.3 1759.04  5106.8 1757.63  5160.1 1759.64  5202.6 1760.03
    5255 1763.78  5260.1 1762.72    5290 1766.51  5330.8 1765.63    5439 1773.25
#Mann= 5 ,-1 , 0
  2807.2     .05       0  4991.7     .12       0  5005.7     .07       0
  5023.7     .12       0  5160.1     .05       0
Bank Sta=5005.7,5023.7
XS Rating Curve= 0 ,0
Exp/Cntr=0.3,0.1

Type RM Length L Ch R = 1 ,37683   ,644,644,644
BEGIN DESCRIPTION:
Lytle Creek 38501.12
END DESCRIPTION:
XS GIS Cut Line= 3
      1601730.45      6820565.33      1603565.73      6821530.52
      1604784.68      6821084.78
#Sta/Elev= 30
  2572.1 1773.47  2828.2 1770.85  2894.3 1767.42  3015.2 1756.19  3163.9 1752.19
  3243.9 1755.31  3279.7 1752.31  3435.9 1751.44  3466.8 1756.93  3488.8 1752.12
  3516.5 1751.66  4586.3 1755.39  4830.3 1756.37  4858.3 1756.52  4921.8 1757.01
  4958.9 1753.28  4964.4 1749.11    4975 1744.94  4987.3 1742.28  4988.8 1741.78
  5005.3 1742.28  5028.2 1744.18  5038.9  1748.4  5045.2 1753.47  5071.3 1755.28
  5113.4 1757.24  5309.3 1757.31  5613.9 1771.97  5784.2  1776.8  5943.6 1777.61
#Mann= 7 ,-1 , 0
  2572.1     .05       0  4586.3     .12       0  4830.3     .05       0
  4858.3     .12       0  4987.3     .07       0  5005.3     .12       0
  5071.3     .05       0
Bank Sta=4987.3,5005.3
XS Rating Curve= 0 ,0
Exp/Cntr=0.3,0.1

Type RM Length L Ch R = 1 ,37039   ,730,730,730
BEGIN DESCRIPTION:
Lytle Creek 37390.876
END DESCRIPTION:
XS GIS Cut Line= 4
      1601666.63      6820635.33      1603591.54      6821990.04
      1604013.02      6822041.39      1604701.25      6822163.51
#Sta/Elev= 30
  2228.5 1773.17  2487.2 1769.41  2567.4 1770.23  2680.6 1758.42  2975.1 1751.03
  3155.9  1750.6  3191.9 1756.41  3227.7 1758.02  3263.4 1751.27  3391.4 1750.48
  4298.2 1754.47  4535.6    1754  4858.9 1755.25  4908.2 1751.77  4935.5  1751.8
  4940.5 1749.79  4948.5 1752.29  4958.5  1751.8  4968.6 1746.23  4979.8 1745.81
  4981.3 1745.31  4997.8 1745.81  5039.4 1746.94  5049.6 1748.15  5069.1 1755.19
  5074.2 1754.16  5100.3 1757.59  5151.1 1753.45    5273 1762.88  5705.9 1771.22
#Mann= 5 ,-1 , 0
  2228.5     .05       0  4298.2     .12       0  4535.6     .05       0
  4979.8     .05       0  4997.8     .05       0
Bank Sta=4979.8,4997.8
XS Rating Curve= 0 ,0
Exp/Cntr=0.3,0.1

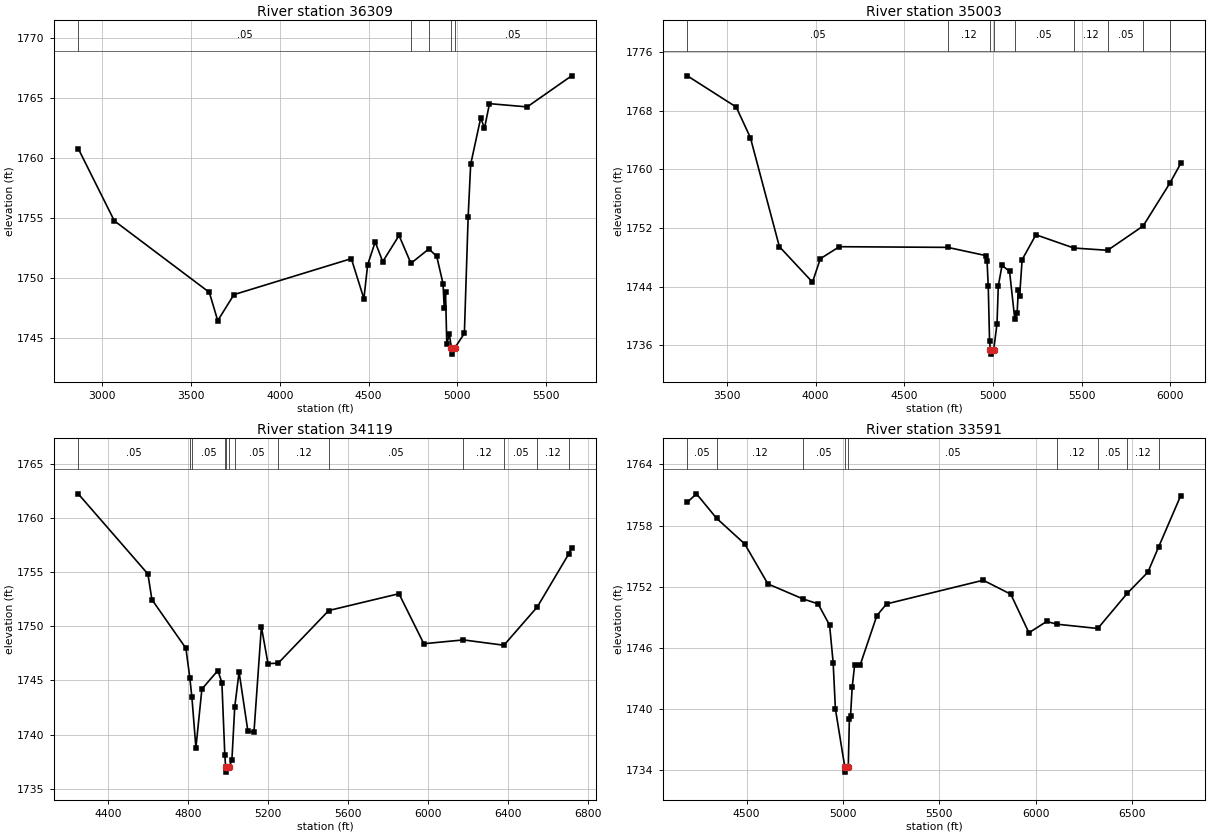
Type RM Length L Ch R = 1 ,36309   ,1306,1306,1306
BEGIN DESCRIPTION:
Lytle Creek 36844.86
END DESCRIPTION:
XS GIS Cut Line= 3
      1601707.74       6821526.3      1603091.84      6822112.36
      1603983.04      6823023.65
#Sta/Elev= 30
  2865.1 1760.82  3068.5 1754.79  3603.2 1748.83  3650.6 1746.47  3741.7 1748.64
  4402.7 1751.64  4473.5  1748.3  4494.6 1751.13    4537 1753.03  4579.5 1751.39
  4671.3 1753.57  4738.3 1751.25  4839.3 1752.45  4883.5 1751.83  4918.9 1749.56
  4925.9  1747.5  4933.1 1748.84  4940.1 1744.51  4954.2 1745.34  4966.5 1744.18
    4968 1743.68  4984.5 1744.18  5039.1 1745.41  5060.4 1755.13  5074.5 1759.49
  5131.1 1763.37  5152.3 1762.51  5180.5 1764.56  5392.7 1764.29  5642.8 1766.88
#Mann= 5 ,-1 , 0
  2865.1     .05       0  4738.3     .12       0  4839.3     .05       0
  4966.5     .05       0  4984.5     .05       0
Bank Sta=4966.5,4984.5
XS Rating Curve= 0 ,0
Exp/Cntr=0.3,0.1

Type RM Length L Ch R = 1 ,35003   ,884,884,884
BEGIN DESCRIPTION:
Lytle Creek 35725.689
END DESCRIPTION:
XS GIS Cut Line= 4
      1601443.58      6822204.53      1602476.76      6822941.71
      1602982.34      6823477.08      1603657.43      6823092.95
#Sta/Elev= 30
  3276.9 1772.77  3552.4 1768.51  3632.3 1764.34  3795.8 1749.46  3982.6 1744.61
  4026.8 1747.81  4133.8 1749.45  4744.9 1749.36  4959.6 1748.24  4966.9 1747.53
  4973.7 1744.05    4981 1736.61  4985.9 1735.29  4987.4 1734.79  5003.9 1735.29
  5023.1 1738.94  5030.4 1744.09  5051.4  1746.9  5093.9 1746.08  5123.3 1739.55
  5136.4 1740.38  5143.7 1743.57  5150.5 1742.68  5164.7 1747.68  5242.5 1751.08
  5456.2 1749.27    5647 1748.96  5847.1 1752.28  5998.3 1758.14  6059.2 1760.82
#Mann= 9 ,-1 , 0
  3276.9     .05       0  4744.9     .12       0  4985.9     .07       0
  5003.9     .12       0  5123.3     .05       0  5456.2     .12       0
    5647     .05       0  5847.1     .12       0  5998.3     .05       0
Bank Sta=4985.9,5003.9
XS Rating Curve= 0 ,0
Exp/Cntr=0.3,0.1

Type RM Length L Ch R = 1 ,34119   ,528,528,528
BEGIN DESCRIPTION:
Lytle Creek 34576.911
END DESCRIPTION:
XS GIS Cut Line= 4
      1601306.45      6823712.44      1602055.32        6823678.
      1602714.32      6823736.57      1603606.94      6823167.05
#Sta/Elev= 30
  4248.5 1762.21  4597.4 1754.82  4617.4 1752.46  4787.6 1747.97  4807.2 1745.26
  4817.7 1743.45  4837.7  1738.8  4867.7 1744.21  4947.8 1745.92  4967.8  1744.8
  4982.5 1738.11  4986.5 1737.05    4988 1736.55  5004.5 1737.05  5017.9 1737.65
  5032.1 1742.56  5053.9 1745.78  5098.2  1740.3  5128.4 1740.24  5165.6 1749.95
  5198.6 1746.56  5249.5 1746.59  5502.8 1751.45  5854.3    1753  5978.7 1748.39
  6176.7 1748.74  6379.7 1748.25  6546.8 1751.78  6703.7 1756.65  6718.6 1757.26
#Mann= 13 ,-1 , 0
  4248.5     .05       0  4807.2     .12       0  4817.7     .05       0
  4982.5     .12       0  4986.5     .07       0  5004.5     .12       0
  5032.1     .05       0  5249.5     .12       0  5502.8     .05       0
  6176.7     .12       0  6379.7     .05       0  6546.8     .12       0
  6703.7     .05       0
Bank Sta=4986.5,5004.5
XS Rating Curve= 0 ,0
Exp/Cntr=0.3,0.1

Type RM Length L Ch R = 1 ,33591   ,561,561,561
BEGIN DESCRIPTION:
Lytle Creek 33980.178
END DESCRIPTION:
XS GIS Cut Line= 3
      1601447.67      6824182.65      1602261.14      6824140.17
      1603683.66      6823127.21
#Sta/Elev= 30
  4192.3  1760.3  4239.7 1761.12  4343.7 1758.73    4490 1756.21  4610.2 1752.29
  4794.8  1750.8  4870.6 1750.34  4930.6 1748.25  4949.1 1744.56  4960.7 1740.04
  5009.5 1734.34    5011 1733.84  5027.5 1734.34  5033.3 1739.04  5039.4 1739.38
    5048  1742.2  5060.7 1744.35  5089.8 1744.37  5175.9 1749.18  5226.3 1750.33
  5727.9 1752.65    5871 1751.28  5965.2  1747.5  6057.4 1748.61  6110.8 1748.34
  6322.5 1747.92  6474.8 1751.35  6582.5 1753.44  6639.3 1755.95  6753.2 1760.95
#Mann= 9 ,-1 , 0
  4192.3     .05       0  4343.7     .12       0  4794.8     .05       0
  5009.5    .035       0  5027.5     .05       0  6110.8     .12       0
  6322.5     .05       0  6474.8     .12       0  6639.3     .05       0
Bank Sta=5009.5,5027.5
XS Rating Curve= 0 ,0
Exp/Cntr=0.3,0.1