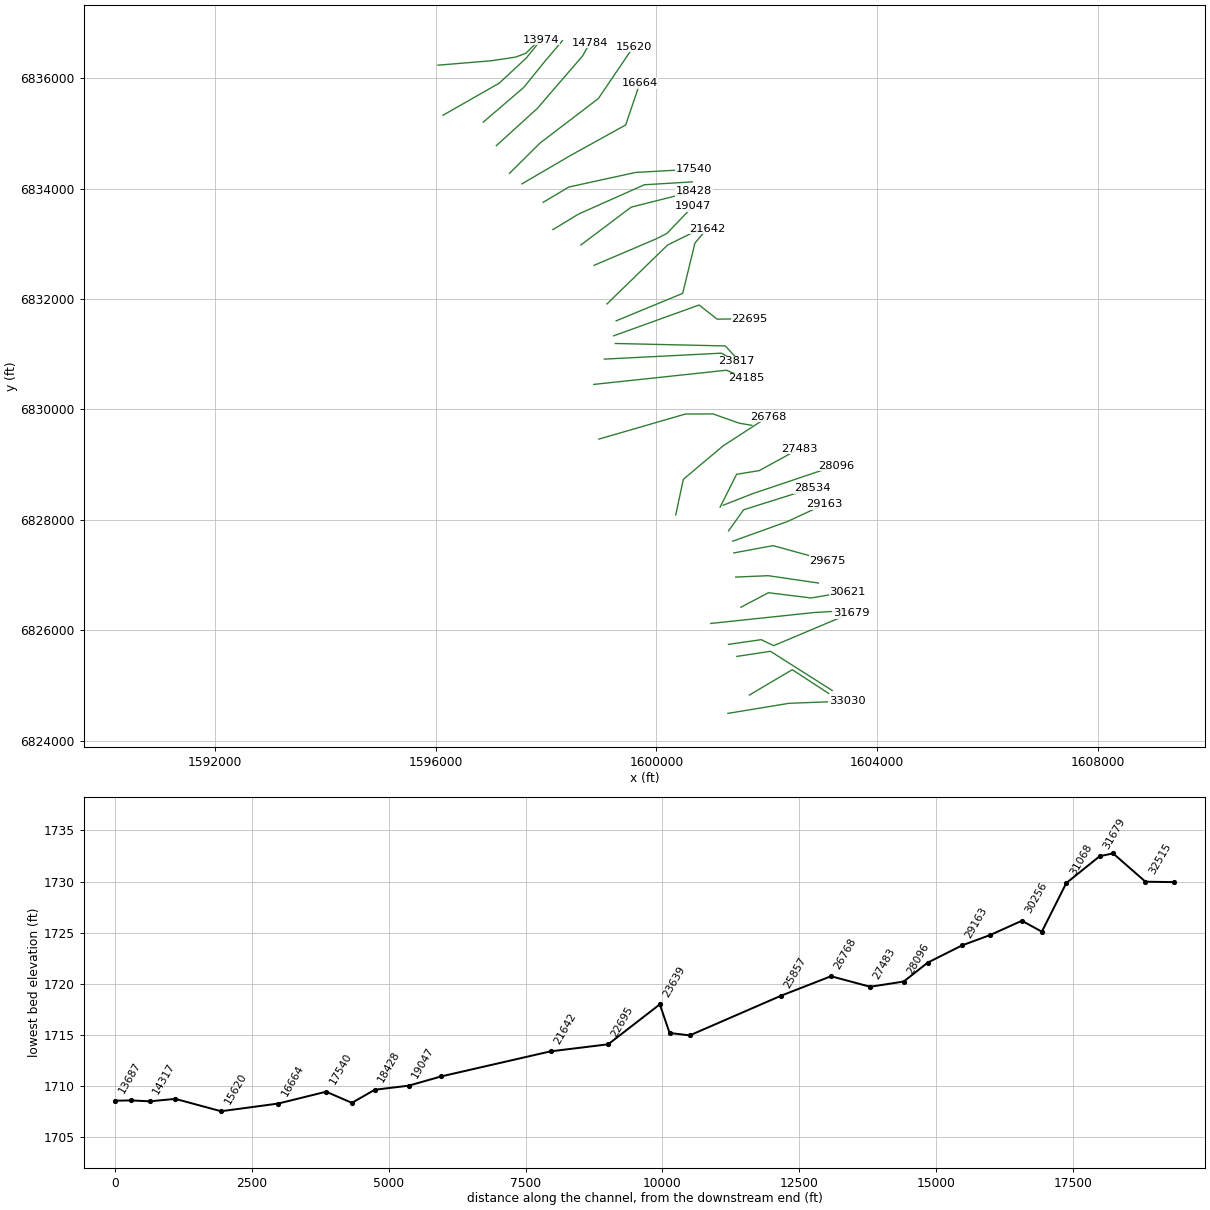
HEC-RAS study Lytle Creek.prj: Lytle Creek Base Level Engineering

--- Lytle Creek.g02 (geometry) --- (continued)

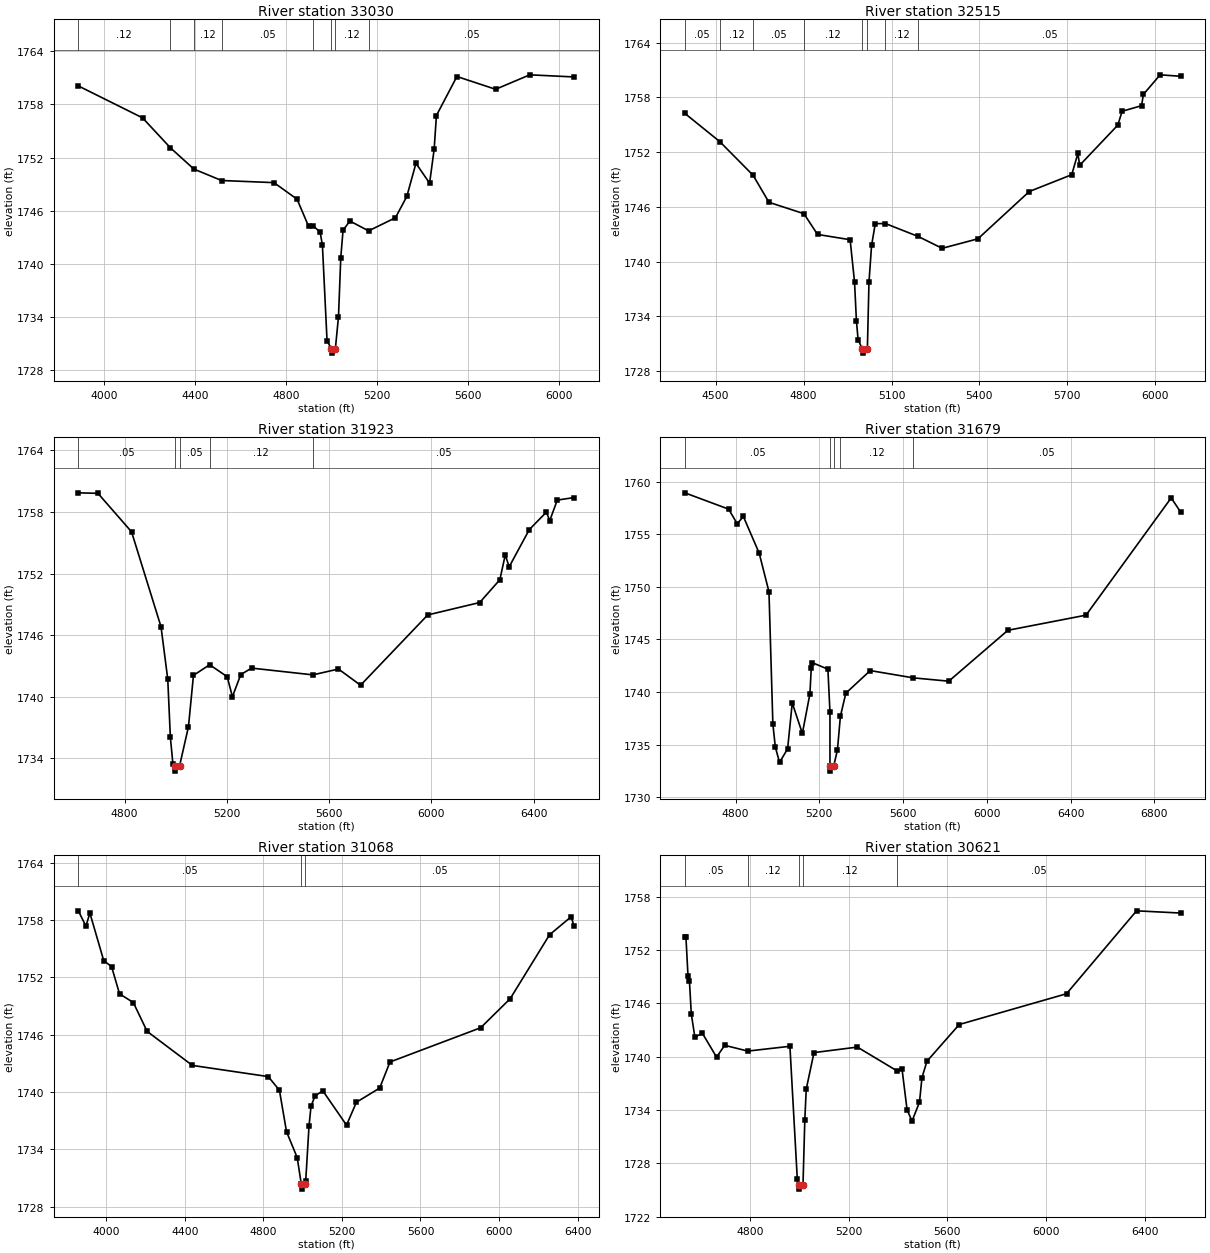
Type RM Length L Ch R = 1 ,33030   ,515,515,515
BEGIN DESCRIPTION:
Lytle Creek 33399.804
END DESCRIPTION:
XS GIS Cut Line= 3
      1601296.62      6824492.31      1602404.63       6824674.8
      1603459.85      6824714.53
#Sta/Elev= 30
  3887.7 1760.08  4169.8 1756.48  4292.3  1753.1  4395.4  1750.7  4517.1 1749.41
  4747.5 1749.17  4848.9  1747.3  4899.5 1744.25  4921.1 1744.26  4950.2  1743.6
  4960.3 1742.12  4980.6 1731.36  4999.3 1730.44  5000.8 1729.94  5017.3 1730.44
    5031 1734.06    5041 1740.72    5051  1743.8  5081.1 1744.84  5163.2 1743.73
  5281.2 1745.21  5331.2 1747.61  5371.3 1751.35  5431.3 1749.11  5451.3 1752.92
  5461.3 1756.74  5551.4 1761.14  5721.5  1759.7  5871.6 1761.33  6066.6 1761.09
#Mann= 8 ,-1 , 0
  3887.7     .12       0  4292.3     .05       0  4395.4     .12       0
  4517.1     .05       0  4921.1     .12       0  4999.3     .07       0
  5017.3     .12       0  5163.2     .05       0
Bank Sta=4999.3,5017.3
XS Rating Curve= 0 ,0
Exp/Cntr=0.3,0.1

Type RM Length L Ch R = 1 ,32515   ,592,592,592
BEGIN DESCRIPTION:
Lytle Creek 32846.541
END DESCRIPTION:
XS GIS Cut Line= 3
      1601686.32      6824824.91      1602462.79      6825283.61
      1603124.59      6824852.26
#Sta/Elev= 30
  4394.7 1756.24  4513.9 1753.15  4627.7 1749.46  4681.8  1746.5  4801.2 1745.25
  4847.5 1742.98  4958.8  1742.4  4973.9 1737.75  4980.2 1733.55    4986 1731.46
  4999.7 1730.48  5001.2 1729.98  5017.7 1730.48  5023.1 1737.74    5032 1741.77
  5044.6 1744.16  5079.4 1744.17  5190.8 1742.76  5272.9 1741.46  5394.9  1742.5
  5570.1 1747.68  5714.9 1749.52    5736 1751.85    5742 1750.55  5872.1 1754.95
  5886.9 1756.47  5953.3 1757.08  5959.3 1758.31  6016.6 1760.46  6086.5  1760.3
#Mann= 8 ,-1 , 0
  4394.7     .05       0  4513.9     .12       0  4627.7     .05       0
  4801.2     .12       0  4999.7     .07       0  5017.7     .12       0
  5079.4     .12       0  5190.8     .05       0
Bank Sta=4999.7,5017.7
XS Rating Curve= 0 ,0
Exp/Cntr=0.3,0.1

Type RM Length L Ch R = 1 ,31923   ,244,244,244
BEGIN DESCRIPTION:
Lytle Creek 32322.286
END DESCRIPTION:
XS GIS Cut Line= 3
      1601459.16      6825524.37      1602066.22      6825617.05
      1603185.74      6824907.56
#Sta/Elev= 30
    4619 1759.87  4695.7 1759.82  4827.2 1756.07  4942.4 1746.82  4968.8 1741.71
    4979 1736.05  4989.1 1733.41  4996.9 1733.25  4998.4 1732.75  5014.9 1733.25
  5049.8 1737.08  5069.3 1742.08  5132.6 1743.12  5201.3 1741.95  5221.7    1740
  5254.4 1742.16  5296.7 1742.79  5536.6 1742.13  5636.5  1742.7    5723 1741.12
  5985.7 1747.97    6189 1749.18  6267.8  1751.4    6289 1753.82  6304.3 1752.66
  6383.1 1756.29    6450 1757.99  6462.9 1757.15  6492.4 1759.16  6558.5 1759.41
#Mann= 5 ,-1 , 0
    4619     .05       0  4996.9     .05       0  5014.9     .05       0
  5132.6     .12       0  5536.6     .05       0
Bank Sta=4996.9,5014.9
XS Rating Curve= 0 ,0
Exp/Cntr=0.3,0.1

Type RM Length L Ch R = 1 ,31679   ,611,611,611
BEGIN DESCRIPTION:
Lytle Creek 31167.796
END DESCRIPTION:
XS GIS Cut Line= 4
      1601307.35      6825742.51      1601898.55      6825827.75
      1602127.77      6825719.74      1603524.73      6826309.11
#Sta/Elev= 30
  4557.9 1758.94  4767.1 1757.39  4808.1    1756  4837.5 1756.69    4913  1753.2
  4959.7 1749.53  4978.3 1736.97    4990 1734.77  5010.2 1733.31  5048.7  1734.6
  5070.8 1738.96  5119.1 1736.07  5155.2 1739.83  5161.6 1742.32  5167.1 1742.79
    5241 1742.17  5250.8 1738.13  5250.9 1732.98  5252.4 1732.48  5268.9 1732.98
  5286.6  1734.5  5300.6 1737.69  5326.6 1739.89  5443.1 1742.04  5647.8 1741.35
    5818 1741.03  6100.2 1745.87  6473.2 1747.31  6879.8 1758.46  6924.8 1757.11
#Mann= 5 ,-1 , 0
  4557.9     .05       0  5250.9     .05       0  5268.9     .05       0
  5300.6     .12       0  5647.8     .05       0
Bank Sta=5250.9,5268.9
XS Rating Curve= 0 ,0
Exp/Cntr=0.3,0.1

Type RM Length L Ch R = 1 ,31068   ,447,447,447
BEGIN DESCRIPTION:
Mapping XS 7648e034
END DESCRIPTION:
XS GIS Cut Line= 3
       1600986.5       6826121.6      1602861.54      6826319.52
      1603500.24      6826357.71
#Sta/Elev= 30
  3857.5 1758.96  3896.2 1757.35  3916.3 1758.73  3986.7 1753.76  4026.9 1753.12
  4067.2 1750.28  4137.5 1749.37  4207.9 1746.35  4438.3 1742.79  4824.9 1741.62
  4881.7 1740.19  4917.8 1735.86  4972.2 1733.15  4993.3 1730.35  4994.8 1729.85
  5011.3 1730.35  5015.7 1730.74  5032.5 1736.48  5042.5  1738.5  5062.7  1739.6
  5102.9 1740.13  5223.5 1736.54  5273.8 1738.94  5392.2 1740.42  5444.8 1743.15
  5906.7 1746.73    6057 1749.77  6257.3 1756.45  6367.5 1758.34  6382.8 1757.33
#Mann= 3 ,-1 , 0
  3857.5     .05       0  4993.3     .05       0  5011.3     .05       0
Bank Sta=4993.3,5011.3
XS Rating Curve= 0 ,0
Exp/Cntr=0.3,0.1

Type RM Length L Ch R = 1 ,30621   ,365,365,365
BEGIN DESCRIPTION:
Mapping XS e18eeca7
END DESCRIPTION:
XS GIS Cut Line= 4
       1601531.7      6826415.23      1602030.46      6826677.95
      1602802.51      6826583.41      1603461.09      6826694.33
#Sta/Elev= 30
  4536.1  1753.4  4540.8  1753.4  4549.1 1749.06  4554.8 1748.55  4562.4 1744.81
  4576.8 1742.21  4607.6 1742.61  4664.9 1739.94  4697.7 1741.27  4791.4 1740.62
  4962.1 1741.16  4991.9 1726.28  4997.1 1725.59  4998.6 1725.09  5015.1 1725.59
  5022.5  1732.9  5028.2 1736.33  5059.7 1740.45  5235.4 1741.07  5394.1 1738.43
  5416.7 1738.55  5436.9 1734.01    5457 1732.75  5487.2 1734.87  5497.3 1737.64
  5517.5 1739.48  5648.4 1743.61    6083 1747.07  6366.9  1756.4  6545.5 1756.15
#Mann= 5 ,-1 , 0
  4536.1     .05       0  4791.4     .12       0  4997.1     .07       0
  5015.1     .12       0  5394.1     .05       0
Bank Sta=4997.1,5015.1
XS Rating Curve= 0 ,0
Exp/Cntr=0.3,0.1

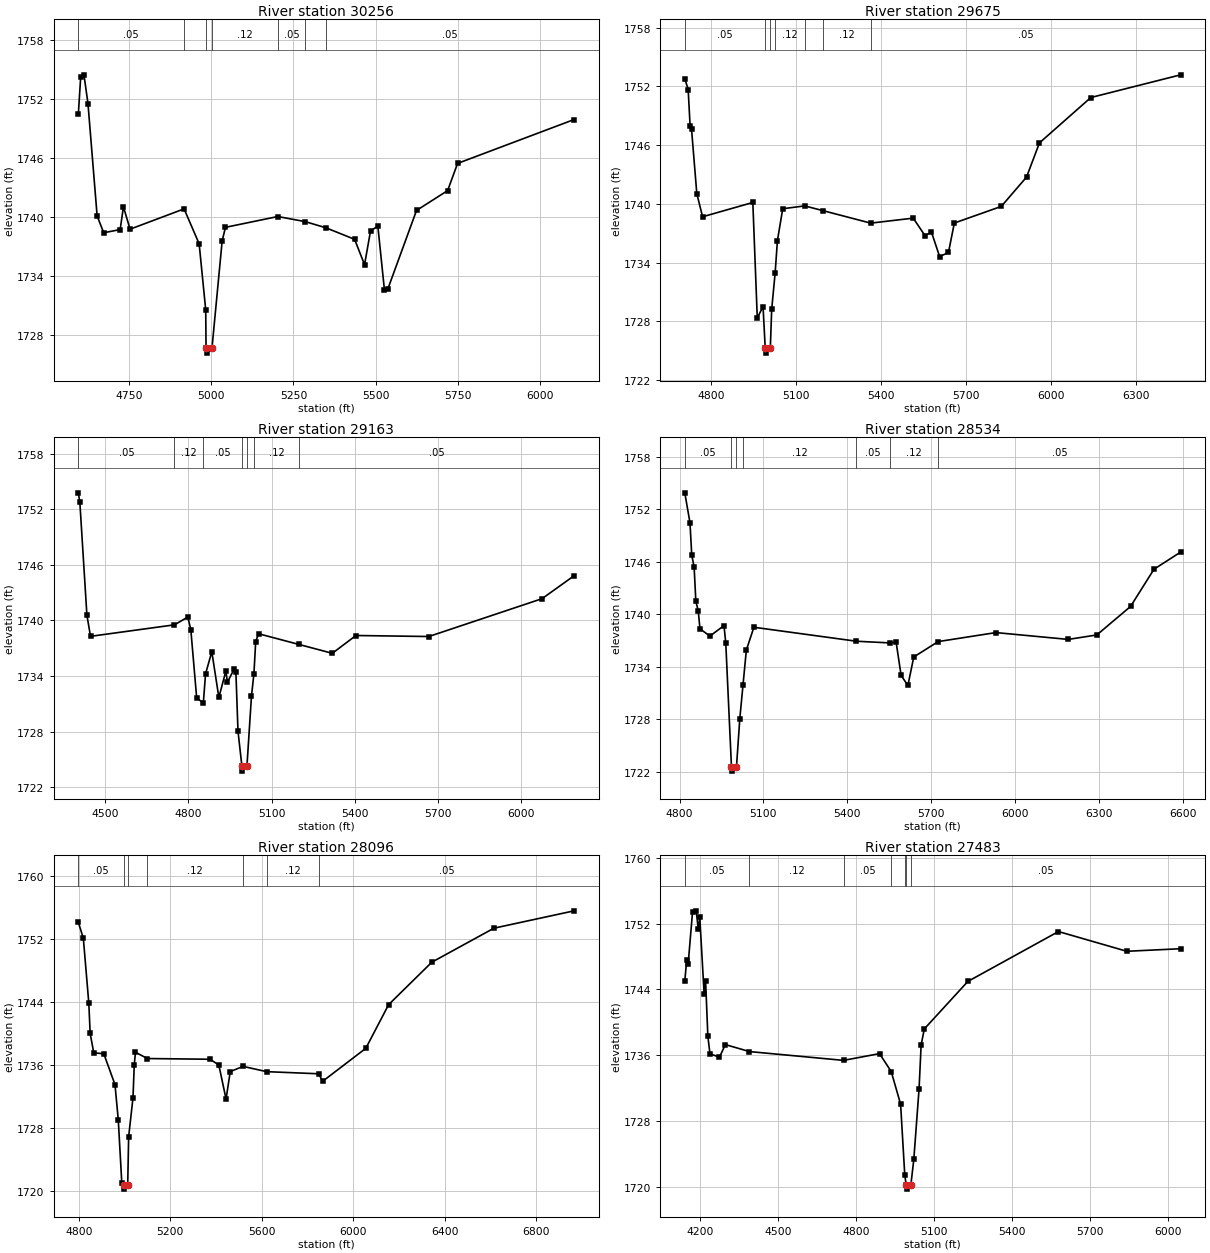
Type RM Length L Ch R = 1 ,30256   ,581,581,581
BEGIN DESCRIPTION:
Mapping XS 778433d1
END DESCRIPTION:
XS GIS Cut Line= 3
      1601437.88      6826961.88      1602026.72      6826986.74
      1602935.89      6826853.86
#Sta/Elev= 30
  4595.8 1750.48  4602.9 1754.24  4612.9  1754.5  4625.1 1751.58    4653 1740.12
    4673 1738.42    4723 1738.74    4733 1741.06  4753.1 1738.78  4917.5 1740.85
  4963.3 1737.29  4983.3 1730.55  4984.3 1726.66  4985.8 1726.16  5002.3 1726.66
  5033.3 1737.59  5043.3 1738.97  5202.5 1740.07  5286.1 1739.55  5349.2 1738.92
  5436.1 1737.75  5466.4 1735.17  5484.6  1738.6  5506.8  1739.1    5527 1732.56
  5537.1 1732.68  5624.5 1740.69  5719.1 1742.71  5749.4 1745.48    6104 1749.95
#Mann= 7 ,-1 , 0
  4595.8     .05       0  4917.5     .12       0  4984.3     .07       0
  5002.3     .12       0  5202.5     .05       0  5286.1     .12       0
  5349.2     .05       0
Bank Sta=4984.3,5002.3
XS Rating Curve= 0 ,0
Exp/Cntr=0.3,0.1

Type RM Length L Ch R = 1 ,29675   ,512,512,512
BEGIN DESCRIPTION:
Mapping XS 8268765c
END DESCRIPTION:
XS GIS Cut Line= 3
      1601403.27      6827399.26      1602115.01      6827531.33
      1603105.72      6827258.83
#Sta/Elev= 30
    4706 1752.81  4717.9 1751.69  4724.8 1747.93  4729.9 1747.61  4748.4 1741.06
  4768.8 1738.69  4946.3 1740.15    4962 1728.36  4982.4 1729.51  4990.1 1725.26
  4991.6 1724.76  5008.1 1725.26  5012.9 1729.23  5025.2 1732.98  5033.2 1736.26
  5051.9 1739.51  5129.4  1739.8  5194.8 1739.31  5362.7 1738.04  5512.9 1738.55
  5554.3 1736.77  5577.3 1737.12  5606.2 1734.62  5637.3 1735.04  5658.1 1738.05
    5824 1739.75    5913 1742.74  5958.8 1746.24  6140.2 1750.87  6457.4 1753.19
#Mann= 7 ,-1 , 0
    4706     .05       0  4990.1    .035       0  5008.1     .05       0
  5025.2     .12       0  5129.4     .05       0  5194.8     .12       0
  5362.7     .05       0
Bank Sta=4990.1,5008.1
XS Rating Curve= 0 ,0
Exp/Cntr=0.3,0.1

Type RM Length L Ch R = 1 ,29163   ,629,629,629
BEGIN DESCRIPTION:
Mapping XS cfcc106c
END DESCRIPTION:
XS GIS Cut Line= 3
      1601383.65      6827611.58      1602375.57      6827968.28
      1603040.06      6828276.74
#Sta/Elev= 30
  4403.6 1753.77  4409.1 1752.73  4434.5 1740.57  4447.5 1738.29  4749.9 1739.53
  4798.2 1740.37  4808.9 1739.02  4830.1 1731.63  4854.1 1731.12    4862 1734.24
  4884.6 1736.63    4910  1731.7  4935.4 1734.56  4940.7 1733.34  4966.1 1734.82
  4971.4 1734.42  4978.9 1728.07  4993.1 1724.25  4994.6 1723.75  5011.1 1724.25
  5027.5 1731.83  5036.4 1734.28  5042.7 1737.71  5052.9 1738.57  5199.2 1737.41
  5318.8 1736.46    5404 1738.38  5666.6 1738.27  6074.5 1742.35  6190.3 1744.83
#Mann= 7 ,-1 , 0
  4403.6     .05       0  4749.9     .12       0  4854.1     .05       0
  4993.1     .05       0  5011.1     .05       0  5036.4     .12       0
  5199.2     .05       0
Bank Sta=4993.1,5011.1
XS Rating Curve= 0 ,0
Exp/Cntr=0.3,0.1

Type RM Length L Ch R = 1 ,28534   ,438,438,438
BEGIN DESCRIPTION:
Mapping XS 1be179b9
END DESCRIPTION:
XS GIS Cut Line= 3
      1601308.63      6827798.58      1601581.03       6828180.7
      1602825.93      6828573.25
#Sta/Elev= 30
  4818.6  1753.9  4837.2 1750.46  4843.4  1746.8    4852  1745.4  4858.1 1741.51
  4866.8 1740.37  4872.9 1738.34  4908.5 1737.51  4958.9 1738.71  4965.3 1736.69
  4985.6 1722.56  4987.1 1722.06  5003.6 1722.56  5015.5 1728.08  5026.9 1731.91
  5038.9 1735.91  5065.9 1738.52  5433.1 1736.92  5551.7 1736.73  5575.1 1736.79
  5592.8 1733.01  5617.1 1731.86  5638.1 1735.12  5725.3 1736.88  5932.1 1737.91
  6190.9 1737.13  6293.2 1737.64    6414  1740.9  6497.9 1745.16  6593.2 1747.12
#Mann= 7 ,-1 , 0
  4818.6     .05       0  4985.6    .035       0  5003.6     .05       0
  5026.9     .12       0  5433.1     .05       0  5551.7     .12       0
  5725.3     .05       0
Bank Sta=4985.6,5003.6
XS Rating Curve= 0 ,0
Exp/Cntr=0.3,0.1

Type RM Length L Ch R = 1 ,28096   ,613,613,613
BEGIN DESCRIPTION:
Mapping XS 4e40e666
END DESCRIPTION:
XS GIS Cut Line= 3
      1601212.27      6828263.98       1601753.9      6828475.77
      1603257.37      6828982.72
#Sta/Elev= 30
  4797.9 1754.17  4819.8 1752.13  4843.8 1743.84  4849.6 1740.04  4865.3 1737.56
  4909.3 1737.44  4958.2 1733.51  4972.6 1729.01  4988.1 1720.93  4995.8 1720.71
  4997.3 1720.21  5013.8 1720.71  5017.9 1726.87    5037 1731.86  5042.4 1736.03
  5047.8 1737.63  5099.9 1736.83  5373.6 1736.74  5412.3 1736.01  5443.9 1731.67
  5462.2 1735.17  5518.3 1735.83  5621.7 1735.16  5849.2 1734.89  5866.1 1733.93
    6055 1738.13  6154.8 1743.69  6343.6 1749.09  6615.3 1753.42  6966.1 1755.63
#Mann= 7 ,-1 , 0
  4797.9     .05       0  4995.8    .035       0  5013.8     .05       0
  5099.9     .12       0  5518.3     .05       0  5621.7     .12       0
  5849.2     .05       0
Bank Sta=4995.8,5013.8
XS Rating Curve= 0 ,0
Exp/Cntr=0.3,0.1

Type RM Length L Ch R = 1 ,27483   ,715,715,715
BEGIN DESCRIPTION:
Lytle Creek 27783.321
END DESCRIPTION:
XS GIS Cut Line= 4
      1601155.57      6828228.81      1601453.88       6828824.1
       1601862.4      6828889.84      1602586.33      6829285.65
#Sta/Elev= 30
  4142.9 1745.02  4150.2 1747.57  4155.8 1747.08  4172.5 1753.36  4186.7 1753.55
  4194.9 1751.28  4200.5 1752.74  4217.2 1743.41  4222.8 1745.03  4231.5 1738.27
  4239.6 1736.16  4276.2 1735.75  4298.6 1737.28  4391.4 1736.43  4752.6 1735.36
  4890.9 1736.18  4935.9    1734  4971.9 1730.03  4987.8 1721.46  4993.3  1720.2
  4994.8  1719.7  5011.3  1720.2  5022.6 1723.31  5042.8 1731.88  5050.8 1737.26
  5063.1 1739.19  5230.2 1744.96  5578.3 1751.03  5840.9 1748.63  6047.6 1748.94
#Mann= 7 ,-1 , 0
  4142.9     .05       0  4391.4     .12       0  4752.6     .05       0
  4935.9     .12       0  4987.8     .05       0  4993.3     .05       0
  5011.3     .05       0
Bank Sta=4993.3,5011.3
XS Rating Curve= 0 ,0
Exp/Cntr=0.3,0.1

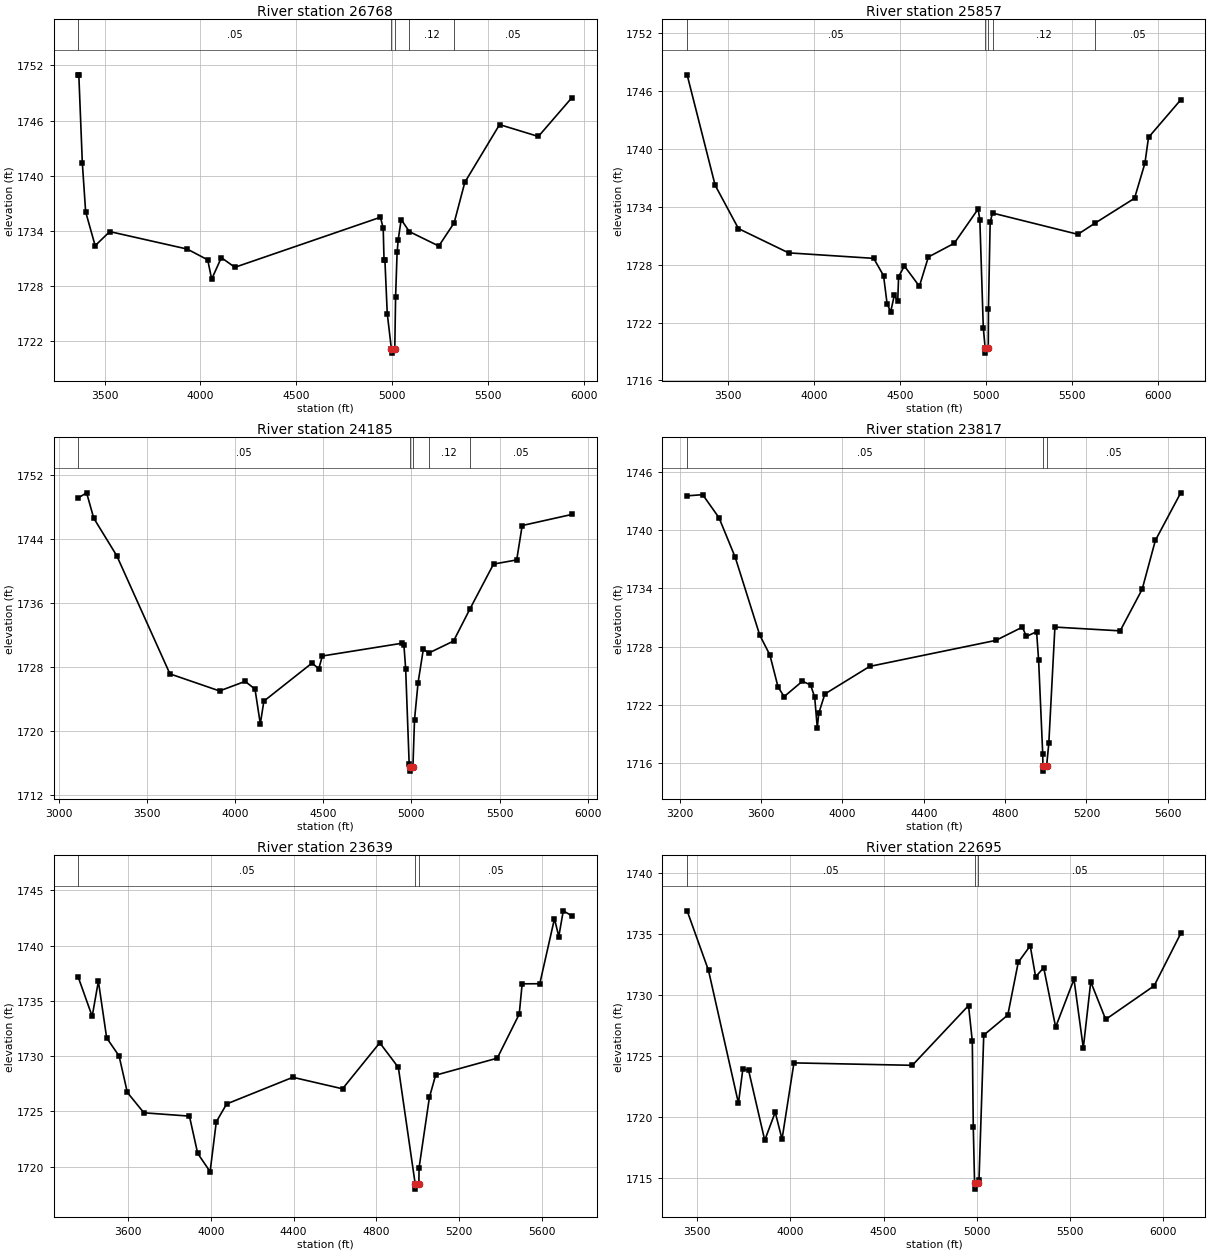
Type RM Length L Ch R = 1 ,26768   ,911,911,911
BEGIN DESCRIPTION:
Lytle Creek 27188.48
END DESCRIPTION:
XS GIS Cut Line= 4
      1600351.55      6828086.99      1600489.02       6828732.8
      1601206.35      6829336.08      1602026.15      6829868.15
#Sta/Elev= 30
  3362.5 1750.98  3365.6 1750.98    3384 1741.39  3401.2 1736.09  3450.8 1732.41
  3527.1 1733.94  3931.2 1732.04  4037.9 1730.87  4058.7 1728.77    4109 1731.11
  4179.7 1730.06  4939.2  1735.5  4953.5 1734.29  4957.7  1730.9  4962.2  1730.9
  4974.6 1725.03  4995.9 1721.23  4997.4 1720.73  5013.9 1721.23  5018.1 1726.85
    5026 1731.72  5031.9 1733.07  5047.1 1735.25  5089.8 1733.94  5243.5 1732.37
  5323.5 1734.89  5379.3  1739.3  5560.5 1745.57  5762.9 1744.28  5937.4 1748.49
#Mann= 5 ,-1 , 0
  3362.5     .05       0  4995.9     .05       0  5013.9     .05       0
  5089.8     .12       0  5323.5     .05       0
Bank Sta=4995.9,5013.9
XS Rating Curve= 0 ,0
Exp/Cntr=0.3,0.1

Type RM Length L Ch R = 1 ,25857   ,1672,1672,1672
BEGIN DESCRIPTION:
Lytle Creek 26661.68
END DESCRIPTION:
XS GIS Cut Line= 5
      1598958.73      6829461.42       1600528.3        6829916.
      1601027.33      6829917.61      1601502.48      6829749.48
      1601730.29      6829711.36
#Sta/Elev= 30
  3262.4 1747.64  3425.1 1736.21  3560.6 1731.72  3851.9 1729.21  4346.5 1728.64
  4403.7 1726.85  4424.5 1723.91  4445.4 1723.12  4466.2 1724.83    4486 1724.21
  4491.2 1726.75  4524.8 1727.85  4611.9 1725.75    4664 1728.78  4814.4  1730.2
  4953.2 1733.75  4963.2 1732.63  4983.2 1721.48  4994.2 1719.33  4995.7 1718.83
  5012.2 1719.33  5013.2 1723.42  5023.2 1732.42    5037 1733.33  5532.7 1731.13
  5630.3 1732.26    5862 1734.86  5922.4 1738.49  5943.2 1741.16  6130.5 1745.05
#Mann= 5 ,-1 , 0
  3262.4     .05       0  4994.2     .05       0  5012.2     .05       0
    5037     .12       0  5630.3     .05       0
Bank Sta=4994.2,5012.2
XS Rating Curve= 0 ,0
Exp/Cntr=0.3,0.1

Type RM Length L Ch R = 1 ,24185   ,368,368,368
BEGIN DESCRIPTION:
Lytle Creek 24387.649
END DESCRIPTION:
XS GIS Cut Line= 3
      1598867.61      6830452.34      1601270.39      6830709.28
      1601624.53      6830559.99
#Sta/Elev= 30
  3109.5 1749.19  3157.2 1749.82  3197.4 1746.65  3328.1 1741.94  3629.8 1727.13
  3911.4 1724.99  4056.7 1726.19  4112.6 1725.22  4142.7 1720.86  4162.9 1723.71
  4435.9 1728.48  4474.6 1727.78  4494.7 1729.37  4947.3 1730.97  4957.4 1730.78
  4967.4 1727.79  4987.5 1715.79  4990.6 1715.44  4992.1 1714.94  5008.6 1715.44
  5017.7 1721.38  5037.8 1726.01    5068 1730.25  5097.7 1729.73    5239 1731.24
  5332.5 1735.28  5466.1 1740.89  5597.6 1741.41  5628.6 1745.72  5910.3 1747.11
#Mann= 5 ,-1 , 0
  3109.5     .05       0  4990.6     .05       0  5008.6     .05       0
  5097.7     .12       0  5332.5     .05       0
Bank Sta=4990.6,5008.6
XS Rating Curve= 0 ,0
Exp/Cntr=0.3,0.1

Type RM Length L Ch R = 1 ,23817   ,178,178,178
BEGIN DESCRIPTION:
Lytle Creek 23884.878
END DESCRIPTION:
XS GIS Cut Line= 3
      1599058.59      6830910.67      1601180.11      6831018.31
      1601444.04      6830868.98
#Sta/Elev= 30
  3236.3 1743.52  3312.8 1743.64  3392.9 1741.27    3473 1737.18  3593.2 1729.19
  3643.2 1727.14  3683.3 1723.85  3713.3 1722.85  3803.4 1724.44  3843.5 1724.04
  3863.5 1722.81  3876.4 1719.63  3883.5 1721.13  3913.6 1723.12  4133.9 1725.96
  4754.7 1728.64  4884.8    1730  4904.9 1729.05  4954.9 1729.53  4964.9 1726.59
    4985 1716.97    4986 1715.68  4987.5 1715.18    5004 1715.68    5015 1718.05
    5045 1730.01  5365.9 1729.62  5474.1  1733.9    5539 1738.93  5663.8 1743.83
#Mann= 3 ,-1 , 0
  3236.3     .05       0    4986     .05       0    5004     .05       0
Bank Sta=4986,5004
XS Rating Curve= 0 ,0
Exp/Cntr=0.3,0.1

Type RM Length L Ch R = 1 ,23639   ,944,944,944
BEGIN DESCRIPTION:
Lytle Creek 23335.647
END DESCRIPTION:
XS GIS Cut Line= 3
      1599257.54      6831193.77      1601251.08      6831149.48
      1601514.22      6830858.43
#Sta/Elev= 30
  3359.2 1737.15  3426.7  1733.6  3456.7 1736.78  3496.7 1731.65  3556.7 1730.02
  3596.7 1726.72  3676.7 1724.88  3896.8 1724.58  3936.8 1721.21  3996.8 1719.56
  4026.8 1724.07  4076.8 1725.68  4396.9 1728.09    4637 1727.05    4817 1731.21
    4907 1728.98  4988.1 1718.48  4989.6 1717.98  5006.1 1718.48  5007.1 1719.91
  5057.1 1726.28  5087.1 1728.28  5385.2 1729.82  5491.3  1733.8  5505.5 1736.54
  5590.7 1736.55  5661.7 1742.43  5682.6 1740.81  5704.2 1743.14  5745.6 1742.69
#Mann= 3 ,-1 , 0
  3359.2     .05       0  4988.1     .03       0  5006.1     .05       0
Bank Sta=4988.1,5006.1
XS Rating Curve= 0 ,0
Exp/Cntr=0.3,0.1

Type RM Length L Ch R = 1 ,22695   ,1053,1053,1053
BEGIN DESCRIPTION:
Lytle Creek 22765.807
END DESCRIPTION:
XS GIS Cut Line= 4
      1599226.11      6831332.64      1600774.76      6831890.73
      1601101.39      6831634.54      1601687.57      6831642.74
#Sta/Elev= 30
  3446.3 1736.93    3561 1732.03  3721.5 1721.13  3745.2 1723.94  3775.9 1723.83
  3862.6 1718.08  3918.7 1720.39  3955.3 1718.17  4019.1 1724.44  4654.1 1724.24
  4955.7 1729.15  4975.8 1726.22  4981.1 1719.15    4988 1714.57  4989.5 1714.07
    5006 1714.57  5011.8 1714.85  5037.2 1726.72  5166.2 1728.37  5222.3  1732.7
  5286.5 1734.06  5315.4 1731.51  5358.8 1732.26  5422.9 1727.38  5521.2 1731.31
  5571.2 1725.66  5611.2  1731.1  5691.2 1728.01  5951.2 1730.77  6093.8 1735.07
#Mann= 3 ,-1 , 0
  3446.3     .05       0    4988     .03       0    5006     .05       0
Bank Sta=4988,5006
XS Rating Curve= 0 ,0
Exp/Cntr=0.3,0.1

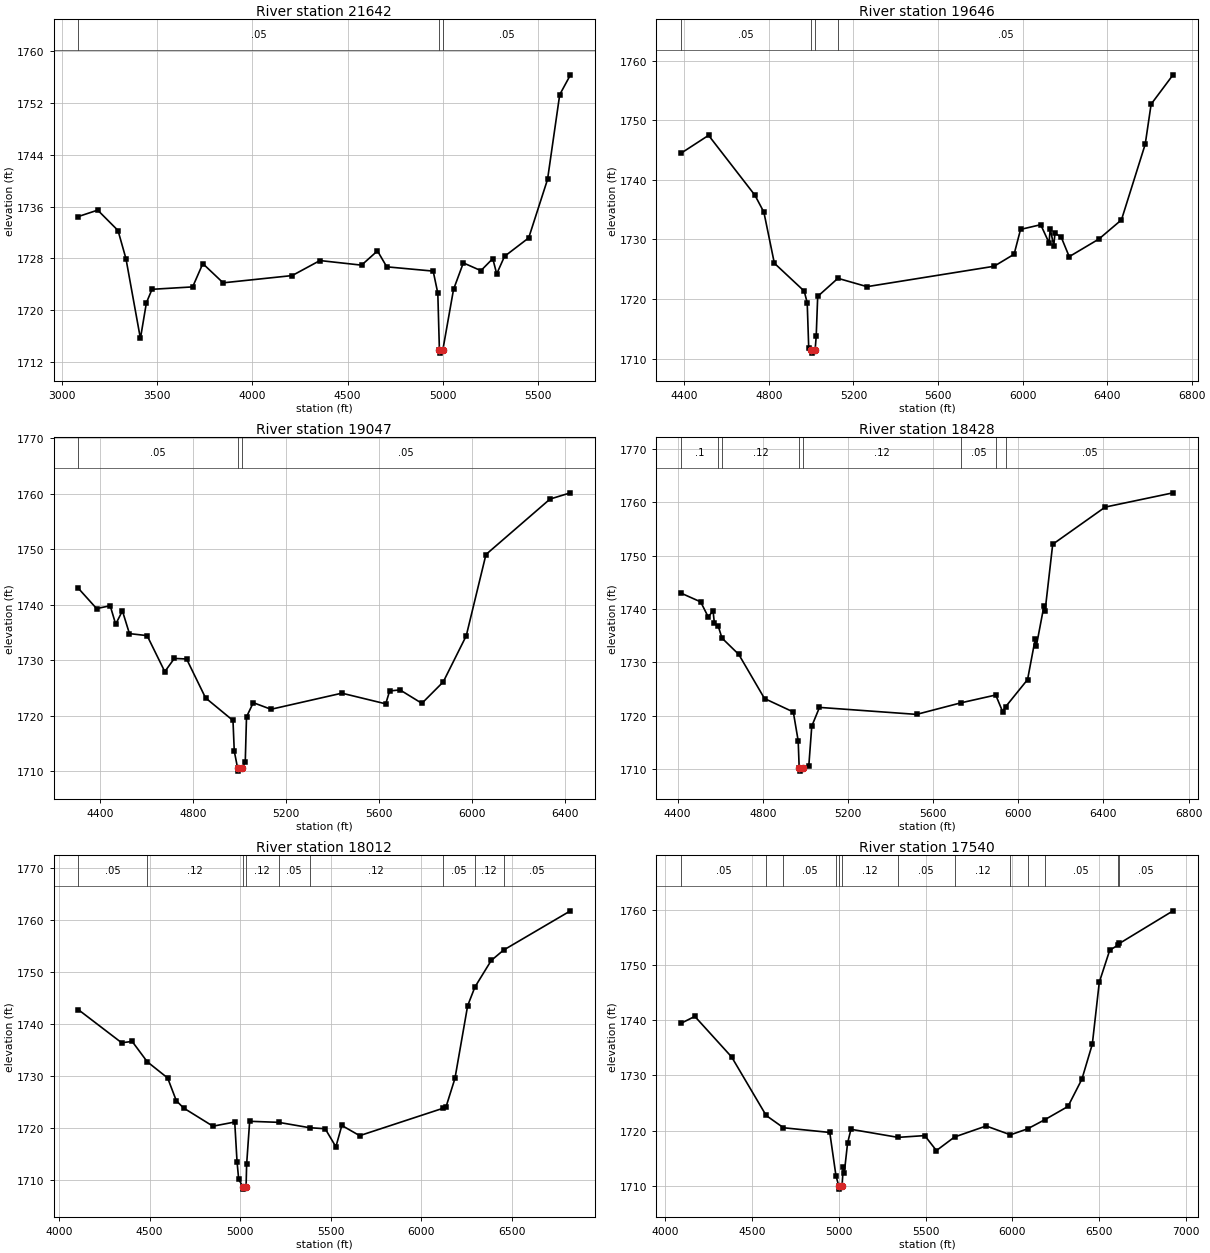
Type RM Length L Ch R = 1 ,21642   ,1996,1996,1996
BEGIN DESCRIPTION:
Lytle Creek 22183.167
END DESCRIPTION:
XS GIS Cut Line= 4
      1599273.24      6831604.78      1600477.57      6832101.73
      1600699.36      6833012.68      1600918.45      6833273.61
#Sta/Elev= 30
  3087.1 1734.47  3189.5 1735.47  3296.1 1732.32  3337.8 1727.96  3413.5 1715.64
    3445 1721.17  3474.4 1723.24  3687.4 1723.61  3740.7 1727.21  3847.2 1724.24
  4209.2 1725.36  4354.7 1727.68  4572.9 1726.97  4656.3 1729.17  4705.1 1726.71
  4948.4 1726.05  4972.7 1722.64  4981.1 1713.88  4982.6 1713.38  4999.1 1713.88
  5055.1 1723.21  5106.5 1727.32  5198.7 1726.12  5260.9 1727.98  5281.5 1725.62
  5322.5 1728.33  5449.2 1731.18    5548 1740.21  5611.8  1753.3  5668.2 1756.37
#Mann= 3 ,-1 , 0
  3087.1     .05       0  4981.1    .035       0  4999.1     .05       0
Bank Sta=4981.1,4999.1
XS Rating Curve= 0 ,0
Exp/Cntr=0.3,0.1

Type RM Length L Ch R = 1 ,19646   ,599,599,599
BEGIN DESCRIPTION:
Mapping XS ea394c71
END DESCRIPTION:
XS GIS Cut Line= 3
       1599106.3      6831910.65      1600204.42      6832978.38
       1600919.6      6833330.49
#Sta/Elev= 30
  4383.2 1744.43  4514.8 1747.46    4734 1737.42  4776.4 1734.58    4826 1726.01
  4967.3 1721.33  4981.4 1719.37  4988.6 1711.77  5000.7 1711.43  5002.2 1710.93
  5018.7 1711.43  5023.9 1713.72    5031 1720.44  5126.6 1723.48  5264.3 1722.08
  5865.5  1725.5  5960.1 1727.52  5990.6 1731.68    6086 1732.47  6125.4 1729.43
  6130.9  1731.8  6147.8 1728.91  6153.4 1731.04    6183 1730.38  6220.8 1727.11
  6361.3 1730.07  6467.9 1733.28  6580.3 1745.97  6608.3 1752.69    6712 1757.61
#Mann= 4 ,-1 , 0
  4383.2     .05       0  5000.7    .035       0  5018.7     .05       0
  5126.6     .05       0
Bank Sta=5000.7,5018.7
XS Rating Curve= 0 ,0
Exp/Cntr=0.3,0.1

Type RM Length L Ch R = 1 ,19047   ,619,619,619
BEGIN DESCRIPTION:
Mapping XS 5db95189
END DESCRIPTION:
XS GIS Cut Line= 4
      1598871.95      6832609.45      1599991.74      6833086.89
       1600191.4      6833186.71      1600660.09      6833677.11
#Sta/Elev= 30
  4306.3 1742.99  4385.7  1739.3  4444.2 1739.81  4467.8 1736.49  4496.8 1738.88
    4527 1734.79  4603.1 1734.43  4679.2 1727.94  4720.3 1730.32    4773 1730.22
  4854.7 1723.21  4972.7 1719.14  4978.2 1713.63  4992.8 1710.52  4994.3 1710.02
  5010.8 1710.52  5025.5 1711.68  5030.9 1719.79    5060 1722.35  5136.3 1721.16
  5441.4 1724.06  5630.1 1722.14  5646.9 1724.46  5691.6 1724.65  5785.7 1722.23
  5877.6 1726.09  5976.6 1734.39  6061.5 1749.04  6337.4 1759.03  6425.2 1760.15
#Mann= 3 ,-1 , 0
  4306.3     .05       0  4992.8    .035       0  5010.8     .05       0
Bank Sta=4992.8,5010.8
XS Rating Curve= 0 ,0
Exp/Cntr=0.3,0.1

Type RM Length L Ch R = 1 ,18428   ,416,416,416
BEGIN DESCRIPTION:
Mapping XS 94faf59f
END DESCRIPTION:
XS GIS Cut Line= 3
      1598633.21      6832978.36       1599544.7      6833664.14
      1600680.94      6833950.37
#Sta/Elev= 30
  4414.4 1742.99  4507.9 1741.33  4543.3 1738.52  4566.2 1739.63  4572.4 1737.31
  4589.9 1736.86    4608 1734.55    4687 1731.48  4807.8 1723.22  4943.1  1720.7
    4966  1715.3  4970.8 1710.12  4972.3 1709.62  4988.8 1710.12    5016 1710.65
  5029.8 1718.04    5066 1721.56    5522 1720.25  5730.9 1722.42  5893.9 1723.88
  5926.6 1720.73  5940.7  1721.7  6043.4 1726.77  6079.4 1734.38  6084.5 1733.03
  6120.5 1740.59  6125.6  1739.6  6161.5 1752.12  6408.1 1759.09  6726.8 1761.76
#Mann= 8 ,-1 , 0
  4414.4      .1       0  4589.9     .05       0    4608     .12       0
  4970.8     .07       0  4988.8     .12       0  5730.9     .05       0
  5893.9     .12       0  5940.7     .05       0
Bank Sta=4970.8,4988.8
XS Rating Curve= 0 ,0
Exp/Cntr=0.3,0.1

Type RM Length L Ch R = 1 ,18012   ,472,472,472
BEGIN DESCRIPTION:
Mapping XS 08cbe365
END DESCRIPTION:
XS GIS Cut Line= 4
      1598127.17      6833257.03       1598590.7      6833538.27
      1599783.41      6834069.52      1600651.61      6834121.51
#Sta/Elev= 30
  4105.5 1742.84  4345.5 1736.46  4403.7 1736.71  4486.8 1732.81  4599.5 1729.69
  4647.3 1725.33  4687.3 1723.93  4849.4 1720.43  4969.8 1721.23  4982.5 1713.63
  4991.7 1710.21  5014.5 1708.84    5016 1708.34  5032.5 1708.84  5035.5 1713.08
  5052.2 1721.37  5211.7 1721.17  5382.7 1720.14  5469.1 1719.94  5528.2 1716.47
    5561 1720.57  5659.5 1718.61  6116.8 1723.84  6135.3 1724.04  6185.4  1729.6
  6255.5 1743.56  6295.7 1747.16  6385.7 1752.26  6453.5 1754.25  6823.1  1761.8
#Mann= 9 ,-1 , 0
  4105.5     .05       0  4486.8     .12       0  5014.5     .07       0
  5032.5     .12       0  5211.7     .05       0  5382.7     .12       0
  6116.8     .05       0  6295.7     .12       0  6453.5     .05       0
Bank Sta=5014.5,5032.5
XS Rating Curve= 0 ,0
Exp/Cntr=0.3,0.1

Type RM Length L Ch R = 1 ,17540   ,876,876,876
BEGIN DESCRIPTION:
Mapping XS 22398246
END DESCRIPTION:
XS GIS Cut Line= 4
      1597950.05       6833751.8      1598413.62      6834027.86
      1599627.16      6834293.48      1600679.29      6834350.78
#Sta/Elev= 30
  4089.3 1739.42  4170.3  1740.7  4382.5 1733.35  4581.3 1722.76    4681 1720.54
  4947.6 1719.69  4983.2 1711.86    5000 1709.93  5001.5 1709.43    5018 1709.93
  5025.7 1713.46  5030.8 1712.27    5050 1717.73  5069.6 1720.26  5340.8  1718.8
  5494.7 1719.12  5561.8 1716.41  5666.3 1718.87  5848.4 1720.86  5988.3 1719.26
  6087.3 1720.35  6186.3    1722  6319.6  1724.4  6399.7 1729.33  6459.8 1735.68
  6499.9 1746.88    6560 1752.68    6605 1753.55  6615.5  1753.9  6924.8 1759.81
#Mann= 13 ,-1 , 0
  4089.3     .05       0  4581.3     .12       0    4681     .05       0
  4983.2     .12       0    5000     .07       0    5018     .12       0
  5340.8     .05       0  5666.3     .12       0  5988.3     .05       0
  6087.3     .12       0  6186.3     .05       0    6605     .12       0
  6615.5     .05       0
Bank Sta=5000,5018
XS Rating Curve= 0 ,0
Exp/Cntr=0.3,0.1

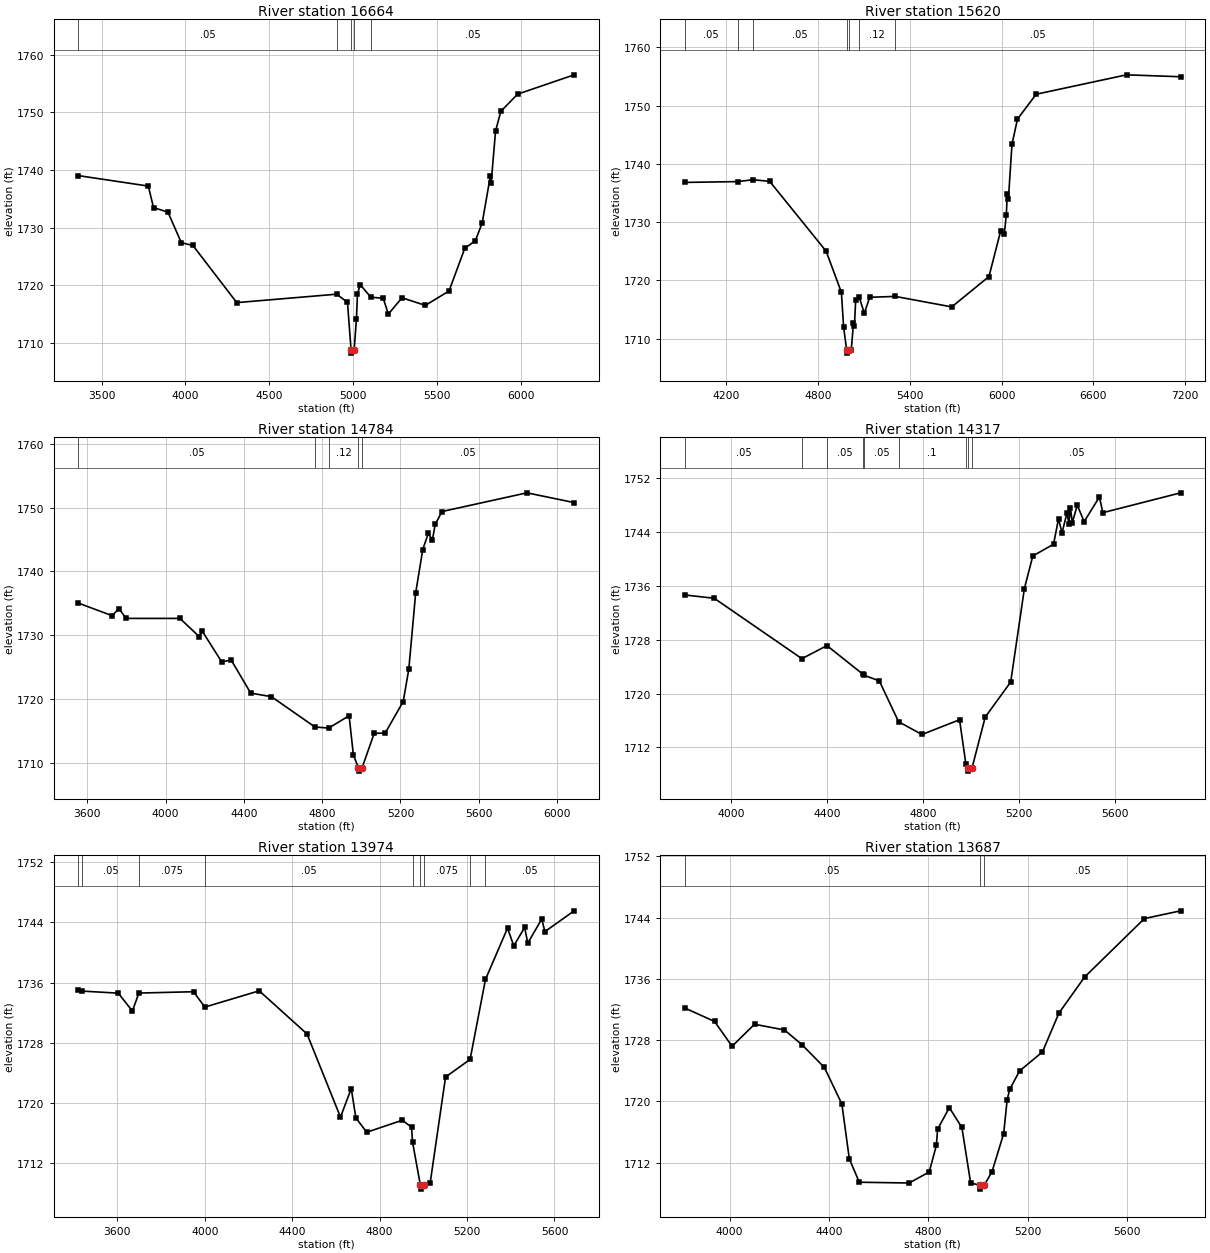
Type RM Length L Ch R = 1 ,16664   ,1044,1044,1044
BEGIN DESCRIPTION:
Mapping XS 42768128
END DESCRIPTION:
XS GIS Cut Line= 4
      1597564.65      6834085.15      1598455.29      6834605.98
      1599444.87      6835152.86      1599700.03      6835907.92
#Sta/Elev= 30
  3360.8 1739.02  3778.3 1737.21  3809.7 1733.48  3895.6 1732.69  3975.8 1727.39
  4044.4 1726.93  4306.4 1717.02  4902.4 1718.48  4967.2 1717.08  4988.8 1708.77
  4990.3 1708.27  5006.8 1708.77  5020.6  1714.1  5026.8 1718.47  5042.9 1720.14
  5106.5 1717.96  5180.6 1717.77  5211.2 1715.03  5292.6 1717.86  5431.9 1716.54
  5573.3 1719.03  5667.6 1726.44  5730.5 1727.74  5771.4 1730.83  5819.6 1738.88
  5824.9  1737.8  5851.1 1746.74  5882.5 1750.15  5982.5 1753.13  6320.2 1756.48
#Mann= 5 ,-1 , 0
  3360.8     .05       0  4902.4     .12       0  4988.8     .07       0
  5006.8     .12       0  5106.5     .05       0
Bank Sta=4988.8,5006.8
XS Rating Curve= 0 ,0
Exp/Cntr=0.3,0.1

Type RM Length L Ch R = 1 ,15620   ,836,836,836
BEGIN DESCRIPTION:
Mapping XS e763e8b1
END DESCRIPTION:
XS GIS Cut Line= 4
      1597340.69      6834277.84      1597892.79      6834824.73
      1598950.08      6835632.02      1599585.48      6836569.51
#Sta/Elev= 30
  3930.1 1736.81    4275 1736.95  4375.7 1737.27  4484.8 1736.99  4853.7 1725.01
  4953.4 1717.94    4968 1711.94    4988 1708.02  4989.5 1707.52    5006 1708.02
  5017.8 1708.08  5032.4 1712.65  5038.7 1712.24  5046.9 1716.72  5068.8  1717.2
  5103.1 1714.37  5138.4  1717.1  5305.2 1717.25  5674.5 1715.45  5917.6 1720.66
  5994.6 1728.54  6017.4 1727.88  6031.1 1731.25  6037.4 1734.88  6044.7 1733.98
  6067.9 1743.32  6103.8 1747.67  6225.9 1751.94  6816.7 1755.27    7170 1754.94
#Mann= 7 ,-1 , 0
  3930.1     .05       0    4275     .12       0  4375.7     .05       0
    4988     .05       0    5006     .05       0  5068.8     .12       0
  5305.2     .05       0
Bank Sta=4988,5006
XS Rating Curve= 0 ,0
Exp/Cntr=0.3,0.1

Type RM Length L Ch R = 1 ,14784   ,467,467,467
BEGIN DESCRIPTION:
Mapping XS 8fef07ec
END DESCRIPTION:
XS GIS Cut Line= 4
      1597101.15      6834777.89       1597840.7      6835449.73
      1598663.62      6836402.86      1598799.05      6836642.46
#Sta/Elev= 30
  3554.4 1735.05    3727 1733.08  3762.3  1734.2    3798 1732.65  4073.7 1732.65
    4173 1729.77  4187.2 1730.68  4286.6 1725.86  4335.9 1726.11  4435.2 1720.95
  4541.3 1720.39  4763.1 1715.65    4833 1715.47    4938  1717.4  4959.9 1711.25
    4986 1709.23  4987.5 1708.73    5004 1709.23  5066.3 1714.65  5122.3 1714.69
  5214.5 1719.63    5243 1724.69  5278.1 1736.61  5314.3 1743.44  5342.8 1745.97
  5363.6 1744.94  5377.9 1747.39    5413 1749.39  5846.7 1752.32    6088 1750.79
#Mann= 5 ,-1 , 0
  3554.4     .05       0  4763.1      .1       0    4833     .12       0
    4986     .07       0    5004     .05       0
Bank Sta=4986,5004
XS Rating Curve= 0 ,0
Exp/Cntr=0.3,0.1

Type RM Length L Ch R = 1 ,14317   ,343,343,343
BEGIN DESCRIPTION:
Mapping XS f29a74ee
END DESCRIPTION:
XS GIS Cut Line= 4
      1596864.99      6835204.92      1597594.17      6835829.94
      1597986.54      6836312.58      1598299.02      6836680.62
#Sta/Elev= 30
  3806.9 1734.65  3929.5 1734.16  4294.6 1725.19  4399.1 1727.13  4549.2 1722.87
  4554.5 1722.71  4616.9  1721.9  4697.3 1715.83  4794.7 1713.93  4951.3 1716.12
  4977.7 1709.53  4985.4 1708.99  4986.9 1708.49  5003.4 1708.99  5058.3 1716.52
  5164.3 1721.72  5221.4 1735.61  5256.5 1740.45  5342.8 1742.18  5363.6 1745.99
  5377.9 1743.85  5398.8 1746.84  5406.5 1745.26  5413.1  1747.6  5420.8  1745.4
  5441.7 1747.98  5470.2 1745.54  5533.9 1749.21  5548.2 1746.87  5872.1 1749.82
#Mann= 9 ,-1 , 0
  3806.9     .05       0  4294.6     .12       0  4399.1     .05       0
  4549.2     .12       0  4554.5     .05       0  4697.3      .1       0
  4977.7     .05       0  4985.4     .05       0  5003.4     .05       0
Bank Sta=4985.4,5003.4
XS Rating Curve= 0 ,0
Exp/Cntr=0.3,0.1

Type RM Length L Ch R = 1 ,13974   ,287,287,287
BEGIN DESCRIPTION:
Mapping XS 96a4ea7a
END DESCRIPTION:
XS GIS Cut Line= 4
      1596135.82      6835329.93       1597153.2       6835909.8
      1597642.79      6836364.66      1597913.62        6836698.
#Sta/Elev= 30
  3421.2 1735.03  3439.2 1734.87  3603.9  1734.6  3668.7 1732.22    3698 1734.61
  3948.2 1734.79    4000 1732.75    4249 1734.91  4467.7 1729.18  4620.7 1718.14
  4670.1 1721.93  4691.1 1718.04  4740.9 1716.13  4903.6 1717.73  4946.1  1716.8
  4950.4 1714.84  4986.5 1709.08    4988 1708.58  5004.5 1709.08  5031.2 1709.41
  5101.5 1723.46  5213.8  1725.8  5284.2 1736.42  5385.1 1743.23  5413.8 1740.88
  5463.4 1743.33  5477.8 1741.24  5541.7 1744.44  5556.1 1742.77    5690 1745.53
#Mann= 9 ,-1 , 0
  3421.2      .1       0  3439.2     .05       0    3698    .075       0
    4000     .05       0  4950.4    .075       0  4986.5    .035       0
  5004.5    .075       0  5213.8    .075       0  5284.2     .05       0
Bank Sta=4986.5,5004.5
XS Rating Curve= 0 ,0
Exp/Cntr=0.3,0.1

Type RM Length L Ch R = 1 ,13687   ,233,233,233
BEGIN DESCRIPTION:
Mapping XS ac820d99
END DESCRIPTION:
XS GIS Cut Line= 5
      1596045.59      6836236.19      1597010.84      6836316.05
      1597448.34      6836382.02      1597635.84      6836451.47
      1597906.71      6836722.33
#Sta/Elev= 30
  3820.1  1732.2  3939.9 1730.44  4010.2  1727.2  4100.5 1730.08  4220.9 1729.33
  4291.1 1727.42  4381.4 1724.44  4451.7 1719.67  4481.8 1712.49  4521.9 1709.45
  4722.6 1709.35    4803 1710.79  4831.7 1714.25  4836.8 1716.37  4883.9 1719.19
  4934.4  1716.6  4969.6 1709.37  5006.3 1709.05  5007.8 1708.55  5024.3 1709.05
  5055.8 1710.85  5102.4 1715.79  5116.5 1720.22  5126.6 1721.56  5166.3 1723.98
  5258.4 1726.46  5324.6 1731.53  5427.9 1736.24  5668.4 1743.88  5814.1 1744.89
#Mann= 3 ,-1 , 0
  3820.1     .05       0  5006.3    .035       0  5024.3     .05       0
Bank Sta=5006.3,5024.3
XS Rating Curve= 0 ,0
Exp/Cntr=0.3,0.1