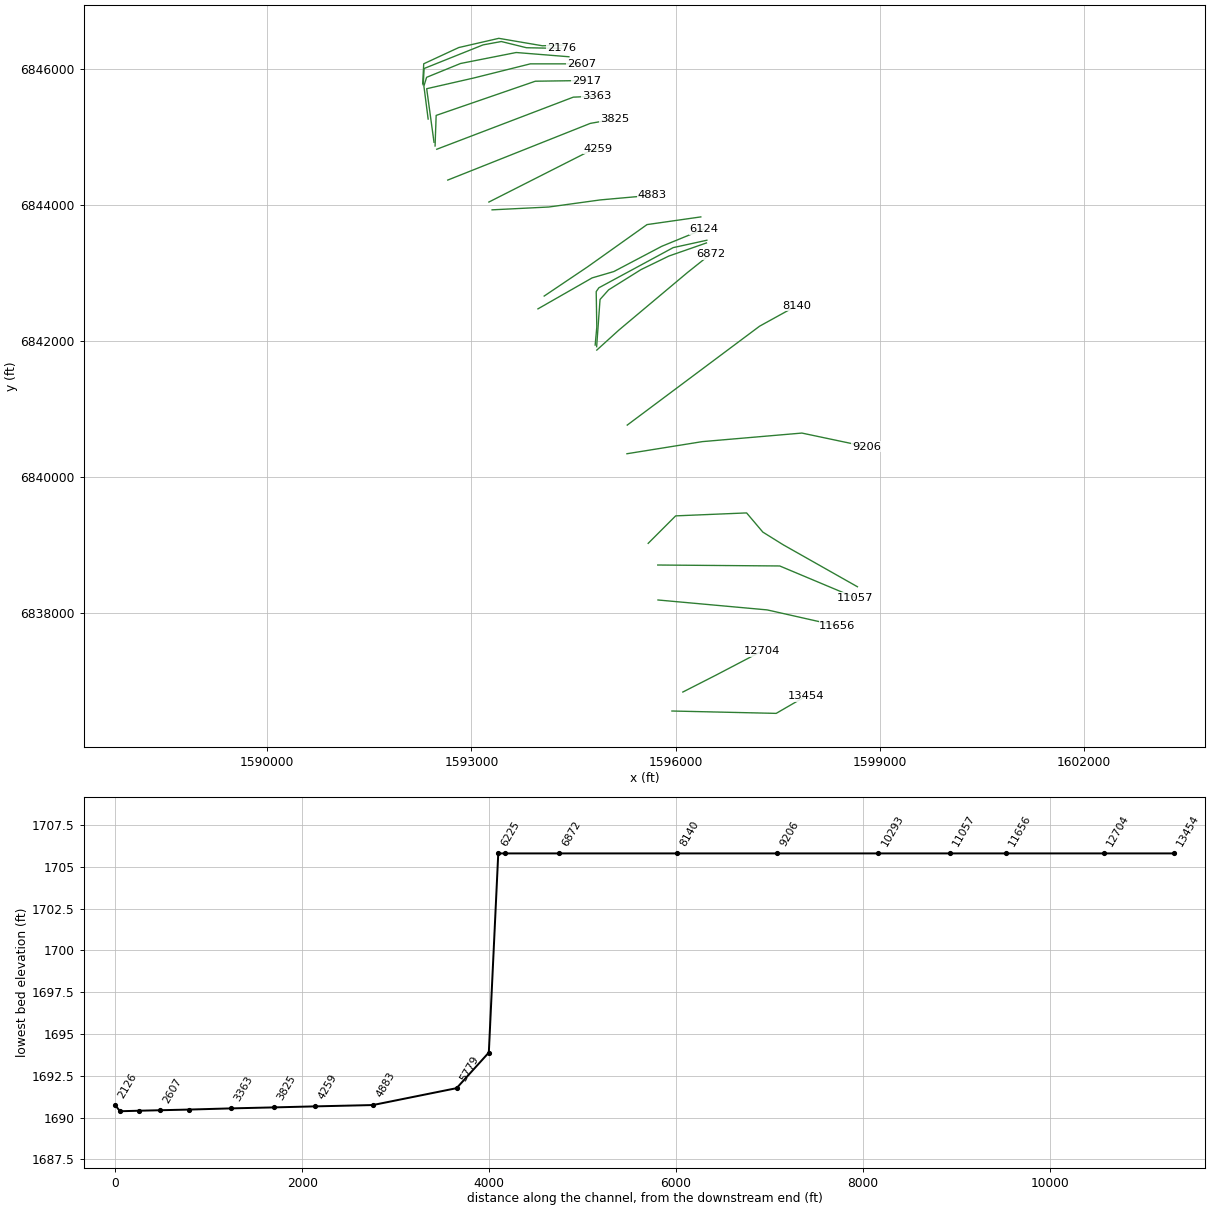
HEC-RAS study Lytle Creek.prj: Lytle Creek Base Level Engineering

--- Lytle Creek.g02 (geometry) --- (continued)

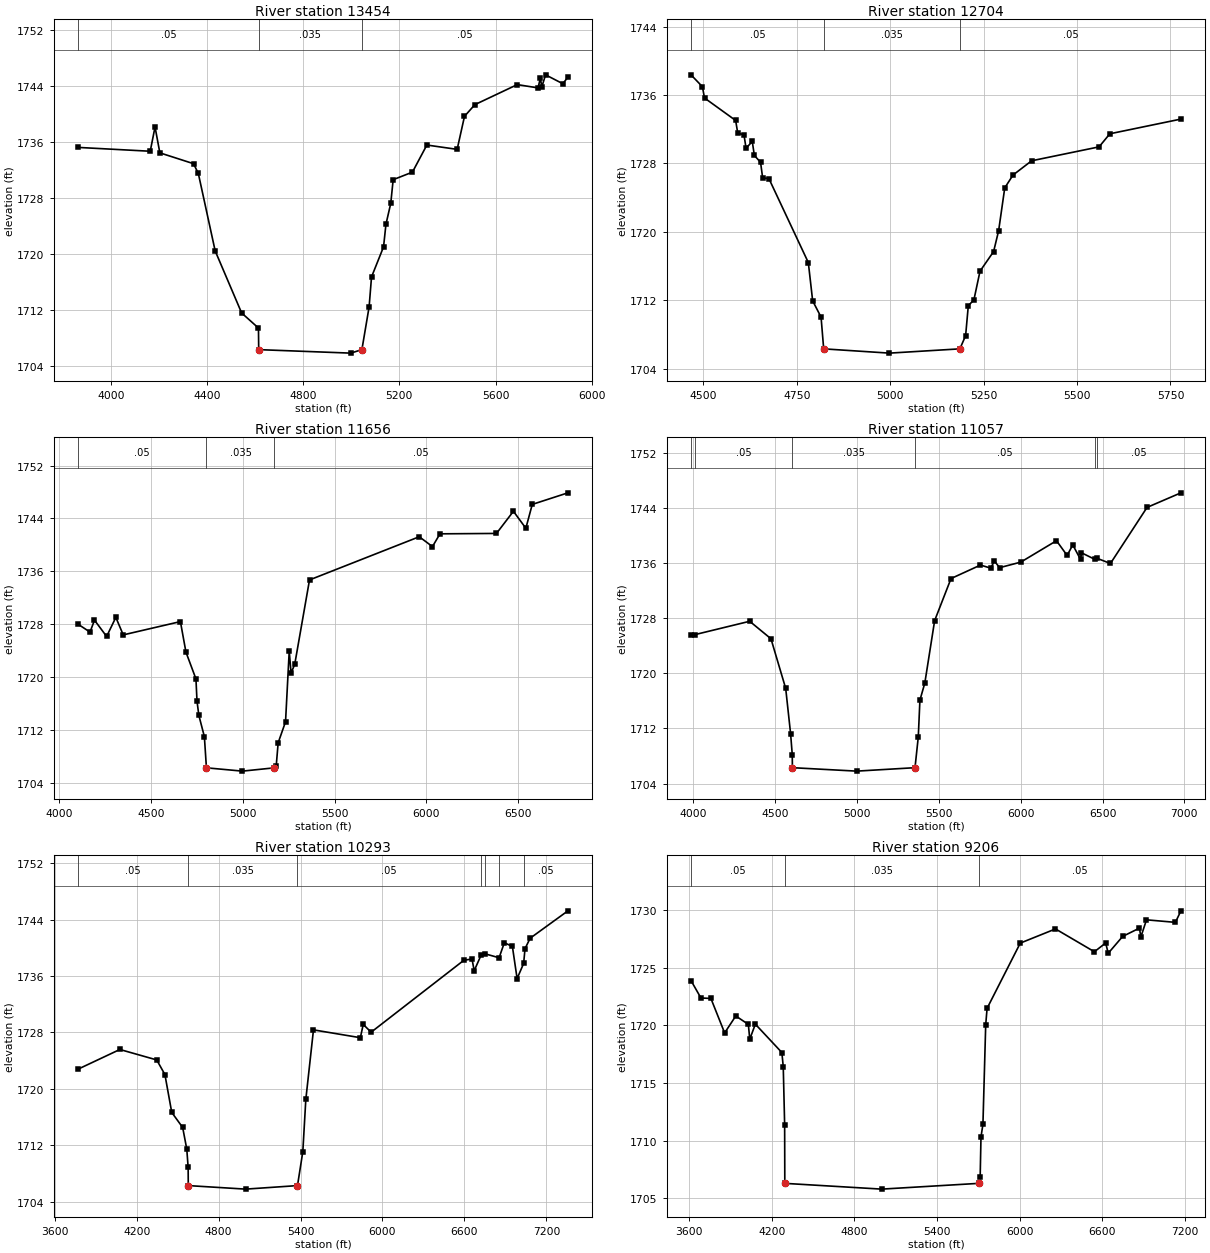
Type RM Length L Ch R = 1 ,13454   ,750,750,750
BEGIN DESCRIPTION:
Mapping XS d7a37edd
END DESCRIPTION:
XS GIS Cut Line= 3
       1595944.9      6836559.11      1597476.12      6836524.39
      1597913.59      6836777.84
#Sta/Elev= 30
    3864 1735.25  4164.2  1734.7  4184.2 1738.18  4204.2 1734.47  4344.2 1732.92
  4364.2 1731.52  4434.2 1720.44  4544.3 1711.55  4614.3 1709.39  4615.3  1706.3
    4998  1705.8  5044.4  1706.3  5074.4 1712.42  5084.4  1716.7  5134.4 1721.01
  5144.4 1724.25  5164.4 1727.24  5174.4 1730.63  5254.5 1731.71  5314.5 1735.59
  5440.5 1734.97    5471  1739.7  5514.1 1741.37  5690.5 1744.24  5776.7 1743.77
  5786.6 1745.17  5792.4  1743.9  5808.2 1745.64  5879.7 1744.37  5901.2  1745.3
#Mann= 3 ,-1 , 0
    3864     .05       0  4615.3    .035       0  5044.4     .05       0
Bank Sta=4615.3,5044.4
XS Rating Curve= 0 ,0
Exp/Cntr=0.3,0.1

Type RM Length L Ch R = 1 ,12704   ,1048,1048,1048
BEGIN DESCRIPTION:
Lytle Creek 13051.031
END DESCRIPTION:
XS GIS Cut Line= 3
      1596105.01        6836838.      1596589.39      6837085.11
      1597269.02      6837440.91
#Sta/Elev= 30
  4467.1 1738.37  4497.6 1736.98  4503.2 1735.66  4586.5 1733.03  4592.2 1731.54
  4608.8 1731.36  4614.4 1729.78    4631 1730.57  4636.6 1728.94  4653.2 1728.13
  4658.8 1726.31  4675.5 1726.23    4781  1716.4  4792.6 1711.92  4815.1 1710.01
  4822.1  1706.3    4998  1705.8  5186.5  1706.3  5201.9 1707.84  5209.1 1711.36
    5224 1712.02  5240.4 1715.39  5276.8 1717.69  5290.2 1720.12  5306.6 1725.14
  5328.7 1726.64  5378.5 1728.31    5559 1729.94  5587.8 1731.47    5778 1733.19
#Mann= 3 ,-1 , 0
  4467.1     .05       0  4822.1    .035       0  5186.5     .05       0
Bank Sta=4822.1,5186.5
XS Rating Curve= 0 ,0
Exp/Cntr=0.3,0.1

Type RM Length L Ch R = 1 ,11656   ,599,599,599
BEGIN DESCRIPTION:
Mapping XS fcdb02d6
END DESCRIPTION:
XS GIS Cut Line= 3
      1595740.03      6838191.05      1597344.17      6838045.22
      1598374.52      6837812.78
#Sta/Elev= 30
  4103.1 1728.02  4168.3 1726.82  4192.7 1728.63  4258.7 1726.16  4308.9 1729.05
  4349.1  1726.4  4660.4 1728.41  4690.5  1723.8    4745 1719.74  4750.7 1716.39
  4760.8 1714.23  4790.9 1711.01    4802  1706.3    4998  1705.8  5172.5  1706.3
  5181.8 1706.53  5192.5 1710.08  5232.7 1713.26  5252.8 1723.97  5262.8 1720.62
  5282.9 1721.97  5363.2 1734.71  5960.7 1741.24  6032.5 1739.75  6073.5 1741.68
    6381 1741.74  6473.3 1745.09  6540.9 1742.52  6575.8 1746.13  6770.1 1747.88
#Mann= 3 ,-1 , 0
  4103.1     .05       0    4802    .035       0  5172.5     .05       0
Bank Sta=4802,5172.5
XS Rating Curve= 0 ,0
Exp/Cntr=0.3,0.1

Type RM Length L Ch R = 1 ,11057   ,764,764,764
BEGIN DESCRIPTION:
Mapping XS 984a383e
END DESCRIPTION:
XS GIS Cut Line= 3
      1595736.56      6838704.94       1597528.2      6838691.05
      1598635.85      6838225.77
#Sta/Elev= 30
  3985.8 1725.55  4009.7 1725.64  4344.3 1727.58  4474.3 1725.04  4564.3 1717.82
  4594.3 1711.23  4604.3 1708.21  4605.3  1706.3    4998  1705.8  5354.3  1706.3
  5374.3 1710.76  5384.3 1716.11  5414.3 1718.61  5474.3 1727.68  5574.3 1733.79
  5754.3 1735.75  5817.4  1735.3  5839.1 1736.36    5871 1735.37  6000.6 1736.18
  6218.7 1739.29  6283.6 1737.15  6318.2 1738.68  6365.8 1736.56  6371.2 1737.54
  6453.8 1736.57  6466.7 1736.73  6548.3 1735.98  6771.9 1744.13  6978.9 1746.25
#Mann= 6 ,-1 , 0
  3985.8    .075       0  4009.7     .05       0  4605.3    .035       0
  5354.3     .05       0  6453.8    .075       0  6466.7     .05       0
Bank Sta=4605.3,5354.3
XS Rating Curve= 0 ,0
Exp/Cntr=0.3,0.1

Type RM Length L Ch R = 1 ,10293   ,1087,1087,1087
BEGIN DESCRIPTION:
Mapping XS 10ce9f81
END DESCRIPTION:
XS GIS Cut Line= 6
      1595596.14      6839023.74      1595999.77      6839427.38
      1597041.44      6839470.78      1597280.16      6839188.67
      1597579.63      6839002.03      1598669.05      6838385.71
#Sta/Elev= 30
  3770.5  1722.8  4076.8 1725.59  4346.6 1724.11  4406.6 1722.04  4456.7 1716.67
  4536.7 1714.54  4566.8 1711.47  4576.8 1708.89  4577.8  1706.3    4998  1705.8
  5377.5  1706.3  5416.5  1711.1  5438.5 1718.51  5494.5 1728.37  5837.8 1727.26
    5859 1729.14  5916.8 1728.04  6596.3 1738.24  6655.5 1738.41  6671.4 1736.75
  6721.5 1738.94  6748.6 1739.16  6853.8 1738.59  6892.2 1740.72  6951.2 1740.19
  6985.7 1735.64  7033.5 1737.78  7043.7 1739.88  7081.3 1741.36    7358 1745.24
#Mann= 7 ,-1 , 0
  3770.5     .05       0  4577.8    .035       0  5377.5     .05       0
  6721.5    .075       0  6748.6     .05       0  6853.8    .075       0
  7033.5     .05       0
Bank Sta=4577.8,5377.5
XS Rating Curve= 0 ,0
Exp/Cntr=0.3,0.1

Type RM Length L Ch R = 1 ,9206    ,1066,1066,1066
BEGIN DESCRIPTION:
Mapping XS 3c507853
END DESCRIPTION:
XS GIS Cut Line= 4
      1595283.99      6840340.62      1596390.72      6840518.56
       1597853.4      6840644.43      1598799.54      6840444.79
#Sta/Elev= 30
  3613.8 1723.89  3685.7 1722.38  3758.2 1722.34  3857.9 1719.35  3938.8 1720.82
  4030.1 1720.09  4040.2  1718.8  4080.7 1720.11  4273.2 1717.65  4283.3 1716.43
  4293.4  1711.4  4294.6  1706.3    4998  1705.8  5702.6  1706.3  5712.6 1706.83
  5718.6 1710.33  5732.7 1711.42  5752.8 1720.04  5762.8 1721.48  6003.7 1727.14
  6259.4 1728.37  6541.7 1726.39  6623.5 1727.15  6642.2 1726.26  6746.9 1727.72
  6868.8 1728.44    6879 1727.67  6919.9 1729.16  7129.7 1728.94  7169.8 1729.94
#Mann= 3 ,-1 , 0
  3613.8     .05       0  4294.6    .035       0  5702.6     .05       0
Bank Sta=4294.6,5702.6
XS Rating Curve= 0 ,0
Exp/Cntr=0.3,0.1

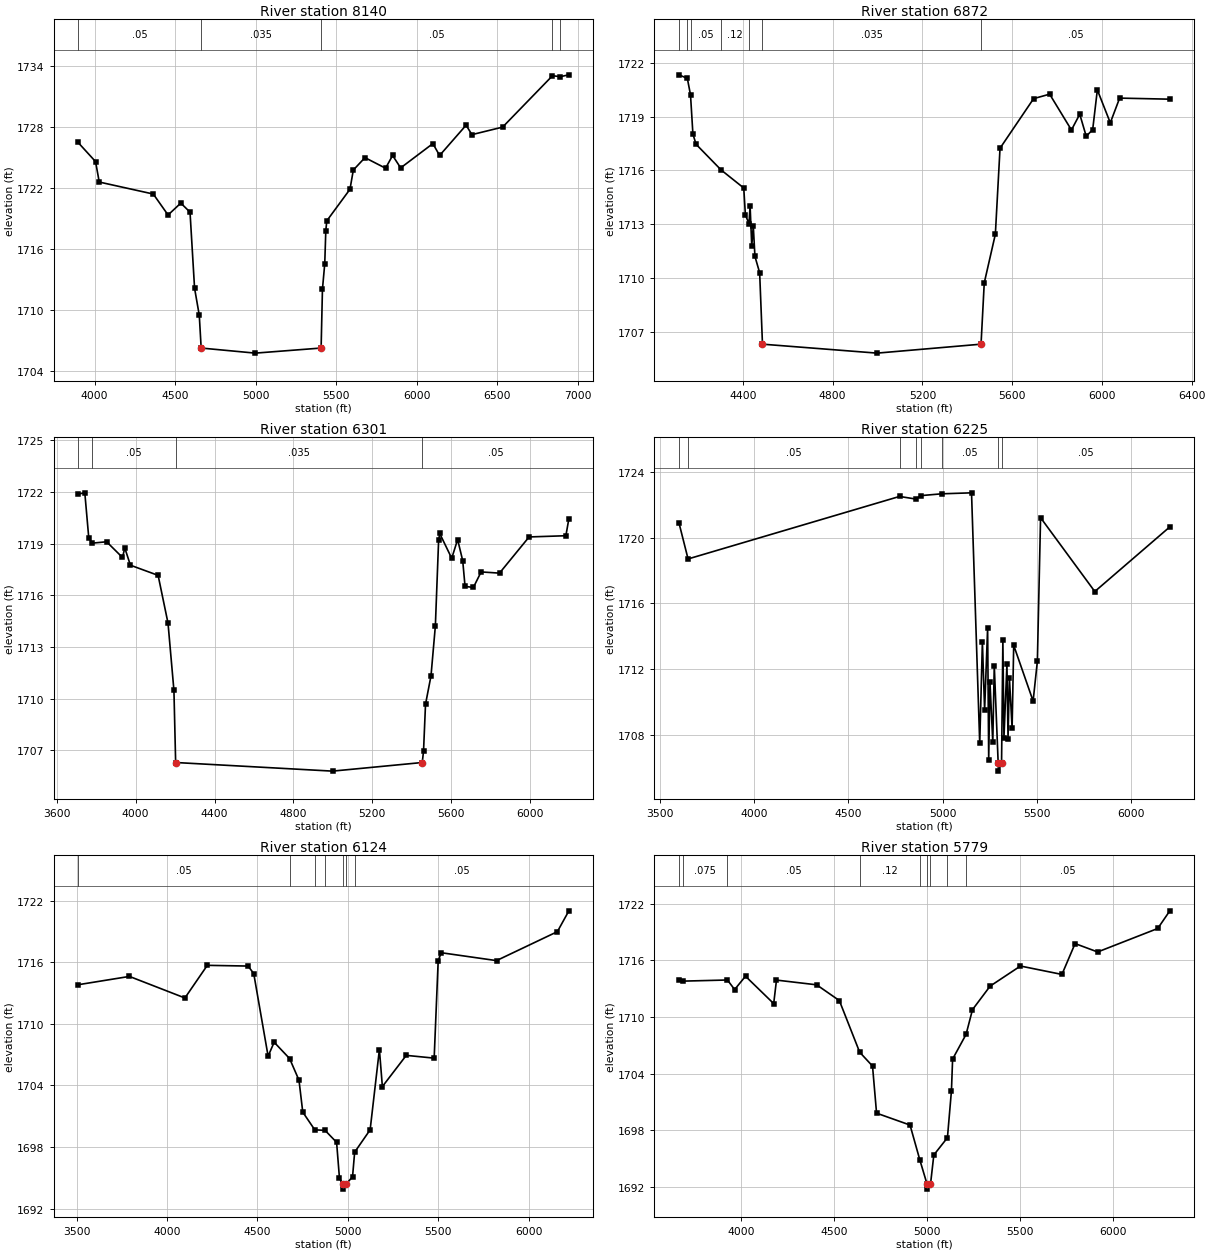
Type RM Length L Ch R = 1 ,8140    ,1268,1268,1268
BEGIN DESCRIPTION:
Mapping XS 9461dd3d
END DESCRIPTION:
XS GIS Cut Line= 3
      1595288.33      6840761.64      1597232.74      6842215.61
      1597775.26      6842515.08
#Sta/Elev= 30
  3897.8 1726.51  4006.3 1724.63  4029.2 1722.62  4364.8 1721.44  4456.5 1719.38
  4535.7 1720.55  4592.9 1719.66  4621.1 1712.18  4650.3 1709.53  4662.1  1706.3
    4998  1705.8  5406.9  1706.3  5415.2 1712.09  5429.5  1714.6    5436 1717.85
  5442.3 1718.81  5586.1 1721.91  5606.9  1723.8  5679.2 1725.02    5807 1723.98
  5850.8 1725.23  5900.8 1724.01  6100.9  1726.4  6142.6 1725.23  6307.2 1728.21
  6343.2 1727.28  6533.9 1728.02  6843.5 1733.07  6892.3 1732.98  6945.4 1733.16
#Mann= 5 ,-1 , 0
  3897.8     .05       0  4662.1    .035       0  5406.9     .05       0
  6843.5    .075       0  6892.3     .05       0
Bank Sta=4662.1,5406.9
XS Rating Curve= 0 ,0
Exp/Cntr=0.3,0.1

Type RM Length L Ch R = 1 ,6872    ,571,571,571
BEGIN DESCRIPTION:
Mapping XS 61d46f32
END DESCRIPTION:
XS GIS Cut Line= 4
      1594841.24      6841864.04      1595166.77      6842159.19
      1596169.37       6843001.2      1596512.22      6843274.61
#Sta/Elev= 30
  4115.5 1721.34  4152.6 1721.14  4166.7 1720.22  4177.4 1718.03  4191.6 1717.46
  4302.9 1716.03    4404 1715.02  4411.2 1713.52  4427.4 1713.03  4432.2 1714.03
  4439.6 1711.78  4446.4 1712.91  4453.8  1711.2  4474.8 1710.29  4487.4  1706.3
    4998  1705.8  5461.4  1706.3  5475.7 1709.72  5525.2 1712.44    5546 1717.24
  5695.6 1720.01  5767.1 1720.26  5864.2 1718.26  5901.3 1719.14  5930.1 1717.91
  5958.9 1718.28  5979.7  1720.5  6037.4 1718.66    6079 1720.04  6302.7 1719.98
#Mann= 7 ,-1 , 0
  4115.5     .05       0  4152.6     .12       0  4166.7     .05       0
  4302.9     .12       0  4427.4     .05       0  4487.4    .035       0
  5461.4     .05       0
Bank Sta=4487.4,5461.4
XS Rating Curve= 0 ,0
Exp/Cntr=0.3,0.1

Type RM Length L Ch R = 1 ,6301    ,76,76,76
BEGIN DESCRIPTION:
Mapping XS e246b9a7
END DESCRIPTION:
XS GIS Cut Line= 6
      1594839.08        6841914.      1594888.99      6842608.41
      1595014.86      6842749.47      1595490.12      6843046.77
      1595900.27      6843246.43      1596451.84      6843438.93
#Sta/Elev= 30
  3708.7 1721.88  3742.8 1721.95  3762.9 1719.33  3781.3 1719.03  3853.3 1719.11
  3933.6  1718.2  3945.5 1718.75  3973.8 1717.75  4114.3 1717.16  4164.4 1714.39
  4194.4 1710.48  4203.1  1706.3    4998  1705.8  5452.8  1706.3  5459.2 1706.96
  5469.3 1709.68  5497.1 1711.33  5519.2 1714.23  5535.7  1719.2  5541.3 1719.59
  5602.1 1718.15    5632 1719.24  5657.8 1718.01  5669.6 1716.52  5711.9 1716.46
    5751 1717.36  5844.2 1717.29  5994.2 1719.39  6180.5 1719.46  6195.8 1720.45
#Mann= 4 ,-1 , 0
  3708.7     .12       0  3781.3     .05       0  4203.1    .035       0
  5452.8     .05       0
Bank Sta=4203.1,5452.8
XS Rating Curve= 0 ,0
Exp/Cntr=0.3,0.1

Type RM Length L Ch R = 1 ,6225    ,101,101,101
BEGIN DESCRIPTION:
Mapping XS 61c250d7
END DESCRIPTION:
XS GIS Cut Line= 6
      1594817.37      6841937.79      1594841.24      6842202.59
      1594832.56      6842723.42      1594871.63      6842779.85
      1595963.21      6843370.12      1596457.98      6843478.63
#Sta/Elev= 30
  3600.4 1720.88  3648.4  1718.7  4771.5  1722.5    4859 1722.34  4884.3 1722.55
  4995.5 1722.66  5153.9 1722.72  5197.5 1707.48  5211.6 1713.67  5223.4  1709.5
  5239.4 1714.51  5245.1  1706.5  5251.8 1711.23  5266.8 1707.55  5274.7 1712.22
  5295.4  1706.3  5296.9  1705.8  5313.4  1706.3  5320.4 1713.77  5326.1 1707.83
    5342  1712.3  5347.8 1707.77    5355 1711.48  5369.4 1708.42  5377.9 1713.45
    5481 1710.06  5503.6 1712.48  5520.6 1721.21  5808.6 1716.72  6207.1 1720.65
#Mann= 8 ,-1 , 0
  3600.4     .12       0  3648.4     .05       0  4771.5     .12       0
    4859     .05       0  4884.3     .12       0  4995.5     .05       0
  5295.4     .05       0  5313.4     .05       0
Bank Sta=5295.4,5313.4
XS Rating Curve= 0 ,0
Exp/Cntr=0.3,0.1

Type RM Length L Ch R = 1 ,6124    ,345,345,345
BEGIN DESCRIPTION:
Mapping XS b8d173da
END DESCRIPTION:
XS GIS Cut Line= 5
      1593977.12      6842469.97      1594772.23      6842924.81
      1595091.68      6843018.56      1595796.54      6843390.09
      1596413.92      6843643.28
#Sta/Elev= 30
  3508.6  1713.8  3792.5 1714.61  4099.1 1712.51  4222.9 1715.69  4448.3 1715.62
  4479.6 1714.89    4559 1706.84  4592.4  1708.2  4677.8 1706.61  4729.7  1704.5
  4750.6 1701.39  4816.8 1699.67    4874 1699.61  4937.6 1698.45  4953.5 1694.94
  4972.6 1694.39  4974.1 1693.89  4990.6 1694.39  5025.7 1695.09  5037.4 1697.49
    5123 1699.67  5174.2 1707.49  5190.6 1703.88  5322.7 1706.92  5476.9 1706.65
    5499 1716.08  5515.3 1716.92  5821.5 1716.15  6157.9 1718.97  6221.6    1721
#Mann= 7 ,-1 , 0
  3508.6     .05       0  4677.8     .12       0  4816.8     .05       0
    4874     .12       0  4972.6     .07       0  4990.6     .12       0
  5037.4     .05       0
Bank Sta=4972.6,4990.6
XS Rating Curve= 0 ,0
Exp/Cntr=0.3,0.1

Type RM Length L Ch R = 1 ,5779    ,896,896,896
BEGIN DESCRIPTION:
Mapping XS 37e76429
END DESCRIPTION:
XS GIS Cut Line= 4
      1594068.65       6842658.3       1594706.7      6843088.01
      1595579.09      6843708.67      1596369.07      6843821.52
#Sta/Elev= 30
  3665.2  1713.9  3685.6  1713.8  3925.3 1713.92  3964.1 1712.91  4022.5 1714.32
    4174 1711.42    4189 1713.91  4404.9 1713.41  4526.9 1711.74  4636.1 1706.27
  4705.2  1704.8  4726.9 1699.81  4906.8 1698.55  4959.4 1694.86  4998.7 1692.26
  5000.2 1691.76  5016.7 1692.26  5034.7 1695.38  5107.8 1697.21  5129.4 1702.19
  5135.6 1705.54    5208 1708.16  5242.5 1710.78  5337.2 1713.27  5500.2  1715.4
  5723.2 1714.51  5793.9 1717.78  5915.1 1716.89  6238.1 1719.38  6303.1 1721.25
#Mann= 9 ,-1 , 0
  3665.2     .05       0  3685.6    .075       0  3925.3     .05       0
  4636.1     .12       0  4959.4     .05       0  4998.7    .035       0
  5016.7     .05       0  5107.8     .12       0    5208     .05       0
Bank Sta=4998.7,5016.7
XS Rating Curve= 0 ,0
Exp/Cntr=0.3,0.1

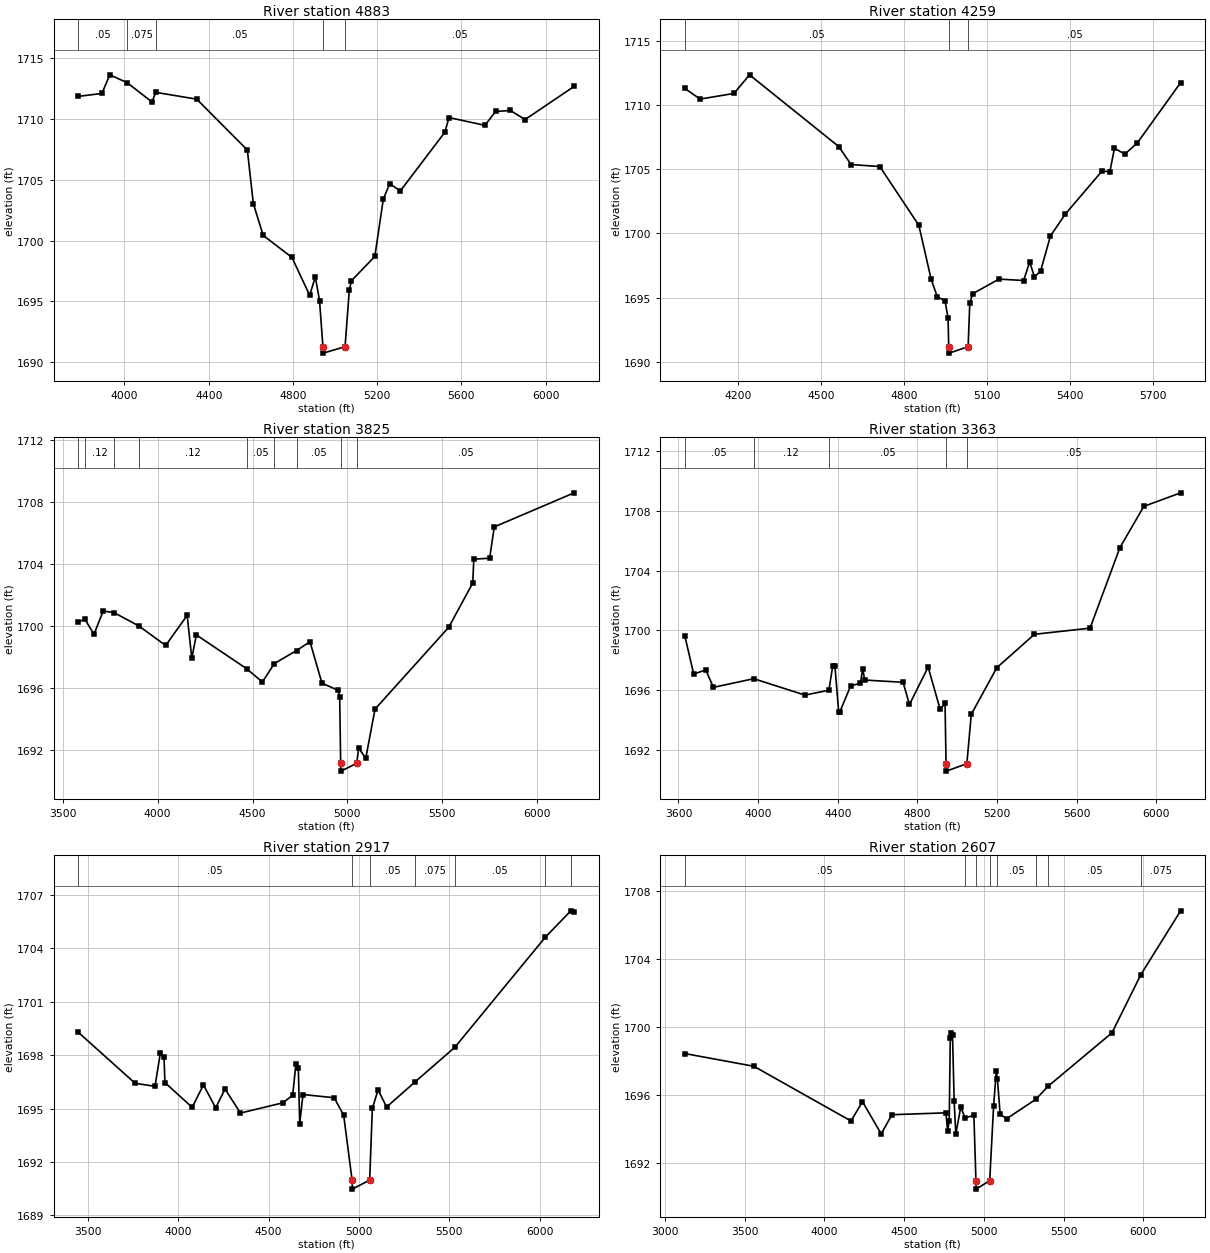
Type RM Length L Ch R = 1 ,4883    ,624,624,624
BEGIN DESCRIPTION:
Mapping XS a91f2043
END DESCRIPTION:
XS GIS Cut Line= 4
      1593303.21       6843925.4      1594136.57      6843967.07
      1594891.78      6844071.24      1595646.99      6844138.95
#Sta/Elev= 30
  3780.8 1711.84  3892.7 1712.08  3930.3 1713.61  4013.2 1712.96  4130.6 1711.38
  4148.6 1712.17  4343.3 1711.61  4583.6 1707.43  4611.9 1703.04  4658.8 1700.42
  4795.3 1698.61  4879.6  1695.5  4906.4 1697.01  4926.5 1695.06  4942.6 1691.25
  4944.1 1690.75  5047.7 1691.28  5067.9 1695.94    5078  1696.7    5189 1698.69
  5229.4  1703.4  5259.7 1704.67  5310.1 1704.07  5521.4 1708.89  5541.4  1710.1
  5712.1 1709.46  5762.3  1710.6  5832.6 1710.68  5902.9 1709.94  6135.8 1712.66
#Mann= 5 ,-1 , 0
  3780.8     .05       0  4013.2    .075       0  4148.6     .05       0
  4942.6    .035       0  5047.7     .05       0
Bank Sta=4942.6,5047.7
XS Rating Curve= 0 ,0
Exp/Cntr=0.3,0.1

Type RM Length L Ch R = 1 ,4259    ,434,434,434
BEGIN DESCRIPTION:
Mapping XS 28d35157
END DESCRIPTION:
XS GIS Cut Line= 3
       1593256.4      6844040.01      1594725.11      6844784.78
      1594865.71      6844821.23
#Sta/Elev= 30
  4008.7  1711.3  4064.2 1710.47  4186.5 1710.91  4242.6 1712.36  4565.1 1706.77
  4609.6 1705.37  4713.5 1705.21  4854.6 1700.63  4899.1 1696.42  4921.4 1695.06
  4949.3 1694.74  4960.2  1693.4  4962.5 1691.17    4964 1690.67  5032.7 1691.17
  5038.7 1694.57  5049.4  1695.3  5144.1 1696.44  5233.1 1696.33  5255.4 1697.78
  5272.1 1696.63  5294.3 1697.04  5330.2  1699.8  5383.4 1701.49    5517 1704.87
  5544.9  1704.8  5561.6 1706.64  5599.3 1706.18  5644.1 1707.05  5800.7 1711.75
#Mann= 3 ,-1 , 0
  4008.7     .05       0  4962.5    .035       0  5032.7     .05       0
Bank Sta=4962.5,5032.7
XS Rating Curve= 0 ,0
Exp/Cntr=0.3,0.1

Type RM Length L Ch R = 1 ,3825    ,462,462,462
BEGIN DESCRIPTION:
Mapping XS e9e981e6
END DESCRIPTION:
XS GIS Cut Line= 3
      1592652.18       6844362.9      1594745.95      6845196.24
      1595100.06      6845258.73
#Sta/Elev= 30
  3581.8 1700.24  3616.4 1700.41  3664.4 1699.44  3712.9 1700.95  3771.5 1700.83
  3900.5 1699.98    4042 1698.72  4155.3 1700.66  4179.6  1697.9  4203.9  1699.4
  4468.8 1697.22  4551.9 1696.36  4614.5 1697.55  4731.7 1698.39  4802.7 1698.96
  4865.6 1696.29  4951.7 1695.82  4959.2 1695.41  4964.3 1691.11  4965.8 1690.61
  5048.6 1691.11  5059.4 1692.09  5096.7 1691.44  5145.3 1694.61  5533.7 1699.89
  5660.5 1702.75  5665.9 1704.29  5749.5 1704.35  5773.8 1706.37  6194.9 1708.57
#Mann= 9 ,-1 , 0
  3581.8     .05       0  3616.4     .12       0  3771.5    .075       0
  3900.5     .12       0  4468.8     .05       0  4614.5     .12       0
  4731.7     .05       0  4964.3    .035       0  5048.6     .05       0
Bank Sta=4964.3,5048.6
XS Rating Curve= 0 ,0
Exp/Cntr=0.3,0.1

Type RM Length L Ch R = 1 ,3363    ,446,446,446
BEGIN DESCRIPTION:
Mapping XS 03b72a6c
END DESCRIPTION:
XS GIS Cut Line= 3
      1592490.71      6844816.02      1594495.95      6845581.66
      1594839.66      6845597.28
#Sta/Elev= 30
  3631.9 1699.63  3676.7 1697.06  3736.9 1697.34  3775.6 1696.17  3978.3 1696.75
  4235.4 1695.65  4355.7 1695.98    4375 1697.61  4385.8 1697.62  4405.1 1694.49
  4410.5 1694.52  4465.3 1696.28  4514.2 1696.44  4525.4 1697.42  4535.6 1696.66
  4728.3 1696.51  4760.4 1695.02  4854.2 1697.53  4914.3  1694.7  4939.1 1695.09
  4944.1 1691.05  4945.6 1690.55  5048.6 1691.05  5070.8 1694.36  5199.3 1697.49
  5388.1 1699.73  5667.4 1700.14  5817.4 1705.54  5937.5 1708.31  6122.4 1709.22
#Mann= 5 ,-1 , 0
  3631.9     .05       0  3978.3     .12       0  4355.7     .05       0
  4944.1    .035       0  5048.6     .05       0
Bank Sta=4944.1,5048.6
XS Rating Curve= 0 ,0
Exp/Cntr=0.3,0.1

Type RM Length L Ch R = 1 ,2917    ,310,310,310
BEGIN DESCRIPTION:
Mapping XS 52a88089
END DESCRIPTION:
XS GIS Cut Line= 4
      1592465.97       6844863.9      1592481.97      6845313.37
      1593938.66      6845816.03      1594691.95      6845826.42
#Sta/Elev= 30
  3446.7 1699.28    3761 1696.42  3871.1 1696.25  3900.7 1698.13  3920.8 1697.92
    3926 1696.46  4076.7 1695.07  4139.1 1696.33  4206.8 1695.04  4258.6  1696.1
    4344 1694.75  4576.7 1695.32    4633 1695.74  4650.7  1697.5  4664.2  1697.3
  4671.9 1694.16  4690.1 1695.79  4862.3 1695.61  4915.2 1694.63  4961.8 1690.98
  4963.3 1690.48  5059.1 1690.99  5073.9 1695.01  5105.6 1696.05  5152.7 1695.09
  5311.7 1696.51  5530.3 1698.44  6031.2 1704.62  6172.5  1706.1  6190.8 1706.03
#Mann= 7 ,-1 , 0
  3446.7     .05       0  4961.8    .035       0  5059.1     .05       0
  5311.7    .075       0  5530.3     .05       0  6031.2    .075       0
  6172.5      .1       0
Bank Sta=4961.8,5059.1
XS Rating Curve= 0 ,0
Exp/Cntr=0.3,0.1

Type RM Length L Ch R = 1 ,2607    ,228,228,228
BEGIN DESCRIPTION:
Mapping XS 53d90626
END DESCRIPTION:
XS GIS Cut Line= 5
      1592450.35      6844918.62      1592342.84      6845705.72
      1593032.41      6845862.91      1593865.74      6846071.24
      1594615.79      6846071.24
#Sta/Elev= 30
    3124 1698.42  3557.4 1697.67  4166.8 1694.45  4238.6 1695.59  4356.3 1693.69
  4423.2 1694.82  4762.3 1694.93  4772.7 1693.86    4783 1694.46  4789.5 1699.32
  4794.7 1699.62  4803.6  1699.5  4813.9 1695.62  4824.2 1693.68  4855.1 1695.26
  4882.6 1694.64  4937.6 1694.78  4950.6 1690.94  4952.1 1690.44  5036.9 1690.94
  5061.3 1695.32  5078.2 1697.39  5085.3 1696.92  5102.5 1694.84  5143.7 1694.59
  5325.5 1695.72  5402.6 1696.49  5803.9 1699.64  5985.5 1703.07  6234.7 1706.82
#Mann= 8 ,-1 , 0
    3124     .05       0  4882.6     .12       0  4950.6    .035       0
  5036.9     .12       0  5085.3     .05       0  5325.5    .075       0
  5402.6     .05       0  5985.5    .075       0
Bank Sta=4950.6,5036.9
XS Rating Curve= 0 ,0
Exp/Cntr=0.3,0.1

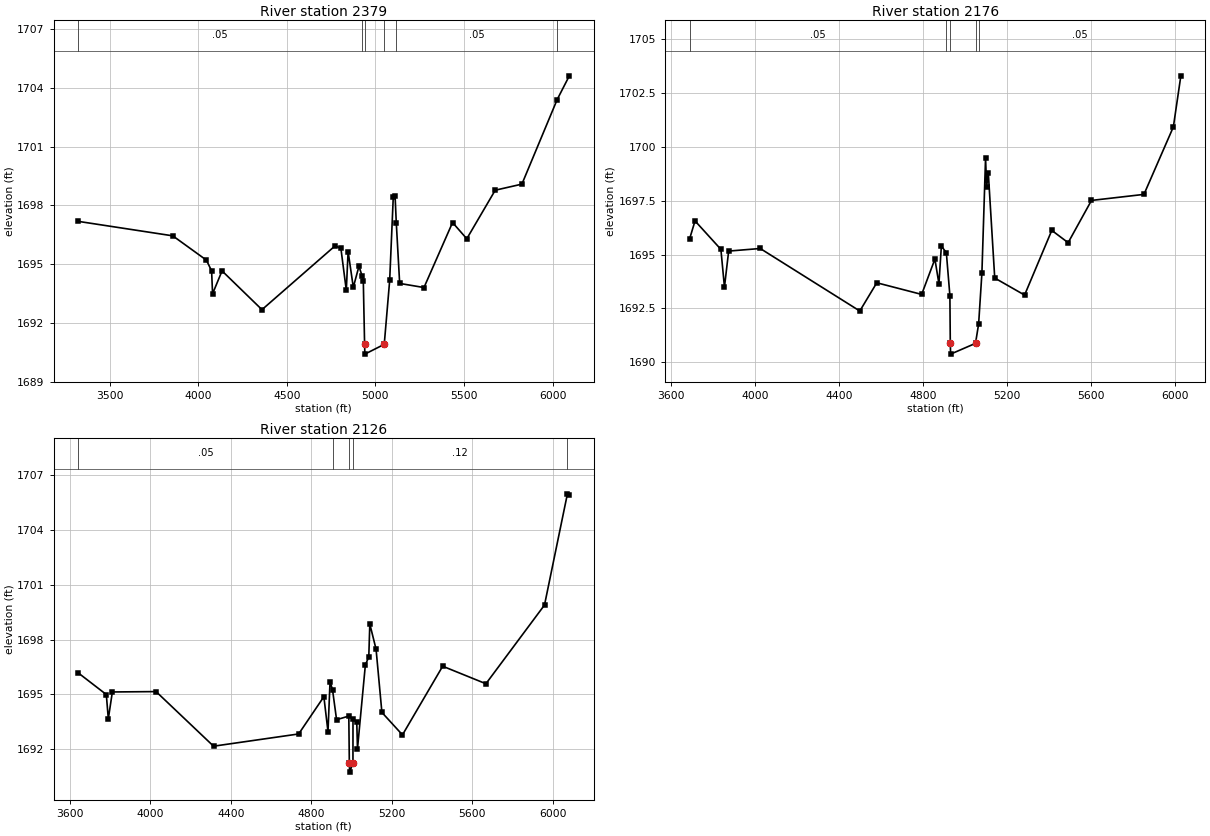
Type RM Length L Ch R = 1 ,2379    ,203,203,203
BEGIN DESCRIPTION:
Mapping XS e7afadb7
END DESCRIPTION:
XS GIS Cut Line= 6
      1592364.41      6845259.79      1592301.91      6845744.14
      1592341.48       6845873.1       1592839.7      6846076.45
      1593657.41      6846237.91      1594431.73      6846175.54
#Sta/Elev= 30
  3322.7 1697.19  3856.9 1696.45  4046.6 1695.21    4076 1694.66  4081.4 1693.49
  4134.9 1694.66  4360.2 1692.68  4772.9 1695.94  4805.5 1695.81    4836 1693.67
  4846.2 1695.65  4875.5 1693.82  4907.4  1694.9  4925.9 1694.38  4931.9 1694.16
  4939.2 1690.91  4940.7 1690.41  5050.1 1690.91  5080.7 1694.17  5101.1 1698.45
  5111.3 1698.47    5118 1697.12  5137.1 1694.02  5274.3 1693.81  5435.5 1697.13
  5515.8  1696.3  5676.3 1698.78  5826.8 1699.09  6025.9 1703.41  6094.4 1704.62
#Mann= 6 ,-1 , 0
  3322.7     .05       0  4925.9     .12       0  4939.2    .035       0
  5050.1     .12       0    5118     .05       0  6025.9    .075       0
Bank Sta=4939.2,5050.1
XS Rating Curve= 0 ,0
Exp/Cntr=0.3,0.1

Type RM Length L Ch R = 1 ,2176    ,50,50,50
BEGIN DESCRIPTION:
Mapping XS 97d56949
END DESCRIPTION:
XS GIS Cut Line= 6
      1592291.49      6845762.37      1592305.45      6846003.09
      1593170.43      6846349.88      1593438.66      6846399.36
      1593808.45      6846308.22      1594320.72      6846297.82
#Sta/Elev= 30
  3688.1 1695.73  3713.8 1696.56    3837 1695.24    3854 1693.49    3874 1695.16
  4024.5 1695.28  4498.8 1692.38  4579.7 1693.69  4793.5 1693.15  4856.6 1694.79
  4875.8 1693.64  4887.3 1695.39  4911.1 1695.09    4928 1693.09  4929.9 1690.88
  4931.4 1690.38    5050 1690.88  5064.9 1691.78  5080.5 1694.14  5097.9 1699.48
    5103 1698.14    5111 1698.79  5141.6 1693.91  5283.8 1693.12  5413.4 1696.12
  5491.3 1695.55  5602.5 1697.51  5852.5 1697.79  5992.6 1700.92  6028.3 1703.29
#Mann= 5 ,-1 , 0
  3688.1     .05       0  4911.1     .12       0  4929.9    .035       0
    5050     .12       0  5064.9     .05       0
Bank Sta=4929.9,5050
XS Rating Curve= 0 ,0
Exp/Cntr=0.3,0.1

Type RM Length L Ch R = 1 ,2126    ,52,52,52
BEGIN DESCRIPTION:
Mapping XS ff393b14
END DESCRIPTION:
XS GIS Cut Line= 6
      1592283.68      6845777.98      1592299.37      6846072.13
      1592813.66      6846310.82       1593402.2      6846446.24
      1594042.82      6846336.86      1594368.38      6846347.28
#Sta/Elev= 30
  3641.2 1696.18  3781.4 1694.99  3791.4 1693.66  3811.5 1695.13  4028.8 1695.15
  4314.6 1692.16  4737.6 1692.83  4862.9 1694.87  4883.4 1692.96  4893.6  1695.7
  4906.1 1695.24  4926.1 1693.61  4986.9 1693.81  4989.5 1691.24    4991 1690.74
  5007.5 1691.24  5007.7 1693.67  5026.5 1693.46    5030 1692.02  5069.2 1696.61
  5086.2 1697.05  5091.3 1698.85  5122.4 1697.47  5151.4 1694.01  5253.6 1692.78
  5453.5 1696.54  5668.5 1695.58  5959.7 1699.89  6073.6 1705.98  6083.1 1705.89
#Mann= 5 ,-1 , 0
  3641.2     .05       0  4906.1     .12       0  4989.5     .07       0
  5007.5     .12       0  6073.6    .075       0
Bank Sta=4989.5,5007.5
XS Rating Curve= 0 ,0
Exp/Cntr=0.3,0.1