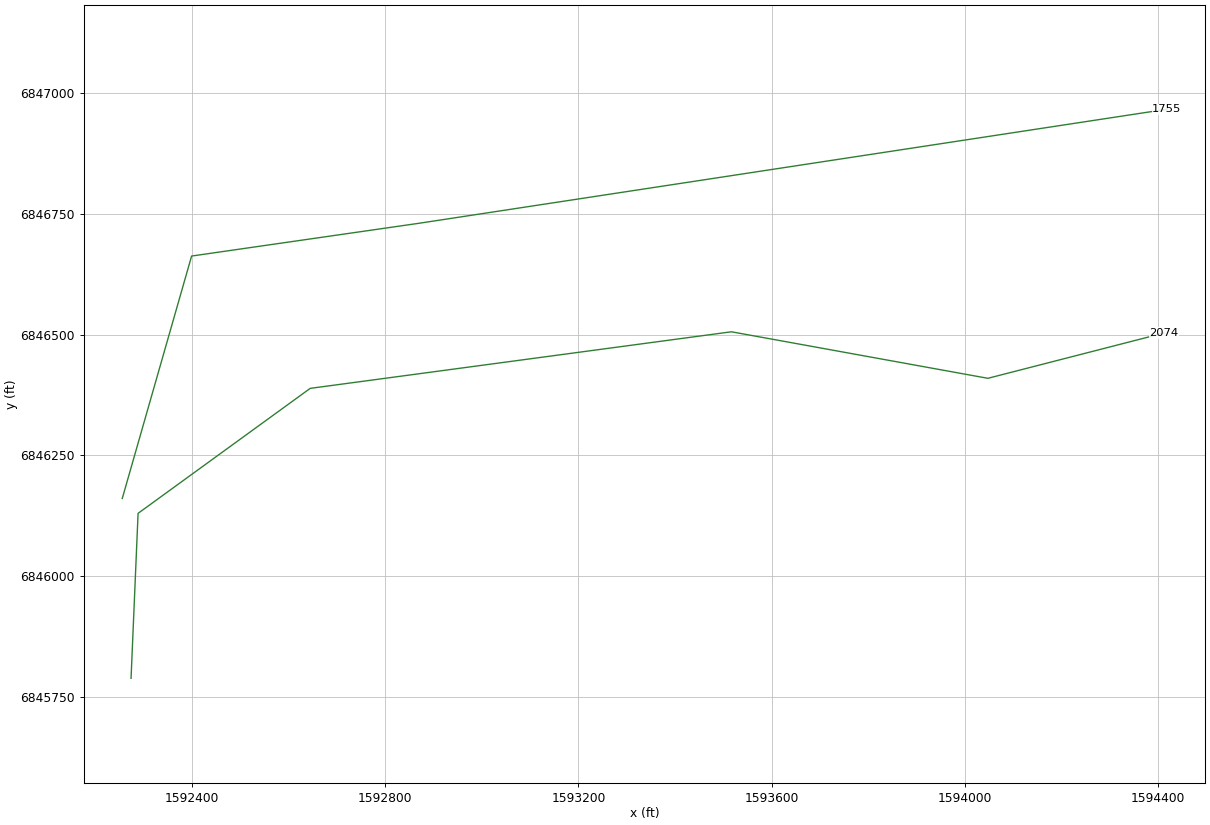
HEC-RAS study Lytle Creek.prj: Lytle Creek Base Level Engineering

--- Lytle Creek.g02 (geometry) --- (continued)

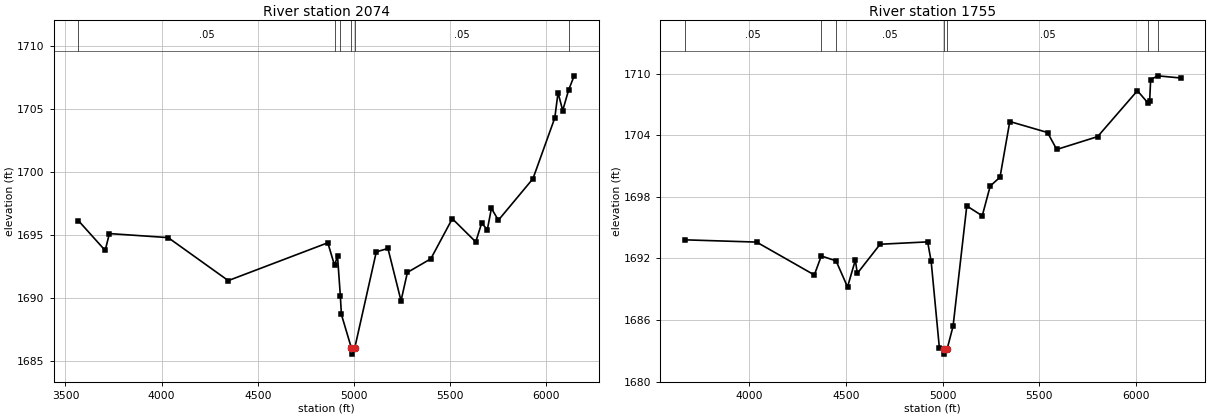
Type RM Length L Ch R = 1 ,2074    ,319,319,319
BEGIN DESCRIPTION:
Mapping XS eb4e3603
END DESCRIPTION:
XS GIS Cut Line= 6
      1592273.26      6845788.43      1592287.81      6846130.06
      1592644.38      6846388.95      1593516.78      6846506.13
      1594048.03      6846409.78      1594412.62      6846503.53
#Sta/Elev= 30
  3566.9 1696.14  3706.6 1693.77  3728.4 1695.11  4034.1 1694.79  4346.8 1691.38
  4864.7 1694.38  4899.6 1692.59  4915.1 1693.33  4929.8 1690.18  4935.3  1688.7
  4986.9 1686.05  4988.4 1685.55  5004.9 1686.05  5116.9 1693.66  5177.5 1693.93
  5245.5 1689.78  5278.7 1692.03  5400.5 1693.11  5512.2 1696.29  5634.2 1694.45
  5664.8 1695.93  5694.6 1695.43  5715.7 1697.11  5751.9 1696.17  5931.7 1699.46
  6045.3 1704.28  6062.2 1706.28  6086.6 1704.87  6117.4  1706.5  6146.1 1707.62
#Mann= 6 ,-1 , 0
  3566.9     .05       0  4899.6     .12       0  4929.8     .05       0
  4986.9    .035       0  5004.9     .05       0  6117.4      .1       0
Bank Sta=4986.9,5004.9
XS Rating Curve= 0 ,0
Exp/Cntr=0.3,0.1

Type RM Length L Ch R = 1 ,1755    ,0,0,0
BEGIN DESCRIPTION:
Lytle Creek 5095.985
END DESCRIPTION:
XS GIS Cut Line= 4
      1592255.04      6846160.84      1592398.69      6846663.03
      1592870.08      6846730.96       1594418.7      6846967.07
#Sta/Elev= 30
  3666.7 1693.81  4038.2 1693.59  4336.8 1690.39  4372.9 1692.24  4449.3 1691.76
  4508.6 1689.22    4549 1691.84  4559.1 1690.54  4677.1 1693.38  4923.1 1693.61
  4941.3  1691.7  4983.8 1683.27  5005.9 1683.18  5007.4 1682.68  5023.9 1683.18
  5054.6  1685.4  5125.5 1697.11  5205.5 1696.15  5246.8 1699.05  5297.4 1699.91
    5348 1705.33  5543.3 1704.26  5590.8 1702.61  5802.4 1703.86  6008.2 1708.33
  6060.8 1707.18  6071.7 1707.36  6076.7 1709.41  6113.1 1709.78  6231.8 1709.57
#Mann= 7 ,-1 , 0
  3666.7     .05       0  4372.9    .075       0  4449.3     .05       0
  5005.9    .035       0  5023.9     .05       0  6060.8    .075       0
  6113.1     .05       0
Bank Sta=5005.9,5023.9
XS Rating Curve= 0 ,0
Exp/Cntr=0.3,0.1

Chan Stop Cuts=-1
Use User Specified Reach Order=0
Composite Channel Slope=5