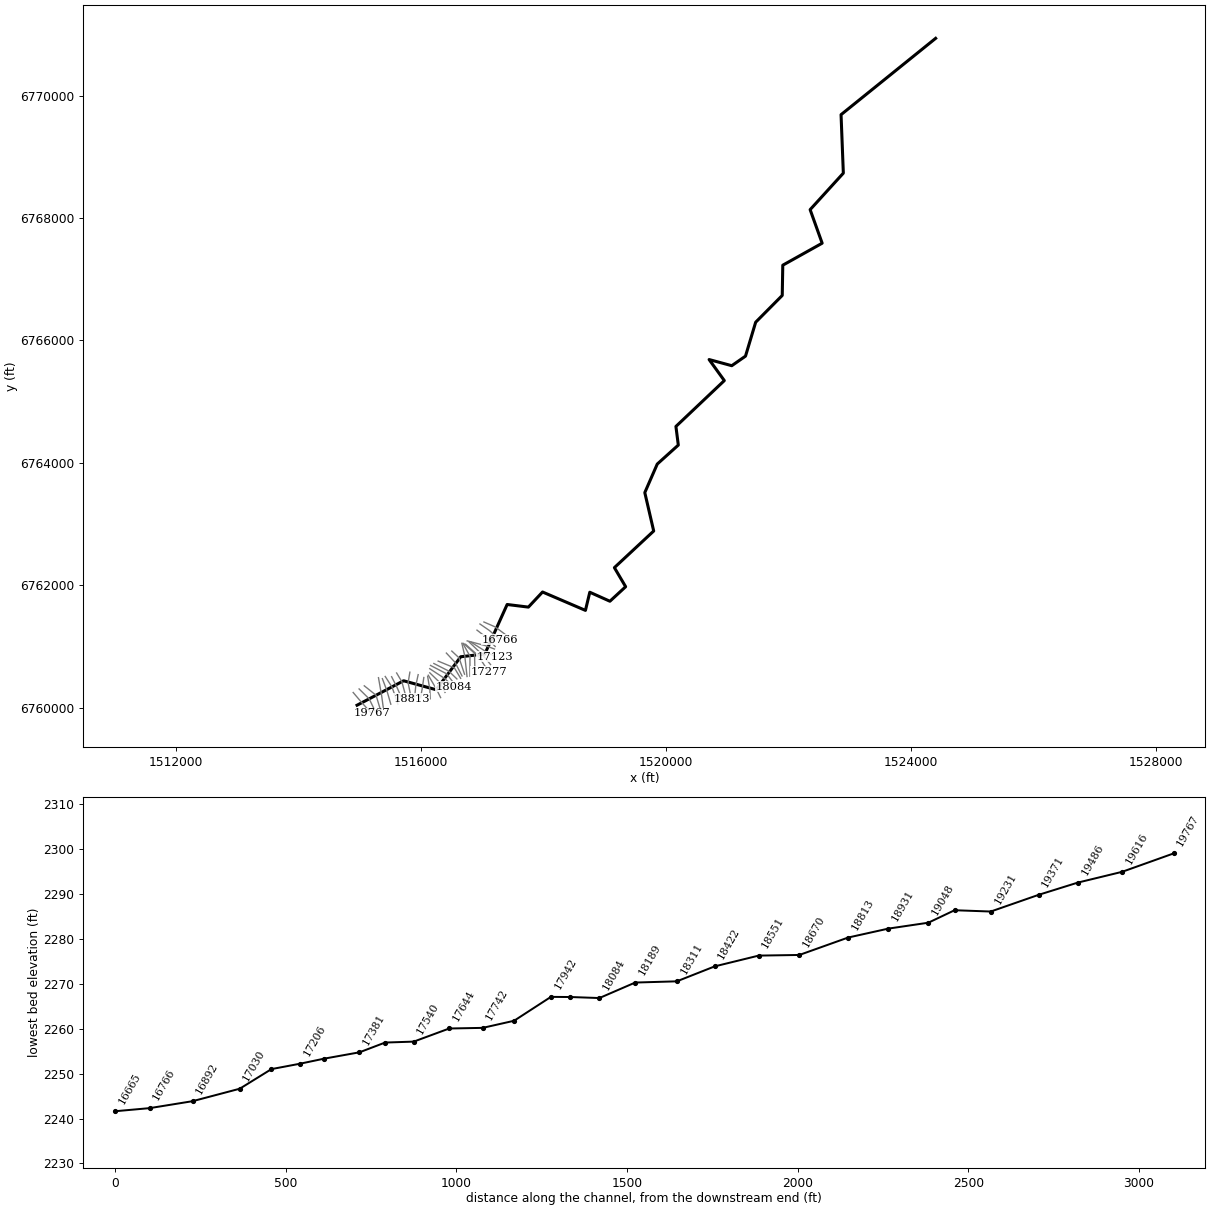
--- Pleasant Run.prj (project) ---

Proj Title=Pleasant Run Base Level Engineering
Current Plan=p01
Default Exp/Contr=0.3,0.1
English Units
Geom File=g01
Flow File=f01
Plan File=p01
BEGIN DESCRIPTION:
Pleasant Run
END DESCRIPTION:

--- Pleasant Run.p01 (plan) ---

Plan Title=Multiple Run
Short Identifier=Multiple
Geom File=g01
Flow File=f01
Subcritical Flow
K Sum by GR= 0
Std Step Tol= 0.01
Critical Tol= 0.01
Num of Std Step Trials= 20
Max Error Tol= 0.3
Flow Tol Ratio= 0.001
Split Flow NTrial= 30
Split Flow Tol= 0.02
Split Flow Ratio= 0.02
Log Output Level= 0
Friction Slope Method= 1
Unsteady Friction Slope Method= 2
Unsteady Bridges Friction Slope Method= 1
Parabolic Critical Depth
Global Vel Dist=  1 , 1 , 1
Global Log Level= 0
CheckData=True
Encroach Param= -1, 0, 0, 0
BEGIN DESCRIPTION:
Multiple Run
END DESCRIPTION:

--- Pleasant Run.f01 (steady flow) ---

Flow Title=Multiple
Number of Profiles=7
Profile Names=10-year,25-year,50-year,1pct_min,100-year,1pct_plu,500-year
River Rch & RM= Pleasant Run,Reach-1,19767
     322     459     576     450     721     991    1140
River Rch & RM= Pleasant Run,Reach-1,13727
     426     617     782     616     987    1360    1590
River Rch & RM= Pleasant Run,Reach-1,12293
     484     706     898     709    1140    1560    1840
River Rch & RM= Pleasant Run,Reach-1,9477
     568     834    1070     846    1360    1870    2220
River Rch & RM= Pleasant Run,Reach-1,8178
     625     919    1180     934    1500    2060    2450
River Rch & RM= Pleasant Run,Reach-1,4117
     658     970    1240     989    1590    2180    2610
River Rch & RM= Pleasant Run,Reach-1,1890
     686    1010    1300    1040    1660    2280    2730
Boundary for River Rch & Prof#=Pleasant Run,Reach-1,1
Up Type=0
Dn Type=3
Dn Slope=0.005
Boundary for River Rch & Prof#=Pleasant Run,Reach-1,2
Up Type=0
Dn Type=3
Dn Slope=0.005
Boundary for River Rch & Prof#=Pleasant Run,Reach-1,3
Up Type=0
Dn Type=3
Dn Slope=0.005
Boundary for River Rch & Prof#=Pleasant Run,Reach-1,4
Up Type=0
Dn Type=3
Dn Slope=0.005
Boundary for River Rch & Prof#=Pleasant Run,Reach-1,5
Up Type=0
Dn Type=3
Dn Slope=0.005
Boundary for River Rch & Prof#=Pleasant Run,Reach-1,6
Up Type=0
Dn Type=3
Dn Slope=0.005
Boundary for River Rch & Prof#=Pleasant Run,Reach-1,7
Up Type=0
Dn Type=3
Dn Slope=0.005

--- Pleasant Run.g01 (geometry) ---

Geom Title=Existing Conditions

River Reach=Pleasant Run,Reach-1
Reach XY= 30
      1514955.00      6760038.00      1515715.63      6760437.40
      1516246.70      6760291.07      1516648.79      6760830.20
      1517041.63      6760874.62      1517406.56      6761684.26
      1517753.53      6761641.53      1517984.77      6761888.50
      1518685.15      6761587.91      1518756.25      6761884.64
      1519084.75      6761737.36      1519341.89      6761974.79
      1519158.01      6762286.57      1519800.03      6762885.42
      1519654.64      6763513.20      1519858.16      6763979.71
      1520201.91      6764289.64      1520163.02      6764594.34
      1520953.51      6765343.91      1520705.00      6765688.00
      1521075.08      6765587.32      1521299.41      6765743.61
      1521465.47      6766297.83      1521899.53      6766735.56
      1521908.37      6767229.97      1522551.54      6767589.49
      1522355.00      6768138.00      1522897.32      6768734.30
      1522860.05      6769690.55      1524405.00      6770938.00

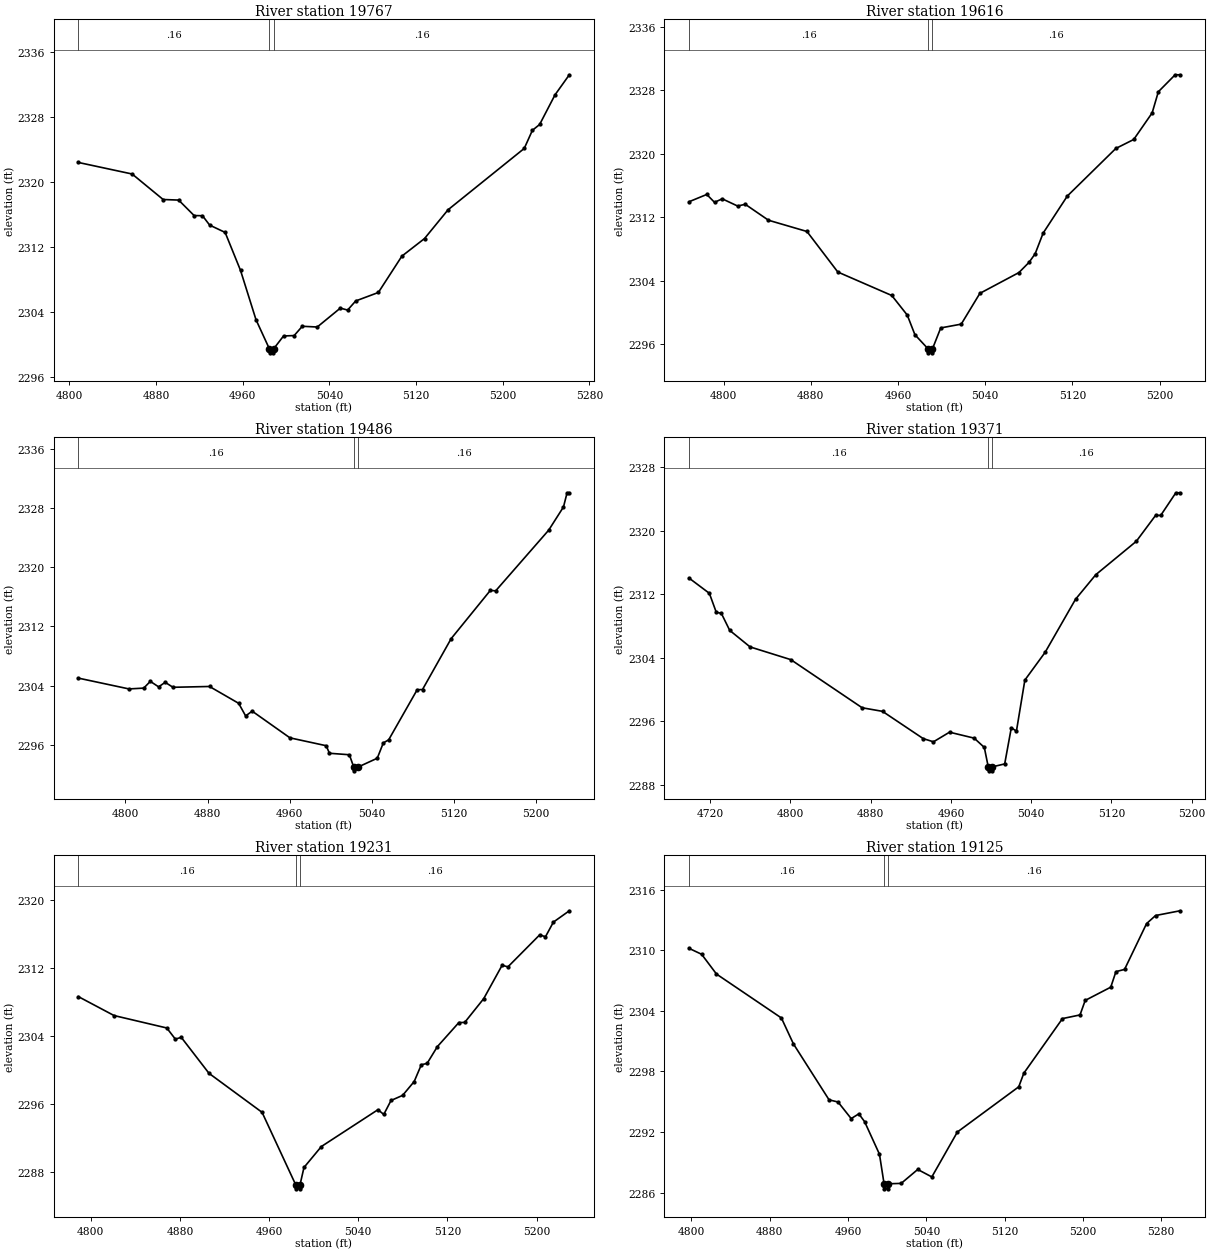
Type RM Length L Ch R = 1,19767,151,151,151
BEGIN DESCRIPTION:
Pleasant Run 4758
END DESCRIPTION:
XS GIS Cut Line= 3
      1514891.86      6760245.70      1515015.86      6760099.50
      1515190.02      6759904.57
#Sta/Elev= 30
  4808.3 2322.39  4858.0 2320.97  4886.6 2317.84  4900.9 2317.77  4915.2 2315.87
  4922.9 2315.85  4929.5 2314.70  4943.8 2313.80  4958.0 2309.14  4972.3 2303.08
  4984.6 2299.52  4984.9 2299.02  4988.4 2299.02  4988.6 2299.52  4997.7 2301.09
  5007.5 2301.14  5015.0 2302.28  5028.8 2302.19  5050.1 2304.51  5056.8 2304.27
  5064.3 2305.39  5085.2 2306.43  5106.9 2310.89  5127.8 2313.05  5149.5 2316.58
  5219.8 2324.11  5227.3 2326.33  5234.0 2327.05  5248.2 2330.69  5261.4 2333.15
#Mann=3,-1,0
  4808.3    0.16       0  4984.6    0.07       0  4988.6    0.16       0
Bank Sta=4984.6,4988.6
Exp/Cntr=0.3,0.1

Type RM Length L Ch R = 1,19616,130,130,130
BEGIN DESCRIPTION:
Pleasant Run 4759
END DESCRIPTION:
XS GIS Cut Line= 3
      1514988.22      6760304.29      1515153.42      6760141.83
      1515248.62      6759944.94
#Sta/Elev= 30
  4768.3 2313.97  4784.6 2314.89  4791.7 2313.90  4798.8 2314.34  4812.9 2313.43
  4819.9 2313.65  4841.2 2311.64  4876.5 2310.22  4904.8 2305.11  4954.3 2302.15
  4968.5 2299.68  4975.5 2297.21  4987.6 2295.42  4987.9 2294.92  4991.4 2294.92
  4991.6 2295.42  4999.2 2298.06  5018.0 2298.54  5035.1 2302.42  5070.9 2305.04
  5080.2 2306.33  5085.8 2307.41  5093.1 2310.01  5115.3 2314.69  5159.8 2320.69
  5176.2 2321.82  5193.1 2325.17  5198.8 2327.84  5214.2 2329.98  5218.7 2329.98
#Mann=3,-1,0
  4768.3    0.16       0  4987.6    0.07       0  4991.6    0.16       0
Bank Sta=4987.6,4991.6
Exp/Cntr=0.3,0.1

Type RM Length L Ch R = 1,19486,115,115,115
BEGIN DESCRIPTION:
Pleasant Run 4757
END DESCRIPTION:
XS GIS Cut Line= 3
      1515072.88      6760355.05      1515265.08      6760201.50
      1515331.98      6759978.73
#Sta/Elev= 30
  4754.0 2305.03  4803.4 2303.57  4817.8 2303.68  4824.2 2304.59  4832.3 2303.85
  4838.7 2304.46  4846.3 2303.79  4881.9 2303.90  4910.3 2301.63  4917.1 2299.93
  4923.5 2300.57  4960.3 2296.97  4995.6 2295.91  4998.8 2294.89  5018.2 2294.69
  5022.5 2293.02  5022.8 2292.52  5026.5 2293.02  5045.4 2294.22  5051.3 2296.29
  5056.5 2296.70  5084.3 2303.46  5089.5 2303.49  5117.4 2310.35  5155.6 2316.86
  5160.8 2316.80  5212.5 2324.99  5226.9 2328.12  5230.4 2330.03  5232.6 2330.03
#Mann=3,-1,0
  4754.0    0.16       0  5022.5    0.07       0  5026.5    0.16       0
Bank Sta=5022.5,5026.5
Exp/Cntr=0.3,0.1

Type RM Length L Ch R = 1,19371,140,140,140
BEGIN DESCRIPTION:
Pleasant Run 19370.744
END DESCRIPTION:
XS GIS Cut Line= 3
      1515305.00      6760488.00      1515357.01      6760191.43
      1515382.75      6760004.79
#Sta/Elev= 30
  4698.9 2314.03  4719.2 2312.11  4726.1 2309.72  4731.1 2309.60  4739.5 2307.45
  4759.8 2305.37  4800.4 2303.77  4871.5 2297.72  4891.8 2297.27  4932.4 2293.84
  4942.6 2293.44  4958.6 2294.65  4983.2 2293.90  4993.3 2292.73  4997.2 2290.29
  4997.5 2289.79  5001.0 2289.79  5001.2 2290.29  5013.6 2290.66  5020.2 2295.21
  5025.3 2294.78  5033.7 2301.20  5053.9 2304.69  5084.2 2311.36  5104.4 2314.45
  5144.8 2318.65  5164.1 2321.92  5169.1 2321.90  5184.2 2324.75  5188.4 2324.75
#Mann=3,-1,0
  4698.9    0.16       0  4997.2    0.07       0  5001.2    0.16       0
Bank Sta=4997.2,5001.2
Exp/Cntr=0.3,0.1

Type RM Length L Ch R = 1,19231,106,106,106
BEGIN DESCRIPTION:
Pleasant Run 19231.11
END DESCRIPTION:
XS GIS Cut Line= 3
      1515368.41      6760472.29      1515442.64      6760275.65
      1515506.46      6760054.25
#Sta/Elev= 30
  4788.8 2308.67  4820.9 2306.44  4868.2 2304.98  4875.9 2303.67  4881.2 2303.88
  4906.1 2299.65  4953.7 2295.07  4983.8 2286.58  4984.0 2286.08  4987.5 2286.08
  4987.8 2286.58  4991.3 2288.59  5006.9 2291.05  5057.7 2295.38  5062.9 2294.82
  5069.4 2296.46  5079.8 2297.06  5090.2 2298.69  5096.6 2300.66  5101.8 2300.82
  5111.0 2302.79  5130.3 2305.62  5135.5 2305.63  5152.6 2308.43  5169.1 2312.35
  5174.3 2312.16  5202.8 2315.92  5208.0 2315.70  5215.1 2317.42  5229.4 2318.75
#Mann=3,-1,0
  4788.8    0.16       0  4983.8    0.07       0  4987.8    0.16       0
Bank Sta=4983.8,4987.8
Exp/Cntr=0.3,0.1

Type RM Length L Ch R = 1,19125,77,77,77
BEGIN DESCRIPTION:
Pleasant Run 19125.28
END DESCRIPTION:
XS GIS Cut Line= 3
      1515415.29      6760507.43      1515527.28      6760332.94
      1515622.31      6760054.34
#Sta/Elev= 30
  4797.5 2310.20  4810.4 2309.61  4825.6 2307.65  4891.9 2303.30  4904.2 2300.73
  4940.6 2295.19  4949.8 2294.97  4963.2 2293.33  4971.0 2293.80  4976.9 2293.03
  4992.1 2289.80  4996.8 2286.87  4997.1 2286.37  5000.6 2286.37  5000.8 2286.87
  5014.3 2286.91  5031.2 2288.29  5045.6 2287.55  5071.7 2292.00  5134.4 2296.48
  5139.6 2297.83  5179.1 2303.24  5197.0 2303.60  5202.3 2305.04  5228.4 2306.35
  5233.7 2307.89  5242.5 2308.11  5265.0 2312.65  5274.2 2313.45  5299.2 2313.92
#Mann=3,-1,0
  4797.5    0.16       0  4996.8    0.07       0  5000.8    0.16       0
Bank Sta=4996.8,5000.8
Exp/Cntr=0.3,0.1

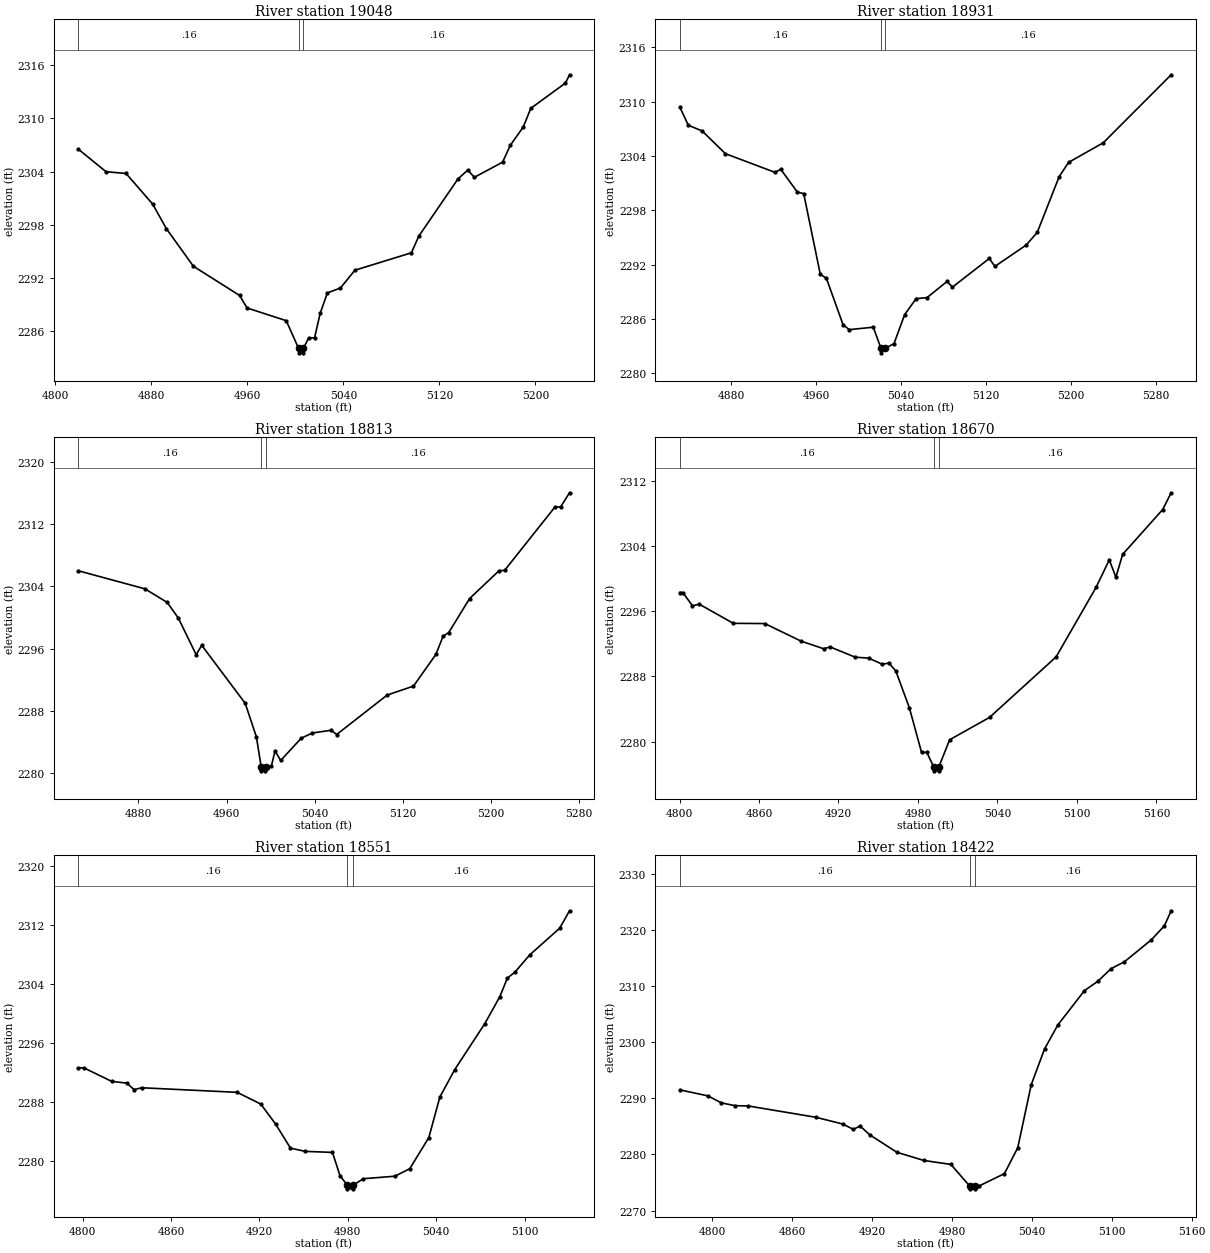
Type RM Length L Ch R = 1,19048,117,117,117
BEGIN DESCRIPTION:
Pleasant Run 19048.07
END DESCRIPTION:
XS GIS Cut Line= 3
      1515519.48      6760503.49      1515606.70      6760331.64
      1515692.53      6760132.68
#Sta/Elev= 30
  4819.0 2306.52  4842.1 2303.98  4858.8 2303.78  4881.0 2300.33  4892.4 2297.57
  4914.9 2293.34  4953.4 2290.05  4959.7 2288.64  4992.3 2287.21  5002.6 2284.09
  5002.8 2283.59  5006.3 2283.59  5006.6 2284.09  5011.0 2285.28  5015.9 2285.28
  5020.6 2288.04  5026.6 2290.34  5037.5 2290.89  5049.5 2292.89  5096.6 2294.85
  5102.8 2296.73  5135.5 2303.18  5143.6 2304.16  5149.1 2303.35  5172.6 2305.05
  5179.0 2306.94  5189.9 2309.03  5196.1 2311.11  5225.0 2313.96  5228.4 2314.89
#Mann=3,-1,0
  4819.0    0.16       0  5002.6    0.07       0  5006.6    0.16       0
Bank Sta=5002.6,5006.6
Exp/Cntr=0.3,0.1

Type RM Length L Ch R = 1,18931,118,118,118
BEGIN DESCRIPTION:
Pleasant Run 18930.91
END DESCRIPTION:
XS GIS Cut Line= 3
      1515601.47      6760564.75      1515687.43      6760420.18
      1515764.27      6760136.29
#Sta/Elev= 30
  4832.0 2309.39  4839.9 2307.41  4853.0 2306.77  4874.8 2304.27  4921.2 2302.22
  4927.0 2302.53  4942.6 2300.02  4948.5 2299.86  4964.1 2290.96  4969.9 2290.50
  4985.5 2285.40  4991.3 2284.84  5014.0 2285.11  5021.2 2282.78  5021.4 2282.28
  5025.2 2282.78  5033.5 2283.30  5043.5 2286.50  5054.3 2288.26  5064.6 2288.38
  5083.4 2290.16  5088.5 2289.54  5123.2 2292.70  5128.4 2291.82  5157.9 2294.18
  5168.3 2295.58  5188.9 2301.73  5197.8 2303.31  5230.4 2305.47  5294.3 2312.98
#Mann=3,-1,0
  4832.0    0.16       0  5021.2    0.07       0  5025.2    0.16       0
Bank Sta=5021.2,5025.2
Exp/Cntr=0.3,0.1

Type RM Length L Ch R = 1,18813,143,143,143
BEGIN DESCRIPTION:
Pleasant Run 18812.97
END DESCRIPTION:
XS GIS Cut Line= 3
      1515817.64      6760577.71      1515789.00      6760404.55
      1515842.37      6760138.97
#Sta/Elev= 30
  4825.3 2306.02  4885.8 2303.70  4906.1 2301.95  4916.2 2299.94  4932.4 2295.23
  4937.5 2296.43  4977.0 2288.97  4987.2 2284.63  4991.5 2280.79  4991.7 2280.29
  4995.2 2280.29  4995.5 2280.79  5000.8 2280.93  5004.1 2282.86  5009.2 2281.62
  5027.9 2284.49  5038.1 2285.16  5055.0 2285.51  5060.1 2284.96  5105.9 2290.03
  5129.9 2291.19  5150.3 2295.27  5156.8 2297.61  5161.9 2298.07  5180.9 2302.45
  5207.6 2306.02  5212.7 2306.07  5258.5 2314.23  5263.6 2314.23  5271.7 2316.05
#Mann=3,-1,0
  4825.3    0.16       0  4991.5    0.07       0  4995.5    0.16       0
Bank Sta=4991.5,4995.5
Exp/Cntr=0.3,0.1

Type RM Length L Ch R = 1,18670,119,119,119
BEGIN DESCRIPTION:
Pleasant Run 18670.15
END DESCRIPTION:
XS GIS Cut Line= 3
      1515953.06      6760537.36      1515914.00      6760355.07
      1515895.91      6760171.59
#Sta/Elev= 30
  4800.3 2298.28  4802.5 2298.28  4809.8 2296.65  4814.9 2296.85  4840.6 2294.50
  4864.4 2294.47  4891.7 2292.32  4908.7 2291.39  4913.8 2291.60  4932.6 2290.35
  4942.8 2290.23  4953.0 2289.49  4958.1 2289.62  4963.3 2288.65  4973.5 2284.14
  4982.7 2278.67  4986.7 2278.67  4991.8 2276.91  4992.1 2276.41  4995.6 2276.41
  4995.8 2276.91  5003.9 2280.22  5034.0 2282.96  5084.3 2290.39  5114.4 2298.90
  5124.4 2302.28  5129.4 2300.16  5134.5 2302.96  5164.7 2308.45  5171.1 2310.51
#Mann=3,-1,0
  4800.3    0.16       0  4991.8    0.07       0  4995.8    0.16       0
Bank Sta=4991.8,4995.8
Exp/Cntr=0.3,0.1

Type RM Length L Ch R = 1,18551,129,129,129
BEGIN DESCRIPTION:
Pleasant Run 18551.3
END DESCRIPTION:
XS GIS Cut Line= 3
      1516045.51      6760490.50      1516016.86      6760295.18
      1515992.42      6760161.40
#Sta/Elev= 30
  4797.1 2292.64  4800.9 2292.64  4819.8 2290.81  4829.9 2290.58  4835.0 2289.70
  4840.1 2289.95  4904.9 2289.33  4920.9 2287.75  4931.0 2285.04  4941.1 2281.78
  4951.2 2281.34  4969.6 2281.20  4974.7 2278.06  4979.6 2276.77  4979.8 2276.27
  4983.3 2276.27  4983.6 2276.77  4990.6 2277.64  5012.0 2277.98  5022.1 2279.00
  5035.0 2283.21  5042.5 2288.70  5052.6 2292.41  5073.0 2298.63  5083.1 2302.24
  5088.3 2304.78  5093.4 2305.59  5103.5 2307.93  5123.8 2311.54  5130.5 2313.90
#Mann=3,-1,0
  4797.1    0.16       0  4979.6    0.07       0  4983.6    0.16       0
Bank Sta=4979.6,4983.6
Exp/Cntr=0.3,0.1

Type RM Length L Ch R = 1,18422,111,111,111
BEGIN DESCRIPTION:
Pleasant Run 18422.47
END DESCRIPTION:
XS GIS Cut Line= 3
      1516108.01      6760508.69      1516144.47      6760291.27
      1516149.67      6760142.92
#Sta/Elev= 30
  4775.7 2291.49  4796.7 2290.42  4806.8 2289.18  4817.0 2288.68  4827.1 2288.62
  4877.8 2286.61  4898.1 2285.40  4905.9 2284.46  4911.0 2285.05  4918.4 2283.47
  4938.6 2280.38  4958.9 2278.92  4979.2 2278.22  4993.3 2274.37  4993.5 2273.87
  4997.0 2273.87  4997.3 2274.37  5000.3 2274.37  5019.4 2276.58  5029.4 2281.18
  5039.5 2292.38  5049.5 2298.76  5059.5 2303.04  5079.5 2309.16  5089.5 2310.81
  5099.5 2313.07  5109.5 2314.29  5129.5 2318.15  5139.5 2320.68  5144.6 2323.37
#Mann=3,-1,0
  4775.7    0.16       0  4993.3    0.07       0  4997.3    0.16       0
Bank Sta=4993.3,4997.3
Exp/Cntr=0.3,0.1

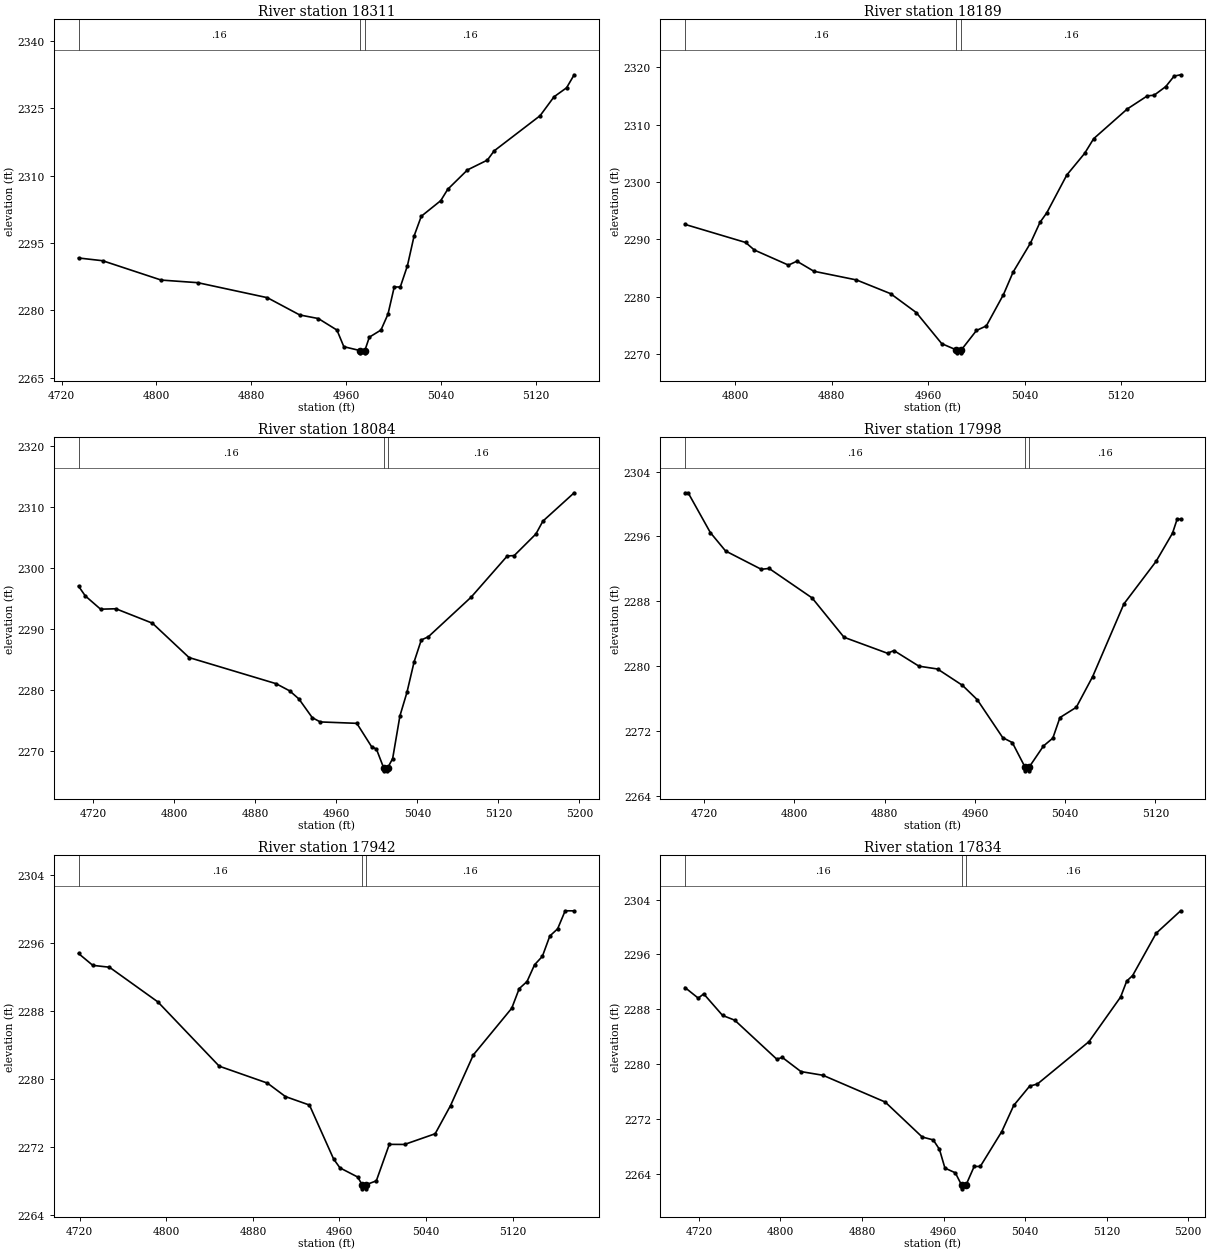
Type RM Length L Ch R = 1,18311,122,122,122
BEGIN DESCRIPTION:
Pleasant Run 18310.66
END DESCRIPTION:
XS GIS Cut Line= 3
      1516118.43      6760528.23      1516255.14      6760293.88
      1516319.66      6760162.26
#Sta/Elev= 30
  4734.3 2291.67  4754.6 2291.06  4804.0 2286.75  4834.8 2286.17  4893.5 2282.83
  4920.8 2278.98  4936.5 2278.18  4952.2 2275.61  4958.0 2271.91  4971.7 2271.04
  4972.0 2270.54  4975.5 2270.54  4975.7 2271.04  4979.5 2274.03  4989.3 2275.62
  4995.2 2279.14  5000.5 2285.21  5005.6 2285.21  5011.6 2289.93  5017.2 2296.54
  5023.3 2300.96  5039.7 2304.44  5045.6 2306.97  5062.2 2311.28  5079.0 2313.47
  5084.7 2315.52  5123.5 2323.37  5135.2 2327.57  5145.8 2329.58  5152.2 2332.48
#Mann=3,-1,0
  4734.3    0.16       0  4971.7    0.07       0  4975.7    0.16       0
Bank Sta=4971.7,4975.7
Exp/Cntr=0.3,0.1

Type RM Length L Ch R = 1,18189,105,105,105
BEGIN DESCRIPTION:
Pleasant Run 18188.88
END DESCRIPTION:
XS GIS Cut Line= 3
      1516143.14      6760567.34      1516312.43      6760403.25
      1516391.84      6760247.04
#Sta/Elev= 30
  4758.3 2292.63  4808.6 2289.48  4815.8 2288.17  4844.1 2285.54  4851.1 2286.22
  4865.2 2284.47  4900.5 2282.96  4928.8 2280.57  4950.1 2277.28  4971.2 2271.87
  4983.4 2270.77  4983.6 2270.27  4987.1 2270.27  4987.4 2270.77  5000.0 2274.16
  5008.2 2274.96  5022.4 2280.42  5030.4 2284.33  5044.8 2289.38  5052.7 2292.99
  5058.3 2294.64  5074.9 2301.22  5089.7 2304.99  5097.2 2307.55  5125.0 2312.71
  5141.7 2315.00  5147.3 2315.11  5157.0 2316.62  5163.9 2318.44  5169.3 2318.67
#Mann=3,-1,0
  4758.3    0.16       0  4983.4    0.07       0  4987.4    0.16       0
Bank Sta=4983.4,4987.4
Exp/Cntr=0.3,0.1

Type RM Length L Ch R = 1,18084,86,86,86
BEGIN DESCRIPTION:
Pleasant Run 18083.89
END DESCRIPTION:
XS GIS Cut Line= 3
      1516141.90      6760634.99      1516387.95      6760473.56
      1516529.92      6760339.42
#Sta/Elev= 30
  4705.2 2297.03  4711.9 2295.43  4727.0 2293.26  4742.1 2293.33  4778.2 2290.97
  4814.4 2285.35  4900.3 2281.08  4913.8 2279.90  4922.9 2278.58  4936.1 2275.52
  4944.0 2274.82  4980.1 2274.59  4994.7 2270.77  4999.5 2270.37  5006.6 2267.32
  5006.8 2266.82  5010.3 2266.82  5010.6 2267.32  5015.5 2268.82  5022.7 2275.82
  5029.6 2279.64  5036.7 2284.65  5043.8 2288.23  5050.7 2288.74  5093.1 2295.24
  5128.7 2301.96  5135.6 2302.03  5157.0 2305.56  5163.9 2307.66  5194.8 2312.30
#Mann=3,-1,0
  4705.2    0.16       0  5006.6    0.07       0  5010.6    0.16       0
Bank Sta=5006.6,5010.6
Exp/Cntr=0.3,0.1

Type RM Length L Ch R = 1,17998,56,56,56
BEGIN DESCRIPTION:
Pleasant Run 17997.937
END DESCRIPTION:
XS GIS Cut Line= 3
      1516154.99      6760688.01      1516418.62      6760551.24
      1516504.99      6760438.02
#Sta/Elev= 30
  4703.0 2301.40  4705.8 2301.40  4725.5 2296.48  4739.0 2294.21  4770.6 2291.95
  4777.6 2292.05  4815.7 2288.41  4844.0 2283.55  4882.6 2281.57  4888.2 2281.91
  4910.4 2279.98  4926.9 2279.63  4949.0 2277.61  4962.1 2275.84  4984.7 2271.15
  4993.2 2270.54  5004.3 2267.55  5004.6 2267.05  5008.1 2267.05  5008.3 2267.55
  5020.8 2270.12  5029.1 2271.09  5035.4 2273.63  5049.9 2274.90  5064.4 2278.69
  5092.1 2287.67  5120.6 2292.92  5135.2 2296.41  5139.3 2298.14  5142.4 2298.14
#Mann=3,-1,0
  4703.0    0.16       0  5004.3    0.07       0  5008.3    0.16       0
Bank Sta=5004.3,5008.3
Exp/Cntr=0.3,0.1

Type RM Length L Ch R = 1,17942,108,108,108
BEGIN DESCRIPTION:
Pleasant Run 17941.83
END DESCRIPTION:
XS GIS Cut Line= 3
      1516209.53      6760719.68      1516453.06      6760595.96
      1516585.85      6760467.08
#Sta/Elev= 30
  4718.8 2294.81  4732.0 2293.41  4747.4 2293.19  4792.2 2289.10  4848.9 2281.53
  4893.4 2279.54  4910.1 2277.95  4932.3 2276.95  4954.6 2270.60  4960.5 2269.55
  4976.9 2268.47  4980.9 2267.58  4981.2 2267.08  4984.7 2267.08  4984.9 2267.58
  4994.1 2268.02  5006.1 2272.32  5020.2 2272.31  5048.5 2273.57  5062.7 2276.89
  5083.8 2282.86  5119.3 2288.36  5126.2 2290.67  5133.4 2291.50  5140.4 2293.48
  5147.6 2294.47  5154.5 2296.87  5161.7 2297.71  5168.7 2299.84  5177.0 2299.83
#Mann=3,-1,0
  4718.8    0.16       0  4980.9    0.07       0  4984.9    0.16       0
Bank Sta=4980.9,4984.9
Exp/Cntr=0.3,0.1

Type RM Length L Ch R = 1,17834,92,92,92
BEGIN DESCRIPTION:
Pleasant Run 17834.34
END DESCRIPTION:
XS GIS Cut Line= 3
      1516279.87      6760758.72      1516544.20      6760649.35
      1516647.08      6760477.45
#Sta/Elev= 30
  4706.3 2291.17  4719.3 2289.62  4724.7 2290.24  4743.2 2287.09  4755.1 2286.40
  4796.4 2280.70  4801.8 2280.96  4820.1 2278.89  4841.7 2278.35  4902.8 2274.44
  4939.1 2269.33  4949.9 2268.91  4956.0 2267.54  4961.4 2264.79  4971.6 2264.10
  4977.9 2262.26  4978.2 2261.76  4981.9 2262.26  4990.1 2265.03  4996.1 2265.03
  5017.2 2270.13  5028.9 2273.94  5044.5 2276.76  5052.2 2277.08  5102.8 2283.27
  5133.8 2289.78  5139.8 2292.11  5145.6 2292.92  5168.7 2299.10  5192.7 2302.38
#Mann=3,-1,0
  4706.3    0.16       0  4977.9    0.07       0  4981.9    0.16       0
Bank Sta=4977.9,4981.9
Exp/Cntr=0.3,0.1

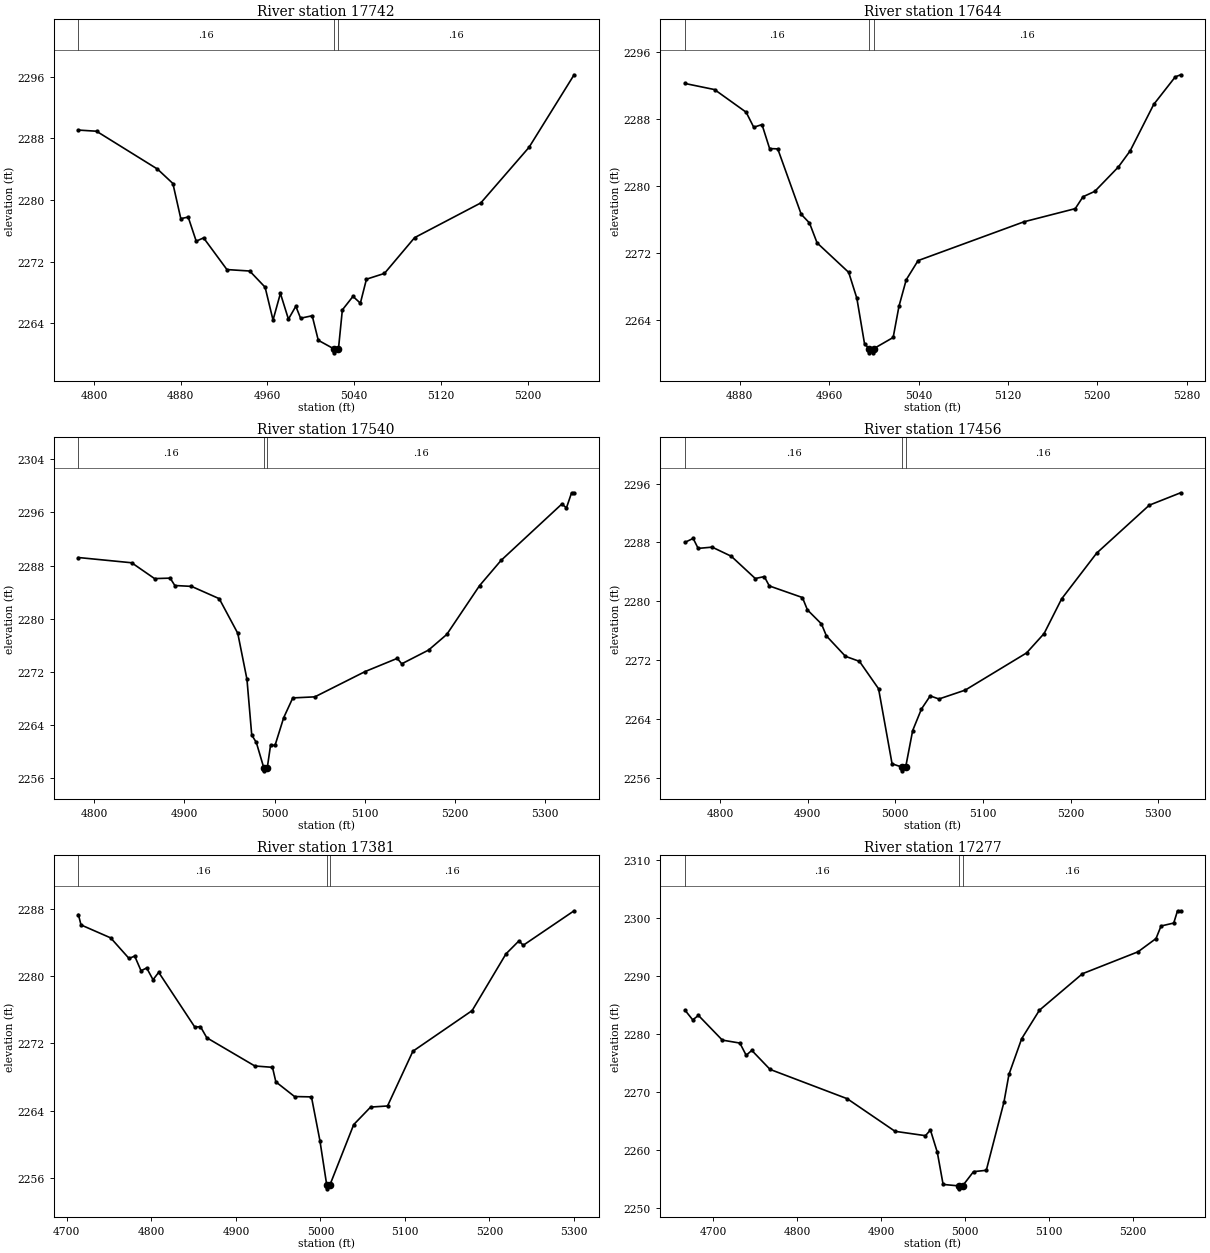
Type RM Length L Ch R = 1,17742,98,98,98
BEGIN DESCRIPTION:
Pleasant Run 17742.31
END DESCRIPTION:
XS GIS Cut Line= 3
      1516413.97      6760890.26      1516555.92      6760737.89
      1516669.20      6760516.54
#Sta/Elev= 30
  4785.7 2289.07  4802.4 2288.92  4858.6 2284.01  4872.8 2282.14  4880.1 2277.58
  4886.9 2277.79  4894.3 2274.66  4901.1 2275.09  4922.6 2270.98  4943.6 2270.79
  4957.8 2268.69  4965.1 2264.43  4971.9 2267.89  4979.3 2264.55  4986.1 2266.22
  4990.5 2264.67  5001.2 2264.99  5006.8 2261.81  5021.4 2260.68  5021.6 2260.18
  5025.4 2260.68  5029.0 2265.75  5038.8 2267.50  5045.6 2266.62  5051.2 2269.73
  5067.8 2270.48  5095.6 2275.12  5156.6 2279.62  5201.1 2286.84  5242.6 2296.24
#Mann=3,-1,0
  4785.7    0.16       0  5021.4    0.07       0  5025.4    0.16       0
Bank Sta=5021.4,5025.4
Exp/Cntr=0.3,0.1

Type RM Length L Ch R = 1,17644,104,104,104
BEGIN DESCRIPTION:
Pleasant Run 17643.7
END DESCRIPTION:
XS GIS Cut Line= 3
      1516502.52      6760922.80      1516621.03      6760812.11
      1516710.45      6760545.15
#Sta/Elev= 30
  4830.9 2292.28  4857.4 2291.55  4885.7 2288.84  4892.5 2287.04  4899.9 2287.36
  4906.7 2284.49  4914.0 2284.45  4935.0 2276.62  4942.4 2275.58  4949.2 2273.20
  4977.5 2269.67  4984.8 2266.57  4991.7 2261.10  4995.9 2260.54  4996.1 2260.04
  4999.6 2260.04  4999.9 2260.54  5017.3 2261.88  5022.5 2265.62  5029.0 2268.79
  5039.6 2271.08  5134.5 2275.73  5180.3 2277.30  5187.2 2278.72  5197.8 2279.37
  5218.9 2282.29  5229.4 2284.21  5250.5 2289.77  5269.8 2293.07  5274.6 2293.32
#Mann=3,-1,0
  4830.9    0.16       0  4995.9    0.07       0  4999.9    0.16       0
Bank Sta=4995.9,4999.9
Exp/Cntr=0.3,0.1

Type RM Length L Ch R = 1,17540,84,84,84
BEGIN DESCRIPTION:
Pleasant Run 17540.31
END DESCRIPTION:
XS GIS Cut Line= 3
      1516666.59      6761050.41      1516714.78      6760842.05
      1516751.24      6760507.39
#Sta/Elev= 30
  4782.2 2289.21  4841.4 2288.42  4866.8 2286.04  4884.1 2286.11  4889.3 2285.00
  4907.8 2284.87  4938.6 2283.02  4959.2 2277.81  4969.4 2270.89  4974.7 2262.51
  4979.8 2261.39  4988.0 2257.62  4988.2 2257.12  4992.0 2257.62  4995.6 2260.96
  5000.6 2260.96  5010.2 2265.12  5020.3 2268.09  5044.8 2268.25  5100.7 2272.06
  5136.3 2274.04  5141.3 2273.22  5171.1 2275.29  5191.3 2277.64  5227.7 2284.98
  5251.6 2288.78  5319.1 2297.26  5324.2 2296.68  5329.9 2298.95  5332.7 2298.95
#Mann=3,-1,0
  4782.2    0.16       0  4988.0    0.07       0  4992.0    0.16       0
Bank Sta=4988,4992
Exp/Cntr=0.3,0.1

Type RM Length L Ch R = 1,17456,75,75,75
BEGIN DESCRIPTION:
Pleasant Run 17456.11
END DESCRIPTION:
XS GIS Cut Line= 3
      1516683.52      6761047.79      1516799.41      6760839.45
      1516798.11      6760512.15
#Sta/Elev= 30
  4759.9 2288.01  4769.3 2288.55  4775.0 2287.19  4791.0 2287.36  4812.8 2286.12
  4840.2 2283.09  4850.5 2283.35  4856.2 2282.08  4894.0 2280.50  4899.7 2278.82
  4915.7 2276.91  4921.4 2275.27  4943.1 2272.50  4959.1 2271.81  4980.9 2268.08
  4996.3 2257.87  5007.8 2257.41  5008.0 2256.91  5011.8 2257.41  5019.8 2262.39
  5029.8 2265.32  5039.8 2267.11  5049.8 2266.69  5079.8 2267.90  5149.8 2272.96
  5169.8 2275.60  5189.8 2280.32  5229.8 2286.55  5289.8 2293.07  5325.6 2294.76
#Mann=3,-1,0
  4759.9    0.16       0  5007.8    0.07       0  5011.8    0.16       0
Bank Sta=5007.8,5011.8
Exp/Cntr=0.3,0.1

Type RM Length L Ch R = 1,17381,104,104,104
BEGIN DESCRIPTION:
Pleasant Run 17380.76
END DESCRIPTION:
XS GIS Cut Line= 3
      1516697.84      6761045.19      1516873.63      6760887.63
      1516881.44      6760537.38
#Sta/Elev= 30
  4713.7 2287.31  4716.8 2286.08  4751.9 2284.54  4773.6 2282.10  4780.3 2282.38
  4787.8 2280.64  4794.5 2280.97  4802.0 2279.57  4808.7 2280.45  4851.4 2273.95
  4858.1 2274.00  4865.6 2272.68  4922.4 2269.33  4943.3 2269.17  4947.3 2267.44
  4969.4 2265.70  4989.4 2265.66  4999.4 2260.47  5007.4 2255.24  5007.7 2254.74
  5011.4 2255.24  5039.4 2262.37  5059.4 2264.45  5079.4 2264.58  5109.4 2271.08
  5179.5 2275.91  5219.5 2282.64  5234.9 2284.19  5239.9 2283.66  5300.1 2287.76
#Mann=3,-1,0
  4713.7    0.16       0  5007.4    0.07       0  5011.4    0.16       0
Bank Sta=5007.4,5011.4
Exp/Cntr=0.3,0.1

Type RM Length L Ch R = 1,17277,71,71,71
BEGIN DESCRIPTION:
Pleasant Run 17276.81
END DESCRIPTION:
XS GIS Cut Line= 3
      1516727.78      6761033.48      1516929.62      6760852.47
      1517104.09      6760585.55
#Sta/Elev= 30
  4666.7 2284.09  4676.0 2282.40  4682.8 2283.17  4711.2 2278.92  4732.1 2278.41
  4739.6 2276.31  4746.3 2277.15  4768.0 2273.88  4859.9 2268.83  4916.8 2263.22
  4953.0 2262.47  4958.9 2263.45  4967.1 2259.61  4974.0 2254.08  4993.1 2253.82
  4993.4 2253.32  4997.1 2253.82  5010.2 2256.28  5025.4 2256.51  5046.4 2268.24
  5052.4 2273.03  5067.5 2279.16  5088.6 2284.06  5139.9 2290.35  5206.0 2294.12
  5227.4 2296.40  5233.4 2298.56  5248.5 2299.07  5253.0 2301.18  5256.7 2301.18
#Mann=3,-1,0
  4666.7    0.16       0  4993.1    0.07       0  4997.1    0.16       0
Bank Sta=4993.1,4997.1
Exp/Cntr=0.3,0.1

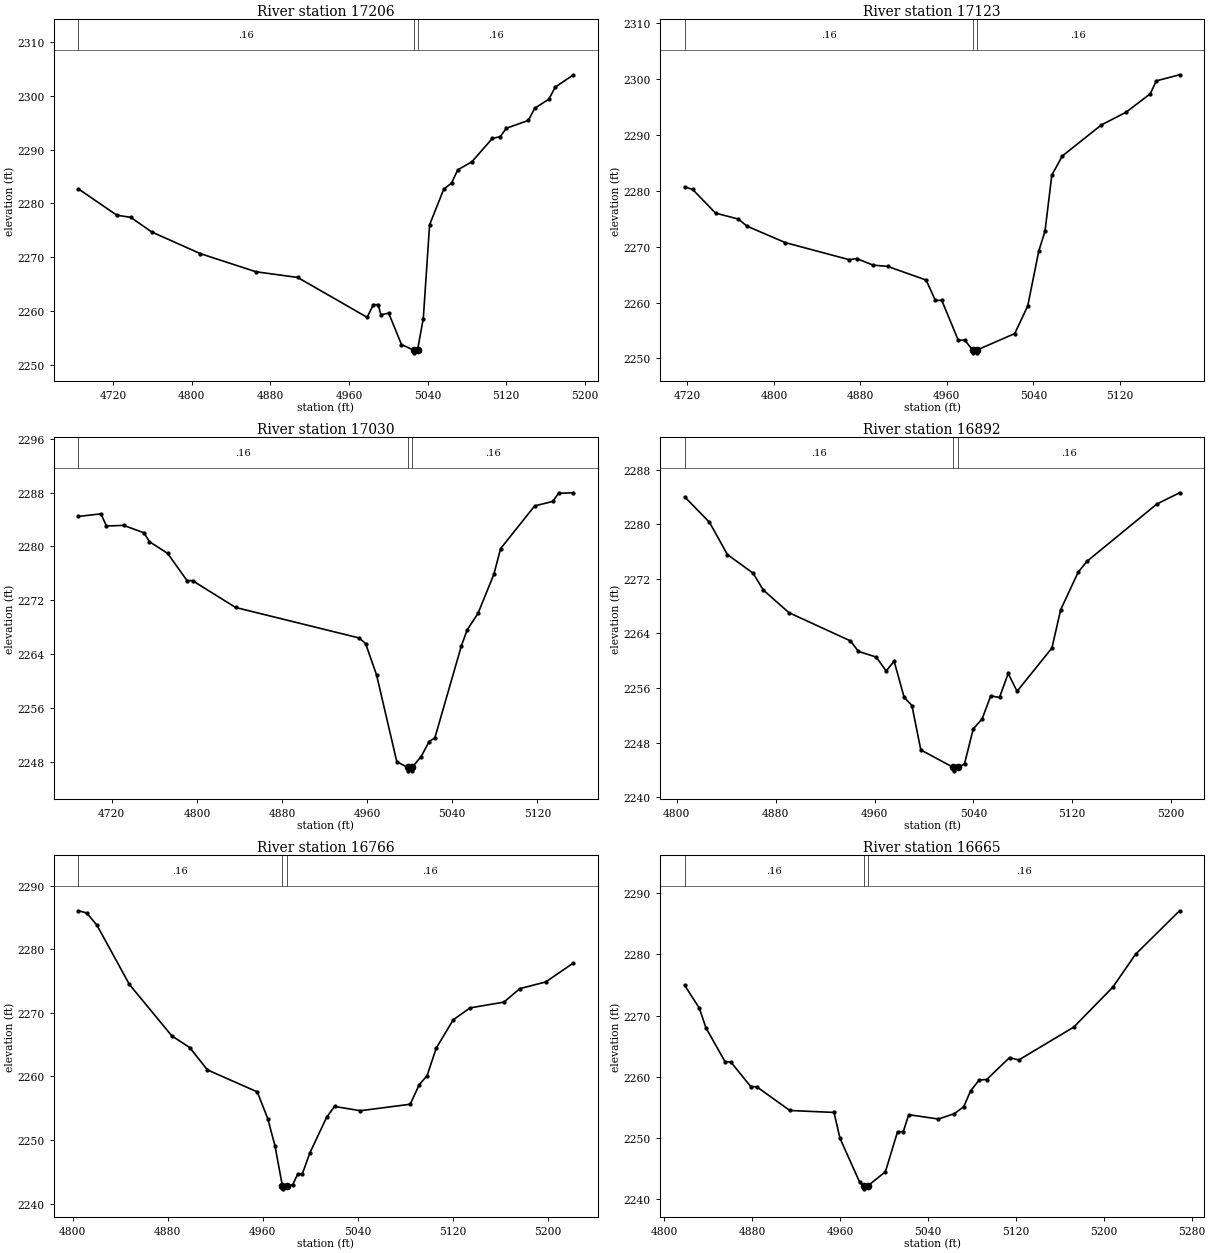
Type RM Length L Ch R = 1,17206,83,83,83
BEGIN DESCRIPTION:
Pleasant Run 17205.75
END DESCRIPTION:
XS GIS Cut Line= 3
      1516789.02      6761067.29      1517009.05      6760856.38
      1517135.23      6760702.88
#Sta/Elev= 30
  4684.8 2282.71  4723.8 2277.82  4738.0 2277.42  4759.3 2274.70  4808.7 2270.67
  4865.3 2267.29  4907.8 2266.23  4978.5 2258.80  4984.8 2261.17  4989.6 2261.17
  4992.5 2259.29  5000.4 2259.57  5013.4 2253.74  5025.7 2252.69  5025.9 2252.19
  5029.7 2252.69  5035.6 2258.58  5042.0 2276.04  5056.4 2282.66  5064.3 2283.80
  5070.7 2286.27  5085.1 2287.78  5105.9 2292.13  5113.8 2292.44  5120.2 2294.02
  5142.5 2295.47  5148.9 2297.73  5163.3 2299.43  5169.8 2301.66  5188.3 2303.97
#Mann=3,-1,0
  4684.8    0.16       0  5025.7    0.07       0  5029.7    0.16       0
Bank Sta=5025.7,5029.7
Exp/Cntr=0.3,0.1

Type RM Length L Ch R = 1,17123,93,93,93
BEGIN DESCRIPTION:
Pleasant Run 17122.76
END DESCRIPTION:
XS GIS Cut Line= 3
      1516816.32      6761068.63      1517054.62      6760917.57
      1517208.32      6760832.33
#Sta/Elev= 30
  4717.4 2280.72  4724.8 2280.27  4746.0 2276.03  4767.2 2274.96  4775.0 2273.70
  4810.6 2270.74  4869.8 2267.68  4876.5 2267.89  4891.8 2266.71  4905.3 2266.48
  4940.8 2264.04  4949.4 2260.39  4955.3 2260.40  4970.6 2253.23  4976.5 2253.30
  4983.8 2251.50  4984.1 2251.00  4987.6 2251.00  4987.8 2251.50  5022.8 2254.45
  5034.8 2259.40  5045.1 2269.28  5050.8 2272.79  5057.1 2282.84  5066.8 2286.26
  5102.9 2291.82  5125.8 2294.10  5148.1 2297.39  5153.8 2299.72  5175.3 2300.81
#Mann=3,-1,0
  4717.4    0.16       0  4983.8    0.07       0  4987.8    0.16       0
Bank Sta=4983.8,4987.8
Exp/Cntr=0.3,0.1

Type RM Length L Ch R = 1,17030,138,138,138
BEGIN DESCRIPTION:
Pleasant Run 17029.97
END DESCRIPTION:
XS GIS Cut Line= 3
      1516753.84      6761089.45      1517048.11      6761012.63
      1517199.14      6760956.64
#Sta/Elev= 30
  4688.7 2284.47  4709.8 2284.86  4715.0 2283.05  4731.2 2283.14  4750.3 2282.03
  4755.4 2280.72  4772.6 2278.96  4790.7 2274.93  4795.9 2274.92  4836.4 2270.93
  4952.6 2266.39  4958.6 2265.55  4968.9 2260.89  4987.9 2247.99  4998.2 2247.13
  4998.4 2246.63  5001.9 2246.63  5002.2 2247.13  5010.8 2248.76  5018.3 2250.98
  5023.7 2251.54  5048.7 2265.27  5054.1 2267.61  5064.2 2270.04  5079.1 2275.85
  5085.5 2279.69  5117.5 2286.04  5134.5 2286.70  5139.9 2287.91  5153.9 2287.99
#Mann=3,-1,0
  4688.7    0.16       0  4998.2    0.07       0  5002.2    0.16       0
Bank Sta=4998.2,5002.2
Exp/Cntr=0.3,0.1

Type RM Length L Ch R = 1,16892,126,126,126
BEGIN DESCRIPTION:
Pleasant Run 16891.65
END DESCRIPTION:
XS GIS Cut Line= 3
      1516913.96      6761265.26      1517059.83      6761151.95
      1517211.12      6760998.07
#Sta/Elev= 30
  4806.3 2284.04  4826.4 2280.30  4840.9 2275.57  4861.7 2272.84  4869.9 2270.38
  4890.7 2267.05  4940.5 2262.91  4946.9 2261.38  4961.3 2260.54  4969.4 2258.50
  4975.8 2259.94  4983.9 2254.65  4990.2 2253.44  4997.4 2246.93  5023.7 2244.36
  5023.9 2243.86  5027.7 2244.36  5032.8 2244.90  5039.8 2250.00  5047.0 2251.47
  5054.0 2254.85  5061.1 2254.62  5068.1 2258.14  5075.3 2255.52  5103.5 2261.87
  5110.6 2267.49  5124.7 2272.97  5131.8 2274.57  5188.4 2282.98  5206.8 2284.63
#Mann=3,-1,0
  4806.3    0.16       0  5023.7    0.07       0  5027.7    0.16       0
Bank Sta=5023.7,5027.7
Exp/Cntr=0.3,0.1

Type RM Length L Ch R = 1,16766,101,101,101
BEGIN DESCRIPTION:
Pleasant Run 16765.81
END DESCRIPTION:
XS GIS Cut Line= 3
      1516962.19      6761365.48      1517117.12      6761258.72
      1517288.99      6761108.99
#Sta/Elev= 30
  4805.0 2286.09  4811.9 2285.75  4820.6 2283.80  4847.8 2274.49  4883.6 2266.37
  4898.5 2264.56  4913.4 2261.04  4955.3 2257.58  4964.1 2253.38  4970.2 2249.09
  4976.4 2242.81  4976.7 2242.31  4980.4 2242.81  4985.1 2242.96  4989.4 2244.66
  4993.2 2244.66  4999.4 2247.91  5013.7 2253.60  5020.3 2255.28  5042.1 2254.61
  5083.9 2255.63  5091.5 2258.71  5098.1 2260.14  5105.8 2264.47  5120.0 2268.91
  5134.2 2270.80  5162.7 2271.71  5176.0 2273.83  5197.8 2274.88  5221.1 2277.87
#Mann=3,-1,0
  4805.0    0.16       0  4976.4    0.07       0  4980.4    0.16       0
Bank Sta=4976.4,4980.4
Exp/Cntr=0.3,0.1

Type RM Length L Ch R = 1,16665,77,77,77
BEGIN DESCRIPTION:
Pleasant Run 16664.99
END DESCRIPTION:
XS GIS Cut Line= 3
      1517027.24      6761398.06      1517209.57      6761318.62
      1517411.32      6761168.60
#Sta/Elev= 30
  4818.7 2274.94  4832.0 2271.23  4838.1 2267.97  4855.4 2262.46  4860.9 2262.35
  4878.8 2258.37  4884.3 2258.33  4914.4 2254.45  4954.6 2254.13  4960.0 2249.91
  4978.0 2242.68  4981.5 2242.12  4981.7 2241.62  4985.5 2242.12  5001.4 2244.43
  5012.4 2250.98  5017.6 2250.98  5022.6 2253.76  5049.6 2253.05  5064.2 2253.94
  5072.6 2255.06  5078.9 2257.67  5086.7 2259.44  5093.5 2259.52  5114.3 2263.11
  5122.7 2262.72  5172.7 2268.10  5208.2 2274.63  5229.0 2280.04  5269.0 2287.15
#Mann=3,-1,0
  4818.7    0.16       0  4981.5    0.07       0  4985.5    0.16       0
Bank Sta=4981.5,4985.5
Exp/Cntr=0.3,0.1