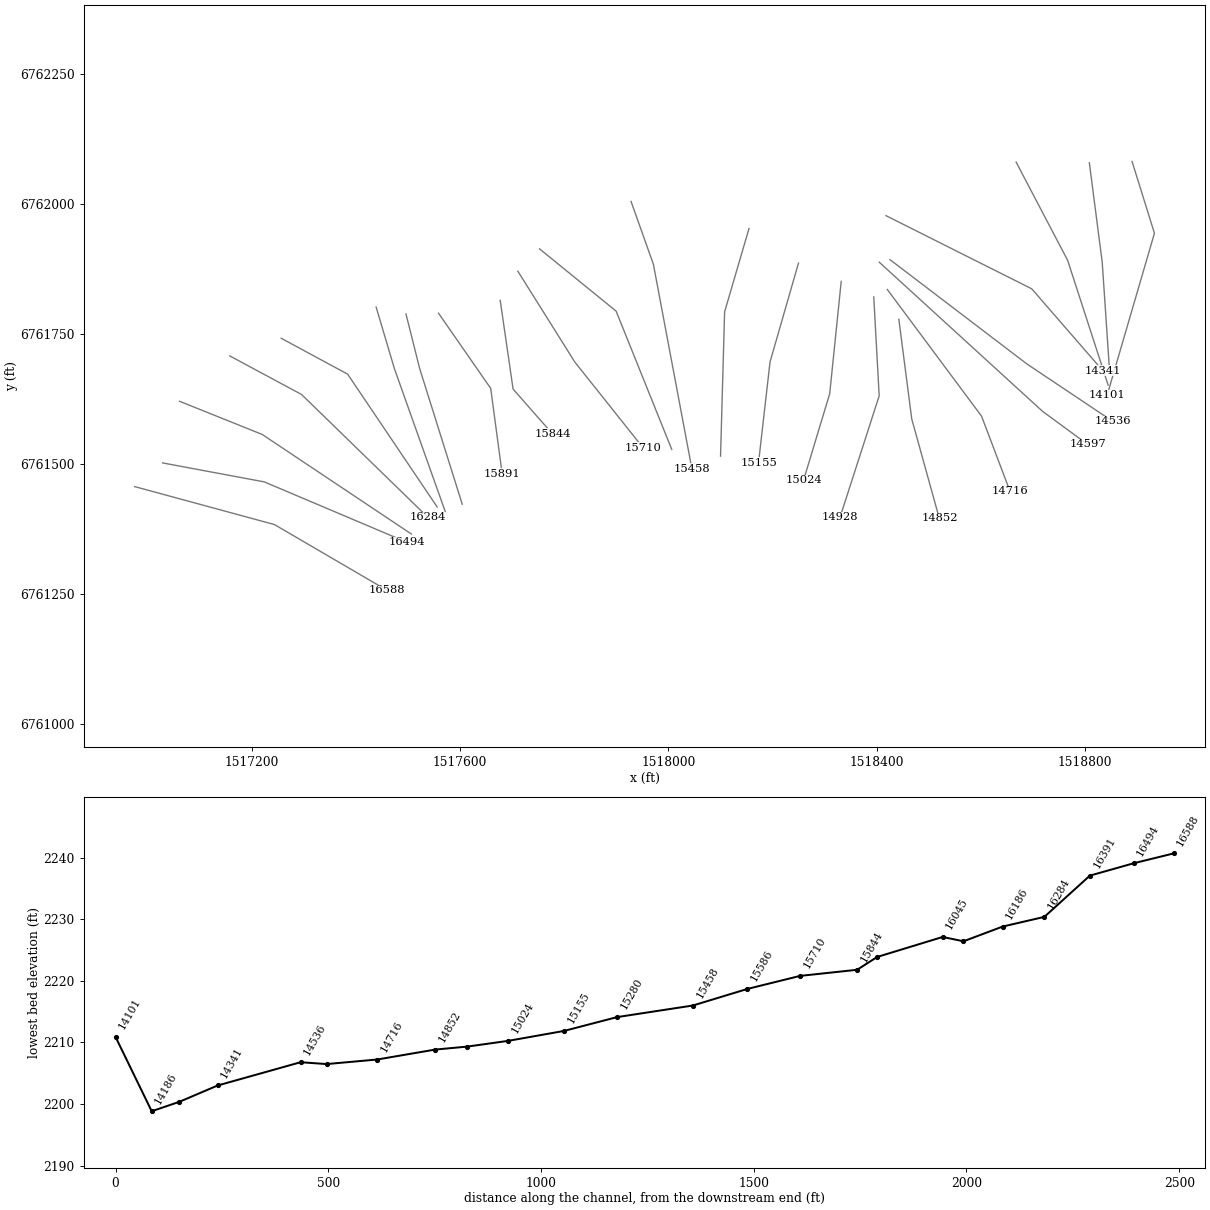
HEC-RAS study Pleasant Run.prj: Pleasant Run Base Level Engineering

--- Pleasant Run.g01 (geometry) --- (continued)

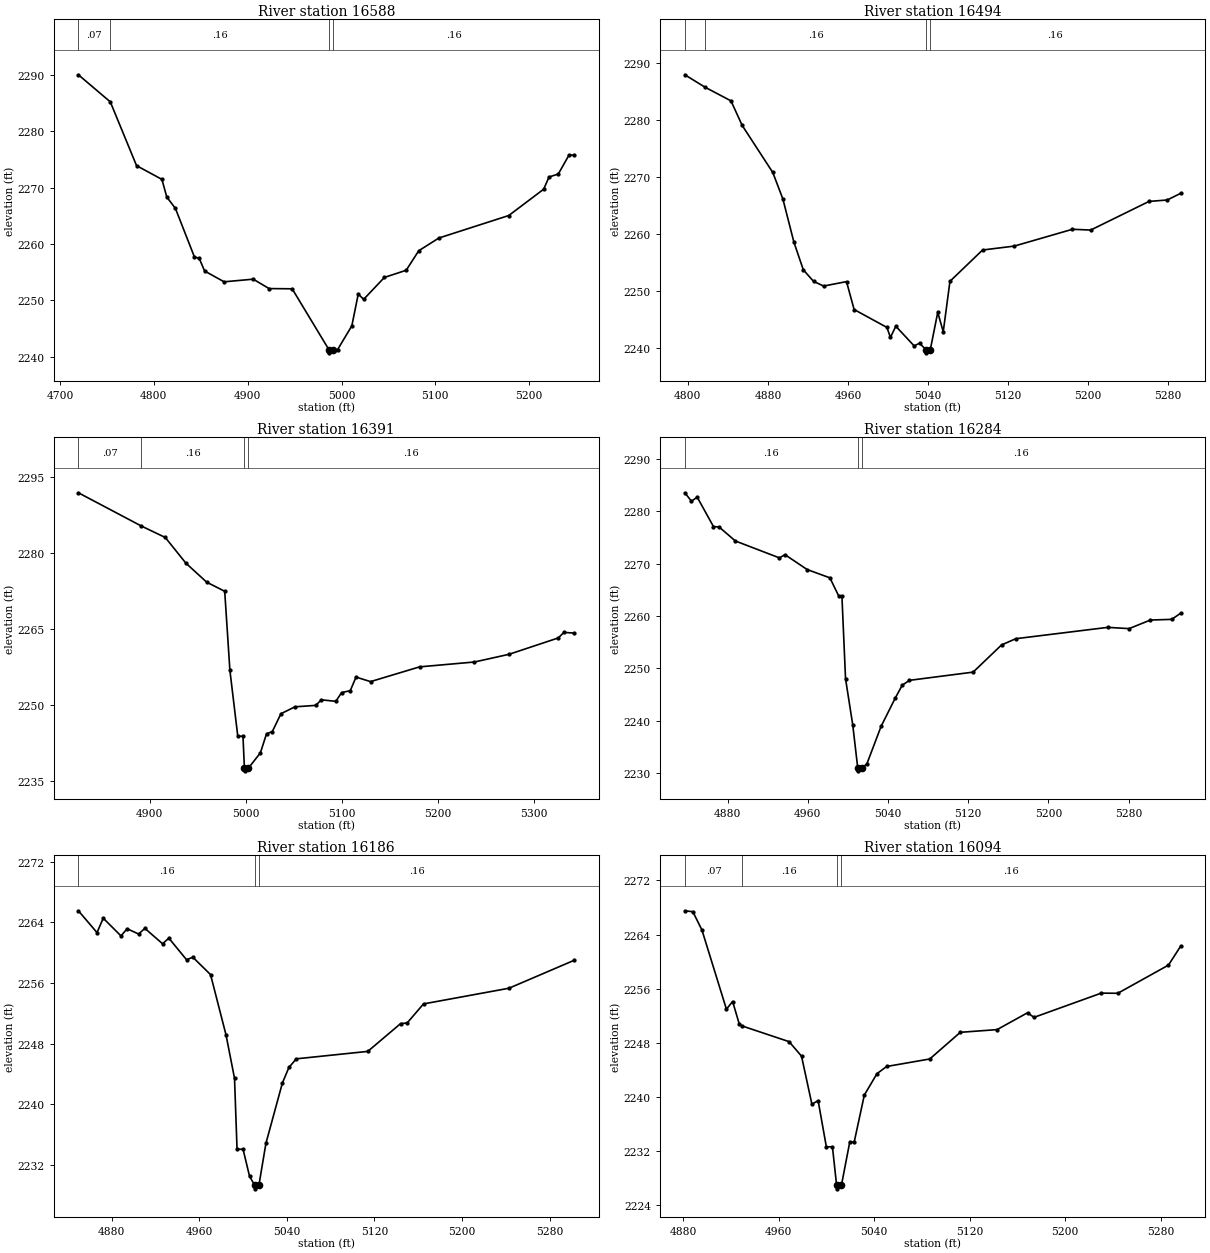
Type RM Length L Ch R = 1,16588,94,94,94
BEGIN DESCRIPTION:
Pleasant Run 16587.66
END DESCRIPTION:
XS GIS Cut Line= 3
      1516975.18      6761456.64      1517243.42      6761383.72
      1517459.55      6761257.43
#Sta/Elev= 30
  4719.6 2290.06  4753.6 2285.25  4781.6 2273.92  4808.6 2271.49  4813.8 2268.35
  4823.0 2266.33  4843.2 2257.73  4848.4 2257.45  4854.1 2255.22  4874.9 2253.30
  4905.9 2253.77  4922.8 2252.10  4947.4 2252.06  4986.8 2241.19  4987.1 2240.69
  4990.8 2241.19  4995.8 2241.26  5011.0 2245.49  5017.8 2251.12  5023.6 2250.19
  5045.7 2254.08  5068.9 2255.35  5082.3 2258.82  5103.8 2261.08  5178.2 2265.07
  5215.4 2269.74  5221.1 2271.91  5231.0 2272.44  5242.4 2275.80  5247.9 2275.80
#Mann=4,-1,0
  4719.6    0.07       0  4753.6    0.16       0  4986.8    0.07       0
  4990.8    0.16       0
Bank Sta=4986.8,4990.8
Exp/Cntr=0.3,0.1

Type RM Length L Ch R = 1,16494,103,103,103
BEGIN DESCRIPTION:
Pleasant Run 16494.48
END DESCRIPTION:
XS GIS Cut Line= 3
      1517028.63      6761502.20      1517223.89      6761465.75
      1517497.31      6761349.87
#Sta/Elev= 30
  4797.0 2288.01  4817.0 2285.84  4843.1 2283.42  4854.3 2279.10  4884.9 2270.82
  4895.0 2266.15  4906.0 2258.57  4915.4 2253.70  4925.6 2251.67  4935.7 2250.84
  4958.6 2251.62  4966.2 2246.71  4999.0 2243.56  5002.5 2241.81  5007.9 2243.77
  5026.2 2240.31  5031.6 2240.78  5038.3 2239.59  5038.5 2239.09  5042.3 2239.59
  5049.8 2246.22  5055.3 2242.80  5062.0 2251.67  5094.6 2257.18  5126.3 2257.87
  5184.5 2260.83  5202.7 2260.69  5261.0 2265.73  5279.2 2265.98  5292.6 2267.15
#Mann=4,-1,0
  4797.0    0.07       0  4817.0    0.16       0  5038.3    0.07       0
  5042.3    0.16       0
Bank Sta=5038.3,5042.3
Exp/Cntr=0.3,0.1

Type RM Length L Ch R = 1,16391,107,107,107
BEGIN DESCRIPTION:
Pleasant Run 16391.2
END DESCRIPTION:
XS GIS Cut Line= 3
      1517061.13      6761620.70      1517219.99      6761556.90
      1517506.43      6761365.50
#Sta/Elev= 30
  4826.0 2291.93  4891.3 2285.39  4916.4 2283.11  4937.9 2278.03  4959.5 2274.29
  4978.2 2272.50  4983.6 2256.89  4991.8 2243.91  4997.2 2243.91  4998.7 2237.58
  4999.0 2237.08  5002.7 2237.58  5015.3 2240.62  5021.7 2244.39  5027.7 2244.82
  5036.7 2248.35  5051.3 2249.71  5072.8 2249.99  5078.8 2251.09  5093.8 2250.79
  5099.8 2252.52  5108.8 2252.89  5114.8 2255.57  5129.9 2254.68  5180.9 2257.59
  5238.0 2258.55  5274.0 2260.07  5325.1 2263.29  5331.1 2264.39  5341.7 2264.25
#Mann=4,-1,0
  4826.0    0.07       0  4891.3    0.16       0  4998.7    0.07       0
  5002.7    0.16       0
Bank Sta=4998.7,5002.7
Exp/Cntr=0.3,0.1

Type RM Length L Ch R = 1,16284,98,98,98
BEGIN DESCRIPTION:
Pleasant Run 16283.67
END DESCRIPTION:
XS GIS Cut Line= 3
      1517157.52      6761707.92      1517295.51      6761633.72
      1517537.69      6761398.05
#Sta/Elev= 30
  4837.4 2283.56  4844.0 2281.94  4849.7 2282.73  4865.9 2277.11  4871.6 2277.01
  4887.8 2274.34  4931.7 2271.11  4937.3 2271.72  4959.4 2268.88  4982.1 2267.29
  4991.0 2263.78  4994.1 2263.78  4997.7 2248.00  5004.9 2239.15  5009.9 2230.88
  5010.1 2230.38  5013.9 2230.88  5019.0 2231.72  5033.2 2238.90  5047.3 2244.30
  5054.3 2246.77  5061.5 2247.69  5125.0 2249.26  5153.3 2254.45  5167.5 2255.65
  5259.3 2257.82  5280.6 2257.58  5301.8 2259.22  5323.1 2259.35  5332.0 2260.52
#Mann=3,-1,0
  4837.4    0.16       0  5009.9    0.07       0  5013.9    0.16       0
Bank Sta=5009.9,5013.9
Exp/Cntr=0.3,0.1

Type RM Length L Ch R = 1,16186,92,92,92
BEGIN DESCRIPTION:
Pleasant Run 16185.55
END DESCRIPTION:
XS GIS Cut Line= 3
      1517256.42      6761741.81      1517384.05      6761672.78
      1517555.93      6761417.56
#Sta/Elev= 30
  4849.6 2265.53  4866.6 2262.65  4872.3 2264.55  4888.5 2262.21  4894.1 2263.16
  4904.6 2262.46  4910.3 2263.21  4926.5 2261.17  4932.2 2261.92  4948.4 2259.06
  4954.1 2259.40  4970.3 2257.10  4984.4 2249.16  4992.2 2243.40  4994.5 2234.04
  5000.0 2234.04  5005.9 2230.48  5010.5 2229.31  5010.8 2228.81  5014.5 2229.31
  5020.9 2234.83  5035.9 2242.78  5041.9 2244.85  5048.7 2245.98  5113.9 2246.96
  5143.8 2250.62  5149.9 2250.72  5164.8 2253.23  5242.8 2255.30  5302.4 2258.99
#Mann=3,-1,0
  4849.6    0.16       0  5010.5    0.07       0  5014.5    0.16       0
Bank Sta=5010.5,5014.5
Exp/Cntr=0.3,0.1

Type RM Length L Ch R = 1,16094,49,49,49
BEGIN DESCRIPTION:
Pleasant Run 16094.18
END DESCRIPTION:
XS GIS Cut Line= 3
      1517438.74      6761801.68      1517473.89      6761683.20
      1517571.56      6761408.42
#Sta/Elev= 30
  4881.5 2267.51  4888.2 2267.37  4895.8 2264.67  4916.3 2252.97  4921.5 2254.10
  4927.1 2250.76  4929.4 2250.49  4968.8 2248.17  4979.2 2246.03  4987.9 2238.92
  4993.1 2239.46  5000.0 2232.63  5005.1 2232.63  5008.6 2226.92  5008.9 2226.42
  5012.6 2226.92  5019.6 2233.34  5023.3 2233.32  5031.8 2240.28  5042.4 2243.44
  5050.5 2244.50  5086.6 2245.61  5112.2 2249.55  5143.0 2249.95  5168.5 2252.44
  5173.9 2251.76  5230.2 2255.34  5244.1 2255.32  5286.5 2259.48  5296.7 2262.27
#Mann=4,-1,0
  4881.5    0.07       0  4929.4    0.16       0  5008.6    0.07       0
  5012.6    0.16       0
Bank Sta=5008.6,5012.6
Exp/Cntr=0.3,0.1

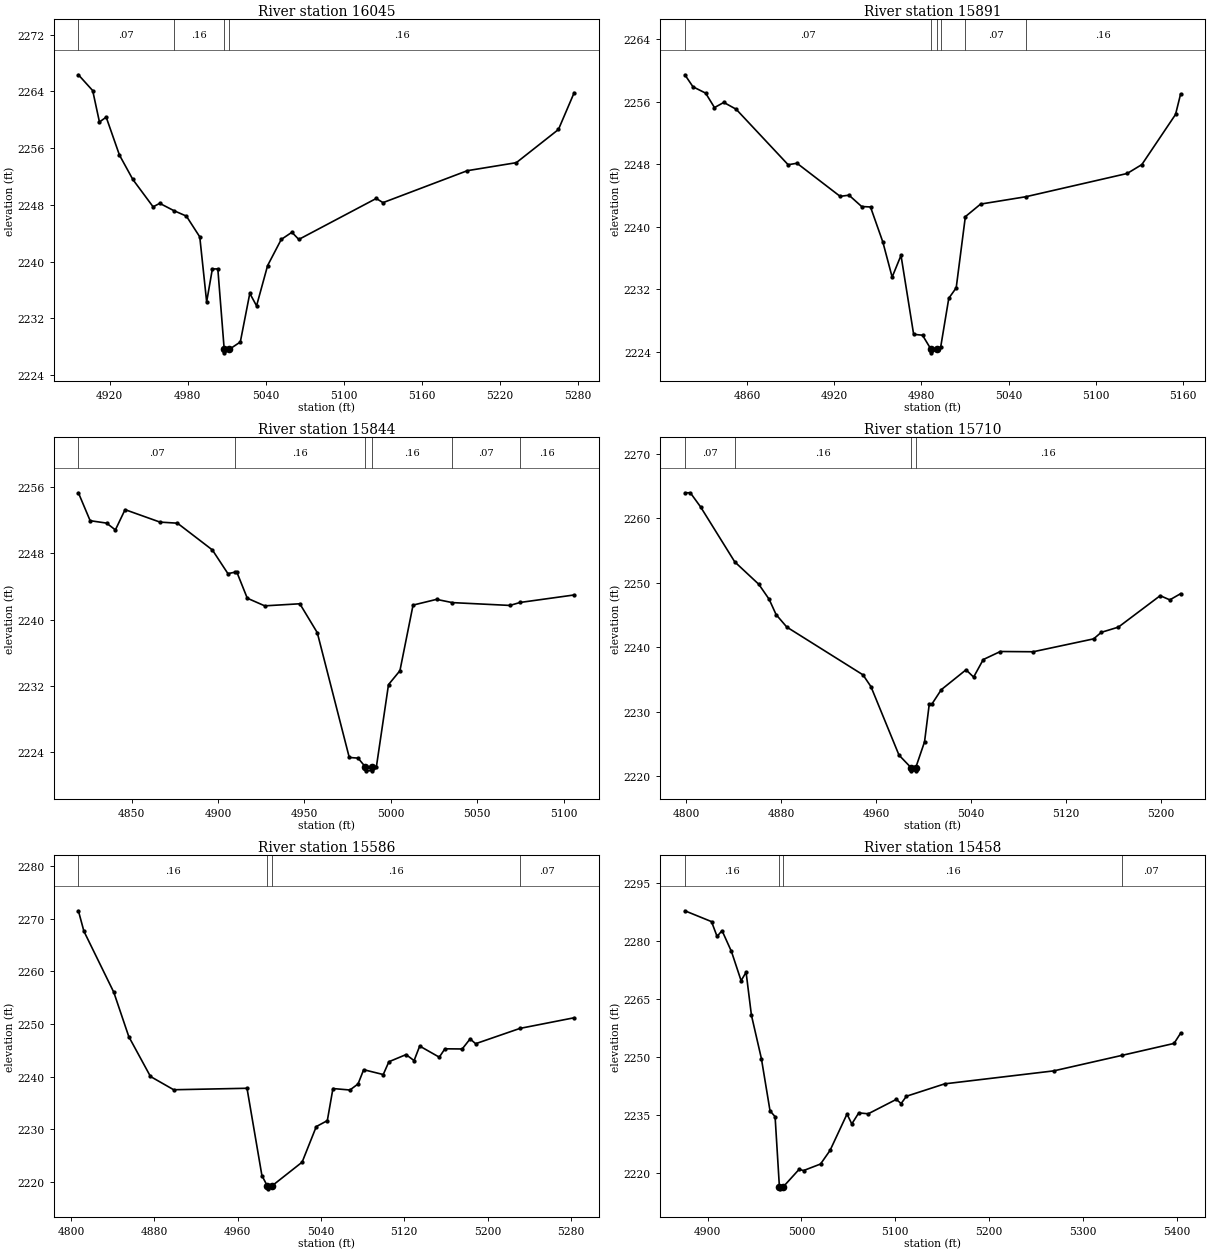
Type RM Length L Ch R = 1,16045,154,154,154
BEGIN DESCRIPTION:
Pleasant Run 16045.34
END DESCRIPTION:
XS GIS Cut Line= 3
      1517496.03      6761788.64      1517522.07      6761684.50
      1517604.06      6761422.90
#Sta/Elev= 30
  4895.9 2266.35  4906.9 2264.12  4912.1 2259.69  4917.3 2260.37  4927.5 2255.02
  4937.8 2251.58  4953.4 2247.72  4958.5 2248.21  4969.4 2247.18  4979.0 2246.41
  4989.3 2243.48  4994.6 2234.31  4999.0 2238.96  5003.2 2238.96  5008.1 2227.62
  5008.3 2227.12  5012.1 2227.62  5020.5 2228.65  5027.8 2235.51  5033.0 2233.75
  5041.5 2239.43  5052.0 2243.12  5060.2 2244.13  5065.5 2243.12  5125.1 2248.90
  5130.3 2248.31  5195.2 2252.82  5232.9 2253.95  5265.3 2258.63  5277.4 2263.82
#Mann=4,-1,0
  4895.9    0.07       0  4969.4    0.16       0  5008.1    0.07       0
  5012.1    0.16       0
Bank Sta=5008.1,5012.1
Exp/Cntr=0.3,0.1

Type RM Length L Ch R = 1,15891,47,47,47
BEGIN DESCRIPTION:
Pleasant Run 15891.26
END DESCRIPTION:
XS GIS Cut Line= 3
      1517558.51      6761790.00      1517658.79      6761645.44
      1517680.73      6761481.53
#Sta/Elev= 30
  4817.1 2259.48  4822.7 2257.94  4831.4 2257.13  4837.5 2255.28  4843.9 2255.94
  4852.4 2255.07  4888.2 2247.96  4894.3 2248.15  4924.0 2243.91  4930.1 2244.06
  4938.8 2242.61  4944.9 2242.55  4953.4 2238.06  4959.8 2233.57  4965.9 2236.35
  4974.6 2226.24  4980.7 2226.13  4986.4 2224.37  4986.7 2223.87  4990.4 2224.37
  4993.2 2224.59  4998.8 2230.86  5003.9 2232.19  5010.2 2241.31  5020.7 2242.92
  5051.8 2243.86  5121.6 2246.84  5131.7 2247.98  5154.9 2254.40  5158.4 2257.03
#Mann=6,-1,0
  4817.1    0.07       0  4986.4    0.07       0  4990.4    0.07       0
  4993.2    0.16       0  5010.2    0.07       0  5051.8    0.16       0
Bank Sta=4986.4,4990.4
Exp/Cntr=0.3,0.1

Type RM Length L Ch R = 1,15844,134,134,134
BEGIN DESCRIPTION:
Pleasant Run 15843.65
END DESCRIPTION:
XS GIS Cut Line= 3
      1517677.02      6761814.73      1517701.76      6761644.14
      1517777.29      6761558.18
#Sta/Elev= 30
  4819.2 2255.26  4826.0 2251.90  4835.5 2251.61  4840.6 2250.79  4846.2 2253.23
  4866.4 2251.73  4876.5 2251.60  4896.7 2248.38  4905.7 2245.53  4909.8 2245.70
  4910.8 2245.74  4916.9 2242.57  4927.0 2241.65  4947.3 2241.90  4957.4 2238.42
  4975.9 2223.40  4981.0 2223.32  4985.1 2222.29  4985.3 2221.79  4988.8 2221.79
  4989.1 2222.29  4991.6 2222.29  4998.6 2232.17  5005.2 2233.84  5012.8 2241.74
  5026.4 2242.43  5035.5 2242.04  5068.8 2241.70  5074.8 2242.06  5106.0 2242.96
#Mann=6,-1,0
  4819.2    0.07       0  4909.8    0.16       0  4985.1    0.07       0
  4989.1    0.16       0  5035.5    0.07       0  5074.8    0.16       0
Bank Sta=4985.1,4989.1
Exp/Cntr=0.3,0.1

Type RM Length L Ch R = 1,15710,124,124,124
BEGIN DESCRIPTION:
Pleasant Run 15709.92
END DESCRIPTION:
XS GIS Cut Line= 3
      1517710.86      6761870.72      1517820.25      6761696.22
      1517951.74      6761530.88
#Sta/Elev= 30
  4799.1 2263.93  4803.7 2263.93  4812.3 2261.75  4841.1 2253.21  4861.3 2249.74
  4870.0 2247.42  4875.9 2245.03  4884.9 2243.10  4949.0 2235.69  4955.7 2233.86
  4979.3 2223.24  4989.4 2221.30  4989.7 2220.80  4993.2 2220.80  4993.4 2221.30
  5000.8 2225.30  5004.8 2231.19  5007.1 2231.19  5014.9 2233.39  5035.7 2236.47
  5042.1 2235.34  5050.2 2238.06  5064.6 2239.31  5092.2 2239.27  5143.1 2241.27
  5149.5 2242.28  5163.9 2243.09  5199.1 2247.97  5207.2 2247.32  5216.3 2248.28
#Mann=4,-1,0
  4799.1    0.07       0  4841.1    0.16       0  4989.4    0.07       0
  4993.4    0.16       0
Bank Sta=4989.4,4993.4
Exp/Cntr=0.3,0.1

Type RM Length L Ch R = 1,15586,128,128,128
BEGIN DESCRIPTION:
Pleasant Run 15586.39
END DESCRIPTION:
XS GIS Cut Line= 3
      1517752.57      6761913.64      1517899.67      6761793.88
      1518006.45      6761528.23
#Sta/Elev= 30
  4807.2 2271.52  4812.5 2267.63  4841.2 2256.03  4855.6 2247.60  4876.4 2240.03
  4898.7 2237.51  4969.1 2237.79  4983.4 2221.21  4988.7 2219.18  4988.9 2218.68
  4992.7 2219.18  5022.0 2223.75  5035.6 2230.51  5046.2 2231.64  5051.6 2237.74
  5067.9 2237.46  5075.7 2238.61  5081.1 2241.32  5099.9 2240.40  5105.3 2242.83
  5121.8 2244.19  5129.5 2243.05  5134.9 2245.81  5153.7 2243.70  5159.1 2245.29
  5175.7 2245.26  5183.3 2247.17  5188.6 2246.26  5231.2 2249.17  5283.2 2251.19
#Mann=4,-1,0
  4807.2    0.16       0  4988.7    0.07       0  4992.7    0.16       0
  5231.2    0.07       0
Bank Sta=4988.7,4992.7
Exp/Cntr=0.3,0.1

Type RM Length L Ch R = 1,15458,178,178,178
BEGIN DESCRIPTION:
Pleasant Run 15457.64
END DESCRIPTION:
XS GIS Cut Line= 3
      1517928.33      6762004.79      1517971.29      6761883.72
      1518045.15      6761491.07
#Sta/Elev= 30
  4875.8 2287.79  4904.2 2284.99  4910.1 2281.17  4915.4 2282.66  4925.4 2277.29
  4935.7 2269.74  4941.0 2271.92  4946.7 2260.82  4957.3 2249.64  4966.5 2236.14
  4971.9 2234.62  4976.5 2216.49  4976.8 2215.99  4980.5 2216.49  4997.4 2221.00
  5002.3 2220.72  5020.3 2222.40  5030.4 2225.90  5048.5 2235.30  5053.6 2232.75
  5061.0 2235.60  5071.1 2235.37  5101.0 2239.09  5106.1 2238.01  5111.8 2239.90
  5152.5 2243.10  5268.7 2246.45  5341.6 2250.47  5396.8 2253.54  5403.8 2256.19
#Mann=4,-1,0
  4875.8    0.16       0  4976.5    0.07       0  4980.5    0.16       0
  5341.6    0.07       0
Bank Sta=4976.5,4980.5
Exp/Cntr=0.3,0.1

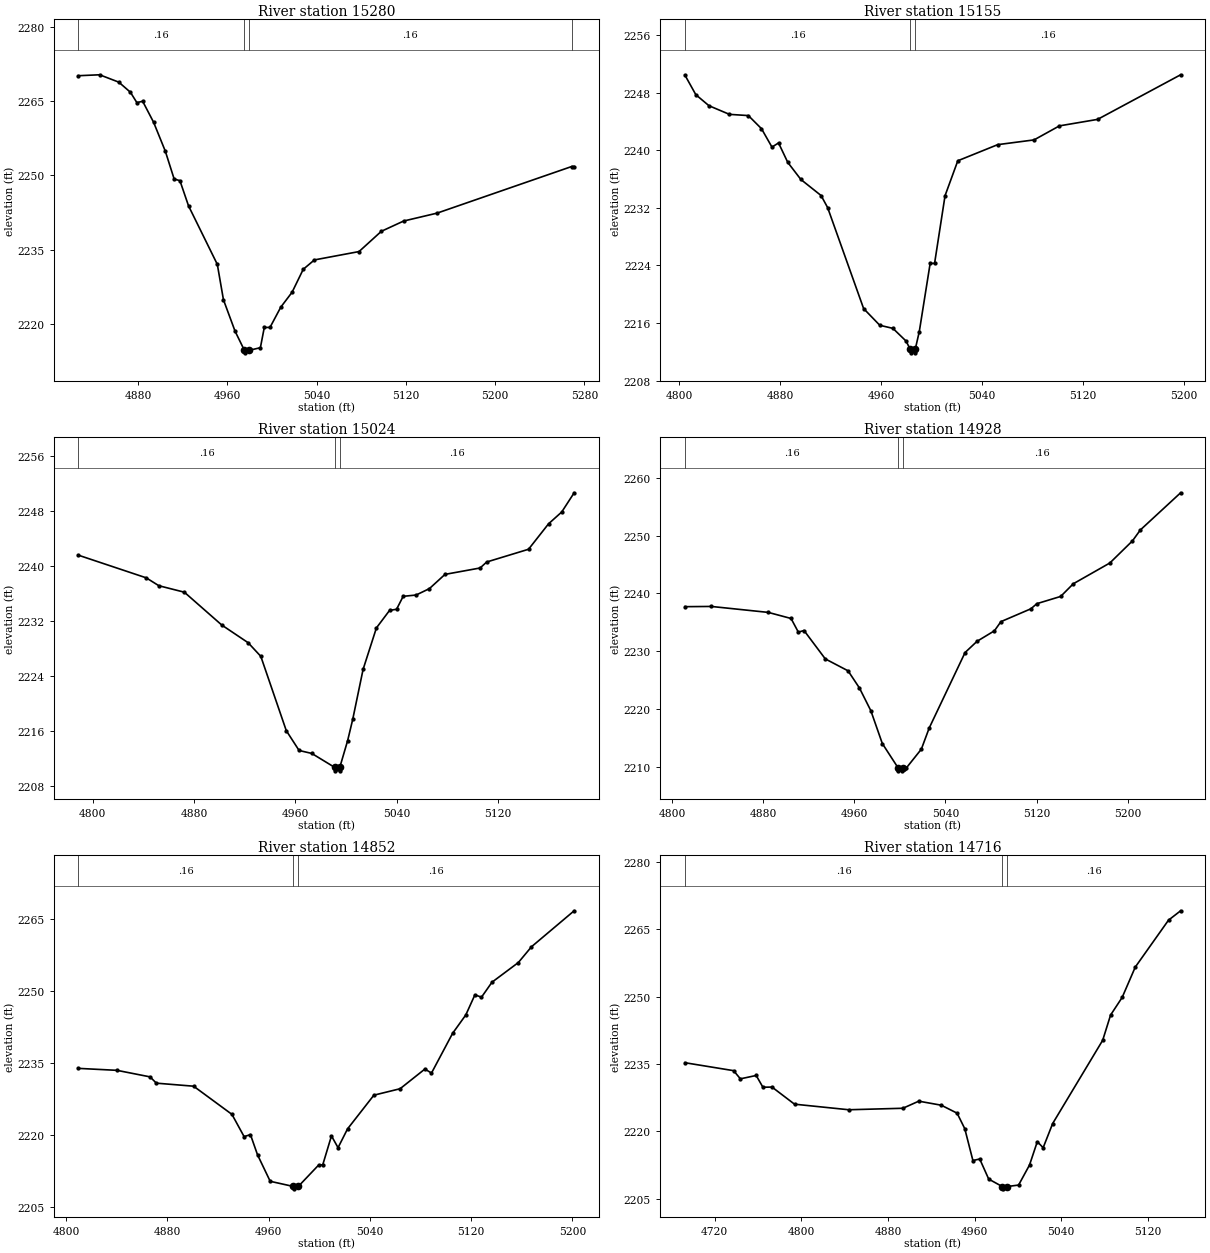
Type RM Length L Ch R = 1,15280,125,125,125
BEGIN DESCRIPTION:
Pleasant Run 15279.64
END DESCRIPTION:
XS GIS Cut Line= 3
      1518154.88      6761952.73      1518108.01      6761792.57
      1518100.20      6761515.25
#Sta/Elev= 30
  4826.5 2270.18  4845.5 2270.37  4862.7 2268.88  4873.1 2266.84  4878.9 2264.74
  4884.1 2265.01  4893.9 2260.76  4904.4 2254.91  4912.3 2249.29  4917.5 2248.94
  4925.2 2243.85  4951.0 2232.01  4956.5 2224.85  4966.9 2218.49  4975.3 2214.61
  4975.5 2214.11  4979.3 2214.61  4989.6 2215.15  4993.1 2219.25  4998.2 2219.25
  5007.9 2223.36  5018.0 2226.37  5028.0 2231.01  5038.0 2232.91  5078.0 2234.60
  5098.0 2238.70  5118.0 2240.78  5148.0 2242.38  5268.6 2251.81  5270.8 2251.81
#Mann=4,-1,0
  4826.5    0.16       0  4975.3    0.07       0  4979.3    0.16       0
  5268.6    0.07       0
Bank Sta=4975.3,4979.3
Exp/Cntr=0.3,0.1

Type RM Length L Ch R = 1,15155,131,131,131
BEGIN DESCRIPTION:
Pleasant Run 15155.47
END DESCRIPTION:
XS GIS Cut Line= 3
      1518249.94      6761886.34      1518195.25      6761696.22
      1518173.16      6761502.61
#Sta/Elev= 30
  4804.5 2250.47  4813.2 2247.73  4823.6 2246.20  4839.8 2245.00  4854.8 2244.83
  4865.2 2243.01  4873.5 2240.45  4878.7 2241.03  4886.0 2238.33  4896.4 2235.95
  4912.4 2233.72  4917.6 2232.04  4946.1 2218.01  4958.9 2215.69  4969.3 2215.26
  4979.7 2213.50  4983.0 2212.36  4983.3 2211.86  4986.8 2211.86  4987.0 2212.36
  4990.2 2214.82  4998.8 2224.29  5002.3 2224.29  5010.6 2233.70  5020.7 2238.55
  5052.3 2240.79  5081.1 2241.45  5101.2 2243.40  5131.4 2244.30  5197.2 2250.50
#Mann=3,-1,0
  4804.5    0.16       0  4983.0    0.07       0  4987.0    0.16       0
Bank Sta=4983,4987
Exp/Cntr=0.3,0.1

Type RM Length L Ch R = 1,15024,96,96,96
BEGIN DESCRIPTION:
Pleasant Run 15023.89
END DESCRIPTION:
XS GIS Cut Line= 3
      1518331.97      6761851.18      1518309.83      6761635.02
      1518259.53      6761468.64
#Sta/Elev= 30
  4788.8 2241.59  4842.3 2238.30  4852.3 2237.15  4872.4 2236.21  4901.9 2231.44
  4922.7 2228.87  4932.7 2226.89  4952.8 2216.09  4962.9 2213.21  4972.9 2212.78
  4991.0 2210.75  4991.3 2210.25  4994.8 2210.25  4995.0 2210.75  5001.2 2214.64
  5005.2 2217.72  5013.4 2225.00  5023.9 2231.02  5034.3 2233.57  5039.8 2233.73
  5045.0 2235.61  5055.2 2235.80  5065.7 2236.73  5078.0 2238.80  5105.7 2239.73
  5110.9 2240.60  5143.9 2242.45  5159.7 2246.15  5170.1 2247.87  5179.9 2250.66
#Mann=3,-1,0
  4788.8    0.16       0  4991.0    0.07       0  4995.0    0.16       0
Bank Sta=4991,4995
Exp/Cntr=0.3,0.1

Type RM Length L Ch R = 1,14928,76,76,76
BEGIN DESCRIPTION:
Pleasant Run 14928.41
END DESCRIPTION:
XS GIS Cut Line= 3
      1518394.47      6761821.20      1518404.88      6761631.12
      1518329.67      6761397.70
#Sta/Elev= 30
  4811.0 2237.70  4834.2 2237.74  4884.3 2236.71  4904.3 2235.66  4910.7 2233.30
  4915.7 2233.58  4934.4 2228.67  4954.4 2226.61  4964.4 2223.64  4974.4 2219.72
  4984.5 2214.04  4998.4 2209.82  4998.7 2209.32  5002.2 2209.32  5002.4 2209.82
  5005.6 2209.82  5018.8 2213.07  5025.7 2216.73  5057.2 2229.77  5067.7 2231.71
  5083.0 2233.53  5088.7 2235.11  5115.0 2237.33  5120.3 2238.22  5141.2 2239.47
  5152.3 2241.66  5184.4 2245.25  5204.3 2249.08  5211.2 2250.96  5246.6 2257.39
#Mann=3,-1,0
  4811.0    0.16       0  4998.4    0.07       0  5002.4    0.16       0
Bank Sta=4998.4,5002.4
Exp/Cntr=0.3,0.1

Type RM Length L Ch R = 1,14852,136,136,136
BEGIN DESCRIPTION:
Pleasant Run 14851.79
END DESCRIPTION:
XS GIS Cut Line= 3
      1518442.64      6761778.30      1518467.38      6761586.85
      1518520.39      6761395.50
#Sta/Elev= 30
  4809.8 2233.91  4840.3 2233.50  4866.4 2232.14  4871.4 2230.83  4900.8 2230.20
  4931.1 2224.33  4940.7 2219.70  4945.7 2220.12  4951.3 2215.91  4961.3 2210.40
  4979.5 2209.33  4979.8 2208.83  4983.5 2209.33  4999.7 2213.82  5002.8 2213.82
  5009.7 2219.85  5014.9 2217.40  5022.4 2221.31  5043.2 2228.33  5063.9 2229.67
  5083.5 2233.77  5088.7 2232.93  5105.4 2241.21  5115.8 2245.03  5123.0 2249.22
  5128.2 2248.73  5136.5 2251.85  5157.3 2255.94  5167.7 2259.23  5201.4 2266.72
#Mann=3,-1,0
  4809.8    0.16       0  4979.5    0.07       0  4983.5    0.16       0
Bank Sta=4979.5,4983.5
Exp/Cntr=0.3,0.1

Type RM Length L Ch R = 1,14716,119,119,119
BEGIN DESCRIPTION:
Pleasant Run 14715.63
END DESCRIPTION:
XS GIS Cut Line= 3
      1518420.49      6761835.57      1518601.50      6761592.05
      1518656.20      6761447.48
#Sta/Elev= 30
  4692.4 2235.29  4737.4 2233.52  4743.7 2231.70  4758.3 2232.45  4764.5 2229.83
  4772.9 2229.87  4793.7 2226.06  4843.8 2224.82  4893.8 2225.15  4908.5 2226.73
  4929.3 2225.83  4943.9 2224.06  4951.0 2220.60  4958.5 2213.52  4964.8 2213.86
  4973.1 2209.39  4985.7 2207.72  4986.0 2207.22  4989.7 2207.72  5000.7 2208.06
  5010.8 2212.52  5018.0 2217.72  5023.4 2216.37  5032.2 2221.76  5078.4 2240.28
  5085.7 2245.90  5096.4 2249.82  5108.5 2256.57  5139.2 2267.01  5150.4 2269.10
#Mann=3,-1,0
  4692.4    0.16       0  4985.7    0.07       0  4989.7    0.16       0
Bank Sta=4985.7,4989.7
Exp/Cntr=0.3,0.1

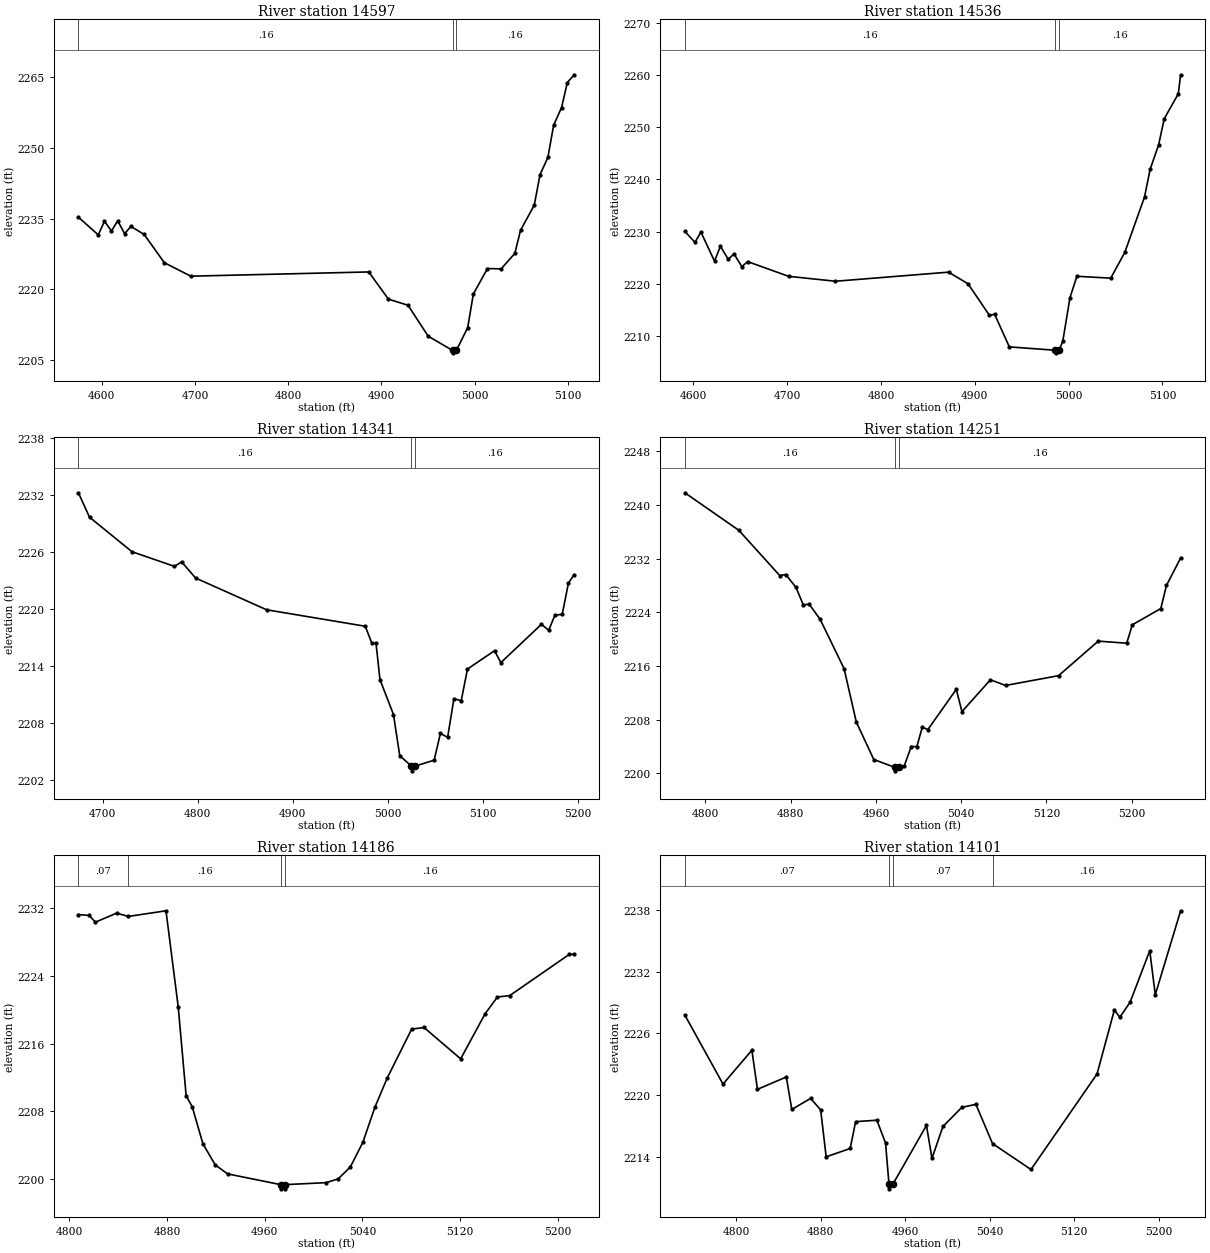
Type RM Length L Ch R = 1,14597,61,61,61
BEGIN DESCRIPTION:
Pleasant Run 14596.559
END DESCRIPTION:
XS GIS Cut Line= 3
      1518405.01      6761887.99      1518718.81      6761601.22
      1518805.01      6761537.99
#Sta/Elev= 30
  4574.9 2235.29  4596.2 2231.53  4602.9 2234.42  4610.4 2232.34  4617.1 2234.52
  4624.5 2231.79  4631.3 2233.32  4645.5 2231.62  4667.1 2225.63  4695.5 2222.76
  4886.5 2223.66  4907.6 2217.88  4928.6 2216.59  4950.2 2210.03  4976.5 2206.98
  4976.8 2206.48  4980.5 2206.98  4992.7 2211.86  4998.7 2218.97  5013.9 2224.39
  5028.5 2224.31  5043.2 2227.59  5049.4 2232.52  5064.1 2237.86  5070.3 2244.34
  5078.7 2247.98  5084.9 2254.84  5093.4 2258.58  5099.6 2263.89  5106.9 2265.53
#Mann=3,-1,0
  4574.9    0.16       0  4976.5    0.07       0  4980.5    0.16       0
Bank Sta=4976.5,4980.5
Exp/Cntr=0.3,0.1

Type RM Length L Ch R = 1,14536,195,195,195
BEGIN DESCRIPTION:
Pleasant Run 14536.24
END DESCRIPTION:
XS GIS Cut Line= 3
      1518425.72      6761892.83      1518688.74      6761692.31
      1518853.09      6761582.31
#Sta/Elev= 30
  4590.9 2230.05  4601.7 2227.95  4608.0 2229.93  4622.5 2224.35  4628.8 2227.20
  4637.1 2224.71  4643.3 2225.74  4651.6 2223.30  4657.9 2224.26  4701.5 2221.44
  4751.4 2220.50  4872.0 2222.24  4892.8 2220.01  4915.6 2213.96  4921.1 2214.18
  4936.8 2207.92  4985.8 2207.28  4986.1 2206.78  4989.8 2207.28  4993.8 2209.01
  5001.4 2217.32  5008.8 2221.45  5044.9 2221.09  5059.9 2226.03  5080.9 2236.64
  5086.9 2241.95  5095.9 2246.60  5101.9 2251.62  5116.9 2256.41  5119.4 2260.06
#Mann=3,-1,0
  4590.9    0.16       0  4985.8    0.07       0  4989.8    0.16       0
Bank Sta=4985.8,4989.8
Exp/Cntr=0.3,0.1

Type RM Length L Ch R = 1,14341,90,90,90
BEGIN DESCRIPTION:
Pleasant Run 14341.38
END DESCRIPTION:
XS GIS Cut Line= 3
      1518417.90      6761977.47      1518697.85      6761836.85
      1518834.58      6761679.28
#Sta/Elev= 30
  4674.5 2232.25  4686.2 2229.68  4730.9 2226.05  4775.6 2224.51  4783.2 2224.98
  4797.9 2223.28  4872.7 2219.94  4976.5 2218.21  4983.4 2216.43  4987.8 2216.43
  4992.0 2212.59  5006.2 2208.92  5012.8 2204.59  5025.1 2203.50  5025.3 2203.00
  5029.1 2203.50  5049.0 2204.12  5055.6 2206.93  5063.2 2206.53  5069.8 2210.58
  5077.5 2210.38  5084.1 2213.71  5112.6 2215.64  5119.2 2214.38  5161.9 2218.41
  5169.6 2217.79  5176.2 2219.39  5183.8 2219.45  5190.4 2222.76  5196.4 2223.64
#Mann=3,-1,0
  4674.5    0.16       0  5025.1    0.07       0  5029.1    0.16       0
Bank Sta=5025.1,5029.1
Exp/Cntr=0.3,0.1

Type RM Length L Ch R = 1,14251,65,65,65
BEGIN DESCRIPTION:
Pleasant Run 14251.02
END DESCRIPTION:
XS GIS Cut Line= 3
      1518667.89      6762080.36      1518766.86      6761891.53
      1518844.61      6761651.82
#Sta/Elev= 30
  4780.7 2241.83  4831.3 2236.24  4869.7 2229.49  4875.4 2229.63  4885.0 2227.71
  4891.8 2225.11  4897.4 2225.21  4907.6 2222.96  4930.1 2215.60  4941.6 2207.62
  4958.0 2202.04  4978.0 2200.85  4978.3 2200.35  4982.0 2200.85  4986.6 2201.10
  4993.1 2203.97  4998.4 2203.97  5003.5 2206.88  5008.7 2206.50  5035.4 2212.51
  5040.7 2209.18  5067.4 2213.93  5081.7 2213.09  5131.4 2214.55  5168.6 2219.70
  5195.3 2219.39  5200.6 2222.14  5227.3 2224.56  5232.6 2228.01  5245.9 2232.10
#Mann=3,-1,0
  4780.7    0.16       0  4978.0    0.07       0  4982.0    0.16       0
Bank Sta=4978,4982
Exp/Cntr=0.3,0.1

Type RM Length L Ch R = 1,14186,85,85,85
BEGIN DESCRIPTION:
Pleasant Run 14186.43
END DESCRIPTION:
XS GIS Cut Line= 3
      1518808.52      6762079.07      1518833.27      6761887.63
      1518847.59      6761675.35
#Sta/Elev= 30
  4807.5 2231.27  4816.3 2231.17  4821.4 2230.37  4838.8 2231.44  4848.4 2231.05
  4879.2 2231.72  4889.2 2220.36  4895.7 2209.83  4900.7 2208.52  4909.4 2204.16
  4919.5 2201.65  4929.6 2200.59  4973.0 2199.32  4973.3 2198.82  4976.8 2198.82
  4977.0 2199.32  5010.2 2199.55  5020.2 2200.00  5030.2 2201.43  5040.3 2204.31
  5050.3 2208.51  5060.3 2211.94  5080.3 2217.72  5090.4 2217.91  5120.4 2214.20
  5140.5 2219.56  5150.5 2221.52  5160.5 2221.68  5209.4 2226.57  5213.3 2226.57
#Mann=4,-1,0
  4807.5    0.07       0  4848.4    0.16       0  4973.0    0.07       0
  4977.0    0.16       0
Bank Sta=4973,4977
Exp/Cntr=0.3,0.1

Type RM Length L Ch R = 1,14101,37,37,37
BEGIN DESCRIPTION:
Pleasant Run 14100.51
END DESCRIPTION:
XS GIS Cut Line= 3
      1518890.55      6762081.65      1518933.53      6761943.62
      1518842.66      6761632.07
#Sta/Elev= 30
  4751.5 2227.77  4787.6 2221.07  4814.9 2224.36  4820.2 2220.56  4847.5 2221.76
  4852.7 2218.60  4870.5 2219.68  4880.0 2218.56  4885.2 2214.00  4907.9 2214.81
  4913.1 2217.42  4933.2 2217.56  4941.4 2215.34  4944.6 2211.39  4944.8 2210.89
  4948.6 2211.39  4980.1 2217.05  4985.3 2213.85  4995.7 2216.95  5013.6 2218.81
  5026.9 2219.10  5042.6 2215.29  5079.0 2212.77  5141.5 2222.05  5157.9 2228.27
  5163.1 2227.56  5172.8 2229.03  5191.4 2234.03  5196.6 2229.75  5220.6 2237.91
#Mann=4,-1,0
  4751.5    0.07       0  4944.6    0.07       0  4948.6    0.07       0
  5042.6    0.16       0
Bank Sta=4944.6,4948.6
Exp/Cntr=0.3,0.1