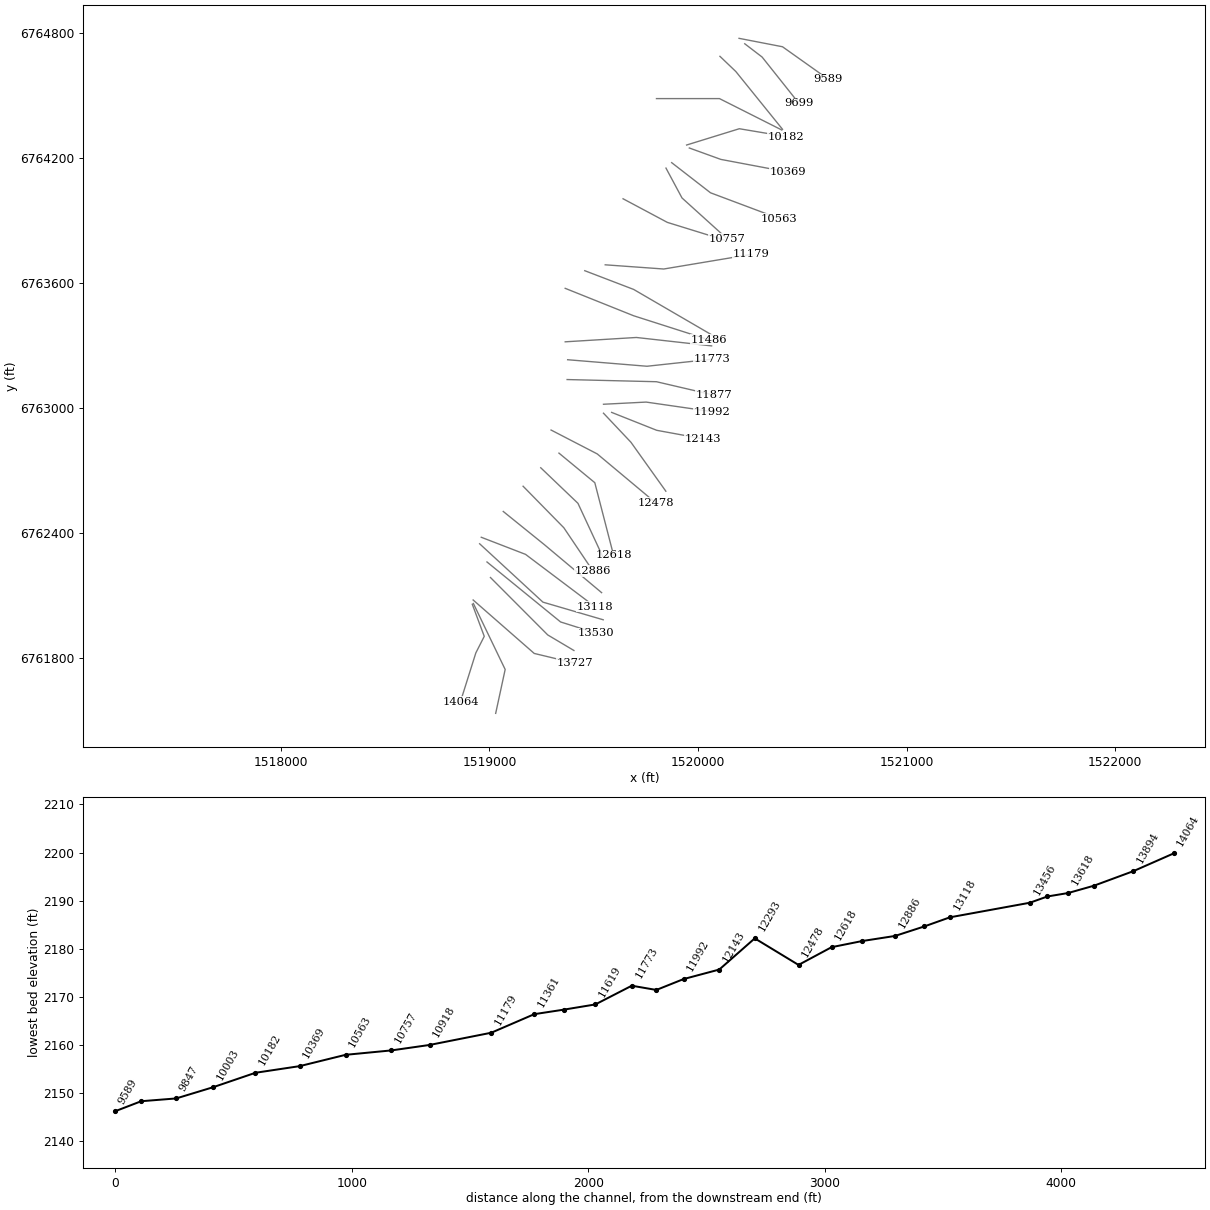
HEC-RAS study Pleasant Run.prj: Pleasant Run Base Level Engineering

--- Pleasant Run.g01 (geometry) --- (continued)

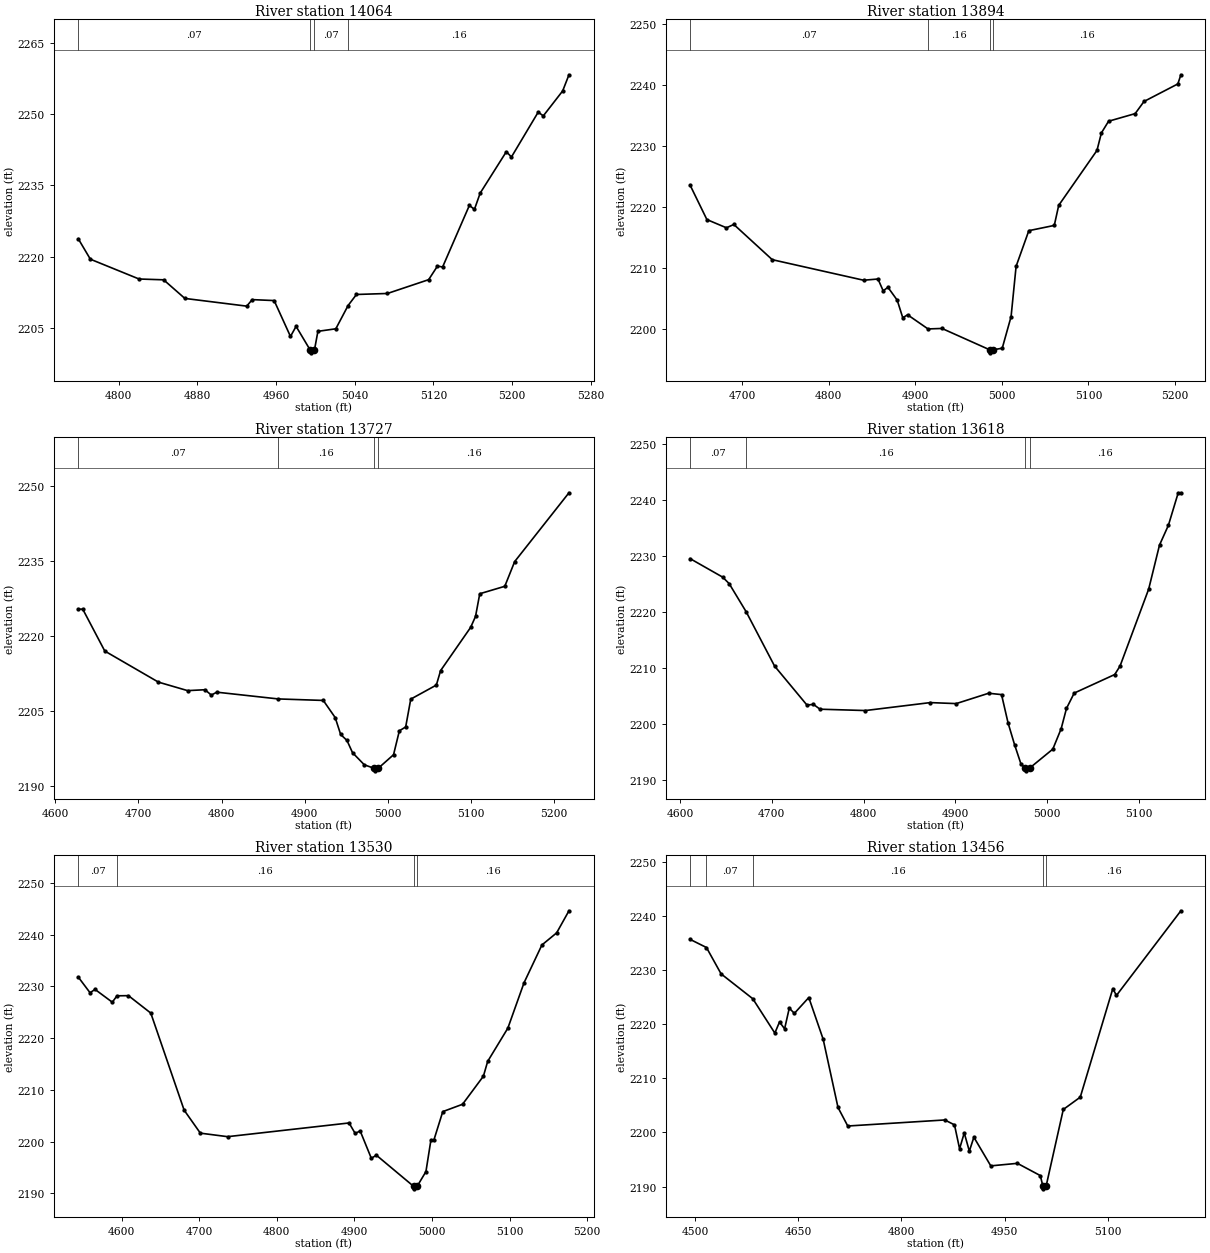
Type RM Length L Ch R = 1,14064,170,170,170
BEGIN DESCRIPTION:
Pleasant Run 14064.05
END DESCRIPTION:
XS GIS Cut Line= 4
      1518917.89      6762059.52      1518975.19      6761905.86
      1518934.83      6761826.43      1518860.97      6761591.88
#Sta/Elev= 30
  4758.9 2223.78  4771.2 2219.49  4820.7 2215.33  4845.7 2215.16  4867.3 2211.25
  4930.2 2209.63  4935.8 2211.00  4958.1 2210.80  4974.7 2203.26  4980.4 2205.38
  4995.0 2200.32  4995.2 2199.82  4999.0 2200.32  5002.6 2204.34  5020.8 2204.87
  5033.3 2209.76  5041.8 2212.08  5073.3 2212.29  5115.2 2215.19  5124.2 2218.05
  5129.4 2217.85  5156.6 2230.78  5161.8 2229.97  5167.6 2233.37  5194.2 2242.07
  5199.4 2240.96  5226.6 2250.38  5231.8 2249.60  5251.5 2254.84  5257.9 2258.23
#Mann=4,-1,0
  4758.9    0.07       0  4995.0    0.07       0  4999.0    0.07       0
  5033.3    0.16       0
Bank Sta=4995,4999
Exp/Cntr=0.3,0.1

Type RM Length L Ch R = 1,13894,167,167,167
BEGIN DESCRIPTION:
Pleasant Run 13894.08
END DESCRIPTION:
XS GIS Cut Line= 3
      1518923.10      6762063.42      1519075.45      6761747.00
      1519029.94      6761536.35
#Sta/Elev= 30
  4640.0 2223.62  4659.3 2218.00  4681.9 2216.65  4690.4 2217.20  4734.8 2211.42
  4840.3 2208.05  4856.9 2208.25  4862.9 2206.31  4868.4 2206.89  4879.1 2204.78
  4885.5 2201.90  4891.1 2202.38  4914.7 2200.06  4930.8 2200.14  4985.9 2196.64
  4986.1 2196.14  4989.9 2196.64  5000.4 2196.90  5010.6 2202.08  5016.4 2210.33
  5031.1 2216.18  5060.5 2217.04  5065.6 2220.33  5109.8 2229.34  5114.9 2232.21
  5123.2 2234.13  5153.9 2235.38  5164.1 2237.37  5203.2 2240.25  5206.7 2241.75
#Mann=4,-1,0
  4640.0    0.07       0  4914.7    0.16       0  4985.9    0.07       0
  4989.9    0.16       0
Bank Sta=4985.9,4989.9
Exp/Cntr=0.3,0.1

Type RM Length L Ch R = 1,13727,109,109,109
BEGIN DESCRIPTION:
Pleasant Run 13727.37
END DESCRIPTION:
XS GIS Cut Line= 3
      1518921.84      6762080.31      1519214.78      6761823.82
      1519410.08      6761776.95
#Sta/Elev= 30
  4627.6 2225.42  4633.0 2225.42  4659.5 2217.05  4724.0 2210.84  4759.1 2209.14
  4780.0 2209.32  4787.6 2208.25  4794.2 2208.83  4868.1 2207.48  4922.3 2207.18
  4936.6 2203.76  4943.2 2200.38  4950.8 2199.18  4957.5 2196.73  4971.7 2194.31
  4983.6 2193.61  4983.9 2193.11  4988.3 2193.61  5006.8 2196.33  5013.8 2201.11
  5021.4 2201.88  5027.5 2207.44  5058.3 2210.25  5063.4 2213.14  5099.5 2221.77
  5105.4 2223.96  5110.5 2228.50  5140.6 2229.99  5152.5 2234.93  5217.8 2248.68
#Mann=4,-1,0
  4627.6    0.07       0  4868.1    0.16       0  4983.6    0.07       0
  4988.3    0.16       0
Bank Sta=4983.6,4988.3
Exp/Cntr=0.3,0.1

Type RM Length L Ch R = 1,13618,88,88,88
BEGIN DESCRIPTION:
Pleasant Run 13617.695
END DESCRIPTION:
XS GIS Cut Line= 3
      1519004.97      6762188.03      1519279.59      6761912.53
      1519405.02      6761837.99
#Sta/Elev= 30
  4611.0 2229.52  4646.4 2226.22  4653.5 2225.06  4672.1 2220.01  4703.0 2210.32
  4738.3 2203.35  4745.4 2203.47  4752.5 2202.61  4802.0 2202.37  4872.7 2203.79
  4901.0 2203.61  4936.3 2205.46  4950.4 2205.22  4957.5 2200.17  4964.6 2196.27
  4971.7 2192.76  4976.4 2192.09  4976.7 2191.59  4981.1 2192.09  5006.3 2195.47
  5015.4 2199.12  5021.2 2202.75  5029.6 2205.49  5073.8 2208.81  5079.6 2210.33
  5110.8 2224.08  5122.6 2231.95  5132.3 2235.49  5143.0 2241.30  5145.9 2241.30
#Mann=4,-1,0
  4611.0    0.07       0  4672.1    0.16       0  4976.4    0.07       0
  4981.1    0.16       0
Bank Sta=4976.4,4981.1
Exp/Cntr=0.3,0.1

Type RM Length L Ch R = 1,13530,74,74,74
BEGIN DESCRIPTION:
Pleasant Run 13529.81
END DESCRIPTION:
XS GIS Cut Line= 3
      1518988.24      6762262.61      1519341.08      6761974.87
      1519510.18      6761921.54
#Sta/Elev= 30
  4544.0 2231.79  4559.2 2228.76  4565.6 2229.41  4587.9 2226.93  4593.9 2228.17
  4608.7 2228.20  4637.5 2224.83  4680.5 2206.07  4701.4 2201.63  4736.5 2200.95
  4893.1 2203.60  4901.0 2201.57  4907.4 2202.07  4921.8 2196.77  4928.3 2197.37
  4976.2 2191.37  4976.5 2190.87  4980.9 2191.37  4992.2 2194.20  4998.6 2200.27
  5002.4 2200.27  5013.9 2205.79  5039.4 2207.21  5066.3 2212.64  5071.8 2215.50
  5097.8 2221.92  5118.7 2230.70  5141.7 2237.99  5160.7 2240.33  5176.6 2244.60
#Mann=4,-1,0
  4544.0    0.07       0  4593.9    0.16       0  4976.2    0.07       0
  4980.9    0.16       0
Bank Sta=4976.2,4980.9
Exp/Cntr=0.3,0.1

Type RM Length L Ch R = 1,13456,338,338,338
BEGIN DESCRIPTION:
Pleasant Run 13455.98
END DESCRIPTION:
XS GIS Cut Line= 3
      1518953.03      6762349.89      1519256.44      6762069.92
      1519545.47      6761985.29
#Sta/Elev= 30
  4492.6 2235.74  4516.3 2234.24  4537.6 2229.36  4583.7 2224.76  4615.8 2218.40
  4622.6 2220.46  4630.0 2219.19  4636.8 2223.02  4644.2 2222.05  4665.2 2224.98
  4686.1 2217.27  4707.7 2204.63  4721.9 2201.20  4863.1 2202.32  4877.2 2201.41
  4884.6 2196.98  4891.4 2199.92  4898.8 2196.55  4905.4 2199.12  4930.0 2193.82
  4968.7 2194.29  5002.1 2192.02  5005.8 2190.07  5006.1 2189.57  5010.5 2190.07
  5035.5 2204.26  5060.2 2206.54  5107.6 2226.64  5112.8 2225.36  5206.6 2241.04
#Mann=5,-1,0
  4492.6    0.16       0  4516.3    0.07       0  4583.7    0.16       0
  5005.8    0.07       0  5010.5    0.16       0
Bank Sta=5005.8,5010.5
Exp/Cntr=0.3,0.1

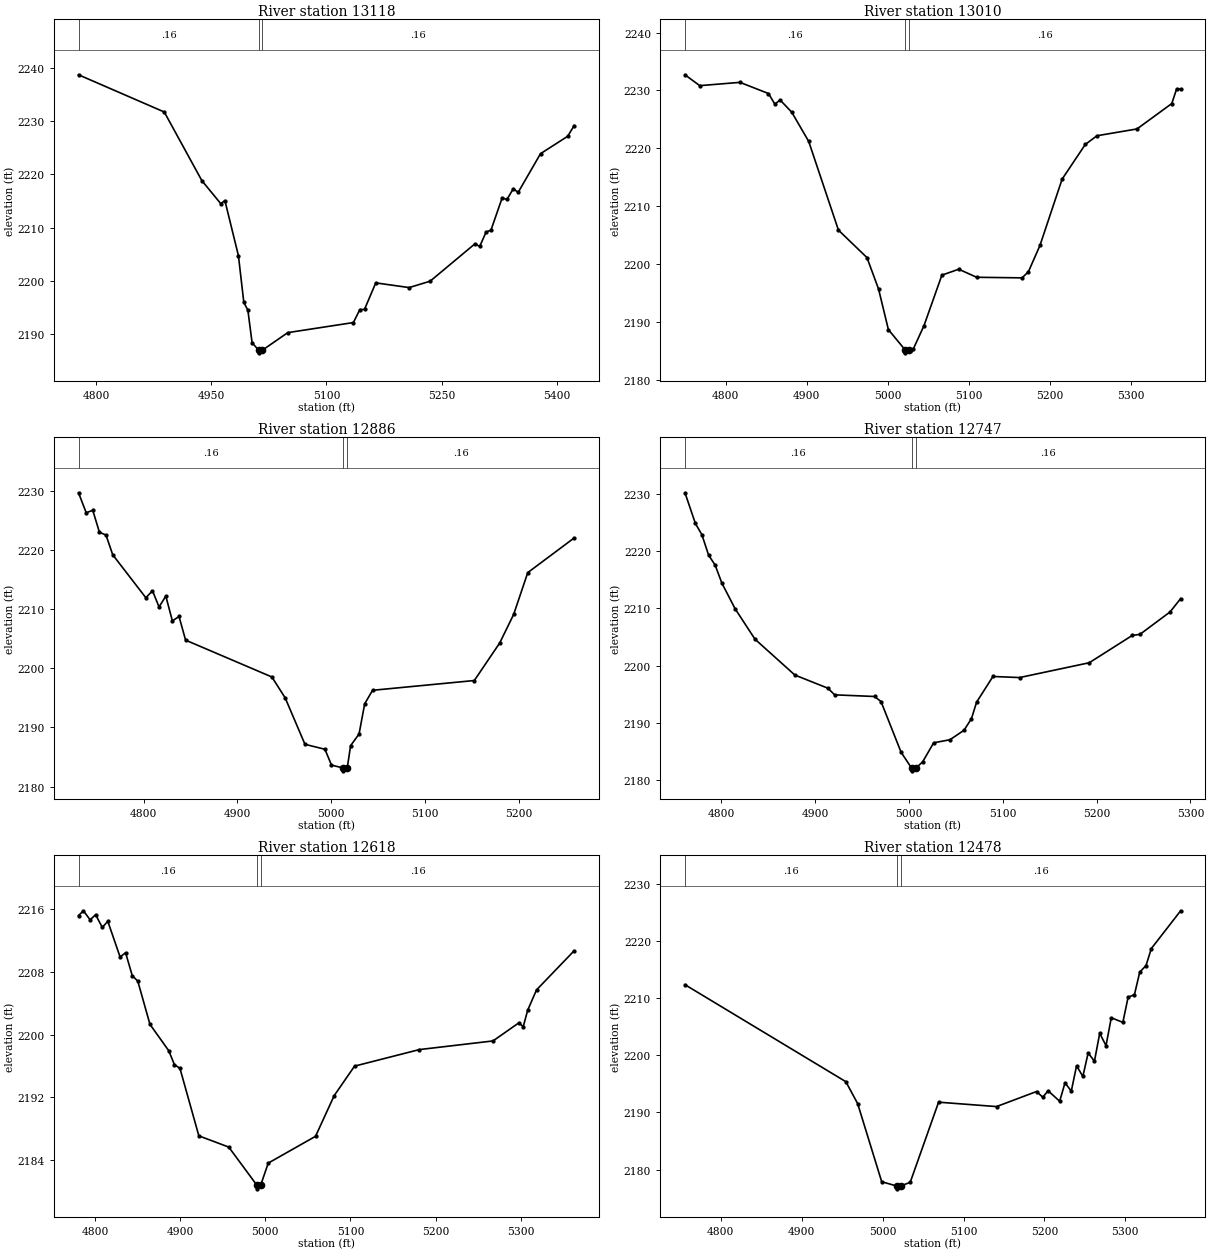
Type RM Length L Ch R = 1,13118,108,108,108
BEGIN DESCRIPTION:
Pleasant Run 13117.99
END DESCRIPTION:
XS GIS Cut Line= 3
      1518960.87      6762381.12      1519173.11      6762299.08
      1519506.45      6762047.78
#Sta/Elev= 30
  4777.3 2238.69  4888.9 2231.71  4937.8 2218.84  4962.4 2214.52  4967.8 2215.09
  4985.4 2204.76  4992.4 2196.01  4997.7 2194.53  5003.2 2188.42  5011.8 2187.04
  5012.2 2186.54  5016.6 2187.04  5049.6 2190.33  5135.0 2192.22  5143.3 2194.62
  5149.5 2194.70  5164.1 2199.66  5207.6 2198.78  5234.9 2199.98  5293.2 2206.99
  5299.4 2206.49  5307.7 2209.21  5314.0 2209.54  5328.6 2215.60  5334.8 2215.30
  5343.1 2217.33  5349.4 2216.63  5378.5 2223.89  5413.9 2227.16  5422.3 2229.17
#Mann=3,-1,0
  4777.3    0.16       0  5011.8    0.07       0  5016.6    0.16       0
Bank Sta=5011.8,5016.6
Exp/Cntr=0.3,0.1

Type RM Length L Ch R = 1,13010,124,124,124
BEGIN DESCRIPTION:
Pleasant Run 13010.41
END DESCRIPTION:
XS GIS Cut Line= 3
      1519066.33      6762504.82      1519262.95      6762345.96
      1519537.71      6762115.48
#Sta/Elev= 30
  4749.7 2232.71  4767.9 2230.83  4817.5 2231.40  4852.7 2229.47  4860.6 2227.63
  4867.0 2228.36  4881.4 2226.24  4902.3 2221.20  4939.0 2205.86  4974.2 2201.11
  4988.5 2195.67  5000.6 2188.67  5021.3 2185.15  5021.6 2184.65  5026.1 2185.15
  5031.3 2185.30  5044.5 2189.34  5066.6 2198.08  5087.4 2199.10  5109.5 2197.71
  5165.5 2197.61  5173.3 2198.66  5187.6 2203.22  5214.9 2214.67  5243.5 2220.67
  5257.9 2222.17  5307.3 2223.35  5350.2 2227.74  5356.1 2230.24  5361.1 2230.24
#Mann=3,-1,0
  4749.7    0.16       0  5021.3    0.07       0  5026.1    0.16       0
Bank Sta=5021.3,5026.1
Exp/Cntr=0.3,0.1

Type RM Length L Ch R = 1,12886,139,139,139
BEGIN DESCRIPTION:
Pleasant Run 12886.39
END DESCRIPTION:
XS GIS Cut Line= 3
      1519161.38      6762625.92      1519356.70      6762426.69
      1519496.06      6762219.62
#Sta/Elev= 30
  4730.5 2229.62  4738.7 2226.25  4745.7 2226.66  4752.8 2222.96  4759.8 2222.48
  4767.0 2219.15  4802.3 2211.90  4809.4 2213.07  4816.4 2210.34  4823.6 2212.18
  4830.6 2207.99  4837.7 2208.73  4844.7 2204.74  4936.7 2198.52  4950.9 2194.99
  4972.0 2187.15  4993.3 2186.31  5000.3 2183.64  5012.3 2183.17  5012.6 2182.67
  5017.1 2183.17  5020.7 2186.93  5029.7 2188.89  5035.7 2193.99  5044.1 2196.27
  5152.6 2197.92  5179.7 2204.26  5194.6 2209.09  5209.6 2216.14  5259.1 2221.99
#Mann=3,-1,0
  4730.5    0.16       0  5012.3    0.07       0  5017.1    0.16       0
Bank Sta=5012.3,5017.1
Exp/Cntr=0.3,0.1

Type RM Length L Ch R = 1,12747,129,129,129
BEGIN DESCRIPTION:
Pleasant Run 12746.58
END DESCRIPTION:
XS GIS Cut Line= 3
      1519246.00      6762714.48      1519424.41      6762543.88
      1519542.89      6762288.69
#Sta/Elev= 30
  4761.3 2230.23  4772.4 2224.86  4779.3 2222.91  4786.5 2219.31  4793.4 2217.60
  4800.7 2214.40  4814.8 2209.93  4835.9 2204.63  4878.4 2198.36  4913.6 2196.06
  4920.8 2194.90  4963.3 2194.61  4970.2 2193.73  4991.6 2184.86  5002.7 2182.11
  5003.1 2181.61  5007.5 2182.11  5014.6 2183.19  5026.3 2186.51  5043.7 2187.05
  5058.7 2188.71  5066.6 2190.74  5072.1 2193.63  5089.5 2198.11  5117.9 2197.92
  5192.1 2200.51  5237.9 2205.28  5246.2 2205.48  5278.2 2209.39  5289.5 2211.72
#Mann=3,-1,0
  4761.3    0.16       0  5002.7    0.07       0  5007.5    0.16       0
Bank Sta=5002.7,5007.5
Exp/Cntr=0.3,0.1

Type RM Length L Ch R = 1,12618,140,140,140
BEGIN DESCRIPTION:
Pleasant Run 12618.28
END DESCRIPTION:
XS GIS Cut Line= 3
      1519333.26      6762784.77      1519505.14      6762642.83
      1519594.99      6762295.16
#Sta/Elev= 30
  4780.7 2215.15  4786.5 2215.76  4794.3 2214.61  4800.8 2215.26  4808.6 2213.64
  4815.1 2214.42  4829.5 2209.88  4836.0 2210.41  4843.8 2207.50  4850.3 2206.80
  4864.6 2201.29  4886.7 2197.93  4893.3 2196.16  4899.8 2195.69  4922.0 2187.09
  4957.1 2185.66  4989.9 2180.84  4990.2 2180.34  4994.7 2180.84  5003.5 2183.62
  5059.0 2187.03  5080.9 2192.21  5104.8 2195.97  5181.0 2198.08  5267.4 2199.18
  5297.7 2201.48  5302.9 2201.00  5308.1 2203.09  5318.5 2205.68  5362.7 2210.67
#Mann=3,-1,0
  4780.7    0.16       0  4989.9    0.07       0  4994.7    0.16       0
Bank Sta=4989.9,4994.7
Exp/Cntr=0.3,0.1

Type RM Length L Ch R = 1,12478,185,185,185
BEGIN DESCRIPTION:
Pleasant Run 12477.52
END DESCRIPTION:
XS GIS Cut Line= 3
      1519295.49      6762895.45      1519516.86      6762780.86
      1519795.47      6762547.81
#Sta/Elev= 30
  4755.8 2212.34  4954.6 2195.38  4969.2 2191.54  4998.9 2177.89  5017.4 2177.15
  5017.7 2176.65  5022.2 2177.15  5034.1 2177.78  5069.2 2191.80  5140.8 2191.03
  5190.2 2193.66  5198.0 2192.66  5204.5 2193.80  5218.8 2191.96  5225.4 2195.17
  5233.2 2193.74  5239.7 2198.16  5247.5 2196.30  5254.0 2200.41  5261.8 2198.96
  5268.3 2203.84  5276.1 2201.69  5282.6 2206.56  5296.9 2205.75  5303.4 2210.16
  5311.2 2210.59  5317.8 2214.55  5325.5 2215.67  5332.1 2218.66  5368.3 2225.26
#Mann=3,-1,0
  4755.8    0.16       0  5017.4    0.07       0  5022.2    0.16       0
Bank Sta=5017.4,5022.2
Exp/Cntr=0.3,0.1

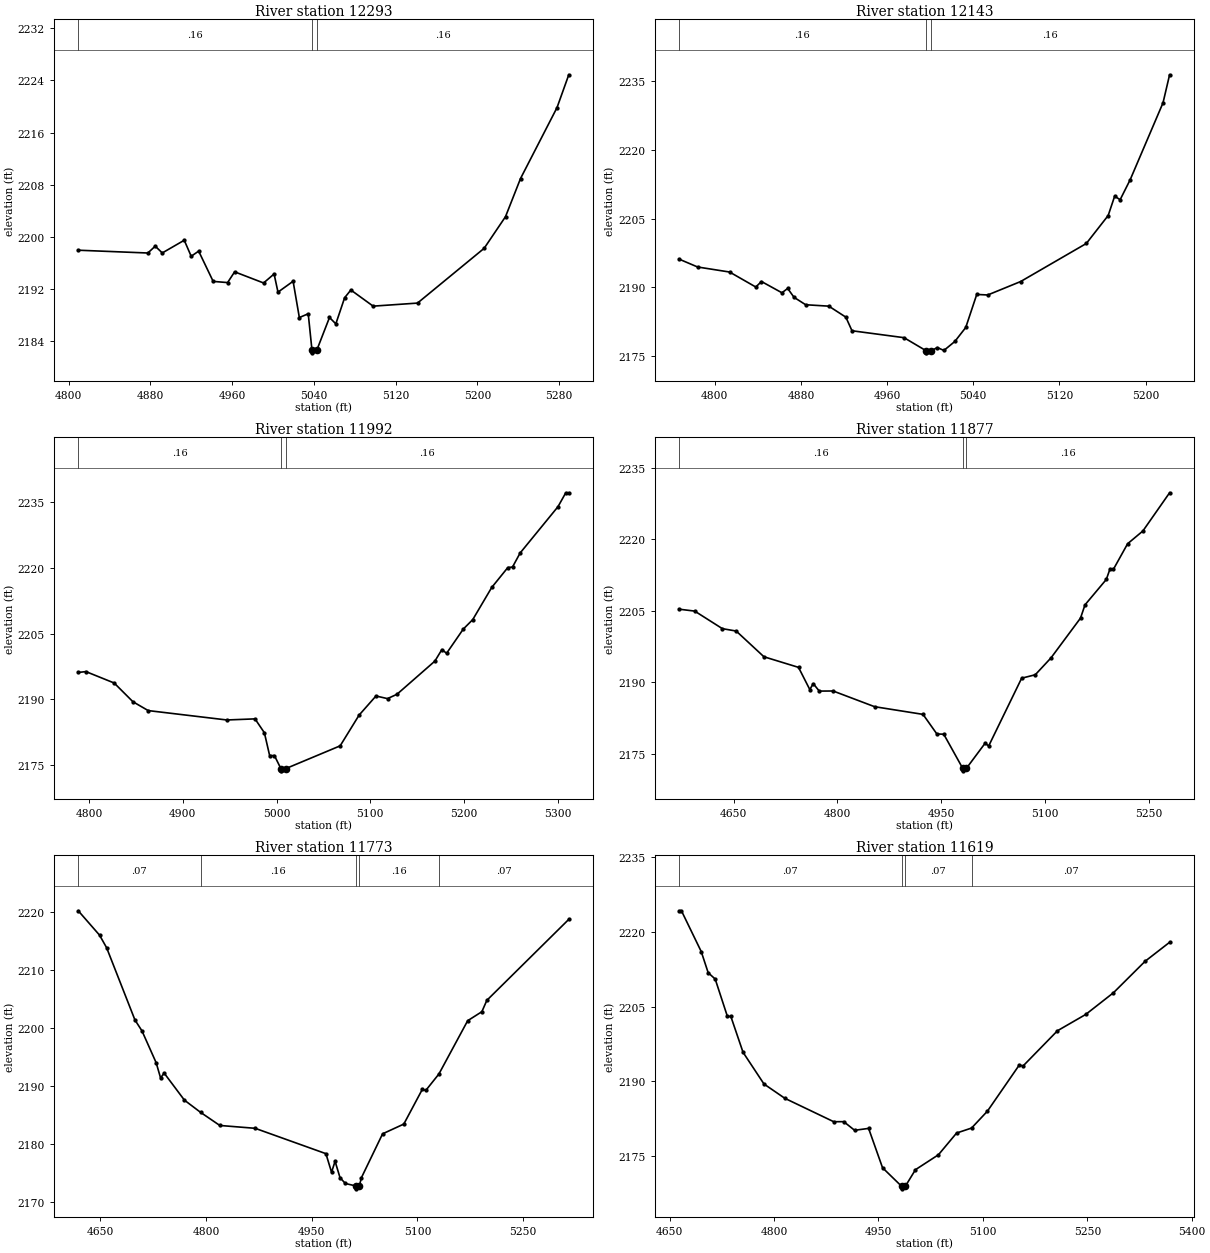
Type RM Length L Ch R = 1,12293,150,150,150
BEGIN DESCRIPTION:
Pleasant Run 12293.25
END DESCRIPTION:
XS GIS Cut Line= 3
      1519546.78      6762976.20      1519678.32      6762836.85
      1519845.63      6762602.10
#Sta/Elev= 30
  4809.5 2197.93  4877.6 2197.50  4884.8 2198.55  4891.7 2197.51  4913.2 2199.46
  4920.0 2197.00  4927.3 2197.79  4941.5 2193.14  4955.6 2192.96  4962.5 2194.61
  4990.8 2192.90  5001.1 2194.28  5004.9 2191.49  5019.7 2193.16  5025.8 2187.59
  5034.5 2188.17  5038.1 2182.67  5038.4 2182.17  5043.1 2182.67  5055.3 2187.60
  5061.5 2186.62  5070.1 2190.63  5076.2 2191.82  5098.0 2189.34  5141.4 2189.81
  5206.6 2198.22  5227.5 2203.08  5242.2 2208.94  5277.9 2219.83  5289.4 2224.87
#Mann=3,-1,0
  4809.5    0.16       0  5038.1    0.07       0  5043.1    0.16       0
Bank Sta=5038.1,5043.1
Exp/Cntr=0.3,0.1

Type RM Length L Ch R = 1,12143,151,151,151
BEGIN DESCRIPTION:
Pleasant Run 12143.35
END DESCRIPTION:
XS GIS Cut Line= 3
      1519585.86      6762980.08      1519802.02      6762894.14
      1520021.05      6762853.96
#Sta/Elev= 30
  4766.9 2196.15  4784.1 2194.43  4813.8 2193.33  4838.1 2190.06  4843.4 2191.26
  4862.4 2188.80  4867.7 2189.75  4873.6 2187.81  4884.4 2186.19  4905.9 2185.88
  4921.7 2183.48  4927.4 2180.51  4975.7 2179.00  4995.9 2176.19  4996.3 2175.69
  5001.0 2176.19  5006.7 2176.84  5012.7 2176.21  5022.9 2178.18  5033.0 2181.23
  5043.2 2188.44  5053.4 2188.32  5083.9 2191.25  5144.9 2199.56  5165.2 2205.67
  5171.2 2209.88  5176.3 2209.12  5185.6 2213.47  5216.1 2230.27  5222.2 2236.39
#Mann=3,-1,0
  4766.9    0.16       0  4995.9    0.07       0  5001.0    0.16       0
Bank Sta=4995.9,5001
Exp/Cntr=0.3,0.1

Type RM Length L Ch R = 1,11992,115,115,115
BEGIN DESCRIPTION:
Pleasant Run 11992.4
END DESCRIPTION:
XS GIS Cut Line= 3
      1519546.78      6763019.14      1519751.24      6763029.55
      1520066.34      6762983.98
#Sta/Elev= 30
  4788.5 2196.15  4796.7 2196.34  4826.8 2193.74  4846.8 2189.47  4863.1 2187.45
  4946.9 2185.31  4977.0 2185.56  4987.0 2182.39  4992.6 2177.19  4997.7 2177.19
  5004.6 2174.21  5005.0 2173.71  5009.7 2174.21  5067.8 2179.41  5088.0 2186.42
  5106.0 2190.78  5118.3 2190.18  5128.4 2191.17  5168.8 2198.73  5176.3 2201.37
  5181.3 2200.51  5199.1 2206.04  5209.2 2208.20  5229.4 2215.52  5246.6 2220.07
  5251.6 2220.19  5259.7 2223.38  5300.1 2233.95  5308.4 2237.12  5311.6 2237.12
#Mann=3,-1,0
  4788.5    0.16       0  5004.6    0.07       0  5009.7    0.16       0
Bank Sta=5004.6,5009.7
Exp/Cntr=0.3,0.1

Type RM Length L Ch R = 1,11877,104,104,104
BEGIN DESCRIPTION:
Pleasant Run 11877.46
END DESCRIPTION:
XS GIS Cut Line= 3
      1519372.38      6763137.63      1519800.72      6763127.21
      1520074.11      6763063.42
#Sta/Elev= 30
  4571.0 2205.32  4593.6 2204.92  4633.6 2201.24  4653.6 2200.74  4693.7 2195.35
  4743.7 2193.13  4760.0 2188.48  4765.0 2189.72  4773.7 2188.16  4793.7 2188.18
  4853.7 2184.89  4923.7 2183.28  4943.7 2179.18  4953.7 2179.12  4981.2 2171.95
  4981.6 2171.45  4986.3 2171.95  5013.5 2177.24  5018.6 2176.65  5066.3 2190.86
  5086.0 2191.58  5108.8 2195.13  5151.4 2203.45  5157.9 2206.23  5188.7 2211.55
  5193.9 2213.70  5199.1 2213.71  5219.5 2219.03  5241.6 2221.71  5280.2 2229.71
#Mann=3,-1,0
  4571.0    0.16       0  4981.2    0.07       0  4986.3    0.16       0
Bank Sta=4981.2,4986.3
Exp/Cntr=0.3,0.1

Type RM Length L Ch R = 1,11773,154,154,154
BEGIN DESCRIPTION:
Pleasant Run 11772.87
END DESCRIPTION:
XS GIS Cut Line= 3
      1519374.92      6763232.68      1519755.14      6763201.43
      1520067.61      6763235.28
#Sta/Elev= 30
  4618.8 2220.24  4649.0 2216.04  4659.0 2213.88  4699.2 2201.43  4709.2 2199.54
  4729.3 2194.06  4735.6 2191.43  4740.6 2192.28  4769.4 2187.61  4792.3 2185.51
  4819.6 2183.25  4869.7 2182.76  4970.1 2178.39  4978.1 2175.19  4983.1 2177.08
  4990.1 2174.26  4997.7 2173.25  5012.5 2172.83  5012.9 2172.33  5017.6 2172.83
  5020.3 2174.21  5050.5 2181.81  5080.6 2183.49  5106.8 2189.46  5111.8 2189.29
  5130.4 2192.12  5171.2 2201.30  5191.3 2202.85  5198.4 2204.81  5314.6 2218.76
#Mann=5,-1,0
  4618.8    0.07       0  4792.3    0.16       0  5012.5    0.07       0
  5017.6    0.16       0  5130.4    0.07       0
Bank Sta=5012.5,5017.6
Exp/Cntr=0.3,0.1

Type RM Length L Ch R = 1,11619,133,133,133
BEGIN DESCRIPTION:
Pleasant Run 11619.35
END DESCRIPTION:
XS GIS Cut Line= 3
      1519363.24      6763318.62      1519704.36      6763339.45
      1520065.06      6763299.08
#Sta/Elev= 30
  4663.5 2224.20  4666.9 2224.20  4695.3 2216.03  4705.3 2211.78  4715.4 2210.51
  4732.9 2203.03  4737.9 2203.00  4755.4 2195.82  4785.5 2189.46  4815.5 2186.59
  4885.7 2181.90  4900.1 2181.91  4915.7 2180.18  4935.8 2180.56  4955.8 2172.67
  4983.3 2168.94  4983.7 2168.44  4988.5 2168.94  5003.1 2172.28  5036.1 2175.27
  5062.2 2179.63  5083.7 2180.63  5106.5 2184.02  5152.5 2193.32  5157.5 2193.05
  5207.1 2200.14  5247.7 2203.41  5287.6 2207.77  5333.0 2214.07  5368.2 2217.88
#Mann=4,-1,0
  4663.5    0.07       0  4983.3    0.07       0  4988.5    0.07       0
  5083.7    0.07       0
Bank Sta=4983.3,4988.5
Exp/Cntr=0.3,0.1

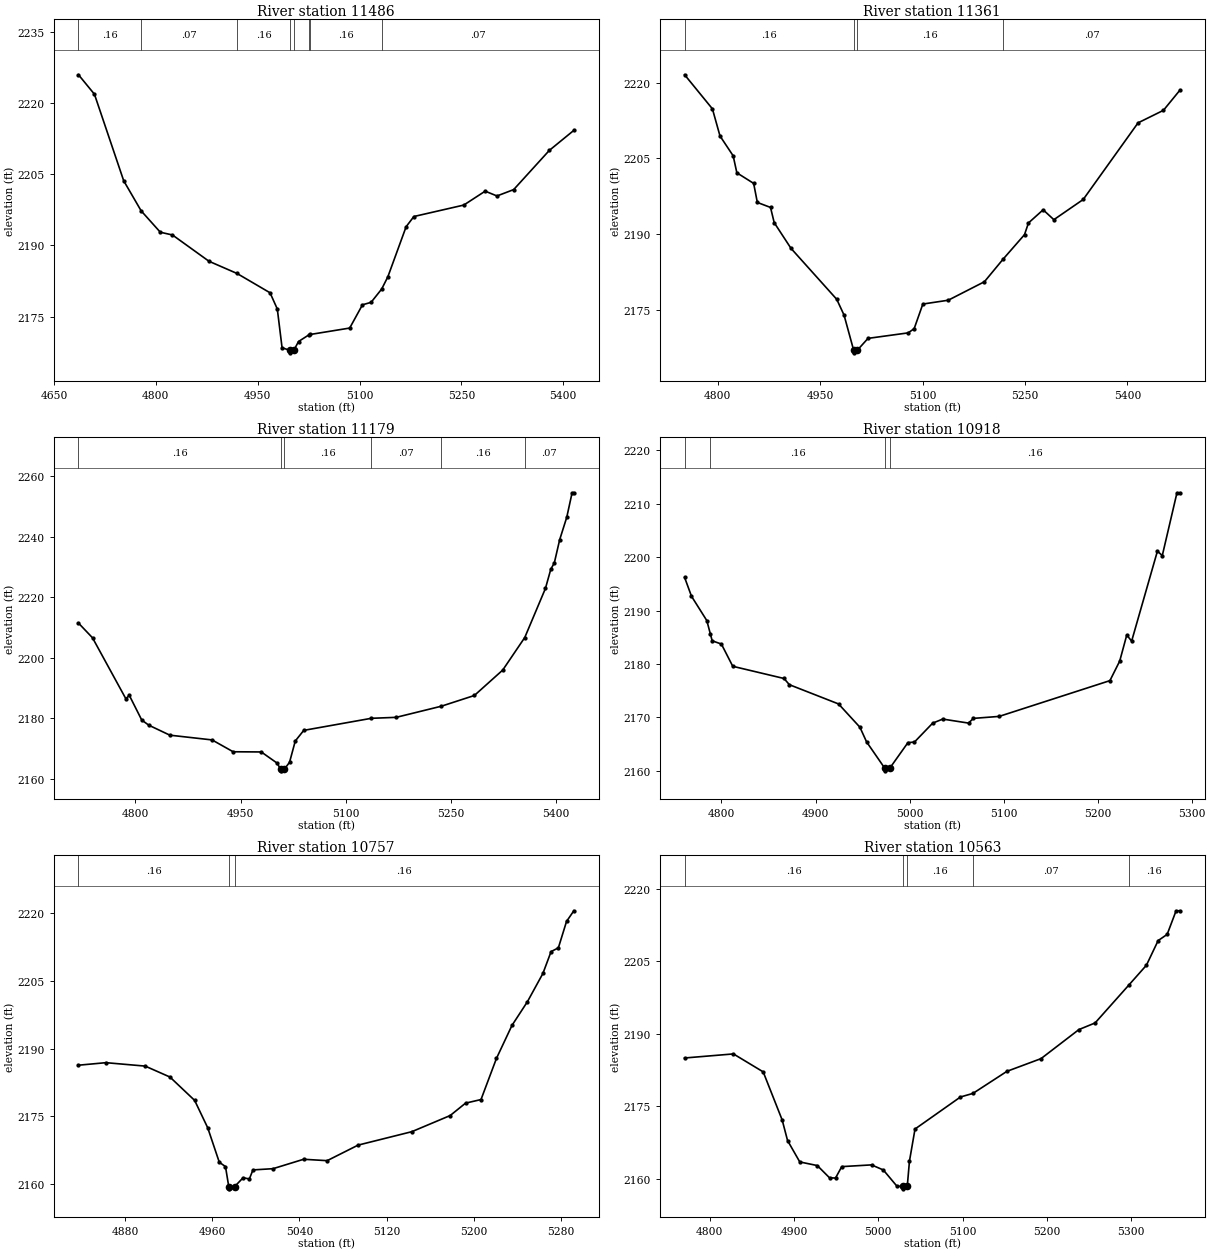
Type RM Length L Ch R = 1,11486,125,125,125
BEGIN DESCRIPTION:
Pleasant Run 11485.59
END DESCRIPTION:
XS GIS Cut Line= 3
      1519363.18      6763575.14      1519691.34      6763443.62
      1520049.41      6763329.03
#Sta/Elev= 30
  4686.1 2225.94  4709.6 2221.84  4752.7 2203.60  4778.4 2197.27  4806.6 2192.77
  4824.5 2192.19  4878.3 2186.65  4919.6 2184.08  4968.2 2180.01  4978.9 2176.59
  4985.9 2168.44  4997.9 2167.86  4998.3 2167.36  5003.1 2167.86  5010.1 2169.74
  5024.9 2171.10  5027.4 2171.23  5085.5 2172.58  5104.3 2177.48  5117.0 2178.00
  5132.6 2180.80  5141.7 2183.38  5168.6 2193.93  5180.0 2196.08  5253.5 2198.49
  5285.0 2201.42  5302.4 2200.41  5327.0 2201.75  5379.5 2210.01  5415.6 2214.23
#Mann=8,-1,0
  4686.1    0.16       0  4778.4    0.07       0  4919.6    0.16       0
  4997.9    0.07       0  5003.1    0.16       0  5024.9    0.07       0
  5027.4    0.16       0  5132.6    0.07       0
Bank Sta=4997.9,5003.1
Exp/Cntr=0.3,0.1

Type RM Length L Ch R = 1,11361,182,182,182
BEGIN DESCRIPTION:
Pleasant Run 11360.85
END DESCRIPTION:
XS GIS Cut Line= 3
      1519457.00      6763659.75      1519691.34      6763569.92
      1520101.42      6763331.14
#Sta/Elev= 30
  4751.6 2221.59  4792.3 2214.83  4803.4 2209.45  4822.7 2205.51  4828.1 2202.14
  4852.7 2200.04  4858.1 2196.26  4877.4 2195.27  4882.8 2192.25  4907.4 2187.15
  4974.4 2177.04  4985.1 2173.91  4999.2 2166.92  4999.6 2166.42  5004.4 2166.92
  5020.2 2169.29  5079.0 2170.38  5087.8 2171.22  5100.5 2176.10  5137.7 2176.86
  5190.7 2180.53  5218.0 2185.00  5249.4 2189.87  5255.2 2192.19  5276.7 2194.80
  5292.4 2192.84  5335.4 2196.85  5415.7 2212.05  5452.9 2214.54  5477.1 2218.55
#Mann=4,-1,0
  4751.6    0.16       0  4999.2    0.07       0  5004.4    0.16       0
  5218.0    0.07       0
Bank Sta=4999.2,5004.4
Exp/Cntr=0.3,0.1

Type RM Length L Ch R = 1,11179,261,261,261
BEGIN DESCRIPTION:
Pleasant Run 11179.168
END DESCRIPTION:
XS GIS Cut Line= 3
      1519555.01      6763688.00      1519835.59      6763667.87
      1520254.97      6763737.99
#Sta/Elev= 30
  4718.7 2211.44  4738.7 2206.57  4786.2 2186.43  4791.2 2187.52  4808.9 2179.37
  4818.9 2177.67  4849.0 2174.36  4909.2 2172.79  4939.3 2168.87  4979.4 2168.81
  5002.2 2165.08  5006.9 2163.06  5007.3 2162.56  5012.1 2163.06  5019.7 2165.38
  5027.9 2172.44  5040.0 2175.95  5136.3 2179.94  5171.8 2180.26  5236.2 2183.94
  5283.3 2187.49  5323.8 2195.91  5355.2 2206.67  5384.7 2222.92  5392.3 2229.24
  5397.4 2231.40  5405.0 2239.04  5415.1 2246.46  5422.7 2254.56  5425.2 2254.56
#Mann=6,-1,0
  4718.7    0.16       0  5006.9    0.07       0  5012.1    0.16       0
  5136.3    0.07       0  5236.2    0.16       0  5355.2    0.07       0
Bank Sta=5006.9,5012.1
Exp/Cntr=0.3,0.1

Type RM Length L Ch R = 1,10918,161,161,161
BEGIN DESCRIPTION:
Pleasant Run 10918.08
END DESCRIPTION:
XS GIS Cut Line= 3
      1519640.54      6764004.82      1519852.80      6763891.53
      1520126.20      6763806.91
#Sta/Elev= 30
  4760.8 2196.18  4768.1 2192.67  4784.4 2188.12  4788.1 2185.67  4790.1 2184.34
  4799.9 2183.73  4812.0 2179.57  4866.5 2177.29  4872.2 2176.13  4924.5 2172.53
  4947.2 2168.18  4954.3 2165.44  4973.6 2160.52  4974.1 2160.02  4979.0 2160.52
  4998.3 2165.30  5005.2 2165.40  5024.6 2168.94  5035.3 2169.70  5062.7 2168.95
  5067.9 2169.83  5095.3 2170.20  5213.1 2176.89  5223.5 2180.54  5231.0 2185.41
  5236.2 2184.28  5263.6 2201.10  5268.8 2200.28  5284.4 2212.02  5287.6 2212.02
#Mann=4,-1,0
  4760.8    0.07       0  4788.1    0.16       0  4973.6    0.07       0
  4979.0    0.16       0
Bank Sta=4973.6,4979
Exp/Cntr=0.3,0.1

Type RM Length L Ch R = 1,10757,194,194,194
BEGIN DESCRIPTION:
Pleasant Run 10756.65
END DESCRIPTION:
XS GIS Cut Line= 3
      1519846.30      6764151.93      1519923.11      6764008.72
      1520139.71      6763812.75
#Sta/Elev= 30
  4837.2 2186.32  4862.4 2186.88  4898.4 2186.12  4921.1 2183.70  4943.8 2178.51
  4955.8 2172.43  4966.4 2164.80  4972.1 2163.82  4975.1 2159.39  4975.5 2158.89
  4980.5 2159.39  4988.3 2161.36  4994.0 2161.08  4997.3 2163.09  5015.7 2163.36
  5043.8 2165.45  5065.4 2165.14  5093.8 2168.59  5143.1 2171.57  5178.3 2175.15
  5192.4 2177.90  5206.6 2178.70  5220.8 2187.84  5235.0 2195.14  5249.2 2200.41
  5263.4 2206.67  5270.9 2211.52  5277.6 2212.36  5285.1 2218.22  5291.8 2220.58
#Mann=3,-1,0
  4837.2    0.16       0  4975.1    0.07       0  4980.5    0.16       0
Bank Sta=4975.1,4980.5
Exp/Cntr=0.3,0.1

Type RM Length L Ch R = 1,10563,194,194,194
BEGIN DESCRIPTION:
Pleasant Run 10563.34
END DESCRIPTION:
XS GIS Cut Line= 3
      1519873.63      6764177.99      1520059.83      6764033.46
      1520389.26      6763909.76
#Sta/Elev= 30
  4770.2 2185.01  4828.1 2185.85  4863.4 2182.14  4885.9 2172.21  4892.3 2167.95
  4906.8 2163.53  4927.6 2162.78  4942.1 2160.25  4949.2 2160.20  4956.6 2162.56
  4991.9 2162.92  5005.9 2161.87  5022.1 2158.51  5028.9 2158.47  5029.3 2157.97
  5034.3 2158.47  5036.9 2163.70  5043.5 2170.33  5097.4 2176.95  5112.2 2177.69
  5152.5 2182.25  5193.0 2184.88  5237.9 2190.88  5257.1 2192.25  5296.9 2200.03
  5318.0 2204.18  5331.9 2209.27  5342.6 2210.55  5353.2 2215.43  5357.8 2215.43
#Mann=5,-1,0
  4770.2    0.16       0  5028.9    0.07       0  5034.3    0.16       0
  5112.2    0.07       0  5296.9    0.16       0
Bank Sta=5028.9,5034.3
Exp/Cntr=0.3,0.1

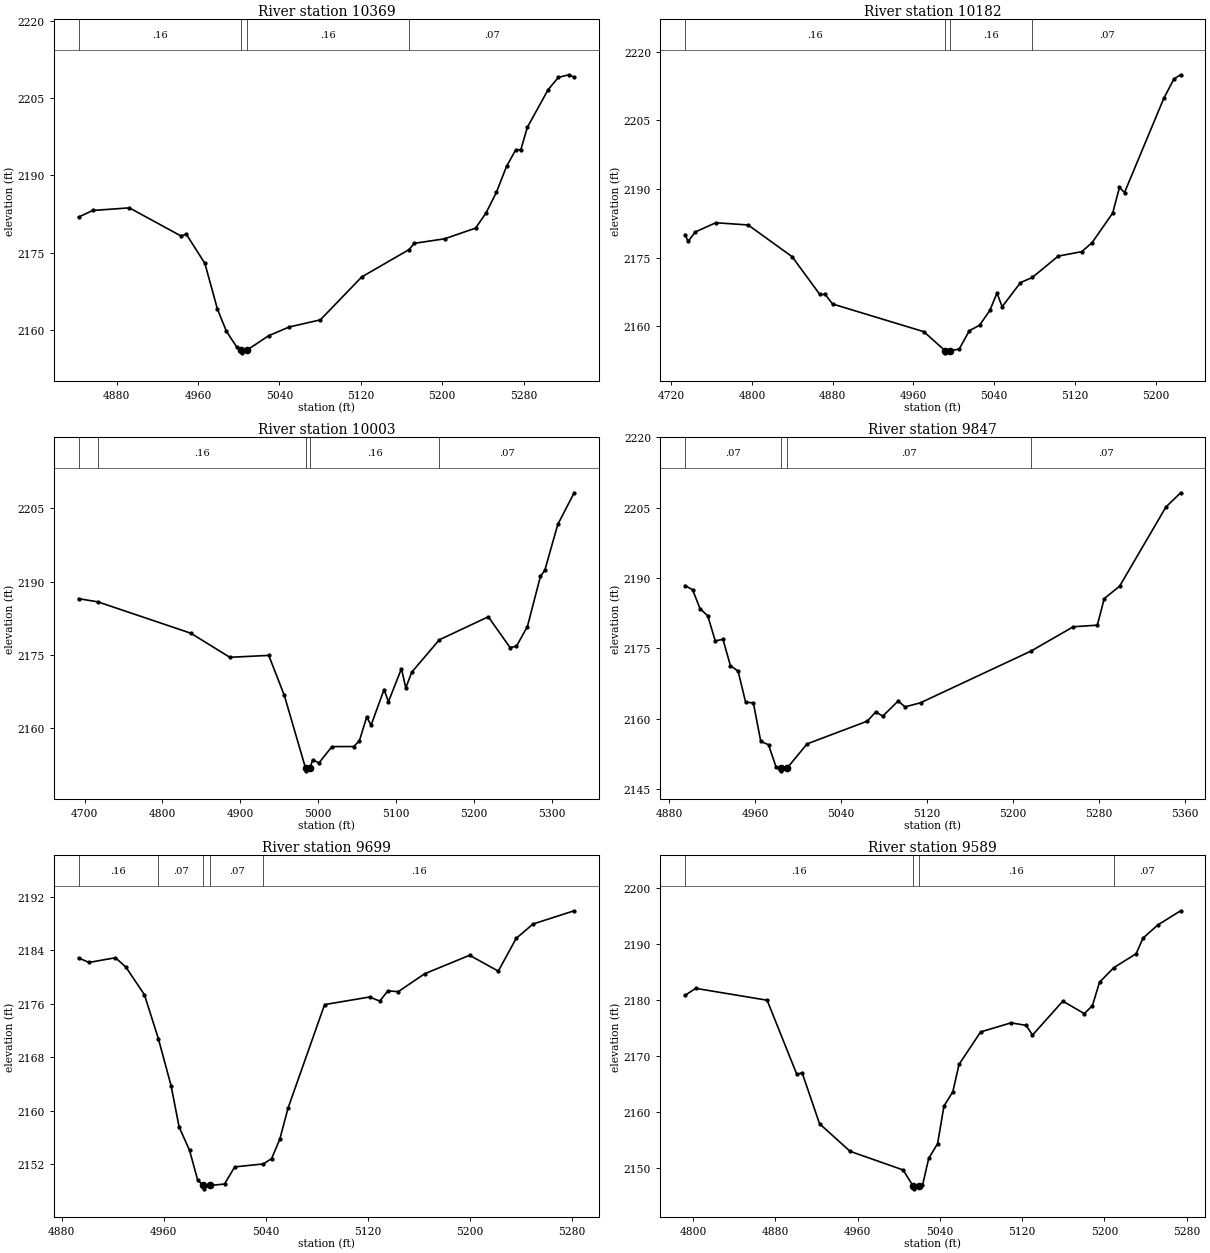
Type RM Length L Ch R = 1,10369,187,187,187
BEGIN DESCRIPTION:
Pleasant Run 10368.9
END DESCRIPTION:
XS GIS Cut Line= 3
      1519958.26      6764248.31      1520109.31      6764193.62
      1520430.20      6764133.05
#Sta/Elev= 30
  4842.6 2181.93  4856.6 2183.21  4892.6 2183.72  4943.2 2178.28  4948.6 2178.59
  4966.8 2172.96  4979.2 2164.06  4988.0 2159.79  4998.3 2156.70  5002.6 2156.12
  5003.0 2155.62  5008.0 2156.12  5029.4 2158.93  5049.7 2160.63  5080.3 2162.01
  5121.0 2170.33  5167.5 2175.63  5172.6 2176.84  5202.4 2177.72  5232.9 2179.79
  5243.1 2182.71  5253.3 2186.70  5263.4 2191.79  5272.3 2194.94  5277.4 2195.01
  5283.8 2199.34  5304.2 2206.62  5314.3 2209.01  5324.5 2209.51  5329.8 2209.05
#Mann=4,-1,0
  4842.6    0.16       0  5002.6    0.07       0  5008.0    0.16       0
  5167.5    0.07       0
Bank Sta=5002.6,5008
Exp/Cntr=0.3,0.1

Type RM Length L Ch R = 1,10182,179,179,179
BEGIN DESCRIPTION:
Pleasant Run 10181.7
END DESCRIPTION:
XS GIS Cut Line= 3
      1519945.24      6764262.62      1520197.85      6764340.75
      1520421.51      6764303.26
#Sta/Elev= 30
  4733.6 2180.08  4736.7 2178.58  4743.8 2180.64  4764.1 2182.66  4796.2 2182.17
  4839.8 2175.24  4867.2 2167.00  4872.5 2167.01  4879.9 2164.91  4970.3 2158.86
  4991.2 2154.74  4991.6 2154.24  4996.7 2154.74  5005.3 2155.04  5015.4 2159.07
  5025.5 2160.27  5035.7 2163.49  5042.8 2167.31  5047.9 2164.31  5066.1 2169.58
  5077.8 2170.71  5103.5 2175.37  5126.9 2176.35  5137.1 2178.33  5157.4 2184.75
  5164.2 2190.38  5169.2 2189.26  5208.1 2209.83  5218.2 2214.08  5224.8 2214.98
#Mann=4,-1,0
  4733.6    0.16       0  4991.2    0.07       0  4996.7    0.16       0
  5077.8    0.07       0
Bank Sta=4991.2,4996.7
Exp/Cntr=0.3,0.1

Type RM Length L Ch R = 1,10003,156,156,156
BEGIN DESCRIPTION:
Pleasant Run 10002.7
END DESCRIPTION:
XS GIS Cut Line= 3
      1519800.76      6764485.28      1520102.80      6764485.28
      1520401.16      6764334.80
#Sta/Elev= 30
  4692.2 2186.50  4716.9 2185.85  4836.4 2179.42  4886.4 2174.49  4936.4 2174.88
  4956.4 2166.67  4983.7 2151.74  4984.1 2151.24  4989.2 2151.74  4992.8 2153.51
  5000.8 2152.86  5017.5 2156.20  5045.4 2156.22  5052.7 2157.38  5062.1 2162.27
  5067.7 2160.58  5084.4 2167.89  5090.0 2165.39  5106.7 2172.15  5112.3 2168.22
  5119.9 2171.44  5155.3 2178.07  5218.2 2182.79  5246.1 2176.49  5254.3 2176.75
  5268.4 2180.79  5285.1 2191.07  5290.7 2192.30  5307.4 2201.71  5328.4 2208.18
#Mann=5,-1,0
  4692.2    0.07       0  4716.9    0.16       0  4983.7    0.07       0
  4989.2    0.16       0  5155.3    0.07       0
Bank Sta=4983.7,4989.2
Exp/Cntr=0.3,0.1

Type RM Length L Ch R = 1,9847,148,148,148
BEGIN DESCRIPTION:
Pleasant Run 9846.968
END DESCRIPTION:
XS GIS Cut Line= 3
      1520104.99      6764688.01      1520181.16      6764615.15
      1520405.03      6764337.96
#Sta/Elev= 30
  4894.6 2188.41  4901.7 2187.52  4908.6 2183.49  4915.8 2181.96  4922.8 2176.61
  4930.0 2176.94  4936.9 2171.36  4944.1 2170.14  4951.1 2163.54  4958.3 2163.39
  4965.2 2155.18  4972.4 2154.48  4979.4 2149.75  4983.9 2149.41  4984.3 2148.91
  4989.4 2149.41  5008.4 2154.66  5064.4 2159.50  5072.4 2161.49  5078.8 2160.56
  5093.2 2163.80  5099.6 2162.54  5114.0 2163.42  5217.2 2174.47  5256.3 2179.62
  5278.7 2179.96  5285.1 2185.61  5299.5 2188.28  5342.6 2205.15  5356.3 2208.18
#Mann=4,-1,0
  4894.6    0.07       0  4983.9    0.07       0  4989.4    0.07       0
  5217.2    0.07       0
Bank Sta=4983.9,4989.4
Exp/Cntr=0.3,0.1

Type RM Length L Ch R = 1,9699,110,110,110
BEGIN DESCRIPTION:
Pleasant Run 9698.64
END DESCRIPTION:
XS GIS Cut Line= 3
      1520223.92      6764748.29      1520307.23      6764684.50
      1520483.86      6764462.40
#Sta/Elev= 30
  4893.1 2182.84  4901.3 2182.17  4922.1 2182.87  4930.3 2181.46  4944.8 2177.34
  4955.7 2170.78  4965.7 2163.75  4972.0 2157.56  4980.2 2154.07  4986.5 2149.68
  4990.7 2148.83  4991.2 2148.33  4996.2 2148.83  5007.6 2149.05  5015.6 2151.61
  5038.0 2152.05  5044.5 2152.84  5050.9 2155.72  5057.4 2160.39  5086.1 2175.87
  5121.3 2177.00  5129.4 2176.39  5135.7 2177.93  5143.8 2177.80  5164.6 2180.48
  5199.8 2183.24  5222.3 2180.87  5236.3 2185.76  5249.5 2187.91  5281.8 2189.89
#Mann=5,-1,0
  4893.1    0.16       0  4955.7    0.07       0  4990.7    0.07       0
  4996.2    0.07       0  5038.0    0.16       0
Bank Sta=4990.7,4996.2
Exp/Cntr=0.3,0.1

Type RM Length L Ch R = 1,9589,112,112,112
BEGIN DESCRIPTION:
Pleasant Run 9588.74
END DESCRIPTION:
XS GIS Cut Line= 3
      1520196.53      6764774.35      1520404.88      6764733.98
      1520624.93      6764577.73
#Sta/Elev= 30
  4792.1 2180.79  4802.5 2182.05  4872.0 2179.93  4900.9 2166.68  4906.0 2166.99
  4923.0 2157.87  4952.7 2152.95  5004.3 2149.62  5014.0 2146.75  5014.4 2146.25
  5019.5 2146.75  5023.1 2146.86  5029.2 2151.70  5037.8 2154.32  5044.0 2161.03
  5052.6 2163.58  5058.7 2168.48  5079.6 2174.26  5109.2 2175.89  5124.0 2175.44
  5130.1 2173.70  5159.6 2179.76  5180.5 2177.54  5188.4 2178.96  5195.3 2183.14
  5209.2 2185.74  5231.0 2188.24  5237.5 2191.00  5251.9 2193.35  5274.2 2195.90
#Mann=4,-1,0
  4792.1    0.16       0  5014.0    0.07       0  5019.5    0.16       0
  5209.2    0.07       0
Bank Sta=5014,5019.5
Exp/Cntr=0.3,0.1