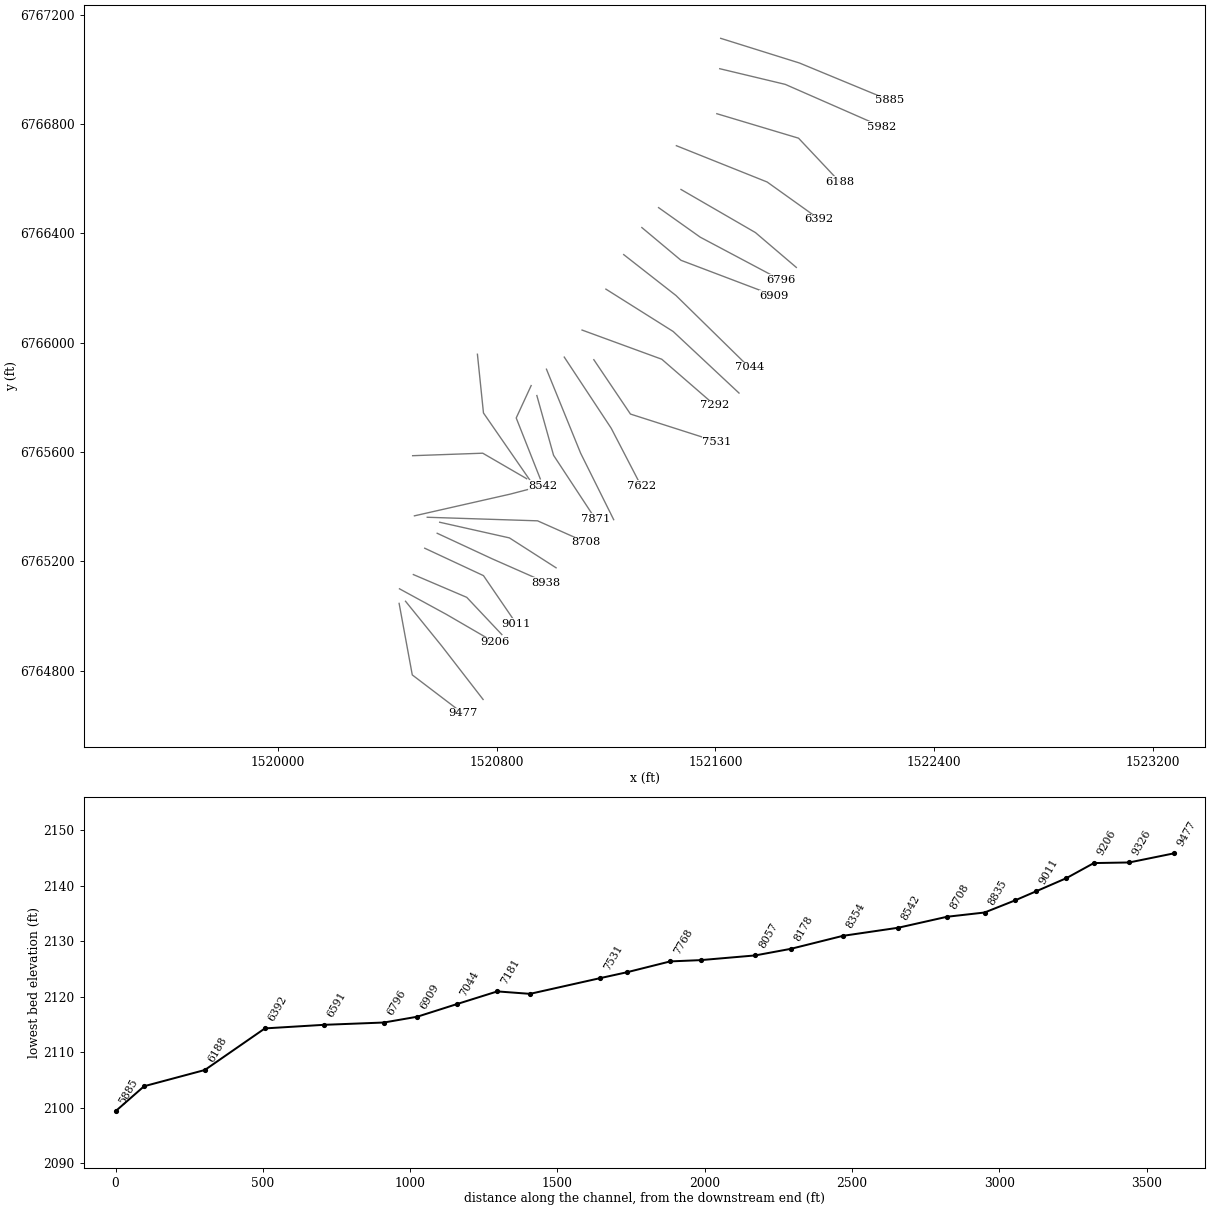
HEC-RAS study Pleasant Run.prj: Pleasant Run Base Level Engineering

--- Pleasant Run.g01 (geometry) --- (continued)

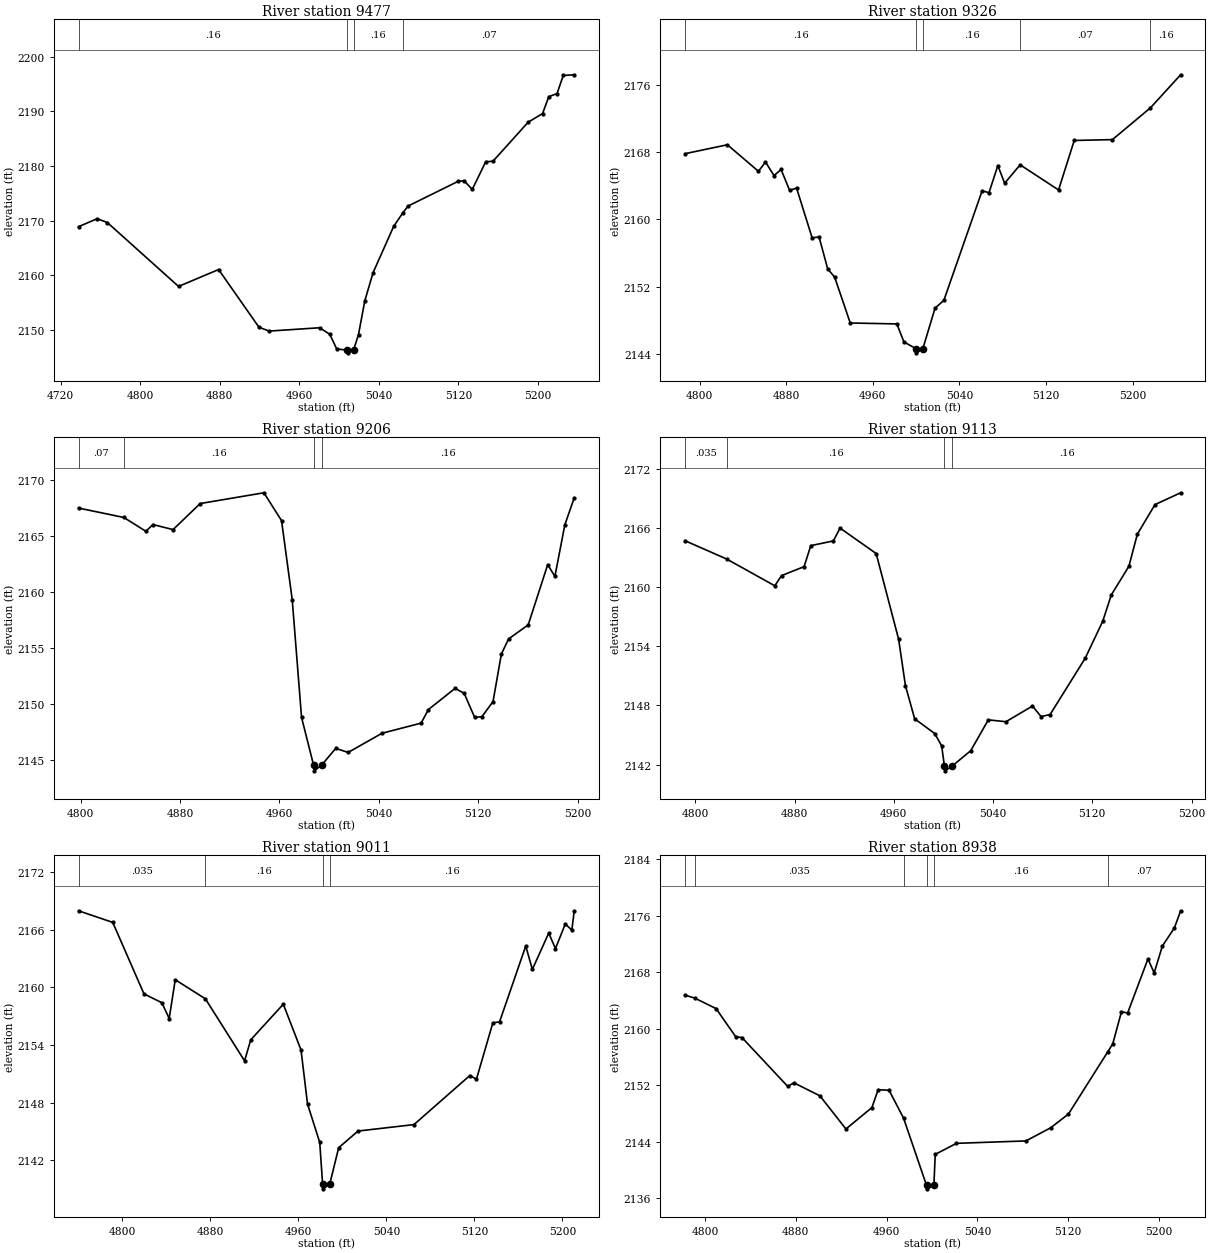
Type RM Length L Ch R = 1,9477,151,151,151
BEGIN DESCRIPTION:
Pleasant Run 9477.49
END DESCRIPTION:
XS GIS Cut Line= 3
      1520442.63      6765046.52      1520490.82      6764784.76
      1520675.75      6764644.11
#Sta/Elev= 30
  4737.9 2168.89  4756.7 2170.35  4766.9 2169.65  4838.5 2157.96  4878.8 2161.05
  4919.4 2150.49  4929.6 2149.79  4980.4 2150.40  4990.6 2149.21  4997.6 2146.52
  5008.1 2146.31  5008.6 2145.81  5014.5 2146.31  5019.5 2149.15  5025.8 2155.30
  5034.1 2160.45  5054.9 2168.96  5064.2 2171.45  5069.4 2172.67  5119.4 2177.16
  5125.6 2177.31  5133.9 2175.71  5147.5 2180.78  5154.7 2180.85  5190.1 2188.00
  5204.6 2189.58  5210.9 2192.69  5219.2 2193.24  5225.4 2196.55  5236.4 2196.68
#Mann=4,-1,0
  4737.9    0.16       0  5008.1    0.07       0  5014.5    0.16       0
  5064.2    0.07       0
Bank Sta=5008.1,5014.5
Exp/Cntr=0.3,0.1

Type RM Length L Ch R = 1,9326,120,120,120
BEGIN DESCRIPTION:
Pleasant Run 9326.14
END DESCRIPTION:
XS GIS Cut Line= 3
      1520466.05      6765054.33      1520598.89      6764890.23
      1520749.92      6764694.94
#Sta/Elev= 30
  4786.4 2167.80  4825.6 2168.86  4854.3 2165.71  4860.8 2166.81  4868.7 2165.20
  4875.2 2165.93  4883.1 2163.44  4889.5 2163.73  4903.9 2157.82  4910.3 2157.92
  4918.3 2154.13  4924.7 2153.16  4939.1 2147.72  4982.2 2147.61  4988.7 2145.47
  4999.8 2144.68  5000.3 2144.18  5006.2 2144.68  5017.5 2149.49  5025.6 2150.40
  5061.0 2163.41  5067.3 2163.17  5075.5 2166.39  5081.8 2164.30  5096.1 2166.48
  5131.6 2163.50  5146.1 2169.37  5181.4 2169.47  5216.5 2173.24  5244.4 2177.16
#Mann=5,-1,0
  4786.4    0.16       0  4999.8    0.07       0  5006.2    0.16       0
  5096.1    0.07       0  5216.5    0.16       0
Bank Sta=4999.8,5006.2
Exp/Cntr=0.3,0.1

Type RM Length L Ch R = 1,9206,93,93,93
BEGIN DESCRIPTION:
Pleasant Run 9206.34
END DESCRIPTION:
XS GIS Cut Line= 3
      1520443.98      6765099.85      1520615.82      6765006.12
      1520791.49      6764904.07
#Sta/Elev= 30
  4798.3 2167.48  4834.8 2166.64  4852.5 2165.41  4858.2 2166.01  4874.4 2165.56
  4896.2 2167.88  4947.5 2168.84  4961.7 2166.36  4970.3 2159.31  4977.8 2148.83
  4987.5 2144.57  4988.0 2144.07  4993.9 2144.57  5005.3 2146.07  5015.3 2145.71
  5042.6 2147.42  5074.0 2148.32  5079.9 2149.53  5101.4 2151.42  5108.7 2150.97
  5117.1 2148.83  5122.9 2148.89  5131.9 2150.24  5138.6 2154.47  5144.4 2155.82
  5160.2 2157.07  5175.9 2162.44  5181.7 2161.39  5189.7 2165.99  5197.2 2168.37
#Mann=4,-1,0
  4798.3    0.07       0  4834.8    0.16       0  4987.5    0.07       0
  4993.9    0.16       0
Bank Sta=4987.5,4993.9
Exp/Cntr=0.3,0.1

Type RM Length L Ch R = 1,9113,102,102,102
BEGIN DESCRIPTION:
Pleasant Run 9112.64
END DESCRIPTION:
XS GIS Cut Line= 3
      1520494.74      6765151.95      1520690.04      6765068.62
      1520818.43      6764932.44
#Sta/Elev= 30
  4791.7 2164.69  4825.2 2162.84  4864.1 2160.12  4869.5 2161.15  4887.7 2162.06
  4893.1 2164.19  4911.3 2164.67  4916.7 2165.97  4945.8 2163.39  4963.9 2154.70
  4969.4 2150.00  4976.8 2146.64  4993.0 2145.14  4998.6 2143.89  5000.8 2141.86
  5001.3 2141.36  5007.2 2141.86  5022.0 2143.40  5036.2 2146.53  5050.4 2146.34
  5071.8 2147.93  5078.7 2146.86  5086.0 2147.07  5114.3 2152.78  5128.4 2156.52
  5135.3 2159.19  5149.5 2162.10  5156.3 2165.35  5170.5 2168.35  5191.2 2169.55
#Mann=4,-1,0
  4791.7   0.035       0  4825.2    0.16       0  5000.8    0.07       0
  5007.2    0.16       0
Bank Sta=5000.8,5007.2
Exp/Cntr=0.3,0.1

Type RM Length L Ch R = 1,9011,73,73,73
BEGIN DESCRIPTION:
Pleasant Run 9010.99
END DESCRIPTION:
XS GIS Cut Line= 3
      1520536.39      6765248.30      1520751.24      6765148.04
      1520871.64      6764971.96
#Sta/Elev= 30
  4760.3 2167.97  4791.4 2166.76  4819.8 2159.31  4836.0 2158.40  4842.7 2156.75
  4848.2 2160.79  4875.6 2158.80  4911.2 2152.34  4916.8 2154.53  4946.4 2158.24
  4962.5 2153.47  4968.4 2147.84  4979.5 2143.85  4982.1 2139.51  4982.6 2139.01
  4988.6 2139.51  4996.7 2143.29  5014.3 2145.03  5065.1 2145.70  5115.9 2150.81
  5121.9 2150.43  5136.8 2156.30  5142.9 2156.40  5166.7 2164.30  5172.7 2161.86
  5187.6 2165.65  5193.7 2164.03  5202.6 2166.59  5208.6 2165.96  5210.7 2167.91
#Mann=4,-1,0
  4760.3   0.035       0  4875.6    0.16       0  4982.1    0.07       0
  4988.6    0.16       0
Bank Sta=4982.1,4988.6
Exp/Cntr=0.3,0.1

Type RM Length L Ch R = 1,8938,103,103,103
BEGIN DESCRIPTION:
Pleasant Run 8937.61
END DESCRIPTION:
XS GIS Cut Line= 3
      1520581.93      6765303.01      1520783.79      6765209.24
      1520979.73      6765122.87
#Sta/Elev= 30
  4782.3 2164.75  4790.8 2164.34  4809.7 2162.85  4827.0 2158.86  4832.5 2158.75
  4872.8 2151.84  4878.3 2152.34  4901.2 2150.50  4924.1 2145.81  4947.0 2148.84
  4952.5 2151.37  4962.1 2151.29  4974.9 2147.34  4995.1 2137.84  4995.6 2137.34
  5001.6 2137.84  5002.8 2142.22  5021.5 2143.78  5082.7 2144.12  5104.6 2145.99
  5120.2 2147.93  5154.7 2156.71  5159.2 2157.86  5166.9 2162.42  5172.3 2162.22
  5190.2 2169.87  5195.7 2167.90  5202.9 2171.70  5213.5 2174.26  5219.0 2176.69
#Mann=6,-1,0
  4782.3    0.16       0  4790.8   0.035       0  4974.9    0.16       0
  4995.1    0.07       0  5001.6    0.16       0  5154.7    0.07       0
Bank Sta=4995.1,5001.6
Exp/Cntr=0.3,0.1

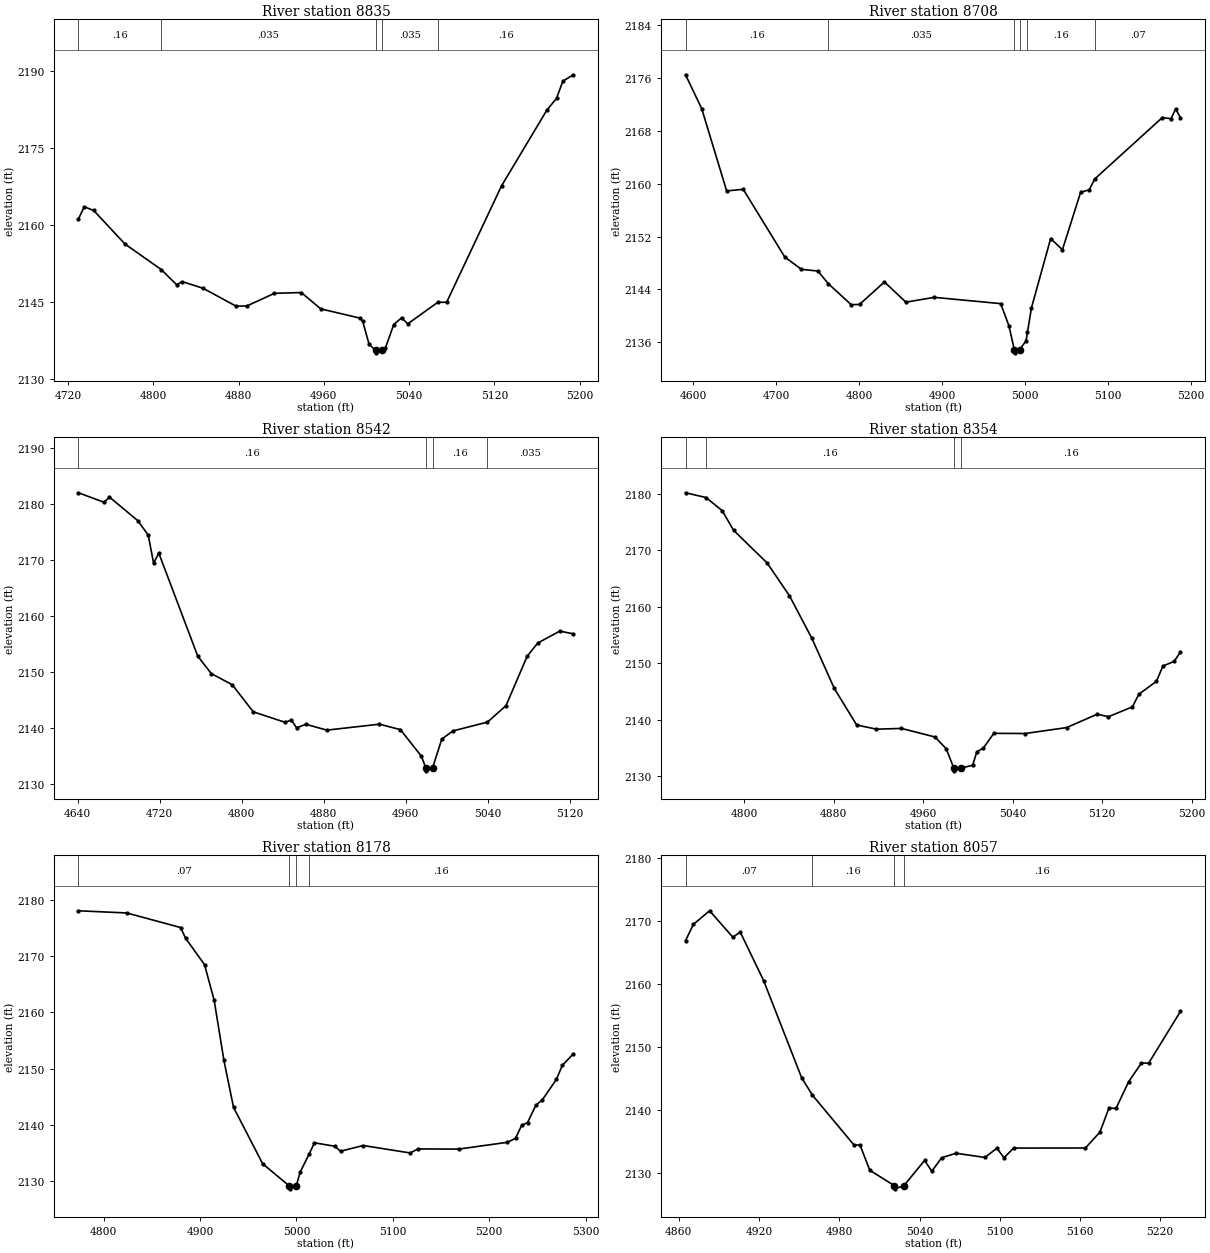
Type RM Length L Ch R = 1,8835,127,127,127
BEGIN DESCRIPTION:
Pleasant Run 8835.18
END DESCRIPTION:
XS GIS Cut Line= 3
      1520591.05      6765343.36      1520846.29      6765286.06
      1521016.85      6765176.70
#Sta/Elev= 30
  4729.9 2161.27  4735.3 2163.64  4744.2 2162.91  4773.5 2156.38  4807.5 2151.41
  4822.0 2148.44  4827.1 2149.05  4846.7 2147.76  4877.4 2144.30  4887.7 2144.29
  4913.7 2146.77  4938.9 2146.92  4957.1 2143.74  4993.7 2141.95  4996.5 2141.30
  5002.5 2136.82  5008.5 2135.67  5009.0 2135.17  5015.0 2135.67  5017.7 2136.07
  5025.6 2140.69  5032.9 2141.99  5038.8 2140.83  5067.0 2145.03  5075.2 2145.02
  5126.7 2167.71  5169.0 2182.40  5178.3 2184.79  5184.2 2188.12  5194.1 2189.36
#Mann=5,-1,0
  4729.9    0.16       0  4807.5   0.035       0  5008.5   0.035       0
  5015.0   0.035       0  5067.0    0.16       0
Bank Sta=5008.5,5015
Exp/Cntr=0.3,0.1

Type RM Length L Ch R = 1,8708,166,166,166
BEGIN DESCRIPTION:
Pleasant Run 8707.8
END DESCRIPTION:
XS GIS Cut Line= 3
      1520545.55      6765361.58      1520949.15      6765348.56
      1521124.96      6765270.43
#Sta/Elev= 30
  4591.1 2176.50  4610.6 2171.36  4640.6 2158.92  4660.6 2159.16  4710.6 2148.92
  4730.6 2147.05  4750.6 2146.79  4762.9 2144.90  4790.7 2141.69  4800.7 2141.74
  4830.7 2145.14  4856.5 2142.08  4890.7 2142.81  4970.7 2141.86  4980.7 2138.49
  4987.1 2134.91  4987.6 2134.41  4993.6 2134.91  5001.3 2136.23  5003.0 2137.54
  5007.7 2141.17  5030.9 2151.70  5045.1 2150.02  5067.0 2158.71  5077.5 2159.10
  5083.9 2160.72  5165.5 2170.03  5175.9 2169.85  5181.4 2171.32  5187.3 2170.03
#Mann=6,-1,0
  4591.1    0.16       0  4762.9   0.035       0  4987.1   0.035       0
  4993.6   0.035       0  5003.0    0.16       0  5083.9    0.07       0
Bank Sta=4987.1,4993.6
Exp/Cntr=0.3,0.1

Type RM Length L Ch R = 1,8542,188,188,188
BEGIN DESCRIPTION:
Pleasant Run 8542.32
END DESCRIPTION:
XS GIS Cut Line= 3
      1520498.59      6765366.78      1520848.89      6765446.22
      1520968.69      6765477.47
#Sta/Elev= 30
  4640.8 2182.02  4665.8 2180.32  4671.0 2181.26  4698.6 2177.06  4708.9 2174.47
  4714.1 2169.47  4719.2 2171.26  4757.2 2152.88  4770.4 2149.78  4790.9 2147.78
  4811.4 2142.95  4842.2 2141.10  4848.6 2141.47  4853.7 2140.10  4862.7 2140.73
  4883.2 2139.69  4934.5 2140.75  4955.0 2139.78  4975.5 2135.03  4979.8 2132.93
  4980.3 2132.43  4986.3 2132.93  4995.4 2138.11  5006.3 2139.55  5039.9 2141.12
  5058.0 2144.05  5078.7 2152.87  5089.0 2155.22  5110.5 2157.35  5123.8 2156.86
#Mann=4,-1,0
  4640.8    0.16       0  4979.8    0.07       0  4986.3    0.16       0
  5039.9   0.035       0
Bank Sta=4979.8,4986.3
Exp/Cntr=0.3,0.1

Type RM Length L Ch R = 1,8354,176,176,176
BEGIN DESCRIPTION:
Pleasant Run 8353.52
END DESCRIPTION:
XS GIS Cut Line= 3
      1520492.11      6765586.84      1520748.63      6765595.96
      1520909.32      6765502.65
#Sta/Elev= 30
  4747.5 2180.15  4765.8 2179.31  4780.4 2176.96  4790.4 2173.52  4820.4 2167.75
  4840.4 2161.94  4860.5 2154.38  4880.5 2145.54  4900.5 2139.08  4918.2 2138.34
  4940.5 2138.47  4970.5 2136.96  4980.5 2134.90  4987.3 2131.47  4987.8 2130.97
  4993.8 2131.47  5004.2 2131.95  5007.9 2134.34  5013.7 2134.98  5023.1 2137.60
  5051.0 2137.57  5088.2 2138.62  5115.6 2140.99  5125.5 2140.54  5147.0 2142.28
  5152.8 2144.52  5168.5 2146.80  5174.3 2149.51  5184.3 2150.32  5190.0 2151.99
#Mann=4,-1,0
  4747.5    0.07       0  4765.8    0.16       0  4987.3    0.07       0
  4993.8    0.16       0
Bank Sta=4987.3,4993.8
Exp/Cntr=0.3,0.1

Type RM Length L Ch R = 1,8178,121,121,121
BEGIN DESCRIPTION:
Pleasant Run 8177.81
END DESCRIPTION:
XS GIS Cut Line= 3
      1520729.10      6765957.97      1520751.24      6765743.10
      1520920.26      6765498.65
#Sta/Elev= 30
  4774.0 2178.05  4824.2 2177.66  4879.9 2175.07  4885.0 2173.19  4904.7 2168.48
  4914.7 2162.15  4924.8 2151.47  4934.8 2143.11  4965.0 2133.10  4992.7 2129.14
  4993.2 2128.64  4999.8 2129.14  5003.9 2131.62  5013.1 2134.80  5018.7 2136.82
  5039.7 2136.21  5045.7 2135.32  5069.2 2136.34  5117.8 2135.02  5126.2 2135.73
  5168.1 2135.70  5218.8 2136.91  5227.2 2137.62  5233.6 2139.94  5239.7 2140.42
  5248.5 2143.57  5254.6 2144.36  5269.5 2148.07  5275.8 2150.60  5287.2 2152.64
#Mann=4,-1,0
  4774.0    0.07       0  4992.7    0.07       0  4999.8    0.07       0
  5013.1    0.16       0
Bank Sta=4992.7,4999.8
Exp/Cntr=0.3,0.1

Type RM Length L Ch R = 1,8057,186,186,186
BEGIN DESCRIPTION:
Pleasant Run 8057.13
END DESCRIPTION:
XS GIS Cut Line= 3
      1520925.70      6765843.32      1520871.03      6765724.87
      1520959.17      6765501.92
#Sta/Elev= 30
  4865.0 2166.85  4870.9 2169.43  4883.0 2171.58  4900.4 2167.38  4905.9 2168.20
  4923.4 2160.50  4951.8 2145.10  4959.9 2142.32  4991.0 2134.41  4995.5 2134.41
  5002.8 2130.40  5021.2 2127.95  5021.7 2127.45  5028.3 2127.95  5043.8 2131.95
  5049.2 2130.25  5056.6 2132.39  5067.4 2133.10  5088.9 2132.43  5097.9 2133.90
  5103.2 2132.38  5110.4 2133.92  5164.1 2133.93  5174.9 2136.44  5181.7 2140.26
  5187.0 2140.22  5196.4 2144.44  5206.0 2147.42  5211.4 2147.39  5235.2 2155.61
#Mann=4,-1,0
  4865.0    0.07       0  4959.9    0.16       0  5021.2    0.07       0
  5028.3    0.16       0
Bank Sta=5021.2,5028.3
Exp/Cntr=0.3,0.1

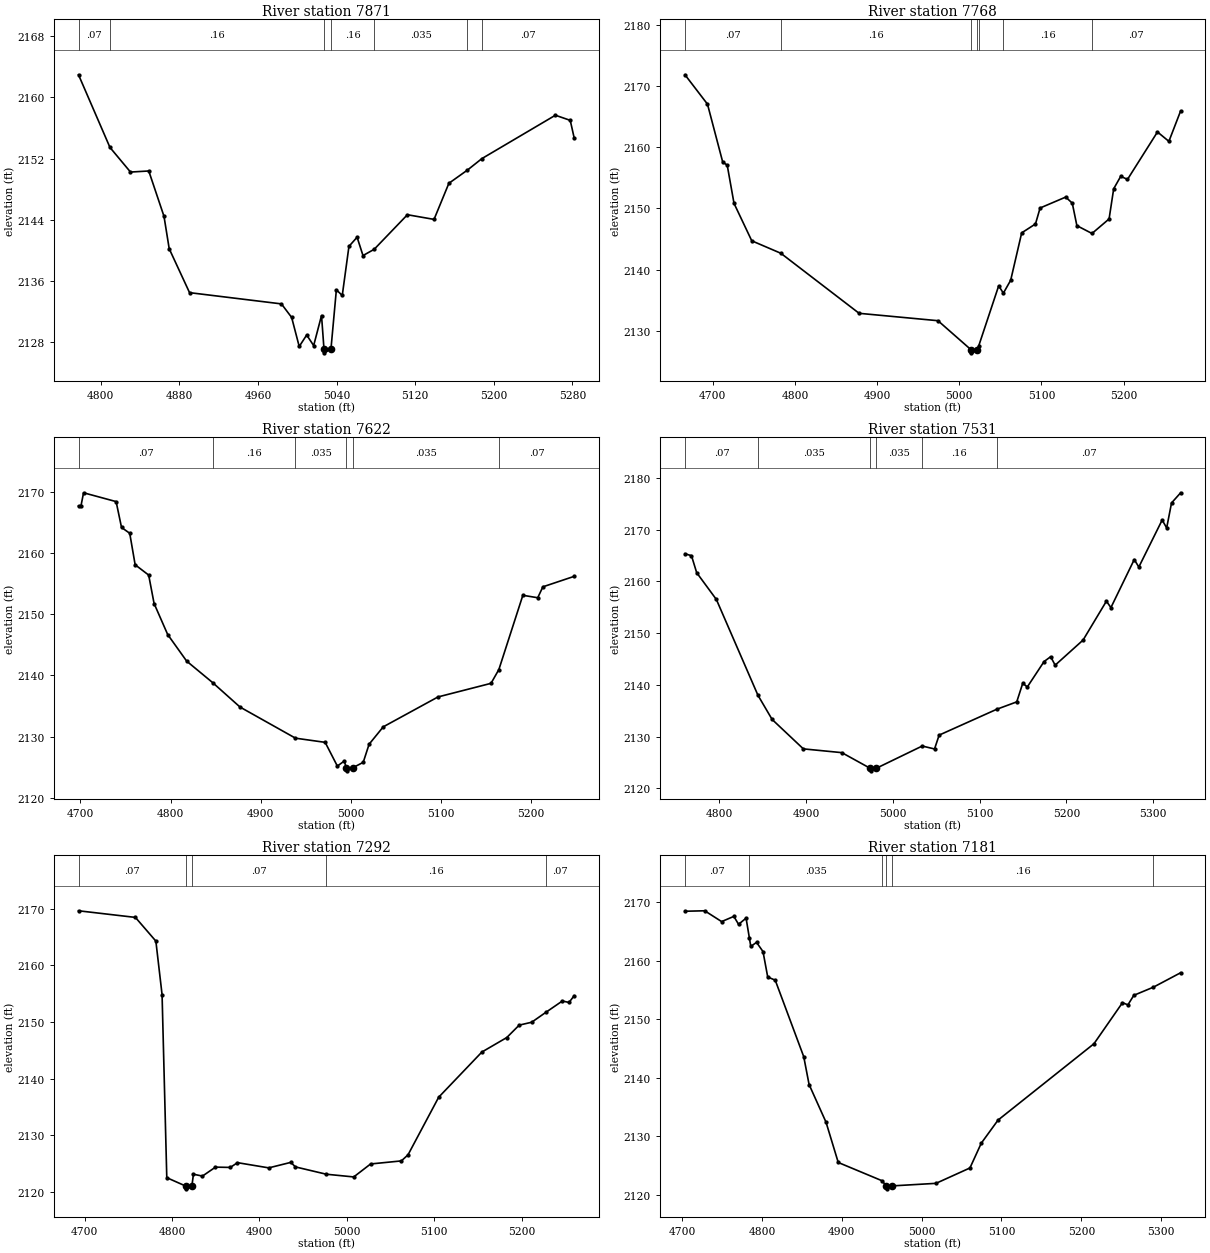
Type RM Length L Ch R = 1,7871,103,103,103
BEGIN DESCRIPTION:
Pleasant Run 7871.08
END DESCRIPTION:
XS GIS Cut Line= 3
      1520946.56      6765806.87      1521007.75      6765588.15
      1521160.05      6765356.44
#Sta/Elev= 30
  4777.3 2162.96  4809.3 2153.46  4830.2 2150.24  4848.8 2150.38  4864.3 2144.45
  4869.6 2140.21  4890.3 2134.47  4983.8 2133.00  4994.2 2131.23  5001.9 2127.43
  5009.5 2128.93  5016.6 2127.55  5024.6 2131.48  5027.1 2127.10  5027.6 2126.60
  5034.2 2127.10  5039.7 2134.84  5045.7 2134.10  5052.5 2140.52  5060.8 2141.72
  5066.8 2139.32  5078.2 2140.14  5112.0 2144.66  5139.1 2144.05  5154.2 2148.77
  5173.1 2150.50  5187.8 2152.00  5262.6 2157.67  5277.7 2157.00  5281.7 2154.71
#Mann=7,-1,0
  4777.3    0.07       0  4809.3    0.16       0  5027.1    0.07       0
  5034.2    0.16       0  5078.2   0.035       0  5173.1    0.16       0
  5187.8    0.07       0
Bank Sta=5027.1,5034.2
Exp/Cntr=0.3,0.1

Type RM Length L Ch R = 1,7768,146,146,146
BEGIN DESCRIPTION:
Pleasant Run 7768.34
END DESCRIPTION:
XS GIS Cut Line= 3
      1520981.69      6765903.29      1521106.70      6765595.96
      1521227.66      6765352.76
#Sta/Elev= 30
  4666.1 2171.89  4693.5 2167.08  4712.1 2157.57  4717.5 2157.11  4725.8 2150.84
  4747.4 2144.71  4782.8 2142.67  4878.1 2132.84  4974.1 2131.63  5014.4 2126.87
  5014.9 2126.37  5021.5 2126.87  5023.8 2127.55  5048.0 2137.34  5053.7 2136.14
  5062.6 2138.25  5076.0 2146.01  5092.8 2147.47  5098.4 2150.08  5129.6 2151.87
  5137.6 2150.87  5143.2 2147.19  5161.6 2145.91  5182.4 2148.29  5188.0 2153.23
  5196.6 2155.27  5204.8 2154.76  5241.3 2162.53  5255.2 2160.99  5269.5 2165.97
#Mann=7,-1,0
  4666.1    0.07       0  4782.8    0.16       0  5014.4    0.07       0
  5021.5    0.16       0  5023.8   0.035       0  5053.7    0.16       0
  5161.6    0.07       0
Bank Sta=5014.4,5021.5
Exp/Cntr=0.3,0.1

Type RM Length L Ch R = 1,7622,91,91,91
BEGIN DESCRIPTION:
Pleasant Run 7621.8
END DESCRIPTION:
XS GIS Cut Line= 3
      1521046.83      6765947.50      1521218.68      6765687.11
      1521328.06      6765476.17
#Sta/Elev= 30
  4698.0 2167.65  4700.7 2167.65  4703.6 2169.81  4739.7 2168.37  4745.7 2164.15
  4754.8 2163.20  4760.8 2158.06  4775.8 2156.38  4781.8 2151.74  4796.9 2146.67
  4817.9 2142.34  4846.8 2138.82  4877.1 2134.84  4938.6 2129.76  4971.5 2129.08
  4985.0 2125.21  4992.6 2126.02  4995.0 2124.93  4995.5 2124.43  5002.1 2124.93
  5013.7 2125.82  5020.2 2128.77  5035.9 2131.61  5096.6 2136.49  5155.4 2138.71
  5164.1 2140.96  5190.7 2153.08  5207.2 2152.68  5212.9 2154.46  5247.6 2156.17
#Mann=6,-1,0
  4698.0    0.07       0  4846.8    0.16       0  4938.6   0.035       0
  4995.0   0.035       0  5002.1   0.035       0  5164.1    0.07       0
Bank Sta=4995,5002.1
Exp/Cntr=0.3,0.1

Type RM Length L Ch R = 1,7531,239,239,239
BEGIN DESCRIPTION:
Pleasant Run 7530.846
END DESCRIPTION:
XS GIS Cut Line= 3
      1521154.99      6765938.02      1521288.98      6765739.15
      1521604.99      6765638.00
#Sta/Elev= 30
  4760.2 2165.36  4767.7 2164.99  4773.7 2161.70  4796.4 2156.52  4844.4 2137.97
  4860.7 2133.31  4896.7 2127.62  4941.1 2126.89  4973.7 2123.87  4974.2 2123.37
  4980.9 2123.87  5033.8 2128.17  5048.0 2127.60  5053.3 2130.28  5119.6 2135.27
  5142.8 2136.71  5149.7 2140.30  5155.0 2139.60  5174.3 2144.51  5181.9 2145.45
  5187.1 2143.81  5219.3 2148.67  5246.2 2156.19  5251.4 2154.95  5278.3 2164.24
  5283.6 2162.80  5310.5 2171.89  5315.7 2170.36  5321.3 2175.19  5331.8 2177.16
#Mann=6,-1,0
  4760.2    0.07       0  4844.4   0.035       0  4973.7   0.035       0
  4980.9   0.035       0  5033.8    0.16       0  5119.6    0.07       0
Bank Sta=4973.7,4980.9
Exp/Cntr=0.3,0.1

Type RM Length L Ch R = 1,7292,111,111,111
BEGIN DESCRIPTION:
Pleasant Run 7292.02
END DESCRIPTION:
XS GIS Cut Line= 3
      1521111.89      6766046.49      1521403.58      6765939.71
      1521597.40      6765771.73
#Sta/Elev= 30
  4693.1 2169.60  4758.2 2168.43  4781.6 2164.25  4788.7 2154.81  4794.1 2122.50
  4815.6 2121.03  4816.1 2120.53  4822.8 2121.03  4824.6 2123.11  4834.9 2122.78
  4849.8 2124.36  4866.8 2124.31  4875.0 2125.15  4910.8 2124.23  4936.0 2125.20
  4941.3 2124.40  4976.6 2123.11  5008.0 2122.63  5027.3 2124.92  5062.5 2125.46
  5070.1 2126.53  5105.2 2136.70  5154.6 2144.67  5183.1 2147.23  5197.3 2149.42
  5211.6 2149.93  5228.2 2151.72  5246.7 2153.68  5254.3 2153.42  5260.2 2154.61
#Mann=5,-1,0
  4693.1    0.07       0  4815.6    0.07       0  4822.8    0.07       0
  4976.6    0.16       0  5228.2    0.07       0
Bank Sta=4815.6,4822.8
Exp/Cntr=0.3,0.1

Type RM Length L Ch R = 1,7181,137,137,137
BEGIN DESCRIPTION:
Pleasant Run 7180.62
END DESCRIPTION:
XS GIS Cut Line= 3
      1521199.15      6766196.22      1521445.25      6766041.27
      1521686.12      6765816.02
#Sta/Elev= 30
  4703.7 2168.45  4728.4 2168.53  4749.6 2166.68  4764.9 2167.57  4770.8 2166.21
  4780.2 2167.27  4784.4 2163.82  4786.1 2162.43  4793.3 2163.13  4801.4 2161.55
  4807.3 2157.20  4816.7 2156.66  4852.4 2143.57  4859.1 2138.81  4880.3 2132.37
  4895.6 2125.48  4950.5 2122.35  4955.6 2121.47  4956.1 2120.97  4962.8 2121.47
  5018.0 2121.91  5060.5 2124.54  5074.7 2128.78  5095.7 2132.73  5215.8 2145.79
  5251.5 2152.81  5258.3 2152.44  5265.7 2154.07  5290.3 2155.47  5324.3 2157.93
#Mann=6,-1,0
  4703.7    0.07       0  4784.4   0.035       0  4950.5    0.16       0
  4955.6    0.07       0  4962.8    0.16       0  5290.3    0.07       0
Bank Sta=4955.6,4962.8
Exp/Cntr=0.3,0.1

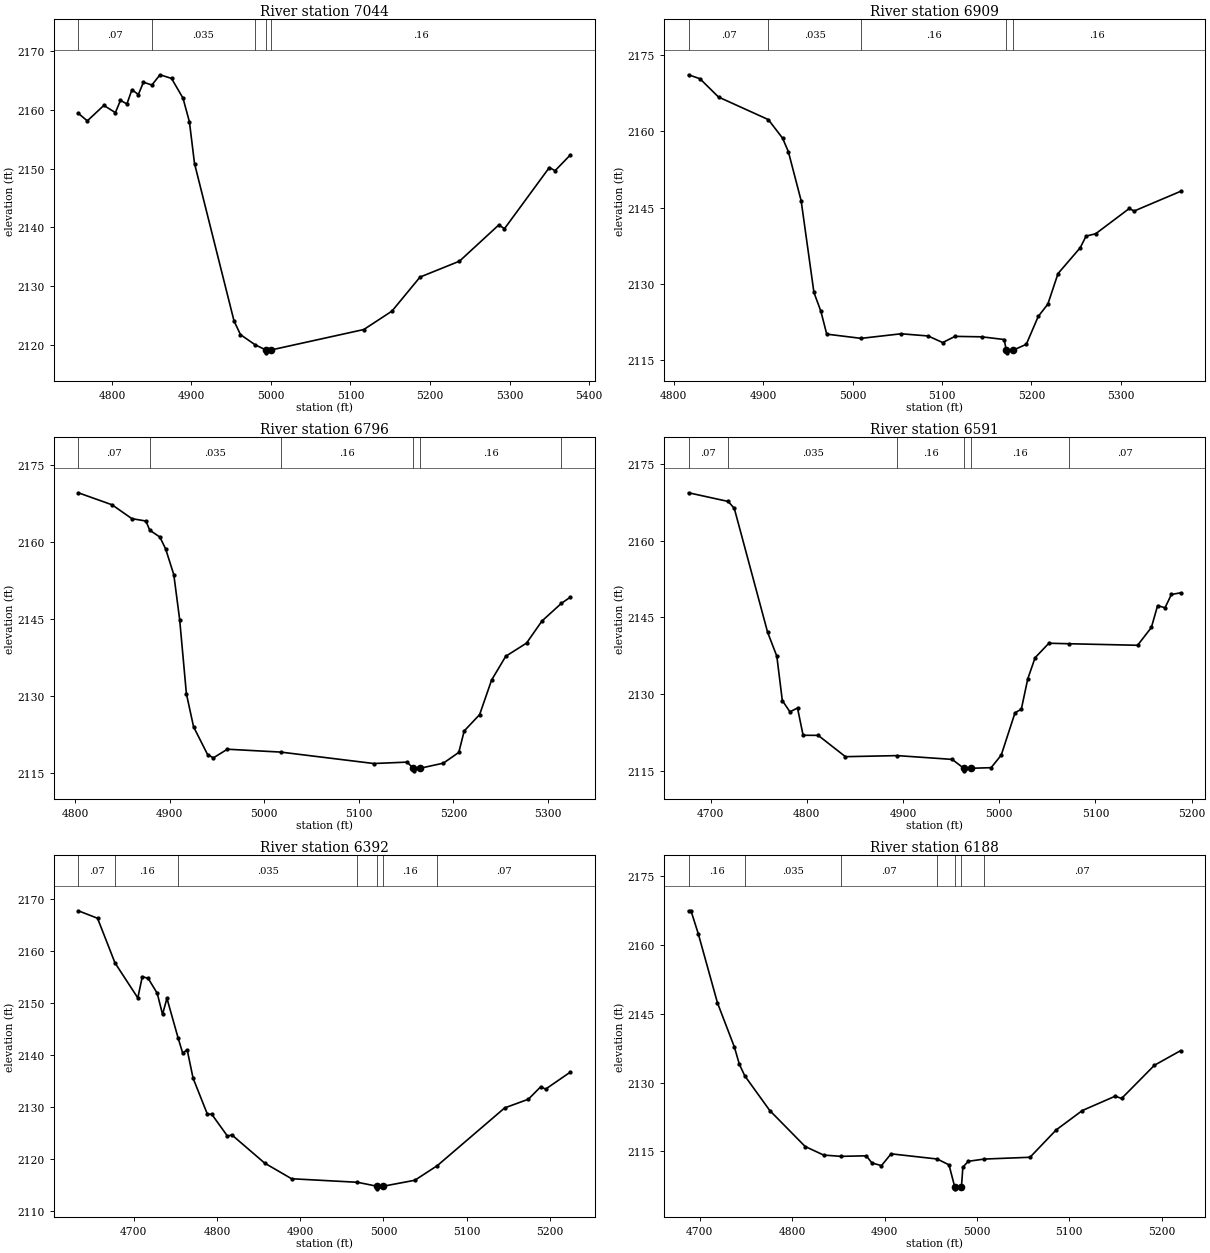
Type RM Length L Ch R = 1,7044,135,135,135
BEGIN DESCRIPTION:
Pleasant Run 7043.86
END DESCRIPTION:
XS GIS Cut Line= 3
      1521264.29      6766322.50      1521455.66      6766172.78
      1521723.86      6765909.80
#Sta/Elev= 30
  4757.8 2159.37  4769.1 2158.09  4789.9 2160.72  4804.4 2159.49  4810.8 2161.58
  4818.9 2160.96  4825.2 2163.38  4833.3 2162.57  4839.7 2164.66  4850.3 2164.18
  4860.5 2165.92  4875.0 2165.30  4889.4 2161.96  4897.5 2157.93  4903.9 2150.85
  4953.6 2124.10  4961.7 2121.78  4980.0 2120.07  4993.4 2119.19  4993.9 2118.69
  5000.6 2119.19  5116.8 2122.65  5152.2 2125.78  5187.5 2131.56  5237.1 2134.26
  5286.5 2140.41  5293.7 2139.78  5350.1 2150.17  5357.3 2149.63  5376.4 2152.29
#Mann=5,-1,0
  4757.8    0.07       0  4850.3   0.035       0  4980.0    0.16       0
  4993.4    0.07       0  5000.6    0.16       0
Bank Sta=4993.4,5000.6
Exp/Cntr=0.3,0.1

Type RM Length L Ch R = 1,6909,113,113,113
BEGIN DESCRIPTION:
Pleasant Run 6908.64
END DESCRIPTION:
XS GIS Cut Line= 3
      1521330.67      6766421.48      1521473.89      6766301.69
      1521813.75      6766172.78
#Sta/Elev= 30
  4816.6 2171.12  4829.3 2170.34  4850.1 2166.74  4905.8 2162.30  4921.7 2158.66
  4928.2 2155.99  4942.5 2146.34  4956.8 2128.29  4964.6 2124.57  4971.1 2120.09
  5009.5 2119.26  5054.3 2120.16  5084.5 2119.73  5100.8 2118.43  5114.6 2119.65
  5144.7 2119.56  5169.5 2119.03  5172.0 2116.91  5172.5 2116.41  5179.2 2116.91
  5194.3 2118.08  5207.7 2123.58  5218.4 2125.99  5229.8 2132.01  5254.6 2137.08
  5261.2 2139.38  5271.9 2139.84  5309.5 2144.81  5314.9 2144.31  5366.8 2148.18
#Mann=5,-1,0
  4816.6    0.07       0  4905.8   0.035       0  5009.5    0.16       0
  5172.0   0.035       0  5179.2    0.16       0
Bank Sta=5172,5179.2
Exp/Cntr=0.3,0.1

Type RM Length L Ch R = 1,6796,205,205,205
BEGIN DESCRIPTION:
Pleasant Run 6795.68
END DESCRIPTION:
XS GIS Cut Line= 3
      1521391.87      6766494.39      1521544.20      6766386.32
      1521838.43      6766230.10
#Sta/Elev= 30
  4803.5 2169.63  4839.2 2167.28  4860.1 2164.58  4874.9 2164.12  4879.0 2162.33
  4889.7 2160.99  4895.8 2158.66  4904.4 2153.65  4910.6 2144.88  4917.7 2130.43
  4925.3 2123.96  4940.1 2118.55  4946.2 2117.90  4961.0 2119.59  5017.3 2119.03
  5115.7 2116.80  5151.0 2117.07  5157.4 2115.87  5157.9 2115.37  5164.6 2115.87
  5189.3 2116.87  5205.6 2118.97  5211.3 2123.15  5227.6 2126.34  5240.3 2133.10
  5255.2 2137.72  5277.2 2140.30  5293.5 2144.61  5314.0 2148.05  5323.4 2149.25
#Mann=6,-1,0
  4803.5    0.07       0  4879.0   0.035       0  5017.3    0.16       0
  5157.4   0.035       0  5164.6    0.16       0  5314.0    0.07       0
Bank Sta=5157.4,5164.6
Exp/Cntr=0.3,0.1

Type RM Length L Ch R = 1,6591,199,199,199
BEGIN DESCRIPTION:
Pleasant Run 6591.01
END DESCRIPTION:
XS GIS Cut Line= 3
      1521473.91      6766560.80      1521746.03      6766403.25
      1521895.79      6766275.63
#Sta/Elev= 30
  4677.2 2169.36  4718.4 2167.66  4724.7 2166.31  4759.3 2142.08  4768.9 2137.38
  4774.6 2128.71  4782.5 2126.50  4790.4 2127.24  4796.2 2121.91  4811.9 2121.89
  4840.2 2117.72  4894.1 2117.93  4951.1 2117.19  4963.2 2115.45  4963.7 2114.95
  4970.5 2115.45  4991.6 2115.57  5002.1 2118.03  5016.4 2126.30  5023.0 2127.03
  5029.7 2132.97  5037.3 2137.09  5051.6 2139.92  5072.4 2139.82  5143.8 2139.52
  5158.1 2143.00  5164.6 2147.28  5172.3 2146.86  5178.9 2149.46  5188.4 2149.78
#Mann=6,-1,0
  4677.2    0.07       0  4718.4   0.035       0  4894.1    0.16       0
  4963.2    0.07       0  4970.5    0.16       0  5072.4    0.07       0
Bank Sta=4963.2,4970.5
Exp/Cntr=0.3,0.1

Type RM Length L Ch R = 1,6392,204,204,204
BEGIN DESCRIPTION:
Pleasant Run 6392.04
END DESCRIPTION:
XS GIS Cut Line= 3
      1521457.01      6766720.94      1521789.00      6766588.15
      1521979.11      6766452.35
#Sta/Elev= 30
  4633.3 2167.76  4656.4 2166.32  4677.4 2157.73  4704.8 2151.01  4710.2 2155.12
  4717.3 2154.75  4728.1 2151.91  4734.5 2147.85  4739.8 2150.93  4753.2 2143.32
  4758.7 2140.41  4764.1 2141.04  4771.2 2135.59  4788.3 2128.70  4793.7 2128.64
  4812.5 2124.45  4817.9 2124.67  4857.3 2119.25  4889.6 2116.25  4968.8 2115.57
  4992.2 2114.81  4992.7 2114.31  4999.6 2114.81  5037.7 2115.96  5064.8 2118.78
  5145.7 2129.87  5174.1 2131.53  5188.8 2133.90  5195.0 2133.49  5224.5 2136.74
#Mann=7,-1,0
  4633.3    0.07       0  4677.4    0.16       0  4753.2   0.035       0
  4968.8    0.16       0  4992.2    0.07       0  4999.6    0.16       0
  5064.8    0.07       0
Bank Sta=4992.2,4999.6
Exp/Cntr=0.3,0.1

Type RM Length L Ch R = 1,6188,206,206,206
BEGIN DESCRIPTION:
Pleasant Run 6188.332
END DESCRIPTION:
XS GIS Cut Line= 3
      1521604.98      6766838.00      1521903.96      6766748.44
      1522055.03      6766587.97
#Sta/Elev= 30
  4687.9 2167.51  4690.5 2167.51  4698.4 2162.49  4719.2 2147.39  4737.5 2137.76
  4742.8 2134.05  4748.7 2131.49  4775.8 2123.91  4814.1 2116.06  4834.1 2114.19
  4852.9 2113.91  4880.3 2114.03  4886.3 2112.47  4896.7 2111.89  4907.1 2114.46
  4957.1 2113.33  4969.8 2112.05  4975.9 2107.32  4976.4 2106.82  4983.3 2107.32
  4984.8 2111.54  4990.6 2112.83  5007.9 2113.32  5057.5 2113.71  5085.8 2119.68
  5114.1 2123.91  5149.8 2127.05  5156.6 2126.54  5192.2 2133.80  5220.4 2136.97
#Mann=7,-1,0
  4687.9    0.16       0  4748.7   0.035       0  4852.9    0.07       0
  4957.1    0.16       0  4975.9    0.07       0  4983.3    0.16       0
  5007.9    0.07       0
Bank Sta=4975.9,4983.3
Exp/Cntr=0.3,0.1

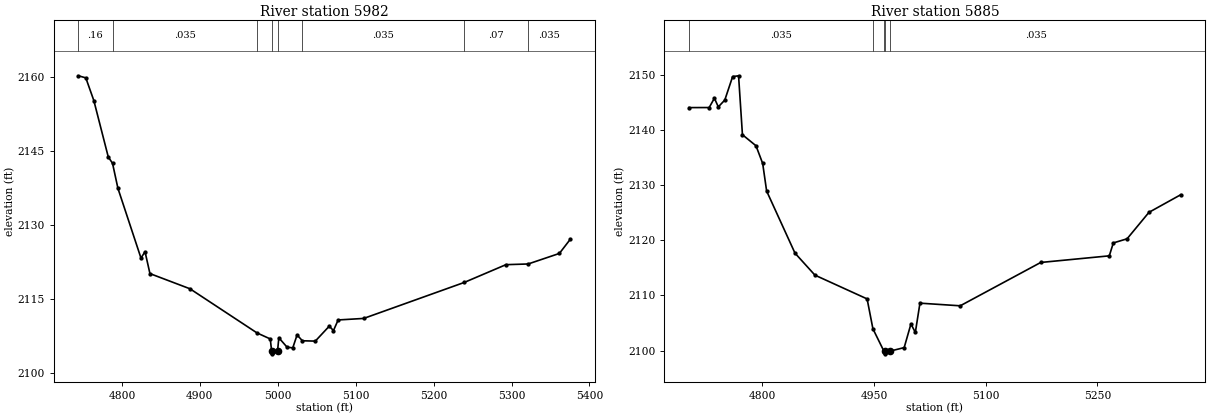
Type RM Length L Ch R = 1,5982,97,97,97
BEGIN DESCRIPTION:
Pleasant Run 5981.51
END DESCRIPTION:
XS GIS Cut Line= 3
      1521615.64      6767002.63      1521855.19      6766945.35
      1522207.60      6766790.84
#Sta/Elev= 30
  4744.1 2160.28  4753.7 2159.86  4764.0 2155.26  4782.5 2143.84  4788.0 2142.53
  4794.9 2137.47  4824.5 2123.32  4829.7 2124.61  4836.0 2120.17  4887.4 2117.09
  4973.4 2108.14  4990.4 2106.92  4992.2 2104.40  4992.7 2103.90  4999.7 2104.40
  5001.4 2107.16  5012.0 2105.24  5019.3 2105.12  5024.8 2107.73  5031.6 2106.55
  5048.2 2106.48  5066.1 2109.51  5071.5 2108.62  5077.5 2110.77  5110.3 2111.08
  5239.2 2118.37  5292.8 2121.98  5321.3 2122.12  5361.4 2124.26  5375.2 2127.09
#Mann=8,-1,0
  4744.1    0.16       0  4788.0   0.035       0  4973.4    0.16       0
  4992.2    0.07       0  4999.7    0.16       0  5031.6   0.035       0
  5239.2    0.07       0  5321.3   0.035       0
Bank Sta=4992.2,4999.7
Exp/Cntr=0.3,0.1

Type RM Length L Ch R = 1,5885,121,121,121
BEGIN DESCRIPTION:
Pleasant Run 5885.12
END DESCRIPTION:
XS GIS Cut Line= 3
      1521619.12      6767113.74      1521907.27      6767023.48
      1522238.87      6766886.32
#Sta/Elev= 30
  4701.3 2144.05  4728.4 2144.06  4735.4 2145.75  4740.7 2144.18  4749.4 2145.42
  4759.9 2149.67  4767.9 2149.82  4773.1 2139.13  4791.3 2137.13  4800.3 2133.92
  4805.6 2128.92  4843.7 2117.66  4870.5 2113.67  4940.6 2109.36  4948.4 2103.94
  4963.1 2099.91  4964.1 2099.90  4964.6 2099.40  4971.6 2099.90  4990.4 2100.53
  4999.5 2104.82  5005.4 2103.28  5011.6 2108.59  5065.7 2108.11  5173.9 2115.97
  5266.0 2117.17  5271.4 2119.51  5289.9 2120.26  5319.3 2125.06  5362.1 2128.26
#Mann=5,-1,0
  4701.3   0.035       0  4948.4    0.16       0  4963.1   0.035       0
  4964.1   0.035       0  4971.6   0.035       0
Bank Sta=4964.1,4971.6
Exp/Cntr=0.3,0.1