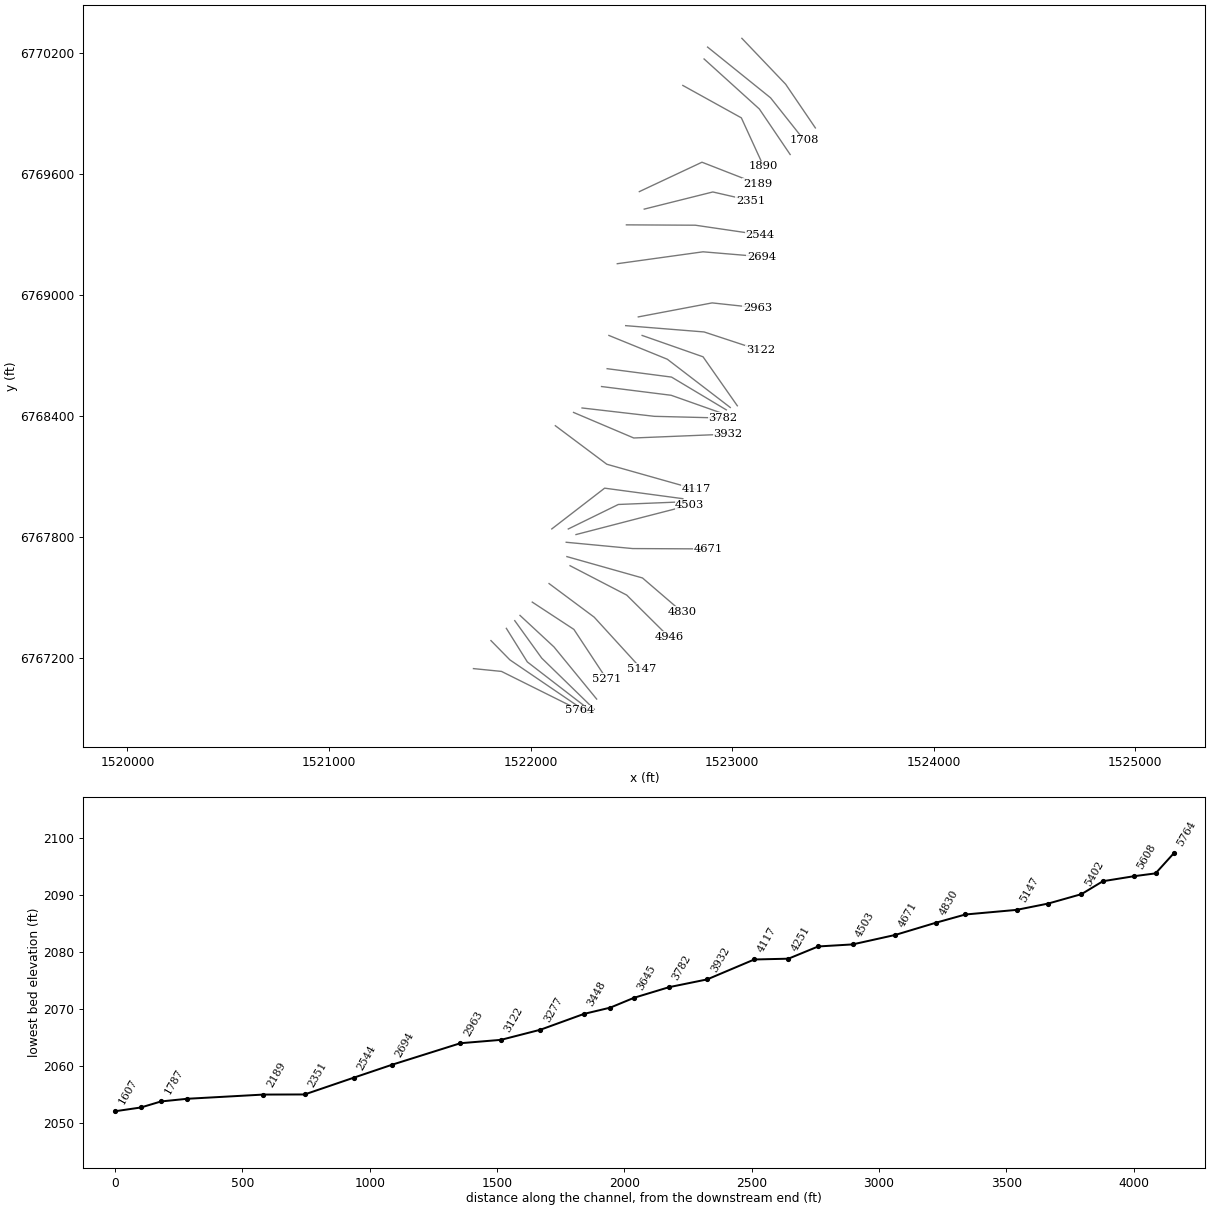
HEC-RAS study Pleasant Run.prj: Pleasant Run Base Level Engineering

--- Pleasant Run.g01 (geometry) --- (continued)

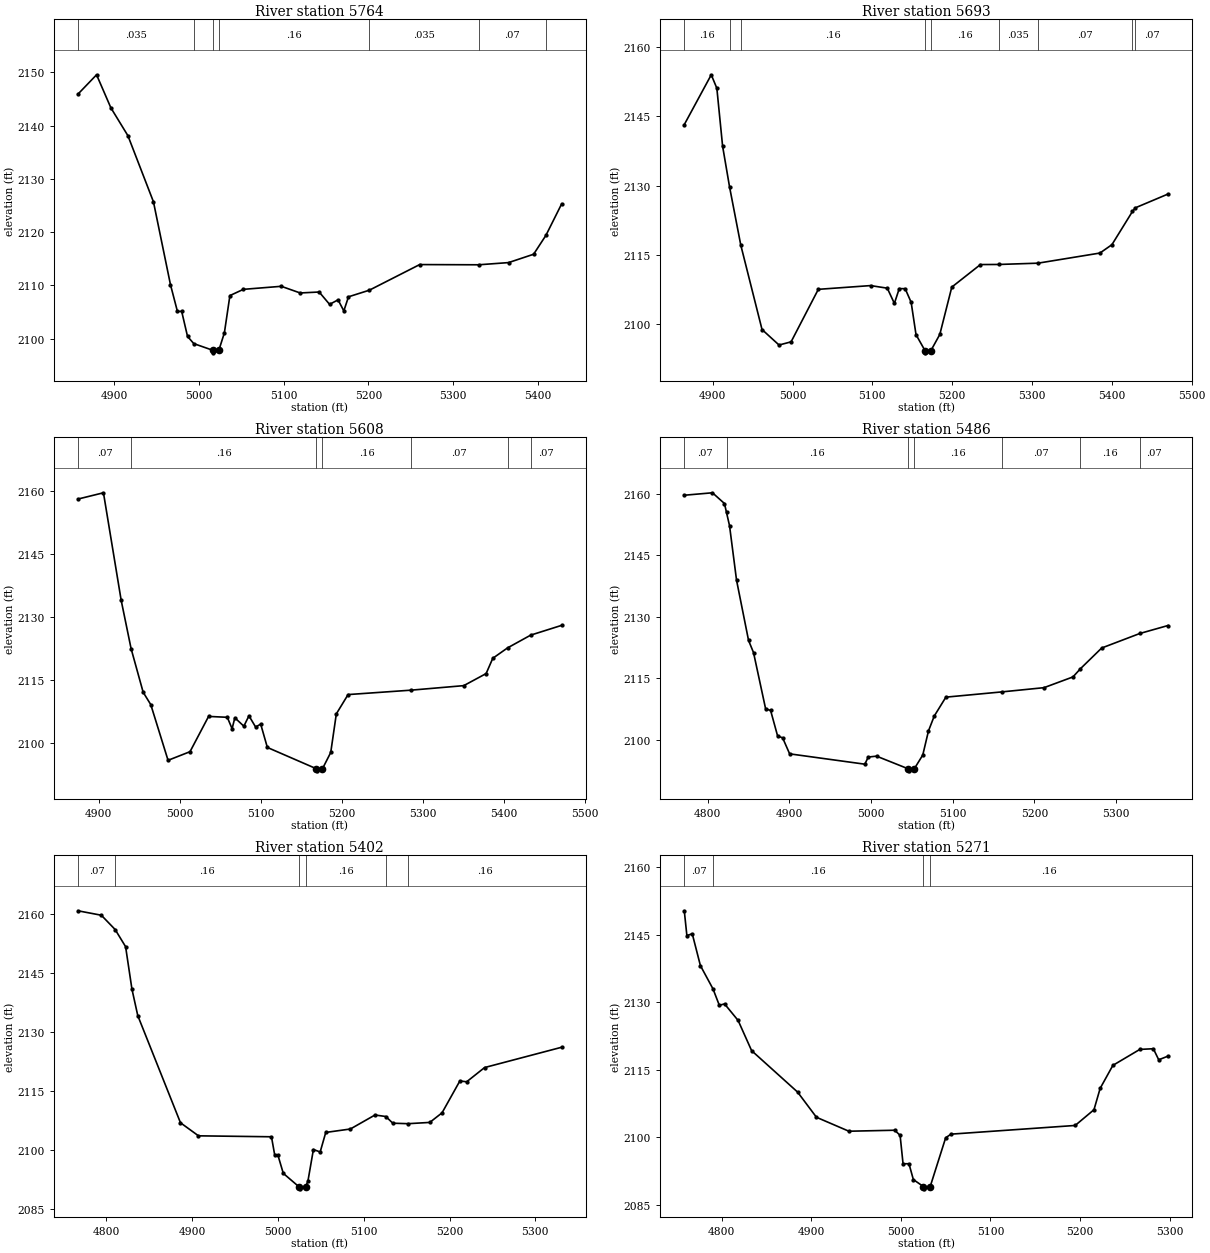
Type RM Length L Ch R = 1,5764,71,71,71
BEGIN DESCRIPTION:
Pleasant Run 5763.88
END DESCRIPTION:
XS GIS Cut Line= 3
      1521716.33      6767145.00      1521855.19      6767131.12
      1522241.17      6766938.99
#Sta/Elev= 30
  4857.2 2145.91  4879.2 2149.55  4896.1 2143.34  4916.2 2138.11  4946.3 2125.71
  4966.4 2110.14  4974.6 2105.12  4979.6 2105.14  4986.5 2100.44  4993.9 2099.08
  5016.0 2097.85  5016.5 2097.35  5023.5 2097.85  5030.0 2101.11  5036.5 2108.10
  5052.4 2109.27  5097.1 2109.84  5119.4 2108.59  5141.8 2108.77  5154.1 2106.45
  5164.1 2107.30  5170.9 2105.22  5176.4 2107.87  5201.0 2109.11  5260.4 2113.92
  5329.9 2113.88  5365.2 2114.29  5394.8 2115.86  5409.3 2119.40  5427.9 2125.32
#Mann=7,-1,0
  4857.2   0.035       0  4993.9    0.16       0  5016.0    0.07       0
  5023.5    0.16       0  5201.0   0.035       0  5329.9    0.07       0
  5409.3   0.035       0
Bank Sta=5016,5023.5
Exp/Cntr=0.3,0.1

Type RM Length L Ch R = 1,5693,85,85,85
BEGIN DESCRIPTION:
Pleasant Run 5692.51
END DESCRIPTION:
XS GIS Cut Line= 3
      1521803.10      6767283.89      1521896.85      6767188.41
      1522287.32      6766922.89
#Sta/Elev= 30
  4864.4 2143.22  4898.2 2154.00  4905.2 2151.08  4912.4 2138.56  4921.1 2129.75
  4935.2 2117.13  4961.8 2098.88  4983.1 2095.53  4998.2 2096.22  5032.3 2107.58
  5097.8 2108.39  5118.7 2107.83  5127.6 2104.53  5133.7 2107.74  5141.1 2107.72
  5148.6 2104.77  5154.7 2097.77  5165.9 2094.34  5166.4 2093.84  5173.4 2094.34
  5184.5 2097.82  5199.5 2108.06  5235.4 2112.94  5258.3 2112.96  5307.5 2113.24
  5385.1 2115.43  5400.1 2117.24  5425.8 2124.42  5429.5 2125.22  5470.4 2128.20
#Mann=9,-1,0
  4864.4    0.16       0  4921.1    0.07       0  4935.2    0.16       0
  5165.9    0.07       0  5173.4    0.16       0  5258.3   0.035       0
  5307.5    0.07       0  5425.8   0.035       0  5429.5    0.07       0
Bank Sta=5165.9,5173.4
Exp/Cntr=0.3,0.1

Type RM Length L Ch R = 1,5608,122,122,122
BEGIN DESCRIPTION:
Pleasant Run 5608.28
END DESCRIPTION:
XS GIS Cut Line= 3
      1521879.48      6767344.68      1521983.66      6767177.99
      1522300.70      6766933.71
#Sta/Elev= 30
  4874.3 2158.16  4905.8 2159.66  4927.7 2133.98  4939.9 2122.49  4954.8 2112.08
  4964.2 2109.13  4985.5 2095.85  5012.6 2097.91  5035.5 2106.32  5058.6 2106.11
  5064.5 2103.39  5067.9 2105.99  5079.0 2103.99  5085.3 2106.46  5093.5 2103.80
  5099.8 2104.48  5108.0 2098.92  5168.5 2093.84  5169.0 2093.34  5176.0 2093.84
  5186.2 2097.72  5193.1 2106.93  5207.6 2111.53  5285.2 2112.58  5350.3 2113.66
  5377.9 2116.54  5386.1 2120.18  5404.3 2122.66  5432.9 2125.71  5471.1 2128.04
#Mann=7,-1,0
  4874.3    0.07       0  4939.9    0.16       0  5168.5    0.07       0
  5176.0    0.16       0  5285.2    0.07       0  5404.3    0.16       0
  5432.9    0.07       0
Bank Sta=5168.5,5176
Exp/Cntr=0.3,0.1

Type RM Length L Ch R = 1,5486,84,84,84
BEGIN DESCRIPTION:
Pleasant Run 5486.11
END DESCRIPTION:
XS GIS Cut Line= 3
      1521921.16      6767382.85      1522054.84      6767197.09
      1522315.28      6766943.59
#Sta/Elev= 30
  4771.3 2159.63  4805.8 2160.23  4820.5 2157.61  4823.0 2155.43  4826.7 2152.21
  4835.3 2138.91  4850.0 2124.24  4856.1 2121.27  4870.9 2107.56  4877.0 2107.18
  4885.6 2100.93  4891.7 2100.51  4900.3 2096.60  4992.4 2094.08  4996.5 2095.82
  5006.7 2096.04  5045.4 2092.96  5045.9 2092.46  5052.9 2092.96  5063.3 2096.31
  5070.3 2102.20  5077.4 2105.83  5091.6 2110.42  5160.1 2111.70  5211.7 2112.73
  5247.2 2115.35  5256.3 2117.34  5282.4 2122.40  5329.1 2125.94  5363.6 2127.88
#Mann=7,-1,0
  4771.3    0.07       0  4823.0    0.16       0  5045.4    0.07       0
  5052.9    0.16       0  5160.1    0.07       0  5256.3    0.16       0
  5329.1    0.07       0
Bank Sta=5045.4,5052.9
Exp/Cntr=0.3,0.1

Type RM Length L Ch R = 1,5402,131,131,131
BEGIN DESCRIPTION:
Pleasant Run 5402
END DESCRIPTION:
XS GIS Cut Line= 3
      1521947.18      6767408.91      1522115.60      6767252.64
      1522327.42      6766993.95
#Sta/Elev= 30
  4766.7 2160.69  4794.0 2159.56  4810.1 2155.94  4822.3 2151.59  4829.7 2140.82
  4836.5 2134.11  4886.3 2106.94  4907.3 2103.63  4992.4 2103.39  4996.2 2098.74
  4999.9 2098.74  5006.2 2094.11  5024.6 2090.69  5025.1 2090.19  5032.1 2090.69
  5034.9 2092.13  5041.3 2100.16  5049.2 2099.54  5055.7 2104.49  5084.4 2105.36
  5113.1 2108.91  5125.7 2108.53  5133.9 2106.83  5151.8 2106.71  5177.0 2107.03
  5191.3 2109.46  5212.1 2117.55  5220.0 2117.33  5240.9 2120.94  5330.8 2126.09
#Mann=6,-1,0
  4766.7    0.07       0  4810.1    0.16       0  5024.6    0.07       0
  5032.1    0.16       0  5125.7    0.07       0  5151.8    0.16       0
Bank Sta=5024.6,5032.1
Exp/Cntr=0.3,0.1

Type RM Length L Ch R = 1,5271,124,124,124
BEGIN DESCRIPTION:
Pleasant Run 5271.33
END DESCRIPTION:
XS GIS Cut Line= 3
      1522007.99      6767474.85      1522214.56      6767339.45
      1522376.00      6767094.69
#Sta/Elev= 30
  4758.1 2150.35  4761.0 2144.84  4767.0 2145.24  4776.1 2138.16  4790.2 2132.97
  4797.2 2129.35  4803.1 2129.64  4818.2 2125.97  4833.3 2119.25  4884.6 2110.05
  4905.7 2104.44  4941.9 2101.34  4993.1 2101.56  4999.1 2100.42  5002.4 2094.11
  5009.0 2094.11  5013.9 2090.59  5025.2 2089.03  5025.7 2088.53  5032.7 2089.03
  5050.0 2099.89  5056.0 2100.69  5194.6 2102.62  5215.6 2106.12  5222.5 2110.87
  5236.7 2115.98  5266.8 2119.53  5281.9 2119.68  5287.9 2117.22  5298.3 2118.04
#Mann=4,-1,0
  4758.1    0.07       0  4790.2    0.16       0  5025.2    0.07       0
  5032.7    0.16       0
Bank Sta=5025.2,5032.7
Exp/Cntr=0.3,0.1

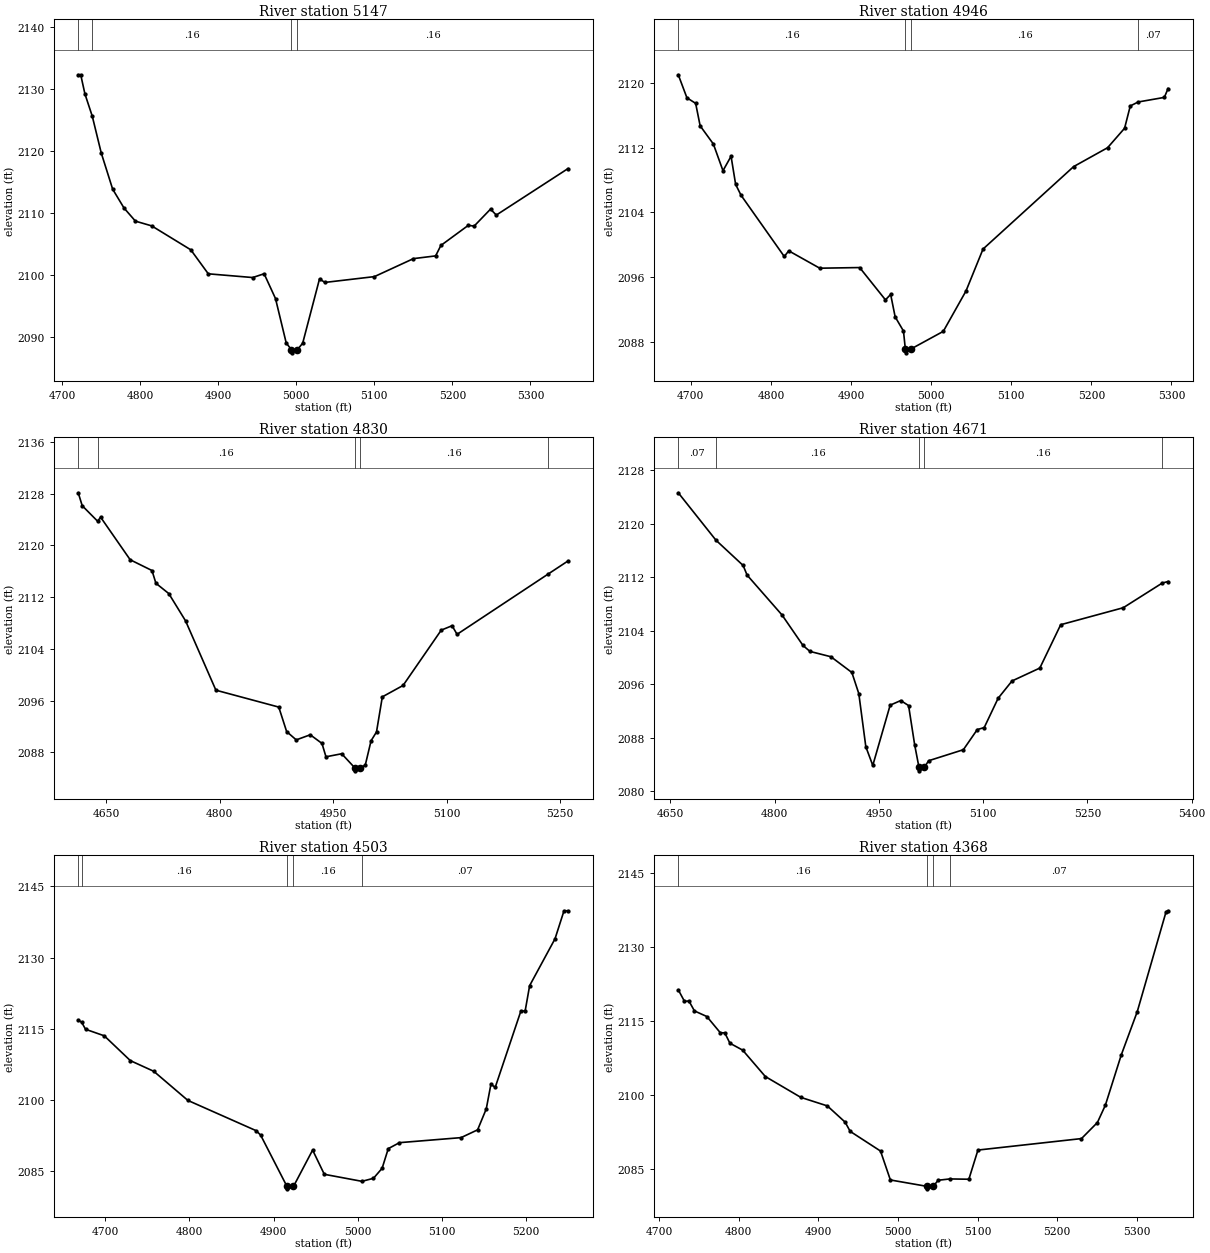
Type RM Length L Ch R = 1,5147,201,201,201
BEGIN DESCRIPTION:
Pleasant Run 5146.73
END DESCRIPTION:
XS GIS Cut Line= 3
      1522091.32      6767566.86      1522315.26      6767400.21
      1522550.04      6767142.99
#Sta/Elev= 30
  4720.8 2132.25  4724.0 2132.25  4729.4 2129.16  4738.8 2125.57  4750.3 2119.64
  4764.9 2113.81  4779.5 2110.76  4794.1 2108.65  4814.9 2107.89  4865.0 2104.03
  4887.4 2100.16  4944.3 2099.56  4958.9 2100.17  4973.5 2096.17  4987.2 2089.02
  4993.9 2087.92  4994.4 2087.42  5001.4 2087.92  5008.3 2088.97  5029.9 2099.35
  5036.7 2098.77  5100.2 2099.71  5150.2 2102.61  5178.6 2103.05  5185.3 2104.73
  5220.5 2107.98  5227.9 2107.85  5248.9 2110.59  5256.3 2109.63  5348.2 2117.13
#Mann=4,-1,0
  4720.8    0.07       0  4738.8    0.16       0  4993.9    0.07       0
  5001.4    0.16       0
Bank Sta=4993.9,5001.4
Exp/Cntr=0.3,0.1

Type RM Length L Ch R = 1,4946,116,116,116
BEGIN DESCRIPTION:
Pleasant Run 4946.34
END DESCRIPTION:
XS GIS Cut Line= 3
      1522195.47      6767655.42      1522476.71      6767509.59
      1522685.88      6767302.15
#Sta/Elev= 30
  4684.4 2121.04  4695.2 2118.19  4706.1 2117.50  4711.7 2114.72  4728.2 2112.47
  4740.2 2109.16  4750.3 2110.95  4756.0 2107.47  4762.7 2106.13  4816.7 2098.54
  4822.3 2099.24  4861.0 2097.09  4910.8 2097.17  4943.0 2093.17  4949.5 2093.84
  4955.1 2091.07  4965.5 2089.31  4967.8 2087.11  4968.3 2086.61  4975.3 2087.11
  5015.2 2089.27  5043.5 2094.26  5064.8 2099.46  5177.9 2109.67  5220.3 2112.01
  5241.5 2114.42  5248.6 2117.18  5258.4 2117.67  5291.1 2118.24  5295.8 2119.34
#Mann=4,-1,0
  4684.4    0.16       0  4967.8    0.07       0  4975.3    0.16       0
  5258.4    0.07       0
Bank Sta=4967.8,4975.3
Exp/Cntr=0.3,0.1

Type RM Length L Ch R = 1,4830,159,159,159
BEGIN DESCRIPTION:
Pleasant Run 4830.36
END DESCRIPTION:
XS GIS Cut Line= 3
      1522179.85      6767700.56      1522554.84      6767594.66
      1522750.49      6767426.71
#Sta/Elev= 30
  4613.0 2128.12  4618.3 2126.12  4638.6 2123.73  4642.6 2124.35  4681.7 2117.77
  4710.5 2116.11  4715.7 2114.14  4732.7 2112.55  4754.9 2108.33  4795.0 2097.62
  4878.1 2095.01  4888.5 2091.23  4901.2 2089.94  4919.7 2090.73  4935.2 2089.40
  4940.5 2087.33  4961.3 2087.80  4978.3 2085.66  4978.8 2085.16  4985.8 2085.66
  4992.4 2086.02  5000.1 2089.80  5007.3 2091.17  5015.0 2096.59  5042.4 2098.35
  5092.9 2106.90  5107.2 2107.58  5113.8 2106.25  5233.5 2115.51  5260.5 2117.59
#Mann=5,-1,0
  4613.0    0.07       0  4638.6    0.16       0  4978.3    0.07       0
  4985.8    0.16       0  5233.5    0.07       0
Bank Sta=4978.3,4985.8
Exp/Cntr=0.3,0.1

Type RM Length L Ch R = 1,4671,168,168,168
BEGIN DESCRIPTION:
Pleasant Run 4671.23
END DESCRIPTION:
XS GIS Cut Line= 3
      1522176.42      6767771.74      1522506.23      6767740.49
      1522879.53      6767738.75
#Sta/Elev= 30
  4661.4 2124.60  4715.6 2117.51  4754.7 2113.73  4760.4 2112.29  4810.7 2106.32
  4840.8 2101.77  4850.8 2100.88  4881.0 2100.08  4911.1 2097.73  4921.1 2094.57
  4931.2 2086.62  4941.2 2083.83  4966.2 2092.84  4981.4 2093.53  4992.7 2092.78
  5001.5 2086.88  5007.7 2083.52  5008.2 2083.02  5015.3 2083.52  5021.5 2084.53
  5071.5 2086.18  5091.5 2089.19  5101.5 2089.49  5121.5 2093.87  5141.5 2096.46
  5181.5 2098.39  5211.5 2104.87  5301.5 2107.41  5357.6 2111.10  5366.0 2111.33
#Mann=5,-1,0
  4661.4    0.07       0  4715.6    0.16       0  5007.7    0.07       0
  5015.3    0.16       0  5357.6    0.07       0
Bank Sta=5007.7,5015.3
Exp/Cntr=0.3,0.1

Type RM Length L Ch R = 1,4503,135,135,135
BEGIN DESCRIPTION:
Pleasant Run 4503.01
END DESCRIPTION:
XS GIS Cut Line= 3
      1522224.98      6767809.94      1522553.10      6767895.00
      1522789.24      6767955.77
#Sta/Elev= 30
  4667.6 2116.89  4671.8 2116.38  4676.3 2114.94  4698.6 2113.56  4729.6 2108.34
  4757.5 2106.09  4798.1 2099.96  4879.2 2093.60  4884.6 2092.67  4916.0 2081.85
  4916.5 2081.35  4923.7 2081.85  4946.5 2089.51  4960.4 2084.41  5005.2 2082.93
  5018.9 2083.57  5029.2 2085.68  5036.5 2089.81  5049.8 2091.07  5123.1 2092.13
  5142.8 2093.77  5153.1 2098.18  5158.6 2103.33  5163.8 2102.74  5194.2 2118.73
  5199.4 2118.82  5204.7 2124.12  5234.9 2133.98  5245.6 2139.88  5250.4 2139.88
#Mann=5,-1,0
  4667.6    0.07       0  4671.8    0.16       0  4916.0    0.07       0
  4923.7    0.16       0  5005.2    0.07       0
Bank Sta=4916,4923.7
Exp/Cntr=0.3,0.1

Type RM Length L Ch R = 1,4368,117,117,117
BEGIN DESCRIPTION:
Pleasant Run 4367.62
END DESCRIPTION:
XS GIS Cut Line= 3
      1522186.74      6767837.69      1522435.05      6767959.24
      1522773.71      6767973.06
#Sta/Elev= 30
  4723.9 2121.38  4731.7 2119.04  4737.3 2119.11  4744.2 2117.10  4759.8 2115.96
  4776.8 2112.65  4782.3 2112.66  4788.8 2110.54  4804.8 2109.14  4833.3 2103.78
  4877.9 2099.55  4911.2 2097.82  4933.5 2094.53  4939.9 2092.65  4978.0 2088.66
  4990.4 2082.79  5036.5 2081.49  5037.0 2080.99  5044.2 2081.49  5050.4 2082.73
  5065.0 2083.00  5089.0 2082.94  5100.4 2088.86  5230.5 2091.19  5250.5 2094.45
  5260.5 2097.97  5280.5 2108.18  5300.6 2116.97  5336.7 2137.19  5339.3 2137.42
#Mann=4,-1,0
  4723.9    0.16       0  5036.5    0.07       0  5044.2    0.16       0
  5065.0    0.07       0
Bank Sta=5036.5,5044.2
Exp/Cntr=0.3,0.1

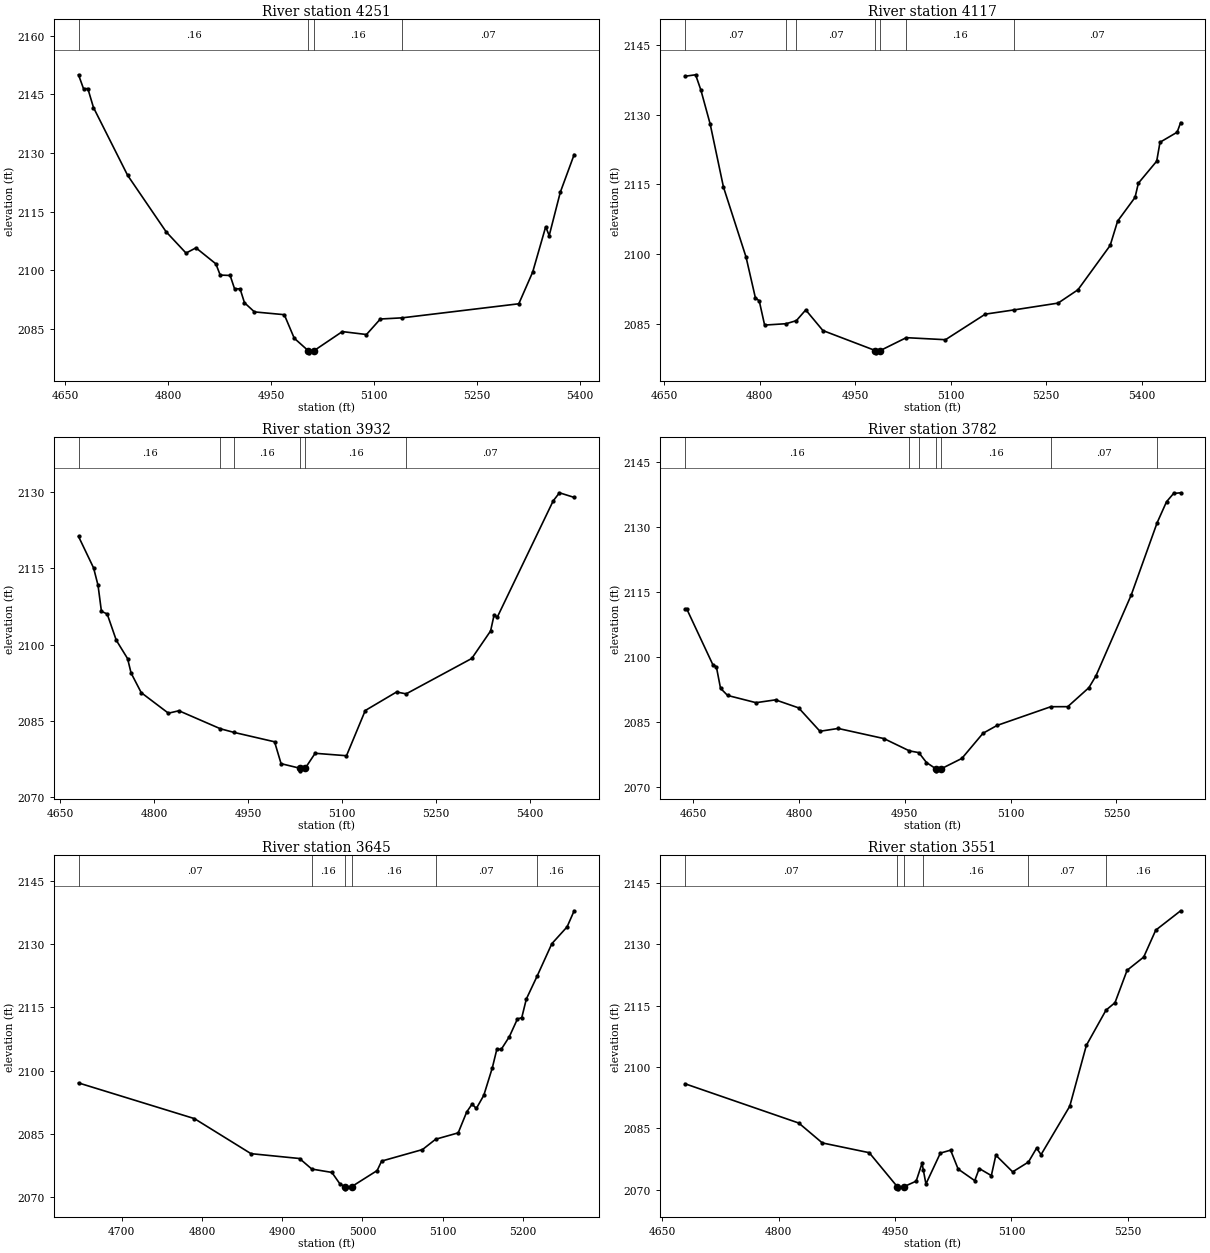
Type RM Length L Ch R = 1,4251,134,134,134
BEGIN DESCRIPTION:
Pleasant Run 4250.956
END DESCRIPTION:
XS GIS Cut Line= 3
      1522104.99      6767837.99      1522367.08      6768040.16
      1522754.99      6767988.00
#Sta/Elev= 30
  4669.0 2150.03  4676.3 2146.46  4682.6 2146.49  4690.8 2141.65  4740.6 2124.28
  4796.7 2109.83  4825.7 2104.38  4840.2 2105.72  4869.2 2101.62  4875.5 2098.75
  4890.0 2098.65  4896.4 2095.25  4904.5 2095.22  4910.9 2091.66  4925.4 2089.32
  4968.9 2088.61  4983.4 2082.59  5004.1 2079.34  5004.6 2078.84  5011.8 2079.34
  5053.5 2084.28  5088.7 2083.53  5108.9 2087.50  5140.6 2087.80  5310.7 2091.40
  5330.9 2099.50  5349.9 2111.12  5355.0 2108.85  5371.2 2119.96  5391.4 2129.60
#Mann=4,-1,0
  4669.0    0.16       0  5004.1    0.07       0  5011.8    0.16       0
  5140.6    0.07       0
Bank Sta=5004.1,5011.8
Exp/Cntr=0.3,0.1

Type RM Length L Ch R = 1,4117,185,185,185
BEGIN DESCRIPTION:
Pleasant Run 4117.41
END DESCRIPTION:
XS GIS Cut Line= 3
      1522122.51      6768349.89      1522377.76      6768158.89
      1522820.26      6768033.95
#Sta/Elev= 30
  4682.5 2138.30  4699.2 2138.62  4707.5 2135.32  4722.1 2127.99  4742.9 2114.45
  4778.4 2099.35  4793.0 2090.62  4799.2 2089.87  4807.6 2084.68  4841.4 2084.98
  4857.5 2085.64  4872.2 2087.95  4899.2 2083.50  4981.4 2079.20  4981.9 2078.70
  4989.4 2079.20  5030.1 2081.97  5091.7 2081.53  5154.3 2087.04  5199.3 2087.95
  5268.6 2089.42  5299.8 2092.29  5350.4 2101.84  5362.1 2107.08  5389.5 2112.20
  5394.7 2115.26  5423.5 2120.00  5428.7 2124.08  5455.6 2126.24  5461.1 2128.31
#Mann=7,-1,0
  4682.5    0.07       0  4841.4    0.16       0  4857.5    0.07       0
  4981.4    0.07       0  4989.4    0.07       0  5030.1    0.16       0
  5199.3    0.07       0
Bank Sta=4981.4,4989.4
Exp/Cntr=0.3,0.1

Type RM Length L Ch R = 1,3932,150,150,150
BEGIN DESCRIPTION:
Pleasant Run 3932.06
END DESCRIPTION:
XS GIS Cut Line= 3
      1522212.81      6768415.84      1522511.44      6768289.10
      1522978.44      6768308.20
#Sta/Elev= 30
  4679.4 2121.28  4703.5 2115.08  4710.6 2111.66  4716.0 2106.56  4725.2 2106.04
  4739.7 2100.88  4757.8 2097.26  4763.4 2094.42  4779.6 2090.57  4823.0 2086.53
  4839.8 2087.01  4906.1 2083.47  4927.3 2082.77  4992.6 2080.91  5003.0 2076.61
  5033.4 2075.70  5033.9 2075.20  5041.5 2075.70  5057.4 2078.65  5107.5 2078.17
  5137.5 2087.06  5187.5 2090.70  5202.8 2090.33  5307.6 2097.29  5337.7 2102.70
  5343.3 2105.85  5348.3 2105.39  5437.7 2128.27  5447.7 2129.86  5471.2 2128.95
#Mann=6,-1,0
  4679.4    0.16       0  4906.1    0.07       0  4927.3    0.16       0
  5033.4    0.07       0  5041.5    0.16       0  5202.8    0.07       0
Bank Sta=5033.4,5041.5
Exp/Cntr=0.3,0.1

Type RM Length L Ch R = 1,3782,137,137,137
BEGIN DESCRIPTION:
Pleasant Run 3782.106
END DESCRIPTION:
XS GIS Cut Line= 3
      1522254.97      6768438.00      1522614.08      6768396.51
      1522954.97      6768388.00
#Sta/Elev= 30
  4638.5 2111.15  4641.0 2111.15  4677.9 2098.33  4683.0 2097.80  4688.9 2092.85
  4698.9 2091.21  4739.2 2089.54  4766.8 2090.19  4799.6 2088.34  4829.8 2082.95
  4855.6 2083.60  4920.4 2081.27  4956.6 2078.43  4969.9 2078.03  4980.8 2075.74
  4993.9 2074.33  4994.4 2073.83  5002.0 2074.33  5030.9 2076.69  5060.9 2082.49
  5080.9 2084.30  5157.0 2088.61  5181.0 2088.62  5211.0 2093.00  5221.0 2095.73
  5271.0 2114.37  5307.7 2131.02  5321.0 2135.85  5331.0 2137.76  5341.0 2137.92
#Mann=7,-1,0
  4638.5    0.16       0  4956.6    0.07       0  4969.9    0.16       0
  4993.9    0.07       0  5002.0    0.16       0  5157.0    0.07       0
  5307.7    0.16       0
Bank Sta=4993.9,5002
Exp/Cntr=0.3,0.1

Type RM Length L Ch R = 1,3645,94,94,94
BEGIN DESCRIPTION:
Pleasant Run 3644.77
END DESCRIPTION:
XS GIS Cut Line= 3
      1522351.73      6768544.31      1522697.20      6768500.91
      1522951.19      6768411.06
#Sta/Elev= 30
  4646.2 2097.08  4790.6 2088.62  4861.1 2080.31  4921.6 2079.16  4936.9 2076.66
  4961.9 2075.86  4972.0 2073.12  4978.3 2072.47  4978.8 2071.97  4986.4 2072.47
  5018.3 2076.30  5023.9 2078.55  5074.8 2081.28  5091.2 2083.73  5119.3 2085.24
  5129.9 2090.19  5136.6 2092.06  5141.9 2091.02  5151.2 2094.14  5161.8 2100.65
  5167.5 2105.09  5172.9 2105.03  5183.0 2108.03  5193.1 2112.24  5198.5 2112.55
  5204.2 2116.97  5217.5 2122.34  5236.0 2130.09  5255.0 2134.08  5263.8 2137.89
#Mann=6,-1,0
  4646.2    0.07       0  4936.9    0.16       0  4978.3    0.07       0
  4986.4    0.16       0  5091.2    0.07       0  5217.5    0.16       0
Bank Sta=4978.3,4986.4
Exp/Cntr=0.3,0.1

Type RM Length L Ch R = 1,3551,103,103,103
BEGIN DESCRIPTION:
Pleasant Run 3550.9
END DESCRIPTION:
XS GIS Cut Line= 3
      1522379.51      6768632.85      1522698.94      6768591.19
      1522970.72      6768428.46
#Sta/Elev= 30
  4679.2 2095.93  4825.9 2086.32  4856.2 2081.46  4916.7 2079.07  4953.0 2070.73
  4953.5 2070.23  4961.1 2070.73  4977.2 2072.11  4984.8 2076.49  4986.4 2074.87
  4989.8 2071.43  5008.4 2078.97  5021.6 2079.69  5031.3 2075.07  5052.7 2072.23
  5058.5 2075.20  5074.1 2073.47  5079.9 2078.46  5101.6 2074.38  5121.9 2076.78
  5132.4 2080.17  5138.2 2078.60  5175.2 2090.44  5196.6 2105.33  5221.9 2113.93
  5233.5 2115.76  5249.1 2123.68  5270.5 2126.91  5286.0 2133.49  5318.1 2138.23
#Mann=6,-1,0
  4679.2    0.07       0  4953.0    0.07       0  4961.1    0.07       0
  4986.4    0.16       0  5121.9    0.07       0  5221.9    0.16       0
Bank Sta=4953,4961.1
Exp/Cntr=0.3,0.1

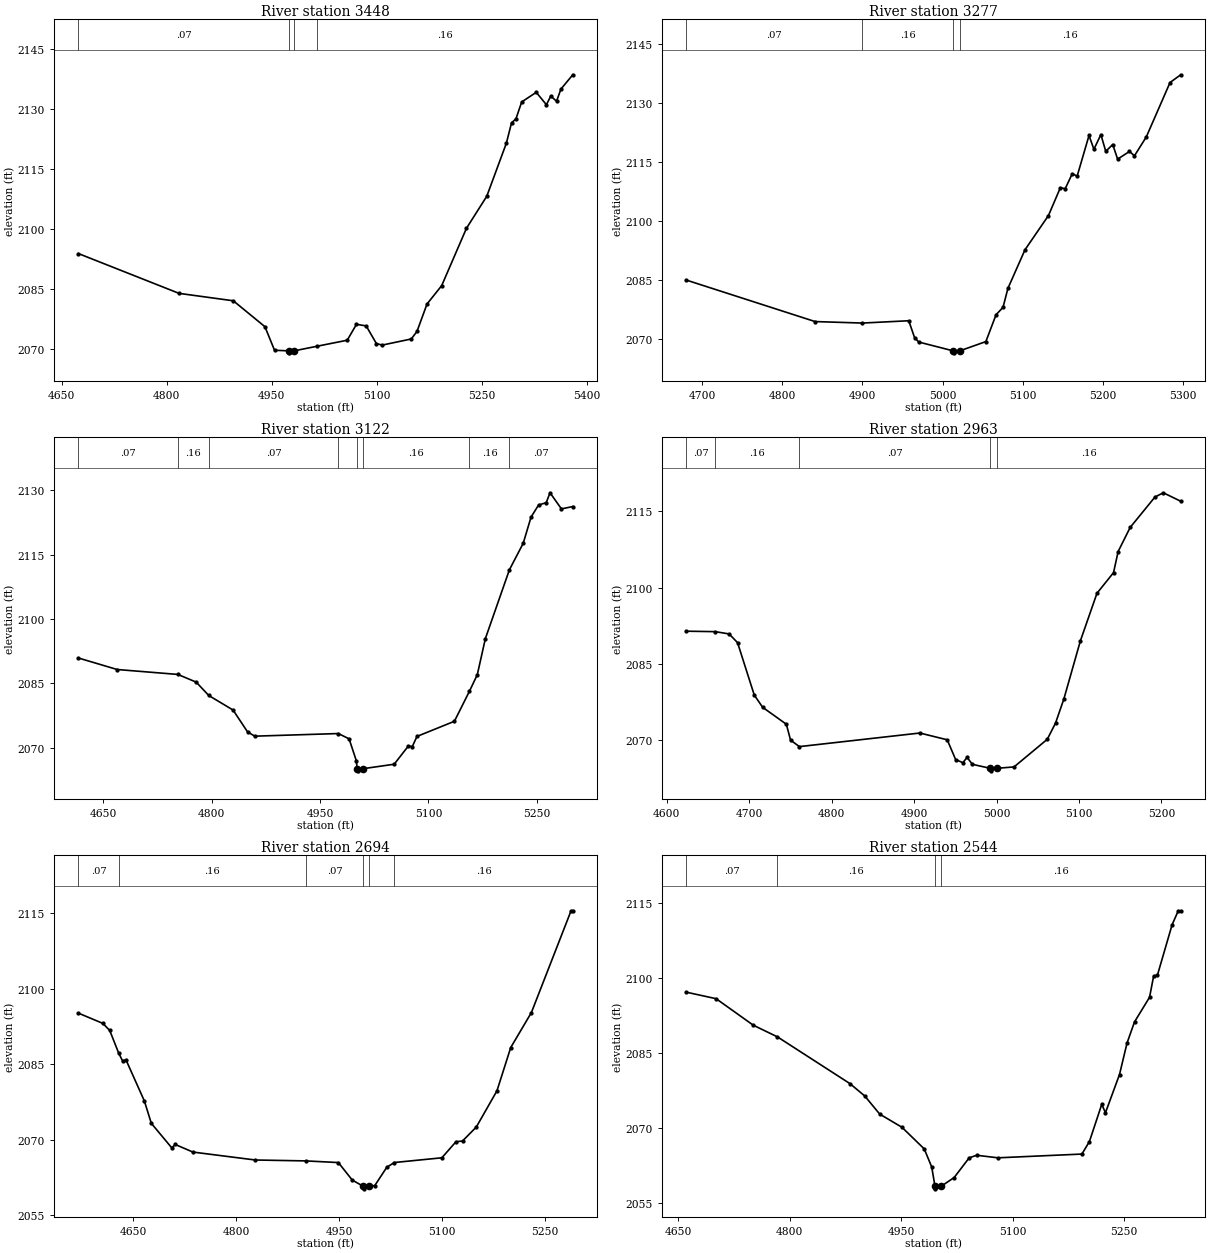
Type RM Length L Ch R = 1,3448,171,171,171
BEGIN DESCRIPTION:
Pleasant Run 3448.34
END DESCRIPTION:
XS GIS Cut Line= 3
      1522388.21      6768797.77      1522678.10      6768679.73
      1522990.31      6768440.37
#Sta/Elev= 30
  4673.7 2093.90  4817.5 2083.97  4895.0 2082.12  4940.2 2075.65  4953.9 2069.77
  4973.9 2069.63  4974.4 2069.13  4982.0 2069.63  5014.2 2070.76  5057.8 2072.28
  5071.0 2076.25  5084.9 2075.85  5099.4 2071.46  5107.7 2071.06  5149.3 2072.59
  5157.5 2074.48  5171.8 2081.31  5192.8 2085.91  5228.2 2100.22  5257.2 2108.20
  5285.2 2121.45  5292.6 2126.53  5298.9 2127.52  5307.1 2131.74  5327.9 2134.14
  5342.4 2131.05  5348.7 2133.21  5356.9 2131.91  5363.2 2134.96  5380.1 2138.52
#Mann=4,-1,0
  4673.7    0.07       0  4973.9    0.07       0  4982.0    0.07       0
  5014.2    0.16       0
Bank Sta=4973.9,4982
Exp/Cntr=0.3,0.1

Type RM Length L Ch R = 1,3277,155,155,155
BEGIN DESCRIPTION:
Pleasant Run 3277.25
END DESCRIPTION:
XS GIS Cut Line= 3
      1522553.09      6768797.79      1522855.19      6768691.88
      1523025.32      6768448.83
#Sta/Elev= 30
  4680.4 2084.89  4841.0 2074.32  4900.0 2073.94  4957.9 2074.53  4965.1 2070.24
  4970.4 2069.10  5013.4 2066.85  5013.9 2066.35  5021.5 2066.85  5054.1 2069.22
  5066.8 2076.06  5075.5 2077.94  5081.6 2082.78  5102.9 2092.61  5132.2 2101.35
  5147.0 2108.42  5153.1 2108.19  5161.9 2112.01  5168.0 2111.38  5182.8 2121.75
  5188.9 2118.23  5197.6 2121.97  5203.7 2117.71  5212.4 2119.45  5218.5 2115.72
  5233.3 2117.68  5239.5 2116.57  5254.3 2121.39  5283.9 2135.25  5297.2 2137.22
#Mann=4,-1,0
  4680.4    0.07       0  4900.0    0.16       0  5013.4    0.07       0
  5021.5    0.16       0
Bank Sta=5013.4,5021.5
Exp/Cntr=0.3,0.1

Type RM Length L Ch R = 1,3122,159,159,159
BEGIN DESCRIPTION:
Pleasant Run 3121.92
END DESCRIPTION:
XS GIS Cut Line= 3
      1522471.54      6768846.39      1522860.39      6768815.14
      1523139.93      6768723.12
#Sta/Elev= 30
  4615.4 2090.89  4669.0 2088.21  4753.1 2087.06  4778.5 2085.26  4795.8 2082.15
  4829.5 2078.75  4849.6 2073.64  4859.6 2072.66  4975.2 2073.27  4990.1 2072.04
  5000.1 2066.94  5001.3 2065.07  5001.8 2064.57  5009.4 2065.07  5052.5 2066.11
  5072.3 2070.39  5077.6 2070.23  5084.1 2072.60  5135.9 2076.13  5156.8 2083.16
  5167.6 2086.99  5178.8 2095.43  5212.1 2111.49  5231.2 2117.66  5242.0 2123.76
  5252.5 2126.60  5263.0 2127.12  5268.3 2129.44  5284.1 2125.68  5299.8 2126.23
#Mann=8,-1,0
  4615.4    0.07       0  4753.1    0.16       0  4795.8    0.07       0
  4975.2    0.16       0  5001.3    0.07       0  5009.4    0.16       0
  5156.8    0.16       0  5212.1    0.07       0
Bank Sta=5001.3,5009.4
Exp/Cntr=0.3,0.1

Type RM Length L Ch R = 1,2963,269,269,269
BEGIN DESCRIPTION:
Pleasant Run 2962.87
END DESCRIPTION:
XS GIS Cut Line= 3
      1522534.03      6768889.80      1522900.32      6768959.24
      1523126.00      6768934.94
#Sta/Elev= 30
  4623.7 2091.42  4658.8 2091.33  4675.6 2090.88  4685.8 2089.17  4706.1 2078.86
  4716.3 2076.46  4745.0 2073.14  4750.1 2070.02  4760.8 2068.74  4907.0 2071.41
  4940.2 2070.08  4950.4 2066.20  4959.2 2065.58  4964.3 2066.63  4970.7 2065.26
  4992.3 2064.48  4992.8 2063.98  5000.5 2064.48  5021.3 2064.75  5061.6 2070.18
  5071.6 2073.35  5081.7 2078.08  5101.8 2089.53  5121.9 2098.87  5142.0 2102.93
  5147.6 2107.08  5162.2 2111.81  5192.3 2117.79  5202.4 2118.62  5223.5 2116.96
#Mann=5,-1,0
  4623.7    0.07       0  4658.8    0.16       0  4760.8    0.07       0
  4992.3    0.07       0  5000.5    0.16       0
Bank Sta=4992.3,5000.5
Exp/Cntr=0.3,0.1

Type RM Length L Ch R = 1,2694,150,150,150
BEGIN DESCRIPTION:
Pleasant Run 2693.89
END DESCRIPTION:
XS GIS Cut Line= 3
      1522429.79      6769153.68      1522855.19      6769212.71
      1523145.10      6769188.41
#Sta/Elev= 30
  4570.1 2095.16  4605.6 2093.13  4615.7 2091.72  4628.8 2087.18  4634.4 2085.66
  4639.4 2085.86  4666.2 2077.67  4676.3 2073.23  4706.1 2068.35  4711.2 2069.02
  4736.9 2067.51  4827.8 2065.93  4901.6 2065.75  4948.9 2065.42  4969.1 2061.94
  4985.2 2060.69  4985.7 2060.19  4993.4 2060.69  5002.0 2060.85  5019.5 2064.49
  5030.5 2065.43  5099.7 2066.37  5120.3 2069.57  5129.8 2069.71  5149.9 2072.49
  5180.0 2079.70  5200.1 2088.32  5230.2 2095.28  5288.0 2115.54  5290.5 2115.54
#Mann=6,-1,0
  4570.1    0.07       0  4628.8    0.16       0  4901.6    0.07       0
  4985.2    0.07       0  4993.4    0.07       0  5030.5    0.16       0
Bank Sta=4985.2,4993.4
Exp/Cntr=0.3,0.1

Type RM Length L Ch R = 1,2544,193,193,193
BEGIN DESCRIPTION:
Pleasant Run 2544.48
END DESCRIPTION:
XS GIS Cut Line= 3
      1522475.00      6769346.39      1522816.99      6769344.66
      1523136.47      6769297.78
#Sta/Elev= 30
  4661.0 2097.22  4701.0 2095.92  4751.0 2090.62  4783.5 2088.29  4881.0 2078.95
  4901.0 2076.47  4921.0 2072.86  4951.0 2070.22  4981.0 2065.89  4991.0 2062.29
  4995.4 2058.42  4995.9 2057.92  5003.6 2058.42  5021.2 2060.18  5041.4 2064.12
  5051.5 2064.63  5080.0 2064.12  5193.0 2064.87  5203.1 2067.36  5219.7 2074.80
  5224.7 2073.13  5243.6 2080.77  5253.7 2087.05  5263.8 2091.29  5284.0 2096.20
  5289.5 2100.45  5294.5 2100.58  5314.3 2110.68  5322.6 2113.49  5325.9 2113.49
#Mann=4,-1,0
  4661.0    0.07       0  4783.5    0.16       0  4995.4    0.07       0
  5003.6    0.16       0
Bank Sta=4995.4,5003.6
Exp/Cntr=0.3,0.1

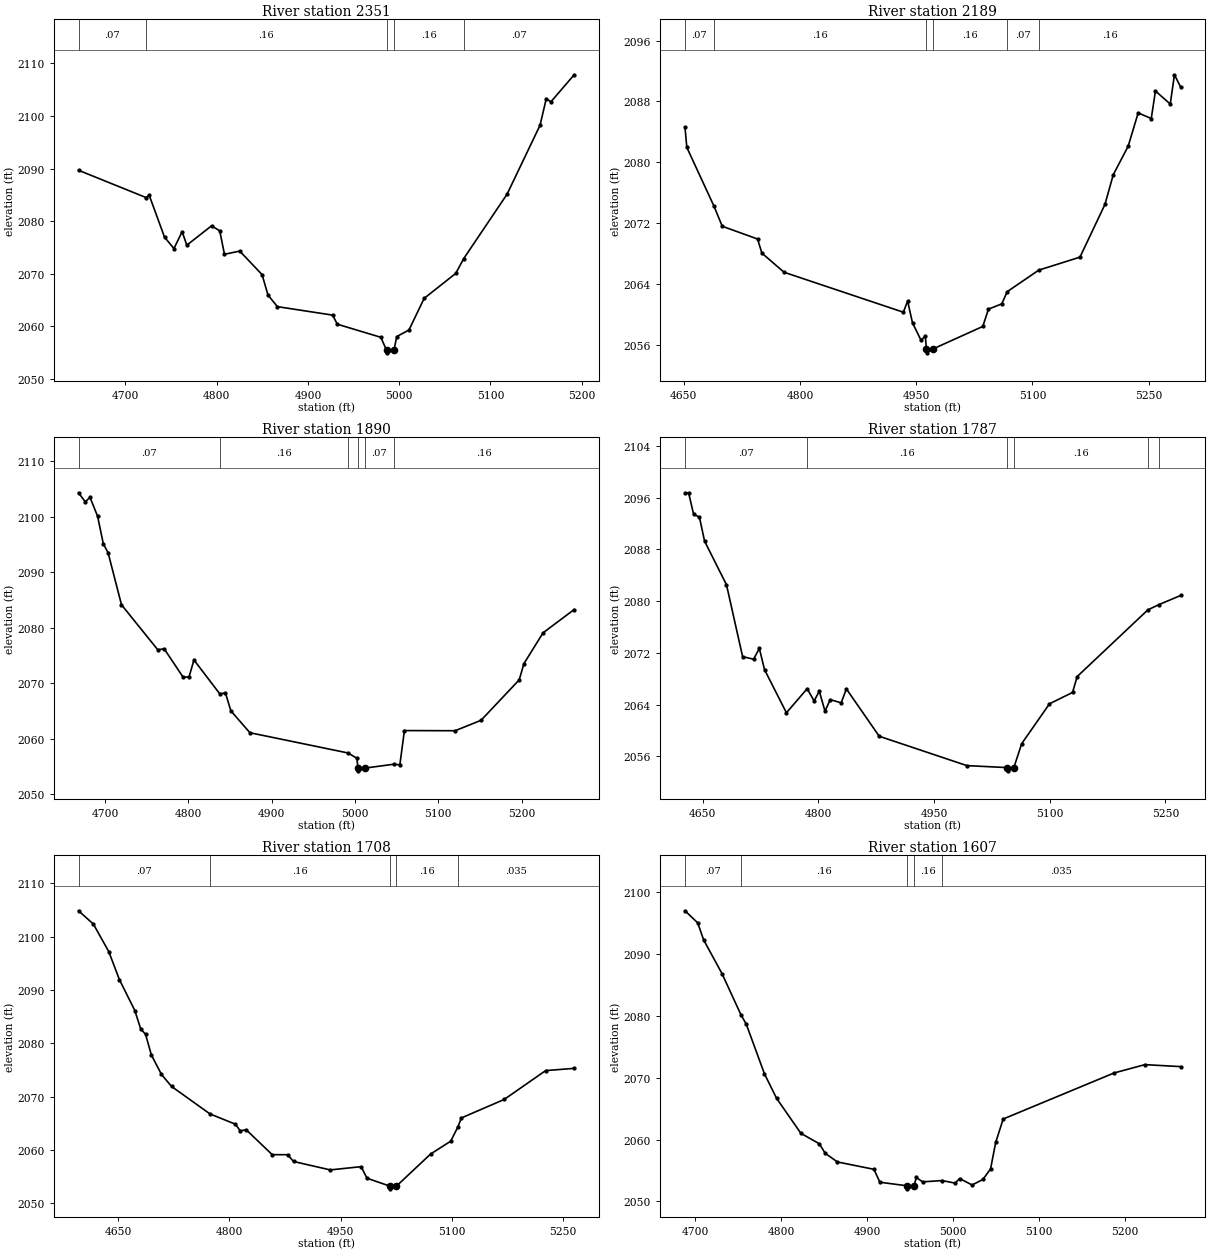
Type RM Length L Ch R = 1,2351,162,162,162
BEGIN DESCRIPTION:
Pleasant Run 2350.76
END DESCRIPTION:
XS GIS Cut Line= 3
      1522563.54      6769424.52      1522903.80      6769509.59
      1523091.50      6769466.54
#Sta/Elev= 30
  4648.5 2089.67  4722.6 2084.48  4726.0 2084.92  4742.8 2076.95  4753.1 2074.79
  4762.1 2078.00  4767.2 2075.43  4794.3 2079.11  4803.3 2078.16  4808.5 2073.70
  4825.2 2074.31  4849.7 2069.84  4856.2 2065.95  4866.5 2063.75  4927.0 2062.14
  4932.2 2060.41  4979.9 2057.92  4986.1 2055.47  4986.6 2054.97  4994.3 2055.47
  4997.3 2058.06  5010.7 2059.31  5027.4 2065.33  5062.0 2070.07  5070.6 2072.85
  5118.3 2085.14  5154.4 2098.23  5161.2 2103.28  5166.3 2102.68  5191.8 2107.82
#Mann=5,-1,0
  4648.5    0.07       0  4722.6    0.16       0  4986.1    0.07       0
  4994.3    0.16       0  5070.6    0.07       0
Bank Sta=4986.1,4994.3
Exp/Cntr=0.3,0.1

Type RM Length L Ch R = 1,2189,299,299,299
BEGIN DESCRIPTION:
Pleasant Run 2188.94
END DESCRIPTION:
XS GIS Cut Line= 3
      1522539.18      6769511.31      1522849.98      6769657.16
      1523126.01      6769549.52
#Sta/Elev= 30
  4651.7 2084.60  4654.1 2081.95  4688.9 2074.28  4699.8 2071.59  4745.4 2069.91
  4750.9 2068.06  4779.6 2065.54  4933.5 2060.29  4939.0 2061.76  4945.3 2058.89
  4956.3 2056.60  4961.8 2057.16  4963.3 2055.45  4963.8 2054.95  4971.5 2055.45
  5036.0 2058.42  5043.3 2060.69  5060.5 2061.39  5067.5 2062.99  5108.2 2065.82
  5161.4 2067.53  5193.6 2074.45  5204.4 2078.37  5223.6 2082.11  5236.5 2086.49
  5253.4 2085.75  5258.8 2089.37  5277.9 2087.65  5283.3 2091.50  5291.3 2089.89
#Mann=6,-1,0
  4651.7    0.07       0  4688.9    0.16       0  4963.3    0.07       0
  4971.5    0.16       0  5067.5    0.07       0  5108.2    0.16       0
Bank Sta=4963.3,4971.5
Exp/Cntr=0.3,0.1

Type RM Length L Ch R = 1,1890,103,103,103
BEGIN DESCRIPTION:
Pleasant Run 1890.01
END DESCRIPTION:
XS GIS Cut Line= 3
      1522754.97      6770038.02      1523045.32      6769877.23
      1523155.01      6769637.97
#Sta/Elev= 30
  4668.1 2104.34  4676.2 2102.71  4681.9 2103.51  4691.0 2100.12  4697.9 2095.12
  4703.6 2093.54  4719.7 2084.15  4763.2 2076.05  4771.0 2076.20  4793.9 2071.05
  4800.9 2071.19  4806.7 2074.20  4837.8 2068.07  4844.5 2068.27  4851.0 2065.03
  4873.9 2061.08  4991.7 2057.43  5002.3 2056.48  5003.6 2054.71  5004.1 2054.21
  5012.2 2054.71  5046.6 2055.40  5053.9 2055.30  5059.4 2061.47  5120.2 2061.44
  5151.4 2063.32  5197.2 2070.61  5202.9 2073.54  5225.9 2079.10  5263.2 2083.29
#Mann=6,-1,0
  4668.1    0.07       0  4837.8    0.16       0  4991.7    0.07       0
  5003.6    0.07       0  5012.2    0.07       0  5046.6    0.16       0
Bank Sta=5003.6,5012.2
Exp/Cntr=0.3,0.1

Type RM Length L Ch R = 1,1787,79,79,79
BEGIN DESCRIPTION:
Pleasant Run 1787.03
END DESCRIPTION:
XS GIS Cut Line= 3
      1522860.37      6770169.33      1523134.70      6769921.05
      1523287.45      6769695.39
#Sta/Elev= 30
  4627.2 2096.76  4631.9 2096.76  4638.4 2093.42  4645.9 2093.00  4652.6 2089.28
  4681.0 2082.53  4701.9 2071.41  4716.1 2071.01  4723.6 2072.68  4730.3 2069.40
  4758.7 2062.72  4785.6 2066.45  4794.6 2064.55  4801.3 2066.07  4808.7 2062.97
  4815.5 2064.76  4829.7 2064.26  4836.4 2066.42  4879.0 2059.09  4992.6 2054.55
  5044.9 2054.24  5045.4 2053.74  5053.5 2054.24  5063.7 2057.95  5099.7 2064.11
  5129.6 2065.87  5135.6 2068.33  5227.2 2078.64  5241.6 2079.46  5269.7 2080.87
#Mann=6,-1,0
  4627.2    0.07       0  4785.6    0.16       0  5044.9    0.07       0
  5053.5    0.16       0  5227.2   0.035       0  5241.6    0.07       0
Bank Sta=5044.9,5053.5
Exp/Cntr=0.3,0.1

Type RM Length L Ch R = 1,1708,101,101,101
BEGIN DESCRIPTION:
Pleasant Run 1708.23
END DESCRIPTION:
XS GIS Cut Line= 3
      1522877.77      6770228.32      1523190.26      6769976.60
      1523356.91      6769766.54
#Sta/Elev= 30
  4596.1 2104.84  4616.2 2102.34  4637.0 2097.17  4651.4 2091.90  4672.2 2086.12
  4680.1 2082.67  4686.6 2081.68  4694.5 2077.79  4708.1 2074.15  4721.8 2071.88
  4773.7 2066.73  4808.1 2064.80  4814.5 2063.55  4822.5 2063.77  4857.7 2059.09
  4878.5 2059.08  4886.5 2057.81  4936.1 2056.23  4977.8 2056.84  4985.7 2054.67
  5016.8 2053.18  5017.3 2052.68  5025.4 2053.18  5071.6 2059.21  5098.8 2061.62
  5108.2 2064.23  5113.2 2065.98  5170.9 2069.44  5227.0 2074.86  5265.5 2075.28
#Mann=5,-1,0
  4596.1    0.07       0  4773.7    0.16       0  5016.8    0.07       0
  5025.4    0.16       0  5108.2   0.035       0
Bank Sta=5016.8,5025.4
Exp/Cntr=0.3,0.1

Type RM Length L Ch R = 1,1607,177,177,177
BEGIN DESCRIPTION:
Pleasant Run 1607.21
END DESCRIPTION:
XS GIS Cut Line= 3
      1523047.90      6770271.73      1523264.91      6770044.31
      1523412.49      6769827.28
#Sta/Elev= 30
  4688.1 2097.02  4702.9 2095.07  4709.8 2092.31  4731.2 2086.85  4753.1 2080.23
  4759.5 2078.64  4780.6 2070.63  4794.7 2066.67  4823.0 2061.00  4844.4 2059.32
  4851.3 2057.77  4865.5 2056.37  4908.0 2055.18  4914.9 2053.09  4946.1 2052.52
  4946.6 2052.02  4954.7 2052.52  4957.3 2053.86  4964.6 2053.15  4987.3 2053.36
  5002.4 2052.95  5007.8 2053.69  5022.2 2052.64  5034.8 2053.54  5043.7 2055.24
  5049.7 2059.54  5058.4 2063.32  5187.4 2070.77  5223.3 2072.12  5264.9 2071.80
#Mann=5,-1,0
  4688.1    0.07       0  4753.1    0.16       0  4946.1   0.035       0
  4954.7    0.16       0  4987.3   0.035       0
Bank Sta=4946.1,4954.7
Exp/Cntr=0.3,0.1