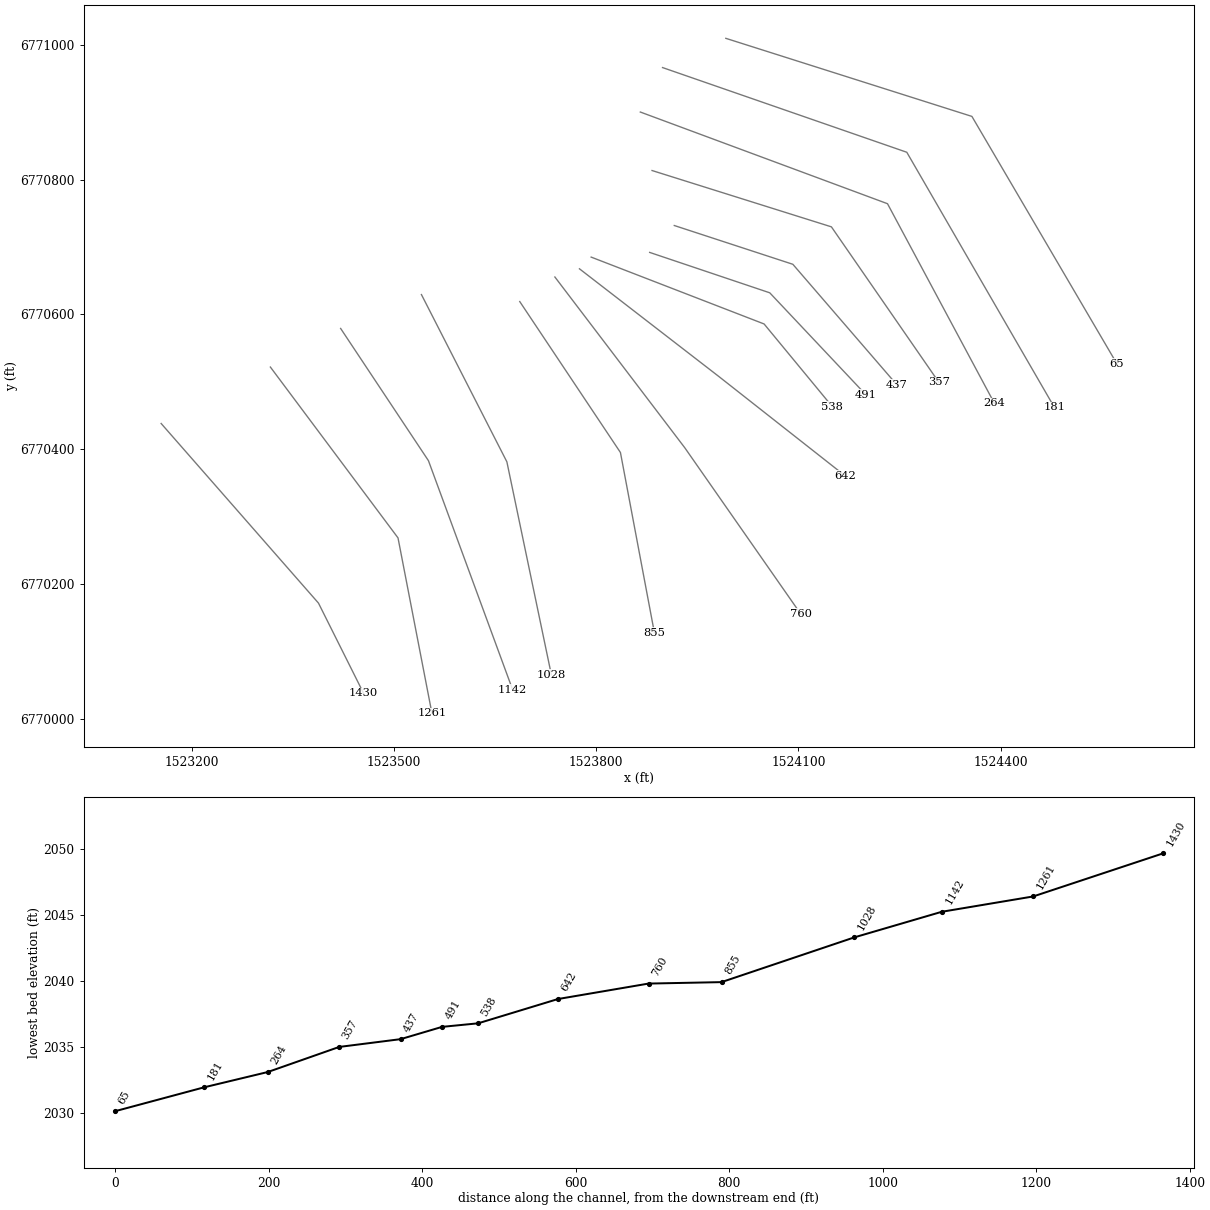
HEC-RAS study Pleasant Run.prj: Pleasant Run Base Level Engineering

--- Pleasant Run.g01 (geometry) --- (continued)

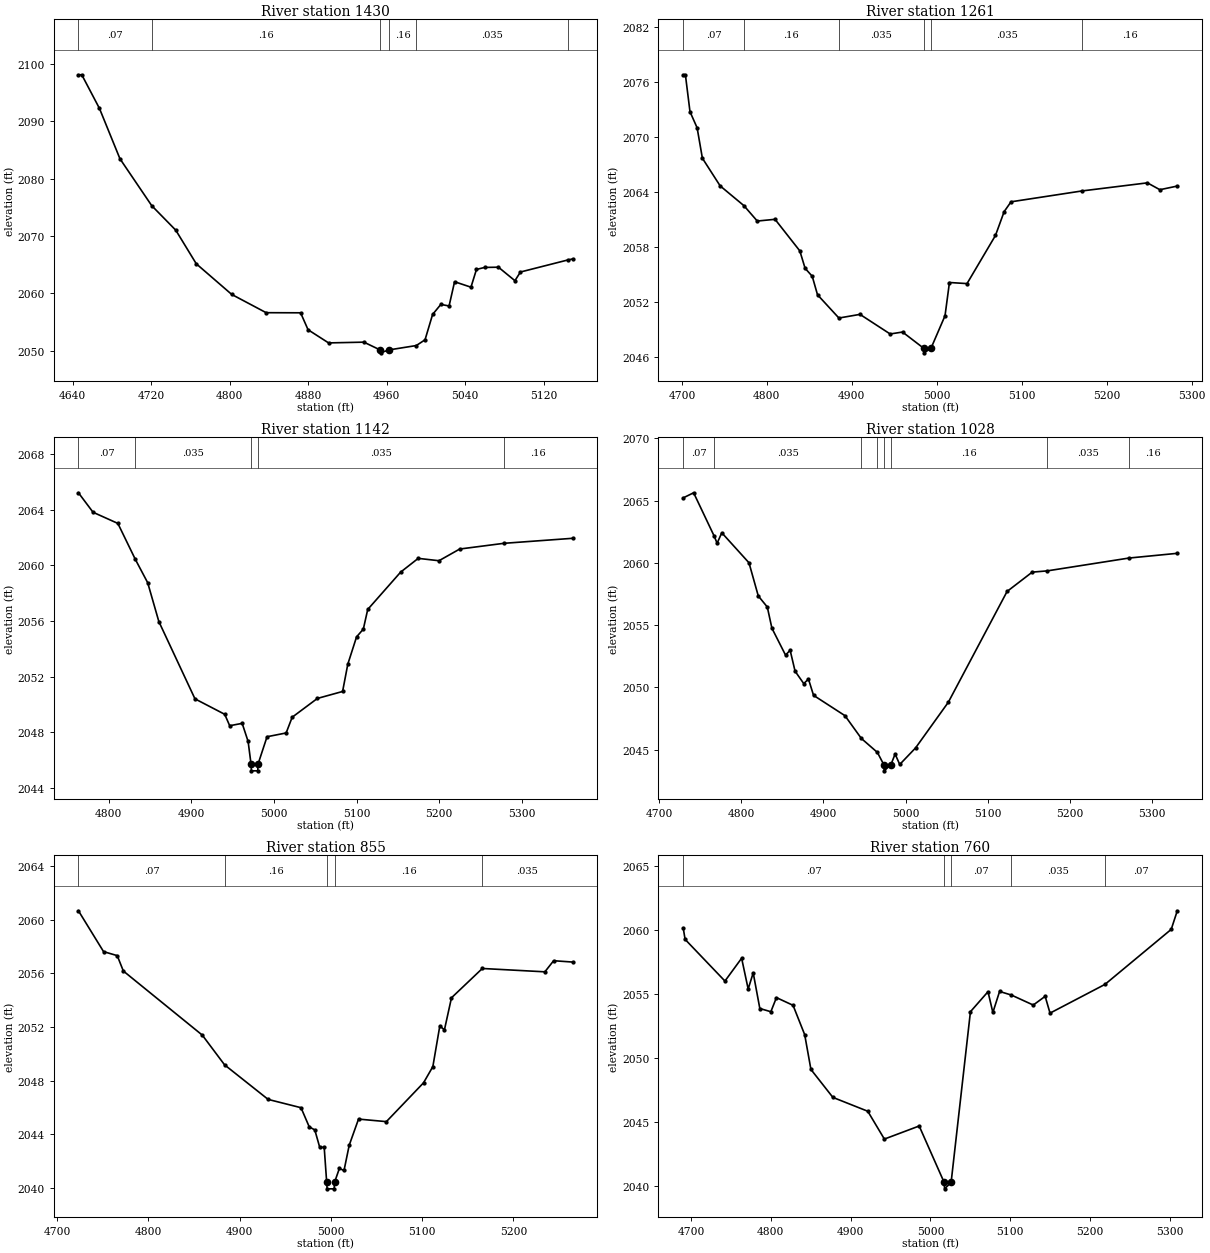
Type RM Length L Ch R = 1,1430,169,169,169
BEGIN DESCRIPTION:
Pleasant Run 1430.084
END DESCRIPTION:
XS GIS Cut Line= 3
      1523154.97      6770438.03      1523388.27      6770171.52
      1523455.01      6770037.97
#Sta/Elev= 30
  4645.8 2098.07  4649.2 2098.07  4667.2 2092.22  4688.1 2083.45  4720.5 2075.28
  4745.0 2071.01  4765.9 2065.16  4802.0 2059.83  4837.1 2056.65  4872.2 2056.63
  4879.8 2053.68  4900.7 2051.39  4936.7 2051.52  4953.3 2050.16  4953.8 2049.66
  4961.9 2050.16  4990.1 2050.93  4999.0 2051.93  5006.7 2056.34  5015.1 2058.09
  5023.5 2057.82  5029.1 2062.04  5045.8 2061.09  5051.4 2064.18  5059.8 2064.53
  5073.8 2064.57  5090.6 2062.22  5096.2 2063.73  5144.3 2065.82  5149.3 2066.00
#Mann=6,-1,0
  4645.8    0.07       0  4720.5    0.16       0  4953.3   0.035       0
  4961.9    0.16       0  4990.1   0.035       0  5144.3    0.16       0
Bank Sta=4953.3,4961.9
Exp/Cntr=0.3,0.1

Type RM Length L Ch R = 1,1261,119,119,119
BEGIN DESCRIPTION:
Pleasant Run 1261.09
END DESCRIPTION:
XS GIS Cut Line= 3
      1523316.96      6770521.78      1523506.23      6770268.27
      1523556.57      6770007.86
#Sta/Elev= 30
  4701.5 2076.76  4704.1 2076.76  4709.5 2072.73  4717.9 2070.97  4724.1 2067.65
  4745.0 2064.63  4773.0 2062.47  4788.7 2060.79  4809.6 2060.98  4838.8 2057.53
  4845.0 2055.63  4853.4 2054.76  4859.6 2052.74  4884.8 2050.20  4909.6 2050.60
  4945.1 2048.46  4959.7 2048.67  4984.6 2046.90  4985.1 2046.40  4993.2 2046.90
  5009.7 2050.45  5014.9 2054.08  5035.6 2053.96  5069.1 2059.22  5079.3 2061.82
  5087.4 2062.89  5171.2 2064.08  5247.9 2064.96  5262.6 2064.21  5283.1 2064.61
#Mann=6,-1,0
  4701.5    0.07       0  4773.0    0.16       0  4884.8   0.035       0
  4984.6   0.035       0  4993.2   0.035       0  5171.2    0.16       0
Bank Sta=4984.6,4993.2
Exp/Cntr=0.3,0.1

Type RM Length L Ch R = 1,1142,114,114,114
BEGIN DESCRIPTION:
Pleasant Run 1141.82
END DESCRIPTION:
XS GIS Cut Line= 3
      1523421.14      6770579.07      1523551.37      6770382.85
      1523676.29      6770042.77
#Sta/Elev= 30
  4763.4 2065.21  4781.1 2063.81  4811.1 2063.01  4832.3 2060.42  4847.2 2058.75
  4860.7 2055.96  4904.4 2050.41  4940.4 2049.30  4946.4 2048.48  4961.5 2048.65
  4968.7 2047.35  4972.2 2045.74  4972.7 2045.24  4980.3 2045.24  4980.8 2045.74
  4991.6 2047.69  5014.7 2047.96  5022.0 2049.09  5052.5 2050.44  5083.0 2050.94
  5089.3 2052.90  5099.9 2054.86  5108.1 2055.42  5113.4 2056.83  5153.2 2059.51
  5174.5 2060.50  5199.6 2060.33  5224.7 2061.17  5278.1 2061.58  5361.2 2061.94
#Mann=5,-1,0
  4763.4    0.07       0  4832.3   0.035       0  4972.2   0.035       0
  4980.8   0.035       0  5278.1    0.16       0
Bank Sta=4972.2,4980.8
Exp/Cntr=0.3,0.1

Type RM Length L Ch R = 1,1028,173,173,173
BEGIN DESCRIPTION:
Pleasant Run 1028.46
END DESCRIPTION:
XS GIS Cut Line= 3
      1523540.97      6770629.35      1523667.69      6770381.12
      1523733.66      6770065.14
#Sta/Elev= 30
  4729.3 2065.21  4742.0 2065.62  4766.9 2062.16  4770.6 2061.57  4776.3 2062.41
  4809.4 2060.00  4820.7 2057.34  4831.7 2056.45  4837.3 2054.75  4853.9 2052.59
  4859.5 2052.98  4865.5 2051.30  4876.1 2050.30  4881.8 2050.67  4888.0 2049.36
  4926.2 2047.73  4946.2 2045.90  4965.7 2044.78  4973.5 2043.80  4974.0 2043.30
  4982.2 2043.80  4987.3 2044.65  4992.9 2043.81  5012.2 2045.14  5052.1 2048.81
  5123.6 2057.70  5154.2 2059.25  5172.4 2059.35  5271.9 2060.38  5330.8 2060.76
#Mann=8,-1,0
  4729.3    0.07       0  4766.9   0.035       0  4946.2    0.07       0
  4965.7    0.16       0  4973.5    0.07       0  4982.2    0.16       0
  5172.4   0.035       0  5271.9    0.16       0
Bank Sta=4973.5,4982.2
Exp/Cntr=0.3,0.1

Type RM Length L Ch R = 1,855,95,95,95
BEGIN DESCRIPTION:
Pleasant Run 855.06
END DESCRIPTION:
XS GIS Cut Line= 3
      1523686.79      6770618.95      1523836.09      6770395.00
      1523886.43      6770127.66
#Sta/Elev= 30
  4723.5 2060.68  4751.0 2057.63  4766.0 2057.33  4772.7 2056.18  4859.2 2051.39
  4883.6 2049.17  4931.3 2046.59  4967.3 2045.97  4976.3 2044.54  4982.4 2044.31
  4987.8 2043.01  4992.7 2043.01  4995.4 2040.41  4995.9 2039.91  5003.6 2039.91
  5004.1 2040.41  5009.3 2041.43  5014.4 2041.28  5020.1 2043.17  5030.3 2045.12
  5060.8 2044.93  5101.5 2047.83  5111.7 2049.04  5119.3 2052.07  5124.4 2051.79
  5132.1 2054.18  5165.9 2056.37  5234.4 2056.12  5244.0 2056.95  5264.7 2056.85
#Mann=5,-1,0
  4723.5    0.07       0  4883.6    0.16       0  4995.4    0.07       0
  5004.1    0.16       0  5165.9   0.035       0
Bank Sta=4995.4,5004.1
Exp/Cntr=0.3,0.1

Type RM Length L Ch R = 1,760,118,118,118
BEGIN DESCRIPTION:
Pleasant Run 759.8
END DESCRIPTION:
XS GIS Cut Line= 3
      1523738.88      6770655.41      1523931.57      6770401.95
      1524103.44      6770155.44
#Sta/Elev= 30
  4690.3 2060.15  4692.7 2059.25  4742.6 2056.00  4763.5 2057.78  4771.7 2055.38
  4778.0 2056.64  4786.3 2053.86  4800.1 2053.61  4807.1 2054.71  4827.9 2054.11
  4842.5 2051.82  4850.3 2049.11  4877.8 2046.93  4921.5 2045.85  4942.3 2043.68
  4985.9 2044.70  5017.2 2040.30  5017.7 2039.80  5025.9 2040.30  5050.1 2053.61
  5072.1 2055.17  5078.2 2053.55  5086.6 2055.19  5101.4 2054.91  5128.8 2054.13
  5143.7 2054.81  5149.8 2053.50  5218.6 2055.74  5301.6 2060.03  5309.2 2061.48
#Mann=5,-1,0
  4690.3    0.07       0  5017.2    0.07       0  5025.9    0.07       0
  5101.4   0.035       0  5218.6    0.07       0
Bank Sta=5017.2,5025.9
Exp/Cntr=0.3,0.1

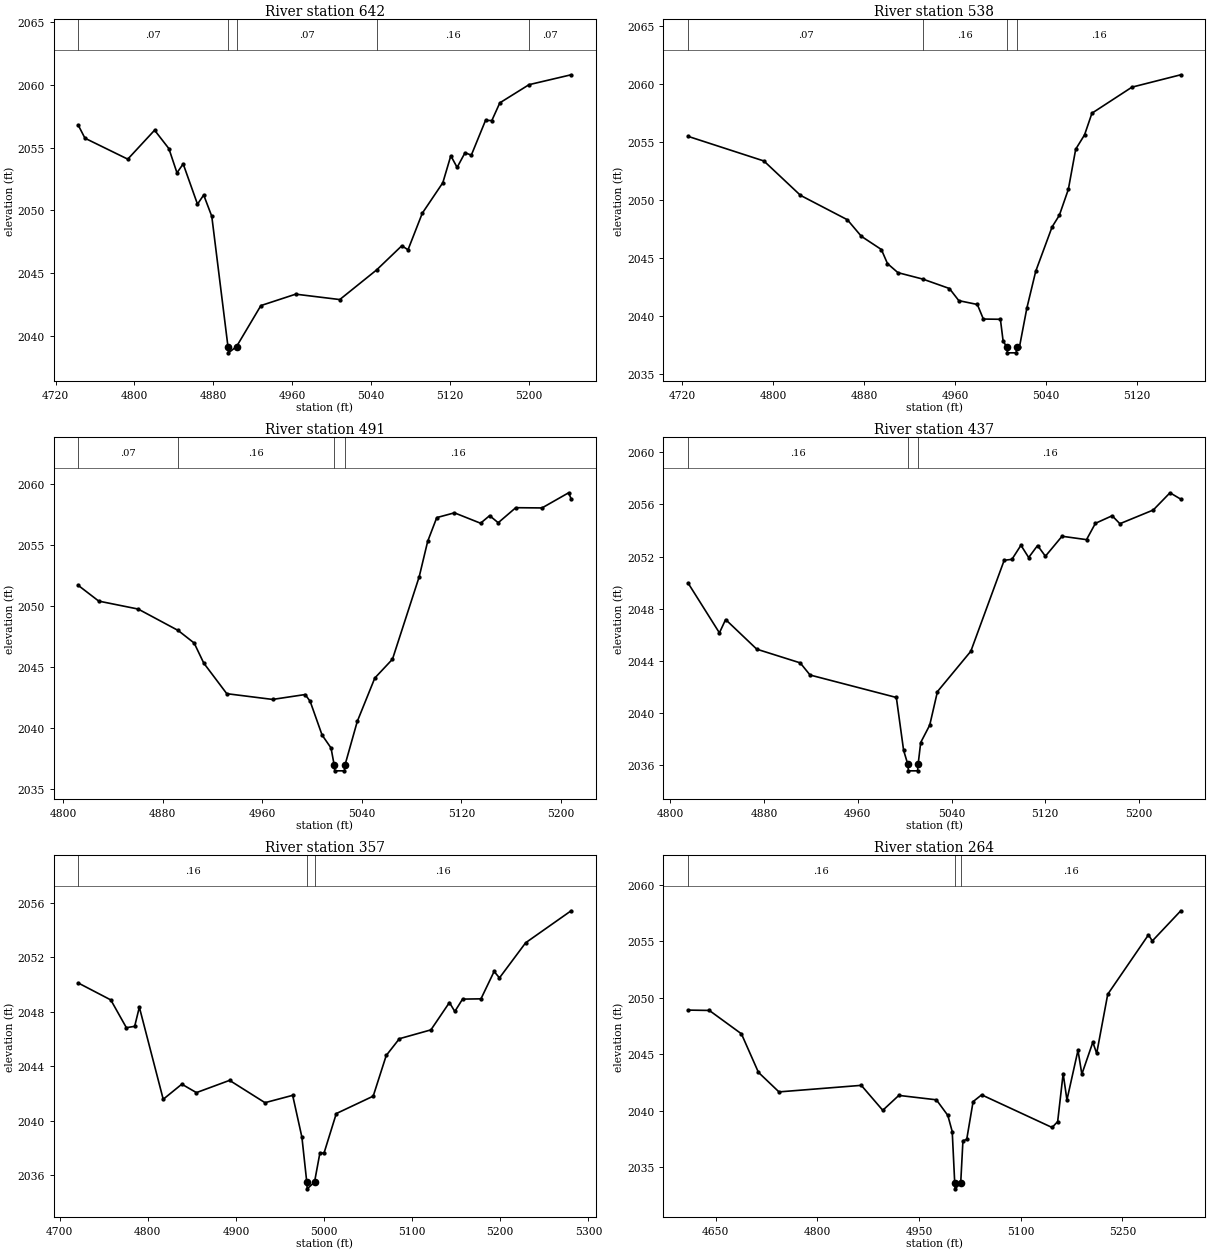
Type RM Length L Ch R = 1,642,104,104,104
BEGIN DESCRIPTION:
Pleasant Run 641.53
END DESCRIPTION:
XS GIS Cut Line= 3
      1523775.33      6770667.57      1523981.92      6770507.85
      1524169.39      6770360.31
#Sta/Elev= 30
  4743.1 2056.77  4749.8 2055.75  4793.2 2054.08  4820.4 2056.39  4834.9 2054.92
  4843.1 2052.99  4849.4 2053.70  4863.9 2050.49  4870.2 2051.22  4878.4 2049.52
  4894.8 2039.13  4895.3 2038.63  4903.5 2039.13  4928.2 2042.40  4963.5 2043.31
  5008.2 2042.88  5045.5 2045.24  5071.1 2047.17  5077.4 2046.85  5091.9 2049.77
  5112.7 2052.20  5120.8 2054.35  5127.2 2053.42  5135.2 2054.59  5141.6 2054.40
  5156.0 2057.17  5162.4 2057.16  5170.5 2058.57  5200.1 2060.02  5242.8 2060.81
#Mann=5,-1,0
  4743.1    0.07       0  4894.8    0.07       0  4903.5    0.07       0
  5045.5    0.16       0  5200.1    0.07       0
Bank Sta=4894.8,4903.5
Exp/Cntr=0.3,0.1

Type RM Length L Ch R = 1,538,47,47,47
BEGIN DESCRIPTION:
Pleasant Run 538.352
END DESCRIPTION:
XS GIS Cut Line= 3
      1523792.66      6770684.95      1524049.13      6770585.72
      1524150.16      6770463.20
#Sta/Elev= 30
  4725.0 2055.50  4791.8 2053.37  4824.0 2050.40  4865.3 2048.29  4877.6 2046.86
  4895.2 2045.72  4900.6 2044.50  4909.8 2043.72  4931.8 2043.16  4955.1 2042.35
  4963.4 2041.30  4979.7 2040.97  4985.0 2039.71  5000.0 2039.69  5002.4 2037.80
  5005.7 2037.29  5006.2 2036.79  5013.9 2036.79  5014.4 2037.29  5016.8 2037.31
  5023.3 2040.66  5031.1 2043.84  5045.5 2047.67  5051.9 2048.68  5059.8 2050.91
  5066.3 2054.39  5074.1 2055.63  5080.6 2057.50  5115.8 2059.75  5158.8 2060.82
#Mann=4,-1,0
  4725.0    0.07       0  4931.8    0.16       0  5005.7    0.07       0
  5014.4    0.16       0
Bank Sta=5005.7,5014.4
Exp/Cntr=0.3,0.1

Type RM Length L Ch R = 1,491,54,54,54
BEGIN DESCRIPTION:
Pleasant Run 4621
END DESCRIPTION:
XS GIS Cut Line= 3
      1523879.45      6770691.90      1524057.53      6770631.96
      1524200.32      6770480.44
#Sta/Elev= 30
  4812.1 2051.68  4828.5 2050.40  4860.2 2049.75  4892.3 2048.00  4905.2 2046.97
  4912.9 2045.33  4931.4 2042.83  4968.2 2042.36  4994.4 2042.76  4998.4 2042.21
  5008.0 2039.45  5015.2 2038.39  5017.7 2037.02  5018.2 2036.52  5026.0 2036.52
  5026.5 2037.02  5036.3 2040.56  5050.4 2044.11  5064.6 2045.65  5086.1 2052.40
  5092.9 2055.29  5100.2 2057.23  5114.4 2057.62  5135.4 2056.77  5142.7 2057.39
  5149.6 2056.81  5163.7 2058.04  5184.8 2058.02  5206.2 2059.26  5208.2 2058.77
#Mann=4,-1,0
  4812.1    0.07       0  4892.3    0.16       0  5017.7    0.07       0
  5026.5    0.16       0
Bank Sta=5017.7,5026.5
Exp/Cntr=0.3,0.1

Type RM Length L Ch R = 1,437,80,80,80
BEGIN DESCRIPTION:
Pleasant Run 4620
END DESCRIPTION:
XS GIS Cut Line= 3
      1523915.95      6770731.81      1524091.78      6770674.28
      1524245.79      6770495.72
#Sta/Elev= 30
  4815.0 2049.98  4841.8 2046.16  4847.1 2047.18  4873.7 2044.91  4910.8 2043.86
  4919.2 2042.93  4992.9 2041.21  4999.1 2037.16  5002.7 2036.09  5003.2 2035.59
  5011.0 2035.59  5011.5 2036.09  5013.7 2037.76  5021.4 2039.09  5028.0 2041.66
  5056.5 2044.75  5085.0 2051.72  5091.6 2051.79  5099.3 2052.87  5105.9 2051.93
  5113.5 2052.85  5120.2 2052.03  5134.4 2053.56  5155.3 2053.30  5162.9 2054.55
  5177.2 2055.13  5183.8 2054.52  5212.3 2055.57  5226.6 2056.89  5235.8 2056.40
#Mann=3,-1,0
  4815.0    0.16       0  5002.7    0.07       0  5011.5    0.16       0
Bank Sta=5002.7,5011.5
Exp/Cntr=0.3,0.1

Type RM Length L Ch R = 1,357,93,93,93
BEGIN DESCRIPTION:
Pleasant Run 4619
END DESCRIPTION:
XS GIS Cut Line= 3
      1523882.97      6770813.41      1524148.95      6770729.84
      1524308.33      6770499.14
#Sta/Elev= 30
  4721.2 2050.12  4758.0 2048.88  4775.7 2046.84  4785.1 2046.94  4790.4 2048.35
  4817.5 2041.58  4838.6 2042.69  4855.2 2042.07  4892.8 2042.97  4933.0 2041.33
  4964.4 2041.87  4974.9 2038.79  4980.4 2035.50  4980.9 2035.00  4989.2 2035.50
  4995.3 2037.63  5000.0 2037.63  5013.9 2040.53  5055.8 2041.81  5070.6 2044.80
  5085.5 2046.03  5121.3 2046.68  5142.3 2048.69  5148.4 2048.03  5157.2 2048.94
  5178.1 2048.96  5193.0 2050.97  5199.1 2050.50  5228.8 2053.08  5280.4 2055.43
#Mann=3,-1,0
  4721.2    0.16       0  4980.4    0.07       0  4989.2    0.16       0
Bank Sta=4980.4,4989.2
Exp/Cntr=0.3,0.1

Type RM Length L Ch R = 1,264,83,83,83
BEGIN DESCRIPTION:
Pleasant Run 4618
END DESCRIPTION:
XS GIS Cut Line= 3
      1523865.57      6770900.22      1524232.14      6770764.17
      1524390.80      6770467.76
#Sta/Elev= 30
  4609.0 2048.92  4640.4 2048.89  4687.8 2046.82  4712.9 2043.41  4743.2 2041.68
  4864.7 2042.26  4896.4 2040.05  4920.1 2041.37  4975.5 2040.98  4992.4 2039.60
  4998.9 2038.17  5002.6 2033.60  5003.1 2033.10  5011.4 2033.60  5014.7 2037.35
  5020.3 2037.48  5029.7 2040.82  5042.3 2041.42  5146.3 2038.53  5154.5 2039.05
  5162.6 2043.30  5168.2 2040.97  5184.5 2045.36  5190.2 2043.25  5206.4 2046.07
  5212.1 2045.09  5228.4 2050.32  5288.5 2055.58  5294.2 2055.04  5336.2 2057.71
#Mann=3,-1,0
  4609.0    0.16       0  5002.6    0.07       0  5011.4    0.16       0
Bank Sta=5002.6,5011.4
Exp/Cntr=0.3,0.1

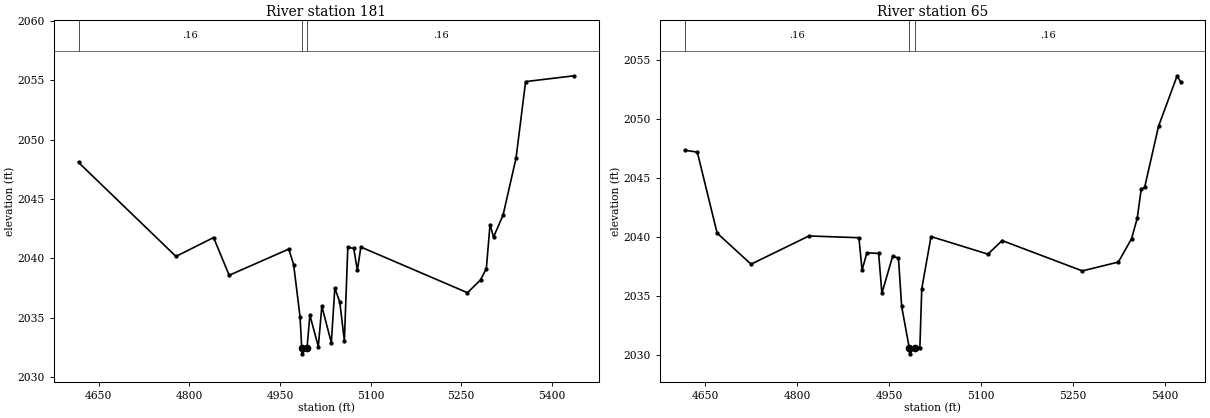
Type RM Length L Ch R = 1,181,116,116,116
BEGIN DESCRIPTION:
Pleasant Run 4617
END DESCRIPTION:
XS GIS Cut Line= 3
      1523898.54      6770966.20      1524260.76      6770840.52
      1524479.53      6770462.11
#Sta/Elev= 30
  4616.6 2048.07  4777.9 2040.15  4840.2 2041.74  4866.0 2038.56  4964.7 2040.77
  4972.7 2039.46  4983.3 2035.07  4986.1 2032.44  4986.6 2031.94  4994.9 2032.44
  4999.6 2035.20  5013.6 2032.55  5019.4 2035.95  5035.1 2032.88  5040.9 2037.50
  5049.1 2036.29  5056.7 2033.05  5062.4 2040.92  5072.2 2040.82  5078.2 2038.99
  5084.0 2040.94  5260.5 2037.09  5282.1 2038.17  5291.7 2039.12  5297.8 2042.83
  5303.6 2041.78  5319.4 2043.63  5340.9 2048.44  5356.7 2054.88  5437.1 2055.37
#Mann=3,-1,0
  4616.6    0.16       0  4986.1    0.07       0  4994.9    0.16       0
Bank Sta=4986.1,4994.9
Exp/Cntr=0.3,0.1

Type RM Length L Ch R = 1,65,0,0,0
BEGIN DESCRIPTION:
Pleasant Run 4616
END DESCRIPTION:
XS GIS Cut Line= 3
      1523992.37      6771009.58      1524357.32      6770893.72
      1524572.21      6770526.93
#Sta/Elev= 30
  4617.1 2047.36  4637.2 2047.21  4669.5 2040.35  4724.8 2037.72  4819.2 2040.11
  4900.6 2039.96  4905.8 2037.22  4913.6 2038.68  4932.8 2038.63  4938.1 2035.26
  4955.6 2038.38  4965.1 2038.25  4970.3 2034.16  4982.7 2030.63  4983.2 2030.13
  4991.5 2030.63  5000.0 2030.64  5003.1 2035.64  5018.2 2040.06  5110.9 2038.57
  5134.1 2039.72  5264.9 2037.15  5323.6 2037.90  5345.1 2039.88  5354.3 2041.59
  5360.8 2044.05  5366.5 2044.24  5389.1 2049.40  5419.4 2053.67  5425.1 2053.15
#Mann=3,-1,0
  4617.1    0.16       0  4982.7    0.07       0  4991.5    0.16       0
Bank Sta=4982.7,4991.5
Exp/Cntr=0.3,0.1

Chan Stop Cuts=-1