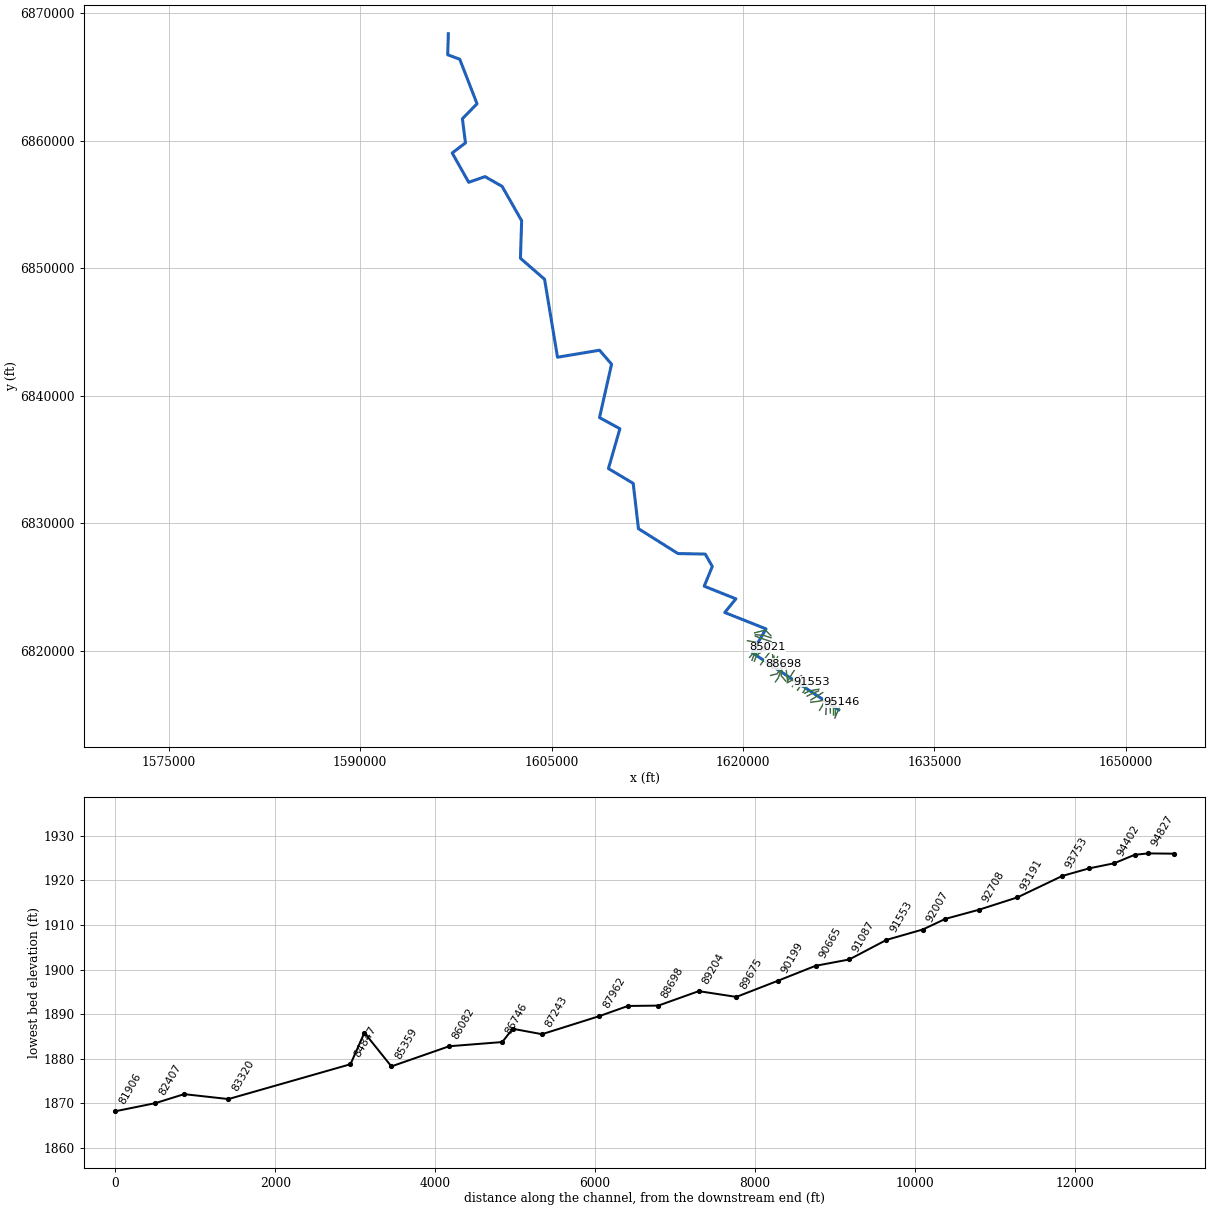
--- Rainy Creek.prj (project) ---

Proj Title=Rainy Creek Base Level Engineering
Current Plan=p01
Default Exp/Contr=0.3,0.1
English Units
Geom File=g01
Flow File=f01
Plan File=p01
Y Axis Title=Elevation
X Axis Title(PF)=Main Channel Distance
X Axis Title(XS)=Station
BEGIN DESCRIPTION:
Rainy Creek
END DESCRIPTION:
DSS Export Rating Curves= 0
DSS Export Rating Curve Sorted= 0
DSS Export Volume Flow Curves= 0
DXF OffsetX= 0
DXF OffsetY= 0
DXF ScaleX= 1
DXF ScaleY= 10

--- Rainy Creek.p01 (plan) ---

Plan Title=Multiple Run
Short Identifier=Multiple
Geom File=g01
Flow File=f01
Subcritical Flow
K Sum by GR= 0
Std Step Tol= 0.01
Critical Tol= 0.01
Num of Std Step Trials= 20
Max Error Tol= 0.3
Flow Tol Ratio= 0.001
Split Flow NTrial= 30
Split Flow Tol= 0.02
Split Flow Ratio= 0.02
Log Output Level= 0
Friction Slope Method= 1
Unsteady Friction Slope Method= 2
Unsteady Bridges Friction Slope Method= 1
Parabolic Critical Depth
Global Vel Dist=  1 , 1 , 1
Global Log Level= 0
CheckData=True
Encroach Param= -1, 0, 0, 0
BEGIN DESCRIPTION:
Multiple Run
END DESCRIPTION:

--- Rainy Creek.f01 (steady flow) ---

Flow Title=Multiple
Program Version=4.10
Number of Profiles= 7
Profile Names=10-year,25-year,50-year,1pct_min,100-year,1pct_plu,500-year
River Rch & RM=Rainy Creek,Reach-1         ,95146
     216     297     364     276     442     609     662
River Rch & RM=Rainy Creek,Reach-1         ,94089
     285     397     489     374     600     825     913
River Rch & RM=Rainy Creek,Reach-1         ,88318
     365     513     637     490     785    1080    1210
River Rch & RM=Rainy Creek,Reach-1         ,81345
     541     773     970     753    1210    1660    1890
River Rch & RM=Rainy Creek,Reach-1         ,69840
     641     925    1170     911    1460    2010    2310
River Rch & RM=Rainy Creek,Reach-1         ,68963
     641     925    1170     911    1460    2010    2310
River Rch & RM=Rainy Creek,Reach-1         ,60417
     714    1040    1310    1030    1640    2260    2620
River Rch & RM=Rainy Creek,Reach-1         ,55498
     862    1260    1600    1260    2020    2780    3250
River Rch & RM=Rainy Creek,Reach-1         ,53809
     862    1260    1600    1260    2020    2780    3250
River Rch & RM=Rainy Creek,Reach-1         ,53167
    1090    1610    2070    1640    2620    3610    4270
River Rch & RM=Rainy Creek,Reach-1         ,51746
    1090    1610    2070    1640    2620    3610    4270
River Rch & RM=Rainy Creek,Reach-1         ,51114
    1690    2530    3270    2600    4170    5740    6910
River Rch & RM=Rainy Creek,Reach-1         ,38838
    1700    2540    3280    2610    4180    5750    6890
River Rch & RM=Rainy Creek,Reach-1         ,34172
    2000    3000    3880    3090    4950    6820    8200
River Rch & RM=Rainy Creek,Reach-1         ,32133
    2000    3000    3880    3090    4950    6820    8200
River Rch & RM=Rainy Creek,Reach-1         ,25571
    2080    3110    4020    3210    5140    7070    8500
River Rch & RM=Rainy Creek,Reach-1         ,23955
    2080    3110    4020    3210    5140    7070    8500
River Rch & RM=Rainy Creek,Reach-1         ,19843
    2080    3120    4030    3210    5150    7090    8520
River Rch & RM=Rainy Creek,Reach-1         ,17586
    2220    3310    4290    3410    5470    7520    9030
River Rch & RM=Rainy Creek,Reach-1         ,16857
    2220    3310    4290    3410    5470    7520    9030
River Rch & RM=Rainy Creek,Reach-1         ,8001
    2270    3400    4400    3500    5610    7720    9270
River Rch & RM=Rainy Creek,Reach-1         ,5080
    2330    3480    4510    3590    5750    7910    9490
Boundary for River Rch & Prof#=Rainy Creek,Reach-1         , 1
Up Type= 0
Dn Type= 3
Dn Slope=0.001
Boundary for River Rch & Prof#=Rainy Creek,Reach-1         , 2
Up Type= 0
Dn Type= 3
Dn Slope=0.001
Boundary for River Rch & Prof#=Rainy Creek,Reach-1         , 3
Up Type= 0
Dn Type= 3
Dn Slope=0.001
Boundary for River Rch & Prof#=Rainy Creek,Reach-1         , 4
Up Type= 0
Dn Type= 3
Dn Slope=0.001
Boundary for River Rch & Prof#=Rainy Creek,Reach-1         , 5
Up Type= 0
Dn Type= 3
Dn Slope=0.001
Boundary for River Rch & Prof#=Rainy Creek,Reach-1         , 6
Up Type= 0
Dn Type= 3
Dn Slope=0.001
Boundary for River Rch & Prof#=Rainy Creek,Reach-1         , 7
Up Type= 0
Dn Type= 3
Dn Slope=0.001
DSS Import GetInterval= 0
DSS Import GetPeak= 0
DSS Import FillOption= 0

--- Rainy Creek.g01 (geometry) ---

Geom Title=Existing Conditions
Program Version=4.10

River Reach=Rainy Creek     ,Reach-1
Reach XY= 30
        1627505.        6815388.      1620721.18       6819871.3
        1621805.        6821738.      1618571.41       6823021.2
      1619446.09       6824094.5      1616963.16      6825081.95
      1617595.61      6826631.33      1617041.45      6827601.54
      1614906.56      6827641.76      1611806.62      6829594.03
      1611396.05      6833144.67      1609454.64      6834303.71
      1610353.64      6837428.35      1608755.39      6838301.91
      1609701.17      6842486.42       1608755.1      6843580.67
      1605463.12      6843031.29      1604449.54      6849140.45
      1602558.46      6850789.47      1602651.44      6853736.52
      1601118.21      6856424.37      1599779.96       6857188.5
      1598502.48      6856743.34      1597208.34      6859039.72
      1598249.17       6859835.7      1598006.11      6861725.92
       1599155.5      6862898.17      1597799.62      6866390.37
        1596858.       6866739.4        1596905.        6868388.

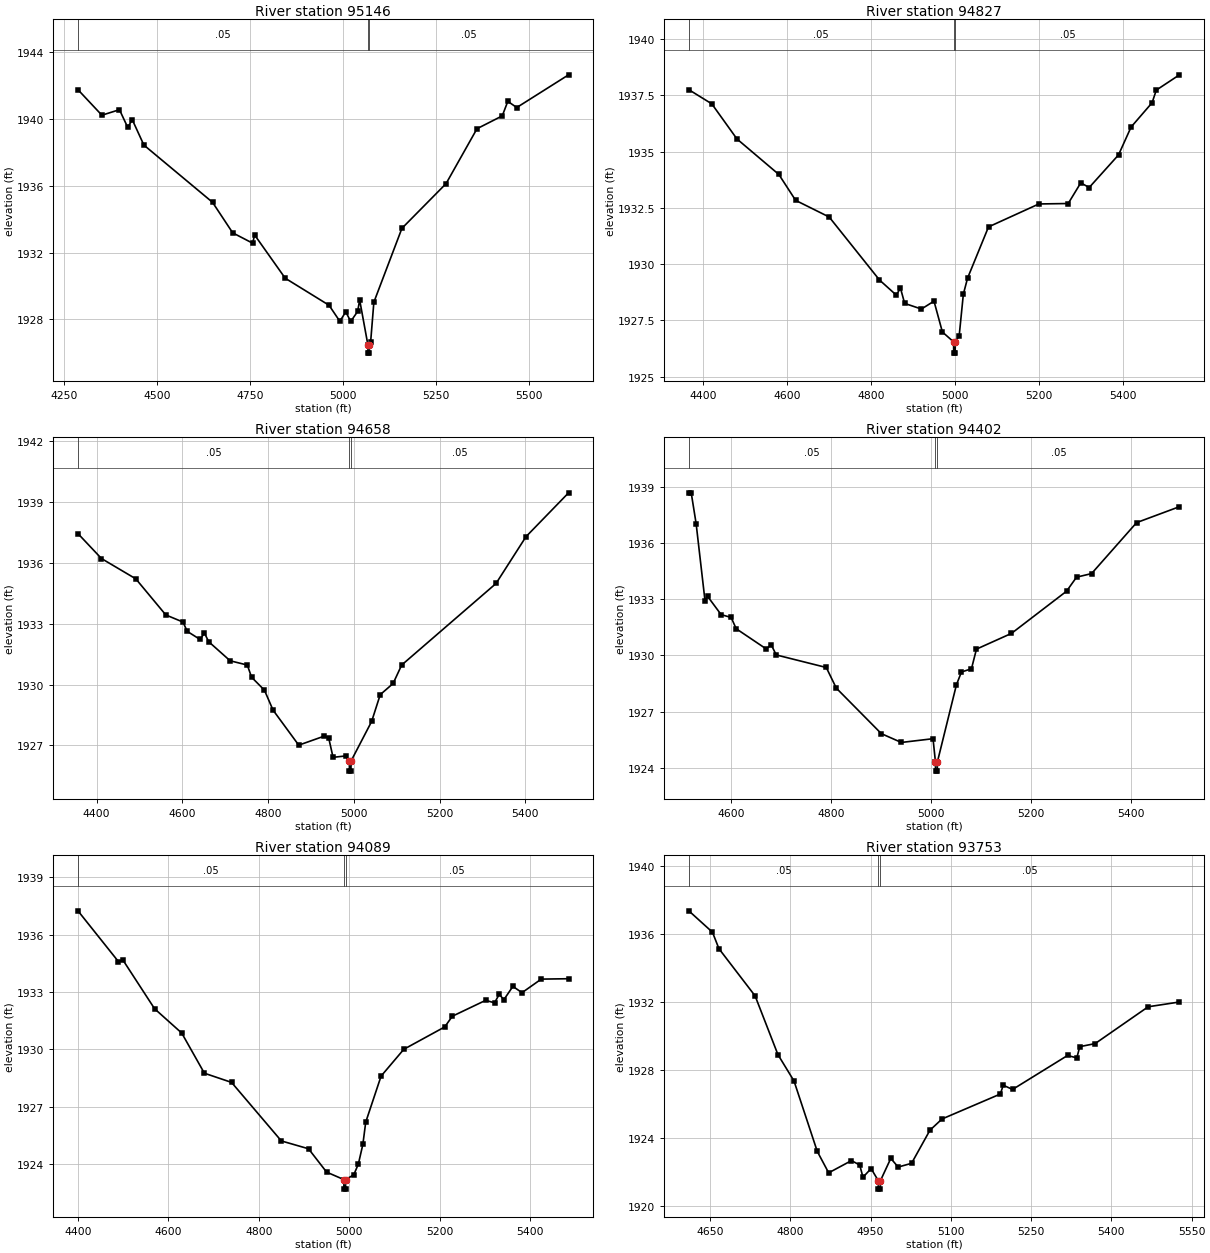
Type RM Length L Ch R = 1 ,95146   ,319,319,319
BEGIN DESCRIPTION:
Rainy Creek 94949.489
END DESCRIPTION:
XS GIS Cut Line= 3
      1627204.43      6814754.72      1627483.18      6815411.08
      1627712.15      6815973.24
#Sta/Elev= 30
  4286.9 1941.77  4351.3 1940.24  4398.6 1940.57  4420.8 1939.51  4433.1 1939.97
  4464.3 1938.45    4649 1935.02  4703.3 1933.19  4756.9 1932.57  4762.3 1933.06
  4844.6 1930.47  4962.5 1928.85  4991.5 1927.89  5007.5 1928.45  5020.9 1927.88
  5039.5 1928.48  5044.9 1929.17    5067 1926.48  5067.2 1925.98  5070.7 1925.98
    5071 1926.48  5074.4 1926.64  5083.1 1929.03  5158.6 1933.46  5277.4 1936.14
  5360.6 1939.43  5428.6  1940.2  5443.5 1941.07  5467.6  1940.7    5607 1942.66
#Mann= 3 ,-1 , 0
  4286.9     .05       0    5067     .03       0    5071     .05       0
Bank Sta=5067,5071
XS Rating Curve= 0 ,0
Exp/Cntr=0.3,0.1

Type RM Length L Ch R = 1 ,94827   ,169,169,169
BEGIN DESCRIPTION:
Rainy Creek 94826.7
END DESCRIPTION:
XS GIS Cut Line= 3
      1627239.65      6814953.25      1627248.33      6815590.39
      1627262.22      6816123.21
#Sta/Elev= 30
  4365.3 1937.75  4420.1 1937.12  4480.1 1935.56  4580.1 1933.98  4620.1 1932.83
  4700.1 1932.09  4820.1 1929.29  4860.1 1928.62  4870.1 1928.93  4880.1 1928.25
  4920.1    1928  4950.1 1928.35  4970.1 1926.98  4996.8 1926.54  4997.1 1926.04
  5000.6 1926.04  5000.8 1926.54  5010.1  1926.8  5020.1 1928.66  5030.1 1929.37
  5080.1 1931.65  5200.2 1932.67  5270.2 1932.69  5300.2 1933.61  5320.2  1933.4
  5390.2 1934.85  5420.2 1936.09  5470.3 1937.17  5480.3 1937.73  5535.5 1938.41
#Mann= 3 ,-1 , 0
  4365.3     .05       0  4996.8     .03       0  5000.8     .05       0
Bank Sta=4996.8,5000.8
XS Rating Curve= 0 ,0
Exp/Cntr=0.3,0.1

Type RM Length L Ch R = 1 ,94658   ,256,256,256
BEGIN DESCRIPTION:
Rainy Creek 94658.3
END DESCRIPTION:
XS GIS Cut Line= 3
      1627095.55      6814993.13      1627095.55        6815639.
      1627099.03      6816137.22
#Sta/Elev= 30
  4356.6 1937.44  4411.5 1936.21  4491.5 1935.21  4561.5 1933.43  4601.5 1933.08
  4611.5 1932.62  4641.5 1932.22  4651.5 1932.54  4661.5 1932.11  4711.5 1931.17
  4751.5 1930.96  4761.5 1930.36  4791.5 1929.72  4811.5 1928.74  4871.5 1927.01
  4931.5 1927.46  4941.5 1927.35  4951.5 1926.41  4981.5 1926.48  4989.5 1926.23
  4989.7 1925.73  4993.2 1925.73  4993.5 1926.23  5041.5 1928.18  5061.5  1929.5
  5091.5 1930.05  5111.5 1930.96  5331.5 1934.98  5401.5 1937.29  5500.7 1939.45
#Mann= 3 ,-1 , 0
  4356.6     .05       0  4989.5     .03       0  4993.5     .05       0
Bank Sta=4989.5,4993.5
XS Rating Curve= 0 ,0
Exp/Cntr=0.3,0.1

Type RM Length L Ch R = 1 ,94402   ,313,313,313
BEGIN DESCRIPTION:
Rainy Creek 94401.55
END DESCRIPTION:
XS GIS Cut Line= 3
      1626850.88      6815153.39      1626838.72       6815641.2
      1626842.19      6816133.63
#Sta/Elev= 30
  4515.9 1938.68  4520.7 1938.68  4530.5 1937.04  4548.3 1932.91  4553.3 1933.16
  4580.5 1932.18  4600.5 1932.03  4610.5 1931.43  4670.6 1930.35  4680.6 1930.57
  4690.6 1930.03  4790.6 1929.36  4810.6 1928.26  4900.6 1925.83  4940.6 1925.36
  5003.9 1925.56  5008.7 1924.33  5008.9 1923.83  5012.4 1923.83  5012.7 1924.33
  5050.7 1928.44  5060.7 1929.12  5080.7 1929.29  5090.7 1930.34  5160.7 1931.18
  5270.7 1933.43  5290.7 1934.18  5320.7 1934.37  5410.7 1937.09  5496.3 1937.94
#Mann= 3 ,-1 , 0
  4515.9     .05       0  5008.7     .03       0  5012.7     .05       0
Bank Sta=5008.7,5012.7
XS Rating Curve= 0 ,0
Exp/Cntr=0.3,0.1

Type RM Length L Ch R = 1 ,94089   ,336,336,336
BEGIN DESCRIPTION:
Rainy Creek 94088.89
END DESCRIPTION:
XS GIS Cut Line= 3
      1626496.71      6815038.75      1626526.22      6815639.46
      1626576.57      6816120.39
#Sta/Elev= 30
  4399.8 1937.24  4489.2 1934.59  4499.2 1934.67  4569.3 1932.12  4629.3 1930.85
  4679.4 1928.75  4739.5 1928.27  4849.6 1925.21  4909.7  1924.8  4949.7 1923.58
  4987.8 1923.19    4988 1922.69  4991.5 1922.69  4991.8 1923.19  5009.8 1923.44
  5019.9    1924  5029.9 1925.03  5036.2 1926.19  5070.2  1928.6  5120.4    1930
  5210.9 1931.17  5227.8 1931.73  5301.4 1932.56  5321.1 1932.43  5331.6 1932.88
  5341.6 1932.59  5361.7 1933.29  5381.8 1932.96  5424.4 1933.67  5484.8 1933.69
#Mann= 3 ,-1 , 0
  4399.8     .05       0  4987.8     .05       0  4991.8     .05       0
Bank Sta=4987.8,4991.8
XS Rating Curve= 0 ,0
Exp/Cntr=0.3,0.1

Type RM Length L Ch R = 1 ,93753   ,562,562,562
BEGIN DESCRIPTION:
Rainy Creek 93753.18
END DESCRIPTION:
XS GIS Cut Line= 3
      1626003.48       6815360.3      1626208.34      6815695.37
      1626428.81      6816171.02
#Sta/Elev= 30
  4610.2 1937.38  4654.4 1936.12  4666.5 1935.15  4734.1 1932.37  4776.8 1928.91
  4806.8 1927.36  4850.3 1923.21  4871.6 1921.95  4914.2 1922.67  4929.6 1922.41
  4935.7 1921.69  4950.9  1922.2  4964.3 1921.49  4964.6 1920.99  4968.1 1920.99
  4968.4 1921.49  4987.7  1922.8  5001.5 1922.29  5026.5 1922.51  5060.9 1924.46
  5083.4 1925.12  5192.4 1926.59  5197.9 1927.11  5215.3 1926.86    5318 1928.86
  5335.4 1928.72  5340.9 1929.38  5369.6 1929.56  5468.8 1931.73  5527.2 1932.01
#Mann= 3 ,-1 , 0
  4610.2     .05       0  4964.3     .03       0  4968.4     .05       0
Bank Sta=4964.3,4968.4
XS Rating Curve= 0 ,0
Exp/Cntr=0.3,0.1

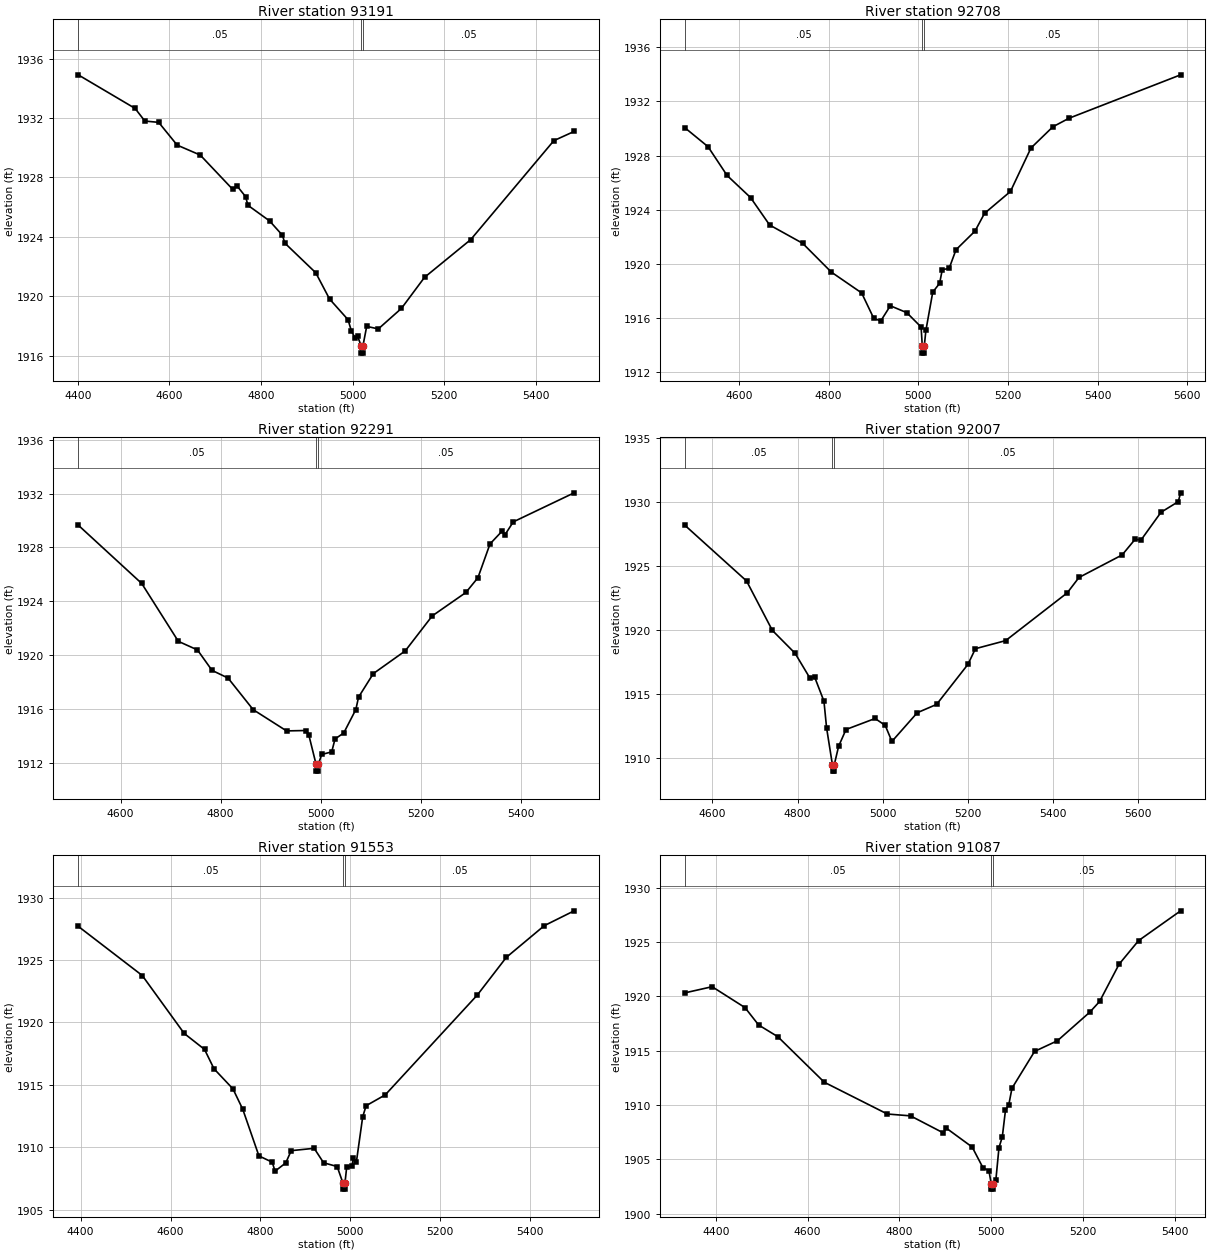
Type RM Length L Ch R = 1 ,93191   ,483,483,483
BEGIN DESCRIPTION:
Rainy Creek 93190.99
END DESCRIPTION:
XS GIS Cut Line= 3
      1625310.78      6815987.03      1625904.52      6816061.69
      1626378.44       6816158.9
#Sta/Elev= 30
    4401 1934.91  4525.1 1932.65  4546.4  1931.8  4576.6 1931.71  4616.9 1930.18
  4667.3 1929.51  4737.9 1927.21  4747.9 1927.42  4766.3 1926.71  4771.3 1926.13
  4818.5 1925.08  4846.7 1924.11  4851.7 1923.59  4919.3 1921.59  4949.5 1919.82
  4989.8 1918.43  4997.1 1917.67  5005.5 1917.17  5010.6 1917.32  5018.3 1916.68
  5018.5 1916.18  5022.1 1916.18  5022.4 1916.68  5030.5 1917.98  5055.9 1917.81
  5106.3 1919.19  5156.7 1921.28  5257.5 1923.82  5438.9 1930.48  5483.2  1931.1
#Mann= 3 ,-1 , 0
    4401     .05       0  5018.3     .03       0  5022.4     .05       0
Bank Sta=5018.3,5022.4
XS Rating Curve= 0 ,0
Exp/Cntr=0.3,0.1

Type RM Length L Ch R = 1 ,92708   ,417,417,417
BEGIN DESCRIPTION:
Rainy Creek 92708.08
END DESCRIPTION:
XS GIS Cut Line= 3
      1625316.67      6816165.27      1625762.86      6816437.84
      1626255.94      6816748.62
#Sta/Elev= 30
  4479.1 1930.07  4531.1 1928.66  4573.7 1926.53  4625.9  1924.9  4668.5 1922.87
    4742 1921.52    4806 1919.39  4873.6 1917.85  4900.8 1915.96  4916.3 1915.78
  4937.6  1916.9  4974.3 1916.39  5006.2 1915.33  5008.9  1913.9  5009.2  1913.4
  5012.9  1913.4  5013.2  1913.9  5016.9 1915.08  5032.2 1917.91  5047.5 1918.56
  5053.4 1919.57  5068.7 1919.66    5084 1921.04  5126.4 1922.42  5147.6 1923.73
  5205.4 1925.35  5251.1 1928.56    5300 1930.13  5335.9 1930.76  5584.8 1933.97
#Mann= 3 ,-1 , 0
  4479.1     .05       0  5008.9     .05       0  5013.2     .05       0
Bank Sta=5008.9,5013.2
XS Rating Curve= 0 ,0
Exp/Cntr=0.3,0.1

Type RM Length L Ch R = 1 ,92291   ,284,284,284
BEGIN DESCRIPTION:
Rainy Creek 92291.42
END DESCRIPTION:
XS GIS Cut Line= 3
      1625026.72      6816465.61      1625460.77      6816686.11
      1625927.74      6816875.32
#Sta/Elev= 30
  4515.4 1929.66  4642.3 1925.32  4715.4 1921.02  4753.6 1920.38  4782.7 1918.86
  4814.7 1918.29  4864.9 1915.94  4931.6 1914.36  4970.5 1914.39  4976.1 1914.05
  4990.6 1911.87  4990.9 1911.37  4994.7 1911.37    4995 1911.87  5001.8 1912.61
  5021.8  1912.8  5028.4 1913.76  5045.9 1914.21    5070 1915.95  5075.4 1916.87
  5104.9 1918.62  5168.7 1920.31  5222.6 1922.91  5289.8 1924.65  5313.9 1925.75
    5338 1928.26  5362.1 1929.21  5367.5 1928.92  5384.5  1929.9  5506.1 1932.06
#Mann= 3 ,-1 , 0
  4515.4     .05       0  4990.6     .03       0    4995     .05       0
Bank Sta=4990.6,4995
XS Rating Curve= 0 ,0
Exp/Cntr=0.3,0.1

Type RM Length L Ch R = 1 ,92007   ,454,454,454
BEGIN DESCRIPTION:
Rainy Creek 92006.67
END DESCRIPTION:
XS GIS Cut Line= 3
      1624838.21      6816691.43      1625261.81      6816889.35
      1625950.53      6817009.05
#Sta/Elev= 30
  4534.6 1928.19  4680.1 1923.83  4740.8 1919.97  4794.3 1918.18  4829.1 1916.25
    4840 1916.35  4862.2 1914.44  4868.4 1912.36  4882.1 1909.48  4882.4 1908.98
  4886.2 1908.98  4886.5 1909.48  4896.7 1910.92  4914.1 1912.23  4982.6 1913.09
  5006.3 1912.55  5022.1  1911.3  5081.7 1913.54  5127.2 1914.19    5201 1917.32
  5218.5 1918.54  5289.6 1919.17  5434.5  1922.9  5462.1  1924.1  5563.6 1925.86
  5594.1 1927.08  5608.4 1927.04    5655 1929.19  5695.6 1930.02  5701.2 1930.71
#Mann= 3 ,-1 , 0
  4534.6     .05       0  4882.1     .05       0  4886.5     .05       0
Bank Sta=4882.1,4886.5
XS Rating Curve= 0 ,0
Exp/Cntr=0.3,0.1

Type RM Length L Ch R = 1 ,91553   ,466,466,466
BEGIN DESCRIPTION:
Rainy Creek 91553.35
END DESCRIPTION:
XS GIS Cut Line= 3
      1624702.79       6816752.2      1625037.86      6817260.88
      1625407.65      6817589.01
#Sta/Elev= 30
  4394.5  1927.7    4537 1923.76  4630.3 1919.12  4675.6 1917.84  4696.6 1916.29
  4738.8 1914.68  4760.7 1913.04  4796.6 1909.31  4826.1 1908.81  4832.5 1908.09
  4856.3 1908.75  4868.4 1909.73  4919.5 1909.92  4940.5 1908.76  4970.7 1908.46
  4983.4 1907.15  4983.7 1906.65  4987.8 1906.65  4988.1 1907.15  4991.8 1908.39
  5003.6  1908.5  5006.6 1909.15  5013.3 1908.79  5027.5 1912.44  5035.1 1913.33
  5077.7  1914.2  5282.6  1922.2    5347 1925.21  5431.5 1927.75    5498 1928.94
#Mann= 3 ,-1 , 0
  4394.5     .05       0  4983.4     .05       0  4988.1     .05       0
Bank Sta=4983.4,4988.1
XS Rating Curve= 0 ,0
Exp/Cntr=0.3,0.1

Type RM Length L Ch R = 1 ,91087   ,422,422,422
BEGIN DESCRIPTION:
Rainy Creek 91087.22
END DESCRIPTION:
XS GIS Cut Line= 3
      1624276.38      6816933.22      1624659.17      6817485.27
      1624956.03       6817766.5
#Sta/Elev= 30
  4332.3 1920.31  4392.1 1920.88  4463.7 1918.96  4493.4 1917.36  4535.3 1916.28
  4636.6 1912.09  4773.8 1909.17  4824.4    1909    4896 1907.43  4902.1 1907.88
  4958.8 1906.13  4982.5 1904.21  4995.2 1903.97  5000.3 1902.76  5000.6 1902.26
  5004.7 1902.26  5005.1 1902.76  5010.3 1903.06  5017.2 1906.08  5024.4 1907.06
  5031.3  1909.5  5038.6 1910.03  5045.5 1911.54  5094.8 1914.93  5144.6 1915.91
  5215.4 1918.55  5236.4 1919.52  5278.9 1922.95  5321.4 1925.12    5413 1927.86
#Mann= 3 ,-1 , 0
  4332.3     .05       0  5000.3     .03       0  5005.1     .05       0
Bank Sta=5000.3,5005.1
XS Rating Curve= 0 ,0
Exp/Cntr=0.3,0.1

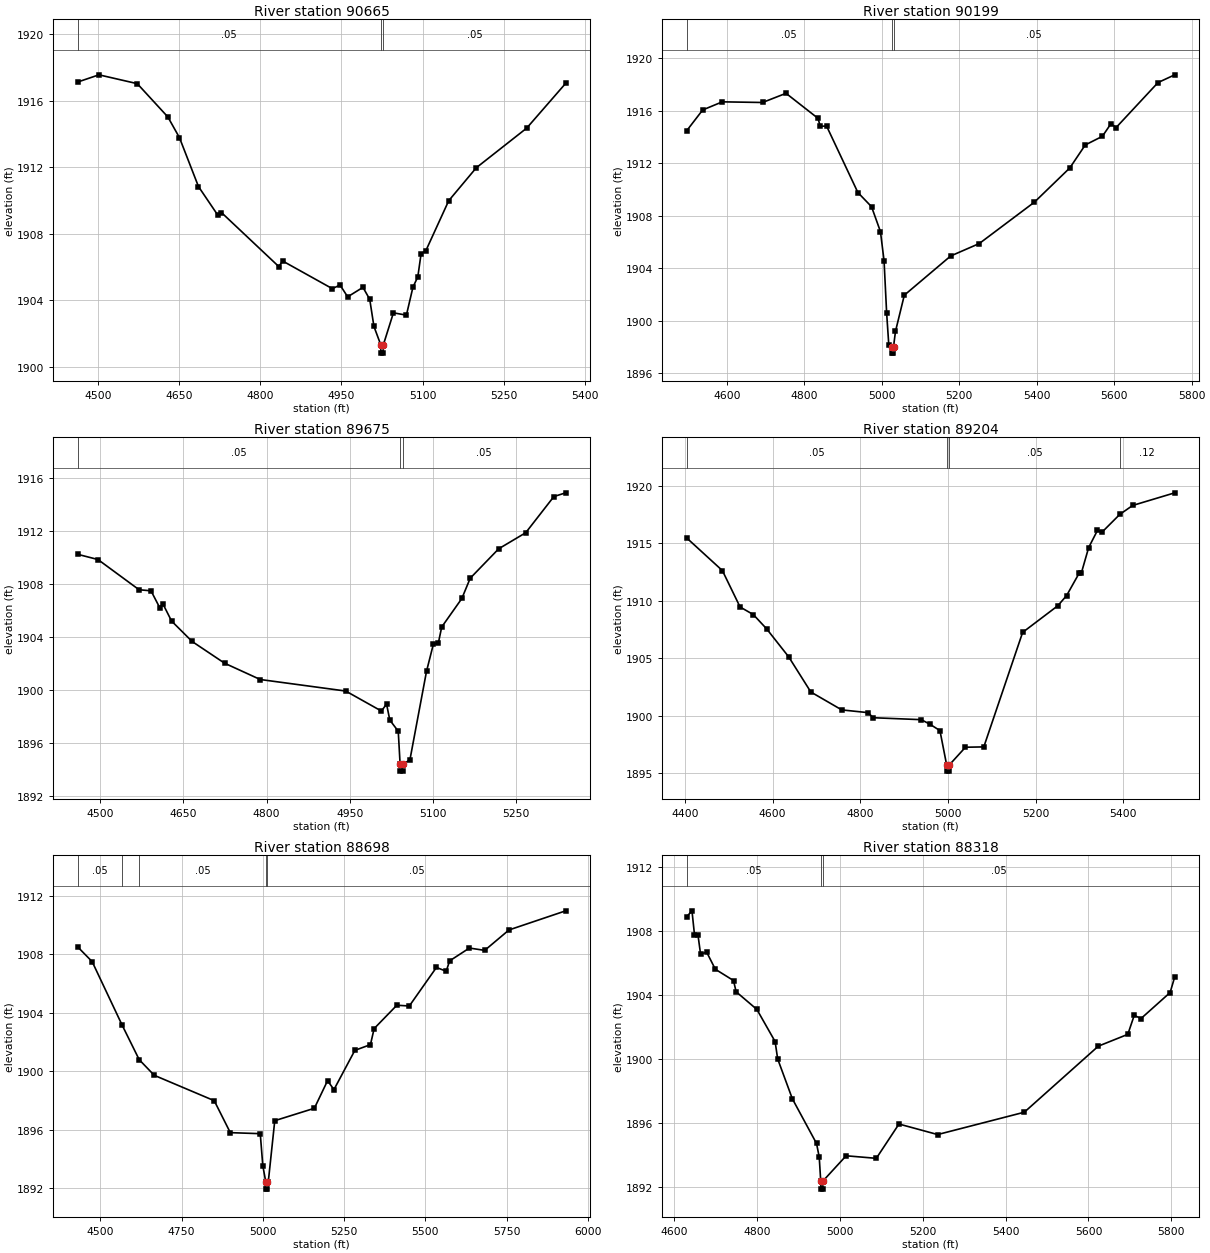
Type RM Length L Ch R = 1 ,90665   ,466,466,466
BEGIN DESCRIPTION:
Rainy Creek 90664.9
END DESCRIPTION:
XS GIS Cut Line= 3
      1623877.92      6817219.64      1624268.54      6817592.04
        1624570.      6817793.01
#Sta/Elev= 30
  4462.6 1917.12  4501.7 1917.55  4572.5 1917.02  4629.1 1915.02  4650.5 1913.78
  4685.7 1910.84  4721.1 1909.14  4728.2 1909.28  4834.1 1906.04  4841.4 1906.37
  4933.2 1904.71  4947.4 1904.93  4961.5 1904.22  4989.8 1904.79  5002.3 1904.07
  5010.1 1902.44  5022.7 1901.34    5023 1900.84  5027.1 1900.84  5027.5 1901.34
  5046.1 1903.26  5070.1 1903.12  5082.2  1904.8  5091.2 1905.42  5097.2  1906.8
  5106.2    1907  5148.3 1909.99  5199.3 1911.97  5292.5 1914.35  5364.6 1917.04
#Mann= 3 ,-1 , 0
  4462.6     .05       0  5022.7     .05       0  5027.5     .05       0
Bank Sta=5022.7,5027.5
XS Rating Curve= 0 ,0
Exp/Cntr=0.3,0.1

Type RM Length L Ch R = 1 ,90199   ,524,524,524
BEGIN DESCRIPTION:
Rainy Creek 90199.15
END DESCRIPTION:
XS GIS Cut Line= 3
      1623463.88      6817513.93      1623906.56      6817745.68
      1624594.03      6818068.58
#Sta/Elev= 30
  4497.1  1914.5    4538 1916.07  4588.7 1916.69  4692.5 1916.64  4753.1 1917.34
  4835.7 1915.43  4841.3 1914.83  4857.8 1914.84  4938.6 1909.77  4973.8 1908.69
  4996.8 1906.79  5006.1 1904.57  5012.8 1900.57  5018.3 1898.16  5025.7 1898.02
  5026.1 1897.52  5030.2 1897.52  5030.6 1898.02  5035.6 1899.18  5058.4 1901.94
    5178 1904.93  5251.9 1905.88  5394.3 1909.04  5485.6 1911.65  5525.4  1913.4
  5569.6 1914.06  5591.7 1915.02  5605.1 1914.73  5713.2 1918.16  5756.3 1918.75
#Mann= 3 ,-1 , 0
  4497.1     .05       0  5025.7     .05       0  5030.6     .05       0
Bank Sta=5025.7,5030.6
XS Rating Curve= 0 ,0
Exp/Cntr=0.3,0.1

Type RM Length L Ch R = 1 ,89675   ,471,471,471
BEGIN DESCRIPTION:
Rainy Creek 89674.73
END DESCRIPTION:
XS GIS Cut Line= 3
      1623563.48      6817738.37      1623839.53      6818205.84
      1624023.16      6818488.43
#Sta/Elev= 30
  4459.4 1910.22  4495.7 1909.83  4569.9 1907.55  4591.4 1907.47    4607 1906.21
  4612.8 1906.49  4628.5 1905.19  4665.5 1903.65  4724.1 1902.01  4788.4 1900.78
  4942.6 1899.91    5007  1898.4  5016.2 1898.93  5022.1 1897.72  5037.3 1896.88
  5040.7 1894.37  5041.1 1893.87  5045.4 1893.87  5045.7 1894.37  5058.4 1894.73
  5088.3  1901.4  5100.6 1903.44  5109.7 1903.55  5115.7 1904.74    5152 1906.89
  5167.1 1908.42  5218.5 1910.64  5267.2 1911.85    5318 1914.58  5339.3 1914.86
#Mann= 3 ,-1 , 0
  4459.4     .05       0  5040.7     .05       0  5045.7     .05       0
Bank Sta=5040.7,5045.7
XS Rating Curve= 0 ,0
Exp/Cntr=0.3,0.1

Type RM Length L Ch R = 1 ,89204   ,506,506,506
BEGIN DESCRIPTION:
Rainy Creek 89203.54
END DESCRIPTION:
XS GIS Cut Line= 3
      1623504.58      6817597.54      1623426.45      6818194.34
      1623380.94      6818703.62
#Sta/Elev= 30
  4404.2 1915.45  4485.3 1912.62  4525.7 1909.45  4555.9 1908.79  4586.2 1907.55
  4636.6 1905.11  4687.1 1902.05  4757.7 1900.49  4818.2 1900.25    4829 1899.81
  4939.2 1899.64  4959.4 1899.23  4981.7 1898.69  4997.2 1895.66  4997.5 1895.16
  5001.8 1895.16  5002.2 1895.66  5039.9 1897.24  5081.8 1897.27  5170.4 1907.24
  5250.7 1909.56  5270.8 1910.45  5299.6 1912.41  5304.6 1912.44    5321 1914.62
  5341.1 1916.12  5351.1 1915.95    5392 1917.51  5421.4 1918.29  5517.4 1919.39
#Mann= 4 ,-1 , 0
  4404.2     .05       0  4997.2     .05       0  5002.2     .05       0
    5392     .12       0
Bank Sta=4997.2,5002.2
XS Rating Curve= 0 ,0
Exp/Cntr=0.3,0.1

Type RM Length L Ch R = 1 ,88698   ,380,380,380
BEGIN DESCRIPTION:
Rainy Creek 88697.79
END DESCRIPTION:
XS GIS Cut Line= 3
      1623358.32      6817639.21      1622983.31      6818083.66
      1623143.02      6818989.87
#Sta/Elev= 30
  4430.4 1908.51  4474.5 1907.51  4567.2 1903.14  4619.4 1900.79  4665.6 1899.72
  4850.3 1897.98  4899.8 1895.79    4992 1895.72  4999.8 1893.53  5008.9 1892.42
  5009.3 1891.92  5013.6 1891.92    5014 1892.42  5016.7 1892.42  5036.6 1896.61
  5158.5 1897.46  5199.1 1899.35  5218.8 1898.74  5283.2 1901.43  5331.1 1901.82
  5342.5 1902.92  5412.3 1904.52  5450.8 1904.47  5534.2 1907.11  5564.3 1906.85
  5574.8 1907.56  5635.7 1908.44  5682.8 1908.28  5757.6 1909.68  5932.1 1910.99
#Mann= 5 ,-1 , 0
  4430.4     .05       0  4567.2     .12       0  4619.4     .05       0
  5008.9     .05       0    5014     .05       0
Bank Sta=5008.9,5014
XS Rating Curve= 0 ,0
Exp/Cntr=0.3,0.1

Type RM Length L Ch R = 1 ,88318   ,356,356,356
BEGIN DESCRIPTION:
Rainy Creek 88318.4
END DESCRIPTION:
XS GIS Cut Line= 3
      1622541.31      6817584.94      1622758.34      6817882.27
      1623033.37      6818644.56
#Sta/Elev= 30
  4629.9 1908.92  4642.3 1909.28  4648.4 1907.78  4656.9 1907.75  4663.1 1906.56
  4677.8 1906.69  4698.7 1905.62  4742.7 1904.91  4748.9 1904.21  4799.1  1903.1
  4843.1 1901.09  4849.3    1900  4884.8  1897.5  4943.2  1894.7  4949.7 1893.85
  4953.3 1892.34  4953.7 1891.84    4958 1891.84  4958.4 1892.34  5014.7 1893.93
  5087.6 1893.77  5142.3 1895.92  5235.7 1895.26  5445.1 1896.66  5623.9  1900.8
  5695.1 1901.54  5710.6 1902.73    5727 1902.53  5797.3 1904.16  5808.4 1905.14
#Mann= 3 ,-1 , 0
  4629.9     .05       0  4953.3     .05       0  4958.4     .05       0
Bank Sta=4953.3,4958.4
XS Rating Curve= 0 ,0
Exp/Cntr=0.3,0.1

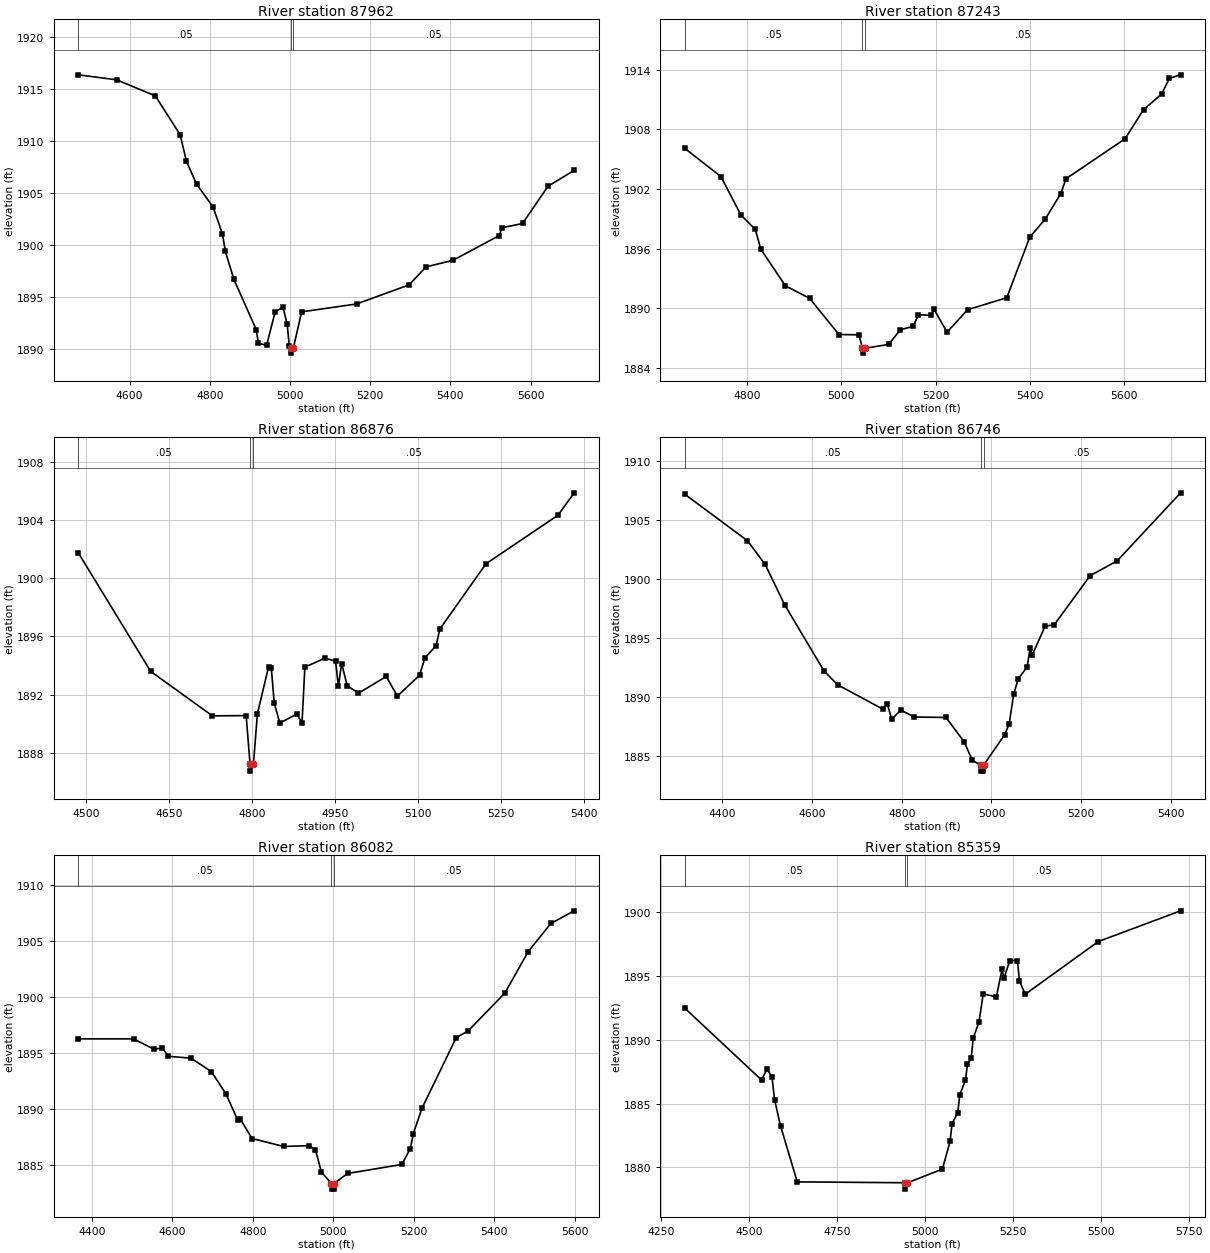
Type RM Length L Ch R = 1 ,87962   ,719,719,719
BEGIN DESCRIPTION:
Rainy Creek 87962.09
END DESCRIPTION:
XS GIS Cut Line= 3
      1622168.08      6818090.61      1622680.21      6818212.13
      1623057.03      6818814.18
#Sta/Elev= 30
  4472.2  1916.4  4567.9 1915.92  4664.3 1914.37    4726 1910.63  4741.9 1908.06
  4767.1 1905.86  4808.2 1903.66  4831.5 1901.08    4839 1899.37  4859.6 1896.74
  4915.9 1891.83  4921.3 1890.53  4941.8 1890.33  4963.3 1893.58  4982.9 1893.98
  4993.2 1892.33  4998.4 1890.22  5002.5 1890.07    5003 1889.57  5008.5 1890.07
  5029.1 1893.55  5166.3 1894.31  5297.1 1896.15  5339.6 1897.89  5406.6 1898.52
  5522.3 1900.91  5528.2 1901.65  5580.1 1902.07  5643.7 1905.66  5708.8 1907.19
#Mann= 3 ,-1 , 0
  4472.2     .05       0  5002.5     .03       0  5008.5     .05       0
Bank Sta=5002.5,5008.5
XS Rating Curve= 0 ,0
Exp/Cntr=0.3,0.1

Type RM Length L Ch R = 1 ,87243   ,367,367,367
BEGIN DESCRIPTION:
Rainy Creek 87243.04
END DESCRIPTION:
XS GIS Cut Line= 3
      1622326.55      6818592.03      1622503.64      6818870.68
      1622711.96      6819560.76
#Sta/Elev= 30
  4668.3 1906.09  4744.9 1903.25  4787.3 1899.39  4817.6 1897.95  4829.6 1895.95
  4881.3 1892.29  4932.9 1891.01  4995.1 1887.38  5037.4 1887.35  5044.8 1886.01
  5045.3 1885.51  5050.9 1886.01  5100.1 1886.38  5125.3 1887.86  5152.4  1888.2
  5163.4 1889.37  5191.2 1889.31  5196.4 1889.94  5224.2 1887.61  5267.6 1889.87
  5350.8 1891.08  5399.5 1897.16  5432.4 1898.99  5465.4 1901.55  5476.2 1903.03
  5601.5 1907.05  5640.7 1909.98  5678.9 1911.54  5695.5 1913.13  5719.3 1913.48
#Mann= 3 ,-1 , 0
  4668.3     .05       0  5044.8     .03       0  5050.9     .05       0
Bank Sta=5044.8,5050.9
XS Rating Curve= 0 ,0
Exp/Cntr=0.3,0.1

Type RM Length L Ch R = 1 ,86876   ,130,130,130
BEGIN DESCRIPTION:
Rainy Creek 86875.6
END DESCRIPTION:
XS GIS Cut Line= 3
      1622342.18      6818709.22      1622428.12      6819219.64
      1622433.33       6819597.2
#Sta/Elev= 30
  4486.3 1901.74  4616.9 1893.59  4728.4 1890.53  4789.3 1890.55  4796.3 1887.23
  4796.8 1886.73  4802.5 1887.23  4809.6 1890.68  4829.7 1893.89  4834.7 1893.84
    4840  1891.4  4850.1 1890.04  4880.6 1890.65  4890.2 1890.07  4895.3 1893.88
  4931.3  1894.5  4950.7  1894.3  4955.8 1892.56  4961.7 1894.13  4971.8  1892.6
  4992.1 1892.09  5042.3 1893.24  5062.3 1891.89  5102.3 1893.32  5112.3 1894.54
  5132.3 1895.35  5138.8 1896.49  5222.3 1900.99  5352.3 1904.33  5381.5 1905.87
#Mann= 3 ,-1 , 0
  4486.3     .05       0  4796.3     .05       0  4802.5     .05       0
Bank Sta=4796.3,4802.5
XS Rating Curve= 0 ,0
Exp/Cntr=0.3,0.1

Type RM Length L Ch R = 1 ,86746   ,664,664,664
BEGIN DESCRIPTION:
Rainy Creek 86745.78
END DESCRIPTION:
XS GIS Cut Line= 3
      1622264.05      6818610.22      1622344.79      6819289.96
      1622321.35      6819709.19
#Sta/Elev= 30
  4316.9 1907.18  4456.4 1903.25  4495.9 1901.24  4539.1 1897.84  4626.8 1892.24
  4657.1 1891.06  4757.8    1889  4767.8 1889.45  4777.9 1888.14    4798 1888.92
  4828.2 1888.33  4898.7 1888.29    4939 1886.24  4957.5 1884.66  4976.2 1884.25
  4976.7 1883.75  4981.9 1883.75  4982.4 1884.25  5029.5 1886.84  5039.5 1887.77
  5049.5 1890.26  5059.5 1891.55  5079.6 1892.58  5085.9 1894.16  5090.9 1893.59
  5119.6 1896.02  5139.7 1896.13  5219.8 1900.29  5279.9 1901.54  5421.3  1907.3
#Mann= 3 ,-1 , 0
  4316.9     .05       0  4976.2     .05       0  4982.4     .05       0
Bank Sta=4976.2,4982.4
XS Rating Curve= 0 ,0
Exp/Cntr=0.3,0.1

Type RM Length L Ch R = 1 ,86082   ,723,723,723
BEGIN DESCRIPTION:
Rainy Creek 86081.91
END DESCRIPTION:
XS GIS Cut Line= 3
      1621381.26      6818930.31       1621749.3       6819454.6
      1622106.92      6819926.79
#Sta/Elev= 30
    4366 1896.26  4503.4 1896.26  4553.9 1895.33  4574.8 1895.44  4589.6  1894.7
  4646.3 1894.53  4696.8 1893.33  4732.6 1891.36  4762.2 1889.01  4768.3  1889.1
  4797.9 1887.34  4876.3 1886.63  4940.8  1886.7  4955.7 1886.32  4970.5 1884.34
  4995.4 1883.31  4995.9 1882.81  5001.2 1882.81  5001.7 1883.31  5035.3 1884.21
  5170.5 1885.02  5191.3 1886.42    5199 1887.78  5220.4 1890.04  5305.7 1896.37
  5334.9 1896.96  5426.4 1900.35  5484.7 1904.07  5540.9 1906.59  5598.9 1907.72
#Mann= 3 ,-1 , 0
    4366     .05       0  4995.4     .03       0  5001.7     .05       0
Bank Sta=4995.4,5001.7
XS Rating Curve= 0 ,0
Exp/Cntr=0.3,0.1

Type RM Length L Ch R = 1 ,85359   ,338,338,338
BEGIN DESCRIPTION:
Rainy Creek 85358.96
END DESCRIPTION:
XS GIS Cut Line= 4
      1620888.18      6819201.09      1621044.44      6819590.01
      1621218.05      6819787.93      1621860.18      6820131.55
#Sta/Elev= 30
  4316.4 1892.49  4534.9 1886.85  4550.2 1887.73  4564.5 1887.08  4571.7 1885.32
  4588.7 1883.26  4636.4 1878.86  4943.4 1878.79  4943.9 1878.29    4950 1878.79
  5049.2 1879.86  5071.1 1882.03  5076.8 1883.43    5093 1884.29  5098.7  1885.7
    5115 1886.83  5120.7 1888.11  5131.3 1888.55  5136.9 1890.14  5153.2 1891.38
  5165.5 1893.61  5202.7 1893.38    5219 1895.53  5224.7 1894.84  5240.9 1896.23
  5262.9 1896.22  5268.6 1894.63  5284.8 1893.58  5492.9 1897.72  5727.1 1900.13
#Mann= 3 ,-1 , 0
  4316.4     .05       0  4943.4     .05       0    4950     .05       0
Bank Sta=4943.4,4950
XS Rating Curve= 0 ,0
Exp/Cntr=0.3,0.1

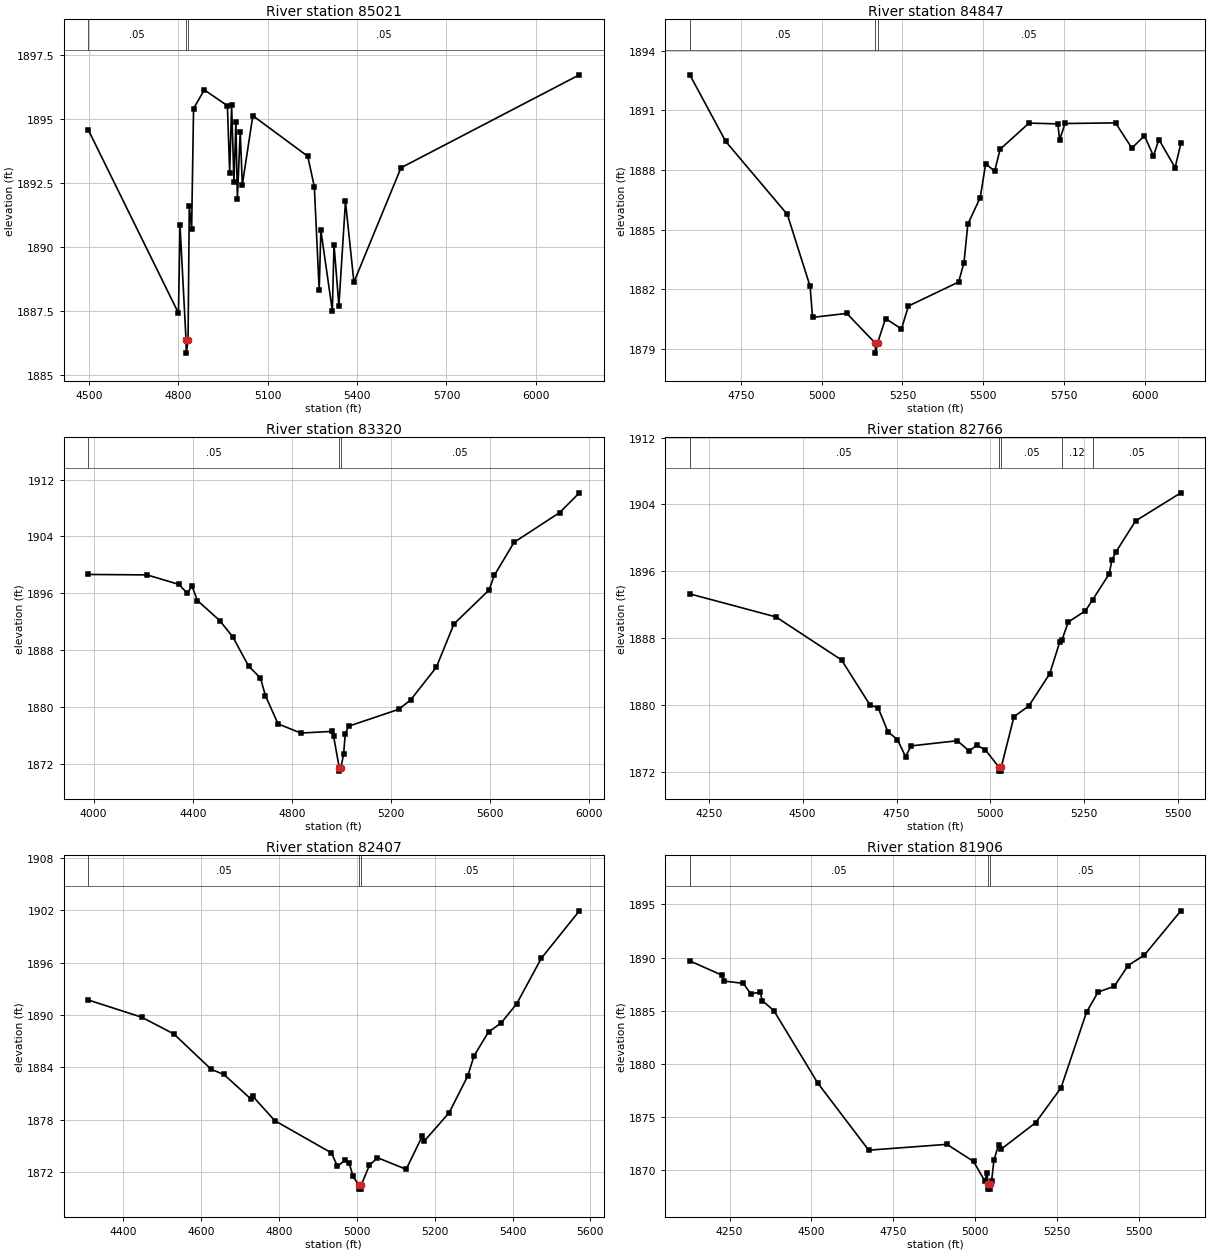
Type RM Length L Ch R = 1 ,85021   ,174,174,174
BEGIN DESCRIPTION:
Rainy Creek 85021.04
END DESCRIPTION:
XS GIS Cut Line= 5
      1620707.65      6819270.61      1620818.74      6819583.07
      1620926.38      6819715.01      1621072.22      6819860.85
      1621905.52      6820298.33
#Sta/Elev= 30
  4497.2 1894.58  4799.8 1887.41  4805.1 1890.84  4825.4 1886.34  4825.9 1885.84
  4832.1 1886.34  4836.2 1891.59  4844.1 1890.71  4850.6 1895.42  4886.8 1896.15
  4964.2 1895.53  4971.9 1892.91  4978.4 1895.54  4986.3 1892.56  4992.8 1894.89
  4997.8 1891.88  5007.3 1894.52  5014.4 1892.44  5049.7 1895.14  5234.1 1893.55
  5256.2 1892.36  5272.6  1888.3  5278.2 1890.65  5316.7  1887.5  5322.3 1890.09
  5338.7  1887.7  5360.8 1891.78  5389.2 1888.62  5547.3  1893.1  6146.5 1896.74
#Mann= 3 ,-1 , 0
  4497.2     .05       0  4825.4     .05       0  4832.1     .05       0
Bank Sta=4825.4,4832.1
XS Rating Curve= 0 ,0
Exp/Cntr=0.3,0.1

Type RM Length L Ch R = 1 ,84847   ,1527,1527,1527
BEGIN DESCRIPTION:
Rainy Creek 84847.46
END DESCRIPTION:
XS GIS Cut Line= 4
       1620513.2      6819503.22      1620790.97      6819812.24
      1620992.36      6819999.74      1621735.38      6820371.25
#Sta/Elev= 30
  4591.1 1892.79  4702.2 1889.44  4893.3 1885.76  4963.8 1882.14  4971.3 1880.58
  5077.4 1880.78  5165.9 1879.28  5166.4 1878.78  5172.6 1879.28  5197.5 1880.52
  5246.9    1880  5268.4 1881.15  5423.9 1882.36  5440.6 1883.34  5452.4 1885.27
  5490.9 1886.61  5507.7 1888.31  5535.7 1887.94  5552.4 1889.04  5641.9 1890.36
  5731.3 1890.32  5736.9 1889.52  5753.7 1890.34  5910.2 1890.37  5960.5  1889.1
  5999.6 1889.72  6027.6 1888.71  6044.4 1889.53  6094.7 1888.12  6112.5 1889.34
#Mann= 3 ,-1 , 0
  4591.1     .05       0  5165.9     .05       0  5172.6     .05       0
Bank Sta=5165.9,5172.6
XS Rating Curve= 0 ,0
Exp/Cntr=0.3,0.1

Type RM Length L Ch R = 1 ,83320   ,554,554,554
BEGIN DESCRIPTION:
Rainy Creek 83319.76
END DESCRIPTION:
XS GIS Cut Line= 3
      1620352.12      6820808.55      1621352.13      6820626.26
      1622305.25      6820480.42
#Sta/Elev= 30
  3979.1 1898.65  4215.8 1898.59  4343.7 1897.26  4378.4 1895.99    4397 1897.03
  4419.1 1894.98  4508.7 1892.17  4561.4 1889.88  4625.5 1885.76  4673.2 1884.08
  4693.6 1881.57  4744.4 1877.62  4835.9 1876.33  4960.5 1876.56    4968 1875.93
  4991.1 1871.47  4991.6 1870.97  4997.9 1871.47  5008.6 1873.33  5015.4 1876.21
  5028.8 1877.29  5231.2 1879.67  5279.1 1880.99  5382.9  1885.6  5453.7 1891.68
  5595.4 1896.46  5616.4 1898.51  5696.5 1903.18  5880.2 1907.36  5959.8 1910.14
#Mann= 3 ,-1 , 0
  3979.1     .05       0  4991.1     .05       0  4997.9     .05       0
Bank Sta=4991.1,4997.9
XS Rating Curve= 0 ,0
Exp/Cntr=0.3,0.1

Type RM Length L Ch R = 1 ,82766   ,359,359,359
BEGIN DESCRIPTION:
Rainy Creek 82765.92
END DESCRIPTION:
XS GIS Cut Line= 3
      1620963.44      6821169.78      1621718.67      6820901.55
      1622199.74      6820742.92
#Sta/Elev= 30
  4199.4 1893.29    4429 1890.53  4603.5 1885.38  4678.6 1880.04  4701.4 1879.61
    4727 1876.79  4752.5 1875.84  4774.1  1873.8  4788.7 1875.09  4912.1 1875.71
  4943.9 1874.46  4963.2 1875.17  4986.3 1874.64  5022.3 1872.57  5022.8 1872.07
  5028.7 1872.07  5029.2 1872.57  5062.8 1878.59  5102.3 1879.87    5158 1883.72
  5184.5 1887.49  5190.1 1887.71  5207.6 1889.92  5253.3 1891.27  5272.1 1892.57
  5316.8 1895.69  5323.4 1897.31  5333.9 1898.27  5386.6 1902.02  5507.4 1905.39
#Mann= 5 ,-1 , 0
  4199.4     .05       0  5022.3     .05       0  5029.2     .05       0
  5190.1     .12       0  5272.1     .05       0
Bank Sta=5022.3,5029.2
XS Rating Curve= 0 ,0
Exp/Cntr=0.3,0.1

Type RM Length L Ch R = 1 ,82407   ,501,501,501
BEGIN DESCRIPTION:
Rainy Creek 82406.99
END DESCRIPTION:
XS GIS Cut Line= 3
       1620968.7      6821284.36      1621653.57      6821216.65
      1622197.87      6821039.55
#Sta/Elev= 30
  4311.1 1891.71  4448.1 1889.74  4530.8 1887.82  4626.9 1883.76  4659.1 1883.19
  4727.9  1880.4    4733  1880.7  4789.7  1877.9  4935.1 1874.21  4950.5 1872.69
  4970.6 1873.37  4980.7 1873.03  4990.7 1871.51  5005.1 1870.56  5005.6 1870.06
  5011.5 1870.06    5012 1870.56  5032.4 1872.77  5053.4 1873.66    5127 1872.33
  5168.3 1876.12  5173.5 1875.56  5237.4 1878.81  5284.7 1882.98  5301.3 1885.32
  5338.5 1888.06  5370.4 1889.06  5410.9 1891.29    5474 1896.49  5571.7 1901.92
#Mann= 3 ,-1 , 0
  4311.1     .05       0  5005.1     .05       0    5012     .05       0
Bank Sta=5005.1,5012
XS Rating Curve= 0 ,0
Exp/Cntr=0.3,0.1

Type RM Length L Ch R = 1 ,81906   ,561,561,561
BEGIN DESCRIPTION:
Rainy Creek 82221.217
END DESCRIPTION:
XS GIS Cut Line= 3
      1620916.55      6821427.58      1621760.57      6821645.12
      1622196.65      6821191.84
#Sta/Elev= 30
  4128.4 1889.69  4227.6 1888.34  4232.7  1887.8    4292 1887.58  4314.1 1886.62
  4343.7 1886.73  4349.6 1885.96    4385 1885.03  4519.2 1878.22  4675.1  1871.9
  4914.1 1872.45  4995.5 1870.84  5029.4 1869.03  5036.6 1869.71  5040.1 1868.74
  5040.6 1868.24  5046.5 1868.24    5047 1868.74  5050.7 1869.01  5057.7 1870.96
  5071.8 1872.39    5079 1871.98    5185 1874.48  5262.7 1877.76  5340.7 1884.87
  5375.9 1886.76  5425.6 1887.31  5467.8 1889.26  5517.4 1890.24    5629  1894.4
#Mann= 3 ,-1 , 0
  4128.4     .05       0  5040.1     .05       0    5047     .05       0
Bank Sta=5040.1,5047
XS Rating Curve= 0 ,0
Exp/Cntr=0.3,0.1