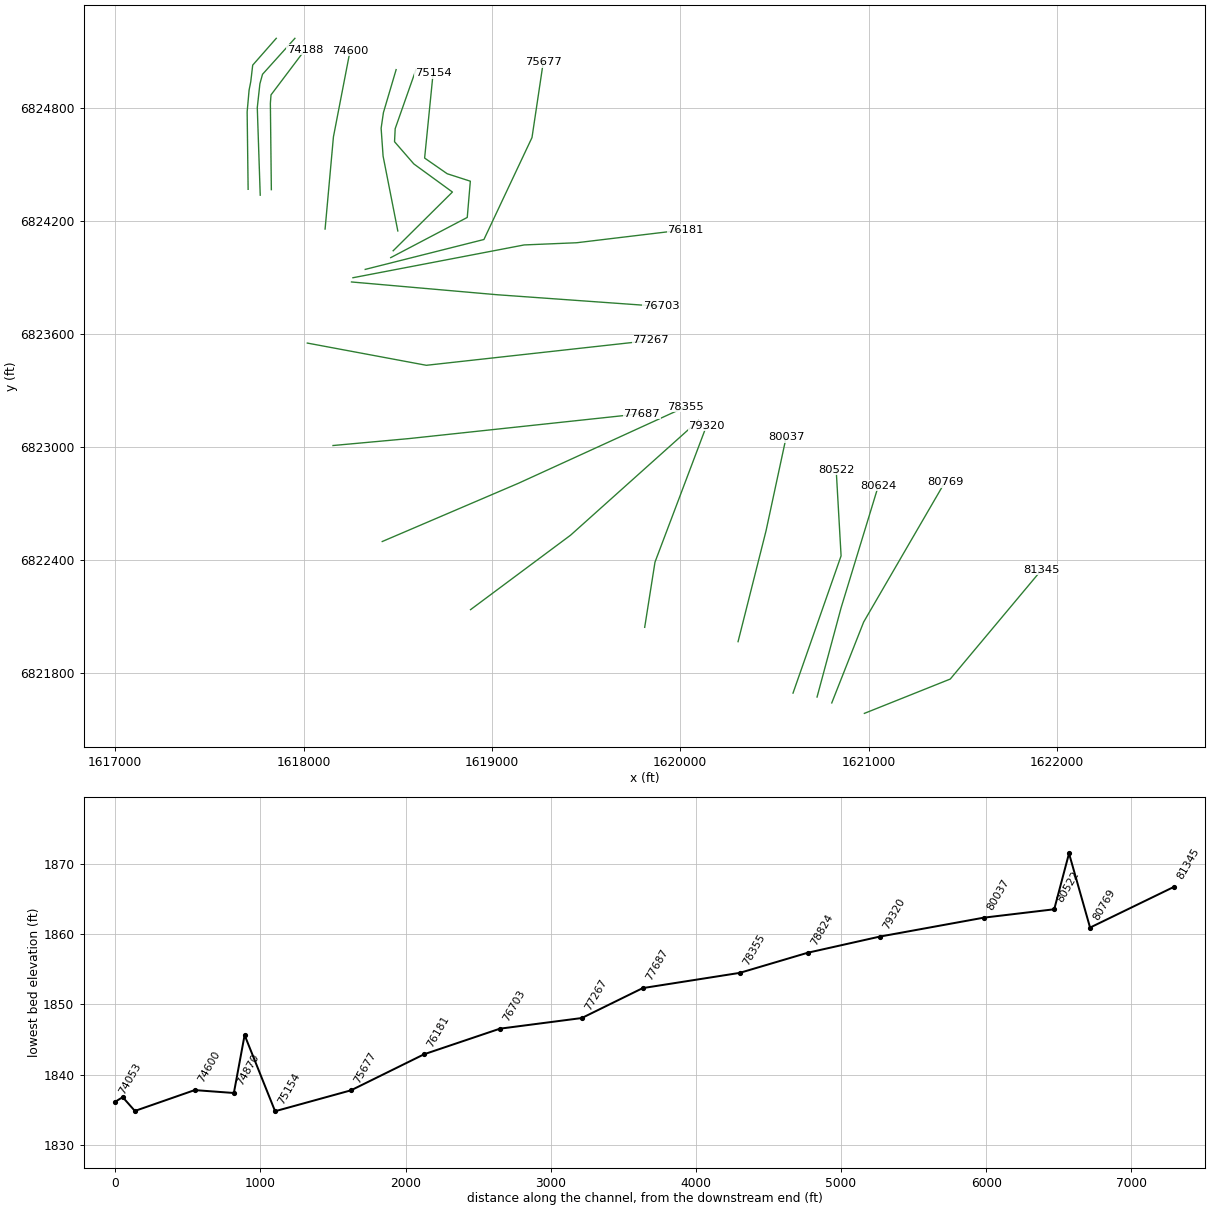
HEC-RAS study Rainy Creek.prj: Rainy Creek Base Level Engineering

--- Rainy Creek.g01 (geometry) --- (continued)

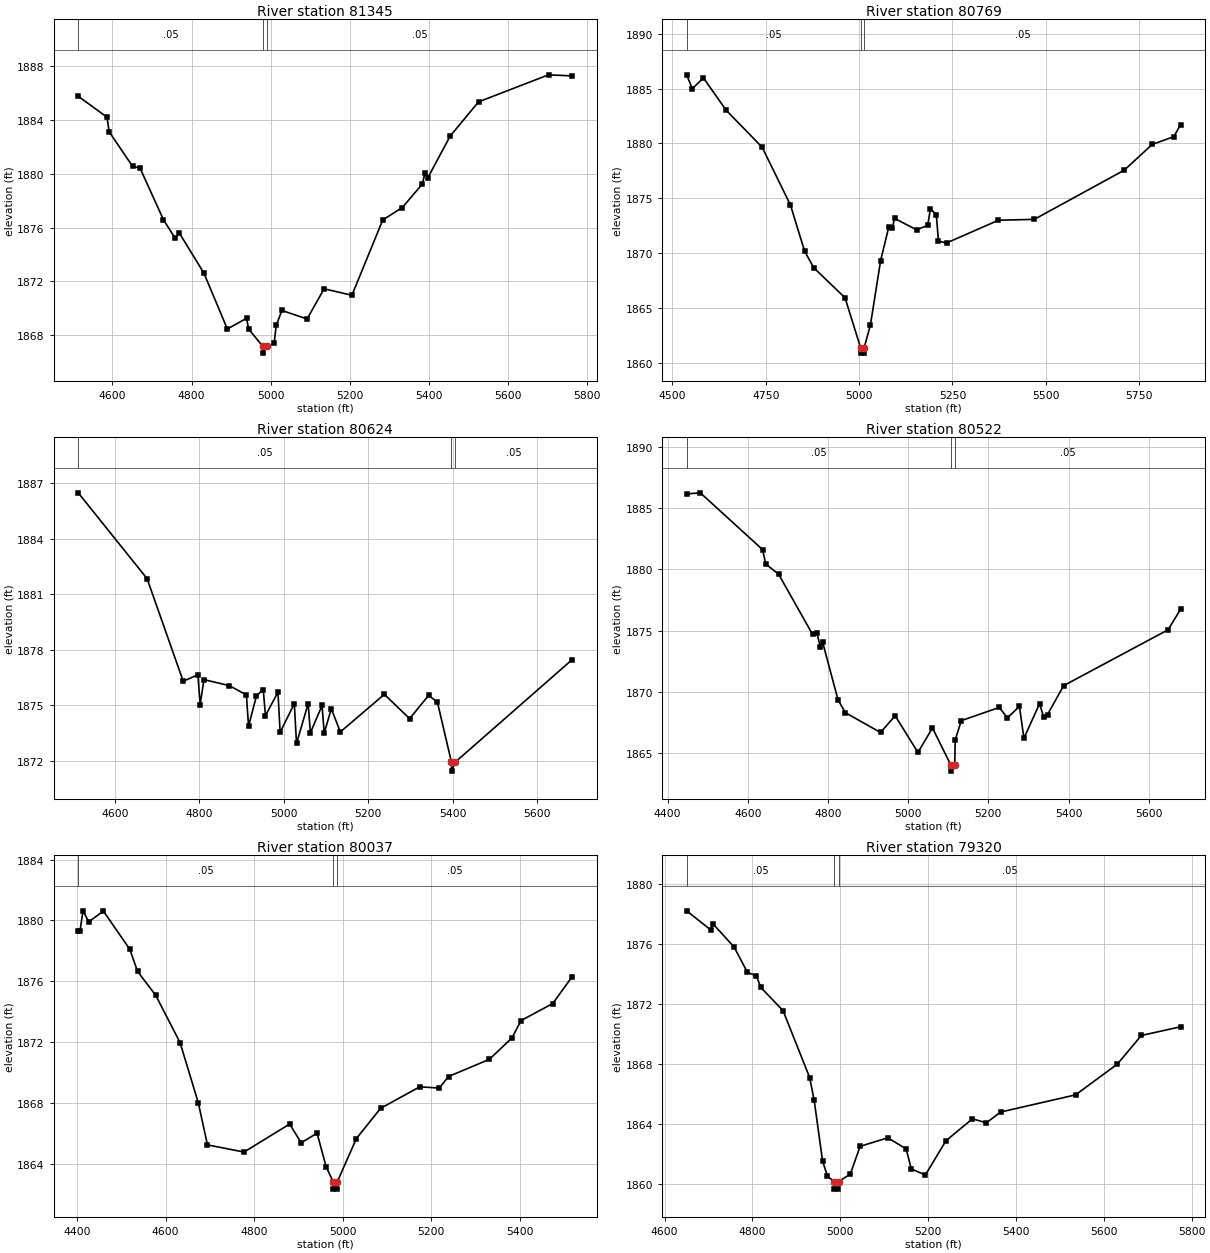
Type RM Length L Ch R = 1 ,81345   ,576,576,576
BEGIN DESCRIPTION:
Rainy Creek 81345.37
END DESCRIPTION:
XS GIS Cut Line= 3
      1620977.41      6821583.99      1621433.09      6821766.26
      1621919.22      6822347.87
#Sta/Elev= 30
  4513.5 1885.76  4586.3  1884.2  4591.7 1883.12  4650.9 1880.55  4669.7 1880.42
    4729 1876.58  4758.6  1875.2  4769.4 1875.58  4831.3 1872.61  4890.5 1868.46
    4939 1869.26  4944.4 1868.46  4980.1 1867.17  4980.6 1866.67  4989.5 1867.17
  5008.7 1867.39  5014.1 1868.73  5028.4 1869.84  5092.1 1869.21  5135.1 1871.45
  5205.4 1870.97  5283.5 1876.57  5332.9 1877.49  5383.6 1879.24  5390.2 1880.08
  5397.5 1879.71  5453.9  1882.8  5525.5 1885.34  5702.5 1887.35  5762.3 1887.27
#Mann= 3 ,-1 , 0
  4513.5     .05       0  4980.1     .03       0  4989.5     .05       0
Bank Sta=4980.1,4989.5
XS Rating Curve= 0 ,0
Exp/Cntr=0.3,0.1

Type RM Length L Ch R = 1 ,80769   ,145,145,145
BEGIN DESCRIPTION:
Rainy Creek 80768.71
END DESCRIPTION:
XS GIS Cut Line= 3
      1620804.17      6821639.48      1620973.46      6822069.21
      1621405.48      6822813.54
#Sta/Elev= 30
  4538.2 1886.25  4553.4 1884.99  4583.2 1885.97  4644.1 1883.02  4740.3 1879.66
  4816.1  1874.4  4853.9 1870.21  4878.3 1868.69  4962.3 1865.95  5003.9 1861.41
  5004.4 1860.91  5013.1 1860.91  5013.6 1861.41  5030.3 1863.48  5057.6 1869.34
  5079.6 1872.42  5089.1 1872.33  5094.9 1873.18  5153.7 1872.14  5183.7 1872.54
  5190.9 1874.05  5206.7 1873.52  5212.4 1871.11    5234 1870.94  5373.1 1873.01
  5469.1 1873.09    5710 1877.57  5784.6 1879.91  5842.7 1880.62  5860.7 1881.72
#Mann= 3 ,-1 , 0
  4538.2     .05       0  5003.9     .05       0  5013.6     .05       0
Bank Sta=5003.9,5013.6
XS Rating Curve= 0 ,0
Exp/Cntr=0.3,0.1

Type RM Length L Ch R = 1 ,80624   ,102,102,102
BEGIN DESCRIPTION:
Rainy Creek 80623.57
END DESCRIPTION:
XS GIS Cut Line= 3
      1620726.05      6821670.73      1620853.67      6822144.73
      1621051.57      6822793.13
#Sta/Elev= 30
  4513.7 1886.49  4676.6 1881.85  4762.1  1876.3  4796.9 1876.65  4802.1 1875.04
  4811.2 1876.39  4871.6 1876.06  4911.6 1875.56  4916.7 1873.87  4935.5 1875.52
  4951.5 1875.85  4956.7 1874.44  4986.3 1875.71  4991.4 1873.54    5025 1875.09
  5030.2 1872.94  5057.8 1875.09    5063 1873.51  5090.6 1874.99  5095.8  1873.5
  5112.5 1874.81  5133.9 1873.56    5238 1875.59  5297.9 1874.28  5342.6 1875.53
  5363.5 1875.18  5396.7 1871.94  5397.2 1871.44  5406.4 1871.94  5682.5 1877.47
#Mann= 3 ,-1 , 0
  4513.7     .05       0  5396.7     .05       0  5406.4     .05       0
Bank Sta=5396.7,5406.4
XS Rating Curve= 0 ,0
Exp/Cntr=0.3,0.1

Type RM Length L Ch R = 1 ,80522   ,485,485,485
BEGIN DESCRIPTION:
Rainy Creek 80521.62
END DESCRIPTION:
XS GIS Cut Line= 4
      1620598.47      6821691.65      1620780.75      6822212.44
      1620853.67      6822420.77      1620827.62      6822879.14
#Sta/Elev= 30
  4447.7 1886.18  4481.8 1886.27  4636.9 1881.63  4645.1 1880.44  4676.9 1879.62
  4761.7 1874.69  4772.3 1874.81  4781.4 1873.66  4786.7 1874.05  4825.2 1869.34
  4843.5 1868.29  4931.2 1866.67  4967.6 1868.04  5024.4 1865.04  5060.7 1867.04
  5106.4 1864.01  5106.9 1863.51  5116.2 1864.01  5117.4 1866.06  5132.5 1867.64
  5227.4 1868.72  5247.5 1867.86  5277.5  1868.8  5288.7  1866.2  5327.6 1869.02
  5337.6 1867.97  5347.6 1868.14  5387.7  1870.5  5648.1 1875.07  5679.3 1876.75
#Mann= 3 ,-1 , 0
  4447.7     .05       0  5106.4     .05       0  5116.2     .05       0
Bank Sta=5106.4,5116.2
XS Rating Curve= 0 ,0
Exp/Cntr=0.3,0.1

Type RM Length L Ch R = 1 ,80037   ,717,717,717
BEGIN DESCRIPTION:
Rainy Creek 80037
END DESCRIPTION:
XS GIS Cut Line= 3
      1620306.78      6821965.01      1620455.23      6822553.59
      1620561.99      6823050.95
#Sta/Elev= 30
  4402.7 1879.32  4406.8 1879.32  4413.4 1880.63  4426.4 1879.91  4459.6 1880.61
  4519.2  1878.1  4536.6 1876.65  4577.7 1875.07  4632.7 1871.96  4673.9    1868
  4694.6 1865.23  4777.1 1864.76  4880.2  1866.6  4906.3 1865.37  4942.1    1866
  4962.7 1863.79  4978.3 1862.82  4978.8 1862.32  4987.6 1862.32  4988.1 1862.82
    5031 1865.65  5085.8 1867.64  5174.1 1869.05  5218.3 1868.97  5239.2 1869.73
  5331.3 1870.86  5382.4 1872.27  5402.9 1873.41  5474.5 1874.53  5518.4  1876.3
#Mann= 3 ,-1 , 0
  4402.7     .05       0  4978.3     .05       0  4988.1     .05       0
Bank Sta=4978.3,4988.1
XS Rating Curve= 0 ,0
Exp/Cntr=0.3,0.1

Type RM Length L Ch R = 1 ,79320   ,496,496,496
BEGIN DESCRIPTION:
Rainy Creek 79320.17
END DESCRIPTION:
XS GIS Cut Line= 3
      1619811.13      6822041.18      1619865.82      6822387.57
      1620139.27      6823111.57
#Sta/Elev= 30
  4650.3 1878.23    4705 1876.96    4710 1877.37  4758.4 1875.81  4788.8 1874.11
  4809.1 1873.89  4819.2 1873.11  4869.8 1871.56  4930.5 1867.08  4940.7 1865.56
  4959.8 1861.51    4971 1860.49  4986.3 1860.13  4986.8 1859.63  4995.7 1859.63
  4996.2 1860.13  5022.8 1860.63  5045.3 1862.49  5108.3 1863.06    5150 1862.32
  5161.8 1860.98  5193.8 1860.57  5240.6 1862.86    5301 1864.33  5332.8 1864.06
  5364.9 1864.78  5535.9 1865.93  5631.1 1867.99  5685.6  1869.9  5774.9 1870.48
#Mann= 3 ,-1 , 0
  4650.3     .05       0  4986.3     .05       0  4996.2     .05       0
Bank Sta=4986.3,4996.2
XS Rating Curve= 0 ,0
Exp/Cntr=0.3,0.1

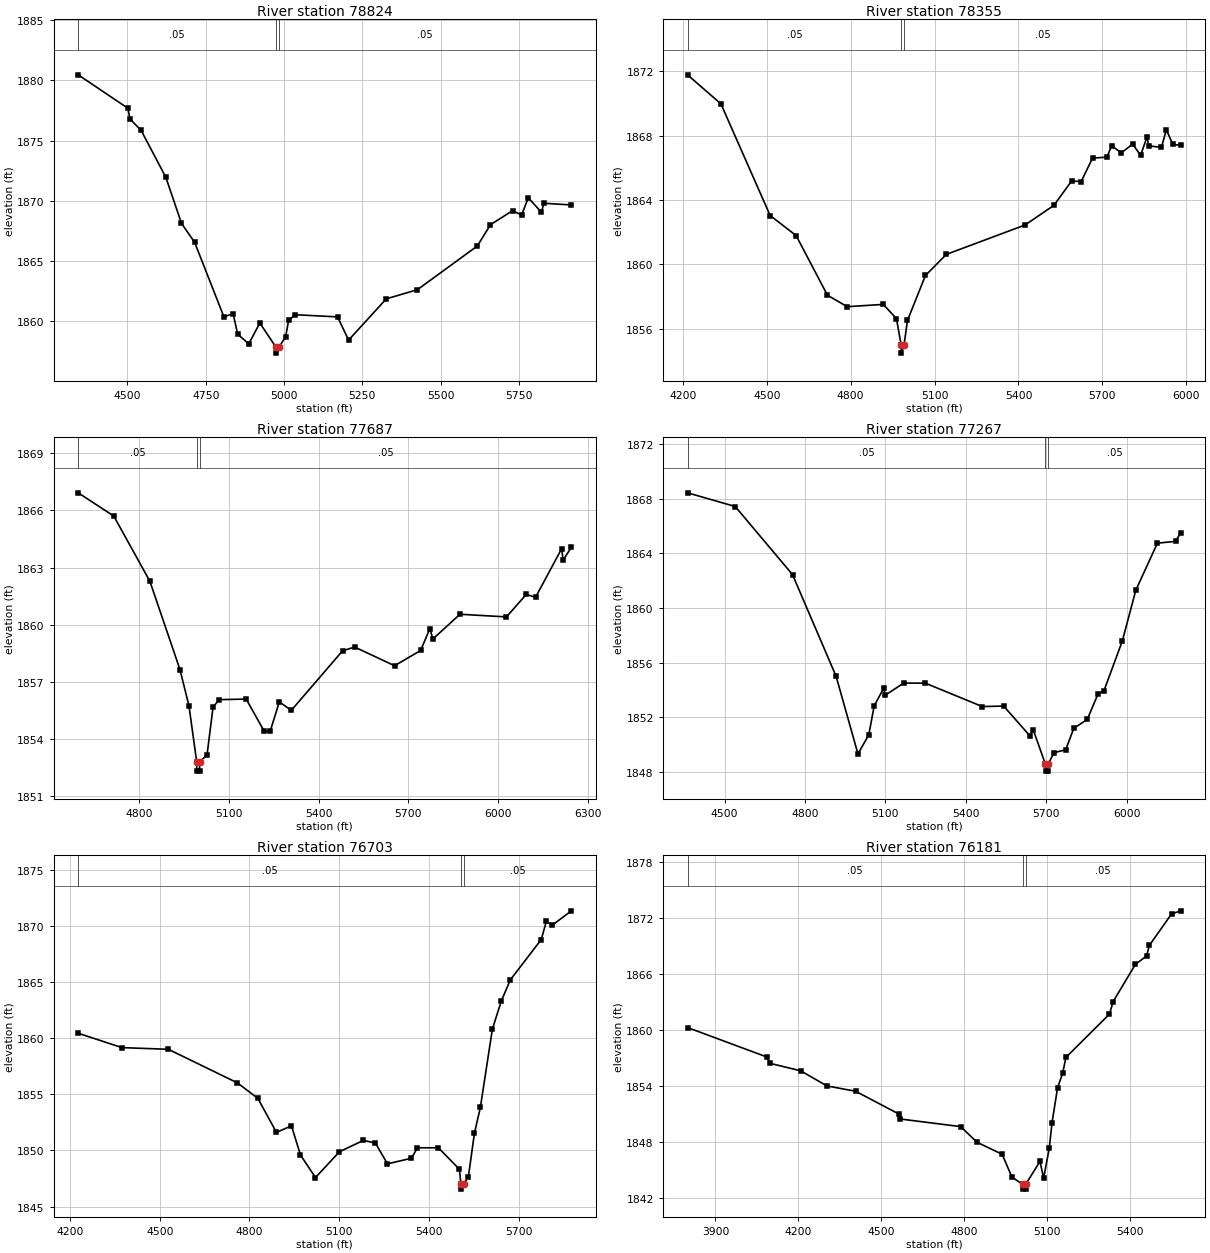
Type RM Length L Ch R = 1 ,78824   ,469,469,469
BEGIN DESCRIPTION:
Rainy Creek 78824.14
END DESCRIPTION:
XS GIS Cut Line= 3
      1618886.67      6822134.98       1619417.9       6822530.8
      1620097.56      6823140.15
#Sta/Elev= 30
  4342.7 1880.46  4501.6 1877.68  4507.9 1876.79  4543.3 1875.86  4622.6 1871.95
  4672.6 1868.12  4714.7 1866.54  4808.1 1860.35  4837.4 1860.63  4851.9 1858.92
  4887.4 1858.11  4922.8 1859.84  4974.2 1857.84  4974.7 1857.34  4984.1 1857.84
  5005.2 1858.71    5015 1860.08  5036.6 1860.53  5171.2 1860.35  5206.3 1858.42
  5326.7 1861.85  5426.1 1862.61  5617.5 1866.24  5659.4 1868.01  5730.4 1869.18
  5758.8 1868.81  5780.3 1870.25  5822.3 1869.04  5829.8 1869.79    5918 1869.65
#Mann= 3 ,-1 , 0
  4342.7     .05       0  4974.2     .05       0  4984.1     .05       0
Bank Sta=4974.2,4984.1
XS Rating Curve= 0 ,0
Exp/Cntr=0.3,0.1

Type RM Length L Ch R = 1 ,78355   ,668,668,668
BEGIN DESCRIPTION:
Rainy Creek 78354.61
END DESCRIPTION:
XS GIS Cut Line= 3
      1618417.91      6822496.95      1619141.86      6822806.84
      1620029.77      6823213.04
#Sta/Elev= 30
  4216.6 1871.79  4336.1 1869.98    4512 1863.04    4605 1861.79    4717 1858.08
  4787.8 1857.37  4916.6 1857.51  4963.7 1856.63  4980.6 1854.98  4981.1 1854.48
  4990.8 1854.98  5003.1 1856.51  5067.5 1859.31    5142 1860.62  5423.7 1862.45
  5526.8 1863.67  5590.3 1865.19  5624.3 1865.15  5664.9 1866.61  5716.4 1866.67
  5733.3 1867.38  5767.9 1866.94  5808.5 1867.48    5837 1866.78    5860 1867.94
  5865.5 1867.37  5911.5 1867.28    5929 1868.37  5952.1 1867.46  5980.5  1867.4
#Mann= 3 ,-1 , 0
  4216.6     .05       0  4980.6     .05       0  4990.8     .05       0
Bank Sta=4980.6,4990.8
XS Rating Curve= 0 ,0
Exp/Cntr=0.3,0.1

Type RM Length L Ch R = 1 ,77687   ,420,420,420
BEGIN DESCRIPTION:
Rainy Creek 77686.94
END DESCRIPTION:
XS GIS Cut Line= 3
       1618156.6      6823006.93      1618560.26      6823043.82
      1619795.05       6823176.2
#Sta/Elev= 30
  4597.2 1866.92  4716.1  1865.7  4836.6 1862.28    4937 1857.65  4967.1 1855.75
  4992.8 1852.82  4993.3 1852.32  5002.5 1852.32    5003 1852.82  5027.4 1853.16
  5047.5 1855.67  5067.6 1856.07  5158.2  1856.1  5218.5 1854.41  5238.6 1854.42
  5268.8 1855.95    5309 1855.51    5480 1858.63  5520.2 1858.83  5653.8 1857.85
  5740.9 1858.65  5771.7  1859.8  5781.7 1859.25  5872.2 1860.55  6027.5 1860.41
  6093.5 1861.59  6124.7 1861.44  6211.8 1863.99  6216.8 1863.39  6244.4 1864.07
#Mann= 3 ,-1 , 0
  4597.2     .05       0  4992.8     .05       0    5003     .05       0
Bank Sta=4992.8,5003
XS Rating Curve= 0 ,0
Exp/Cntr=0.3,0.1

Type RM Length L Ch R = 1 ,77267   ,564,564,564
BEGIN DESCRIPTION:
Rainy Creek 77267.14
END DESCRIPTION:
XS GIS Cut Line= 3
      1618020.18       6823551.2      1618652.13      6823433.14
      1619841.57      6823564.92
#Sta/Elev= 30
  4361.9 1868.42  4539.7 1867.42  4753.4 1862.44  4916.1    1855  4997.5 1849.33
  5037.9 1850.72    5058 1852.84  5093.7 1854.14  5098.8 1853.62  5168.6 1854.51
  5249.1  1854.5  5461.5 1852.79  5540.9 1852.83  5637.8 1850.67  5651.6 1851.08
  5696.8 1848.57  5697.3 1848.07  5706.5 1848.07    5707 1848.57  5728.5 1849.42
  5772.3 1849.63  5802.5  1851.2  5852.8 1851.85  5893.1 1853.72  5914.9 1853.94
  5983.6 1857.59  6033.9  1861.3  6114.4 1864.74  6181.9 1864.87  6201.5 1865.51
#Mann= 3 ,-1 , 0
  4361.9     .05       0  5696.8     .05       0    5707     .05       0
Bank Sta=5696.8,5707
XS Rating Curve= 0 ,0
Exp/Cntr=0.3,0.1

Type RM Length L Ch R = 1 ,76703   ,522,522,522
BEGIN DESCRIPTION:
Rainy Creek 76703.3
END DESCRIPTION:
XS GIS Cut Line= 3
      1618254.61      6823875.85       1619025.4      6823808.14
      1619898.61      6823745.65
#Sta/Elev= 30
  4227.3 1860.44  4373.7 1859.16  4528.8 1859.01  4759.7 1856.02  4828.1 1854.64
  4890.2 1851.61  4940.4  1852.2  4970.5  1849.6  5020.7 1847.59  5100.9 1849.89
  5181.1  1850.9  5221.2 1850.66  5261.3 1848.81  5341.5 1849.31  5361.6 1850.24
  5431.8 1850.24  5501.9 1848.33  5506.8 1847.06  5507.3 1846.56  5517.1 1847.06
    5532 1847.65  5552.1 1851.53  5572.1 1853.84  5612.2 1860.81  5642.3 1863.33
  5672.4  1865.2  5775.6 1868.78  5792.7  1870.4  5812.7 1870.07  5876.5 1871.34
#Mann= 3 ,-1 , 0
  4227.3     .05       0  5506.8     .05       0  5517.1     .05       0
Bank Sta=5506.8,5517.1
XS Rating Curve= 0 ,0
Exp/Cntr=0.3,0.1

Type RM Length L Ch R = 1 ,76181   ,504,504,504
BEGIN DESCRIPTION:
Rainy Creek 76181.18
END DESCRIPTION:
XS GIS Cut Line= 4
      1618262.38      6823898.31      1619171.38      6824072.54
      1619449.93      6824084.18      1620028.03      6824153.63
#Sta/Elev= 30
    3799 1860.25  4085.6  1857.1  4096.9 1856.42    4209 1855.61  4303.9 1853.99
  4407.9 1853.42  4563.9 1850.99    4569 1850.45  4788.2 1849.63  4848.3 1847.94
  4938.4 1846.67  4974.2 1844.22  5013.3 1843.43  5013.8 1842.93  5023.3 1842.93
  5023.8 1843.43  5075.6  1845.9    5089 1844.11  5109.2 1847.31  5119.2 1850.02
  5139.4 1853.81  5157.8 1855.34  5169.6 1857.05  5327.3 1861.69  5340.8 1863.03
  5421.4 1867.03  5461.7 1867.92  5471.8 1869.05  5552.3 1872.43  5585.6 1872.76
#Mann= 3 ,-1 , 0
    3799     .05       0  5013.3     .05       0  5023.8     .05       0
Bank Sta=5013.3,5023.8
XS Rating Curve= 0 ,0
Exp/Cntr=0.3,0.1

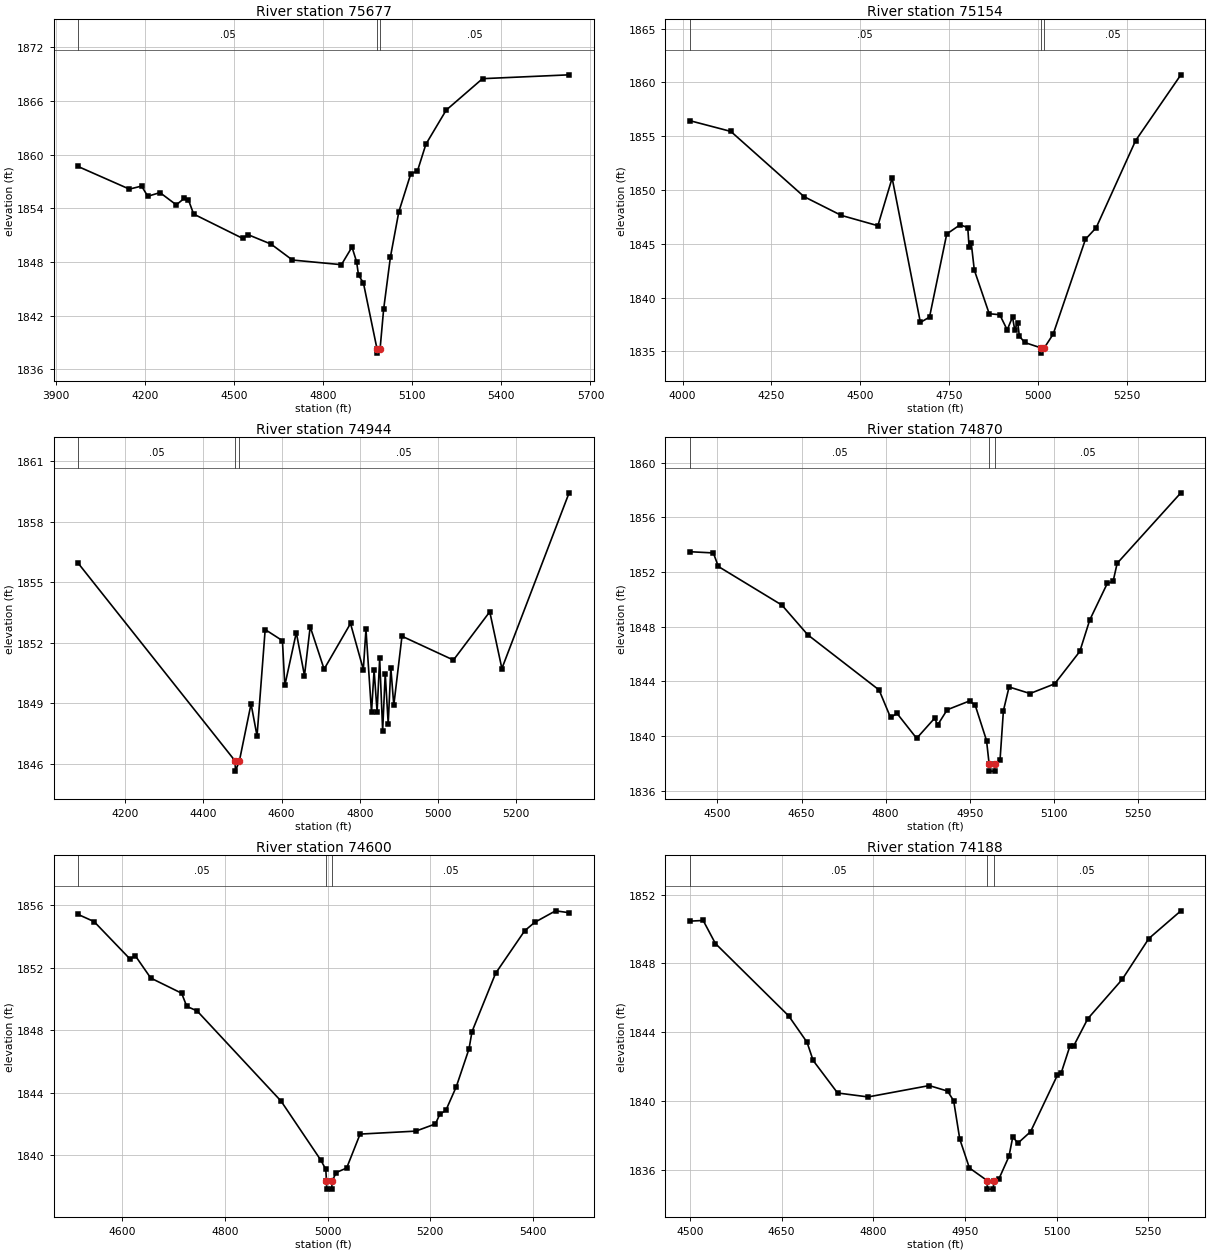
Type RM Length L Ch R = 1 ,75677   ,523,523,523
BEGIN DESCRIPTION:
Mapping XS 7853c820
END DESCRIPTION:
XS GIS Cut Line= 4
      1618327.56      6823942.59      1618957.72      6824101.44
      1619212.93       6824643.1      1619272.75      6825043.61
#Sta/Elev= 30
  3974.4 1858.68  4147.1 1856.15  4188.3 1856.49    4209 1855.35  4250.2 1855.76
  4305.1 1854.39  4332.7 1855.14  4346.2 1854.92  4363.6 1853.36  4528.7 1850.64
  4546.5 1851.06  4624.3    1850  4696.2 1848.22  4861.2  1847.7  4896.8 1849.67
  4912.3 1848.03  4918.9 1846.51  4935.1 1845.69  4980.9 1838.31  4981.4 1837.81
  4991.5 1838.31  5003.4 1842.72  5026.2 1848.55  5054.5 1853.61  5094.6 1857.84
  5117.4 1858.19  5145.7 1861.17    5214 1864.98  5336.4  1868.5    5628 1868.93
#Mann= 3 ,-1 , 0
  3974.4     .05       0  4980.9     .05       0  4991.5     .05       0
Bank Sta=4980.9,4991.5
XS Rating Curve= 0 ,0
Exp/Cntr=0.3,0.1

Type RM Length L Ch R = 1 ,75154   ,210,210,210
BEGIN DESCRIPTION:
Rainy Creek 75153.5
END DESCRIPTION:
XS GIS Cut Line= 6
      1618462.93      6824005.08      1618869.18      6824218.63
      1618885.58      6824411.14      1618762.69      6824450.76
       1618642.9       6824534.1      1618687.89      6824984.22
#Sta/Elev= 30
  4020.6 1856.44  4135.9 1855.44  4341.7 1849.38  4446.3 1847.64  4549.2 1846.68
  4589.3 1851.11  4668.7 1837.69  4694.4 1838.19  4742.8 1845.91  4780.1 1846.76
  4801.9 1846.51  4805.5 1844.74  4811.6 1845.09  4820.3 1842.56  4862.2  1838.5
  4891.9 1838.41  4912.8    1837  4927.7  1838.2  4933.8 1837.03  4942.5 1837.68
  4946.9 1836.43  4961.7 1835.83  5006.6 1835.34  5007.1 1834.84  5017.3 1835.34
  5042.1 1836.61  5132.8 1845.42    5163  1846.5  5273.8 1854.59    5401  1860.7
#Mann= 3 ,-1 , 0
  4020.6     .05       0  5006.6     .05       0  5017.3     .05       0
Bank Sta=5006.6,5017.3
XS Rating Curve= 0 ,0
Exp/Cntr=0.3,0.1

Type RM Length L Ch R = 1 ,74944   ,74,74,74
BEGIN DESCRIPTION:
Rainy Creek 74943.95
END DESCRIPTION:
XS GIS Cut Line= 6
      1618475.93      6824041.52      1618790.47      6824353.54
      1618585.61      6824502.85      1618483.18       6824620.9
      1618486.65      6824690.35      1618597.19       6825004.7
#Sta/Elev= 30
  4079.6 1855.95  4481.3 1846.15  4481.8 1845.65    4492 1846.15  4521.9 1848.98
  4537.2 1847.39    4558 1852.66  4602.1 1852.11  4608.2 1849.89  4637.6 1852.51
  4658.5 1850.38  4673.1  1852.8  4708.7  1850.7  4776.2 1852.96    4809 1850.68
  4815.7 1852.67  4829.9 1848.56  4836.5 1850.65  4844.2 1848.59  4850.8 1851.23
  4858.4 1847.66    4865 1850.48  4872.6    1848  4879.3 1850.77  4886.9 1848.91
  4907.8 1852.33  5039.4 1851.15  5132.3 1853.54  5163.3 1850.73  5335.2 1859.43
#Mann= 3 ,-1 , 0
  4079.6     .05       0  4481.3     .05       0    4492     .05       0
Bank Sta=4481.3,4492
XS Rating Curve= 0 ,0
Exp/Cntr=0.3,0.1

Type RM Length L Ch R = 1 ,74870   ,270,270,270
BEGIN DESCRIPTION:
Rainy Creek 74869.68
END DESCRIPTION:
XS GIS Cut Line= 5
      1618500.55      6824146.92      1618422.42      6824544.51
        1618412.      6824692.08      1618424.15      6824775.42
      1618491.63      6825003.81
#Sta/Elev= 30
  4450.9 1853.49  4492.8  1853.4  4501.7 1852.41  4615.1 1849.58  4661.1 1847.41
  4788.3 1843.37  4808.7 1841.36  4820.4 1841.65  4855.3 1839.83  4887.5 1841.31
  4892.6  1840.8  4909.7 1841.92  4949.8 1842.57  4959.8 1842.24  4979.9 1839.67
  4984.6 1837.93  4985.1 1837.43  4994.8 1837.43  4995.3 1837.93    5004 1838.26
    5010 1841.86  5020.1 1843.59  5057.5 1843.11  5101.4 1843.82  5146.2 1846.19
  5163.9 1848.49  5195.2 1851.17  5205.6 1851.32  5212.8 1852.64  5326.4  1857.8
#Mann= 3 ,-1 , 0
  4450.9     .05       0  4984.6     .05       0  4995.3     .05       0
Bank Sta=4984.6,4995.3
XS Rating Curve= 0 ,0
Exp/Cntr=0.3,0.1

Type RM Length L Ch R = 1 ,74600   ,412,412,412
BEGIN DESCRIPTION:
Rainy Creek 74599.5
END DESCRIPTION:
XS GIS Cut Line= 3
      1618114.52      6824156.92      1618158.79      6824646.51
      1618247.16      6825103.97
#Sta/Elev= 30
  4513.6 1855.41  4544.8 1854.95  4615.1 1852.55  4625.1 1852.77  4655.3 1851.34
  4715.5 1850.37  4725.5 1849.53  4745.6 1849.24  4909.4 1843.47  4986.6 1839.71
  4996.6 1839.11    4998 1838.34  4998.5 1837.84  5008.3 1837.84  5008.8 1838.34
  5016.9  1838.9  5037.3 1839.19  5063.5 1841.36  5172.2 1841.55  5210.4 1842.01
    5219 1842.63  5230.8 1842.88  5251.1 1844.39  5275.9 1846.81  5281.7 1847.91
  5327.7 1851.64  5384.6 1854.37  5403.9  1854.9  5444.7 1855.64  5471.1 1855.52
#Mann= 3 ,-1 , 0
  4513.6     .05       0    4998     .05       0  5008.8     .05       0
Bank Sta=4998,5008.8
XS Rating Curve= 0 ,0
Exp/Cntr=0.3,0.1

Type RM Length L Ch R = 1 ,74188   ,84,84,84
BEGIN DESCRIPTION:
Rainy Creek 74187.63
END DESCRIPTION:
XS GIS Cut Line= 4
      1617829.25      6824366.25      1617824.04      6824824.61
      1617827.51      6824869.75      1618008.09      6825109.36
#Sta/Elev= 30
  4499.7 1850.46  4521.5  1850.5  4541.5 1849.16  4661.5 1844.95  4691.5 1843.42
  4701.5 1842.36  4741.5 1840.47  4791.5 1840.24  4891.5  1840.9  4921.5 1840.58
  4931.5 1840.02  4941.5 1837.79  4957.3 1836.11  4986.2 1835.38  4986.7 1834.88
  4996.5 1834.88    4997 1835.38  5005.4 1835.46    5022 1836.78  5028.3 1837.92
  5036.6 1837.55  5057.4 1838.22  5101.1 1841.49  5107.4 1841.62    5122 1843.22
  5128.2 1843.22  5151.1 1844.79  5207.3 1847.07    5251 1849.45  5303.4 1851.06
#Mann= 3 ,-1 , 0
  4499.7     .05       0  4986.2     .05       0    4997     .05       0
Bank Sta=4986.2,4997
XS Rating Curve= 0 ,0
Exp/Cntr=0.3,0.1

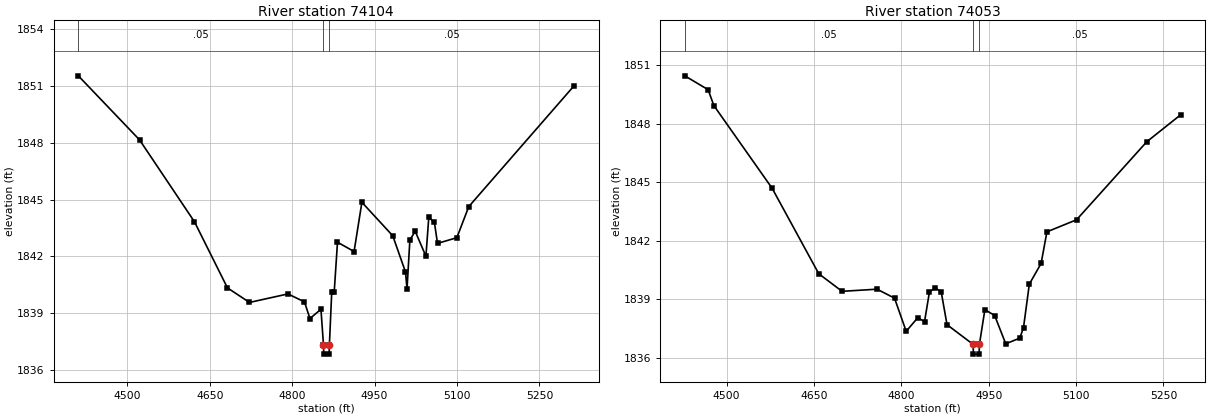
Type RM Length L Ch R = 1 ,74104   ,51,51,51
BEGIN DESCRIPTION:
Rainy Creek 74104.45
END DESCRIPTION:
XS GIS Cut Line= 5
      1617770.22      6824336.81      1617754.59      6824802.04
      1617768.48      6824928.77      1617782.37      6824979.12
      1617954.22      6825170.06
#Sta/Elev= 30
    4411 1851.54  4522.3 1848.16  4622.3 1843.83  4682.3 1840.34  4722.4 1839.57
  4792.4 1840.02  4822.4  1839.6  4832.4 1838.72  4852.4 1839.21    4857 1837.34
  4857.5 1836.84  4867.3 1836.84  4867.8 1837.34    4872  1840.1  4876.5  1840.1
  4882.5 1842.75  4912.7 1842.26  4926.9 1844.86  4983.1 1843.09  5006.2 1841.18
    5009 1840.28  5014.2 1842.87  5023.9 1843.33  5043.4 1842.01  5048.6 1844.06
  5058.8  1843.8  5064.5 1842.69  5099.7 1842.99  5121.3 1844.63  5313.1 1851.02
#Mann= 3 ,-1 , 0
    4411     .05       0    4857     .05       0  4867.8     .05       0
Bank Sta=4857,4867.8
XS Rating Curve= 0 ,0
Exp/Cntr=0.3,0.1

Type RM Length L Ch R = 1 ,74053   ,547,547,547
BEGIN DESCRIPTION:
Rainy Creek 74052.87
END DESCRIPTION:
XS GIS Cut Line= 6
      1617705.98      6824368.05      1617700.77      6824779.47
      1617711.19      6824895.79      1617719.87      6824939.19
      1617730.29      6825027.73      1617855.29      6825170.09
#Sta/Elev= 30
  4428.4 1850.46  4468.4 1849.75  4478.4 1848.93  4578.4 1844.69  4658.4 1840.31
  4698.4 1839.41  4758.4 1839.52  4788.4 1839.06  4808.4 1837.36  4828.4 1838.06
  4839.9 1837.85  4848.4 1839.39  4858.5 1839.58  4868.5 1839.39  4878.5  1837.7
  4923.3 1836.69  4923.8 1836.19  4933.6 1836.19  4934.1 1836.69  4943.5 1838.47
  4960.3 1838.17  4979.3 1836.72  5003.4 1837.01  5009.8 1837.55  5019.8 1839.78
    5040 1840.84    5050 1842.46  5100.9 1843.08  5221.4 1847.08  5279.5 1848.46
#Mann= 3 ,-1 , 0
  4428.4     .05       0  4923.3     .05       0  4934.1     .05       0
Bank Sta=4923.3,4934.1
XS Rating Curve= 0 ,0
Exp/Cntr=0.3,0.1