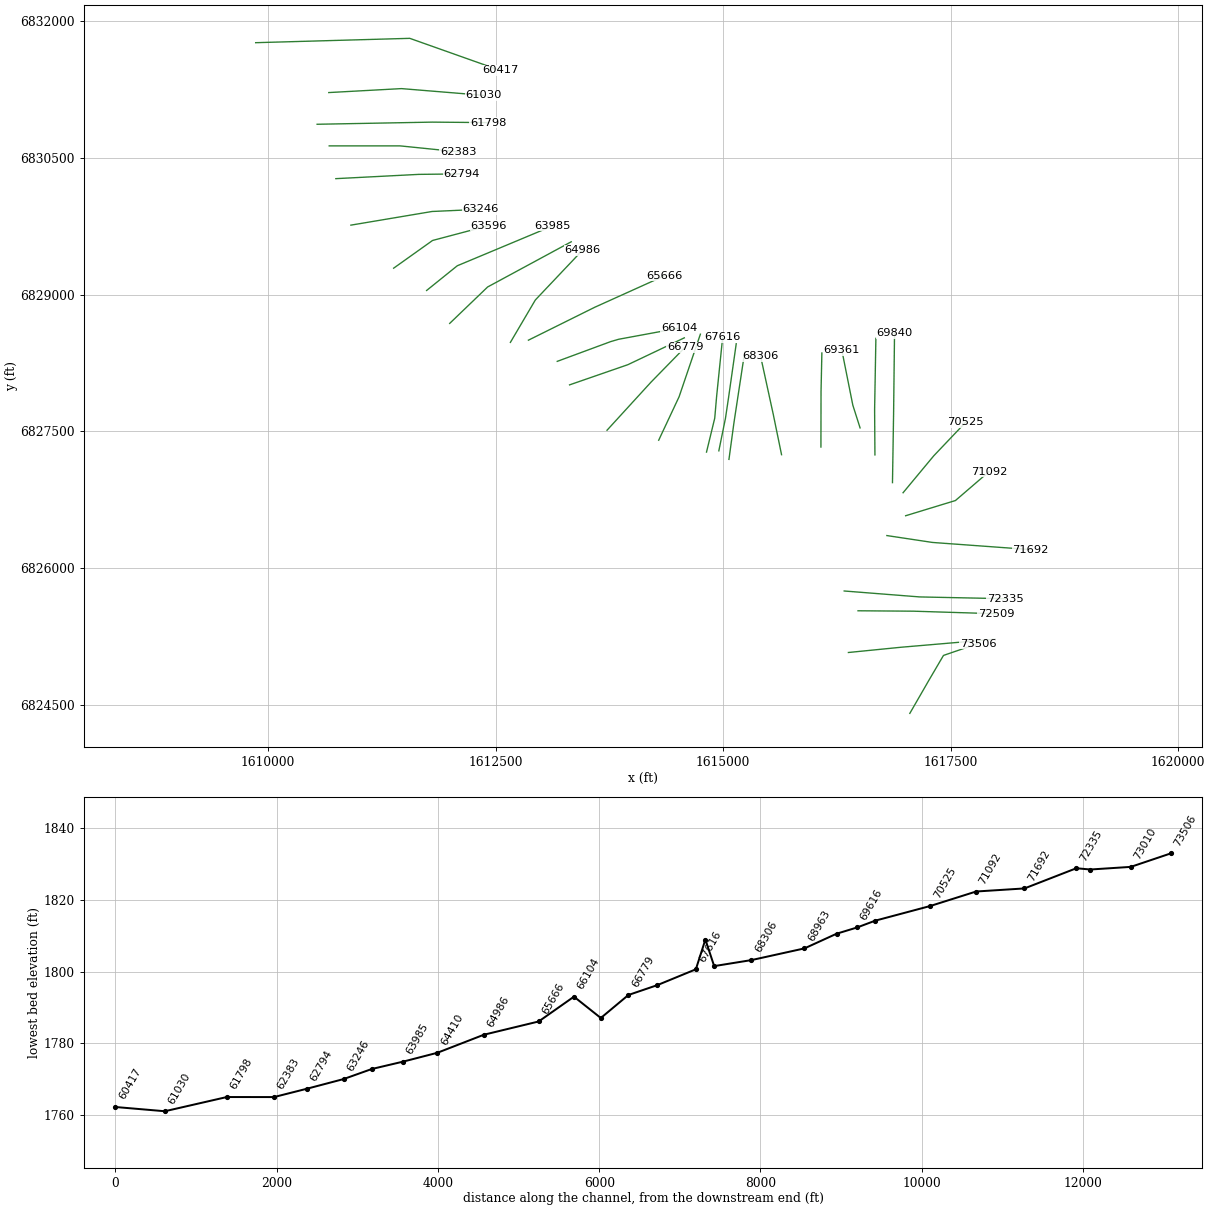
HEC-RAS study Rainy Creek.prj: Rainy Creek Base Level Engineering

--- Rainy Creek.g01 (geometry) --- (continued)

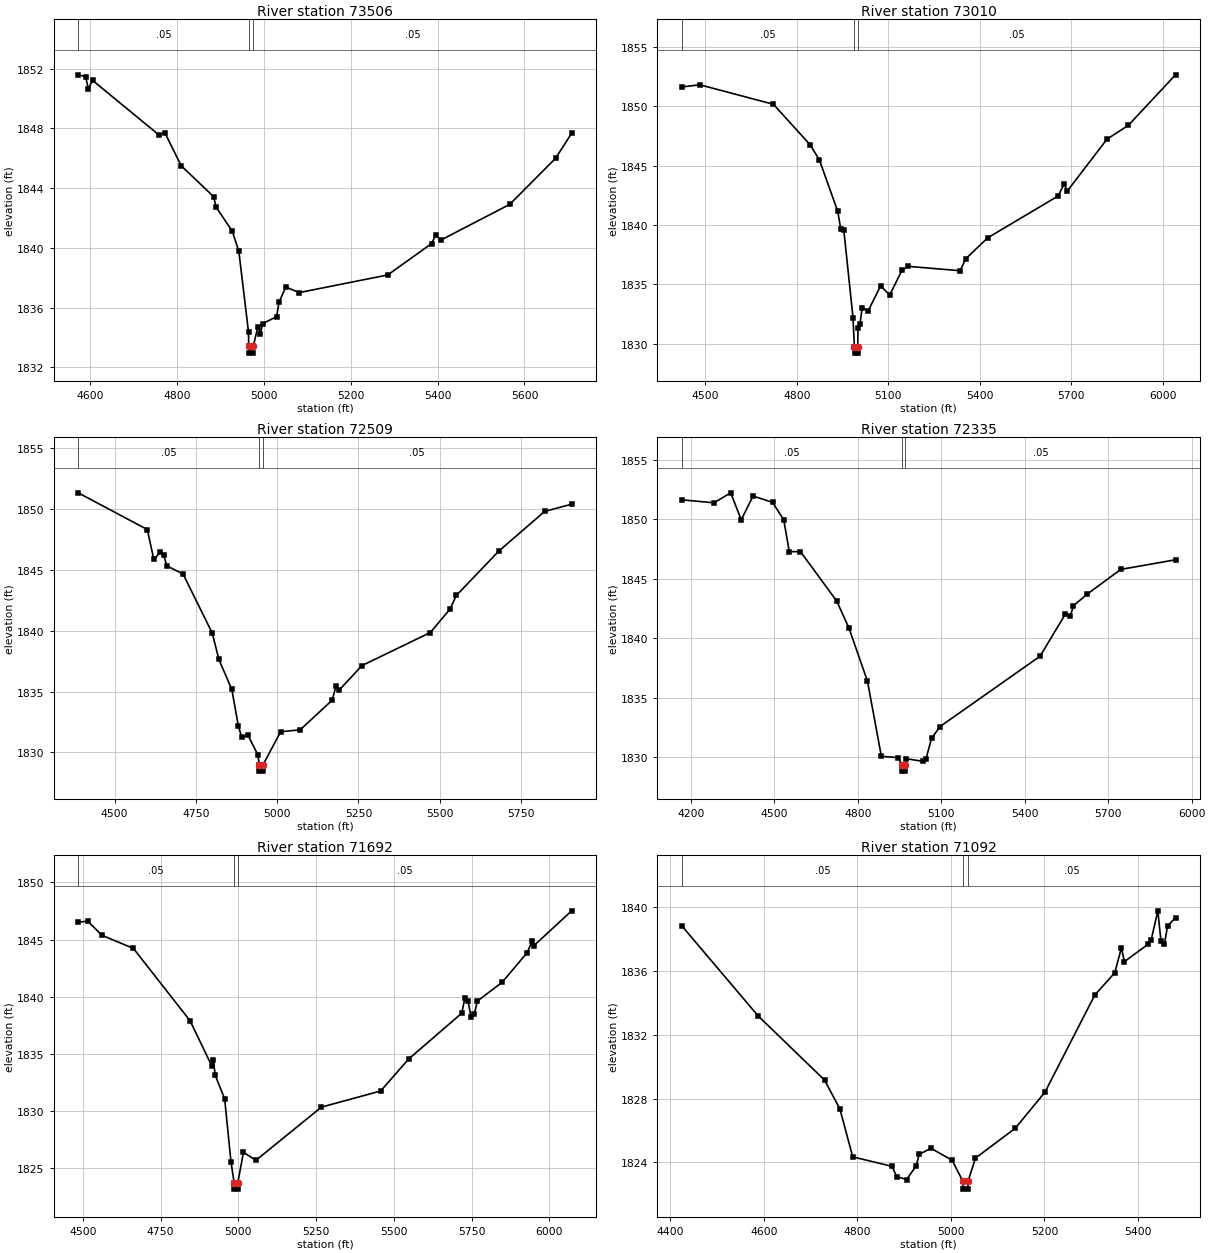
Type RM Length L Ch R = 1 ,73506   ,496,496,496
BEGIN DESCRIPTION:
Rainy Creek 73505.6
END DESCRIPTION:
XS GIS Cut Line= 4
      1617051.49      6824407.98      1617265.01      6824777.73
      1617421.26      6825043.36      1617799.92      6825173.03
#Sta/Elev= 30
  4573.2 1851.58  4590.4 1851.46  4596.3 1850.64  4606.2 1851.21    4758 1847.58
  4772.8 1847.69  4810.1  1845.5  4884.7 1843.43  4890.5 1842.73  4927.8 1841.11
  4942.8 1839.77  4965.1 1834.35  4965.4 1833.46  4965.9 1832.96  4975.8 1832.96
  4976.3 1833.46  4986.7 1834.73  4992.4 1834.27  4997.4 1834.93  5029.6  1835.4
  5035.4 1836.39  5051.1 1837.38  5081.7 1837.01  5285.4 1838.19  5386.3 1840.29
  5395.7 1840.86  5407.4 1840.52    5566 1842.91  5671.7    1846  5708.6 1847.67
#Mann= 3 ,-1 , 0
  4573.2     .05       0  4965.4     .05       0  4976.3     .05       0
Bank Sta=4965.4,4976.3
XS Rating Curve= 0 ,0
Exp/Cntr=0.3,0.1

Type RM Length L Ch R = 1 ,73010   ,501,501,501
BEGIN DESCRIPTION:
Rainy Creek 73009.9
END DESCRIPTION:
XS GIS Cut Line= 3
      1616377.02      6825075.48      1616952.51      6825132.77
        1617989.      6825221.31
#Sta/Elev= 30
  4423.9 1851.62  4482.2  1851.8  4723.4 1850.16  4843.9 1846.75  4874.1 1845.49
  4934.4 1841.15  4944.4 1839.67  4954.5 1839.55  4984.6 1832.18  4989.2  1829.7
  4989.7  1829.2  4999.6  1829.2  5000.1  1829.7    5001 1831.29  5007.4 1831.63
  5014.8 1833.03  5034.8 1832.78    5075 1834.86  5105.1  1834.1  5145.2 1836.18
  5165.3 1836.51  5335.9 1836.14  5354.2 1837.14  5426.3 1838.91  5657.1 1842.43
  5677.2 1843.44  5687.2 1842.84  5817.7 1847.22  5887.9 1848.39  6042.5 1852.64
#Mann= 3 ,-1 , 0
  4423.9     .05       0  4989.2     .05       0  5000.1     .05       0
Bank Sta=4989.2,5000.1
XS Rating Curve= 0 ,0
Exp/Cntr=0.3,0.1

Type RM Length L Ch R = 1 ,72509   ,174,174,174
BEGIN DESCRIPTION:
Rainy Creek 72508.98
END DESCRIPTION:
XS GIS Cut Line= 3
      1616482.57      6825532.85      1617088.01      6825528.51
      1617999.42       6825500.3
#Sta/Elev= 30
  4388.3  1851.3  4600.7 1848.29  4620.7 1845.85  4640.7 1846.41  4650.7 1846.24
  4660.7 1845.31  4710.7 1844.64  4800.7 1839.78  4820.7 1837.64  4860.7 1835.17
  4880.7 1832.17  4890.7 1831.28  4910.7  1831.4  4940.7  1829.8  4945.2 1828.97
  4945.7 1828.47  4955.7 1828.47  4956.2 1828.97  5010.8  1831.7  5070.8 1831.86
  5168.9 1834.28  5180.8 1835.42  5190.8 1835.12  5260.9 1837.13    5471 1839.84
    5531 1841.74    5551 1842.88  5681.1 1846.51  5822.3 1849.77  5905.6 1850.37
#Mann= 3 ,-1 , 0
  4388.3     .05       0  4945.2     .05       0  4956.2     .05       0
Bank Sta=4945.2,4956.2
XS Rating Curve= 0 ,0
Exp/Cntr=0.3,0.1

Type RM Length L Ch R = 1 ,72335   ,643,643,643
BEGIN DESCRIPTION:
Rainy Creek 72334.82
END DESCRIPTION:
XS GIS Cut Line= 3
      1616330.66      6825749.86      1617159.63      6825684.76
      1618101.81      6825665.27
#Sta/Elev= 30
  4168.1 1851.63  4282.8 1851.38    4343 1852.22  4380.8 1849.95  4423.2 1851.95
  4493.4 1851.42  4533.6 1849.95  4553.6 1847.27  4593.7 1847.28  4724.1 1843.12
    4768 1840.85  4834.5 1836.39  4884.6 1830.06  4944.8 1829.96  4959.4 1829.32
  4959.9 1828.82  4969.9 1828.82  4970.4 1829.32  4974.9 1829.86    5035 1829.64
    5045 1829.86    5065 1831.57    5095 1832.56  5455.1 1838.48  5545.1 1841.99
  5564.2 1841.89  5575.1 1842.73  5625.1 1843.71  5745.1 1845.78    5942 1846.59
#Mann= 3 ,-1 , 0
  4168.1     .05       0  4959.4     .03       0  4970.4     .05       0
Bank Sta=4959.4,4970.4
XS Rating Curve= 0 ,0
Exp/Cntr=0.3,0.1

Type RM Length L Ch R = 1 ,71692   ,600,600,600
BEGIN DESCRIPTION:
Rainy Creek 71692.31
END DESCRIPTION:
XS GIS Cut Line= 3
      1616799.37      6826357.51      1617301.99      6826281.99
       1618377.5      6826203.86
#Sta/Elev= 30
  4485.1 1846.53  4515.8 1846.61  4561.6 1845.38  4662.7 1844.23  4844.7 1837.91
  4914.8 1833.95  4919.9 1834.44  4925.6 1833.14    4956 1831.08  4976.2  1825.6
  4986.8 1823.69  4987.3 1823.19  4997.4 1823.19  4997.9 1823.69  5016.4 1826.41
  5056.5 1825.71  5267.1 1830.36  5457.6 1831.77  5547.8 1834.57  5718.3 1838.57
  5728.3 1839.89  5738.3 1839.67  5748.4  1838.2  5758.4 1838.46  5768.4 1839.63
  5848.6 1841.28  5928.8 1843.87  5944.7 1844.88  5949.7 1844.46  6071.7 1847.52
#Mann= 3 ,-1 , 0
  4485.1     .05       0  4986.8     .05       0  4997.9     .05       0
Bank Sta=4986.8,4997.9
XS Rating Curve= 0 ,0
Exp/Cntr=0.3,0.1

Type RM Length L Ch R = 1 ,71092   ,567,567,567
BEGIN DESCRIPTION:
Rainy Creek 71091.68
END DESCRIPTION:
XS GIS Cut Line= 3
      1617005.79      6826574.96      1617552.64      6826741.62
       1617919.8       6827056.7
#Sta/Elev= 30
    4425  1838.8    4588 1833.17  4729.8 1829.16  4762.6 1827.35  4790.1 1824.35
  4873.7 1823.76  4884.2 1823.12  4905.1 1822.93    4926 1823.79    4932  1824.5
  4957.3 1824.89  5002.6 1824.14  5025.5 1822.83    5026 1822.33  5036.3 1822.33
  5036.8 1822.83  5052.5 1824.27  5137.6 1826.14  5201.2  1828.4  5307.7 1834.48
  5350.5 1835.88  5364.7 1837.43  5371.3 1836.58  5421.5 1837.66  5428.4 1837.94
  5442.7 1839.76  5449.3 1837.87  5456.9 1837.69  5463.5 1838.81  5480.5 1839.34
#Mann= 3 ,-1 , 0
    4425     .05       0  5025.5     .05       0  5036.8     .05       0
Bank Sta=5025.5,5036.8
XS Rating Curve= 0 ,0
Exp/Cntr=0.3,0.1

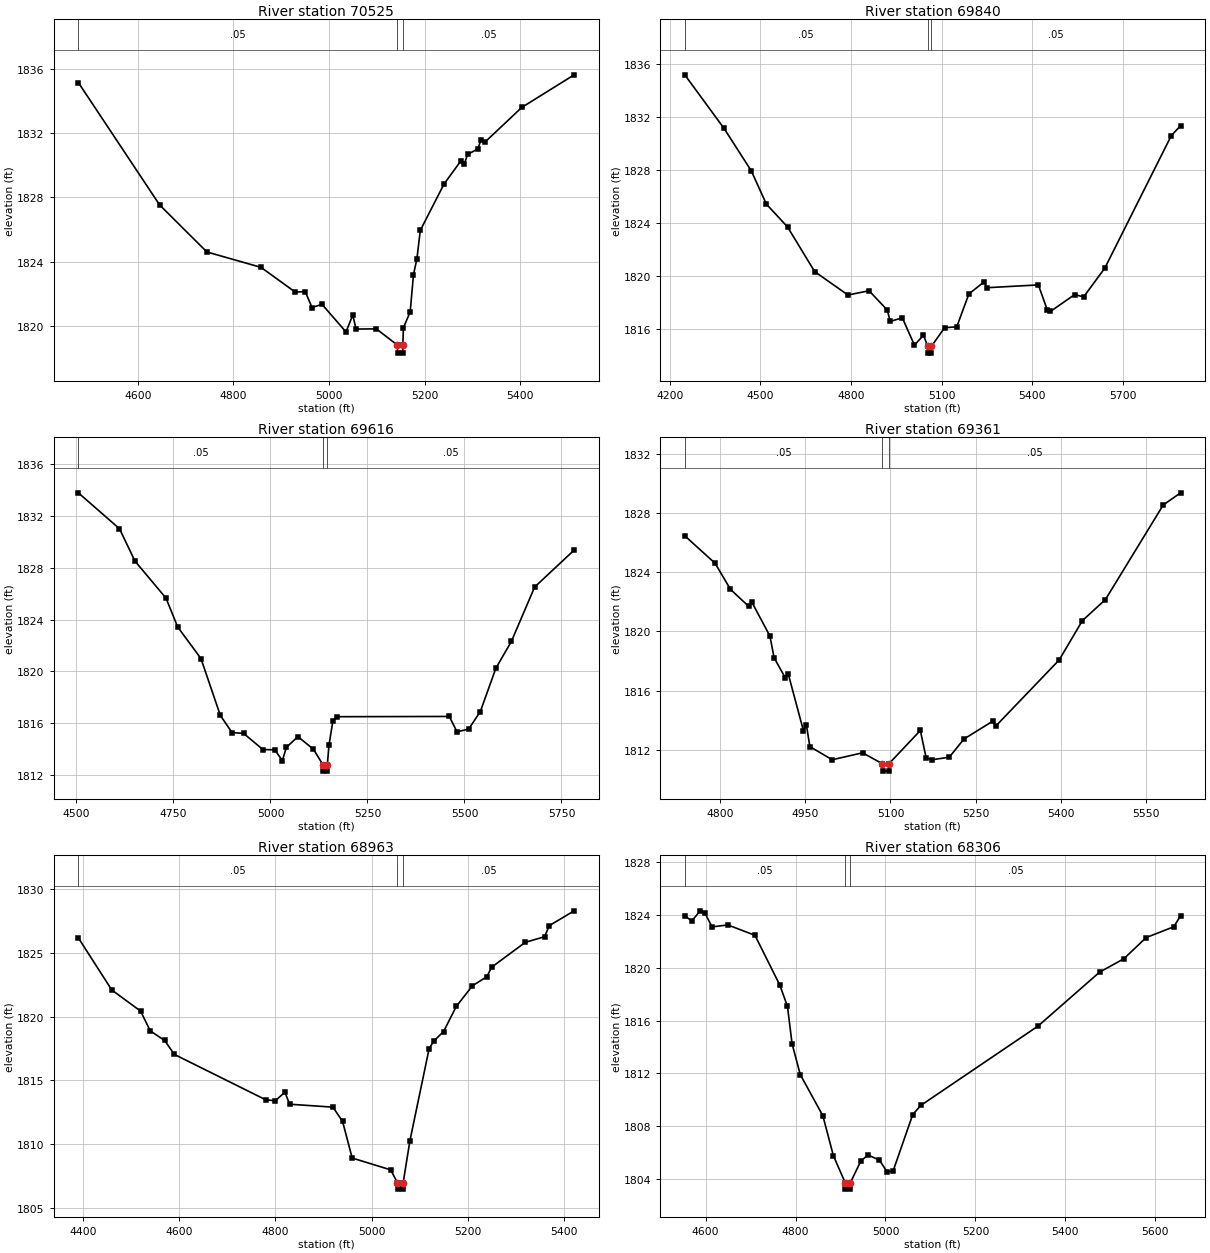
Type RM Length L Ch R = 1 ,70525   ,685,685,685
BEGIN DESCRIPTION:
Rainy Creek 70524.55
END DESCRIPTION:
XS GIS Cut Line= 3
      1616977.31      6826827.11       1617314.1      6827231.61
      1617666.54      6827601.41
#Sta/Elev= 30
  4475.6 1835.15  4645.6 1827.53  4744.5  1824.6  4857.8 1823.64  4929.4  1822.1
  4950.2 1822.13  4964.5 1821.14  4985.3 1821.34  5035.5 1819.62  5049.7 1820.67
  5056.6  1819.8    5099 1819.81    5143  1818.8  5143.5  1818.3  5153.9  1818.3
  5154.4  1818.8  5155.6 1819.88  5169.8 1820.87  5176.7 1823.19  5183.9 1824.18
  5190.9 1825.94  5240.6 1828.83  5275.8 1830.27    5283 1830.08  5289.9 1830.67
  5311.3 1831.02  5318.2  1831.6  5325.5 1831.42  5403.2  1833.6  5512.8 1835.63
#Mann= 3 ,-1 , 0
  4475.6     .05       0    5143     .05       0  5154.4     .05       0
Bank Sta=5143,5154.4
XS Rating Curve= 0 ,0
Exp/Cntr=0.3,0.1

Type RM Length L Ch R = 1 ,69840   ,224,224,224
BEGIN DESCRIPTION:
Rainy Creek 69839.97
END DESCRIPTION:
XS GIS Cut Line= 3
      1616860.97      6826938.16      1616873.13      6827689.94
      1616883.54       6828578.8
#Sta/Elev= 30
  4250.2 1835.16  4380.1 1831.12  4470.1 1827.93  4520.1 1825.42  4590.1  1823.7
  4680.1 1820.33  4790.1 1818.57  4860.1 1818.89  4920.1 1817.44  4930.1 1816.58
  4970.1 1816.85  5010.1 1814.79  5040.1 1815.54  5054.4 1814.69  5054.9 1814.19
  5065.4 1814.19  5065.9 1814.69  5110.1 1816.11  5150.2 1816.17  5190.2 1818.65
  5240.2 1819.55  5250.2 1819.12  5420.2 1819.33  5450.2 1817.42  5460.2 1817.33
  5540.2  1818.6  5570.2 1818.43  5640.2  1820.6  5860.2 1830.58    5891 1831.33
#Mann= 3 ,-1 , 0
  4250.2     .05       0  5054.4     .05       0  5065.9     .05       0
Bank Sta=5054.4,5065.9
XS Rating Curve= 0 ,0
Exp/Cntr=0.3,0.1

Type RM Length L Ch R = 1 ,69616   ,255,255,255
BEGIN DESCRIPTION:
Rainy Creek 69801.739
END DESCRIPTION:
XS GIS Cut Line= 3
      1616668.26      6827242.03      1616664.67      6827737.21
      1616678.68      6828519.79
#Sta/Elev= 30
  4504.8 1833.78  4610.8 1831.01  4650.8 1828.51  4730.8 1825.65  4760.8 1823.43
  4820.8 1820.99  4870.8  1816.6  4900.8 1815.28  4930.8 1815.21  4980.8 1813.96
  5010.8 1813.95  5030.8 1813.11  5040.8 1814.13  5070.8 1814.96  5110.8 1813.99
  5135.1  1812.8  5135.6  1812.3  5146.1  1812.3  5146.6  1812.8  5150.8 1814.31
  5160.8 1816.16  5170.8  1816.5  5460.9 1816.52  5480.9 1815.33  5510.9 1815.55
  5540.9  1816.9  5580.9 1820.24  5620.9 1822.31  5680.9 1826.51  5782.7 1829.36
#Mann= 3 ,-1 , 0
  4504.8     .05       0  5135.1     .05       0  5146.6     .05       0
Bank Sta=5135.1,5146.6
XS Rating Curve= 0 ,0
Exp/Cntr=0.3,0.1

Type RM Length L Ch R = 1 ,69361   ,398,398,398
BEGIN DESCRIPTION:
Rainy Creek 69360.629
END DESCRIPTION:
XS GIS Cut Line= 3
      1616505.01      6827537.98      1616425.09      6827788.23
        1616305.      6828388.02
#Sta/Elev= 30
  4737.3 1826.47  4790.8 1824.61  4817.8 1822.85    4850  1821.7  4855.2 1822.01
  4887.4 1819.69  4894.8 1818.22  4914.3 1816.88  4919.6 1817.15  4946.5 1813.29
  4951.8 1813.67  4957.8 1812.21  4997.3 1811.32  5050.8 1811.79  5085.8 1811.05
  5086.3 1810.55  5096.8 1810.55  5097.3 1811.05  5152.7  1813.3  5162.9 1811.45
  5173.1 1811.32  5203.7 1811.49  5229.5 1812.72  5280.4 1813.93  5285.5 1813.59
  5397.5 1818.07  5438.4 1820.73  5479.1 1822.16  5581.1 1828.56  5611.7 1829.38
#Mann= 3 ,-1 , 0
  4737.3     .05       0  5085.8     .05       0  5097.3     .05       0
Bank Sta=5085.8,5097.3
XS Rating Curve= 0 ,0
Exp/Cntr=0.3,0.1

Type RM Length L Ch R = 1 ,68963   ,657,657,657
BEGIN DESCRIPTION:
Rainy Creek 68884.305
END DESCRIPTION:
XS GIS Cut Line= 3
      1616074.92      6827328.36      1616076.11      6827938.16
      1616085.34      6828359.56
#Sta/Elev= 30
  4390.2 1826.17  4459.8 1822.08  4519.8 1820.42  4539.8 1818.87  4569.8 1818.12
  4589.8 1817.03  4779.8 1813.47  4799.8 1813.39  4819.8 1814.06  4829.8 1813.12
  4919.8 1812.89  4939.8 1811.77  4959.8  1808.9  5039.9 1807.97    5054 1806.96
  5054.5 1806.46  5065.3 1806.46  5065.8 1806.96  5079.9 1810.26  5119.9 1817.49
  5129.9 1818.09  5149.9 1818.82  5176.3 1820.79  5209.9 1822.41  5239.9 1823.12
  5249.9 1823.87  5319.9 1825.82  5359.9 1826.26  5369.9 1827.13  5421.5 1828.29
#Mann= 3 ,-1 , 0
  4390.2     .05       0    5054     .05       0  5065.8     .05       0
Bank Sta=5054,5065.8
XS Rating Curve= 0 ,0
Exp/Cntr=0.3,0.1

Type RM Length L Ch R = 1 ,68306   ,463,463,463
BEGIN DESCRIPTION:
Rainy Creek 68306.08
END DESCRIPTION:
XS GIS Cut Line= 3
      1615642.34      6827244.26      1615551.19      6827686.98
      1615412.29      6828322.88
#Sta/Elev= 30
  4553.6 1823.95    4569 1823.56    4588 1824.33  4598.3 1824.16  4614.2 1823.11
  4649.3 1823.26  4709.7 1822.47  4765.1 1818.68    4782 1817.07  4792.2 1814.24
  4810.4  1811.9  4860.7 1808.77  4884.1 1805.74  4910.2  1803.7  4910.7  1803.2
  4921.6  1803.2  4922.1  1803.7  4945.4 1805.35  4961.3 1805.79  4986.2 1805.41
  5003.6 1804.52  5016.9 1804.57  5060.5 1808.85  5078.3 1809.55  5339.3 1815.58
  5476.1 1819.67  5530.2 1820.69  5579.9  1822.3  5641.3 1823.12  5656.5 1823.96
#Mann= 3 ,-1 , 0
  4553.6     .05       0  4910.2     .05       0  4922.1     .05       0
Bank Sta=4910.2,4922.1
XS Rating Curve= 0 ,0
Exp/Cntr=0.3,0.1

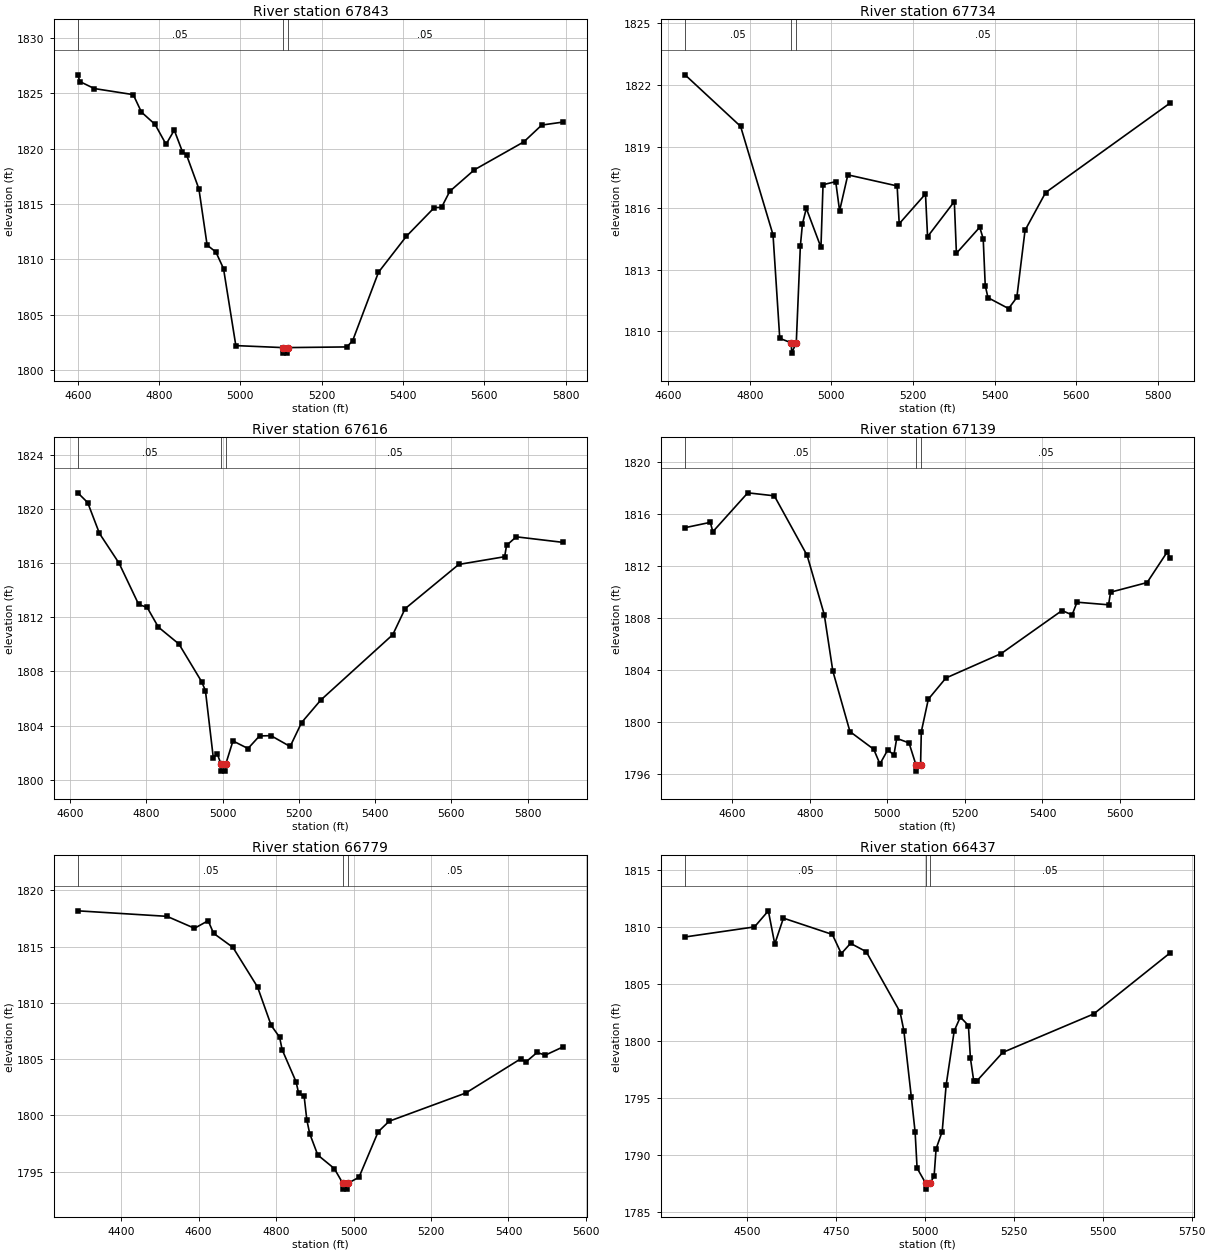
Type RM Length L Ch R = 1 ,67843   ,109,109,109
BEGIN DESCRIPTION:
Rainy Creek 67842.83
END DESCRIPTION:
XS GIS Cut Line= 3
      1615064.51      6827192.96      1615120.06      6827599.17
      1615238.08      6828373.23
#Sta/Elev= 30
  4600.2 1826.67  4605.3 1826.06  4640.7 1825.43  4736.5 1824.88  4756.7  1823.3
  4790.2 1822.19  4817.2 1820.39  4837.4 1821.67  4857.4 1819.73  4867.7 1819.42
    4898 1816.36  4918.2 1811.28  4939.7 1810.66  4958.5 1809.16  4988.8  1802.2
  5104.2 1802.02  5104.7 1801.52  5115.7 1801.52  5116.2 1802.02  5261.9 1802.08
  5276.1 1802.65  5339.6 1808.83  5408.2 1812.08  5476.8 1814.67  5494.6 1814.69
  5514.8 1816.14  5575.5 1818.09  5696.9 1820.61    5741 1822.13  5793.2  1822.4
#Mann= 3 ,-1 , 0
  4600.2     .05       0  5104.2     .05       0  5116.2     .05       0
Bank Sta=5104.2,5116.2
XS Rating Curve= 0 ,0
Exp/Cntr=0.3,0.1

Type RM Length L Ch R = 1 ,67734   ,118,118,118
BEGIN DESCRIPTION:
Rainy Creek 67733.73
END DESCRIPTION:
XS GIS Cut Line= 4
      1614953.39      6827286.66      1615026.31       6827644.3
      1615057.56      6827852.64      1615144.37       6828460.3
#Sta/Elev= 30
  4641.1 1822.49  4777.3 1819.98  4856.8  1814.7  4873.3 1809.66  4901.8 1809.44
  4902.3 1808.94  4913.8 1809.44  4923.8 1814.15  4928.9 1815.23  4938.4 1815.99
  4974.3 1814.09  4979.4 1817.14  5010.5 1817.29    5020 1815.87  5040.2 1817.62
  5161.1 1817.08  5166.2 1815.24  5230.6 1816.69  5235.7 1814.61  5301.3 1816.32
  5306.4  1813.8  5363.6 1815.07  5372.1 1814.51  5377.1 1812.23  5383.8 1811.64
  5434.3 1811.11  5454.5 1811.65  5474.7 1814.92  5525.2 1816.76  5830.6 1821.12
#Mann= 3 ,-1 , 0
  4641.1     .05       0  4901.8     .05       0  4913.8     .05       0
Bank Sta=4901.8,4913.8
XS Rating Curve= 0 ,0
Exp/Cntr=0.3,0.1

Type RM Length L Ch R = 1 ,67616   ,477,477,477
BEGIN DESCRIPTION:
Rainy Creek 67615.91
END DESCRIPTION:
XS GIS Cut Line= 4
      1614817.98      6827272.81      1614908.25       6827644.3
      1614929.09      6827883.89      1614995.06      6828529.74
#Sta/Elev= 30
  4620.5 1821.19  4646.4 1820.47  4677.3 1818.19  4728.7 1815.99  4780.2 1812.94
  4802.2 1812.73  4831.7 1811.27  4885.7 1810.02  4944.9 1807.25  4955.1 1806.58
  4975.7 1801.63    4986 1801.92  4996.1 1801.13  4996.6 1800.63  5007.7 1800.63
  5008.2 1801.13  5027.3 1802.86  5066.7  1802.3  5096.9 1803.23    5127 1803.25
  5177.2 1802.45  5207.3 1804.22  5257.5 1805.88  5446.3 1810.71  5478.6 1812.63
  5619.3  1815.9  5739.6 1816.47  5744.6 1817.31  5770.1 1817.94  5892.5 1817.53
#Mann= 3 ,-1 , 0
  4620.5     .05       0  4996.1     .05       0  5008.2     .05       0
Bank Sta=4996.1,5008.2
XS Rating Curve= 0 ,0
Exp/Cntr=0.3,0.1

Type RM Length L Ch R = 1 ,67139   ,360,360,360
BEGIN DESCRIPTION:
Rainy Creek 67138.96
END DESCRIPTION:
XS GIS Cut Line= 3
       1614292.8      6827403.12      1614516.76      6827879.69
      1614750.58      6828565.55
#Sta/Elev= 30
  4478.3 1814.94  4543.4 1815.35    4550 1814.63  4640.1 1817.62  4708.5 1817.39
  4793.1 1812.81  4837.3 1808.26  4859.4 1803.92  4903.6 1799.26  4964.9  1797.9
  4980.9 1796.77  5001.2 1797.86  5016.9 1797.45  5024.2 1798.74  5055.9 1798.39
  5073.6 1796.72  5074.1 1796.22  5085.7 1796.72  5087.6 1799.25  5105.7 1801.75
    5151 1803.38  5293.7 1805.26  5450.5 1808.57  5476.5 1808.23  5489.1 1809.21
  5570.5 1809.01  5575.8 1809.98  5669.9 1810.72  5721.5 1813.06  5729.5  1812.6
#Mann= 3 ,-1 , 0
  4478.3     .05       0  5073.6     .03       0  5085.7     .05       0
Bank Sta=5073.6,5085.7
XS Rating Curve= 0 ,0
Exp/Cntr=0.3,0.1

Type RM Length L Ch R = 1 ,66779   ,342,342,342
BEGIN DESCRIPTION:
Rainy Creek 66779.21
END DESCRIPTION:
XS GIS Cut Line= 3
      1613725.06      6827512.47      1614209.47      6828041.15
      1614584.03      6828423.51
#Sta/Elev= 30
  4288.3 1818.18  4518.6 1817.69  4589.5 1816.63  4624.7  1817.3  4638.9 1816.18
  4688.8 1814.93  4752.3 1811.41  4787.5    1808  4809.1 1806.96  4815.8 1805.84
  4851.6    1803  4858.4 1801.97  4872.6 1801.69  4879.4 1799.62  4886.8  1798.4
  4907.7 1796.49  4950.3 1795.29  4972.6 1793.96  4973.1 1793.46  4984.2 1793.46
  4984.7 1793.96  5014.2 1794.52  5063.6 1798.55  5091.9 1799.49  5289.9    1802
  5431.4 1805.03  5445.5 1804.77  5473.8  1805.6  5494.9 1805.36  5540.6 1806.09
#Mann= 3 ,-1 , 0
  4288.3     .05       0  4972.6     .05       0  4984.7     .05       0
Bank Sta=4972.6,4984.7
XS Rating Curve= 0 ,0
Exp/Cntr=0.3,0.1

Type RM Length L Ch R = 1 ,66437   ,333,333,333
BEGIN DESCRIPTION:
Rainy Creek 66436.99
END DESCRIPTION:
XS GIS Cut Line= 3
      1613313.65      6828009.91      1613954.26      6828231.25
      1614574.07      6828525.54
#Sta/Elev= 30
  4325.8 1809.14    4521 1810.02    4560 1811.43    4578 1808.52  4602.3 1810.79
  4739.9 1809.36  4765.1 1807.68    4791 1808.58  4835.1 1807.85  4930.3 1802.56
  4940.9 1800.93    4962 1795.08  4972.6 1792.03  4978.1 1788.88  5002.6 1787.54
  5003.1 1787.04  5014.9 1787.54    5026  1788.2  5031.5 1790.57  5048.7 1792.09
  5059.8 1796.16  5082.5 1800.91  5099.7 1802.12  5122.4 1801.38    5128 1798.53
  5137.2 1796.55  5145.2 1796.49  5218.9 1799.02  5474.4 1802.39  5689.7 1807.75
#Mann= 3 ,-1 , 0
  4325.8     .05       0  5002.6     .05       0  5014.9     .05       0
Bank Sta=5002.6,5014.9
XS Rating Curve= 0 ,0
Exp/Cntr=0.3,0.1

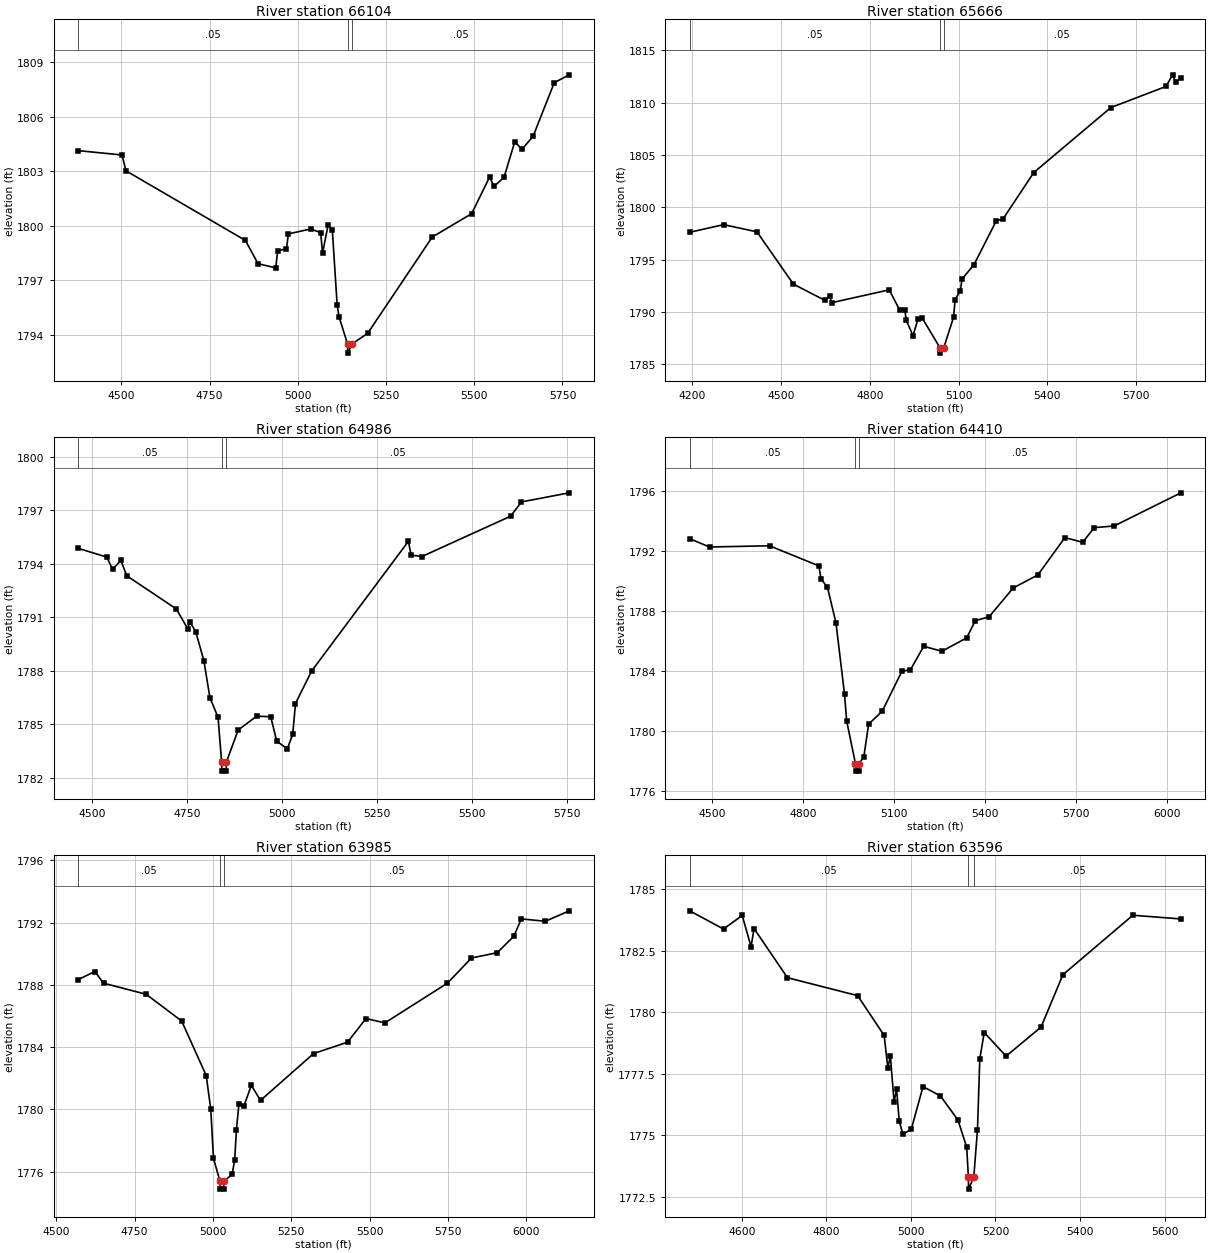
Type RM Length L Ch R = 1 ,66104   ,438,438,438
BEGIN DESCRIPTION:
Rainy Creek 66104.13
END DESCRIPTION:
XS GIS Cut Line= 4
      1613178.23      6828267.72      1613764.16      6828483.86
       1613852.7       6828509.9       1614516.8       6828632.3
#Sta/Elev= 30
  4377.2 1804.13  4501.7 1803.89  4512.8 1803.02  4851.4 1799.19  4887.2 1797.91
  4937.4 1797.68  4942.7 1798.61  4967.8 1798.73  4973.2 1799.55  5036.6 1799.82
  5064.7 1799.62    5070 1798.49    5086 1800.06  5097.7 1799.77  5111.4 1795.65
  5116.7 1794.99    5141 1793.49  5141.5 1792.99  5153.3 1793.49    5198 1794.08
  5381.1 1799.38  5492.6 1800.66  5543.8 1802.69  5555.7 1802.16  5584.4 1802.66
  5614.9 1804.62  5635.3  1804.2  5666.8 1804.92  5726.8 1807.87  5769.3  1808.3
#Mann= 3 ,-1 , 0
  4377.2     .05       0    5141     .03       0  5153.3     .05       0
Bank Sta=5141,5153.3
XS Rating Curve= 0 ,0
Exp/Cntr=0.3,0.1

Type RM Length L Ch R = 1 ,65666   ,680,680,680
BEGIN DESCRIPTION:
Rainy Creek 65665.53
END DESCRIPTION:
XS GIS Cut Line= 3
       1612861.3      6828499.86      1613590.43      6828860.95
      1614360.65       6829207.9
#Sta/Elev= 30
  4192.1 1797.62    4307 1798.35  4419.2 1797.66  4542.5 1792.66    4649 1791.11
  4664.9 1791.53  4671.4 1790.89  4865.8 1792.12  4901.3 1790.18  4918.1 1790.22
  4923.7 1789.19  4946.1 1787.74    4963 1789.33  4977.4 1789.41  5037.5 1786.57
    5038 1786.07  5049.8 1786.57  5082.9 1789.49  5088.4 1791.19  5106.1 1792.05
  5111.5 1793.14  5152.3 1794.54  5227.2 1798.71  5250.4 1798.91  5353.9 1803.33
    5614 1809.54  5800.4 1811.56  5822.4 1812.67  5833.2 1811.94  5850.5 1812.38
#Mann= 3 ,-1 , 0
  4192.1     .05       0  5037.5     .05       0  5049.8     .05       0
Bank Sta=5037.5,5049.8
XS Rating Curve= 0 ,0
Exp/Cntr=0.3,0.1

Type RM Length L Ch R = 1 ,64986   ,576,576,576
BEGIN DESCRIPTION:
Rainy Creek 64985.63
END DESCRIPTION:
XS GIS Cut Line= 3
      1612663.34      6828475.53      1612937.65      6828940.81
      1613455.02      6829485.96
#Sta/Elev= 30
  4463.3 1794.86  4538.6 1794.37  4554.2 1793.68  4575.7 1794.18  4591.3 1793.32
  4721.6 1791.46  4751.3 1790.36  4757.1 1790.75  4772.8 1790.18  4794.2 1788.55
  4809.9 1786.49  4831.3 1785.39  4840.8 1782.87  4841.3 1782.37  4852.7 1782.37
  4853.2 1782.87  4884.1 1784.67  4932.8 1785.45  4969.9 1785.42  4985.6 1784.05
  5013.5 1783.62  5027.7 1784.43    5035 1786.16  5077.4 1787.98  5331.9 1795.25
  5339.1 1794.48  5367.5  1794.4  5600.8 1796.66  5629.2 1797.46    5755 1797.97
#Mann= 3 ,-1 , 0
  4463.3     .05       0  4840.8     .05       0  4853.2     .05       0
Bank Sta=4840.8,4853.2
XS Rating Curve= 0 ,0
Exp/Cntr=0.3,0.1

Type RM Length L Ch R = 1 ,64410   ,425,425,425
BEGIN DESCRIPTION:
Rainy Creek 64409.51
END DESCRIPTION:
XS GIS Cut Line= 3
      1611996.66      6828683.85      1612413.34      6829083.17
      1613331.72      6829578.75
#Sta/Elev= 30
  4425.3 1792.83  4490.8 1792.28  4688.7 1792.36  4851.6 1791.02  4858.5 1790.16
  4879.9 1789.59  4907.9 1787.23  4936.2 1782.47  4943.4 1780.67  4972.3 1777.84
  4972.8 1777.34  4984.4 1777.34  4984.9 1777.84    5000 1778.31  5015.7 1780.47
  5060.4 1781.33    5126 1784.01  5153.6 1784.09  5197.5 1785.66  5257.4 1785.33
  5339.3 1786.22  5367.9 1787.37  5413.4 1787.63  5492.9 1789.55  5574.4 1790.42
  5663.4 1792.91    5722 1792.59  5760.1 1793.57  5825.7 1793.68    6046 1795.89
#Mann= 3 ,-1 , 0
  4425.3     .05       0  4972.3     .05       0  4984.9     .05       0
Bank Sta=4972.3,4984.9
XS Rating Curve= 0 ,0
Exp/Cntr=0.3,0.1

Type RM Length L Ch R = 1 ,63985   ,389,389,389
BEGIN DESCRIPTION:
Rainy Creek 63984.92
END DESCRIPTION:
XS GIS Cut Line= 3
      1611743.23        6829045.      1612080.01      6829315.81
      1613128.27      6829753.17
#Sta/Elev= 30
  4569.5 1788.33  4623.1 1788.85  4650.6  1788.1  4786.6 1787.39  4900.2 1785.67
  4978.6 1782.16    4993 1780.01  5001.7 1776.85  5022.4 1775.37  5022.9 1774.87
  5034.5 1774.87    5035 1775.37  5061.2 1775.82  5069.5 1776.76  5074.9 1778.69
  5082.9 1780.31  5098.7  1780.2  5122.5 1781.54  5151.8 1780.57  5321.3 1783.58
  5429.6 1784.31  5488.5 1785.83  5548.8 1785.55  5748.4  1788.1  5825.3 1789.72
  5907.6 1790.06  5960.6 1791.12  5984.5 1792.23  6061.3 1792.08  6137.5 1792.75
#Mann= 3 ,-1 , 0
  4569.5     .05       0  5022.4     .05       0    5035     .05       0
Bank Sta=5022.4,5035
XS Rating Curve= 0 ,0
Exp/Cntr=0.3,0.1

Type RM Length L Ch R = 1 ,63596   ,350,350,350
BEGIN DESCRIPTION:
Rainy Creek 63596.17
END DESCRIPTION:
XS GIS Cut Line= 3
      1611380.92      6829289.37      1611808.47      6829593.22
      1612424.82      6829755.98
#Sta/Elev= 30
  4476.6 1784.13  4556.6 1783.39  4600.9 1783.94  4621.8 1782.67  4628.8 1783.41
  4707.9 1781.41    4874 1780.68  4936.7 1779.06  4945.3 1777.75  4951.4 1778.22
  4960.1 1776.36  4966.2 1776.87  4972.3 1775.58    4981 1775.04  5000.9 1775.25
  5028.6 1776.98  5069.9  1776.6  5111.3 1775.62    5132 1774.51  5135.9 1773.31
  5136.4 1772.81  5148.8 1773.31  5157.4 1775.22    5163 1778.12  5173.4 1779.18
  5225.1 1778.22  5307.8  1779.4  5359.5 1781.53    5525 1783.95  5638.6  1783.8
#Mann= 3 ,-1 , 0
  4476.6     .05       0  5135.9     .05       0  5148.8     .05       0
Bank Sta=5135.9,5148.8
XS Rating Curve= 0 ,0
Exp/Cntr=0.3,0.1

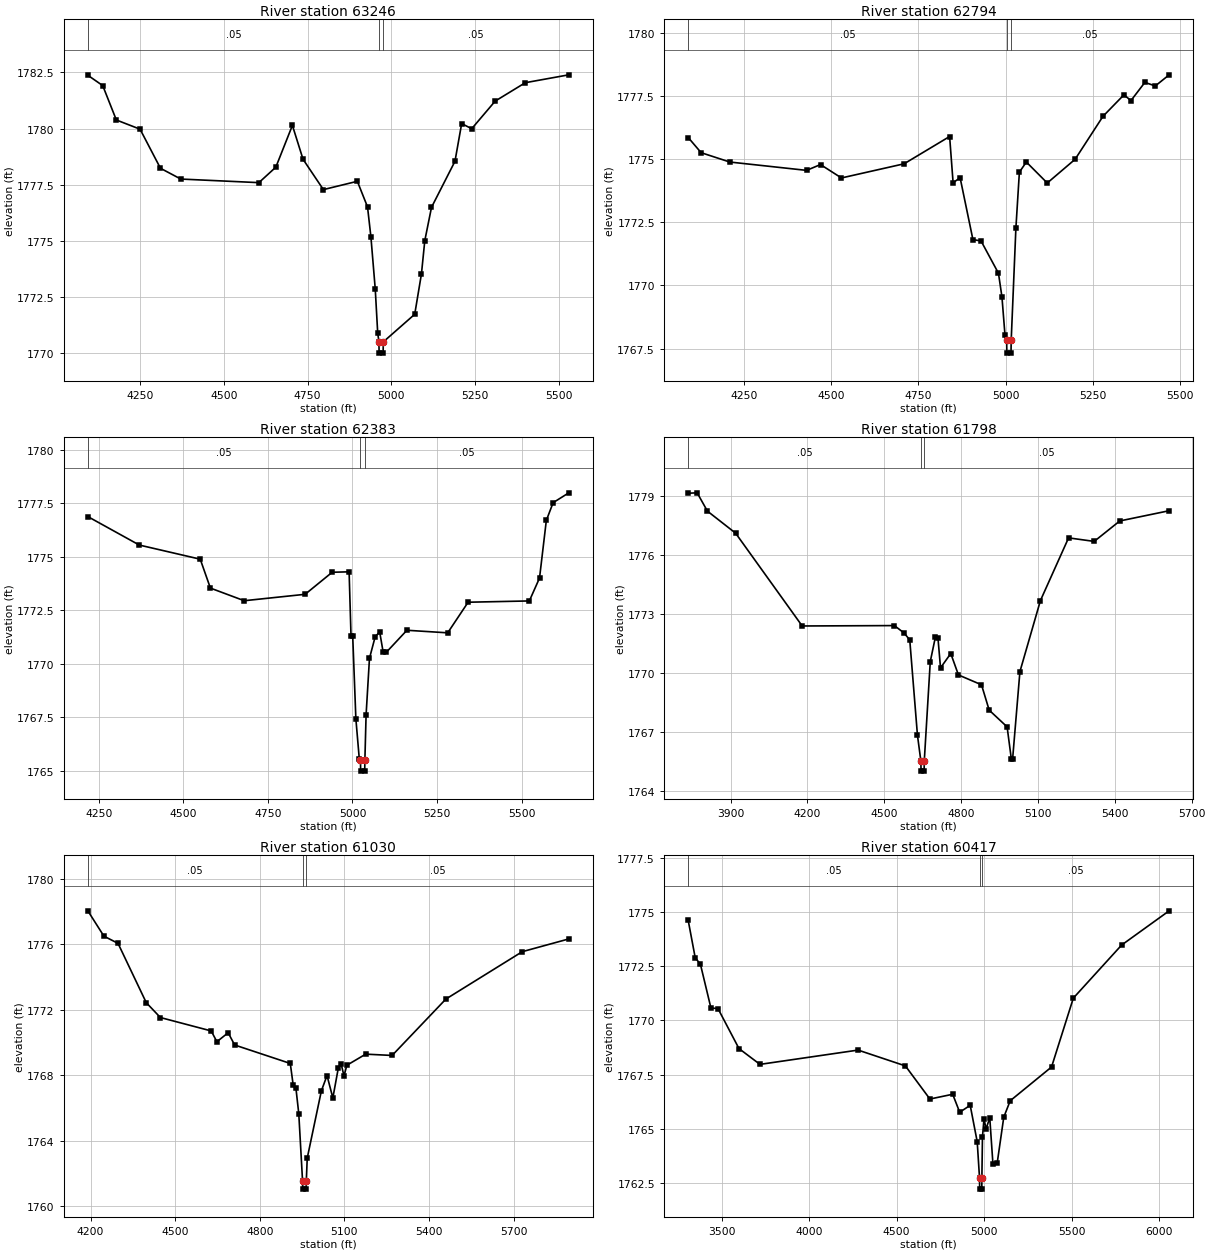
Type RM Length L Ch R = 1 ,63246   ,452,452,452
BEGIN DESCRIPTION:
Rainy Creek 63246.22
END DESCRIPTION:
XS GIS Cut Line= 3
      1610911.12      6829761.22      1611803.05      6829910.96
       1612334.7      6829934.83
#Sta/Elev= 30
  4093.8 1782.37  4138.3 1781.91  4178.9 1780.38  4249.8 1779.97  4310.7 1778.23
  4371.5 1777.75  4604.7 1777.59  4655.4 1778.28  4704.8 1780.14  4736.6 1778.63
  4797.4 1777.28  4898.8 1777.65  4929.2 1776.51  4939.3 1775.18  4952.3 1772.85
  4959.6  1770.9  4963.3  1770.5  4963.8    1770  4975.8    1770  4976.3  1770.5
  5070.2 1771.73  5090.3 1773.53  5100.3 1775.01  5120.3 1776.49  5190.4 1778.54
  5210.4 1780.22  5240.4 1779.99  5310.5 1781.22  5400.6 1782.04  5530.4 1782.39
#Mann= 3 ,-1 , 0
  4093.8     .05       0  4963.3     .05       0  4976.3     .05       0
Bank Sta=4963.3,4976.3
XS Rating Curve= 0 ,0
Exp/Cntr=0.3,0.1

Type RM Length L Ch R = 1 ,62794   ,411,411,411
BEGIN DESCRIPTION:
Rainy Creek 62793.83
END DESCRIPTION:
XS GIS Cut Line= 3
      1610745.77      6830270.94      1611657.21      6830317.82
      1612124.74      6830323.01
#Sta/Elev= 30
  4089.3 1775.85  4126.4 1775.25  4208.7 1774.88    4429 1774.55    4469 1774.78
  4529.1 1774.25  4708.9 1774.81  4839.5 1775.89  4849.5 1774.06  4869.6 1774.26
  4906.4 1771.81  4929.6 1771.76  4979.7 1770.48  4989.7 1769.54  4998.3 1768.05
  5003.2 1767.82  5003.7 1767.32  5015.7 1767.32  5016.2 1767.82  5029.7 1772.27
  5039.7 1774.48  5059.7 1774.88  5119.7 1774.05  5199.7 1774.99  5279.7 1776.69
  5339.8 1777.54  5359.8 1777.31  5399.8 1778.03  5429.8 1777.89  5469.5 1778.33
#Mann= 3 ,-1 , 0
  4089.3     .05       0  5003.2     .03       0  5016.2     .05       0
Bank Sta=5003.2,5016.2
XS Rating Curve= 0 ,0
Exp/Cntr=0.3,0.1

Type RM Length L Ch R = 1 ,62383   ,585,585,585
BEGIN DESCRIPTION:
Rainy Creek 62383.43
END DESCRIPTION:
XS GIS Cut Line= 3
      1610672.84      6830630.32      1611451.49      6830630.32
      1612091.05      6830565.32
#Sta/Elev= 30
  4217.9 1776.87  4370.1 1775.54  4550.1 1774.88  4580.1 1773.53  4680.1 1772.94
  4860.1 1773.24  4940.1 1774.27  4990.1 1774.29  4995.8 1771.27  5000.8 1771.27
  5010.1 1767.42  5020.2 1765.55  5023.7 1765.48  5024.2 1764.98  5036.2 1764.98
  5036.7 1765.48  5040.3 1767.61  5050.3 1770.25  5067.2 1771.26  5080.5 1771.48
  5090.5 1770.56  5100.6 1770.54  5160.9 1771.56  5281.5 1771.44  5341.8 1772.87
  5522.8 1772.93  5552.9    1774    5573 1776.69  5593.1 1777.52  5639.4 1777.98
#Mann= 3 ,-1 , 0
  4217.9     .05       0  5023.7     .05       0  5036.7     .05       0
Bank Sta=5023.7,5036.7
XS Rating Curve= 0 ,0
Exp/Cntr=0.3,0.1

Type RM Length L Ch R = 1 ,61798   ,768,768,768
BEGIN DESCRIPTION:
Rainy Creek 61798.47
END DESCRIPTION:
XS GIS Cut Line= 3
      1610540.01       6830867.3      1611803.05      6830890.74
      1612417.67      6830885.53
#Sta/Elev= 30
  3734.2 1779.12  3769.2 1779.14  3809.2 1778.21  3919.2 1777.09  4179.3 1772.37
  4539.3 1772.39  4577.4 1772.01  4599.3 1771.66  4629.3 1766.82  4642.8 1765.49
  4643.3 1764.99  4655.4 1764.99  4655.9 1765.49  4679.4 1770.56  4699.4 1771.81
  4709.4 1771.76  4719.4 1770.24  4759.4 1770.97  4789.4 1769.88  4879.4 1769.38
  4909.4 1768.09  4979.4 1767.24  4995.9 1765.61  5000.9 1765.61  5029.4 1770.05
  5109.4 1773.66  5219.4 1776.85  5319.4 1776.67  5419.4 1777.71  5612.1 1778.23
#Mann= 3 ,-1 , 0
  3734.2     .05       0  4642.8     .05       0  4655.9     .05       0
Bank Sta=4642.8,4655.9
XS Rating Curve= 0 ,0
Exp/Cntr=0.3,0.1

Type RM Length L Ch R = 1 ,61030   ,613,613,613
BEGIN DESCRIPTION:
Rainy Creek 61030.34
END DESCRIPTION:
XS GIS Cut Line= 3
      1610668.12      6831214.85      1611466.68      6831258.25
      1612369.43      6831184.47
#Sta/Elev= 30
  4190.4 1778.06  4247.4 1776.51  4297.4 1776.07  4397.6 1772.44  4447.7 1771.53
  4627.9 1770.71    4648 1770.05    4688  1770.6    4711 1769.85  4908.3 1768.72
  4918.4 1767.42  4928.4 1767.19  4938.4 1765.65  4951.8 1761.53  4952.3 1761.03
  4964.6 1761.03  4965.1 1761.53  4968.4 1762.93  5018.6 1767.05  5038.6 1767.98
  5059.2 1766.61  5078.8 1768.46  5088.8 1768.67  5098.8 1767.96  5108.9 1768.61
  5175.7 1769.29  5269.4 1769.21    5460 1772.66  5730.9 1775.56  5895.9 1776.34
#Mann= 3 ,-1 , 0
  4190.4     .05       0  4951.8     .05       0  4965.1     .05       0
Bank Sta=4951.8,4965.1
XS Rating Curve= 0 ,0
Exp/Cntr=0.3,0.1

Type RM Length L Ch R = 1 ,60417   ,445,445,445
BEGIN DESCRIPTION:
Rainy Creek 60417.4
END DESCRIPTION:
XS GIS Cut Line= 3
      1609865.15      6831761.73      1611557.83      6831809.47
      1612550.88      6831458.21
#Sta/Elev= 30
  3309.4 1774.62  3349.3  1772.9  3379.3 1772.59  3439.3 1770.57  3479.3 1770.55
  3599.4  1768.7  3719.4 1767.97  4279.6 1768.63  4549.7  1767.9  4689.8 1766.37
  4819.9 1766.59  4859.9 1765.76  4919.9 1766.08  4959.9  1764.4  4973.3 1762.71
  4973.8 1762.21  4986.1 1762.21  4986.6 1762.71  4989.9 1764.62  4998.8 1765.46
  5010.4 1764.99  5031.6  1765.5  5049.8 1763.37    5074 1763.41  5111.6 1765.53
  5148.3 1766.29  5384.5 1767.85  5508.9 1771.03  5784.7 1773.48  6056.1 1775.06
#Mann= 3 ,-1 , 0
  3309.4     .05       0  4973.3     .03       0  4986.6     .05       0
Bank Sta=4973.3,4986.6
XS Rating Curve= 0 ,0
Exp/Cntr=0.3,0.1