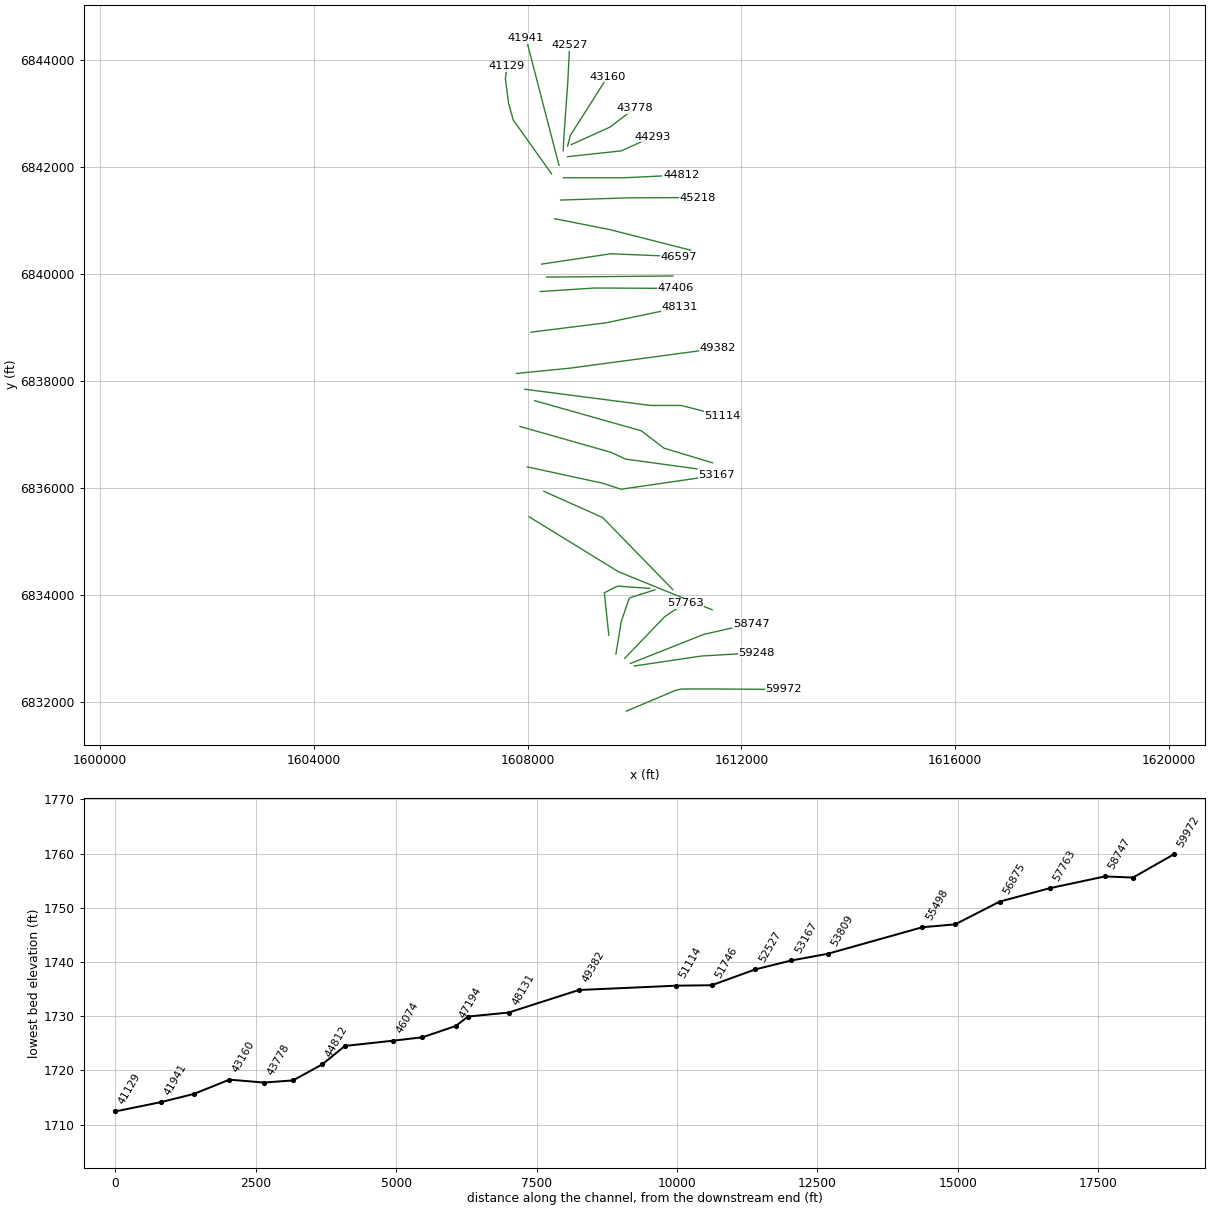
HEC-RAS study Rainy Creek.prj: Rainy Creek Base Level Engineering

--- Rainy Creek.g01 (geometry) --- (continued)

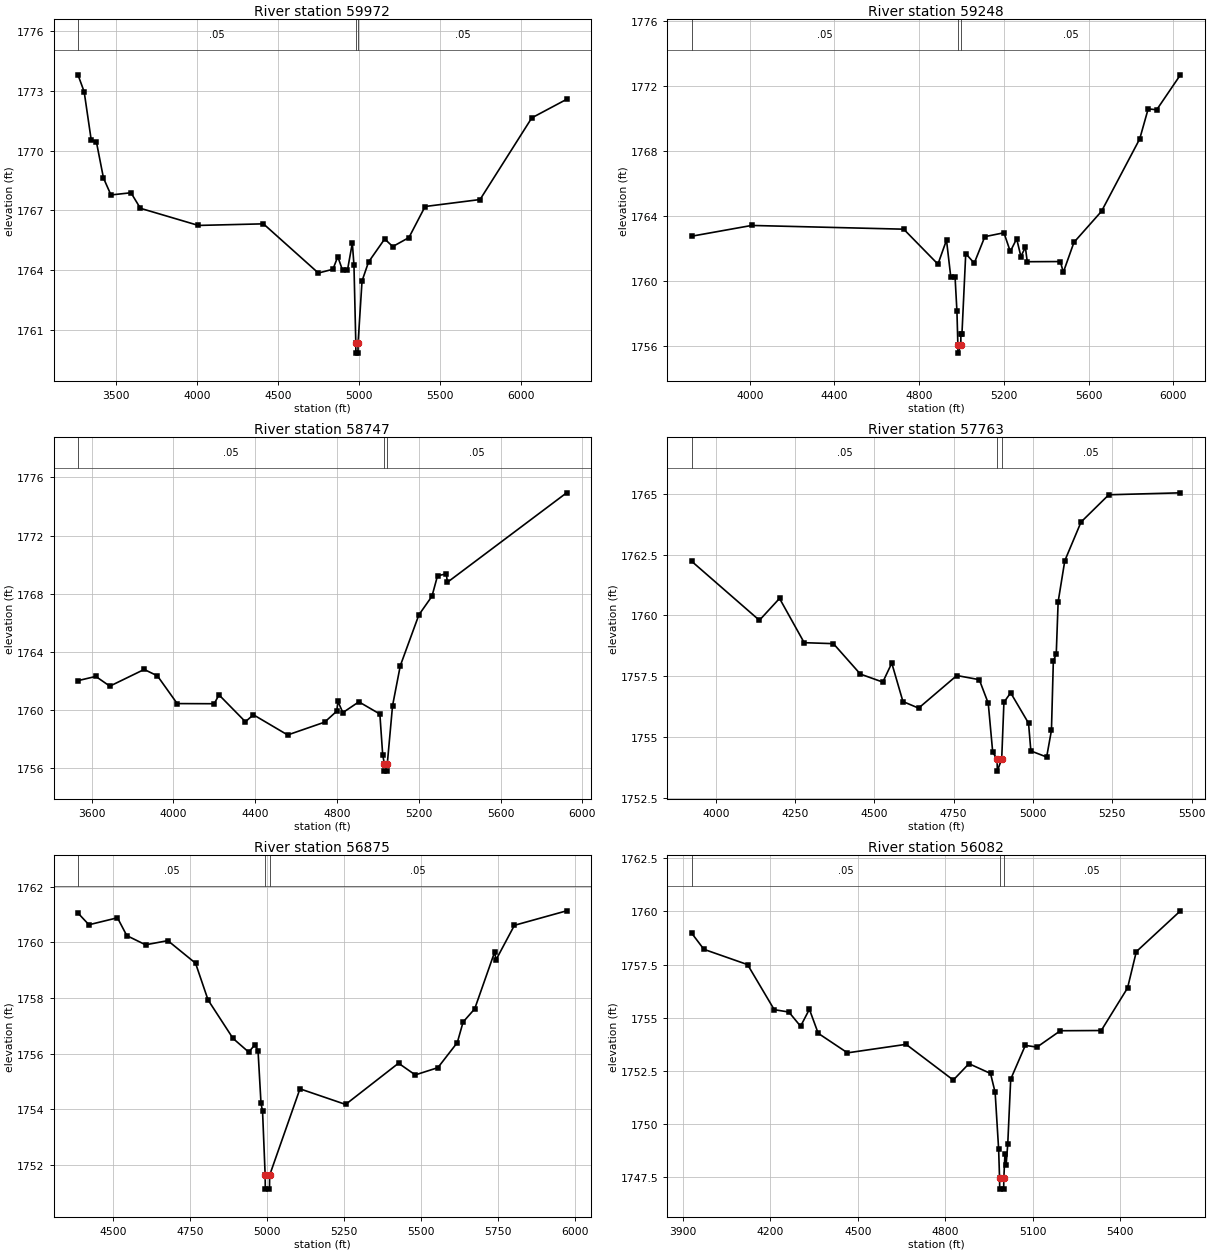
Type RM Length L Ch R = 1 ,59972   ,724,724,724
BEGIN DESCRIPTION:
Rainy Creek 59972.28
END DESCRIPTION:
XS GIS Cut Line= 5
      1609849.72       6831824.7      1610774.22      6832215.34
      1610883.59      6832239.16      1611497.07      6832239.16
      1612790.28      6832230.48
#Sta/Elev= 30
  3262.5 1773.81  3300.8 1772.96  3344.2 1770.55  3376.8 1770.43  3420.2 1768.63
  3466.4 1767.78  3590.3 1767.89  3648.6 1767.11  4007.5 1766.25  4409.5 1766.33
  4749.5 1763.86  4839.5 1764.05  4869.5 1764.68  4899.5 1763.99  4929.5 1764.01
  4959.5 1765.37  4969.5 1764.26    4981 1760.34  4981.5 1759.84  4994.5 1759.84
    4995 1760.34  5019.5 1763.46  5059.5 1764.41  5159.5 1765.57  5209.5 1765.19
  5309.5 1765.64  5409.5  1767.2  5749.5 1767.55  6069.5 1771.65  6284.8 1772.58
#Mann= 3 ,-1 , 0
  3262.5     .05       0    4981     .05       0    4995     .05       0
Bank Sta=4981,4995
XS Rating Curve= 0 ,0
Exp/Cntr=0.3,0.1

Type RM Length L Ch R = 1 ,59248   ,501,501,501
BEGIN DESCRIPTION:
Rainy Creek 59248.23
END DESCRIPTION:
XS GIS Cut Line= 3
      1609995.36      6832668.85      1611254.01      6832855.48
      1612287.01      6832916.24
#Sta/Elev= 30
  3726.7 1762.76  4009.4 1763.42  4727.2 1763.19  4888.9 1761.04  4929.3 1762.52
  4949.6 1760.24  4969.8 1760.22  4978.5 1758.16    4983 1756.07  4983.5 1755.57
    4997 1756.07  4997.1 1756.72  5002.1 1756.72  5020.1 1761.69  5060.2  1761.1
  5110.3 1762.73  5200.4 1762.97  5230.5 1761.82  5260.6  1762.6  5280.6 1761.51
  5301.6 1762.08  5310.6 1761.19  5466.9  1761.2  5480.9 1760.54    5531 1762.38
  5661.2 1764.29  5841.6 1768.74  5881.6 1770.59  5921.7 1770.53  6033.9 1772.68
#Mann= 3 ,-1 , 0
  3726.7     .05       0    4983     .05       0    4997     .05       0
Bank Sta=4983,4997
XS Rating Curve= 0 ,0
Exp/Cntr=0.3,0.1

Type RM Length L Ch R = 1 ,58747   ,984,984,984
BEGIN DESCRIPTION:
Rainy Creek 58746.75
END DESCRIPTION:
XS GIS Cut Line= 3
      1609923.91      6832716.04      1611293.07      6833259.12
      1612186.96      6833463.07
#Sta/Elev= 30
  3533.5 1762.01  3620.7  1762.3  3689.3 1761.63  3857.4 1762.78    3922 1762.34
  4018.8 1760.43  4199.8 1760.42  4223.2 1761.03  4352.3 1759.18  4391.5 1759.66
    4559 1758.27  4739.6 1759.15  4799.4 1759.91  4804.7 1760.58  4829.1 1759.81
  4907.4 1760.55    5010 1759.71  5023.8 1756.91    5032 1756.28  5032.5 1755.78
  5045.8 1755.78  5046.3 1756.28    5072 1760.28  5109.8 1763.03  5200.9 1766.54
  5264.8 1767.82    5292 1769.23    5335 1769.36  5340.2 1768.78  5923.3 1774.94
#Mann= 3 ,-1 , 0
  3533.5     .05       0    5032     .05       0  5046.3     .05       0
Bank Sta=5032,5046.3
XS Rating Curve= 0 ,0
Exp/Cntr=0.3,0.1

Type RM Length L Ch R = 1 ,57763   ,888,888,888
BEGIN DESCRIPTION:
Rainy Creek 57763.26
END DESCRIPTION:
XS GIS Cut Line= 3
       1609818.6      6832813.41       1610569.5      6833594.69
      1610950.72      6833845.95
#Sta/Elev= 30
  3924.6 1762.22  4137.6  1759.8  4201.1  1760.7  4278.8 1758.88  4370.9 1758.84
  4455.8 1757.59  4526.6 1757.26  4554.9 1758.04  4590.1 1756.46  4639.5 1756.19
  4759.9 1757.53  4830.7 1757.36    4859 1756.39  4873.1 1754.37    4887  1754.1
  4887.5  1753.6  4901.4  1754.1  4908.4 1756.43  4929.6 1756.82    4986 1755.57
  4993.3 1754.43  5043.1 1754.18  5058.2 1755.28  5064.2 1758.14  5073.3  1758.4
  5079.3 1760.56  5100.3 1762.25  5151.5 1763.84  5238.9 1764.96  5464.8 1765.04
#Mann= 3 ,-1 , 0
  3924.6     .05       0    4887     .05       0  4901.4     .05       0
Bank Sta=4887,4901.4
XS Rating Curve= 0 ,0
Exp/Cntr=0.3,0.1

Type RM Length L Ch R = 1 ,56875   ,793,793,793
BEGIN DESCRIPTION:
Rainy Creek 56875.33
END DESCRIPTION:
XS GIS Cut Line= 4
      1609653.69      6832891.53      1609753.52      6833503.54
      1609905.43      6833941.91       1610382.9      6834093.83
#Sta/Elev= 30
  4386.9 1761.05  4422.4 1760.63    4515 1760.88  4545.3 1760.24  4606.2 1759.91
  4678.4 1760.06  4768.3 1759.25  4808.9 1757.93  4889.9 1756.55  4940.6 1756.06
  4960.9 1756.32    4971 1756.11  4980.6 1754.23  4985.7 1753.93  4994.1 1751.64
  4994.6 1751.14  5008.2 1751.14  5008.7 1751.64    5107 1754.74  5255.1 1754.18
  5426.8 1755.66    5481 1755.24  5554.4  1755.5  5617.4  1756.4  5636.3 1757.14
  5673.8 1757.61  5738.2 1759.64  5743.5 1759.38  5802.7 1760.61    5972 1761.13
#Mann= 3 ,-1 , 0
  4386.9     .05       0  4994.1     .05       0  5008.7     .05       0
Bank Sta=4994.1,5008.7
XS Rating Curve= 0 ,0
Exp/Cntr=0.3,0.1

Type RM Length L Ch R = 1 ,56082   ,584,584,584
BEGIN DESCRIPTION:
Rainy Creek 56082.45
END DESCRIPTION:
XS GIS Cut Line= 4
      1609520.45       6833246.8      1609437.12      6834038.48
      1609681.91      6834163.48      1610286.06      6834121.81
#Sta/Elev= 30
  3930.5 1758.97  3971.9 1758.22  4121.8  1757.5  4213.3 1755.38  4263.5 1755.27
  4303.7  1754.6  4333.9  1755.4  4364.1 1754.27  4464.6 1753.35  4665.7 1753.75
  4827.6 1752.07  4881.4 1752.84  4955.4 1752.38  4971.2 1751.49  4983.2 1748.82
  4986.4 1747.44  4986.9 1746.94  5000.5 1746.94    5001 1747.44  5004.9  1748.6
    5009 1748.09  5014.5 1749.06  5024.6 1752.11  5074.7  1753.7  5114.8 1753.62
    5195 1754.39  5335.3  1754.4  5425.5  1756.4  5455.6 1758.11    5607 1760.03
#Mann= 3 ,-1 , 0
  3930.5     .05       0  4986.4     .05       0    5001     .05       0
Bank Sta=4986.4,5001
XS Rating Curve= 0 ,0
Exp/Cntr=0.3,0.1

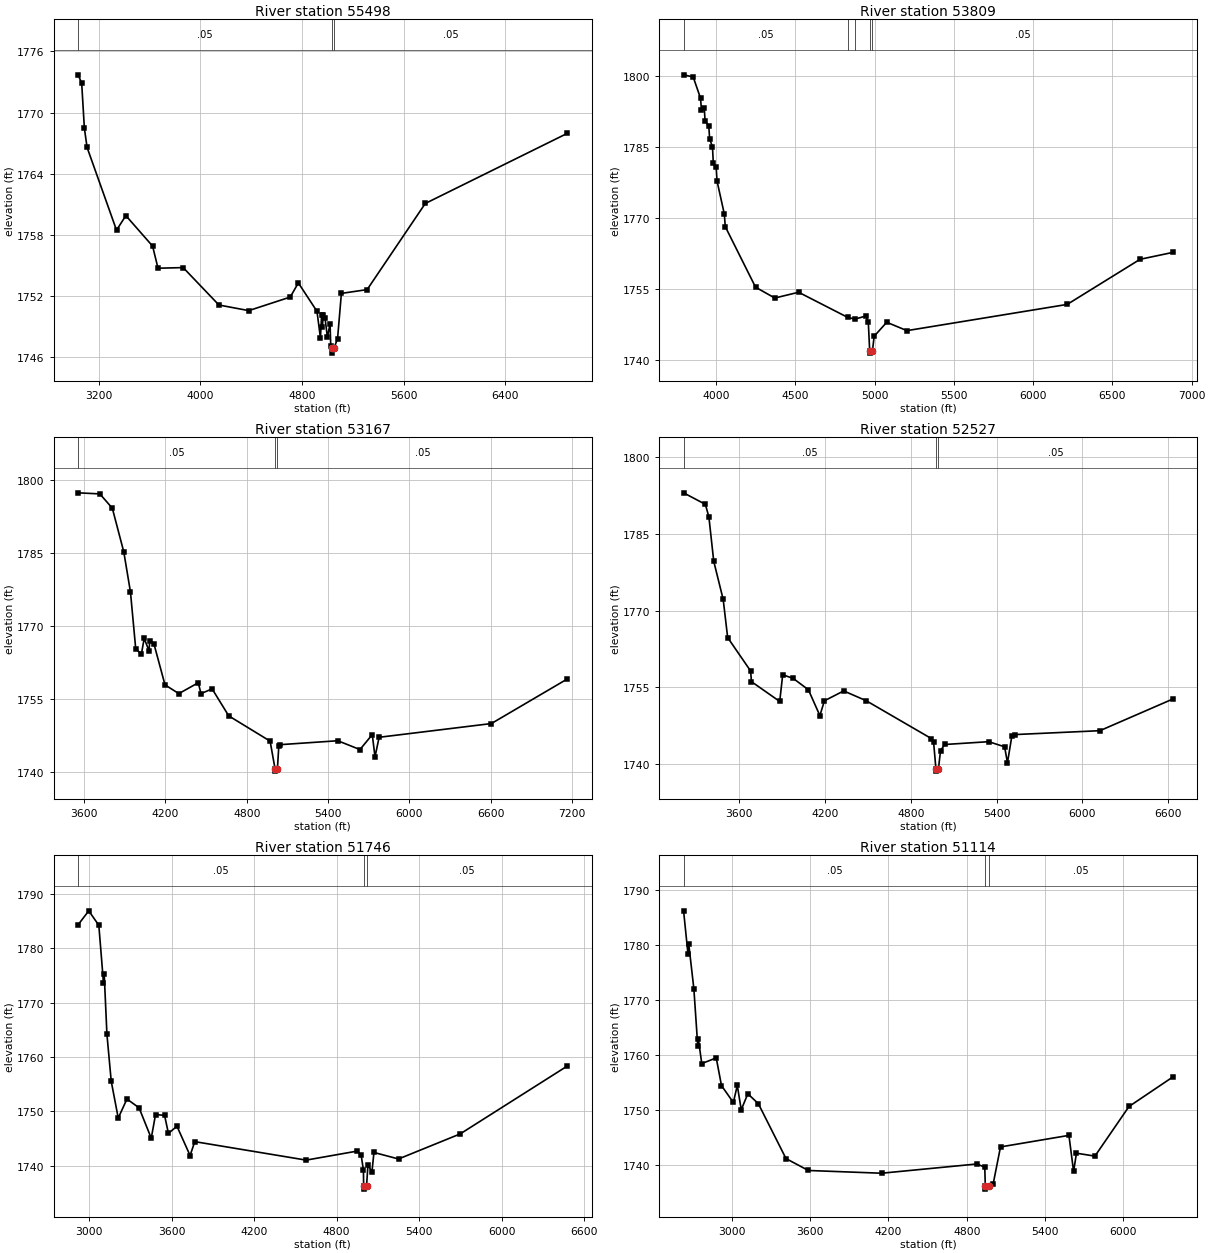
Type RM Length L Ch R = 1 ,55498   ,1689,1689,1689
BEGIN DESCRIPTION:
Rainy Creek 55112.27
END DESCRIPTION:
XS GIS Cut Line= 3
      1608029.36      6835460.54       1609702.8      6834431.92
      1611453.87      6833720.93
#Sta/Elev= 30
  3035.7 1773.71  3064.6 1772.92  3085.8 1768.48  3107.1 1766.59  3339.1 1758.47
  3412.5  1759.9  3623.2 1756.91  3665.7 1754.74    3864  1754.8  4145.7 1751.13
  4380.5 1750.58  4707.4 1751.91  4771.2  1753.3    4918 1750.51  4945.2  1747.9
  4954.7 1750.17  4960.6 1748.97  4967.4 1750.19  4981.9 1749.81    5000 1747.97
  5021.1  1749.3  5026.5 1747.07  5037.9 1746.91  5038.4 1746.41  5052.6 1746.91
  5080.1 1747.84  5110.3 1752.27    5313 1752.64    5771 1761.09  6889.9 1767.97
#Mann= 3 ,-1 , 0
  3035.7     .05       0  5037.9     .05       0  5052.6     .05       0
Bank Sta=5037.9,5052.6
XS Rating Curve= 0 ,0
Exp/Cntr=0.3,0.1

Type RM Length L Ch R = 1 ,53809   ,642,642,642
BEGIN DESCRIPTION:
Rainy Creek 54125.452
END DESCRIPTION:
XS GIS Cut Line= 3
      1608305.04      6835937.98      1609405.33      6835446.42
      1610717.78      6834097.99
#Sta/Elev= 30
  3794.9 1800.29  3855.6 1799.83    3902 1795.34  3907.5 1792.83  3925.3 1793.32
  3930.7 1790.48  3953.9 1789.52  3959.4  1786.7  3977.1 1785.13  3982.6 1781.59
  4000.4 1780.84  4005.8 1777.88  4052.3 1770.83  4057.7 1768.24  4248.9 1755.43
  4370.4 1753.14  4520.6 1754.36  4830.3 1749.05  4876.5 1748.69  4944.9 1749.34
  4960.3 1747.98  4968.9    1742  4969.4  1741.5  4986.6    1742  4997.1 1745.06
  5076.5 1748.02  5203.8 1746.25  6214.9 1751.79  6674.6 1761.32  6881.7 1762.78
#Mann= 5 ,-1 , 0
  3794.9     .05       0  4830.3     .12       0  4876.5     .05       0
  4968.9     .05       0  4986.6     .05       0
Bank Sta=4968.9,4986.6
XS Rating Curve= 0 ,0
Exp/Cntr=0.3,0.1

Type RM Length L Ch R = 1 ,53167   ,640,640,640
BEGIN DESCRIPTION:
Rainy Creek 53167.01
END DESCRIPTION:
XS GIS Cut Line= 4
      1607997.52      6836394.15      1609407.28      6836088.59
      1609747.56      6835975.74      1611540.04      6836236.15
#Sta/Elev= 30
  3554.2 1797.44  3715.3 1797.22  3807.4 1794.29  3892.2  1785.3  3941.4 1777.08
  3980.4 1765.36  4022.3 1764.36  4042.8 1767.54  4078.8 1764.98  4083.9 1767.09
  4114.4 1766.46  4196.3    1758  4298.6  1756.2  4441.8 1758.43  4462.3  1756.2
  4544.1 1757.18  4666.9 1751.63  4972.3 1746.44  5008.6 1740.78  5009.1 1740.28
  5026.4 1740.78  5036.4 1745.41    5044 1745.71    5472 1746.52  5635.6 1744.71
  5726.5 1747.78  5746.7 1743.21    5777 1747.23  6605.6 1750.05  7166.5 1759.21
#Mann= 3 ,-1 , 0
  3554.2     .05       0  5008.6     .05       0  5026.4     .05       0
Bank Sta=5008.6,5026.4
XS Rating Curve= 0 ,0
Exp/Cntr=0.3,0.1

Type RM Length L Ch R = 1 ,52527   ,781,781,781
BEGIN DESCRIPTION:
Rainy Creek 52526.88
END DESCRIPTION:
XS GIS Cut Line= 4
      1607858.65      6837151.09        1609567.      6836664.98
       1609833.3      6836539.98       1611170.6      6836357.76
#Sta/Elev= 30
  3212.6 1793.08  3364.8 1790.83  3389.5 1788.37  3423.4 1779.69  3489.5 1772.22
  3520.7 1764.77  3681.2 1758.23  3687.1 1756.14  3884.6 1752.27  3905.4 1757.49
  3978.2 1756.79  4084.9 1754.56  4165.3  1749.5  4196.9  1752.4  4331.7 1754.33
  4488.6 1752.42  4945.1    1745  4960.1 1744.29  4976.2 1739.14  4976.7 1738.64
  4994.1 1739.14  5008.7 1742.67  5038.4 1743.85  5345.2  1744.4  5456.2  1743.4
  5476.4 1740.29  5506.7 1745.46  5526.9 1745.79  6122.3 1746.55  6632.6 1752.75
#Mann= 3 ,-1 , 0
  3212.6     .05       0  4976.2     .05       0  4994.1     .05       0
Bank Sta=4976.2,4994.1
XS Rating Curve= 0 ,0
Exp/Cntr=0.3,0.1

Type RM Length L Ch R = 1 ,51746   ,632,632,632
BEGIN DESCRIPTION:
Rainy Creek 51745.57
END DESCRIPTION:
XS GIS Cut Line= 4
      1608132.68      6837633.65      1610129.24       6837069.4
      1610554.59      6836743.88      1611460.84      6836470.71
#Sta/Elev= 30
  2919.9 1784.34    2998 1786.93  3071.2 1784.27  3105.1 1773.68  3110.3 1775.29
  3130.1 1764.21  3161.3 1755.58  3212.3 1748.79  3275.6 1752.29  3363.7 1750.68
  3452.3 1745.08  3483.5 1749.44  3549.2 1749.28    3577 1745.98  3639.3 1747.28
  3734.6 1741.89  3768.6 1744.45  4578.4 1741.05  4949.3 1742.71    4978    1742
  4994.7 1739.18  4996.1 1736.21  4996.6 1735.71  5017.2 1736.21  5027.5 1740.17
  5056.6 1738.88  5071.1 1742.46  5249.7 1741.26  5697.8 1745.87  6476.8 1758.37
#Mann= 3 ,-1 , 0
  2919.9     .05       0  4996.1     .05       0  5017.2     .05       0
Bank Sta=4996.1,5017.2
XS Rating Curve= 0 ,0
Exp/Cntr=0.3,0.1

Type RM Length L Ch R = 1 ,51114   ,1732,1732,1732
BEGIN DESCRIPTION:
Rainy Creek 51114.02
END DESCRIPTION:
XS GIS Cut Line= 4
      1607946.85      6837847.47      1610299.24      6837543.65
      1610875.62      6837543.66       1611650.8      6837345.96
#Sta/Elev= 30
  2630.4 1786.21  2664.5 1778.28  2669.6 1780.25  2709.2 1772.05  2738.9  1761.7
  2743.9 1762.88  2769.7 1758.45  2880.6 1759.48  2920.9 1754.44  3011.7 1751.38
  3041.9 1754.47  3072.2 1750.06  3122.6 1752.96  3203.3 1751.15    3415 1741.18
  3586.4 1739.02  4147.3 1738.52  4877.1  1740.2  4937.6 1739.62  4941.7 1736.13
  4942.2 1735.63  4973.8 1736.13  5002.3 1736.62  5058.1  1743.3  5582.3  1745.4
    5618 1738.84    5640 1742.16  5781.5 1741.63  6042.5 1750.65  6378.7 1756.02
#Mann= 3 ,-1 , 0
  2630.4     .05       0  4941.7     .05       0  4973.8     .05       0
Bank Sta=4941.7,4973.8
XS Rating Curve= 0 ,0
Exp/Cntr=0.3,0.1

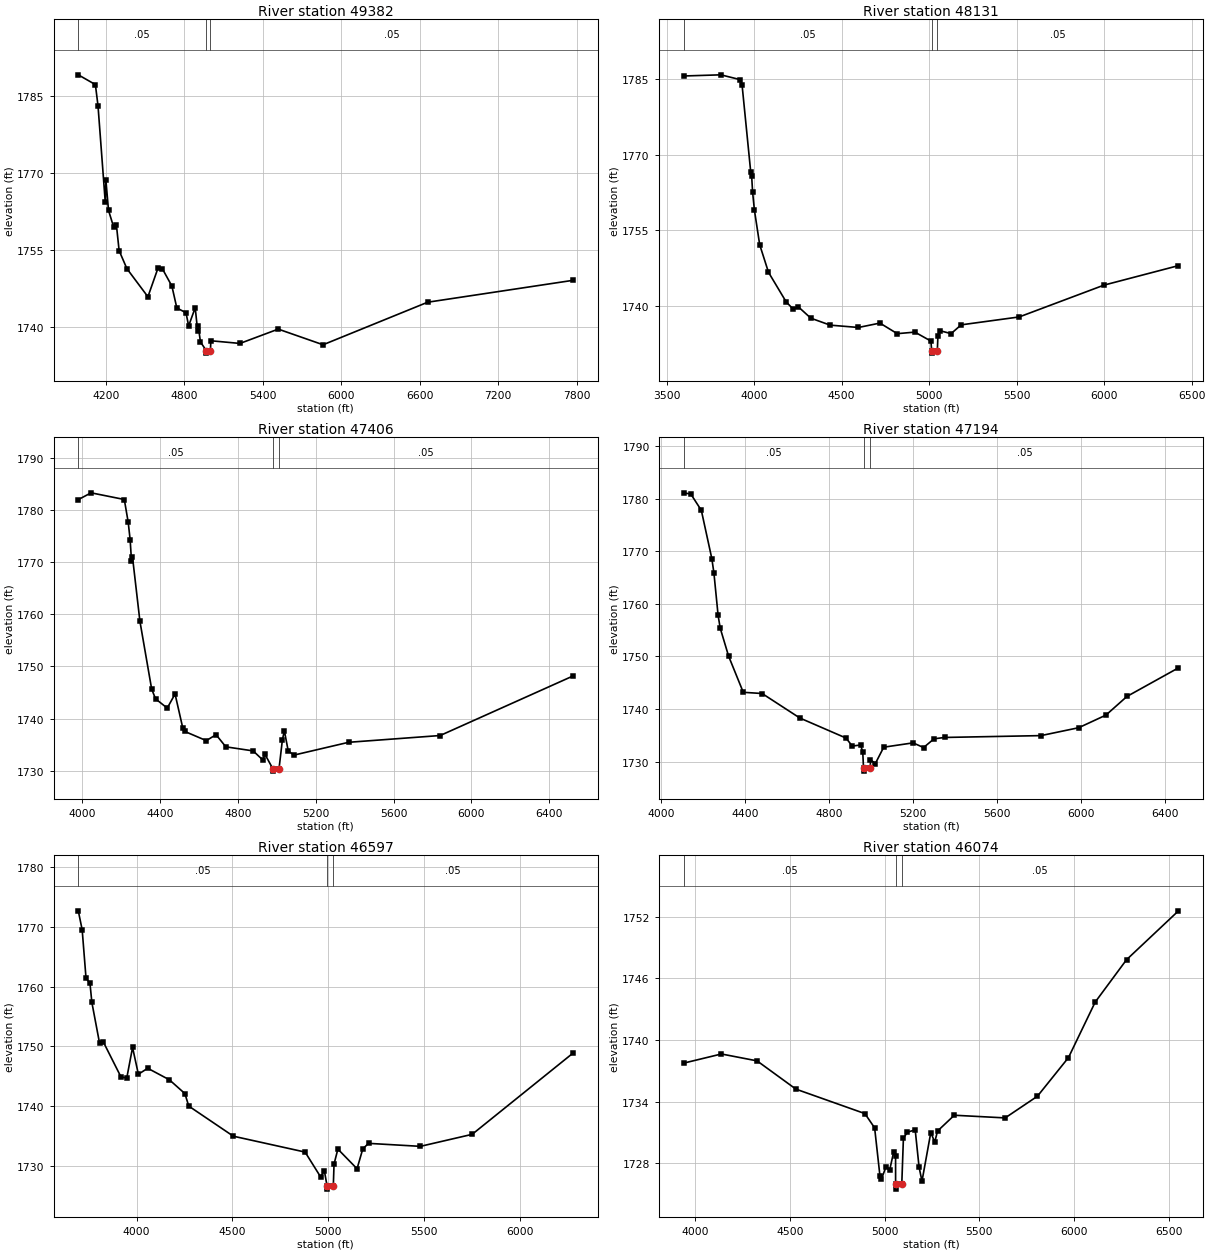
Type RM Length L Ch R = 1 ,49382   ,1251,1251,1251
BEGIN DESCRIPTION:
Rainy Creek 49382.17
END DESCRIPTION:
XS GIS Cut Line= 3
      1607794.88      6838142.61      1608801.84      6838242.44
      1611550.91      6838611.24
#Sta/Elev= 30
  3988.5 1789.06  4119.3 1787.16  4139.4 1783.03  4194.9 1764.23  4199.9 1768.49
  4219.7 1762.65  4259.9 1759.34    4280 1759.84  4300.9  1754.8  4360.4 1751.29
  4521.2 1745.81  4598.6 1751.42  4631.8 1751.27  4704.6  1747.9  4742.3 1743.64
  4812.6 1742.69  4832.7 1740.14    4883 1743.68  4901.4 1739.23  4906.4 1740.04
  4923.2 1737.01  4967.3 1735.33  4967.9 1734.83  4999.6 1735.33  5002.5 1737.24
  5225.4 1736.72  5518.2 1739.51  5861.2 1736.46  6661.3 1744.75  7774.1 1749.02
#Mann= 3 ,-1 , 0
  3988.5     .05       0  4967.3     .05       0  4999.6     .05       0
Bank Sta=4967.3,4999.6
XS Rating Curve= 0 ,0
Exp/Cntr=0.3,0.1

Type RM Length L Ch R = 1 ,48131   ,725,725,725
BEGIN DESCRIPTION:
Rainy Creek 48131.19
END DESCRIPTION:
XS GIS Cut Line= 3
      1608063.99      6838915.18      1609461.56      6839088.79
      1610850.24      6839379.54
#Sta/Elev= 30
  3597.8 1785.65  3810.4 1785.88  3921.3 1784.92  3931.4 1783.91  3981.2 1766.53
  3986.2 1765.82  3991.8 1762.57  4001.9 1759.07  4032.1 1752.19  4082.5  1746.7
  4183.3 1740.85  4223.6 1739.39  4253.8 1739.83  4324.4  1737.6  4435.2 1736.22
  4596.4 1735.76  4719.1 1736.63  4818.1 1734.53  4918.9 1734.84  5010.4 1733.06
  5014.7 1731.17  5015.3 1730.67  5047.1 1731.17  5050.5 1734.11  5060.7 1735.13
  5125.7 1734.54  5183.3 1736.28    5515 1737.85  5999.1 1744.16  6424.9 1748.03
#Mann= 3 ,-1 , 0
  3597.8     .05       0  5014.7     .05       0  5047.1     .05       0
Bank Sta=5014.7,5047.1
XS Rating Curve= 0 ,0
Exp/Cntr=0.3,0.1

Type RM Length L Ch R = 1 ,47406   ,212,212,212
BEGIN DESCRIPTION:
Rainy Creek 47405.64
END DESCRIPTION:
XS GIS Cut Line= 3
      1608239.22      6839675.16      1609253.14      6839741.13
      1610777.46      6839734.19
#Sta/Elev= 30
  3981.6 1782.01  4047.5 1783.31  4217.9 1782.03  4237.9 1777.66  4247.9  1774.3
  4254.7 1770.32  4259.7 1771.07    4298 1758.68  4358.2 1745.69  4378.2  1743.8
  4438.3 1742.02  4478.4 1744.73  4518.5 1738.13  4528.5 1737.54  4638.8 1735.78
  4688.9 1736.92    4739 1734.59  4879.3 1733.81  4929.4 1732.05  4939.4 1733.19
  4979.8 1730.43  4980.4 1729.93  5012.3 1730.43  5029.5 1735.94  5039.5 1737.68
  5059.5 1733.78  5089.5 1733.01  5369.5 1735.46  5839.5 1736.76    6522 1748.19
#Mann= 3 ,-1 , 0
  3981.6     .05       0  4979.8     .03       0  5012.3     .05       0
Bank Sta=4979.8,5012.3
XS Rating Curve= 0 ,0
Exp/Cntr=0.3,0.1

Type RM Length L Ch R = 1 ,47194   ,597,597,597
BEGIN DESCRIPTION:
Rainy Creek 47193.8
END DESCRIPTION:
XS GIS Cut Line= 3
      1608360.74        6839946.      1609253.14      6839952.94
      1610720.94      6839966.82
#Sta/Elev= 30
    4106  1781.1  4140.3 1780.86  4190.3 1777.77  4240.3 1768.61  4250.3 1765.88
  4270.3 1757.81  4280.3 1755.39  4320.3 1750.07  4390.3 1743.19  4480.3 1742.96
  4660.3  1738.3  4880.3  1734.5  4910.3 1732.97  4950.3 1733.18  4960.3 1731.82
    4964 1728.71  4964.6 1728.21  4996.5 1728.71  4996.9 1730.39  5020.3 1729.65
  5060.3 1732.76  5200.3 1733.58  5250.3 1732.69  5300.3 1734.35  5350.3 1734.61
  5810.3 1734.96  5990.3 1736.46  6120.3 1738.86  6220.3  1742.4  6466.3 1747.84
#Mann= 3 ,-1 , 0
    4106     .05       0    4964     .03       0  4996.5     .05       0
Bank Sta=4964,4996.5
XS Rating Curve= 0 ,0
Exp/Cntr=0.3,0.1

Type RM Length L Ch R = 1 ,46597   ,523,523,523
BEGIN DESCRIPTION:
Rainy Creek 46597.3
END DESCRIPTION:
XS GIS Cut Line= 3
      1608264.91      6840189.05      1609556.62      6840381.76
      1610831.35      6840329.73
#Sta/Elev= 30
  3695.5 1772.69  3715.8 1769.52    3736 1761.37  3756.3 1760.62  3766.4 1757.35
  3806.8 1750.49    3827 1750.69    3918  1744.9  3948.4  1744.7  3978.7 1749.82
    4009 1745.34  4057.8 1746.34  4170.8 1744.41  4251.7  1742.1  4271.9 1740.01
  4504.4 1734.97    4879 1732.31  4959.4 1728.18  4979.6 1729.16  4993.6 1726.61
  4994.2 1726.11  5026.1 1726.61  5029.9  1730.3  5049.9 1732.81    5150 1729.52
    5180 1732.86  5210.1 1733.77  5480.3 1733.27  5750.5 1735.28  6277.3 1748.89
#Mann= 3 ,-1 , 0
  3695.5     .05       0  4993.6     .05       0  5026.1     .05       0
Bank Sta=4993.6,5026.1
XS Rating Curve= 0 ,0
Exp/Cntr=0.3,0.1

Type RM Length L Ch R = 1 ,46074   ,856,856,856
BEGIN DESCRIPTION:
Rainy Creek 46073.55
END DESCRIPTION:
XS GIS Cut Line= 3
      1608509.71      6841038.02      1609535.78      6840834.88
      1611050.68      6840449.65
#Sta/Elev= 30
  3940.8 1737.74  4139.9 1738.63  4327.8 1737.96  4532.7 1735.21  4896.4 1732.83
  4947.7 1731.44  4975.8 1726.76  4983.8 1726.46  5006.6 1727.61  5027.3 1727.36
  5047.9 1729.08  5058.2 1728.73  5058.3 1725.98  5058.9 1725.48  5090.9 1725.98
  5099.5 1730.44  5120.7 1731.02  5161.6 1731.25    5182 1727.63  5197.4 1726.25
  5243.9 1730.99  5264.6 1730.05  5279.3 1731.13  5367.8 1732.67    5636 1732.41
  5806.1 1734.52  5969.8 1738.28  6110.7 1743.68  6275.8  1747.8  6549.9 1752.56
#Mann= 3 ,-1 , 0
  3940.8     .05       0  5058.3     .05       0  5090.9     .05       0
Bank Sta=5058.3,5090.9
XS Rating Curve= 0 ,0
Exp/Cntr=0.3,0.1

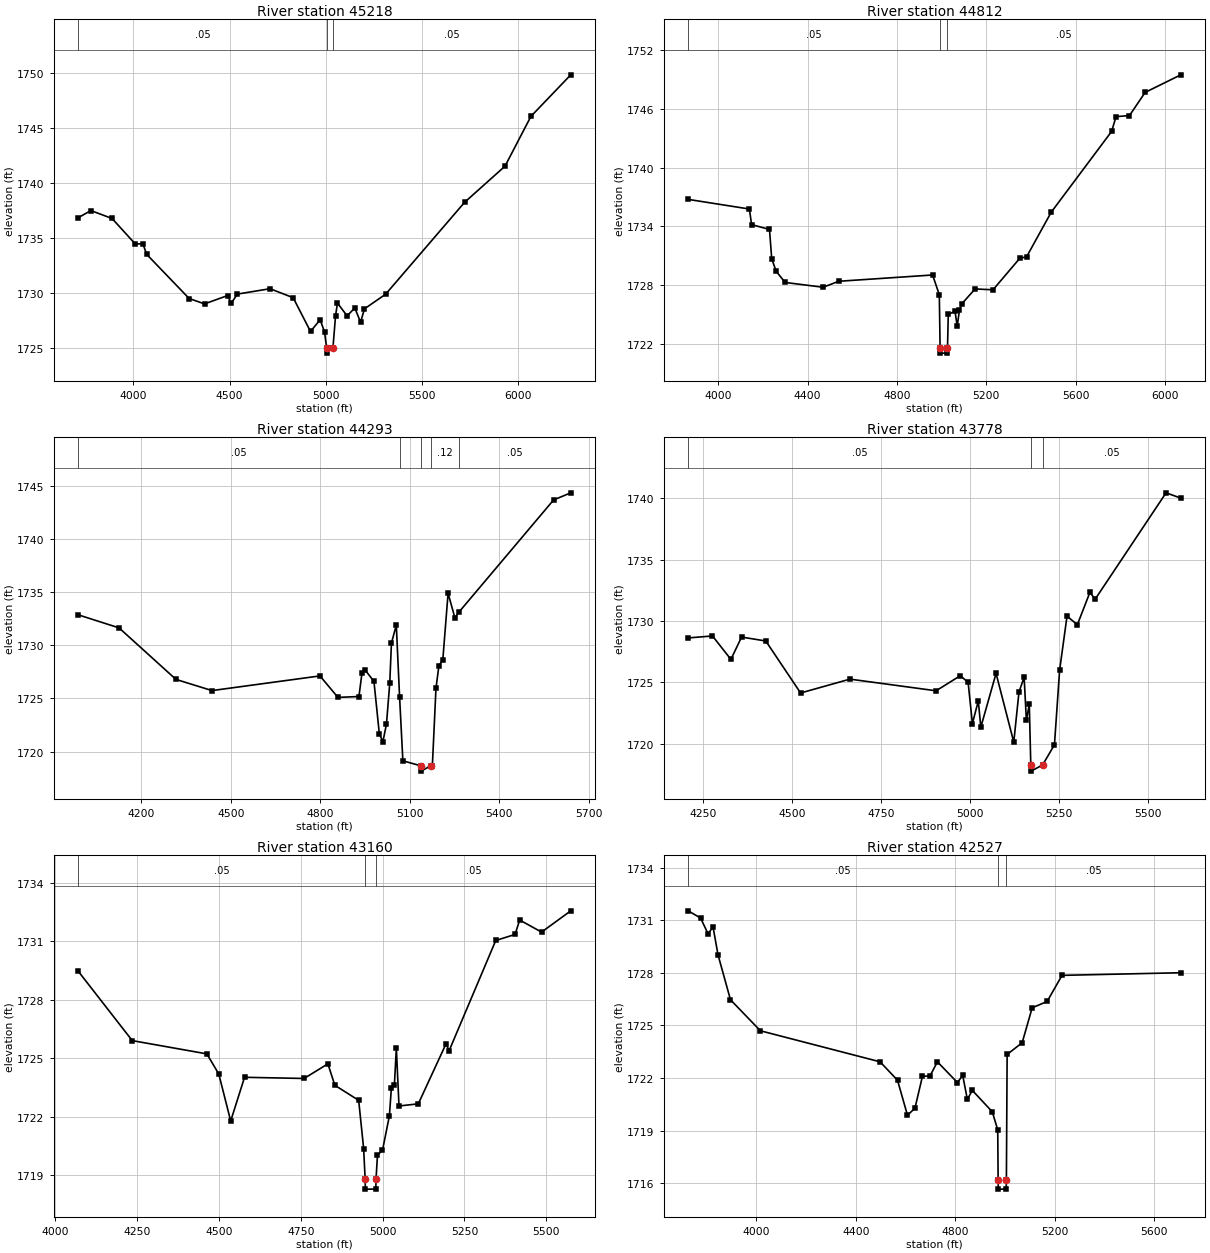
Type RM Length L Ch R = 1 ,45218   ,406,406,406
BEGIN DESCRIPTION:
Rainy Creek 45217.58
END DESCRIPTION:
XS GIS Cut Line= 3
      1608619.11      6841386.97      1609895.16      6841428.63
      1611176.41      6841433.84
#Sta/Elev= 30
  3713.9 1736.84  3779.8 1737.49  3889.9 1736.77    4010 1734.46    4050 1734.46
    4070  1733.5  4290.1 1729.49  4370.1    1729  4490.2 1729.76  4508.4 1729.04
  4540.2 1729.89  4710.3 1730.38  4830.4 1729.56  4920.4 1726.49  4970.5 1727.56
  4993.1 1726.46    5004 1725.02  5004.6 1724.52    5037 1725.02  5050.5 1727.93
  5060.5 1729.07  5110.5 1727.91  5150.5 1728.63  5180.5 1727.33  5200.5 1728.55
  5310.5 1729.88  5720.5 1738.24  5930.5 1741.53    6065 1746.06  6271.9 1749.84
#Mann= 3 ,-1 , 0
  3713.9     .05       0    5004     .05       0    5037     .05       0
Bank Sta=5004,5037
XS Rating Curve= 0 ,0
Exp/Cntr=0.3,0.1

Type RM Length L Ch R = 1 ,44812   ,519,519,519
BEGIN DESCRIPTION:
Rainy Creek 44811.67
END DESCRIPTION:
XS GIS Cut Line= 3
      1608671.18      6841803.63      1609806.62      6841803.63
      1610874.31      6841855.72
#Sta/Elev= 30
  3865.9 1736.76  4139.7 1735.78  4149.7 1734.19  4229.7  1733.7  4239.7 1730.71
  4259.7 1729.43  4299.7  1728.3  4469.7 1727.81  4539.7 1728.42  4959.7 1729.06
  4989.7 1727.04  4993.2  1721.6  4993.8  1721.1  5025.7  1721.1  5026.3  1721.6
  5029.8 1725.04  5059.8 1725.37  5069.8 1723.85  5079.8 1725.49  5089.8 1726.11
  5149.9 1727.64    5230 1727.55  5350.1 1730.77  5380.2 1730.91  5490.3 1735.45
  5760.6 1743.68  5780.6 1745.19  5840.7  1745.3  5910.8 1747.66  6070.3 1749.45
#Mann= 3 ,-1 , 0
  3865.9     .05       0  4993.2     .05       0  5026.3     .05       0
Bank Sta=4993.2,5026.3
XS Rating Curve= 0 ,0
Exp/Cntr=0.3,0.1

Type RM Length L Ch R = 1 ,44293   ,515,515,515
BEGIN DESCRIPTION:
Rainy Creek 44292.51
END DESCRIPTION:
XS GIS Cut Line= 3
      1608748.87      6842198.84      1609755.84      6842307.35
      1610337.42      6842572.09
#Sta/Elev= 30
  3987.9 1732.87    4125 1731.64  4315.9 1726.79  4436.6 1725.74  4798.7 1727.12
    4859  1725.1  4929.4 1725.18  4939.5 1727.38  4949.6 1727.69  4979.7 1726.61
  4997.8 1721.66  5009.8 1720.94  5021.7 1722.59  5032.7 1726.42  5038.4 1730.21
  5054.7  1731.9  5065.7 1725.14  5076.7 1719.13    5137 1718.66  5137.6 1718.16
  5170.1 1718.66  5175.6 1718.66  5187.7 1725.96  5197.5 1728.06  5210.7 1728.66
  5228.3  1734.9  5251.3 1732.57  5264.2 1733.11  5582.1 1743.68  5639.7 1744.35
#Mann= 5 ,-1 , 0
  3987.9     .05       0  5065.7     .12       0    5137     .03       0
  5170.1     .12       0  5264.2     .05       0
Bank Sta=5137,5170.1
XS Rating Curve= 0 ,0
Exp/Cntr=0.3,0.1

Type RM Length L Ch R = 1 ,43778   ,618,618,618
BEGIN DESCRIPTION:
Rainy Creek 43778.37
END DESCRIPTION:
XS GIS Cut Line= 3
      1608818.36      6842424.54      1609547.51      6842754.39
      1610010.98      6843109.58
#Sta/Elev= 30
  4207.5 1728.62  4275.8 1728.78  4327.5 1726.87  4357.5 1728.69  4425.5 1728.37
  4523.4 1724.13    4662 1725.26  4904.1 1724.31  4972.1 1725.54  4994.1    1725
  5006.1 1721.64  5022.7 1723.48  5029.8 1721.34  5072.6 1725.73  5122.4 1720.12
    5137 1724.21  5151.5 1725.41  5157.8 1721.91    5166  1723.2  5170.2 1718.26
  5170.8 1717.76  5203.4 1718.26  5236.7 1719.91  5251.2 1725.99    5272 1730.39
  5301.1  1729.7  5336.4 1732.34  5350.9 1731.77  5550.3 1740.45  5591.7 1740.02
#Mann= 3 ,-1 , 0
  4207.5     .05       0  5170.2     .03       0  5203.4     .05       0
Bank Sta=5170.2,5203.4
XS Rating Curve= 0 ,0
Exp/Cntr=0.3,0.1

Type RM Length L Ch R = 1 ,43160   ,633,633,633
BEGIN DESCRIPTION:
Rainy Creek 43160.02
END DESCRIPTION:
XS GIS Cut Line= 4
      1608750.77      6842394.97      1608798.47      6842593.53
       1609191.6      6843210.12       1609495.4      6843691.87
#Sta/Elev= 30
  4069.8 1729.47    4235 1725.91    4463 1725.23  4499.4  1724.2  4535.8 1721.79
  4578.1 1724.03    4760 1723.97  4832.8 1724.72    4854 1723.62  4926.8 1722.85
    4942 1720.38  4946.6  1718.8  4947.2  1718.3  4979.2  1718.3  4979.8  1718.8
  4984.3 1720.05  4999.5 1720.28  5020.7 1722.06  5026.7 1723.48    5036 1723.65
  5041.9 1725.52    5050 1722.56    5109 1722.67  5193.8 1725.75  5203.1 1725.39
  5345.6 1731.04  5404.7 1731.35  5418.6 1732.09  5485.6 1731.47  5574.8 1732.56
#Mann= 3 ,-1 , 0
  4069.8     .05       0  4946.6     .05       0  4979.8     .05       0
Bank Sta=4946.6,4979.8
XS Rating Curve= 0 ,0
Exp/Cntr=0.3,0.1

Type RM Length L Ch R = 1 ,42527   ,586,586,586
BEGIN DESCRIPTION:
Rainy Creek 42526.6
END DESCRIPTION:
XS GIS Cut Line= 4
      1608667.45      6842308.25      1608677.95      6842533.91
      1608753.23      6843592.07      1608787.87      6844284.77
#Sta/Elev= 30
  3725.8 1731.53  3775.6 1731.12  3805.6 1730.22  3825.7 1730.61  3845.7 1729.02
  3895.7 1726.46    4016 1724.69  4497.2 1722.92  4567.3 1721.87  4607.4 1719.87
  4637.5 1720.28  4667.6  1722.1  4697.7 1722.11  4727.7 1722.92  4807.9 1721.74
  4829.5 1722.14    4848 1720.78  4868.1 1721.29  4948.3 1720.07  4970.2 1719.04
  4971.8 1716.16  4972.4 1715.66  5004.4 1715.66    5005 1716.16    5008 1723.34
  5068.5 1724.01  5108.6    1726  5168.7 1726.36  5228.7 1727.85  5706.1    1728
#Mann= 3 ,-1 , 0
  3725.8     .05       0  4971.8     .05       0    5005     .05       0
Bank Sta=4971.8,5005
XS Rating Curve= 0 ,0
Exp/Cntr=0.3,0.1

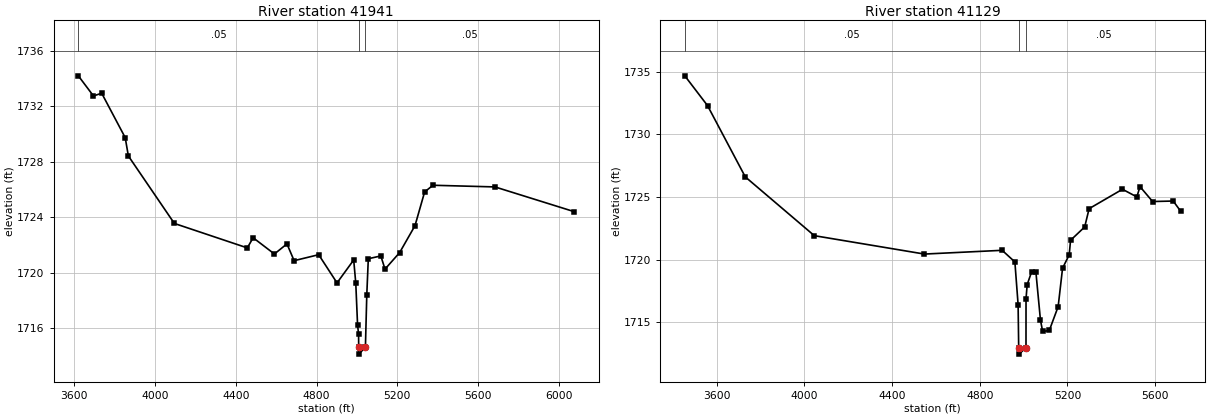
Type RM Length L Ch R = 1 ,41941   ,812,812,812
BEGIN DESCRIPTION:
Rainy Creek 41941.41
END DESCRIPTION:
XS GIS Cut Line= 3
      1608588.31      6842038.24      1608236.74      6843392.41
      1607972.47      6844414.84
#Sta/Elev= 30
  3620.5 1734.19  3695.5 1732.74  3736.1 1732.94  3852.6 1729.74  3868.2 1728.42
    4096 1723.56  4457.1  1721.8  4486.1 1722.53  4591.4 1721.36  4653.5 1722.09
  4688.9 1720.88  4810.6 1721.31  4901.4 1719.28    4984 1720.93  4994.3 1719.25
  5003.1 1716.27  5008.2 1715.57  5008.7 1714.65  5009.3 1714.15    5042 1714.65
  5048.8 1718.42  5056.3 1721.02  5118.3 1721.22    5139 1720.27  5211.4 1721.46
  5287.5  1723.4  5335.2 1725.83  5376.5 1726.31  5683.5 1726.19  6075.6 1724.41
#Mann= 3 ,-1 , 0
  3620.5     .05       0  5008.7     .05       0    5042     .05       0
Bank Sta=5008.7,5042
XS Rating Curve= 0 ,0
Exp/Cntr=0.3,0.1

Type RM Length L Ch R = 1 ,41129   ,1027,1027,1027
BEGIN DESCRIPTION:
Rainy Creek 41128.53
END DESCRIPTION:
XS GIS Cut Line= 5
      1608449.42      6841877.65      1607733.27       6842884.6
      1607646.46      6843192.76      1607585.32      6843660.36
      1607617.15       6843891.5
#Sta/Elev= 30
  3455.4 1734.69    3559 1732.31  3731.2 1726.61    4046 1721.91    4548 1720.44
  4902.4 1720.74  4960.4 1719.81  4975.1  1716.4  4977.8 1712.94  4978.4 1712.44
  5011.1 1712.94  5011.2 1716.87  5016.5    1718  5036.7 1719.02  5056.4 1718.97
    5077 1715.16  5087.1 1714.25  5117.3 1714.33  5157.7 1716.24  5177.8 1719.31
  5208.1 1720.38  5214.2 1721.54  5278.7 1722.61  5298.9 1724.07  5450.9 1725.62
  5516.4 1725.01  5530.9 1725.83  5588.4 1724.64  5682.3 1724.68  5716.1 1723.87
#Mann= 3 ,-1 , 0
  3455.4     .05       0  4977.8     .03       0  5011.1     .05       0
Bank Sta=4977.8,5011.1
XS Rating Curve= 0 ,0
Exp/Cntr=0.3,0.1