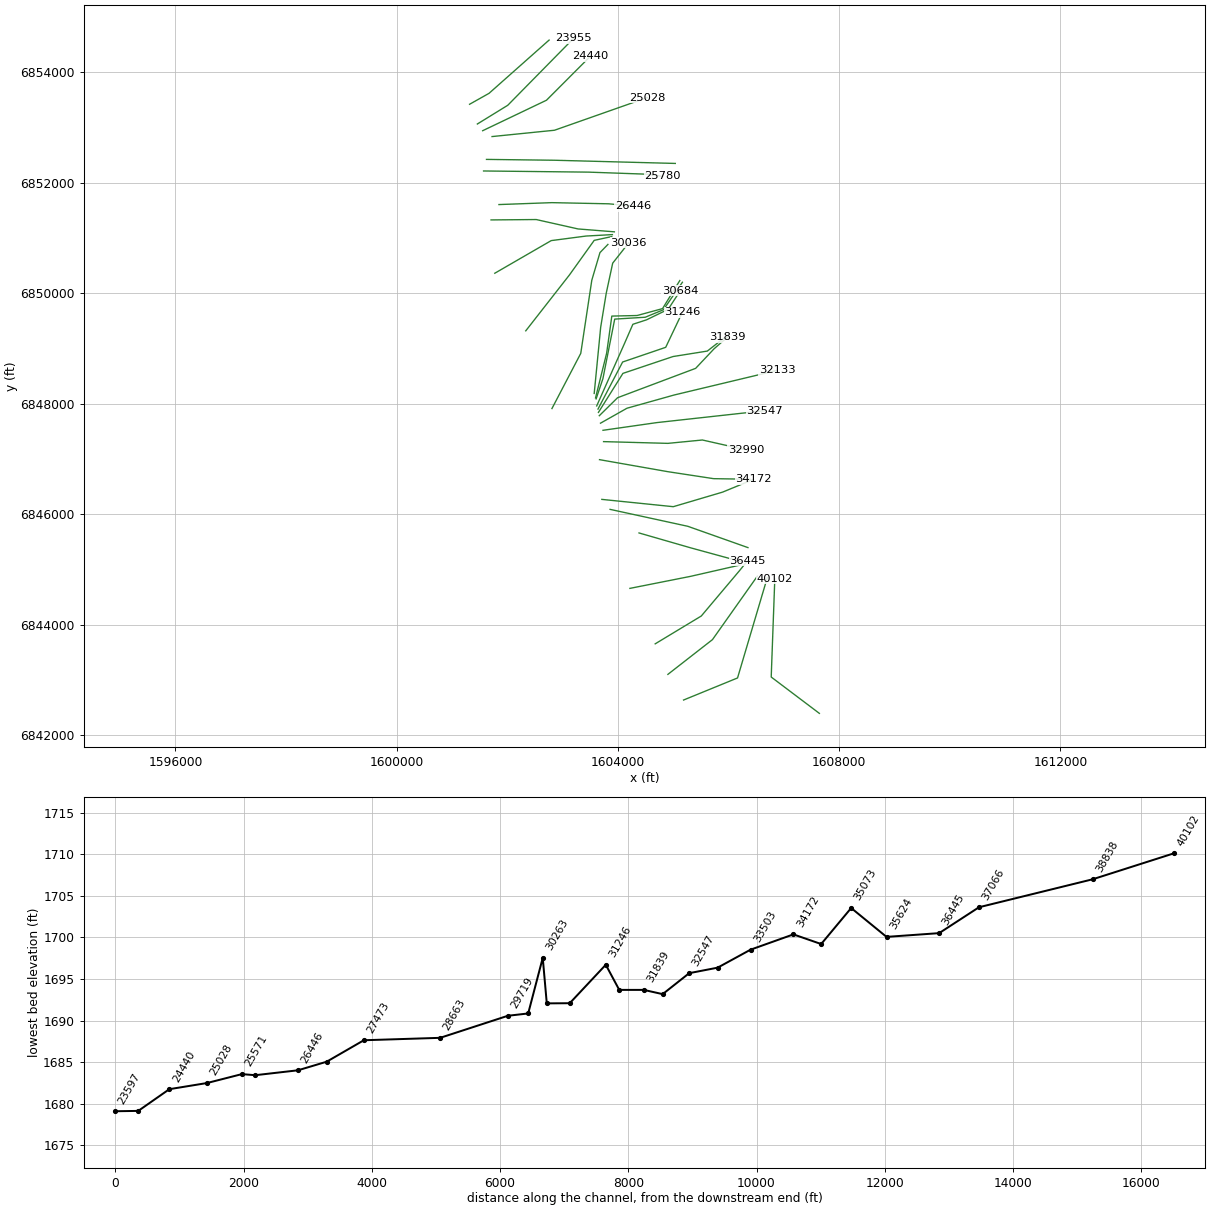
HEC-RAS study Rainy Creek.prj: Rainy Creek Base Level Engineering

--- Rainy Creek.g01 (geometry) --- (continued)

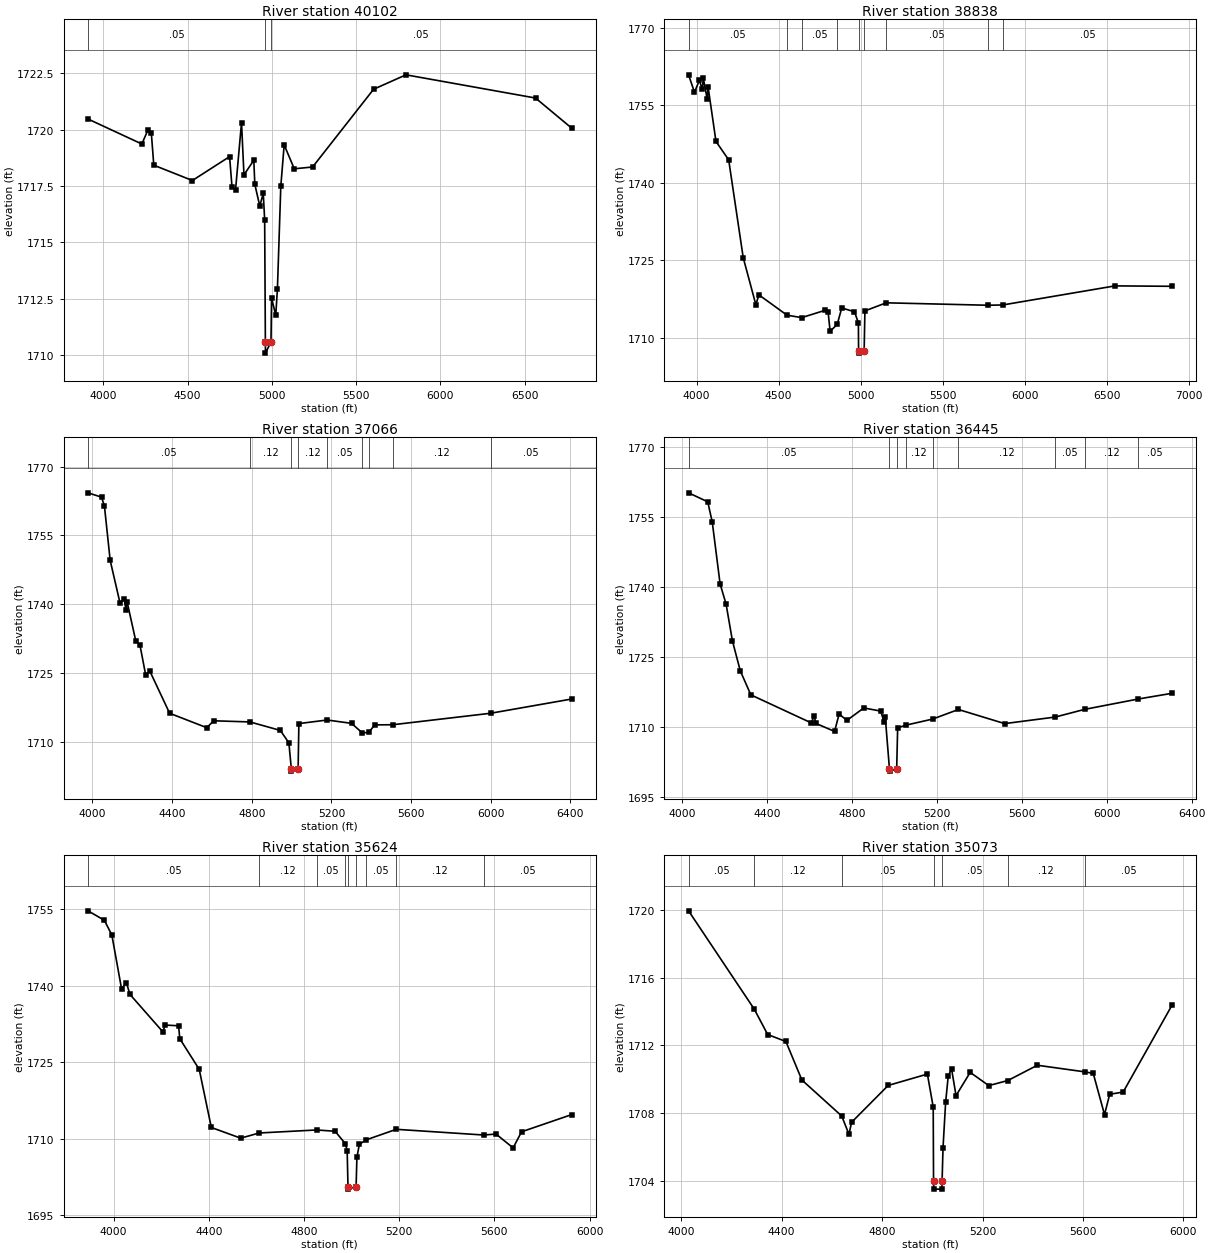
Type RM Length L Ch R = 1 ,40102   ,1264,1264,1264
BEGIN DESCRIPTION:
Rainy Creek 42691.285
END DESCRIPTION:
XS GIS Cut Line= 3
      1607641.52       6842397.7      1606771.04      6843055.05
      1606835.99      6844831.36
#Sta/Elev= 30
  3909.2 1720.48  4228.8 1719.37  4264.2 1719.98    4285 1719.86  4299.6 1718.43
  4528.5 1717.75  4749.2 1718.81  4763.7 1717.46  4784.6 1717.34    4820 1720.32
  4834.5    1718  4892.8 1718.65    4899 1717.58  4928.2 1716.62    4949 1717.18
  4957.3    1716  4961.5 1710.59  4962.1 1710.09  4994.8 1710.59  4998.3 1712.54
    5023 1711.76    5033 1712.94    5053 1717.49    5073 1719.33    5133 1718.27
  5241.7 1718.35  5603.4  1721.8  5795.5 1722.44    6564 1721.41  6777.5 1720.08
#Mann= 3 ,-1 , 0
  3909.2     .05       0  4961.5     .05       0  4994.8     .05       0
Bank Sta=4961.5,4994.8
XS Rating Curve= 0 ,0
Exp/Cntr=0.3,0.1

Type RM Length L Ch R = 1 ,38838   ,1772,1772,1772
BEGIN DESCRIPTION:
Rainy Creek 38837.81
END DESCRIPTION:
XS GIS Cut Line= 3
      1605186.69      6842639.19      1606162.36      6843038.49
      1606700.06      6844852.77
#Sta/Elev= 30
  3951.2 1760.91  3987.4 1757.52  4016.8 1759.84  4035.4 1758.07  4040.8  1760.3
  4064.8  1756.2  4070.2 1758.57  4118.3    1748  4195.7 1744.43  4284.3 1725.47
  4361.3 1716.37  4379.9 1718.27  4551.2 1714.33  4640.6 1713.86  4783.2 1715.28
  4801.8 1714.89  4813.8  1711.2  4857.3 1712.57  4884.7 1715.74  4962.1 1714.99
  4986.1 1712.84  4987.1 1707.48  4987.8 1706.98  5021.1 1707.48  5025.8 1715.16
  5155.4 1716.73  5773.4 1716.26  5864.9 1716.31  6549.7 1720.01  6897.7 1719.93
#Mann= 9 ,-1 , 0
  3951.2     .05       0  4551.2     .12       0  4640.6     .05       0
  4857.3     .12       0  4987.1     .07       0  5021.1     .12       0
  5155.4     .05       0  5773.4     .12       0  5864.9     .05       0
Bank Sta=4987.1,5021.1
XS Rating Curve= 0 ,0
Exp/Cntr=0.3,0.1

Type RM Length L Ch R = 1 ,37066   ,621,621,621
BEGIN DESCRIPTION:
Rainy Creek 37065.69
END DESCRIPTION:
XS GIS Cut Line= 3
      1604903.34      6843103.42      1605708.89      6843731.89
       1606520.7      6844880.21
#Sta/Elev= 30
  3977.3 1764.27  4045.4 1763.33  4059.9  1761.4  4088.8 1749.55  4138.6 1740.18
  4159.4 1741.11  4167.5 1738.82  4173.8 1740.51  4217.3    1732  4238.1 1731.15
    4267 1724.58  4287.8 1725.43  4387.3 1716.23  4573.7 1713.09  4608.9 1714.59
  4790.7 1714.34  4943.3 1712.49  4986.1 1709.78  4998.4 1704.12  4999.1 1703.62
  5032.5 1704.12  5036.3 1713.98    5178 1714.76    5301 1714.03  5354.4 1711.96
  5387.6 1712.05  5416.7  1713.7  5507.9 1713.73  5998.9 1716.23  6405.3 1719.33
#Mann= 9 ,-1 , 0
  3977.3     .05       0  4790.7     .12       0  4998.4     .07       0
  5032.5     .12       0    5178     .05       0  5354.4     .12       0
  5387.6     .05       0  5507.9     .12       0  5998.9     .05       0
Bank Sta=4998.4,5032.5
XS Rating Curve= 0 ,0
Exp/Cntr=0.3,0.1

Type RM Length L Ch R = 1 ,36445   ,821,821,821
BEGIN DESCRIPTION:
Rainy Creek 36444.78
END DESCRIPTION:
XS GIS Cut Line= 4
       1604673.7      6843655.62      1605507.04      6844159.09
      1606201.48      6844983.74      1606344.17      6845160.13
#Sta/Elev= 30
  4029.3 1760.25  4119.7 1758.32    4141 1753.97  4177.9 1740.71  4206.1 1736.37
  4236.1 1728.46    4273 1722.04  4322.9 1716.88  4606.8 1710.88  4622.3 1712.37
  4628.1 1710.77  4717.4 1709.04  4738.7 1712.76  4775.6 1711.41  4855.1 1714.07
  4934.7  1713.4  4950.2 1711.11  4956.1 1712.19  4975.9 1701.01  4976.6 1700.51
    5010 1701.01  5014.6 1709.79  5052.5 1710.37  5179.2 1711.68  5300.9 1713.74
  5518.9 1710.71  5757.5 1712.12  5895.9 1713.77  6149.3    1716  6307.9 1717.22
#Mann= 9 ,-1 , 0
  4029.3     .05       0  4975.9     .05       0    5010     .05       0
  5052.5     .12       0  5179.2     .05       0  5300.9     .12       0
  5757.5     .05       0  5895.9     .12       0  6149.3     .05       0
Bank Sta=4975.9,5010
XS Rating Curve= 0 ,0
Exp/Cntr=0.3,0.1

Type RM Length L Ch R = 1 ,35624   ,551,551,551
BEGIN DESCRIPTION:
Rainy Creek 35624.3
END DESCRIPTION:
XS GIS Cut Line= 3
      1604216.49      6844658.88      1605310.21      6844875.89
      1606204.29      6845079.88
#Sta/Elev= 30
  3892.1 1754.73  3960.8 1752.88  3992.5 1749.98  4033.3  1739.4  4053.7 1740.64
  4068.2 1738.33  4206.6 1730.97  4216.7 1732.29  4272.9 1732.15    4278 1729.61
  4359.6 1723.59  4410.5 1712.17  4533.9 1710.07  4611.9 1711.09  4852.6 1711.68
  4930.5 1711.43  4974.1 1708.97  4981.4 1707.59  4984.8 1700.56  4985.4 1700.06
  5018.9 1700.56  5022.3 1706.31  5032.6 1708.86  5060.8 1709.73  5187.7 1711.81
    5555 1710.69    5607 1710.88  5678.8 1708.16  5714.1 1711.32  5924.2 1714.69
#Mann= 9 ,-1 , 0
  3892.1     .05       0  4611.9     .12       0  4852.6     .05       0
  4974.1     .12       0  4984.8     .07       0  5018.9     .12       0
  5060.8     .05       0  5187.7     .12       0    5555     .05       0
Bank Sta=4984.8,5018.9
XS Rating Curve= 0 ,0
Exp/Cntr=0.3,0.1

Type RM Length L Ch R = 1 ,35073   ,468,468,468
BEGIN DESCRIPTION:
Rainy Creek 35073.36
END DESCRIPTION:
XS GIS Cut Line= 3
      1604381.42      6845661.47      1605314.55      6845392.38
      1606234.69      6845140.64
#Sta/Elev= 30
  4029.6 1719.93  4291.4 1714.13  4344.6 1712.64  4417.1 1712.23  4480.8 1709.96
  4639.3 1707.84  4668.2 1706.76  4678.7 1707.47  4824.3 1709.64  4980.4 1710.31
  5003.6 1708.37  5004.9 1704.03  5005.6 1703.53  5038.4 1703.53    5039 1704.03
  5042.7 1705.98  5053.1 1708.66  5063.4 1710.19  5076.6 1710.62  5094.5 1709.04
  5150.8 1710.41  5224.9 1709.63  5300.7 1709.93  5418.2 1710.83  5607.5 1710.44
  5640.7 1710.35  5685.6 1707.92  5706.2 1709.12  5759.8 1709.25  5954.7 1714.38
#Mann= 7 ,-1 , 0
  4029.6     .05       0  4291.4     .12       0  4639.3     .05       0
  5004.9     .05       0    5039     .05       0  5300.7     .12       0
  5607.5     .05       0
Bank Sta=5004.9,5039
XS Rating Curve= 0 ,0
Exp/Cntr=0.3,0.1

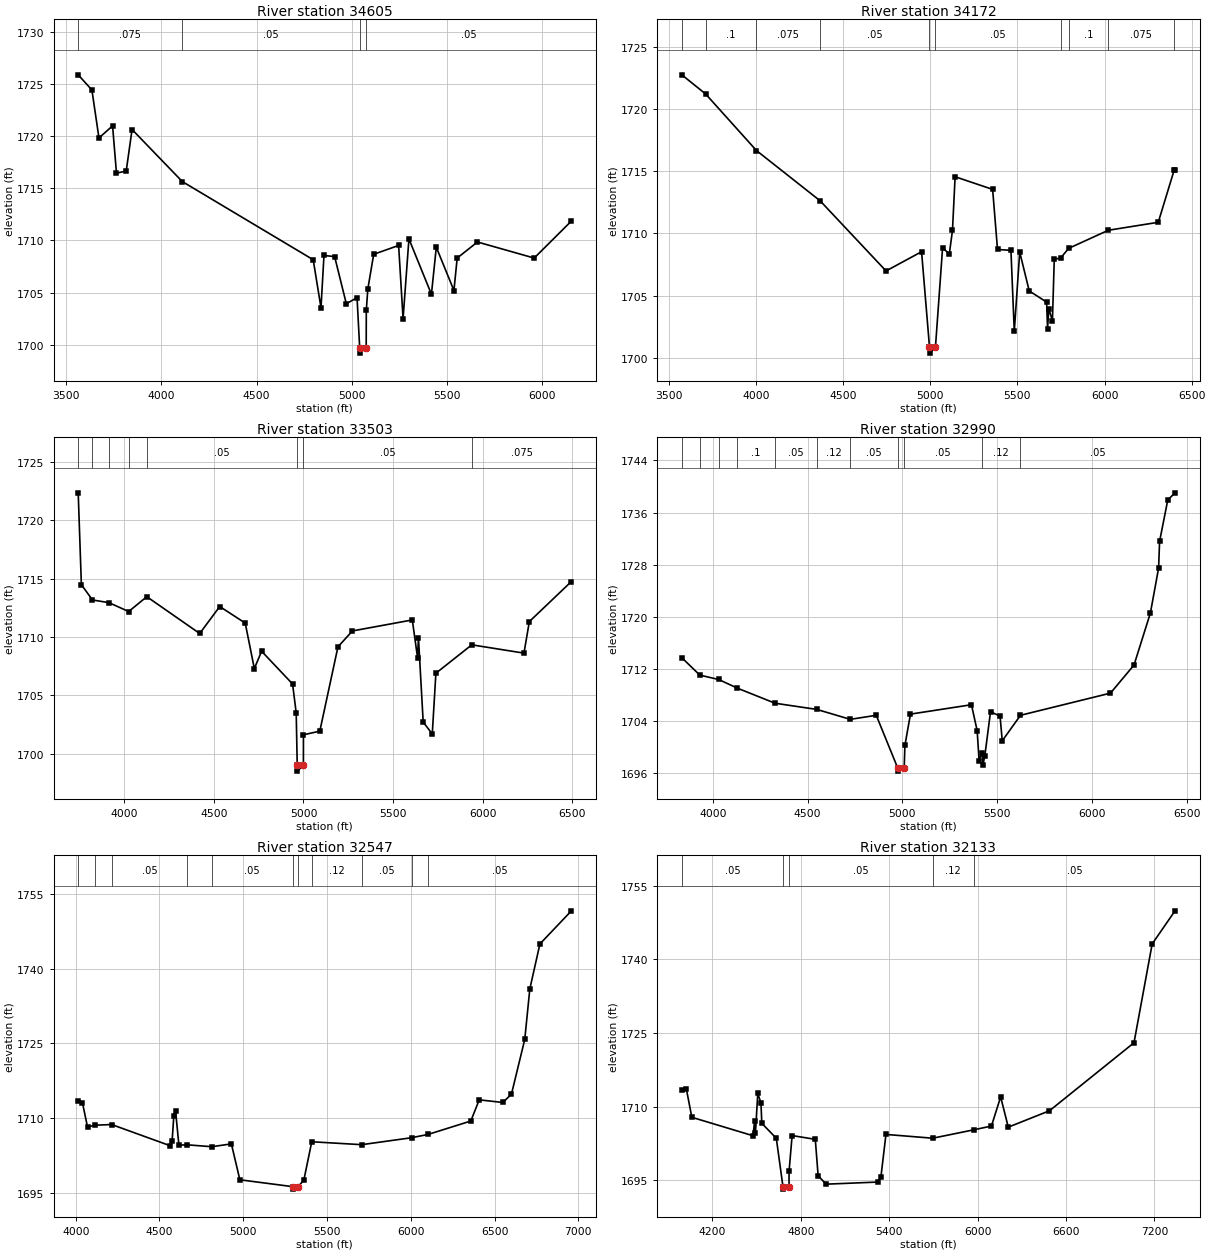
Type RM Length L Ch R = 1 ,34605   ,433,433,433
BEGIN DESCRIPTION:
Rainy Creek 34604.978
END DESCRIPTION:
XS GIS Cut Line= 3
      1603858.53      6846088.07      1605263.16      6845781.95
      1606350.83      6845396.36
#Sta/Elev= 30
  3562.4 1725.87  3634.4 1724.42  3671.4 1719.82    3743 1720.98  3763.5 1716.44
  3814.7 1716.66  3845.4 1720.63  4109.5 1715.64  4797.2 1708.15  4838.1 1703.55
  4853.8 1708.56  4909.8 1708.45  4971.2 1703.93  5027.6 1704.52  5041.4  1699.7
  5042.1  1699.2  5075.7  1699.7  5076.2  1703.3  5084.1 1705.33    5115 1708.67
    5246 1709.52  5269.4 1702.51  5300.2 1710.15  5418.4 1704.84    5444 1709.35
  5536.7  1705.2  5553.7 1708.31  5660.2 1709.85  5958.4 1708.31    6154 1711.86
#Mann= 4 ,-1 , 0
  3562.4    .075       0  4109.5     .05       0  5041.4     .05       0
  5075.7     .05       0
Bank Sta=5041.4,5075.7
XS Rating Curve= 0 ,0
Exp/Cntr=0.3,0.1

Type RM Length L Ch R = 1 ,34172   ,669,669,669
BEGIN DESCRIPTION:
Rainy Creek 34057.653
END DESCRIPTION:
XS GIS Cut Line= 4
      1603709.17      6846268.64      1605000.84      6846136.69
      1605893.21      6846400.58      1606448.74      6846629.74
#Sta/Elev= 30
  3574.7 1722.78  3711.2 1721.24  4003.1 1716.68  4368.4 1712.63  4746.6 1706.98
  4950.4 1708.53  4995.8 1700.86  4996.5 1700.36  5030.1 1700.86    5071 1708.85
  5109.5 1708.34  5127.7 1710.25  5142.8 1714.57  5358.1 1713.55  5386.1 1708.71
  5463.1 1708.64  5482.3 1702.11  5513.5  1708.5  5568.1 1705.37  5667.9 1704.47
  5673.2 1702.32  5680.4 1703.92  5701.2 1702.98  5711.7 1707.91  5749.4 1708.04
  5794.2  1708.8  6022.3 1710.26  6308.4  1710.9    6400 1715.12  6404.6 1715.12
#Mann= 10 ,-1 , 0
  3574.7    .075       0  3711.2      .1       0  4003.1    .075       0
  4368.4     .05       0  4995.8     .03       0  5030.1     .05       0
  5749.4    .075       0  5794.2      .1       0  6022.3    .075       0
    6400     .05       0
Bank Sta=4995.8,5030.1
XS Rating Curve= 0 ,0
Exp/Cntr=0.3,0.1

Type RM Length L Ch R = 1 ,33503   ,513,513,513
BEGIN DESCRIPTION:
Rainy Creek 33502.9
END DESCRIPTION:
XS GIS Cut Line= 4
      1603667.55      6846987.38      1604904.72      6846769.55
      1605730.01      6846643.63      1606389.69      6846633.22
#Sta/Elev= 30
  3743.8 1722.34  3761.5 1714.48  3823.3 1713.17  3915.2 1712.94  4025.4 1712.18
  4126.4 1713.45  4421.5  1710.3  4533.2 1712.61  4675.4 1711.19  4726.1  1707.3
  4766.7 1708.78  4939.4 1705.98  4959.7  1703.5  4965.3 1699.02    4966 1698.52
  4999.8 1699.02    5000 1701.63  5091.3 1701.94  5192.5 1709.16  5273.4 1710.52
  5607.2 1711.46  5636.3 1708.24  5641.4 1709.95  5667.9 1702.72  5718.5  1701.7
  5738.7  1706.9  5938.9 1709.33  6229.9 1708.62  6259.9 1711.32  6494.6 1714.75
#Mann= 8 ,-1 , 0
  3743.8     .05       0  3823.3    .075       0  3915.2      .1       0
  4025.4    .075       0  4126.4     .05       0  4965.3     .03       0
  4999.8     .05       0  5938.9    .075       0
Bank Sta=4965.3,4999.8
XS Rating Curve= 0 ,0
Exp/Cntr=0.3,0.1

Type RM Length L Ch R = 1 ,32990   ,443,443,443
BEGIN DESCRIPTION:
Rainy Creek 32990.192
END DESCRIPTION:
XS GIS Cut Line= 4
      1603740.46      6847313.77      1604902.93      6847282.14
      1605526.57      6847343.12      1606316.82      6847164.47
#Sta/Elev= 30
  3837.1 1713.75  3932.1 1711.08  4031.2 1710.41  4130.3 1709.08  4328.5 1706.77
    4549 1705.82    4725  1704.3    4862 1704.92  4974.8 1696.86  4975.5 1696.36
  5009.3 1696.86    5013 1700.29  5042.3  1705.1  5363.8 1706.54  5393.9 1702.56
    5404 1697.98  5419.1 1699.21  5424.5 1697.35  5434.1 1698.67  5464.3 1705.46
  5514.5  1704.8  5526.1 1701.01  5622.2 1704.92  6096.6 1708.32  6220.7 1712.63
  6307.1 1720.62  6350.3 1727.51  6355.4 1731.58  6398.6 1737.94  6436.8 1739.03
#Mann= 11 ,-1 , 0
  3837.1    .075       0  3932.1     .05       0  4031.2    .075       0
  4130.3      .1       0  4328.5     .05       0    4549     .12       0
    4725     .05       0  4974.8     .03       0  5009.3     .05       0
  5419.1     .12       0  5622.2     .05       0
Bank Sta=4974.8,5009.3
XS Rating Curve= 0 ,0
Exp/Cntr=0.3,0.1

Type RM Length L Ch R = 1 ,32547   ,414,414,414
BEGIN DESCRIPTION:
Rainy Creek 32400.675
END DESCRIPTION:
XS GIS Cut Line= 3
      1603730.05      6847518.64      1604705.23      6847658.09
      1606651.85      6847872.61
#Sta/Elev= 30
  4014.9 1713.47  4040.1 1713.11  4070.4  1708.2  4115.1 1708.56  4214.7 1708.69
  4565.4 1704.41  4575.5 1705.44  4585.6  1710.5  4595.7  1711.5  4615.9 1704.55
  4666.8 1704.61  4812.3 1704.23  4929.1  1704.8  4979.6 1697.58  5294.4  1696.2
  5295.1  1695.7  5328.9  1696.2  5361.9 1697.58  5408.7 1705.23  5706.5 1704.64
  6004.4 1706.04  6103.7 1706.71  6357.9  1709.4  6408.2 1713.66  6549.1 1713.13
  6600.6 1714.81  6679.9 1725.82  6710.1 1735.97  6770.4 1745.02  6958.4 1751.68
#Mann= 11 ,-1 , 0
  4014.9     .05       0  4115.1    .075       0  4214.7     .05       0
  4666.8     .12       0  4812.3     .05       0  5294.4     .03       0
  5328.9     .05       0  5408.7     .12       0  5706.5     .05       0
  6004.4     .12       0  6103.7     .05       0
Bank Sta=5294.4,5328.9
XS Rating Curve= 0 ,0
Exp/Cntr=0.3,0.1

Type RM Length L Ch R = 1 ,32133   ,294,294,294
BEGIN DESCRIPTION:
Mapping XS b52f421c
END DESCRIPTION:
XS GIS Cut Line= 4
       1603684.9      6847647.12      1604164.04      6847917.94
      1605018.21      6848157.52      1606875.87      6848601.97
#Sta/Elev= 30
    3992 1713.31  4022.5 1713.65  4060.1 1707.81  4475.8 1704.05    4486 1707.08
  4491.7 1704.54  4507.6 1712.66  4529.3  1710.7    4535 1706.58  4633.4 1703.54
  4678.6 1693.68  4679.6 1693.18  4719.8 1693.68  4719.9 1696.78  4740.7 1704.09
    4898 1703.32  4917.3  1695.9  4971.4 1694.19  5322.3 1694.62  5343.5 1695.68
  5377.6 1704.32  5694.9 1703.55  5973.9 1705.26  6093.6 1706.03  6156.2 1711.97
  6207.7  1705.8  6487.4 1709.14  7061.1 1722.99  7184.5 1743.12  7339.6 1749.86
#Mann= 5 ,-1 , 0
    3992     .05       0  4678.6     .03       0  4719.8     .05       0
  5694.9     .12       0  5973.9     .05       0
Bank Sta=4678.6,4719.8
XS Rating Curve= 0 ,0
Exp/Cntr=0.3,0.1

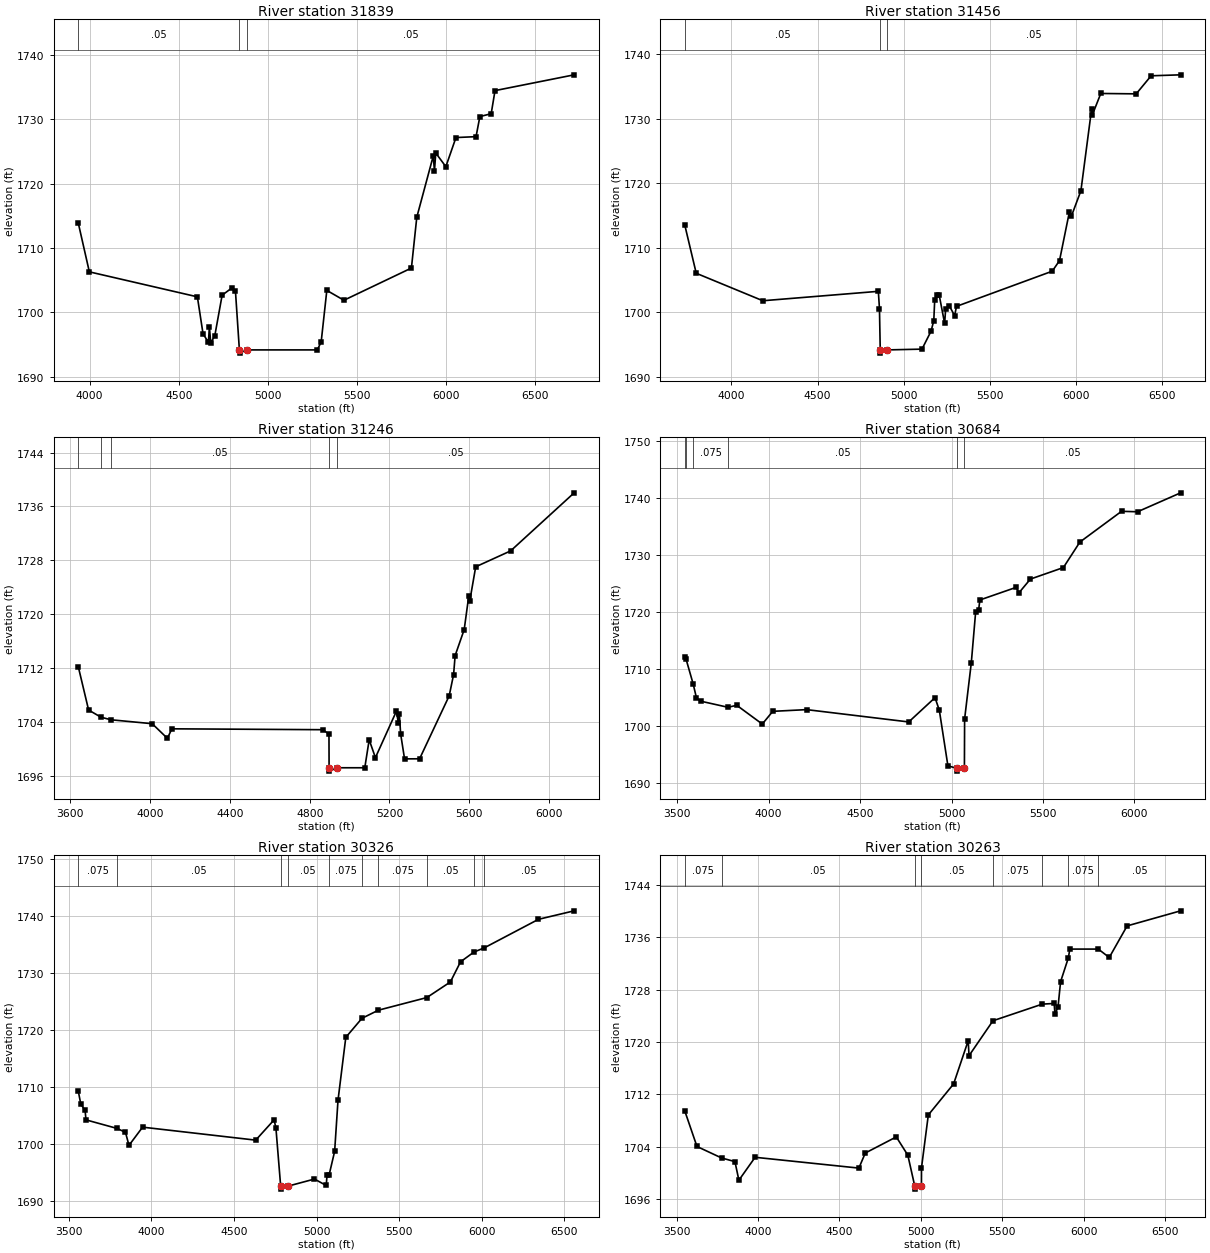
Type RM Length L Ch R = 1 ,31839   ,383,383,383
BEGIN DESCRIPTION:
Mapping XS 59e0ed95
END DESCRIPTION:
XS GIS Cut Line= 5
      1603663.14      6847782.49       1603993.9      6848108.04
      1605405.36      6848639.29      1605738.69      6848993.46
      1605983.46      6849206.98
#Sta/Elev= 30
  3936.3 1713.85  3998.1 1706.31  4604.6 1702.43  4636.4 1696.68  4666.7 1695.37
    4672 1697.82  4679.4 1695.29  4702.2 1696.37  4743.5 1702.68  4796.9 1703.79
  4818.3 1703.31  4840.4 1694.19  4841.4 1693.69  4881.6 1694.19  5277.7 1694.19
  5299.5 1695.42  5331.2 1703.43  5427.3  1701.9  5806.1  1706.9  5836.3 1714.79
  5928.6 1724.29  5935.5    1722  5942.8 1724.76  5999.4 1722.64  6056.1 1727.16
  6168.9  1727.3  6190.4 1730.42  6253.9 1730.86  6275.4 1734.45  6719.7  1736.9
#Mann= 3 ,-1 , 0
  3936.3     .05       0  4840.4     .03       0  4881.6     .05       0
Bank Sta=4840.4,4881.6
XS Rating Curve= 0 ,0
Exp/Cntr=0.3,0.1

Type RM Length L Ch R = 1 ,31456   ,210,210,210
BEGIN DESCRIPTION:
Mapping XS c2e29514
END DESCRIPTION:
XS GIS Cut Line= 5
      1603647.52      6847842.38      1604090.25      6848548.15
       1604996.5      6848852.84       1605616.3      6848951.79
      1605978.29      6849235.66
#Sta/Elev= 30
    3730 1713.53  3796.3 1706.07  4182.8 1701.81    4853 1703.27  4859.5 1700.58
    4864 1694.19    4865 1693.69  4905.2 1694.19  5106.2 1694.31  5158.9  1697.1
  5174.7 1698.73    5180 1701.91  5190.6 1702.65  5206.2 1702.67  5237.7 1698.29
  5243.3 1700.47  5263.9 1701.07  5295.5  1699.5  5306.6 1700.94    5862 1706.39
  5904.2 1708.03  5961.2 1715.54  5973.4 1714.94  6028.4 1718.87  6090.5 1731.55
  6095.5 1730.68  6143.7 1733.94  6349.1 1733.88  6435.8 1736.68  6606.9 1736.83
#Mann= 3 ,-1 , 0
    3730     .05       0    4864     .03       0  4905.2     .05       0
Bank Sta=4864,4905.2
XS Rating Curve= 0 ,0
Exp/Cntr=0.3,0.1

Type RM Length L Ch R = 1 ,31246   ,562,562,562
BEGIN DESCRIPTION:
Mapping XS 73423c88
END DESCRIPTION:
XS GIS Cut Line= 4
      1603639.75      6847902.35      1604085.05      6848753.88
      1604863.69       6849019.5       1605165.3      6849653.92
#Sta/Elev= 30
  3639.9 1712.18  3691.4 1705.78  3753.7 1704.71  3804.2 1704.33  4010.2 1703.75
  4086.4 1701.58    4109 1702.99  4864.9 1702.86  4896.6 1702.22  4897.2 1697.21
  4898.2 1696.71  4938.4 1697.21  5076.2 1697.21  5098.2 1701.36  5129.5 1698.71
  5234.7  1705.6  5244.3 1703.91  5249.6 1705.16  5255.9 1702.25  5275.6 1698.53
    5351 1698.54  5499.4 1707.89  5521.5 1711.05  5529.2 1713.86  5574.7 1717.73
  5597.4 1722.67  5602.9 1722.02  5632.3 1727.04  5807.4  1729.4    6126 1738.02
#Mann= 5 ,-1 , 0
  3639.9     .05       0  3753.7    .075       0  3804.2     .05       0
  4897.2     .03       0  4938.4     .05       0
Bank Sta=4897.2,4938.4
XS Rating Curve= 0 ,0
Exp/Cntr=0.3,0.1

Type RM Length L Ch R = 1 ,30684   ,358,358,358
BEGIN DESCRIPTION:
Mapping XS 8917d087
END DESCRIPTION:
XS GIS Cut Line= 6
       1603616.3      6847959.61       1604121.5      6849095.02
      1604269.94      6849436.17      1604517.34       6849516.9
      1604907.96        6849707.       1605126.7      6850042.93
#Sta/Elev= 30
  3542.1 1712.02  3549.1 1711.71  3588.1 1707.34    3606  1704.9  3629.2 1704.35
  3778.3 1703.28  3826.1 1703.63  3965.6 1700.34    4023 1702.57    4208 1702.87
  4766.2 1700.71  4909.9 1704.97  4933.4 1702.76  4980.3 1693.02  5029.1 1692.59
  5030.1 1692.09  5070.5 1692.59  5071.6 1701.22  5108.3 1711.11  5131.8 1719.94
    5148  1720.3  5155.1 1722.09  5351.5 1724.28  5369.8 1723.39  5431.1 1725.75
  5611.5 1727.77  5701.7 1732.24  5929.4 1737.63    6017 1737.55  6252.4 1740.87
#Mann= 6 ,-1 , 0
  3542.1    .075       0  3549.1     .05       0  3588.1    .075       0
  3778.3     .05       0  5029.1     .05       0  5070.5     .05       0
Bank Sta=5029.1,5070.5
XS Rating Curve= 0 ,0
Exp/Cntr=0.3,0.1

Type RM Length L Ch R = 1 ,30326   ,63,63,63
BEGIN DESCRIPTION:
Mapping XS c7f29279
END DESCRIPTION:
XS GIS Cut Line= 6
      1603605.89      6848087.25      1603728.27      6848451.79
      1603941.82      6849529.92       1604493.9      6849563.77
      1604822.02      6849699.19      1605165.78      6850196.59
#Sta/Elev= 30
  3557.4 1709.23  3572.2 1707.01  3598.4 1705.89  3603.7 1704.23  3792.7 1702.72
    3843 1702.03  3864.1 1699.75  3946.6 1702.95  4631.6 1700.67  4742.9 1704.23
    4754  1702.8  4782.8 1692.57  4783.8 1692.07  4824.2 1692.57  4987.4 1693.84
  5058.5 1692.71  5063.6 1694.53  5075.4 1694.48  5109.6  1698.7  5129.9 1707.65
  5177.2 1718.72  5275.1 1722.06  5374.1 1723.48  5667.7  1725.7  5810.4 1728.44
  5872.1 1731.98  5953.1 1733.69  6015.8 1734.43    6344 1739.44  6560.1 1740.93
#Mann= 10 ,-1 , 0
  3557.4    .075       0  3792.7     .05       0  4782.8     .03       0
  4824.2     .05       0  5075.4    .075       0  5275.1     .05       0
  5374.1    .075       0  5667.7     .05       0  5953.1    .075       0
  6015.8     .05       0
Bank Sta=4782.8,4824.2
XS Rating Curve= 0 ,0
Exp/Cntr=0.3,0.1

Type RM Length L Ch R = 1 ,30263   ,227,227,227
BEGIN DESCRIPTION:
Mapping XS 7a2723fd
END DESCRIPTION:
XS GIS Cut Line= 6
      1603595.47      6848105.46      1603795.98      6848912.73
      1603889.73      6849584.61      1604348.07      6849595.02
       1604806.4      6849720.02      1605118.89      6850227.82
#Sta/Elev= 30
  3550.6 1709.47  3625.3 1704.05  3776.2  1702.3  3858.5 1701.74  3882.9  1698.9
  3982.5  1702.4  4619.9 1700.75  4659.1 1703.05  4849.7 1705.51  4920.5 1702.72
  4962.7 1698.04  4963.7 1697.54  5004.1 1698.04  5004.4 1700.79  5046.3 1708.86
  5201.7  1713.6  5291.4  1720.2  5296.4 1717.91  5443.4 1723.24  5746.5 1725.78
  5819.1 1725.88  5824.3 1724.29  5842.9 1725.31  5858.8  1729.2  5906.6 1732.85
  5915.5 1734.18  6090.4 1734.18  6157.7  1732.9  6267.5 1737.72  6596.1 1740.02
#Mann= 8 ,-1 , 0
  3550.6    .075       0  3776.2     .05       0  4962.7     .03       0
  5004.1     .05       0  5443.4    .075       0  5746.5     .05       0
  5906.6    .075       0  6090.4     .05       0
Bank Sta=4962.7,5004.1
XS Rating Curve= 0 ,0
Exp/Cntr=0.3,0.1

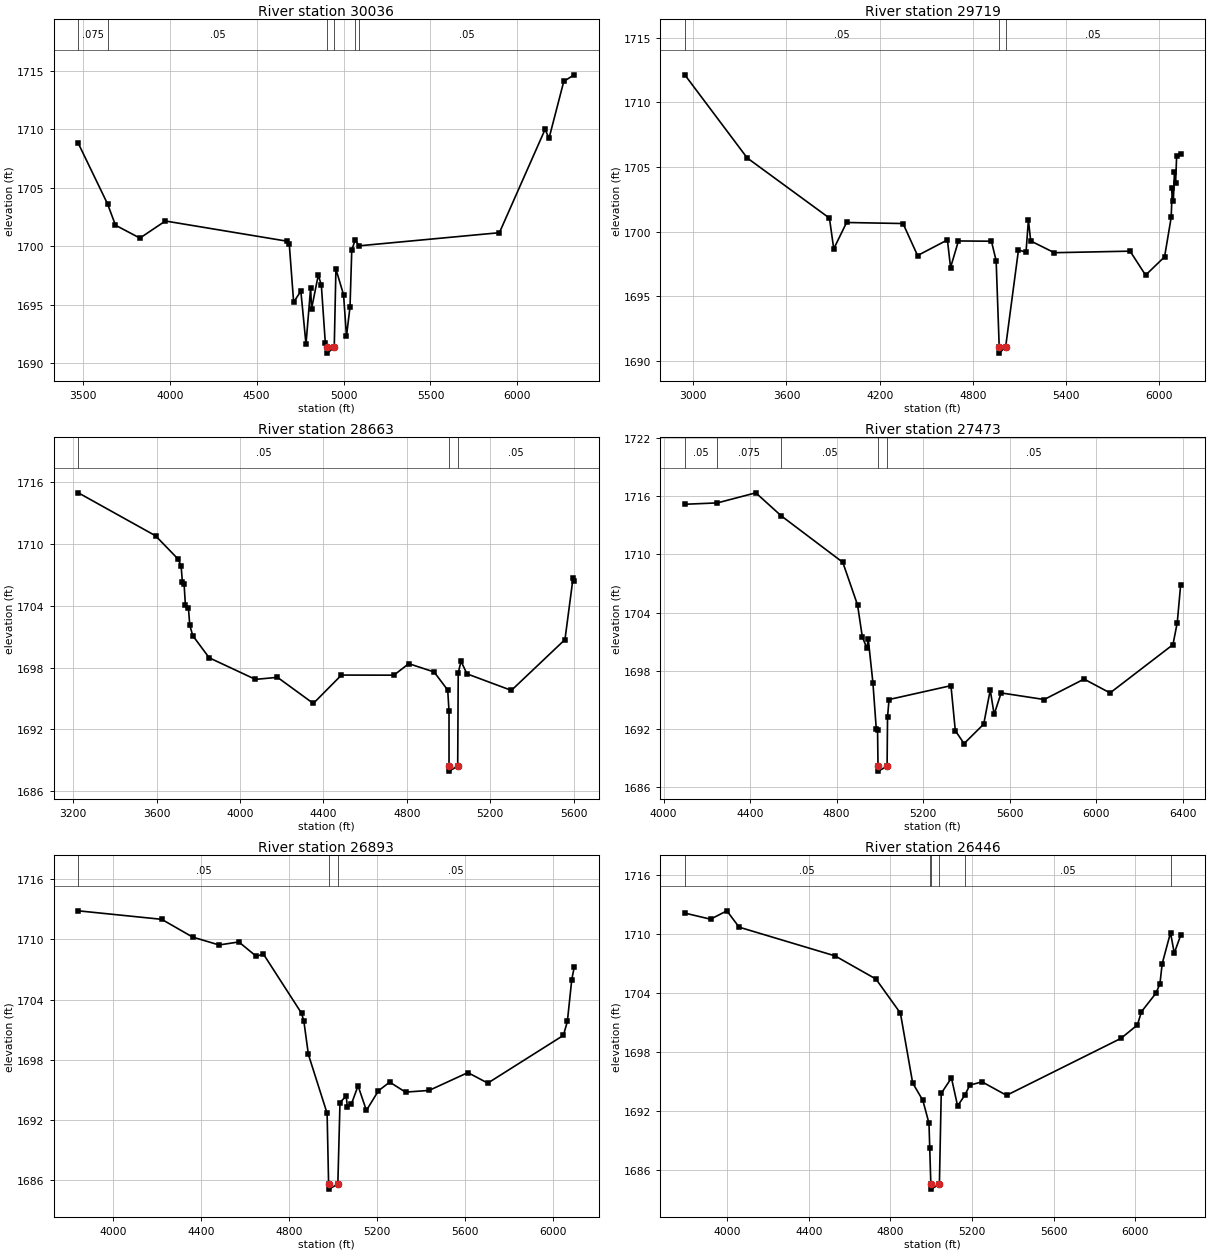
Type RM Length L Ch R = 1 ,30036   ,317,317,317
BEGIN DESCRIPTION:
Mapping XS 4c6b5fe4
END DESCRIPTION:
XS GIS Cut Line= 5
      1603571.16      6848185.33      1603688.34      6849383.22
      1603788.17       6849995.2      1603905.36      6850542.07
      1604196.15      6850910.99
#Sta/Elev= 30
  3474.1 1708.78  3642.5  1703.6  3687.8 1701.79  3828.4 1700.69  3974.9 1702.15
  4672.5 1700.43  4687.8 1700.15  4712.9 1695.21  4754.3 1696.16  4783.9 1691.63
  4810.7 1696.45  4815.8 1694.64  4854.8 1697.54  4872.2 1696.66  4895.3 1691.69
    4905 1691.36    4906 1690.86  4946.5 1691.36  4956.1 1698.04  5000.1 1695.85
  5016.9  1692.3  5037.2 1694.81  5047.3 1699.67  5066.8 1700.52  5089.9 1700.03
  5896.7 1701.15  6159.6 1709.98  6182.1 1709.21  6267.1 1714.08  6326.8 1714.64
#Mann= 6 ,-1 , 0
  3474.1    .075       0  3642.5     .05       0    4905     .05       0
  4946.5     .05       0  5066.8    .075       0  5089.9     .05       0
Bank Sta=4905,4946.5
XS Rating Curve= 0 ,0
Exp/Cntr=0.3,0.1

Type RM Length L Ch R = 1 ,29719   ,1056,1056,1056
BEGIN DESCRIPTION:
Mapping XS 9d355e4b
END DESCRIPTION:
XS GIS Cut Line= 5
      1602807.29       6847911.9       1603328.1      6848910.13
      1603527.75      6850233.91      1603675.32      6850733.04
      1603818.54       6850880.6
#Sta/Elev= 30
  2945.8 1712.14  3347.4  1705.7  3876.6 1701.04  3904.3 1698.66    3987  1700.7
  4350.2 1700.62  4443.8 1698.14  4635.9 1699.35  4656.1 1697.21  4706.7 1699.27
  4919.1 1699.25  4949.4 1697.74  4969.1 1691.08  4970.1 1690.58  5010.7 1691.08
  5093.2 1698.58  5141.6 1698.39    5157 1700.88  5171.9 1699.27  5323.6 1698.36
  5811.3 1698.48  5911.1 1696.62  6033.3 1698.04  6075.8 1701.09  6082.7 1703.36
  6089.9 1702.38  6096.9 1704.63  6104.1 1703.73    6111 1705.85  6136.6    1706
#Mann= 3 ,-1 , 0
  2945.8     .05       0  4969.1     .05       0  5010.7     .05       0
Bank Sta=4969.1,5010.7
XS Rating Curve= 0 ,0
Exp/Cntr=0.3,0.1

Type RM Length L Ch R = 1 ,28663   ,1190,1190,1190
BEGIN DESCRIPTION:
Mapping XS 21440bee
END DESCRIPTION:
XS GIS Cut Line= 4
      1602334.17       6849318.1      1603124.11       6850329.4
      1603571.16       6850954.4      1603889.23      6851023.17
#Sta/Elev= 30
  3224.7 1714.99  3595.2 1710.81  3702.8 1708.55  3717.3 1707.91  3723.7 1706.29
  3731.8  1706.1  3738.1 1704.04  3752.6  1703.8  3758.9 1702.12  3773.4  1701.1
  3852.1 1698.95  4073.7 1696.85  4179.5 1697.05  4351.3 1694.51  4486.1 1697.27
  4737.6 1697.26  4808.9 1698.38  4930.5 1697.57  4995.6 1695.81  5001.8 1693.77
  5001.9 1688.43  5002.9 1687.93  5043.5 1688.43    5046 1697.49  5059.5 1698.61
  5087.8 1697.39  5300.8 1695.78  5557.7 1700.72  5596.7 1706.73  5601.8 1706.43
#Mann= 3 ,-1 , 0
  3224.7     .05       0  5001.9     .03       0  5043.5     .05       0
Bank Sta=5001.9,5043.5
XS Rating Curve= 0 ,0
Exp/Cntr=0.3,0.1

Type RM Length L Ch R = 1 ,27473   ,580,580,580
BEGIN DESCRIPTION:
Mapping XS 43feeade
END DESCRIPTION:
XS GIS Cut Line= 4
      1601774.26      6850359.77      1602794.25      6850950.06
      1603423.59      6851032.52      1603900.47      6851058.54
#Sta/Elev= 30
  4098.4 1715.18  4248.8 1715.32  4426.4 1716.36  4544.2 1713.98  4828.3 1709.19
  4896.5 1704.79  4918.6 1701.49  4940.1 1700.31  4945.9 1701.28  4967.5 1696.77
  4983.2 1691.94    4989 1691.85  4991.1 1688.14  4992.1 1687.64    5033 1688.14
  5035.1 1693.22    5042 1695.03  5328.1 1696.46  5348.2 1691.82  5388.6 1690.48
  5479.4 1692.49  5509.6 1696.01  5527.6  1693.5    5560 1695.71    5759 1695.03
  5943.1 1697.14  6063.2 1695.71  6353.7 1700.69  6373.7 1702.97  6389.2 1706.83
#Mann= 5 ,-1 , 0
  4098.4     .05       0  4248.8    .075       0  4544.2     .05       0
  4991.1     .05       0    5033     .05       0
Bank Sta=4991.1,5033
XS Rating Curve= 0 ,0
Exp/Cntr=0.3,0.1

Type RM Length L Ch R = 1 ,26893   ,447,447,447
BEGIN DESCRIPTION:
Mapping XS edc6d75a
END DESCRIPTION:
XS GIS Cut Line= 4
      1601706.53      6851324.19      1602522.55      6851331.13
      1603279.49        6851161.      1603935.75      6851108.91
#Sta/Elev= 30
  3843.7 1712.86  4222.2 1712.01  4362.2 1710.24  4482.2 1709.45  4572.2 1709.75
  4652.2  1708.3  4682.8 1708.57    4857 1702.62  4867.3 1701.82  4887.8 1698.51
  4972.7 1692.63  4979.5 1685.56  4980.5 1685.06  5021.4 1685.56  5031.2 1693.71
  5059.3 1694.37  5064.4 1693.31  5082.5 1693.53  5113.2 1695.38    5151 1692.92
  5205.5 1694.88  5256.7 1695.75  5328.5 1694.75  5435.6 1694.92  5611.6  1696.7
  5701.9 1695.65  6045.1 1700.42  6063.1 1701.81  6083.1    1706  6093.9  1707.2
#Mann= 3 ,-1 , 0
  3843.7     .05       0  4979.5     .05       0  5021.4     .05       0
Bank Sta=4979.5,5021.4
XS Rating Curve= 0 ,0
Exp/Cntr=0.3,0.1

Type RM Length L Ch R = 1 ,26446   ,666,666,666
BEGIN DESCRIPTION:
Mapping XS 0a9cd797
END DESCRIPTION:
XS GIS Cut Line= 4
      1601848.94      6851601.97       1602803.8      6851636.69
      1603831.57      6851615.86      1604276.05      6851574.19
#Sta/Elev= 30
  3792.8 1712.08  3918.9 1711.46    3999 1712.31    4059 1710.65  4529.3 1707.73
  4729.5 1705.38  4849.5 1701.91  4909.5 1694.82  4959.5 1693.04  4989.5 1690.72
  4993.2  1688.2  4998.6 1684.53  4999.6 1684.03  5040.5 1684.53  5049.5 1693.76
  5099.6 1695.33  5129.6 1692.49  5164.5 1693.55  5189.6  1694.6  5249.6 1694.93
  5369.6 1693.56  5930.4 1699.35  6010.7 1700.71  6030.8 1702.06  6101.1 1703.92
  6121.2 1704.88  6132.3 1706.93  6173.1 1710.09  6191.5 1708.01  6222.7 1709.81
#Mann= 6 ,-1 , 0
  3792.8     .05       0  4993.2     .12       0  4998.6     .07       0
  5040.5     .12       0  5164.5     .05       0  6173.1    .075       0
Bank Sta=4998.6,5040.5
XS Rating Curve= 0 ,0
Exp/Cntr=0.3,0.1

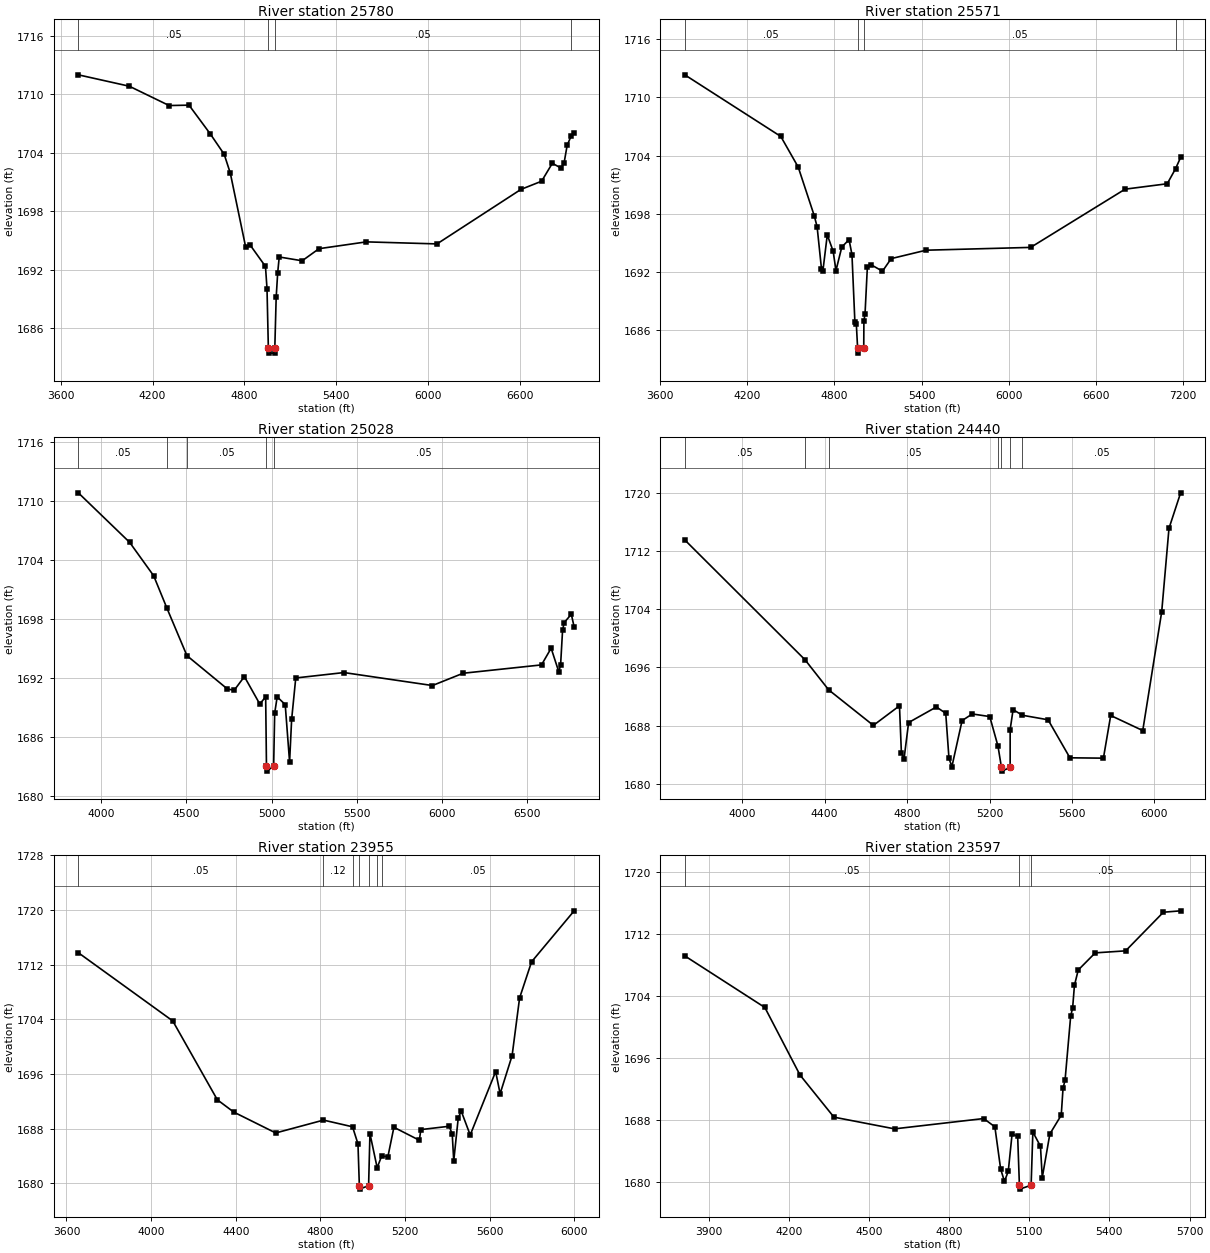
Type RM Length L Ch R = 1 ,25780   ,209,209,209
BEGIN DESCRIPTION:
Mapping XS 44ebe181
END DESCRIPTION:
XS GIS Cut Line= 4
      1601571.19      6852209.61      1603466.99      6852188.77
      1604546.85      6852150.58      1604810.35      6852112.44
#Sta/Elev= 30
  3714.2 1711.98    4048 1710.81    4308 1708.83  4438.1 1708.87  4578.1  1705.9
  4668.1 1703.83  4708.1  1701.9  4808.1 1694.35  4838.1 1694.52  4938.1 1692.33
  4948.1 1690.06    4957 1683.94    4958 1683.44  4998.1 1683.44  4999.1 1683.94
  5008.1 1689.16  5018.1  1691.7  5028.1  1693.3  5178.1 1692.91  5288.1 1694.15
  5598.1 1694.85  6059.9 1694.64  6608.8 1700.23    6744 1701.07  6814.2 1702.91
  6870.7 1702.42  6890.9 1702.93  6911.1 1704.75  6936.6 1705.68  6956.9    1706
#Mann= 4 ,-1 , 0
  3714.2     .05       0    4957     .05       0  4999.1     .05       0
  6936.6    .075       0
Bank Sta=4957,4999.1
XS Rating Curve= 0 ,0
Exp/Cntr=0.3,0.1

Type RM Length L Ch R = 1 ,25571   ,543,543,543
BEGIN DESCRIPTION:
Rainy Creek 25571.258
END DESCRIPTION:
XS GIS Cut Line= 3
      1601624.06      6852418.95      1602854.36      6852403.73
       1605037.2      6852346.04
#Sta/Elev= 30
  3769.6 1712.34  4430.6 1705.97  4550.6  1702.8  4660.6 1697.79  4680.6 1696.64
  4710.6  1692.3  4720.6 1692.09  4750.6 1695.79  4790.6 1694.13  4810.6 1692.11
  4850.6 1694.54  4900.6  1695.3  4920.6 1693.76  4940.6 1686.83  4950.6 1686.59
  4959.6 1684.07  4960.6 1683.57  5001.7 1684.07  5002.8  1686.9  5010.6 1687.63
  5026.7 1692.48  5050.7 1692.72  5130.7 1692.04  5190.7 1693.34  5430.8 1694.21
    6151  1694.5  6801.3 1700.52  7091.4 1701.08  7148.5 1702.63  7183.6  1703.8
#Mann= 4 ,-1 , 0
  3769.6     .05       0  4959.6     .05       0  5001.7     .05       0
  7148.5    .075       0
Bank Sta=4959.6,5001.7
XS Rating Curve= 0 ,0
Exp/Cntr=0.3,0.1

Type RM Length L Ch R = 1 ,25028   ,588,588,588
BEGIN DESCRIPTION:
Rainy Creek 25028.437
END DESCRIPTION:
XS GIS Cut Line= 3
      1601724.71      6852832.15      1602853.93      6852946.56
      1604530.19      6853536.98
#Sta/Elev= 30
    3865 1710.82  4166.4 1705.78  4307.5 1702.38  4385.4 1699.08  4502.9 1694.25
  4739.7 1690.87    4780 1690.72  4840.3 1692.12  4930.7 1689.33  4965.3 1690.06
    4970    1683    4971  1682.5  5012.1    1683  5018.2 1688.39  5032.9 1690.06
  5080.1 1689.27  5105.8 1683.43  5117.8 1687.76    5142 1691.98  5425.2 1692.53
  5944.7 1691.21    6125 1692.46  6585.4 1693.31    6642 1695.01  6686.9 1692.61
  6697.5  1693.3  6709.2 1696.85  6718.7 1697.62  6760.5 1698.46  6777.2 1697.17
#Mann= 5 ,-1 , 0
    3865     .05       0  4385.4     .12       0  4502.9     .05       0
    4970     .04       0  5012.1     .05       0
Bank Sta=4970,5012.1
XS Rating Curve= 0 ,0
Exp/Cntr=0.3,0.1

Type RM Length L Ch R = 1 ,24440   ,485,485,485
BEGIN DESCRIPTION:
Rainy Creek 24439.583
END DESCRIPTION:
XS GIS Cut Line= 3
      1601554.99        6852938.      1602708.83      6853489.58
      1603504.97      6854287.97
#Sta/Elev= 30
  3721.1  1713.5  4304.5 1697.05  4419.3 1692.92  4636.2 1688.04    4763 1690.73
  4772.3 1684.27  4785.2 1683.46  4807.3 1688.43  4942.1 1690.57  4987.5  1689.7
  5003.2 1683.52  5017.4 1682.38  5066.9  1688.7  5116.4 1689.61  5201.2 1689.25
  5241.1 1685.19    5258 1682.26    5259 1681.76  5300.1 1682.26  5300.2 1687.47
  5314.4  1690.2  5359.7 1689.43  5484.1 1688.81  5590.2 1683.59  5752.8 1683.54
  5788.1  1689.4  5943.7 1687.33  6035.6 1703.62    6071 1715.09  6127.5 1719.97
#Mann= 7 ,-1 , 0
  3721.1     .05       0  4304.5     .12       0  4419.3     .05       0
  5241.1     .12       0    5258     .04       0  5300.1     .12       0
  5359.7     .05       0
Bank Sta=5258,5300.1
XS Rating Curve= 0 ,0
Exp/Cntr=0.3,0.1

Type RM Length L Ch R = 1 ,23955   ,358,358,358
BEGIN DESCRIPTION:
Mapping XS 9dfce1b3
END DESCRIPTION:
XS GIS Cut Line= 3
      1601459.06      6853059.55      1602008.58      6853398.12
      1603198.68      6854609.05
#Sta/Elev= 30
  3656.2 1713.74  4102.4 1703.76  4313.2 1692.22  4390.9 1690.42    4589 1687.37
  4814.8 1689.25  4952.1 1688.27  4977.8 1685.77  4984.3 1679.65  4985.3 1679.15
    5028 1679.65  5034.4 1687.27  5068.5 1682.28  5089.4 1683.97  5119.3 1683.91
  5147.6  1688.2  5267.9  1686.3  5274.9 1687.86  5409.2 1688.35  5423.3 1687.18
  5430.4 1683.28  5451.6 1689.54  5465.7 1690.57  5508.2 1687.07  5628.5 1696.35
  5649.6 1693.11  5706.2 1698.68  5741.6 1707.12  5798.2 1712.41  5999.5 1719.87
#Mann= 7 ,-1 , 0
  3656.2     .05       0  4814.8     .12       0  4952.1     .05       0
  4984.3     .04       0    5028     .05       0  5068.5     .12       0
  5089.4     .05       0
Bank Sta=4984.3,5028
XS Rating Curve= 0 ,0
Exp/Cntr=0.3,0.1

Type RM Length L Ch R = 1 ,23597   ,421,421,421
BEGIN DESCRIPTION:
Mapping XS 35db60c5
END DESCRIPTION:
XS GIS Cut Line= 3
      1601318.47      6853416.35      1601670.04      6853614.27
      1602755.95      6854577.79
#Sta/Elev= 30
  3811.2 1709.18  4110.7 1702.53  4242.1 1693.83  4369.2 1688.39  4595.9 1686.88
  4929.6 1688.21  4971.4 1687.14  4993.1 1681.68  5007.3 1680.11  5021.5 1681.41
  5035.8 1686.22  5056.7  1685.9  5063.2 1679.61  5064.2 1679.11    5107 1679.61
  5113.5 1686.48    5142 1684.63  5148.7  1680.6  5177.1 1686.22  5219.7 1688.64
  5226.4 1692.11    5234 1693.16  5254.9 1701.38  5262.4 1702.51  5269.1 1705.38
  5283.3 1707.36  5346.9 1709.57  5460.6 1709.83  5601.9 1714.81  5666.4 1714.99
#Mann= 3 ,-1 , 0
  3811.2     .05       0  5063.2     .05       0    5107     .05       0
Bank Sta=5063.2,5107
XS Rating Curve= 0 ,0
Exp/Cntr=0.3,0.1