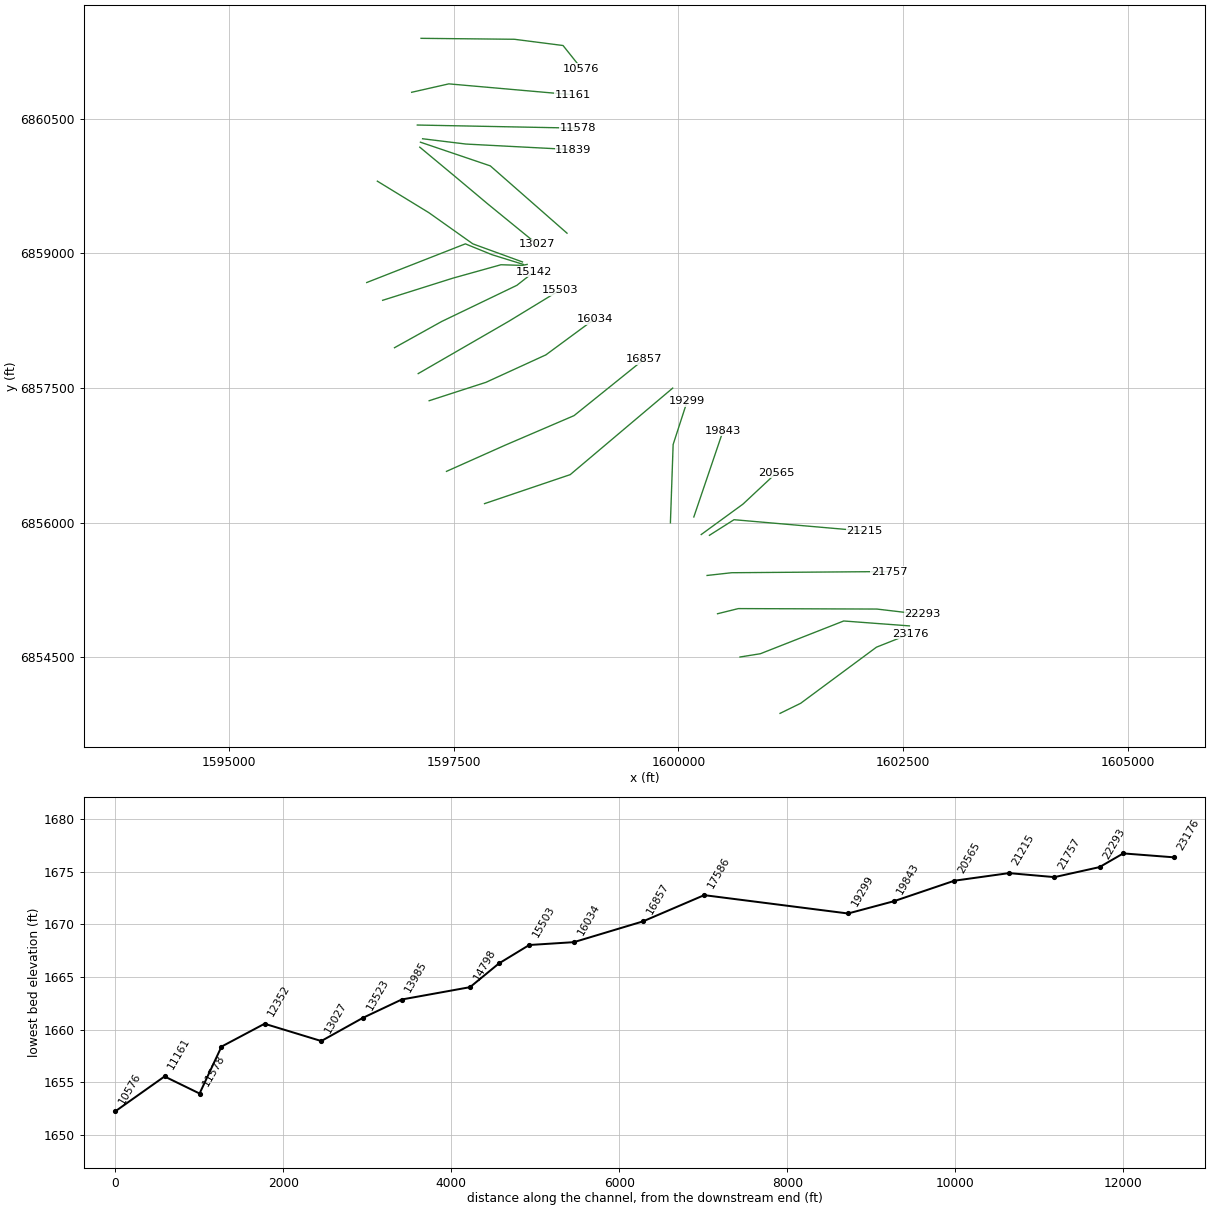
HEC-RAS study Rainy Creek.prj: Rainy Creek Base Level Engineering

--- Rainy Creek.g01 (geometry) --- (continued)

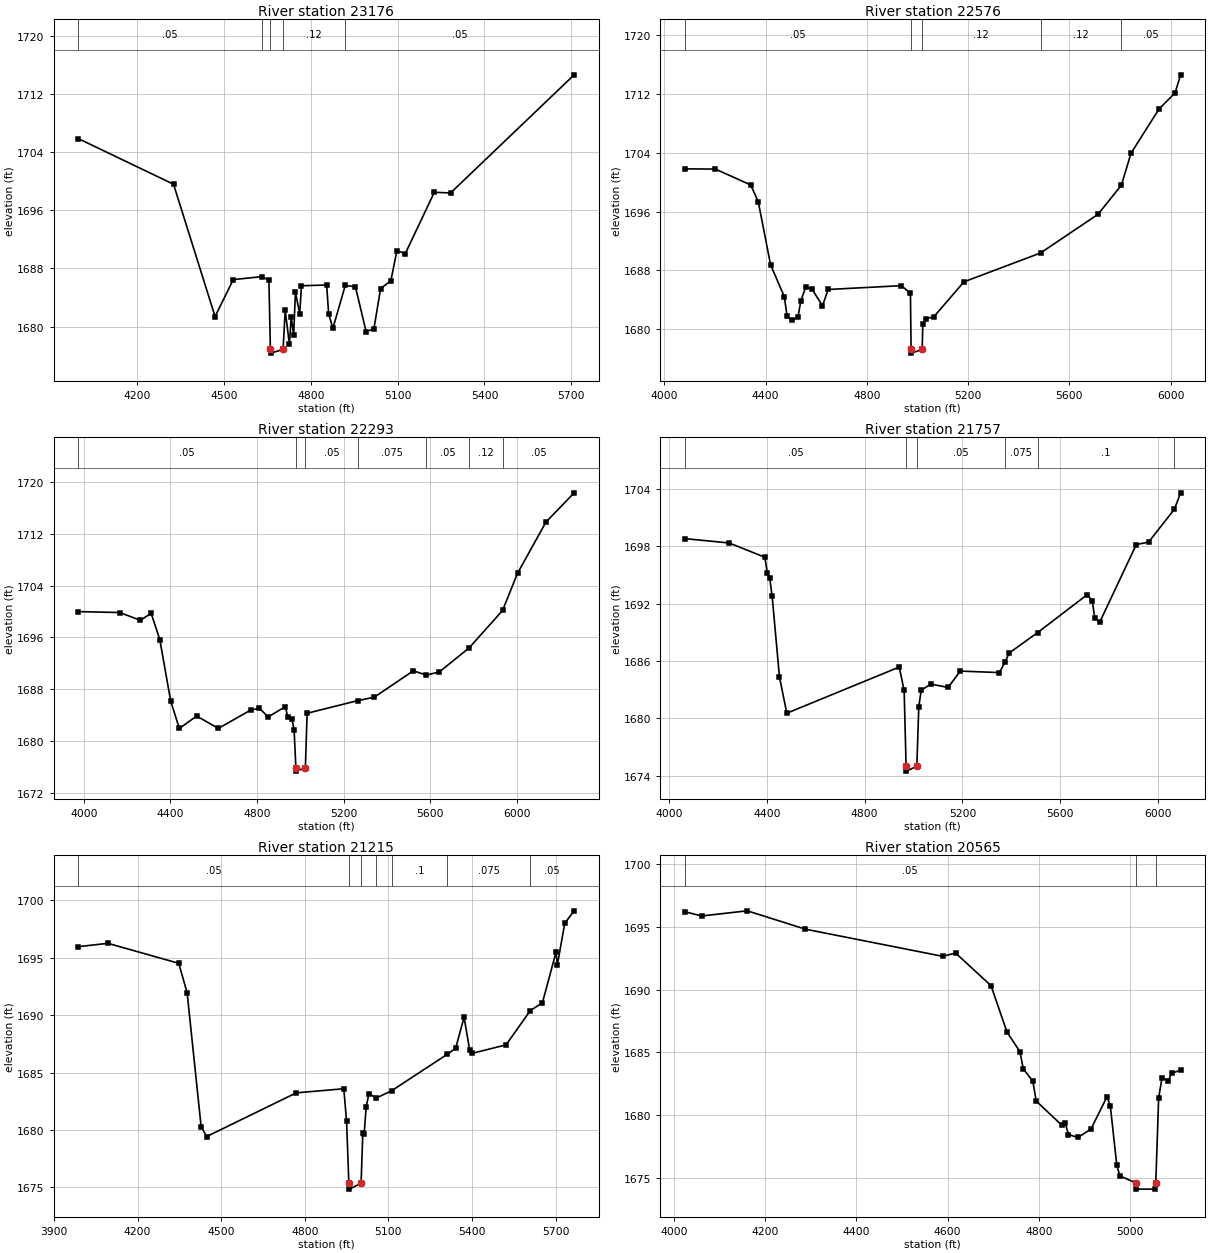
Type RM Length L Ch R = 1 ,23176   ,600,600,600
BEGIN DESCRIPTION:
Mapping XS 331fd70f
END DESCRIPTION:
XS GIS Cut Line= 4
      1601130.94      6853877.27      1601360.14      6853989.27
      1602203.89      6854614.27      1602584.07       6854765.3
#Sta/Elev= 30
  3995.8 1705.88  4324.9  1699.6  4468.5 1681.39  4531.5 1686.47    4630 1686.88
  4654.7 1686.41  4659.8 1676.85  4660.8 1676.35  4703.6 1676.85    4711 1682.23
  4725.6 1677.56  4731.8 1681.33  4740.2 1678.81  4746.4 1684.74  4761.1 1681.75
  4767.3 1685.62  4854.3 1685.73  4861.2 1681.76  4875.9 1679.77  4918.7 1685.68
  4953.8 1685.48  4990.7 1679.32  5017.7 1679.68  5040.8 1685.24  5076.2  1686.3
  5097.1 1690.44  5126.3 1690.06  5226.5 1698.49  5282.8  1698.4    5710 1714.66
#Mann= 5 ,-1 , 0
  3995.8     .05       0    4630     .12       0  4659.8     .05       0
  4703.6     .12       0  4918.7     .05       0
Bank Sta=4659.8,4703.6
XS Rating Curve= 0 ,0
Exp/Cntr=0.3,0.1

Type RM Length L Ch R = 1 ,22576   ,283,283,283
BEGIN DESCRIPTION:
Mapping XS 911d1d93
END DESCRIPTION:
XS GIS Cut Line= 4
       1600685.7       6854504.9      1600912.22      6854541.35
      1601839.31      6854905.93      1602570.54      6854851.28
#Sta/Elev= 30
  4080.6 1701.82  4201.4 1701.79  4340.9 1699.63  4370.7 1697.37  4419.5 1688.76
  4473.7 1684.41  4484.9 1681.73  4503.4 1681.17  4527.8 1681.63  4538.7 1683.79
  4557.6 1685.66  4581.7 1685.52  4624.6 1683.16    4647 1685.39  4936.3 1685.91
  4972.1 1684.86  4974.6 1677.22  4975.6 1676.72  5018.4 1677.22  5020.9 1680.68
    5033 1681.38  5065.2  1681.7  5183.4 1686.43  5485.9 1690.36  5713.1 1695.63
  5805.7 1699.61  5843.4 1703.94  5953.7 1709.95  6017.7 1712.18  6039.5 1714.63
#Mann= 5 ,-1 , 0
  4080.6     .05       0  4974.6     .07       0  5018.4     .12       0
  5485.9     .12       0  5805.7     .05       0
Bank Sta=4974.6,5018.4
XS Rating Curve= 0 ,0
Exp/Cntr=0.3,0.1

Type RM Length L Ch R = 1 ,22293   ,536,536,536
BEGIN DESCRIPTION:
Mapping XS 0aab3df4
END DESCRIPTION:
XS GIS Cut Line= 4
      1600435.67      6854986.66      1600667.43      6855043.95
       1602209.1      6855038.74      1602714.35      6854978.84
#Sta/Elev= 30
  3974.7 1699.98  4166.2 1699.84    4261 1698.64    4311 1699.71    4351 1695.65
    4401 1686.22    4441 1681.99    4521  1683.9    4621    1682    4771 1684.83
    4811 1685.09    4851 1683.77    4931 1685.35    4941 1683.78    4961 1683.44
    4971 1681.75  4979.1 1675.92  4980.1 1675.42  5022.9 1675.92    5031 1684.33
  5264.1 1686.27    5341  1686.8    5521 1690.86  5581.6 1690.22    5641 1690.68
  5779.9 1694.42  5933.4 1700.16  6002.7  1705.9  6133.6 1713.76  6263.9 1718.27
#Mann= 7 ,-1 , 0
  3974.7     .05       0  4979.1     .03       0  5022.9     .05       0
  5264.1    .075       0  5581.6     .05       0  5779.9     .12       0
  5933.4     .05       0
Bank Sta=4979.1,5022.9
XS Rating Curve= 0 ,0
Exp/Cntr=0.3,0.1

Type RM Length L Ch R = 1 ,21757   ,542,542,542
BEGIN DESCRIPTION:
Mapping XS ecb6127e
END DESCRIPTION:
XS GIS Cut Line= 3
      1600319.32      6855412.87      1600592.78      6855443.26
      1602346.29      6855456.28
#Sta/Elev= 30
    4064  1698.8    4246 1698.34  4391.4 1696.85  4401.4 1695.23  4411.4 1694.68
  4421.4 1692.76  4451.4 1684.31  4481.4 1680.53  4941.4 1685.36  4961.4 1682.91
  4969.5 1674.97  4970.5 1674.47  5013.3 1674.97  5021.4 1681.21  5031.4 1682.95
  5071.4 1683.57  5141.4 1683.23  5191.4 1684.94  5351.4 1684.78  5374.5 1685.91
  5391.4 1686.83  5507.8 1688.97  5711.4 1692.95  5731.4 1692.23  5741.4 1690.51
  5761.4 1690.04  5911.4 1698.18  5961.4 1698.43  6067.4 1701.88  6092.7 1703.59
#Mann= 6 ,-1 , 0
    4064     .05       0  4969.5     .05       0  5013.3     .05       0
  5374.5    .075       0  5507.8      .1       0  6067.4     .05       0
Bank Sta=4969.5,5013.3
XS Rating Curve= 0 ,0
Exp/Cntr=0.3,0.1

Type RM Length L Ch R = 1 ,21215   ,650,650,650
BEGIN DESCRIPTION:
Mapping XS 3c21e2a8
END DESCRIPTION:
XS GIS Cut Line= 3
      1600345.34       6855859.9      1600618.82      6856033.54
      1602068.52      6855907.66
#Sta/Elev= 30
  3987.4 1695.96  4093.6 1696.25  4347.7 1694.51  4377.8 1691.94    4428 1680.29
    4448 1679.43  4769.2 1683.23  4939.9 1683.59  4949.9 1680.75  4958.1 1675.35
  4959.1 1674.85  5001.9 1675.35  5008.2 1679.72  5013.2 1679.69  5020.2 1682.03
  5030.2 1683.17    5056 1682.78  5111.3 1683.41  5310.6 1686.58  5341.4 1687.12
  5371.5 1689.82  5391.6 1686.96  5401.6 1686.68  5522.1 1687.41  5609.4  1690.4
  5652.6 1691.07  5701.3 1695.47  5706.3 1694.38  5732.9 1698.01  5766.5 1699.08
#Mann= 7 ,-1 , 0
  3987.4     .05       0  4958.1     .05       0  5001.9     .05       0
    5056    .075       0  5111.3      .1       0  5310.6    .075       0
  5609.4     .05       0
Bank Sta=4958.1,5001.9
XS Rating Curve= 0 ,0
Exp/Cntr=0.3,0.1

Type RM Length L Ch R = 1 ,20565   ,722,722,722
BEGIN DESCRIPTION:
Mapping XS 14923597
END DESCRIPTION:
XS GIS Cut Line= 3
      1600254.23       6855868.6      1600718.65      6856207.15
      1601093.34      6856557.67
#Sta/Elev= 30
  4023.4  1696.2  4060.1 1695.86  4160.5 1696.27    4288 1694.81  4589.2 1692.65
  4617.5 1692.91  4695.2 1690.32  4730.3 1686.62  4758.7 1685.06    4766  1683.7
    4787 1682.71  4794.3 1681.14    4851  1679.2  4857.8  1679.4  4865.2 1678.47
  4886.2 1678.24  4914.5 1678.91  4949.7 1681.48    4957 1680.73  4971.2 1676.02
    4978 1675.18  5012.7 1674.63  5013.7 1674.13  5055.7 1674.13  5056.7 1674.63
    5063 1681.38  5070.3 1682.98  5084.5 1682.77  5091.3 1683.35  5111.2 1683.59
#Mann= 3 ,-1 , 0
  4023.4     .05       0  5012.7     .03       0  5056.7     .05       0
Bank Sta=5012.7,5056.7
XS Rating Curve= 0 ,0
Exp/Cntr=0.3,0.1

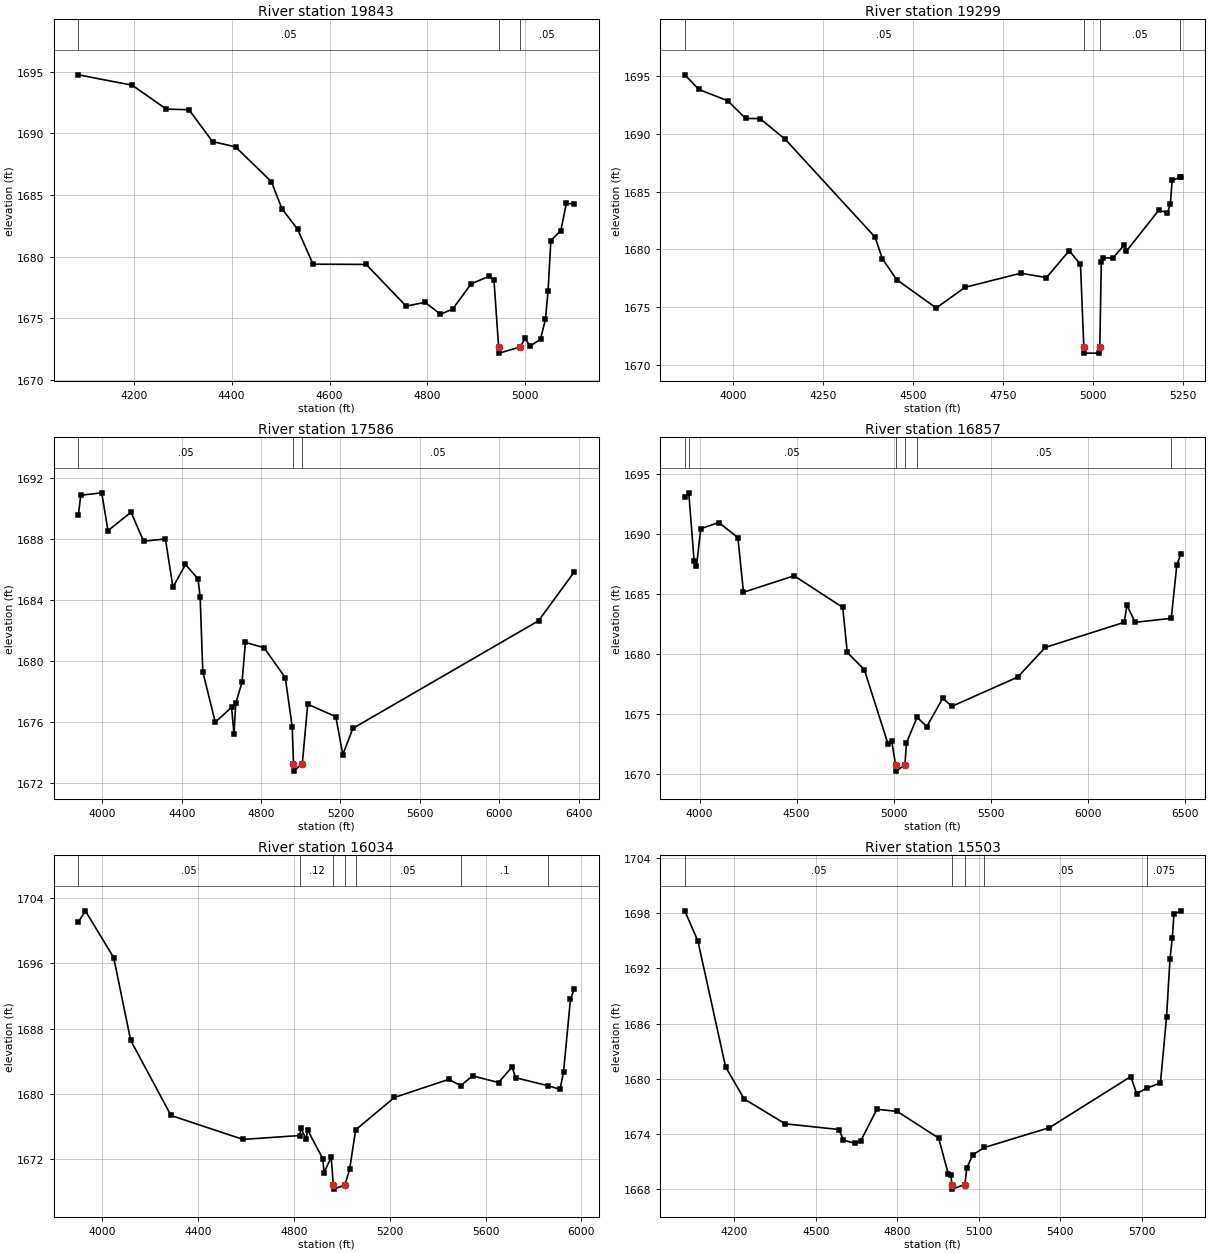
Type RM Length L Ch R = 1 ,19843   ,544,544,544
BEGIN DESCRIPTION:
Mapping XS df5b13bc
END DESCRIPTION:
XS GIS Cut Line= 2
      1600171.78      6856063.93      1600497.29       6857023.1
#Sta/Elev= 30
  4086.8 1694.74  4196.7  1693.9  4266.7 1691.96  4312.9 1691.91  4360.9 1689.33
  4407.9  1688.9  4481.2 1686.08  4502.9 1683.87  4534.6 1682.24  4566.3 1679.39
  4674.8 1679.37  4756.4 1675.99  4795.2  1676.3  4826.6 1675.33  4851.4 1675.75
  4889.4  1677.8    4926 1678.41  4935.9 1678.08  4945.4 1672.68  4946.4 1672.18
  4989.8 1672.68  4999.3 1673.39  5009.7 1672.75    5031 1673.31  5041.1 1674.93
  5046.4 1677.22  5052.1  1681.3  5072.5 1682.12  5083.8 1684.31  5099.7 1684.27
#Mann= 3 ,-1 , 0
  4086.8     .05       0  4945.4     .03       0  4989.8     .05       0
Bank Sta=4945.4,4989.8
XS Rating Curve= 0 ,0
Exp/Cntr=0.3,0.1

Type RM Length L Ch R = 1 ,19299   ,1713,1713,1713
BEGIN DESCRIPTION:
Mapping XS e47d68af
END DESCRIPTION:
XS GIS Cut Line= 3
      1599911.36      6855998.84      1599941.74      6856871.21
      1600097.99        6857353.
#Sta/Elev= 30
  3864.9 1695.12  3904.1 1693.85  3984.1 1692.88  4034.2 1691.34  4074.2 1691.33
  4144.2 1689.54  4394.4 1681.06  4414.4  1679.2  4454.4 1677.38  4564.5 1674.93
  4644.5 1676.72  4799.9 1677.94  4871.1 1677.56  4934.2 1679.89  4965.7 1678.71
    4975 1671.52    4976 1671.02  5018.4 1671.02  5019.4 1671.52  5023.7 1678.91
    5029 1679.29  5055.7 1679.23  5087.7 1680.41  5092.9 1679.83  5183.6  1683.4
  5207.5 1683.18  5215.6  1683.9  5220.8 1685.99  5242.6 1686.23  5244.3 1686.23
#Mann= 4 ,-1 , 0
  3864.9     .05       0    4975     .03       0  5019.4     .05       0
  5242.6    .075       0
Bank Sta=4975,5019.4
XS Rating Curve= 0 ,0
Exp/Cntr=0.3,0.1

Type RM Length L Ch R = 1 ,17586   ,729,729,729
BEGIN DESCRIPTION:
Rainy Creek 17023.936
END DESCRIPTION:
XS GIS Cut Line= 3
      1597843.36      6856212.44      1598796.53      6856535.37
      1599937.14       6857498.9
#Sta/Elev= 30
  3878.4 1689.58  3890.7 1690.89  3996.3 1691.05  4027.9 1688.56  4144.1 1689.78
  4207.4 1687.87  4317.4 1688.02  4355.3 1684.85  4418.6 1686.34    4482 1685.39
  4492.5 1684.18  4505.9 1679.29  4568.7 1675.97  4650.9 1676.96    4663 1675.21
    4672 1677.22  4703.7 1678.61  4720.6 1681.22  4814.8 1680.87  4921.6  1678.9
  4956.7 1675.67    4963 1673.26    4964 1672.76  5007.5 1673.26  5034.7 1677.16
  5176.4 1676.34  5211.6 1673.84  5262.2 1675.57  6198.3 1682.64  6377.9 1685.84
#Mann= 3 ,-1 , 0
  3878.4     .05       0    4963     .03       0  5007.5     .05       0
Bank Sta=4963,5007.5
XS Rating Curve= 0 ,0
Exp/Cntr=0.3,0.1

Type RM Length L Ch R = 1 ,16857   ,823,823,823
BEGIN DESCRIPTION:
Mapping XS b0ff0803
END DESCRIPTION:
XS GIS Cut Line= 4
      1597420.05      6856571.74      1598071.08      6856862.53
      1598839.31      6857192.39      1599620.26      6857821.49
#Sta/Elev= 30
  3924.2 1693.09  3944.6 1693.42  3972.2 1687.77  3984.4  1687.3  4006.3 1690.44
  4099.2 1690.95  4197.5 1689.69  4226.2 1685.15    4487 1686.52  4736.9 1683.89
  4760.5 1680.14  4848.3 1678.71  4970.7  1672.5  4988.8 1672.79  5009.5 1670.77
  5010.5 1670.27  5057.1 1670.77  5064.9 1672.62  5119.7 1674.75    5170 1673.98
  5251.5 1676.33  5298.7 1675.66  5637.4 1678.09  5779.7 1680.56    6186 1682.65
  6199.7 1684.07    6242 1682.65    6428 1682.98  6456.3 1687.39  6476.1  1688.3
#Mann= 6 ,-1 , 0
  3924.2      .1       0  3944.6     .05       0  5009.5     .05       0
  5057.1     .05       0  5119.7     .05       0    6428    .075       0
Bank Sta=5009.5,5057.1
XS Rating Curve= 0 ,0
Exp/Cntr=0.3,0.1

Type RM Length L Ch R = 1 ,16034   ,531,531,531
BEGIN DESCRIPTION:
Mapping XS 154798e0
END DESCRIPTION:
XS GIS Cut Line= 4
      1597227.05      6857358.27      1597859.03      6857563.14
      1598525.69       6857868.7      1599067.32      6858267.98
#Sta/Elev= 30
  3899.6 1701.06    3929 1702.45  4047.3 1696.71  4118.2 1686.56  4286.4 1677.34
  4587.3  1674.4  4824.9 1674.88  4828.3 1675.83  4851.3 1674.39  4856.8 1675.58
  4920.3 1672.04  4925.8 1670.33  4955.5 1672.22  4964.6  1668.8  4965.6  1668.3
  5012.4  1668.8  5032.5 1670.73  5057.7 1675.57  5219.5 1679.55  5445.6 1681.76
  5496.9 1681.01  5545.8  1682.2  5654.5 1681.38  5710.8  1683.3  5725.5 1681.97
  5861.8 1680.98  5911.3 1680.54    5926 1682.72  5954.9 1691.65  5970.2 1692.83
#Mann= 7 ,-1 , 0
  3899.6     .05       0  4824.9     .12       0  4964.6     .07       0
  5012.4     .12       0  5057.7     .05       0  5496.9      .1       0
  5861.8    .075       0
Bank Sta=4964.6,5012.4
XS Rating Curve= 0 ,0
Exp/Cntr=0.3,0.1

Type RM Length L Ch R = 1 ,15503   ,361,361,361
BEGIN DESCRIPTION:
Mapping XS 569e758a
END DESCRIPTION:
XS GIS Cut Line= 3
      1597105.53      6857660.35      1598109.03      6858240.23
      1598678.43      6858587.43
#Sta/Elev= 30
  4017.2 1698.24  4065.5 1694.95  4167.5 1681.29    4236 1677.81  4387.1 1675.12
  4585.2  1674.5    4601 1673.35  4644.1    1673  4665.6 1673.29  4724.5  1676.7
  4799.1 1676.47  4952.1 1673.57  4987.2 1669.71  4997.2 1669.58  5000.6 1668.53
  5001.6 1668.03  5048.4 1668.53    5056 1670.34  5077.6 1671.75  5120.7 1672.55
  5359.6  1674.7  5659.6 1680.25  5680.9 1678.41  5718.8 1678.98  5768.8 1679.58
  5791.3 1686.71  5803.9 1693.01  5812.6 1695.34  5818.5 1697.91  5843.1 1698.22
#Mann= 5 ,-1 , 0
  4017.2     .05       0  5000.6     .05       0  5048.4     .05       0
  5120.7     .05       0  5718.8    .075       0
Bank Sta=5000.6,5048.4
XS Rating Curve= 0 ,0
Exp/Cntr=0.3,0.1

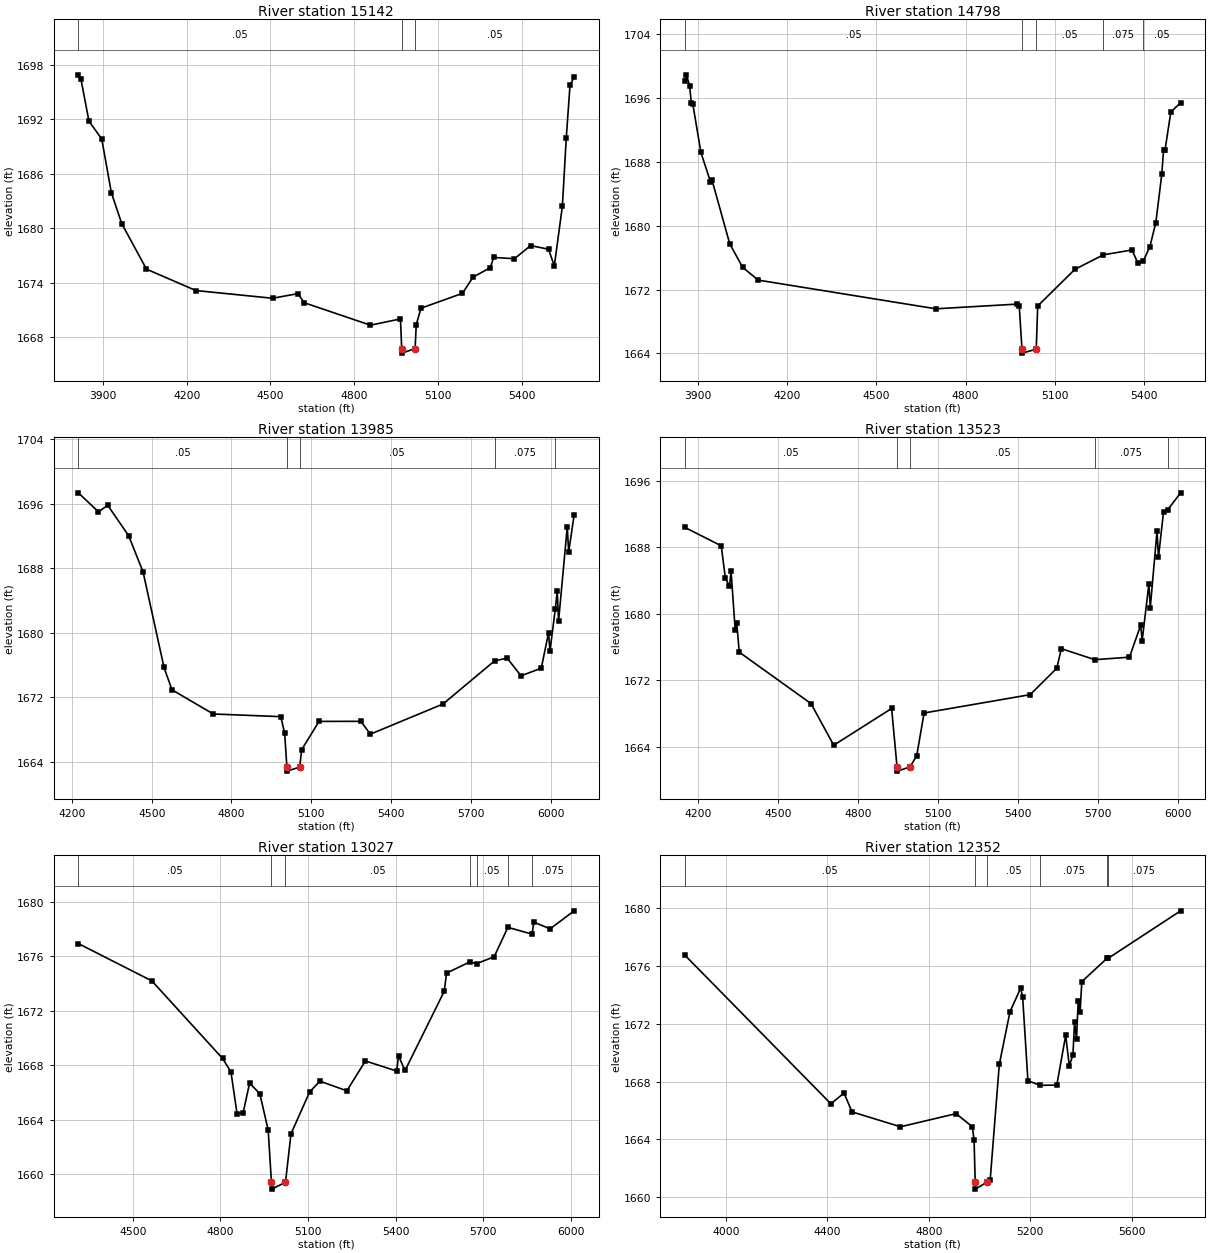
Type RM Length L Ch R = 1 ,15142   ,344,344,344
BEGIN DESCRIPTION:
Mapping XS 5b9074c2
END DESCRIPTION:
XS GIS Cut Line= 4
      1596841.68      6857948.57      1597365.97      6858240.23
      1598202.78      6858643.01      1598397.19      6858795.76
#Sta/Elev= 30
  3812.1 1696.87  3821.4  1696.4  3850.2 1691.77    3896 1689.82  3930.3 1683.92
  3967.8  1680.5  4056.2 1675.51  4233.1 1673.16    4508 1672.31  4598.5 1672.82
  4621.1 1671.82  4858.5 1669.35  4965.9 1670.04  4970.3 1666.78  4971.3 1666.28
  5018.3 1666.78  5022.4 1669.42  5039.5 1671.22  5187.8 1672.85  5226.1 1674.64
  5287.7 1675.67  5299.5  1676.8  5374.2 1676.66  5432.1  1678.1  5496.2  1677.7
    5517 1675.86  5545.9 1682.46  5559.8 1689.97  5573.1 1695.71    5588 1696.65
#Mann= 3 ,-1 , 0
  3812.1     .05       0  4970.3     .05       0  5018.3     .05       0
Bank Sta=4970.3,5018.3
XS Rating Curve= 0 ,0
Exp/Cntr=0.3,0.1

Type RM Length L Ch R = 1 ,14798   ,813,813,813
BEGIN DESCRIPTION:
Mapping XS 7013b02d
END DESCRIPTION:
XS GIS Cut Line= 5
      1596709.68      6858476.33      1597490.97      6858722.87
      1598025.69      6858872.17       1598261.8      6858865.23
      1598317.38      6858875.65
#Sta/Elev= 30
  3855.9 1698.12  3861.5 1698.94    3872 1697.58  3877.6 1695.46  3882.9 1695.25
    3910 1689.22  3942.3 1685.51  3947.6 1685.71    4007 1677.75  4050.2  1674.8
  4102.7 1673.19  4700.1 1669.59  4974.2 1670.18  4980.4    1670  4989.6 1664.53
  4990.6 1664.03  5037.6 1664.53  5042.5 1669.94  5167.3 1674.53  5263.1 1676.36
  5359.7 1676.97  5379.7  1675.3  5397.2 1675.55  5419.7 1677.39  5439.7  1680.4
  5459.7 1686.44  5465.7 1689.52  5470.7 1689.52  5490.2 1694.28  5523.1 1695.44
#Mann= 5 ,-1 , 0
  3855.9     .05       0  4989.6     .05       0  5037.6     .05       0
  5263.1    .075       0  5397.2     .05       0
Bank Sta=4989.6,5037.6
XS Rating Curve= 0 ,0
Exp/Cntr=0.3,0.1

Type RM Length L Ch R = 1 ,13985   ,462,462,462
BEGIN DESCRIPTION:
Mapping XS e5eb5fb5
END DESCRIPTION:
XS GIS Cut Line= 4
      1596532.66      6858674.27      1597629.86      6859104.81
      1597928.47      6858983.28      1598275.73      6858875.63
#Sta/Elev= 30
  4224.1 1697.34  4299.6 1694.99  4334.8 1695.79  4413.4 1692.02  4467.7 1687.52
  4546.3 1675.71  4576.1 1672.94  4731.5 1669.94  4985.5 1669.61  5000.1 1667.54
  5008.3 1663.36  5009.3 1662.86  5056.3 1663.36  5064.2 1665.53  5129.2 1669.02
  5286.5 1669.03  5322.3 1667.44  5595.2 1671.17  5789.5 1676.52  5836.7 1676.86
    5889 1674.67    5965 1675.61  5992.4    1680  5997.6 1677.72  6017.6  1682.9
    6025 1685.13  6030.2 1681.49  6062.8 1693.13    6068    1690  6088.7 1694.62
#Mann= 5 ,-1 , 0
  4224.1     .05       0  5008.3     .05       0  5056.3     .05       0
  5789.5    .075       0  6017.6     .05       0
Bank Sta=5008.3,5056.3
XS Rating Curve= 0 ,0
Exp/Cntr=0.3,0.1

Type RM Length L Ch R = 1 ,13523   ,496,496,496
BEGIN DESCRIPTION:
Mapping XS 9613f093
END DESCRIPTION:
XS GIS Cut Line= 4
       1596650.7      6859802.73      1597223.61      6859452.03
      1597713.19      6859104.81      1598265.27      6858903.42
#Sta/Elev= 30
  4150.8 1690.38  4287.5 1688.17    4303 1684.28  4318.4 1683.31  4324.3 1685.12
  4339.7 1678.11  4345.6 1678.86  4355.1  1675.4  4624.1 1669.23  4709.3 1664.23
  4926.5 1668.64  4946.8 1661.62  4947.8 1661.12  4994.9 1661.62  5020.4 1662.94
  5048.3  1668.1    5446  1670.3  5545.9 1673.47    5563 1675.82  5688.7  1674.5
  5818.5  1674.8  5860.7 1678.64  5866.1 1676.78  5891.3 1683.56  5896.6 1680.76
  5921.9 1689.95  5927.2 1686.78  5946.2 1692.21  5962.1  1692.5  6010.4 1694.53
#Mann= 5 ,-1 , 0
  4150.8     .05       0  4946.8     .05       0  4994.9     .05       0
  5688.7    .075       0  5962.1     .05       0
Bank Sta=4946.8,4994.9
XS Rating Curve= 0 ,0
Exp/Cntr=0.3,0.1

Type RM Length L Ch R = 1 ,13027   ,675,675,675
BEGIN DESCRIPTION:
Mapping XS 36eb34a4
END DESCRIPTION:
XS GIS Cut Line= 4
      1597122.88      6860181.23      1597515.28      6859854.81
      1597883.33      6859545.78      1598430.98      6859098.65
#Sta/Elev= 30
  4313.8 1676.93  4565.7 1674.19  4807.9  1668.5  4836.5 1667.51  4857.3 1664.46
  4878.1 1664.51  4900.2 1666.69  4935.4 1665.92    4964 1663.24  4975.1 1659.42
  4976.1 1658.92  5023.2 1659.42    5042 1662.97  5105.8 1666.04  5140.9 1666.84
  5233.3 1666.13    5297 1668.32  5403.9 1667.58  5410.4 1668.69  5432.6 1667.62
  5566.9 1673.43  5574.8 1674.76  5654.1 1675.58    5678 1675.46  5737.8 1675.96
  5784.9 1678.12  5867.7 1677.62  5873.5  1678.5  5929.5 1678.01  6011.8 1679.33
#Mann= 7 ,-1 , 0
  4313.8     .05       0  4975.1     .03       0  5023.2     .05       0
  5654.1      .1       0    5678     .05       0  5784.9      .1       0
  5867.7    .075       0
Bank Sta=4975.1,5023.2
XS Rating Curve= 0 ,0
Exp/Cntr=0.3,0.1

Type RM Length L Ch R = 1 ,12352   ,513,513,513
BEGIN DESCRIPTION:
Mapping XS 37f4e0f8
END DESCRIPTION:
XS GIS Cut Line= 3
       1597129.9      6860236.74      1597907.64      6859972.87
      1598760.84      6859223.72
#Sta/Elev= 30
  3836.9 1676.74  4413.3 1666.46  4465.3  1667.2  4496.9  1665.9  4688.1 1664.87
  4907.5 1665.78  4971.8 1664.87  4978.5 1663.94  4982.9 1661.06  4983.9 1660.56
    5031 1661.06  5042.1 1661.21  5078.1 1669.19  5120.4 1672.84  5162.6 1674.46
  5170.2 1673.83    5191 1668.05  5239.6 1667.74  5304.9 1667.75    5340 1671.19
  5354.2  1669.1  5368.5 1669.82  5375.1 1672.14  5382.7 1670.93  5389.4 1673.59
  5396.9 1672.78  5403.6  1674.9  5503.2 1676.52  5507.8 1676.52  5793.6  1679.8
#Mann= 6 ,-1 , 0
  3836.9     .05       0  4982.9     .03       0    5031     .05       0
  5239.6    .075       0  5503.2      .1       0  5507.8    .075       0
Bank Sta=4982.9,5031
XS Rating Curve= 0 ,0
Exp/Cntr=0.3,0.1

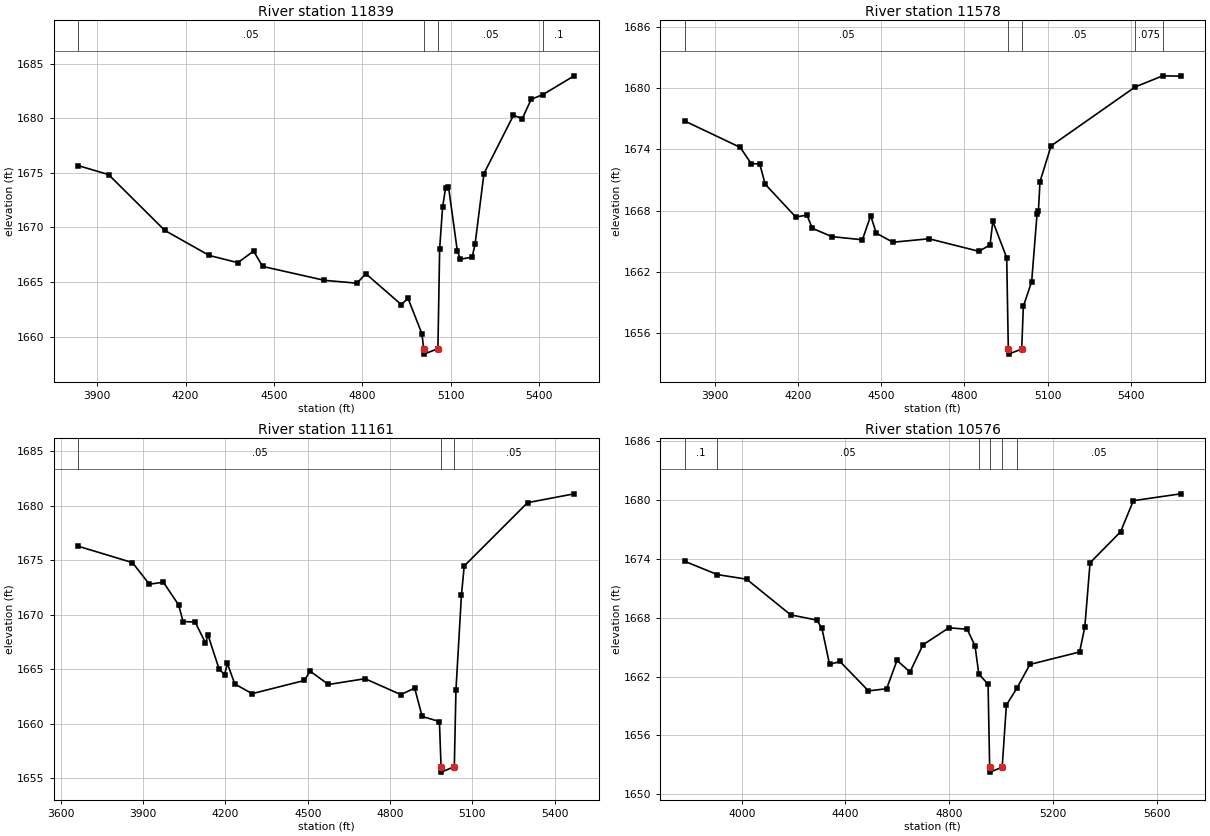
Type RM Length L Ch R = 1 ,11839   ,261,261,261
BEGIN DESCRIPTION:
Mapping XS fafbbf6d
END DESCRIPTION:
XS GIS Cut Line= 3
      1597154.13      6860274.95       1597636.8      6860215.92
       1598830.6      6860153.46
#Sta/Elev= 30
  3836.4 1675.66    3939 1674.84  4129.4 1669.73  4280.6 1667.43  4377.3 1666.77
    4431 1667.83  4461.1 1666.43  4671.3 1665.15  4781.5 1664.89  4811.5 1665.76
  4931.7 1662.93  4954.7  1663.5  5001.8 1660.25  5007.7 1658.89  5008.7 1658.39
    5056 1658.89  5061.9 1668.06  5071.9 1671.86  5081.9 1673.59  5091.9 1673.73
    5122 1667.81    5132 1667.09    5172 1667.27    5182 1668.46  5212.1 1674.93
  5312.2 1680.27  5342.3 1679.97  5372.3 1681.74    5412 1682.17  5518.1 1683.89
#Mann= 4 ,-1 , 0
  3836.4     .05       0  5007.7     .03       0    5056     .05       0
    5412      .1       0
Bank Sta=5007.7,5056
XS Rating Curve= 0 ,0
Exp/Cntr=0.3,0.1

Type RM Length L Ch R = 1 ,11578   ,417,417,417
BEGIN DESCRIPTION:
Mapping XS 119aa1f2
END DESCRIPTION:
XS GIS Cut Line= 2
      1597095.15      6860427.73      1598881.71      6860393.04
#Sta/Elev= 30
    3792 1676.77  3991.9 1674.19  4031.2  1672.6  4061.9 1672.57  4081.9 1670.58
  4191.9 1667.37  4231.9 1667.56  4251.9 1666.26    4322 1665.45    4432 1665.14
    4462  1667.5    4482 1665.79    4542  1664.9    4672 1665.24  4852.1 1664.01
  4892.1 1664.64  4902.1 1666.94  4952.1 1663.38  4957.9 1654.44  4958.9 1653.94
  5006.2 1654.44  5012.1 1658.62  5042.1 1661.05  5061.4 1667.65  5066.4 1667.97
  5072.1 1670.84  5112.1 1674.34  5415.1 1680.11  5514.2  1681.2  5578.9 1681.17
#Mann= 5 ,-1 , 0
    3792     .05       0  4957.9     .05       0  5006.2     .05       0
  5415.1    .075       0  5514.2     .05       0
Bank Sta=4957.9,5006.2
XS Rating Curve= 0 ,0
Exp/Cntr=0.3,0.1

Type RM Length L Ch R = 1 ,11161   ,585,585,585
BEGIN DESCRIPTION:
Mapping XS 2bbf9141
END DESCRIPTION:
XS GIS Cut Line= 3
      1597032.62      6860792.31      1597445.83      6860886.06
      1598824.27      6860764.54
#Sta/Elev= 30
  3663.8 1676.28  3861.1 1674.78  3922.6  1672.8  3973.9 1672.98  4029.4  1670.9
  4045.6 1669.37  4089.6 1669.33  4127.1 1667.42  4136.9  1668.1    4177 1665.01
  4197.1 1664.51  4207.1 1665.53  4234.2 1663.64  4297.5 1662.76  4488.2 1663.97
  4508.3 1664.83  4575.7  1663.6  4709.1 1664.13  4839.6 1662.67  4889.8 1663.27
  4917.2 1660.67  4980.1  1660.2  4986.1 1656.06  4987.1 1655.56  5034.4 1656.06
  5040.4  1663.1  5060.4  1671.8  5070.5 1674.47  5301.4 1680.28  5471.3 1681.09
#Mann= 3 ,-1 , 0
  3663.8     .05       0  4986.1     .05       0  5034.4     .05       0
Bank Sta=4986.1,5034.4
XS Rating Curve= 0 ,0
Exp/Cntr=0.3,0.1

Type RM Length L Ch R = 1 ,10576   ,943,943,943
BEGIN DESCRIPTION:
Mapping XS a945fc27
END DESCRIPTION:
XS GIS Cut Line= 4
      1597136.83      6861393.01        1598175.      6861382.59
      1598716.66      6861313.14      1598920.76      6861057.16
#Sta/Elev= 30
  3780.6 1673.77  3905.8 1672.42  4018.8 1671.95  4188.8 1668.31  4288.8 1667.78
  4308.8 1666.99  4338.8 1663.25  4378.8 1663.55  4488.8 1660.55  4558.8 1660.77
  4598.8 1663.66  4648.8 1662.48  4698.8 1665.25  4798.8 1666.99  4869.2 1666.84
  4899.5 1665.16  4914.2 1662.27  4949.9 1661.23    4956 1652.76    4957 1652.26
  5004.3 1652.76  5020.5  1659.1  5062.2 1660.88  5111.2 1663.25  5302.7 1664.52
  5322.9 1667.07  5343.1 1673.62  5460.6 1676.78  5510.2 1679.96  5692.3 1680.66
#Mann= 6 ,-1 , 0
  3780.6      .1       0  3905.8     .05       0  4914.2     .12       0
    4956     .07       0  5004.3     .12       0  5062.2     .05       0
Bank Sta=4956,5004.3
XS Rating Curve= 0 ,0
Exp/Cntr=0.3,0.1