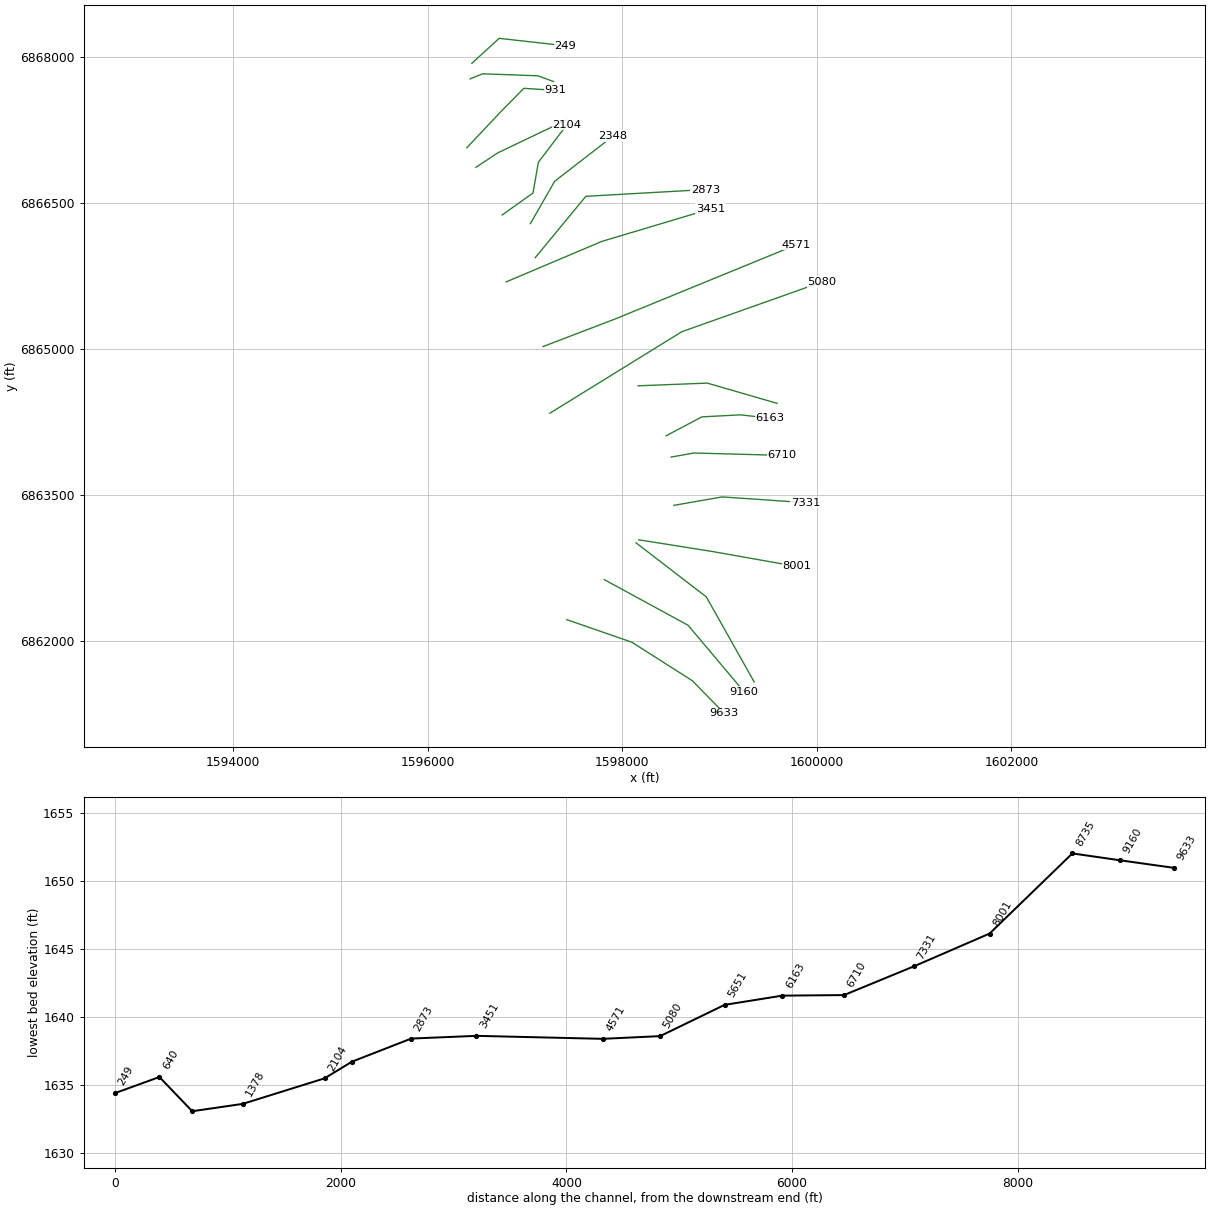
HEC-RAS study Rainy Creek.prj: Rainy Creek Base Level Engineering

--- Rainy Creek.g01 (geometry) --- (continued)

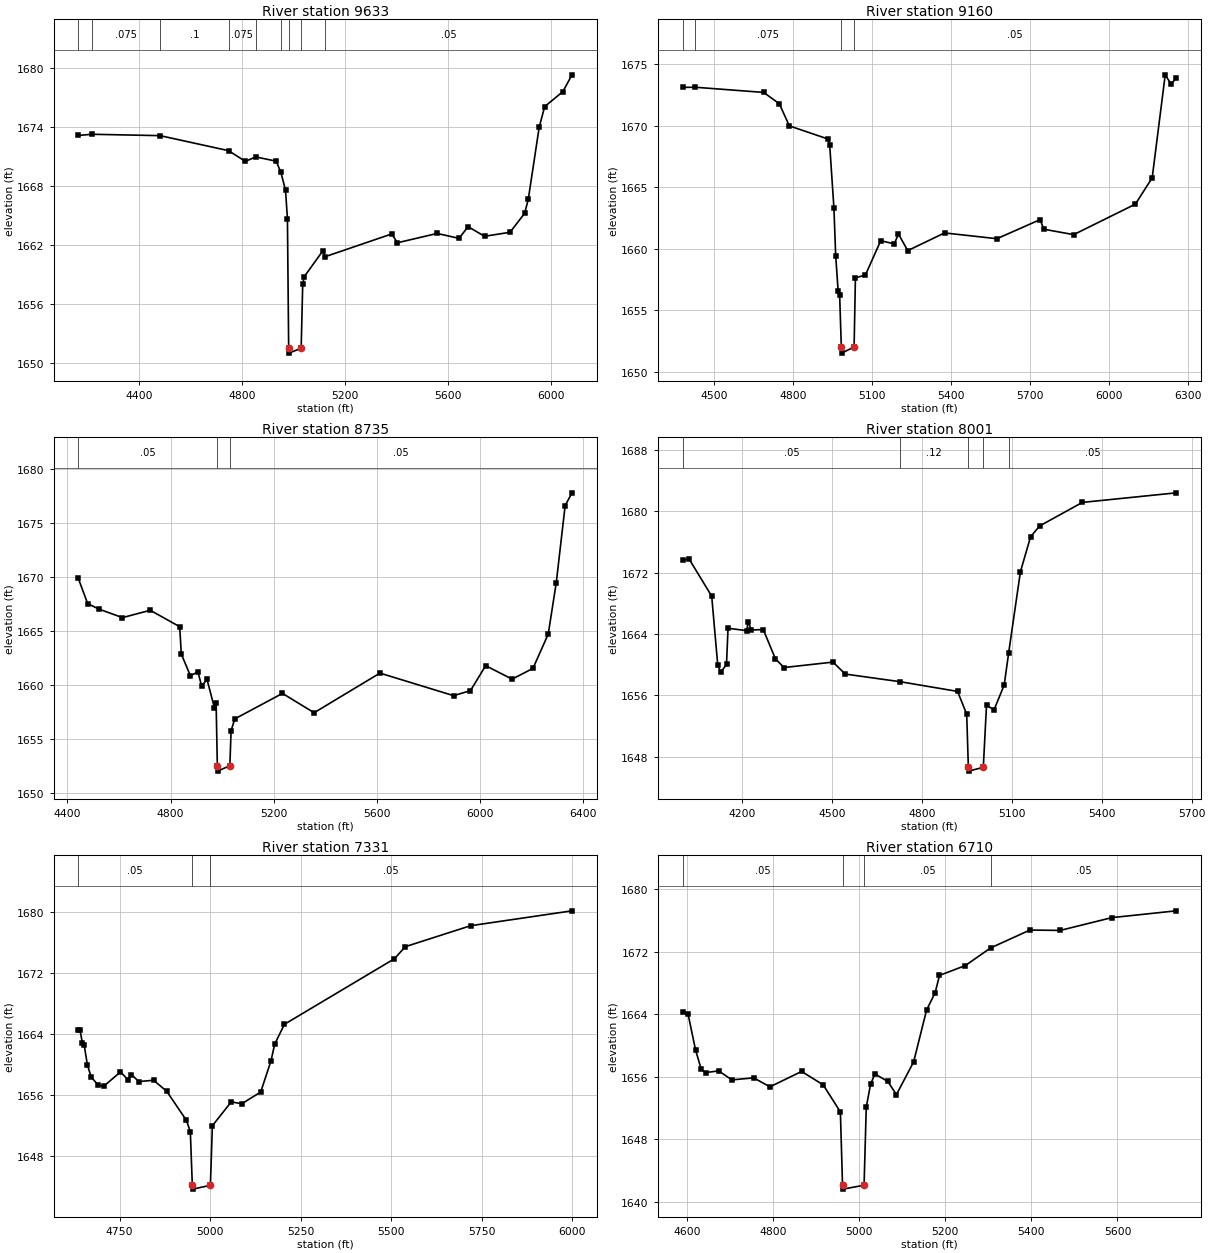
Type RM Length L Ch R = 1 ,9633    ,473,473,473
BEGIN DESCRIPTION:
Mapping XS 8d4d27a0
END DESCRIPTION:
XS GIS Cut Line= 4
      1597428.45      6862215.93      1598098.61      6861983.28
      1598720.14      6861587.45      1599048.82      6861251.85
#Sta/Elev= 30
  4164.2 1673.15  4218.3 1673.27  4481.7 1673.13  4747.5  1671.6  4812.5 1670.51
  4853.3 1670.96  4932.2 1670.53  4950.7 1669.38  4968.6 1667.56    4976 1664.66
  4980.8 1651.46  4981.8 1650.96  5029.3 1651.46  5035.3    1658  5041.4 1658.76
  5114.2 1661.42  5121.1 1660.78  5380.9 1663.11  5402.8 1662.21  5556.9 1663.16
  5641.8 1662.66  5677.2 1663.85  5740.8 1662.87  5839.8 1663.28  5896.4 1665.21
  5910.5 1666.63  5952.9 1673.98  5974.1 1676.09  6044.8 1677.62  6080.2 1679.33
#Mann= 9 ,-1 , 0
  4164.2      .1       0  4218.3    .075       0  4481.7      .1       0
  4747.5    .075       0  4853.3     .05       0  4950.7     .12       0
  4980.8     .07       0  5029.3     .12       0  5121.1     .05       0
Bank Sta=4980.8,5029.3
XS Rating Curve= 0 ,0
Exp/Cntr=0.3,0.1

Type RM Length L Ch R = 1 ,9160    ,425,425,425
BEGIN DESCRIPTION:
Rainy Creek 9043.257
END DESCRIPTION:
XS GIS Cut Line= 3
      1597814.71      6862626.97      1598675.87       6862158.2
      1599251.11      6861475.52
#Sta/Elev= 30
  4381.4 1673.11    4430 1673.12  4689.1  1672.7  4748.5 1671.78  4786.5 1669.98
  4933.7 1668.91  4939.6 1668.44  4955.6 1663.32  4962.4 1659.43  4971.7 1656.53
  4977.4  1656.2  4983.7 1652.01  4984.7 1651.51  5032.2 1652.01  5037.2 1657.63
  5075.2 1657.86  5133.2 1660.65  5184.5 1660.39  5200.6 1661.19  5235.6 1659.84
  5375.2 1661.28    5574 1660.81  5737.8 1662.36  5752.1 1661.58  5865.2 1661.14
  6099.3 1663.62  6163.1 1665.76  6212.5 1674.13  6234.5 1673.38  6254.6 1673.86
#Mann= 4 ,-1 , 0
  4381.4      .1       0    4430    .075       0  4983.7     .07       0
  5032.2     .05       0
Bank Sta=4983.7,5032.2
XS Rating Curve= 0 ,0
Exp/Cntr=0.3,0.1

Type RM Length L Ch R = 1 ,8735    ,734,734,734
BEGIN DESCRIPTION:
Mapping XS 86a0bb3e
END DESCRIPTION:
XS GIS Cut Line= 3
      1598141.15      6863005.42      1598863.37      6862449.86
      1599356.41      6861574.89
#Sta/Elev= 30
  4441.8 1669.89  4478.4 1667.54  4521.9 1667.03  4613.4 1666.24  4721.2 1666.92
  4835.4  1665.4  4841.7 1662.86  4877.1 1660.85  4906.1 1661.22  4920.6  1659.9
  4941.4 1660.52  4970.4 1657.86  4976.7 1658.32  4981.5 1652.52  4982.5 1652.02
    5030 1652.52  5034.8 1655.77  5049.3 1656.86  5234.1 1659.22  5356.9 1657.43
  5612.2  1661.1  5898.2 1659.01  5963.5 1659.48  6022.5 1661.79    6125 1660.54
    6206 1661.54  6265.2 1664.72  6296.3 1669.48  6330.8 1676.62  6357.3  1677.8
#Mann= 3 ,-1 , 0
  4441.8     .05       0  4981.5     .05       0    5030     .05       0
Bank Sta=4981.5,5030
XS Rating Curve= 0 ,0
Exp/Cntr=0.3,0.1

Type RM Length L Ch R = 1 ,8001    ,670,670,670
BEGIN DESCRIPTION:
Mapping XS a582c9eb
END DESCRIPTION:
XS GIS Cut Line= 3
      1598168.94      6863036.66      1598932.81      6862915.14
      1599793.89      6862762.37
#Sta/Elev= 30
  4000.9 1673.61  4023.2 1673.74  4098.2 1668.92  4118.4 1659.92  4128.5 1659.01
  4147.6 1660.03  4152.7 1664.74  4214.9 1664.43    4220 1665.62  4229.8 1664.51
  4270.3 1664.57  4310.8 1660.76  4339.3 1659.62  4503.2 1660.33  4543.7 1658.77
  4727.7 1657.77  4918.8 1656.51  4949.3 1653.54  4954.8 1646.62  4955.8 1646.12
  5004.7 1646.62  5015.4 1654.69  5040.7 1654.12  5074.5 1657.36  5089.5 1661.58
  5128.5 1672.09  5162.5 1676.67    5193 1678.08  5335.2 1681.14  5648.9 1682.39
#Mann= 5 ,-1 , 0
  4000.9     .05       0  4727.7     .12       0  4954.8     .07       0
  5004.7     .12       0  5089.5     .05       0
Bank Sta=4954.8,5004.7
XS Rating Curve= 0 ,0
Exp/Cntr=0.3,0.1

Type RM Length L Ch R = 1 ,7331    ,621,621,621
BEGIN DESCRIPTION:
Mapping XS 45bf717e
END DESCRIPTION:
XS GIS Cut Line= 3
      1598530.06      6863390.84      1599026.56      6863477.64
       1599884.2      6863418.61
#Sta/Elev= 30
  4635.6 1664.56  4640.6 1664.56  4646.9 1662.91    4652  1662.6  4660.9    1660
  4671.1 1658.43  4691.4  1657.3  4706.4 1657.21  4752.3 1659.07  4772.6 1658.08
  4782.7 1658.72    4803 1657.81  4843.6 1657.98  4879.8 1656.55  4934.2 1652.74
  4945.2 1651.25  4950.7 1644.21  4951.7 1643.71  5000.6 1644.21  5006.1 1652.02
  5058.3 1655.15  5087.3  1654.9  5139.6 1656.44  5168.1 1660.55  5178.2 1662.72
  5205.2 1665.32  5508.9 1673.91    5539 1675.49  5719.4 1678.24  5999.3 1680.19
#Mann= 3 ,-1 , 0
  4635.6     .05       0  4950.7     .05       0  5000.6     .05       0
Bank Sta=4950.7,5000.6
XS Rating Curve= 0 ,0
Exp/Cntr=0.3,0.1

Type RM Length L Ch R = 1 ,6710    ,547,547,547
BEGIN DESCRIPTION:
Mapping XS 2b7b7b4c
END DESCRIPTION:
XS GIS Cut Line= 3
      1598502.26      6863887.36      1598738.37      6863929.03
      1599644.59      6863904.72
#Sta/Elev= 30
  4590.3 1664.27  4603.2 1663.98  4620.6 1659.38  4633.7 1656.94  4643.8 1656.52
  4674.3 1656.73  4704.8 1655.58  4755.5 1655.84  4793.2 1654.69  4866.7 1656.66
  4916.7 1654.95  4956.7 1651.48  4961.7 1642.09  4962.7 1641.59  5011.7 1642.09
  5016.8 1652.08  5026.8 1655.03  5036.8 1656.34  5066.8 1655.38  5086.8 1653.69
  5126.8 1657.89  5156.8 1664.52  5176.8 1666.76  5186.8 1668.96  5246.8 1670.22
  5305.5 1672.48  5396.9 1674.77  5466.9 1674.72    5587 1676.36  5736.6 1677.23
#Mann= 4 ,-1 , 0
  4590.3     .05       0  4961.7     .05       0  5011.7     .05       0
  5305.5     .05       0
Bank Sta=4961.7,5011.7
XS Rating Curve= 0 ,0
Exp/Cntr=0.3,0.1

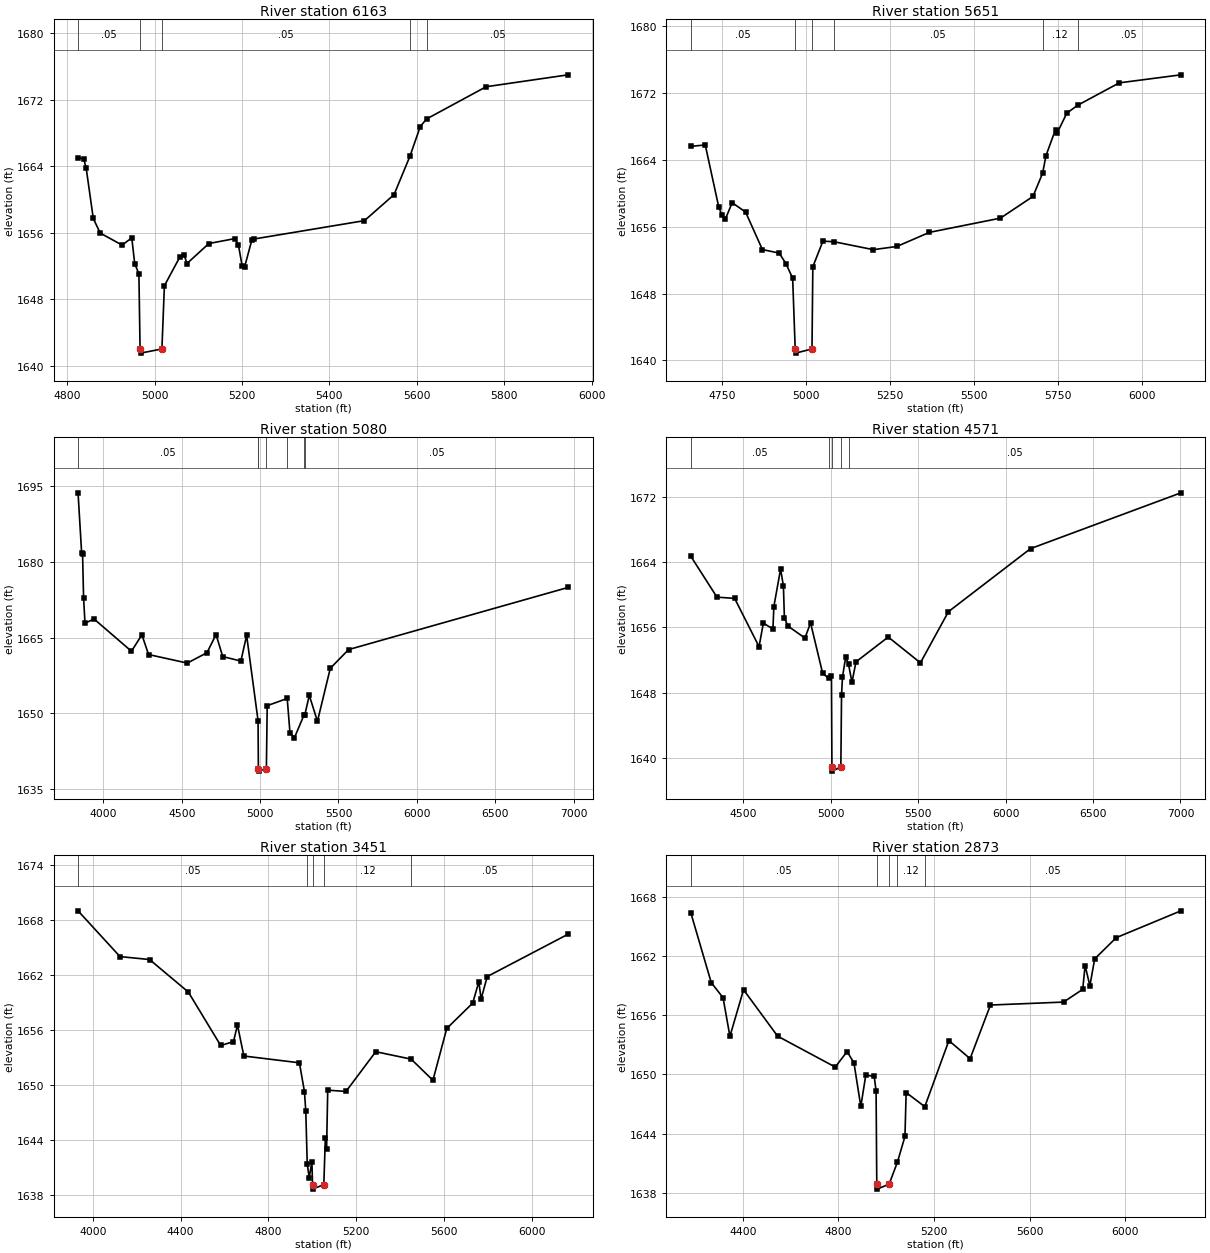
Type RM Length L Ch R = 1 ,6163    ,512,512,512
BEGIN DESCRIPTION:
Mapping XS 784db680
END DESCRIPTION:
XS GIS Cut Line= 4
       1598450.2      6864106.13      1598818.23      6864300.56
      1599214.06      6864321.39      1599521.52      6864286.85
#Sta/Elev= 30
  4824.5 1665.04  4837.4 1664.87  4843.1 1663.78  4859.4 1657.72  4875.2 1655.97
  4925.5 1654.52  4947.5  1655.4  4954.3 1652.27  4963.8 1651.09  4966.5 1642.05
  4967.5 1641.55  5016.5 1642.05  5022.2 1649.64  5057.5 1653.09  5067.4 1653.33
  5073.9 1652.31    5124 1654.71    5184 1655.31  5191.8  1654.5  5200.3 1651.99
    5206 1651.94  5222.3 1655.11    5228 1655.26  5480.2 1657.46  5547.9 1660.58
  5584.3 1665.19    5608 1668.76  5622.4 1669.67  5758.8 1673.54  5946.5 1674.97
#Mann= 5 ,-1 , 0
  4824.5     .05       0  4966.5     .05       0  5016.5     .05       0
  5584.3     .12       0  5622.4     .05       0
Bank Sta=4966.5,5016.5
XS Rating Curve= 0 ,0
Exp/Cntr=0.3,0.1

Type RM Length L Ch R = 1 ,5651    ,571,571,571
BEGIN DESCRIPTION:
Mapping XS 1a4e26d0
END DESCRIPTION:
XS GIS Cut Line= 3
      1598162.02        6864620.      1598873.78      6864647.78
      1599591.24      6864439.82
#Sta/Elev= 30
  4657.1 1665.61  4700.1 1665.78  4740.1 1658.38  4750.2 1657.34  4760.2 1656.93
  4780.2 1658.87  4820.2 1657.75  4870.2 1653.26  4920.3 1652.84  4940.3 1651.58
  4960.3 1649.84  4967.9 1641.37  4968.9 1640.87  5017.9 1641.37  5020.4  1651.2
  5050.4 1654.27  5083.2  1654.2  5200.5 1653.25  5270.5 1653.63  5367.5 1655.32
  5578.9 1657.02  5675.9 1659.62  5704.6  1662.4  5714.7 1664.51    5743 1667.62
  5748.2 1667.23  5776.6 1669.58  5808.6 1670.52  5932.9 1673.21  6116.4 1674.17
#Mann= 6 ,-1 , 0
  4657.1     .05       0  4967.9     .07       0  5017.9     .05       0
  5083.2     .05       0  5704.6     .12       0  5808.6     .05       0
Bank Sta=4967.9,5017.9
XS Rating Curve= 0 ,0
Exp/Cntr=0.3,0.1

Type RM Length L Ch R = 1 ,5080    ,509,509,509
BEGIN DESCRIPTION:
Rainy Creek 5146.037
END DESCRIPTION:
XS GIS Cut Line= 3
      1597255.04      6864338.03       1598612.5      6865176.43
      1600054.98      6865687.99
#Sta/Elev= 30
  3838.9 1693.64  3861.9 1681.71  3867.8 1681.49  3874.1 1672.92  3883.2 1667.85
  3941.1 1668.67  4179.7 1662.29  4246.2 1665.55  4288.7 1661.64  4535.8 1659.95
  4661.2    1662  4719.1  1665.6  4761.7 1661.24  4877.5 1660.35  4914.2 1665.43
  4987.1 1648.56  4989.1 1639.07  4990.1 1638.57  5040.2 1639.07  5045.4 1651.52
  5173.1 1652.95  5190.5 1646.19  5219.2 1645.19  5279.1 1649.59  5285.9 1649.77
  5313.8 1653.56  5365.9 1648.43  5447.7 1658.91  5564.4 1662.62  6964.9 1674.92
#Mann= 7 ,-1 , 0
  3838.9     .05       0  4987.1     .12       0  4989.1     .07       0
  5040.2     .12       0  5173.1     .05       0  5279.1     .12       0
  5285.9     .05       0
Bank Sta=4989.1,5040.2
XS Rating Curve= 0 ,0
Exp/Cntr=0.3,0.1

Type RM Length L Ch R = 1 ,4571    ,1120,1120,1120
BEGIN DESCRIPTION:
Rainy Creek 4571.355
END DESCRIPTION:
XS GIS Cut Line= 3
      1597185.38      6865023.64       1597933.1      6865309.77
      1599786.08      6866068.77
#Sta/Elev= 30
  4199.4 1664.71  4348.9  1659.7    4450 1659.55  4589.6 1653.63  4614.3 1656.52
    4669 1655.79  4674.4 1658.55  4712.9 1663.16  4729.1 1661.02  4734.5 1657.19
  4753.8 1656.17  4852.1 1654.69  4884.3 1656.54  4953.5 1650.35  4988.6 1649.75
  5003.7 1650.06  5006.4 1638.87  5007.4 1638.37  5057.5 1638.87  5061.4 1647.72
  5066.9 1649.93  5085.4 1652.37  5101.5 1651.47  5120.9 1649.26  5144.2 1651.77
  5328.4 1654.81  5512.6 1651.65  5672.8 1657.92  6142.5 1665.65  7002.4 1672.49
#Mann= 5 ,-1 , 0
  4199.4     .05       0  4988.6     .12       0  5006.4     .07       0
  5057.5     .12       0  5101.5     .05       0
Bank Sta=5006.4,5057.5
XS Rating Curve= 0 ,0
Exp/Cntr=0.3,0.1

Type RM Length L Ch R = 1 ,3451    ,578,578,578
BEGIN DESCRIPTION:
Rainy Creek 3451.405
END DESCRIPTION:
XS GIS Cut Line= 3
      1596804.99      6865687.99      1597787.77      6866104.24
      1598904.98        6866438.
#Sta/Elev= 30
  3932.7 1668.99  4123.9 1663.99  4258.6 1663.67  4435.2 1660.12  4582.7 1654.28
  4640.9  1654.7  4659.2 1656.51  4688.3 1653.13  4941.4 1652.39  4964.4 1649.25
  4970.5 1647.09  4977.1 1641.34  4986.1 1639.84  4998.4 1641.59  5001.3 1639.09
  5002.3 1638.59  5052.6 1639.09  5059.7 1644.18  5065.2 1642.99  5070.5  1649.4
  5153.7 1649.26  5289.3  1653.6  5450.6 1652.79  5549.8 1650.48  5612.9 1656.14
  5731.1 1658.91    5759 1661.24  5769.4 1659.36  5797.4 1661.81    6166 1666.44
#Mann= 5 ,-1 , 0
  3932.7     .05       0  4977.1     .12       0  5001.3     .07       0
  5052.6     .12       0  5450.6     .05       0
Bank Sta=5001.3,5052.6
XS Rating Curve= 0 ,0
Exp/Cntr=0.3,0.1

Type RM Length L Ch R = 1 ,2873    ,525,525,525
BEGIN DESCRIPTION:
Rainy Creek 2873.161
END DESCRIPTION:
XS GIS Cut Line= 3
        1597105.        6865938.      1597625.15      6866568.42
      1598854.99        6866638.
#Sta/Elev= 30
  4182.7 1666.37    4268 1659.31  4317.5 1657.77  4346.2 1653.86  4403.1 1658.58
  4545.6 1653.88  4786.6 1650.75  4836.1 1652.32  4864.8 1651.17  4893.4 1646.76
  4914.3 1649.94  4949.4  1649.8  4957.3 1648.34  4960.2 1638.89  4961.2 1638.39
  5011.8 1638.89  5046.6 1641.13    5078 1643.72    5083 1648.17    5161 1646.74
  5261.7 1653.43  5350.4  1651.6  5435.4 1657.03    5741 1657.33  5821.2 1658.62
  5831.2 1661.03  5851.2 1658.98  5871.2  1661.7  5961.3 1663.85  6231.8 1666.57
#Mann= 5 ,-1 , 0
  4182.7     .05       0  4960.2     .05       0  5011.8     .05       0
  5046.6     .12       0    5161     .05       0
Bank Sta=4960.2,5011.8
XS Rating Curve= 0 ,0
Exp/Cntr=0.3,0.1

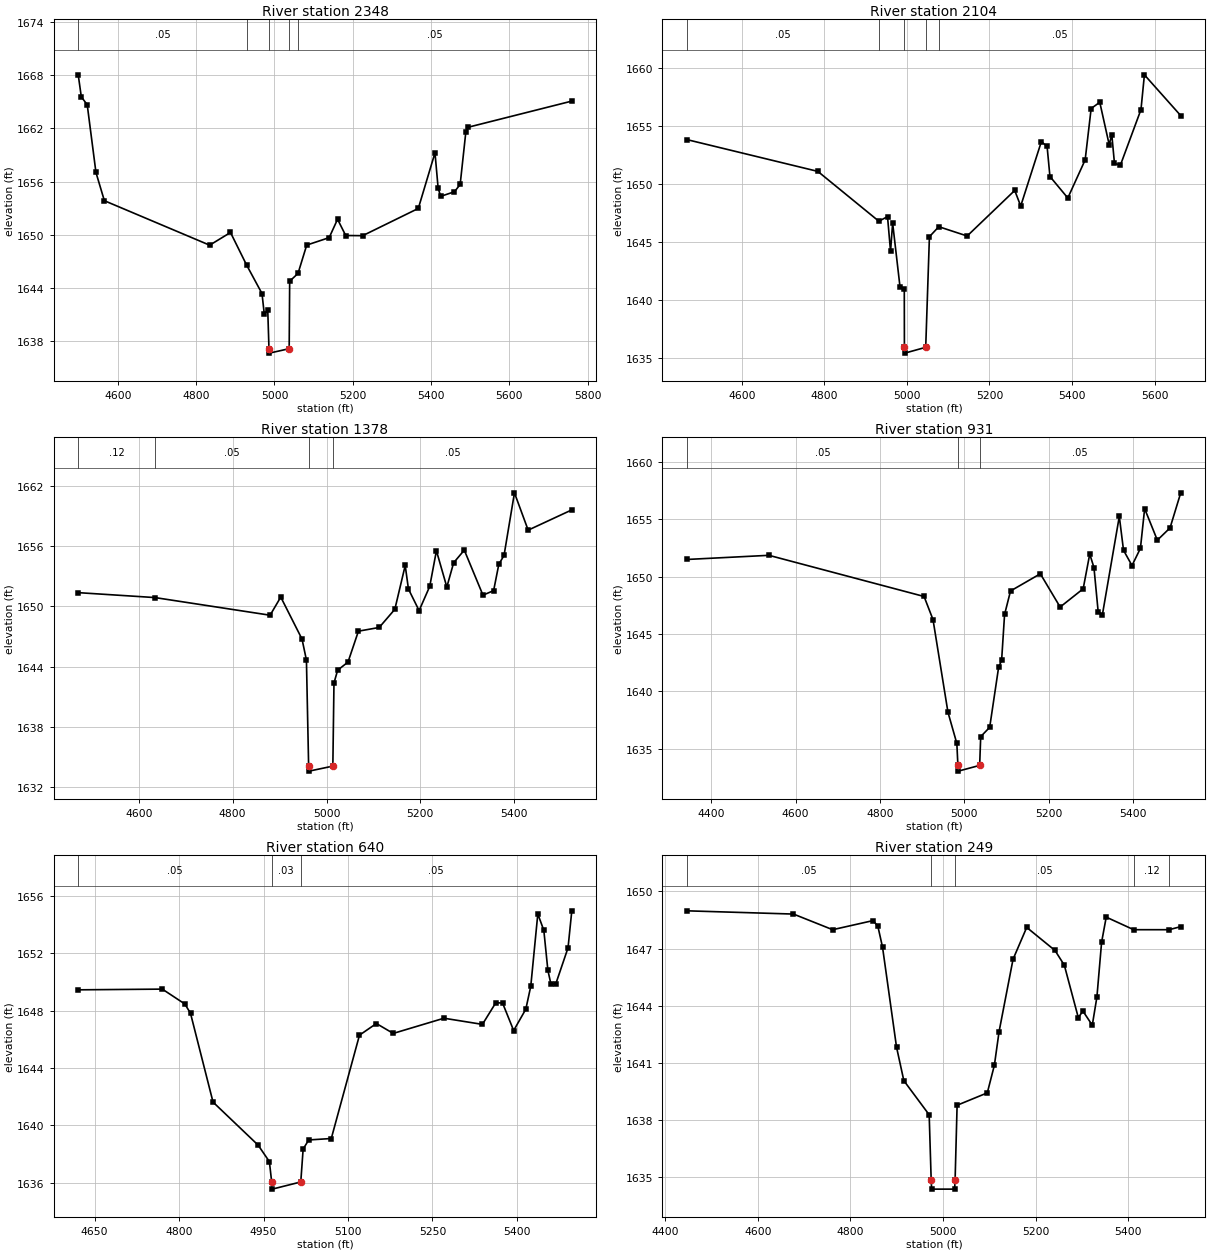
Type RM Length L Ch R = 1 ,2348    ,244,244,244
BEGIN DESCRIPTION:
Rainy Creek 2348.182
END DESCRIPTION:
XS GIS Cut Line= 3
      1597055.01      6866288.02      1597304.54      6866722.93
        1597905.        6867188.
#Sta/Elev= 30
  4498.6 1668.04  4506.5 1665.56  4521.6 1664.67  4543.9 1657.04  4565.4 1653.86
  4834.4 1648.85  4887.6 1650.28  4928.8 1646.61  4968.1  1643.4  4973.9 1641.09
  4982.8  1641.5  4985.9 1637.19  4986.9 1636.69  5037.5 1637.19  5038.8 1644.79
  5060.1 1645.67  5082.3 1648.86  5139.7  1649.7  5161.1 1651.77  5181.9 1649.94
  5225.3 1649.92  5367.4 1652.99    5410 1659.26    5418 1655.29  5424.5 1654.35
  5459.8 1654.87  5474.3 1655.69  5488.8  1661.6  5495.1 1662.14  5759.5 1665.08
#Mann= 5 ,-1 , 0
  4498.6     .05       0  4928.8     .12       0  4985.9     .07       0
  5037.5     .12       0  5060.1     .05       0
Bank Sta=4985.9,5037.5
XS Rating Curve= 0 ,0
Exp/Cntr=0.3,0.1

Type RM Length L Ch R = 1 ,2104    ,726,726,726
BEGIN DESCRIPTION:
Mapping XS 112c5f1e
END DESCRIPTION:
XS GIS Cut Line= 4
      1596765.55      6866376.79      1597081.54      6866602.49
      1597137.09      6866918.46      1597431.12      6867305.89
#Sta/Elev= 30
  4467.9 1653.83  4784.4  1651.1  4932.3 1646.81  4953.2 1647.21  4960.5 1644.22
  4965.6 1646.65  4983.6 1641.11  4993.8 1641.02  4994.1 1635.96  4995.1 1635.46
  5045.7 1635.96  5054.7 1645.48  5077.4 1646.34  5146.1 1645.54  5261.3 1649.46
  5275.8 1648.12  5325.8 1653.66  5339.7 1653.25  5346.6 1650.66  5389.9 1648.81
  5431.9 1652.09  5446.4 1656.51  5467.3 1657.05  5490.1  1653.4  5496.4 1654.26
  5502.9 1651.79  5517.2 1651.63  5567.1 1656.42  5575.4 1659.41  5663.4  1655.9
#Mann= 5 ,-1 , 0
  4467.9     .05       0  4932.3     .12       0  4994.1     .07       0
  5045.7     .12       0  5077.4     .05       0
Bank Sta=4994.1,5045.7
XS Rating Curve= 0 ,0
Exp/Cntr=0.3,0.1

Type RM Length L Ch R = 1 ,1378    ,447,447,447
BEGIN DESCRIPTION:
Mapping XS f4b7c79a
END DESCRIPTION:
XS GIS Cut Line= 3
      1596494.73      6866866.37      1596720.43      6867015.68
      1597425.27      6867352.48
#Sta/Elev= 30
  4470.9 1651.37  4634.3 1650.88  4879.8 1649.12  4902.5 1650.93  4947.8 1646.74
  4957.2 1644.65  4961.9 1634.08  4962.9 1633.58  5013.5 1634.08  5015.9 1642.36
  5023.7 1643.64  5045.8 1644.45    5068 1647.53  5112.3  1647.9  5145.6 1649.71
  5167.7 1654.08  5174.6 1651.73  5197.3 1649.58    5220    1652  5234.2 1655.55
  5256.4 1651.93  5270.9 1654.35  5293.6 1655.61  5333.4 1651.12  5356.1 1651.57
  5367.2  1654.2  5378.3 1655.08  5400.5 1661.32  5429.7  1657.6  5522.7 1659.62
#Mann= 4 ,-1 , 0
  4470.9     .12       0  4634.3     .05       0  4961.9     .05       0
  5013.5     .05       0
Bank Sta=4961.9,5013.5
XS Rating Curve= 0 ,0
Exp/Cntr=0.3,0.1

Type RM Length L Ch R = 1 ,931     ,291,291,291
BEGIN DESCRIPTION:
Mapping XS 0816e4a8
END DESCRIPTION:
XS GIS Cut Line= 4
      1596400.95      6867067.73      1596755.15      6867442.77
      1596987.79      6867678.88       1597310.4      6867658.06
#Sta/Elev= 30
  4342.8  1651.5  4536.7 1651.86  4904.7 1648.27  4925.9 1646.25  4961.3 1638.18
  4982.4 1635.45  4984.9 1633.54  4985.9 1633.04  5036.5 1633.54    5039 1636.05
  5060.3 1636.86  5081.4 1642.08  5088.6 1642.71  5095.6  1646.7  5109.7 1648.75
  5180.4 1650.25  5227.4 1647.35    5282 1648.94  5297.6 1651.97  5307.6 1650.79
  5317.6 1646.93  5327.6 1646.68  5367.7 1655.25  5377.7  1652.3  5397.8 1650.97
  5417.8 1652.47  5427.8 1655.93  5457.9 1653.18    5488 1654.25  5513.4 1657.31
#Mann= 3 ,-1 , 0
  4342.8     .05       0  4984.9     .05       0  5036.5     .05       0
Bank Sta=4984.9,5036.5
XS Rating Curve= 0 ,0
Exp/Cntr=0.3,0.1

Type RM Length L Ch R = 1 ,640     ,391,391,391
BEGIN DESCRIPTION:
Mapping XS 594ffd36
END DESCRIPTION:
XS GIS Cut Line= 4
      1596435.72      6867776.11      1596564.18      6867828.18
      1597133.62      6867807.35      1597291.64      6867748.95
#Sta/Elev= 30
  4620.8 1649.46  4770.2 1649.51  4810.3 1648.47  4820.3 1647.82  4860.3 1641.63
  4940.4 1638.63  4960.4 1637.48  4964.5 1636.06  4965.5 1635.56  5016.2 1636.06
  5020.4 1638.36  5030.4 1638.99  5070.4 1639.09  5120.5  1646.3  5150.5 1647.11
  5180.5 1646.42  5270.6 1647.48  5338.9 1647.05  5362.7 1648.56  5374.7 1648.54
  5394.4 1646.62    5416 1648.11  5424.8 1649.71  5437.3 1654.75    5448 1653.61
  5455.2 1650.82  5460.6 1649.87  5469.3 1649.88    5491 1652.39  5497.7 1654.97
#Mann= 3 ,-1 , 0
  4620.8     .05       0  4964.5     .03       0  5016.2     .05       0
Bank Sta=4964.5,5016.2
XS Rating Curve= 0 ,0
Exp/Cntr=0.3,0.1

Type RM Length L Ch R = 1 ,249     ,0,0,0
BEGIN DESCRIPTION:
Rainy Creek 1777.314
END DESCRIPTION:
XS GIS Cut Line= 3
      1596453.04       6867935.8      1596734.31      6868192.77
      1597414.85      6868116.38
#Sta/Elev= 30
  4447.4 1648.98    4677 1648.81  4761.6 1647.99  4849.2 1648.47  4859.3 1648.16
  4869.3 1647.07  4899.5 1641.83  4915.3 1640.07    4970 1638.28  4974.3 1634.88
  4975.3 1634.38    5025 1634.38    5026 1634.88  5030.3 1638.78  5095.5 1639.43
  5110.8 1640.88  5120.9 1642.64  5151.1 1646.44  5180.6 1648.11  5241.7  1646.9
  5261.8 1646.13    5292 1643.38    5302 1643.72  5322.2 1642.98  5332.2 1644.46
  5342.3 1647.33  5352.3 1648.65  5411.6 1647.99    5488 1647.99  5513.2 1648.15
#Mann= 5 ,-1 , 0
  4447.4     .05       0  4974.3     .03       0    5026     .05       0
  5411.6     .12       0    5488     .05       0
Bank Sta=4974.3,5026
XS Rating Curve= 0 ,0
Exp/Cntr=0.3,0.1

Chan Stop Cuts=-1
Use User Specified Reach Order=0
Composite Channel Slope=5