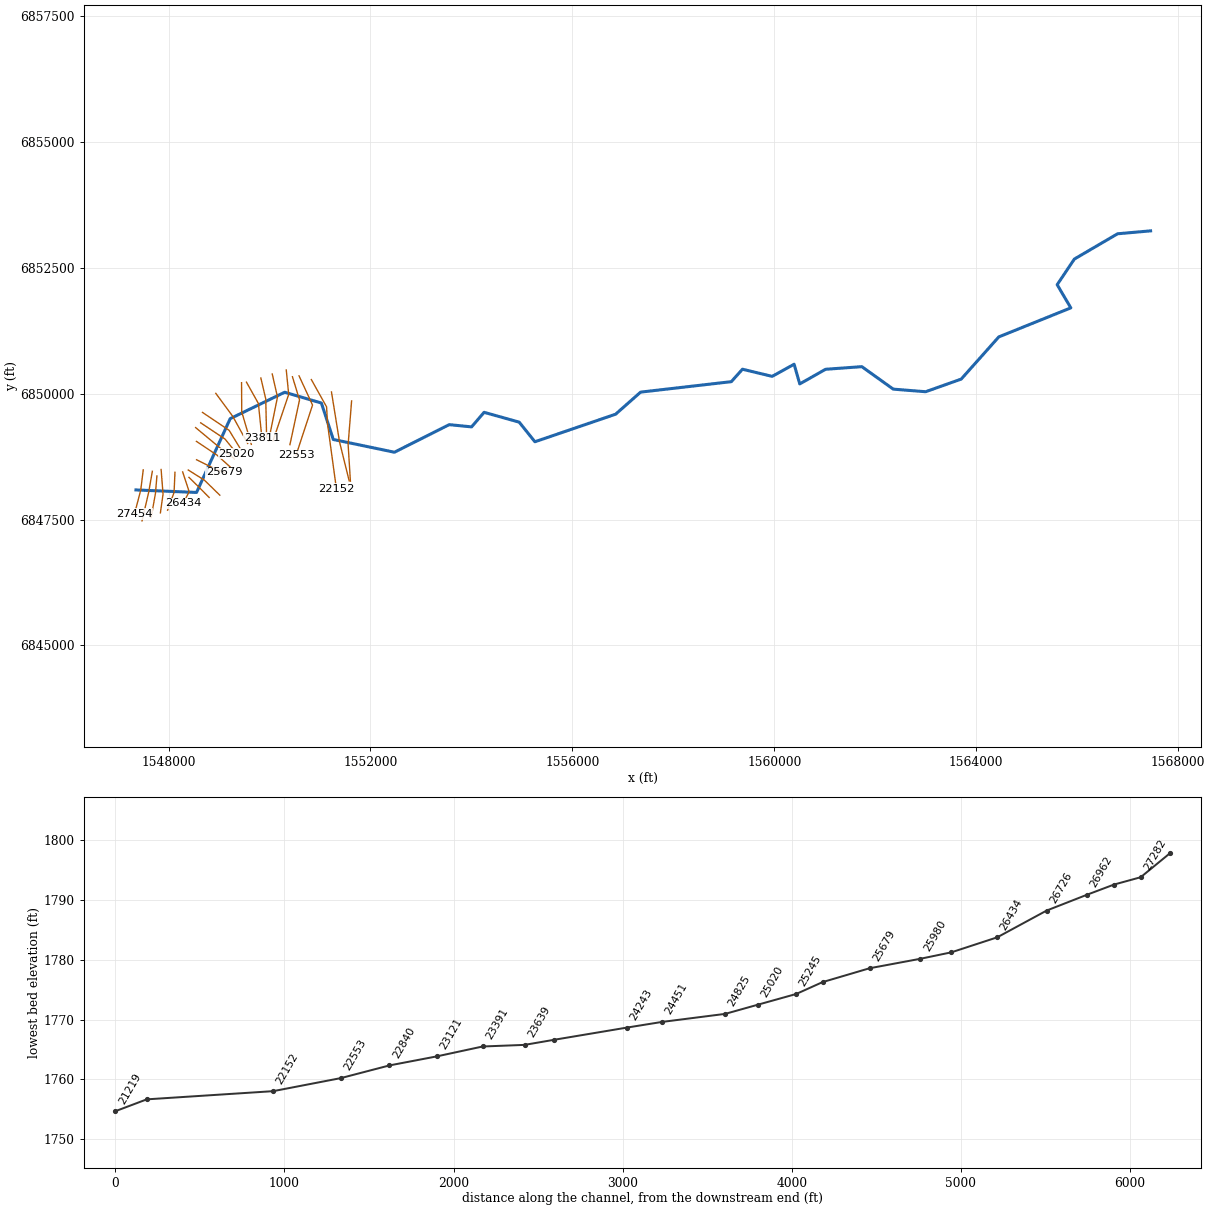
--- Tributary 1 to Little Elm Cr.prj (project) ---

Proj Title=Tributary 1 to Little Elm Cr Base Level Engineering
Current Plan=p01
Default Exp/Contr=0.3,0.1
English Units
Geom File=g01
Flow File=f01
Plan File=p01
Y Axis Title=Elevation
X Axis Title(PF)=Main Channel Distance
X Axis Title(XS)=Station
BEGIN DESCRIPTION:
Tributary 1 to Little Elm Cr
END DESCRIPTION:
DSS Export Rating Curves= 0
DSS Export Rating Curve Sorted= 0
DSS Export Volume Flow Curves= 0
DXF OffsetX= 0
DXF OffsetY= 0
DXF ScaleX= 1
DXF ScaleY= 10

--- Tributary 1 to Little Elm Cr.p01 (plan) ---

Plan Title=Multiple Run
Program Version=4.10
Short Identifier=Multiple
Geom File=g01
Flow File=f01
Subcritical Flow
K Sum by GR= 0
Std Step Tol= 0.01
Critical Tol= 0.01
Num of Std Step Trials= 20
Max Error Tol= 0.3
Flow Tol Ratio= 0.001
Split Flow NTrial= 30
Split Flow Tol= 0.02
Split Flow Ratio= 0.02
Log Output Level= 0
Friction Slope Method= 1
Unsteady Friction Slope Method= 2
Unsteady Bridges Friction Slope Method= 1
Parabolic Critical Depth
Global Vel Dist= 1 , 1 , 1
Global Log Level= 0
CheckData=True
Encroach Param=-1 ,0,0, 0
BEGIN DESCRIPTION:
Multiple Run
END DESCRIPTION:
Computation Interval=1HOUR
Output Interval=1HOUR
Run HTab= 0
Run UNet= 0
Run PostProcess= 0
Run WQNet= 0
UNET Theta= 1
UNET Theta Warmup= 1
UNET ZTol= 0.02
UNET ZSATol= 0.05
UNET MxIter= 20
UNET MaxInSteps= 0
UNET DtIC= 0
UNET DtMin= 0
UNET MaxCRTS= 20
UNET WFStab= 2
UNET SFStab= 1
UNET WFX= 1
UNET SFX= 1
UNET DSS MLevel= 4
UNET DZMax Abort= 100
UNET Convert EG Bridges= 0
UNET Use Existing IB Tables=-1
UNET Froude Reduction=False
UNET Froude Limit= 1
UNET Froude Power= 10
UNET Time Slicing=0,0, 5
UNET Junction Losses=0
Instantaneous Interval=1HOUR
Write IC File= 0
Write IC File at Sim End=0
Echo Input=False
Echo Parameters=False
Echo Output=False
Write Detailed= 0
WQ AD Non Conservative
WQ ULTIMATE=-1
WQ Max Comp Step=1HOUR
WQ Output Interval=15MIN
WQ Output Selected Increments= 0
WQ Output face flow=0
WQ Output face velocity=0
WQ Output face area=0
WQ Output face dispersion=0
WQ Output cell volume=0
WQ Output cell surface area=0
WQ Output cell continuity=0
WQ Output cumulative cell continuity=0
WQ Output face conc=0
WQ Output face dconc_dx=0
WQ Output face courant=0
WQ Output face peclet=0
WQ Output face adv mass=0
WQ Output face disp mass=0
WQ Output cell mass=0
WQ Output cell source sink temp=0
WQ Output cell source sink nsm=0
WQ Output MaxMinRange=-1
WQ Daily Max Min Mean=-1
WQ Daily Range=0
WQ Daily Time=0
WQ Create Restart=0
WQ Fixed Restart=0
WQ System Summary=0
WQ Use Fixed Temperature=0
Sorting and Armoring Iterations= 10
XS Update Threshold= 0.02
Hydraulics Update Threshold= 0.02
Energy Slope Method= 1
Volume Change Method= 0
XS Weighting Method= 0
Number of US Weighted Cross Sections= 1
Number of DS Weighted Cross Sections= 1
Upstream XS Weight=0.25
Main XS Weight=0.5
Downstream XS Weight=0.25
Number of DS XS's Weighted with US Boundary= 1
Upstream Boundary Weight= 1
Weight of XSs Associated with US Boundary= 0
Number of US XS's Weighted with DS Boundary= 1
Downstream Boundary Weight= 0.5
Weight of XSs Associated with DS Boundary= 0.5
Sediment Output Level= 4
Mass or Volume Output= 0
Output Increment Type= 1
Profile and TS Output Increment= 10
XS Output Flag= 0
XS Output Increment= 10
Disregard all LS=0
Disregard all Conn=0
Disregard all Breaches=0
Disregard all Pumps=0

--- Tributary 1 to Little Elm Cr.f01 (steady flow) ---

Flow Title=Multiple
Number of Profiles=7
Profile Names=10-year,25-year,50-year,1pct_min,100-year,1pct_plu,500-year
River Rch & RM= Tributary 1 to L,Reach-1,27454
      45      56      64      46      74     101      98
River Rch & RM= Tributary 1 to L,Reach-1,26163
     182     247     299     225     360     496     530
River Rch & RM= Tributary 1 to L,Reach-1,18421
     221     302     368     278     446     614     663
River Rch & RM= Tributary 1 to L,Reach-1,16579
     265     365     448     340     545     750     819
River Rch & RM= Tributary 1 to L,Reach-1,13794
     323     451     556     425     681     936    1030
River Rch & RM= Tributary 1 to L,Reach-1,13302
     345     481     593     452     725     998    1100
River Rch & RM= Tributary 1 to L,Reach-1,9466
     406     569     705     539     864    1190    1320
River Rch & RM= Tributary 1 to L,Reach-1,4790
     453     635     787     602     965    1330    1470
Boundary for River Rch & Prof#=Tributary 1 to L,Reach-1,1
Up Type=0
Dn Type=3
Dn Slope=0.005
Boundary for River Rch & Prof#=Tributary 1 to L,Reach-1,2
Up Type=0
Dn Type=3
Dn Slope=0.005
Boundary for River Rch & Prof#=Tributary 1 to L,Reach-1,3
Up Type=0
Dn Type=3
Dn Slope=0.005
Boundary for River Rch & Prof#=Tributary 1 to L,Reach-1,4
Up Type=0
Dn Type=3
Dn Slope=0.005
Boundary for River Rch & Prof#=Tributary 1 to L,Reach-1,5
Up Type=0
Dn Type=3
Dn Slope=0.005
Boundary for River Rch & Prof#=Tributary 1 to L,Reach-1,6
Up Type=0
Dn Type=3
Dn Slope=0.005
Boundary for River Rch & Prof#=Tributary 1 to L,Reach-1,7
Up Type=0
Dn Type=3
Dn Slope=0.005

--- Tributary 1 to Little Elm Cr.g01 (geometry) ---

Geom Title=Existing Conditions

River Reach=Tributary 1 to L,Reach-1
Reach XY= 30
      1547355.00      6848088.00      1548555.00      6848038.00
      1549221.18      6849504.70      1550301.60      6850030.22
      1551028.52      6849815.31      1551263.10      6849091.35
      1552475.18      6848837.57      1553560.85      6849385.94
      1554003.72      6849341.37      1554251.66      6849631.04
      1554947.09      6849435.10      1555258.20      6849045.58
      1556857.38      6849593.70      1557352.57      6850032.48
      1559149.07      6850240.24      1559370.02      6850487.68
      1559958.13      6850345.50      1560393.51      6850586.53
      1560504.96      6850195.52      1561016.88      6850486.47
      1561734.88      6850538.46      1562356.50      6850091.62
      1562999.07      6850040.24      1563703.50      6850291.61
      1564448.54      6851130.26      1565875.09      6851707.37
      1565604.57      6852167.62      1565945.00      6852677.37
      1566801.67      6853179.99      1567455.00      6853238.00

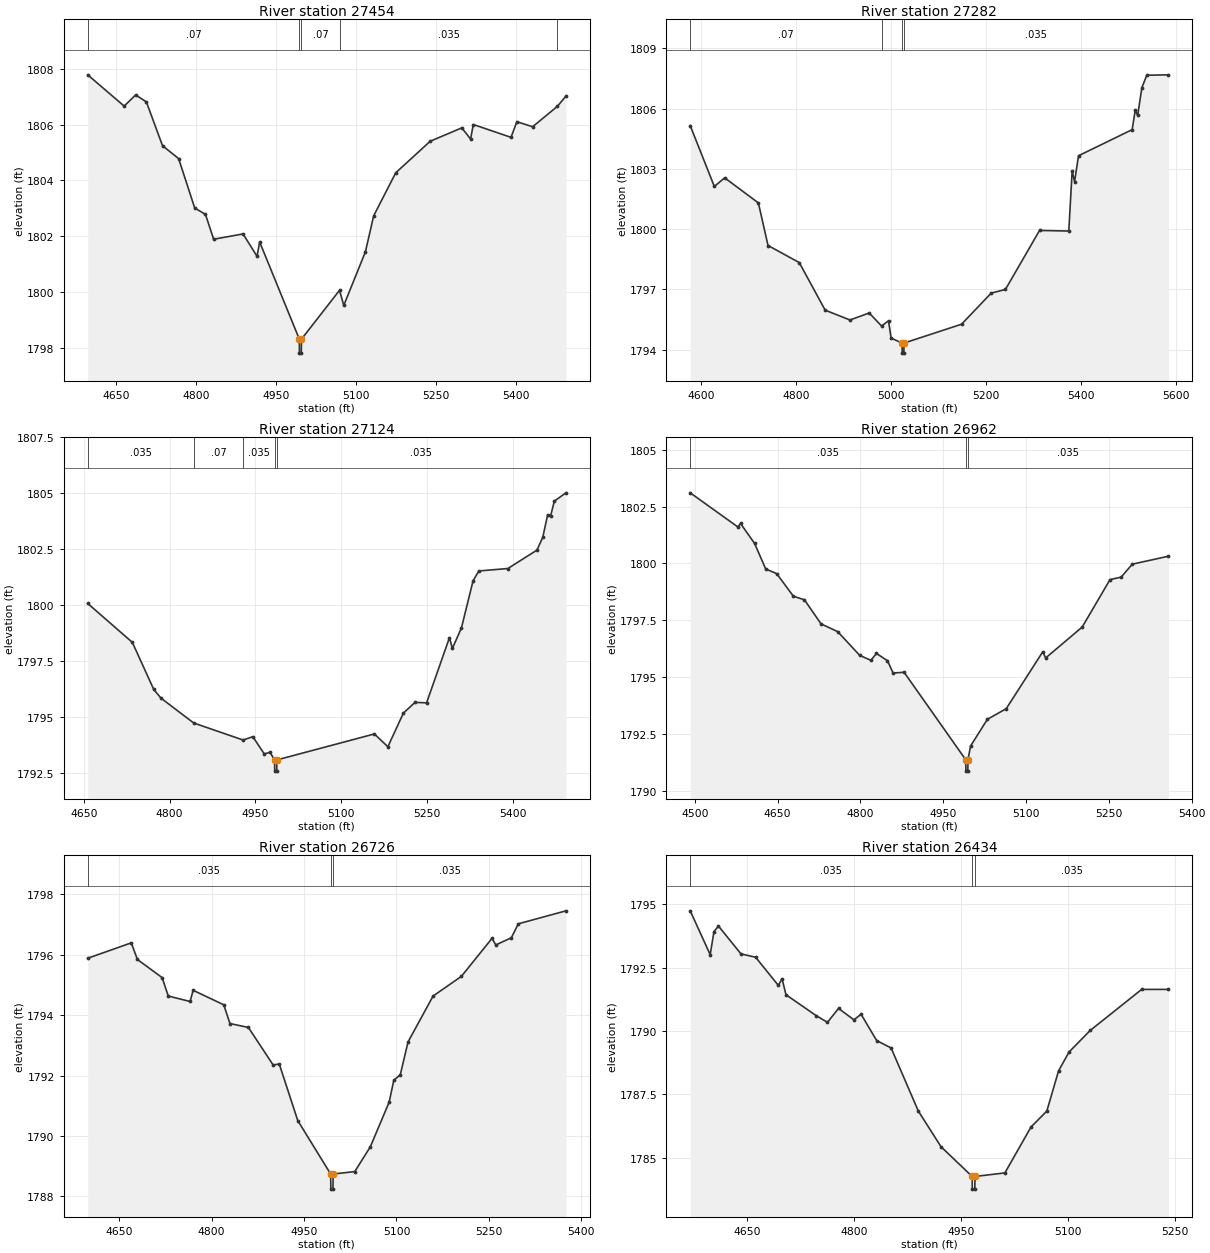
Type RM Length L Ch R = 1,27454,172,172,172
BEGIN DESCRIPTION:
Tributary 1 to Little Elm Cr 27453.598
END DESCRIPTION:
XS GIS Cut Line= 3
      1547498.77      6848487.31      1547449.75      6848087.40
      1547325.16      6847608.86
#Sta/Elev= 30
  4597.1 1807.78  4665.5 1806.66  4687.1 1807.06  4707.2 1806.81  4737.5 1805.24
  4767.7 1804.78  4797.9 1803.01  4818.1 1802.78  4833.4 1801.89  4888.6 1802.08
  4914.8 1801.28  4919.8 1801.79  4994.2 1798.31  4994.4 1797.81  4997.9 1797.81
  4998.2 1798.31  5069.6 1800.06  5077.6 1799.52  5118.2 1801.44  5133.7 1802.73
  5175.1 1804.27  5239.7 1805.40  5299.1 1805.88  5315.5 1805.48  5320.7 1806.00
  5391.4 1805.54  5402.4 1806.10  5431.9 1805.92  5478.4 1806.65  5494.5 1807.02
#Mann=5,-1,0
  4597.1    0.07       0  4994.2    0.07       0  4998.2    0.07       0
  5069.6   0.035       0  5478.4    0.07       0
Bank Sta=4994.2,4998.2
Exp/Cntr=0.3,0.1

Type RM Length L Ch R = 1,27282,158,158,158
BEGIN DESCRIPTION:
Tributary 1 to Little Elm Cr 27281.642
END DESCRIPTION:
XS GIS Cut Line= 3
      1547679.32      6848459.50      1547606.75      6848042.16
      1547474.47      6847473.44
#Sta/Elev= 30
  4576.4 1805.15  4627.2 1802.12  4649.0 1802.55  4720.0 1801.30  4740.3 1799.18
  4806.1 1798.33  4860.7 1795.96  4912.9 1795.47  4953.5 1795.82  4979.5 1795.17
  4994.1 1795.43  4999.6 1794.57  5022.7 1794.32  5023.0 1793.82  5026.5 1793.82
  5026.7 1794.32  5148.0 1795.26  5210.5 1796.81  5240.4 1796.99  5312.3 1799.93
  5373.9 1799.90  5381.0 1802.89  5386.1 1802.36  5394.4 1803.65  5507.4 1804.95
  5513.9 1805.92  5519.0 1805.66  5527.9 1807.04  5538.2 1807.66  5583.9 1807.68
#Mann=4,-1,0
  4576.4    0.07       0  4979.5   0.035       0  5022.7   0.035       0
  5026.7   0.035       0
Bank Sta=5022.7,5026.7
Exp/Cntr=0.3,0.1

Type RM Length L Ch R = 1,27124,162,162,162
BEGIN DESCRIPTION:
Tributary 1 to Little Elm Cr 27123.725
END DESCRIPTION:
XS GIS Cut Line= 3
      1547769.60      6848365.81      1547741.63      6848023.65
      1547655.00      6847538.02
#Sta/Elev= 30
  4656.7 1800.08  4734.8 1798.34  4772.2 1796.24  4784.9 1795.85  4842.1 1794.74
  4928.5 1793.98  4945.5 1794.13  4965.5 1793.36  4975.6 1793.43  4983.6 1793.09
  4983.9 1792.59  4987.4 1792.59  4987.6 1793.09  5158.1 1794.25  5181.8 1793.68
  5208.9 1795.18  5229.2 1795.66  5249.5 1795.64  5289.5 1798.55  5294.6 1798.07
  5310.5 1798.99  5330.8 1801.09  5340.9 1801.53  5391.7 1801.64  5442.5 1802.46
  5452.7 1803.03  5461.3 1804.04  5466.4 1803.98  5473.0 1804.65  5493.3 1805.02
#Mann=5,-1,0
  4656.7   0.035       0  4842.1    0.07       0  4928.5   0.035       0
  4983.6   0.035       0  4987.6   0.035       0
Bank Sta=4983.6,4987.6
Exp/Cntr=0.3,0.1

Type RM Length L Ch R = 1,26962,236,236,236
BEGIN DESCRIPTION:
Tributary 1 to Little Elm Cr 26961.78
END DESCRIPTION:
XS GIS Cut Line= 3
      1547852.93      6848494.25      1547891.12      6848004.66
      1547839.05      6847633.17
#Sta/Elev= 30
  4491.8 1803.11  4578.0 1801.61  4583.0 1801.76  4608.4 1800.88  4628.5 1799.76
  4648.5 1799.55  4678.6 1798.56  4698.7 1798.40  4728.8 1797.34  4758.9 1797.00
  4799.0 1795.95  4819.0 1795.74  4829.1 1796.04  4849.1 1795.72  4859.2 1795.18
  4879.2 1795.21  4990.8 1791.36  4991.1 1790.86  4994.6 1790.86  4994.8 1791.36
  4999.7 1791.97  5030.0 1793.14  5064.2 1793.61  5130.5 1796.12  5135.5 1795.84
  5201.7 1797.20  5252.1 1799.29  5272.3 1799.40  5292.5 1799.97  5358.0 1800.32
#Mann=3,-1,0
  4491.8   0.035       0  4990.8   0.035       0  4994.8   0.035       0
Bank Sta=4990.8,4994.8
Exp/Cntr=0.3,0.1

Type RM Length L Ch R = 1,26726,292,292,292
BEGIN DESCRIPTION:
Tributary 1 to Little Elm Cr 26725.52
END DESCRIPTION:
XS GIS Cut Line= 3
      1548127.24      6848438.67      1548109.87      6848039.38
      1547981.41      6847685.23
#Sta/Elev= 30
  4598.8 1795.88  4669.5 1796.39  4679.5 1795.84  4719.6 1795.24  4729.6 1794.63
  4765.0 1794.45  4770.0 1794.82  4819.7 1794.34  4829.7 1793.72  4859.7 1793.59
  4899.8 1792.35  4909.8 1792.38  4939.8 1790.51  4993.2 1788.74  4993.5 1788.24
  4997.0 1788.24  4997.2 1788.74  5032.3 1788.82  5057.6 1789.64  5088.2 1791.12
  5095.7 1791.84  5106.3 1792.03  5118.8 1793.11  5159.5 1794.63  5205.4 1795.28
  5255.2 1796.54  5261.3 1796.32  5286.6 1796.56  5297.8 1797.02  5375.2 1797.45
#Mann=3,-1,0
  4598.8   0.035       0  4993.2   0.035       0  4997.2   0.035       0
Bank Sta=4993.2,4997.2
Exp/Cntr=0.3,0.1

Type RM Length L Ch R = 1,26434,271,271,271
BEGIN DESCRIPTION:
Tributary 1 to Little Elm Cr 26434.26
END DESCRIPTION:
XS GIS Cut Line= 3
      1548280.00      6848445.67      1548408.49      6848053.27
      1548290.43      6847824.09
#Sta/Elev= 30
  4569.9 1794.74  4597.9 1793.01  4603.2 1793.92  4609.5 1794.14  4641.1 1793.04
  4661.6 1792.91  4693.4 1791.80  4698.7 1792.06  4704.2 1791.43  4746.3 1790.61
  4762.4 1790.34  4777.9 1790.89  4799.5 1790.44  4809.5 1790.66  4831.4 1789.62
  4851.6 1789.33  4889.8 1786.84  4921.7 1785.43  4965.3 1784.26  4965.5 1783.76
  4969.0 1783.76  4969.3 1784.26  5011.2 1784.40  5047.8 1786.21  5070.0 1786.84
  5086.5 1788.43  5101.2 1789.17  5130.8 1790.02  5203.0 1791.64  5240.6 1791.64
#Mann=3,-1,0
  4569.9   0.035       0  4965.3   0.035       0  4969.3   0.035       0
Bank Sta=4965.3,4969.3
Exp/Cntr=0.3,0.1

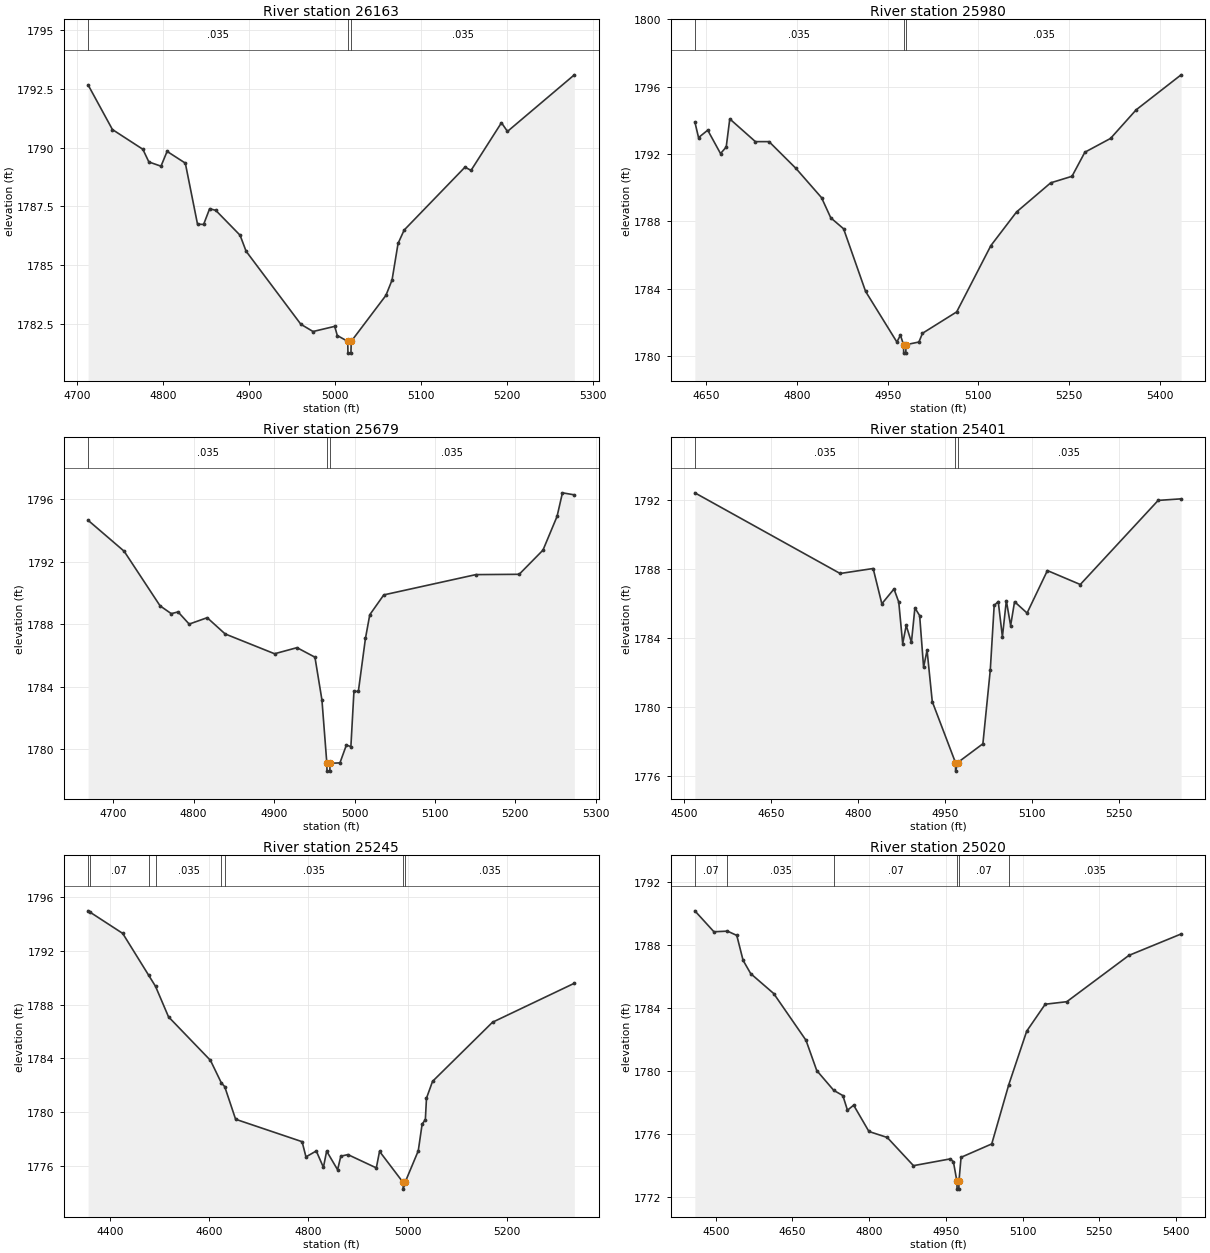
Type RM Length L Ch R = 1,26163,183,183,183
BEGIN DESCRIPTION:
Tributary 1 to Little Elm Cr 26163.029
END DESCRIPTION:
XS GIS Cut Line= 3
      1548404.99      6848338.01      1548609.04      6848136.33
      1548805.00      6847938.00
#Sta/Elev= 30
  4713.1 1792.67  4741.4 1790.77  4776.8 1789.93  4783.8 1789.39  4797.9 1789.21
  4805.0 1789.84  4826.2 1789.34  4840.4 1786.74  4847.5 1786.73  4854.5 1787.40
  4861.6 1787.33  4889.9 1786.27  4896.9 1785.59  4960.6 1782.48  4974.8 1782.17
  5000.0 1782.39  5003.0 1782.00  5015.2 1781.75  5015.4 1781.25  5018.9 1781.25
  5019.2 1781.75  5059.6 1783.71  5066.7 1784.36  5073.7 1785.92  5080.8 1786.49
  5151.6 1789.17  5158.6 1789.03  5194.0 1791.06  5201.0 1790.69  5278.8 1793.10
#Mann=3,-1,0
  4713.1   0.035       0  5015.2   0.035       0  5019.2   0.035       0
Bank Sta=5015.2,5019.2
Exp/Cntr=0.3,0.1

Type RM Length L Ch R = 1,25980,301,301,301
BEGIN DESCRIPTION:
Tributary 1 to Little Elm Cr 25980.37
END DESCRIPTION:
XS GIS Cut Line= 3
      1548391.09      6848483.84      1548710.57      6848282.43
      1549016.12      6847983.83
#Sta/Elev= 30
  4630.8 1793.91  4636.9 1792.98  4652.1 1793.42  4673.3 1792.03  4682.7 1792.42
  4688.6 1794.09  4731.0 1792.74  4753.6 1792.74  4798.1 1791.15  4840.5 1789.41
  4855.8 1788.21  4877.0 1787.56  4913.4 1783.84  4965.2 1780.83  4971.1 1781.24
  4976.2 1780.67  4976.5 1780.17  4980.0 1780.17  4980.2 1780.67  5001.7 1780.83
  5007.6 1781.35  5064.2 1782.62  5120.8 1786.56  5163.3 1788.56  5219.8 1790.29
  5255.1 1790.68  5276.4 1792.11  5318.9 1792.93  5361.3 1794.63  5435.7 1796.71
#Mann=3,-1,0
  4630.8   0.035       0  4976.2   0.035       0  4980.2   0.035       0
Bank Sta=4976.2,4980.2
Exp/Cntr=0.3,0.1

Type RM Length L Ch R = 1,25679,278,278,278
BEGIN DESCRIPTION:
Tributary 1 to Little Elm Cr 25679.133
END DESCRIPTION:
XS GIS Cut Line= 3
      1548554.98      6848688.01      1548851.17      6848539.58
      1549105.00      6848438.00
#Sta/Elev= 30
  4668.7 1794.65  4713.5 1792.67  4758.2 1789.17  4772.1 1788.67  4780.6 1788.78
  4794.4 1788.00  4816.8 1788.41  4839.1 1787.37  4900.6 1786.10  4928.5 1786.49
  4950.8 1785.88  4959.5 1783.14  4965.6 1779.08  4965.8 1778.58  4969.3 1778.58
  4969.6 1779.08  4981.9 1779.11  4989.9 1780.25  4995.5 1780.15  4999.3 1783.69
  5004.8 1783.69  5013.6 1787.08  5019.0 1788.60  5036.4 1789.87  5150.9 1791.17
  5204.8 1791.19  5234.4 1792.74  5251.9 1794.90  5258.6 1796.41  5273.4 1796.28
#Mann=3,-1,0
  4668.7   0.035       0  4965.6   0.035       0  4969.6   0.035       0
Bank Sta=4965.6,4969.6
Exp/Cntr=0.3,0.1

Type RM Length L Ch R = 1,25401,156,156,156
BEGIN DESCRIPTION:
Tributary 1 to Little Elm Cr 25422.15
END DESCRIPTION:
XS GIS Cut Line= 3
      1548552.38      6849053.13      1548962.15      6848778.80
      1549219.07      6848546.18
#Sta/Elev= 30
  4518.1 1792.44  4769.0 1787.75  4826.0 1788.04  4841.0 1785.99  4862.0 1786.85
  4870.2 1786.09  4877.0 1783.67  4883.1 1784.73  4892.1 1783.75  4898.1 1785.75
  4906.3 1785.30  4913.1 1782.30  4919.1 1783.29  4928.1 1780.30  4968.1 1776.76
  4968.4 1776.26  4972.1 1776.76  5015.5 1777.85  5028.3 1782.15  5035.0 1785.89
  5042.0 1786.12  5049.2 1784.07  5056.0 1786.17  5063.4 1784.72  5070.2 1786.11
  5091.8 1785.45  5126.9 1787.92  5183.7 1787.11  5318.2 1792.00  5357.8 1792.09
#Mann=3,-1,0
  4518.1   0.035       0  4968.1   0.035       0  4972.1   0.035       0
Bank Sta=4968.1,4972.1
Exp/Cntr=0.3,0.1

Type RM Length L Ch R = 1,25245,225,225,225
BEGIN DESCRIPTION:
Tributary 1 to Little Elm Cr 25209.11
END DESCRIPTION:
XS GIS Cut Line= 3
      1548536.34      6849327.63      1549060.68      6848890.10
      1549300.16      6848713.10
#Sta/Elev= 30
  4355.6 1794.98  4359.5 1794.88  4425.4 1793.30  4477.5 1790.20  4491.6 1789.36
  4517.8 1787.09  4602.4 1783.85  4624.4 1782.17  4631.1 1781.90  4653.1 1779.47
  4787.2 1777.80  4795.0 1776.67  4815.8 1777.11  4830.2 1775.89  4836.7 1777.10
  4858.8 1775.71  4865.3 1776.72  4879.6 1776.84  4936.9 1775.85  4943.4 1777.08
  4990.9 1774.77  4991.1 1774.27  4994.9 1774.77  5021.5 1777.12  5029.3 1779.11
  5035.8 1779.44  5038.1 1781.04  5050.3 1782.29  5171.3 1786.69  5336.3 1789.59
#Mann=8,-1,0
  4355.6   0.063       0  4359.5    0.07       0  4477.5   0.063       0
  4491.6   0.035       0  4624.4    0.07       0  4631.1   0.035       0
  4990.9   0.035       0  4994.9   0.035       0
Bank Sta=4990.9,4994.9
Exp/Cntr=0.3,0.1

Type RM Length L Ch R = 1,25020,195,195,195
BEGIN DESCRIPTION:
Tributary 1 to Little Elm Cr 24848.7
END DESCRIPTION:
XS GIS Cut Line= 3
      1548636.87      6849422.27      1549119.52      6849099.35
      1549352.17      6848811.14
#Sta/Elev= 30
  4459.1 1790.16  4496.4 1788.83  4522.9 1788.87  4541.1 1788.60  4553.4 1787.02
  4568.4 1786.17  4613.3 1784.91  4676.5 1781.94  4697.5 1780.02  4730.8 1778.76
  4748.6 1778.43  4757.6 1777.50  4769.7 1777.82  4799.6 1776.15  4835.4 1775.77
  4886.7 1773.98  4958.7 1774.41  4964.8 1774.23  4971.7 1772.99  4972.0 1772.49
  4975.5 1772.49  4975.7 1772.99  4979.8 1774.51  5039.8 1775.36  5073.1 1779.12
  5108.2 1782.52  5144.4 1784.23  5186.6 1784.39  5308.1 1787.33  5410.2 1788.69
#Mann=6,-1,0
  4459.1    0.07       0  4522.9   0.035       0  4730.8    0.07       0
  4971.7    0.07       0  4975.7    0.07       0  5073.1   0.035       0
Bank Sta=4971.7,4975.7
Exp/Cntr=0.3,0.1

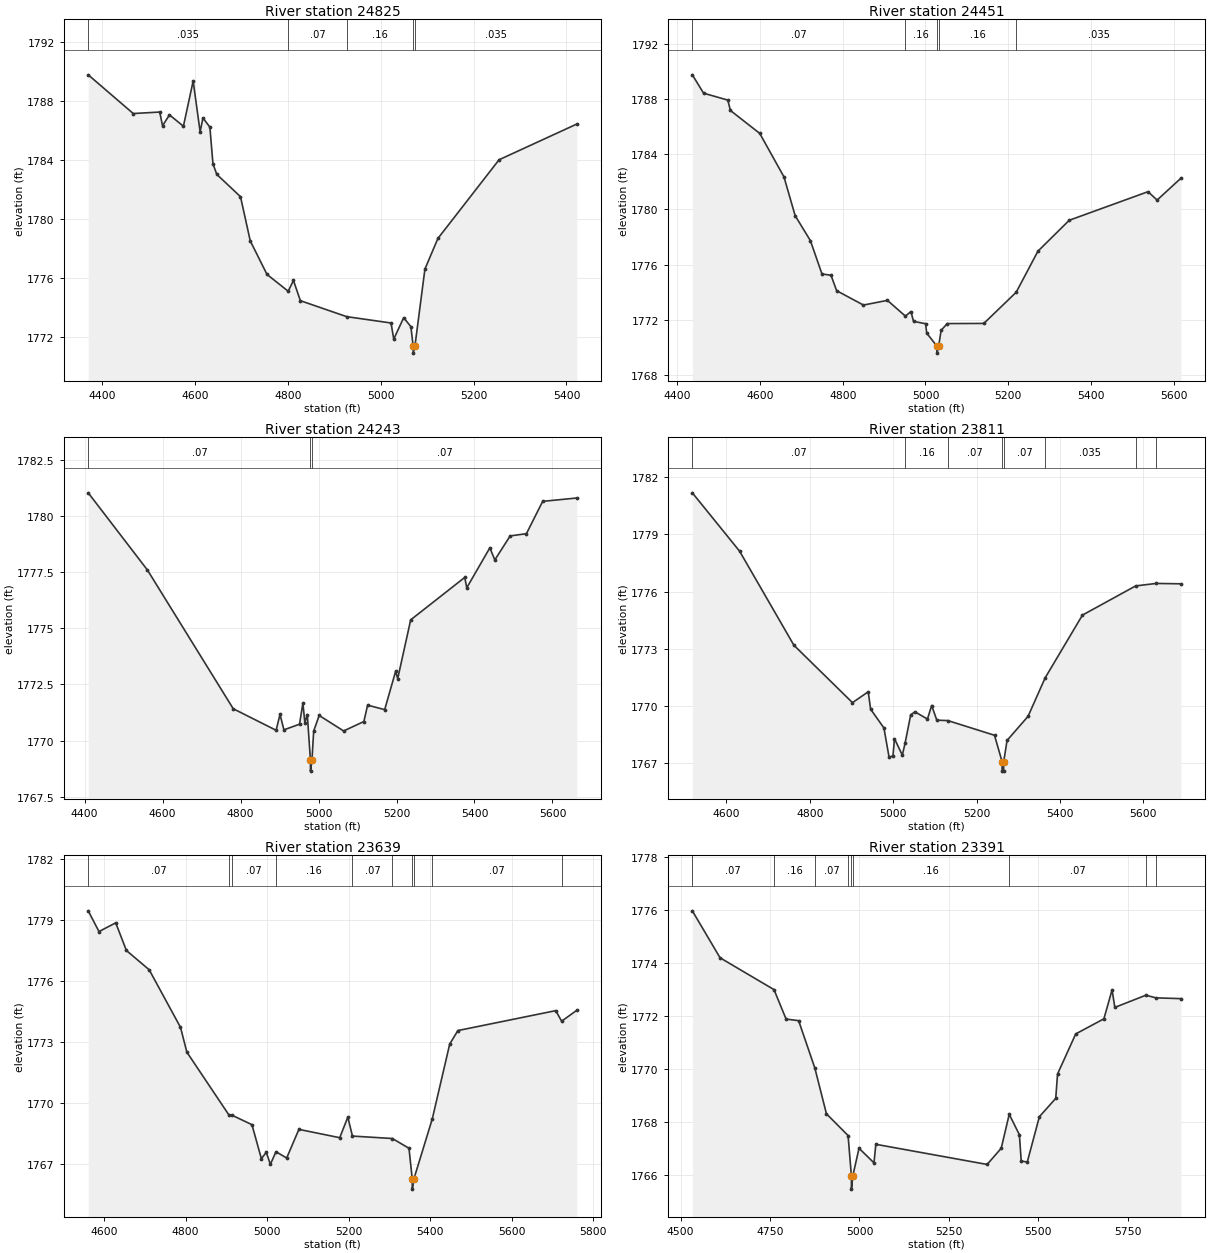
Type RM Length L Ch R = 1,24825,374,374,374
BEGIN DESCRIPTION:
Tributary 1 to Little Elm Cr 24744.73
END DESCRIPTION:
XS GIS Cut Line= 3
      1548672.36      6849629.05      1549200.84      6849272.67
      1549416.13      6848918.48
#Sta/Elev= 30
  4370.5 1789.78  4467.4 1787.16  4524.4 1787.26  4530.5 1786.33  4545.4 1787.07
  4575.4 1786.30  4596.4 1789.36  4611.4 1785.92  4617.4 1786.86  4632.4 1786.24
  4639.0 1783.76  4647.3 1783.04  4698.3 1781.53  4719.3 1778.54  4755.3 1776.27
  4801.0 1775.13  4812.3 1775.86  4827.2 1774.49  4926.8 1773.41  5022.4 1772.98
  5028.2 1771.89  5049.6 1773.34  5065.1 1772.73  5069.9 1771.44  5070.1 1770.94
  5073.9 1771.44  5095.3 1776.63  5123.2 1778.70  5254.9 1784.03  5422.4 1786.45
#Mann=5,-1,0
  4370.5   0.035       0  4801.0    0.07       0  4926.8    0.16       0
  5069.9    0.07       0  5073.9   0.035       0
Bank Sta=5069.9,5073.9
Exp/Cntr=0.3,0.1

Type RM Length L Ch R = 1,24451,208,208,208
BEGIN DESCRIPTION:
Tributary 1 to Little Elm Cr 24451.09
END DESCRIPTION:
XS GIS Cut Line= 3
      1548936.24      6850008.16      1549273.07      6849549.80
      1549567.81      6849012.32
#Sta/Elev= 30
  4436.1 1789.74  4463.3 1788.41  4521.9 1787.91  4528.1 1787.16  4599.1 1785.50
  4657.7 1782.35  4684.8 1779.54  4721.7 1777.73  4749.6 1775.32  4771.4 1775.23
  4785.1 1774.11  4849.9 1773.07  4907.9 1773.41  4951.4 1772.27  4964.8 1772.60
  4971.0 1771.89  5000.3 1771.72  5002.9 1771.04  5027.8 1770.09  5028.0 1769.59
  5031.8 1770.09  5037.8 1771.24  5052.6 1771.73  5141.1 1771.74  5219.4 1774.00
  5271.9 1776.97  5347.7 1779.21  5538.3 1781.28  5560.1 1780.67  5617.9 1782.26
#Mann=5,-1,0
  4436.1    0.07       0  4951.4    0.16       0  5027.8    0.07       0
  5031.8    0.16       0  5219.4   0.035       0
Bank Sta=5027.8,5031.8
Exp/Cntr=0.3,0.1

Type RM Length L Ch R = 1,24243,432,432,432
BEGIN DESCRIPTION:
Tributary 1 to Little Elm Cr 24243.09
END DESCRIPTION:
XS GIS Cut Line= 3
      1549446.68      6850219.94      1549450.15      6849640.07
      1549640.22      6848993.83
#Sta/Elev= 30
  4409.1 1781.04  4561.0 1777.60  4781.1 1771.42  4891.1 1770.46  4901.1 1771.17
  4911.1 1770.48  4951.1 1770.73  4959.8 1771.67  4964.8 1770.80  4971.1 1771.16
  4979.1 1769.14  4979.3 1768.64  4983.1 1769.14  4987.5 1770.43  5001.6 1771.12
  5064.3 1770.43  5116.2 1770.85  5125.8 1771.58  5169.6 1771.38  5197.7 1773.09
  5203.0 1772.76  5236.3 1775.38  5374.9 1777.27  5380.2 1776.81  5439.4 1778.59
  5452.1 1778.05  5491.5 1779.12  5533.2 1779.22  5574.9 1780.66  5662.6 1780.81
#Mann=3,-1,0
  4409.1    0.07       0  4979.1    0.07       0  4983.1    0.07       0
Bank Sta=4979.1,4983.1
Exp/Cntr=0.3,0.1

Type RM Length L Ch R = 1,23811,172,172,172
BEGIN DESCRIPTION:
Tributary 1 to Little Elm Cr 23810.87
END DESCRIPTION:
XS GIS Cut Line= 3
      1549543.89      6850230.37      1549780.01      6849806.74
      1549849.44      6849122.84
#Sta/Elev= 30
  4518.2 1781.18  4631.6 1778.12  4761.9 1773.19  4902.4 1770.18  4940.2 1770.75
  4945.9 1769.84  4977.9 1768.85  4990.3 1767.31  4999.6 1767.40  5003.2 1768.29
  5022.0 1767.43  5028.6 1768.05  5042.1 1769.54  5052.2 1769.70  5082.3 1769.32
  5092.4 1770.03  5104.8 1769.26  5131.2 1769.24  5243.2 1768.47  5261.3 1767.09
  5261.5 1766.59  5265.0 1766.59  5265.3 1767.09  5273.3 1768.20  5323.6 1769.46
  5364.7 1771.48  5454.2 1774.77  5581.9 1776.30  5631.3 1776.43  5690.6 1776.41
#Mann=8,-1,0
  4518.2    0.07       0  5028.6    0.16       0  5131.2    0.07       0
  5261.3    0.07       0  5265.3    0.07       0  5364.7   0.035       0
  5581.9    0.07       0  5631.3   0.035       0
Bank Sta=5261.3,5265.3
Exp/Cntr=0.3,0.1

Type RM Length L Ch R = 1,23639,248,248,248
BEGIN DESCRIPTION:
Tributary 1 to Little Elm Cr 23638.54
END DESCRIPTION:
XS GIS Cut Line= 3
      1549828.62      6850313.70      1549925.85      6849897.02
      1549943.21      6849126.19
#Sta/Elev= 30
  4561.3 1779.44  4587.7 1778.42  4628.8 1778.85  4654.9 1777.49  4710.9 1776.54
  4787.7 1773.71  4803.3 1772.49  4906.1 1769.41  4913.7 1769.39  4963.0 1768.92
  4986.1 1767.25  4998.2 1767.56  5008.2 1766.97  5022.0 1767.59  5048.2 1767.28
  5078.2 1768.69  5178.4 1768.28  5198.2 1769.29  5209.6 1768.36  5307.5 1768.24
  5348.3 1767.76  5356.3 1766.25  5356.5 1765.75  5360.3 1766.25  5405.4 1769.20
  5448.3 1772.89  5468.3 1773.55  5708.4 1774.53  5722.8 1774.01  5760.2 1774.55
#Mann=10,-1,0
  4561.3    0.07       0  4906.1    0.16       0  4913.7    0.07       0
  5022.0    0.16       0  5209.6    0.07       0  5307.5   0.035       0
  5356.3    0.07       0  5360.3   0.035       0  5405.4    0.07       0
  5722.8   0.035       0
Bank Sta=5356.3,5360.3
Exp/Cntr=0.3,0.1

Type RM Length L Ch R = 1,23391,270,270,270
BEGIN DESCRIPTION:
Tributary 1 to Little Elm Cr 23391.15
END DESCRIPTION:
XS GIS Cut Line= 3
      1550054.32      6850393.55      1550158.49      6849935.21
      1549981.40      6849056.71
#Sta/Elev= 30
  4532.7 1775.97  4610.2 1774.20  4761.0 1773.00  4794.8 1771.89  4829.9 1771.83
  4875.3 1770.04  4907.6 1768.32  4968.1 1767.50  4977.4 1765.98  4977.6 1765.48
  4981.4 1765.98  4998.7 1767.02  5040.6 1766.47  5045.7 1767.17  5356.9 1766.41
  5396.3 1767.02  5418.7 1768.30  5447.1 1767.53  5452.2 1766.54  5469.1 1766.50
  5503.0 1768.21  5548.7 1768.90  5553.8 1769.82  5604.6 1771.33  5683.4 1771.90
  5706.2 1772.99  5714.0 1772.33  5800.8 1772.79  5828.6 1772.69  5898.9 1772.66
#Mann=9,-1,0
  4532.7    0.07       0  4761.0    0.16       0  4875.3    0.07       0
  4968.1    0.16       0  4977.4    0.07       0  4981.4    0.16       0
  5418.7    0.07       0  5800.8   0.035       0  5828.6    0.07       0
Bank Sta=4977.4,4981.4
Exp/Cntr=0.3,0.1

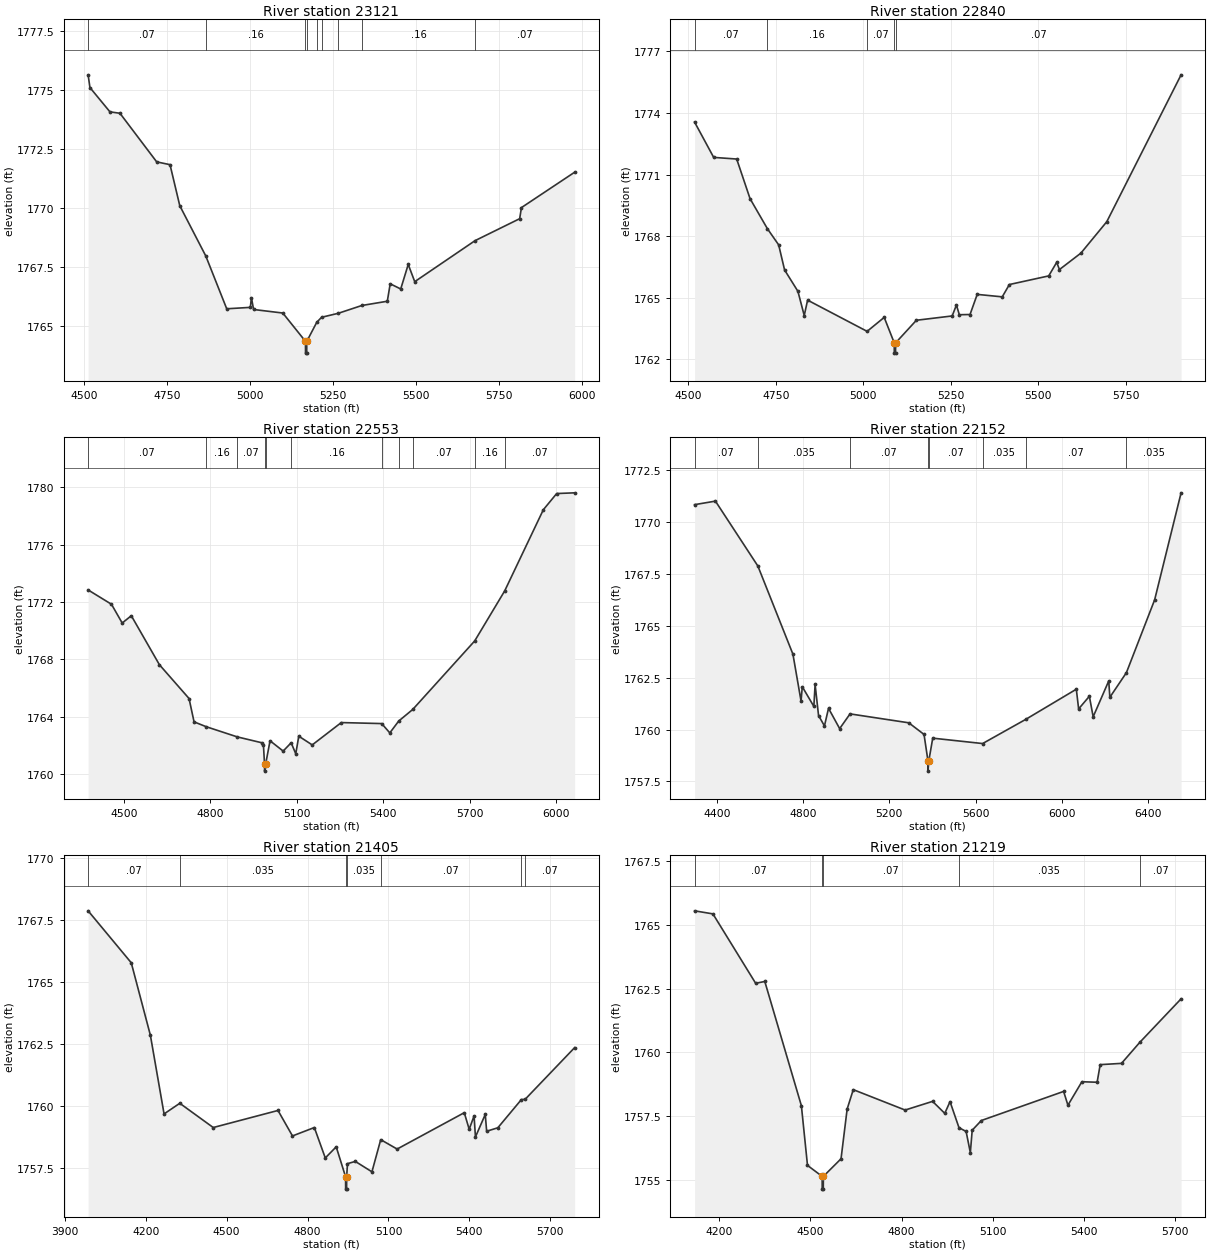
Type RM Length L Ch R = 1,23121,281,281,281
BEGIN DESCRIPTION:
Tributary 1 to Little Elm Cr 23120.51
END DESCRIPTION:
XS GIS Cut Line= 3
      1550332.09      6850473.43      1550380.71      6849987.30
      1550068.69      6849061.63
#Sta/Elev= 30
  4512.7 1775.63  4518.2 1775.09  4578.5 1774.06  4608.6 1774.00  4719.2 1771.94
  4759.4 1771.82  4788.8 1770.08  4867.1 1767.95  4930.2 1765.71  5001.3 1765.77
  5004.6 1766.18  5011.1 1765.68  5099.1 1765.53  5167.4 1764.33  5167.6 1763.83
  5171.1 1763.83  5171.4 1764.33  5201.5 1765.14  5216.0 1765.35  5266.5 1765.52
  5337.3 1765.85  5413.9 1766.03  5422.6 1766.77  5454.3 1766.55  5476.9 1767.59
  5496.5 1766.86  5678.3 1768.60  5812.6 1769.53  5817.9 1770.00  5978.1 1771.50
#Mann=9,-1,0
  4512.7    0.07       0  4867.1    0.16       0  5167.4    0.07       0
  5171.4    0.16       0  5201.5    0.07       0  5216.0    0.16       0
  5266.5    0.07       0  5337.3    0.16       0  5678.3    0.07       0
Bank Sta=5167.4,5171.4
Exp/Cntr=0.3,0.1

Type RM Length L Ch R = 1,22840,287,287,287
BEGIN DESCRIPTION:
Tributary 1 to Little Elm Cr 22839.851
END DESCRIPTION:
XS GIS Cut Line= 3
      1550454.99      6850338.03      1550595.00      6849876.29
      1550405.00      6848987.98
#Sta/Elev= 30
  4517.5 1773.56  4572.1 1771.84  4637.9 1771.76  4676.1 1769.83  4725.6 1768.37
  4757.9 1767.58  4774.8 1766.36  4812.9 1765.32  4831.0 1764.14  4840.6 1764.89
  5010.8 1763.37  5059.6 1764.05  5088.3 1762.81  5088.5 1762.31  5092.0 1762.31
  5092.3 1762.81  5151.6 1763.91  5253.9 1764.12  5266.1 1764.65  5274.4 1764.18
  5305.0 1764.19  5325.5 1765.17  5397.1 1765.05  5417.5 1765.65  5530.0 1766.07
  5552.7 1766.73  5560.7 1766.38  5622.0 1767.18  5696.0 1768.71  5908.4 1775.86
#Mann=5,-1,0
  4517.5    0.07       0  4725.6    0.16       0  5010.8    0.07       0
  5088.3    0.07       0  5092.3    0.07       0
Bank Sta=5088.3,5092.3
Exp/Cntr=0.3,0.1

Type RM Length L Ch R = 1,22553,401,401,401
BEGIN DESCRIPTION:
Tributary 1 to Little Elm Cr 22552.8
END DESCRIPTION:
XS GIS Cut Line= 3
      1550585.56      6850355.37      1550852.93      6849775.49
      1550526.53      6848778.93
#Sta/Elev= 30
  4376.0 1772.84  4457.0 1771.84  4494.2 1770.53  4525.8 1771.04  4623.2 1767.62
  4726.0 1765.26  4743.4 1763.63  4785.7 1763.29  4893.3 1762.58  4978.5 1762.17
  4984.0 1762.01  4987.8 1760.69  4988.0 1760.19  4991.8 1760.69  5006.9 1762.31
  5052.4 1761.59  5080.2 1762.17  5096.1 1761.40  5106.6 1762.63  5153.2 1762.02
  5254.0 1763.58  5394.1 1763.51  5422.3 1762.86  5453.3 1763.69  5502.0 1764.50
  5716.7 1769.28  5820.6 1772.77  5954.7 1778.44  6001.0 1779.57  6063.2 1779.62
#Mann=11,-1,0
  4376.0    0.07       0  4785.7    0.16       0  4893.3    0.07       0
  4987.8    0.07       0  4991.8    0.07       0  5080.2    0.16       0
  5394.1    0.07       0  5453.3    0.16       0  5502.0    0.07       0
  5716.7    0.16       0  5820.6    0.07       0
Bank Sta=4987.8,4991.8
Exp/Cntr=0.3,0.1

Type RM Length L Ch R = 1,22152,747,747,747
BEGIN DESCRIPTION:
Tributary 1 to Little Elm Cr 22286.88
END DESCRIPTION:
XS GIS Cut Line= 4
      1550828.61      6850282.46      1551130.84      6849739.60
      1551150.46      6849395.53      1551324.75      6848116.40
#Sta/Elev= 30
  4296.6 1770.85  4393.3 1771.02  4590.2 1767.89  4752.8 1763.64  4790.5 1761.38
  4796.2 1762.07  4849.9 1761.12  4855.7 1762.18  4871.7 1760.68  4899.1 1760.18
  4917.9 1761.03  4969.6 1760.05  5017.8 1760.76  5290.3 1760.33  5361.0 1759.77
  5379.2 1758.50  5379.4 1758.00  5383.2 1758.50  5401.4 1759.59  5632.8 1759.33
  5831.9 1760.49  6067.5 1761.95  6078.2 1761.00  6128.0 1761.61  6145.6 1760.62
  6217.9 1762.35  6223.0 1761.56  6299.9 1762.75  6430.8 1766.26  6553.5 1771.42
#Mann=8,-1,0
  4296.6    0.07       0  4590.2   0.035       0  5017.8    0.07       0
  5379.2   0.035       0  5383.2    0.07       0  5632.8   0.035       0
  5831.9    0.07       0  6299.9   0.035       0
Bank Sta=5379.2,5383.2
Exp/Cntr=0.3,0.1

Type RM Length L Ch R = 1,21405,186,186,186
BEGIN DESCRIPTION:
Tributary 1 to Little Elm Cr 21404.99
END DESCRIPTION:
XS GIS Cut Line= 3
      1551227.93      6850035.90      1551387.65      6849042.85
      1551578.62      6848268.56
#Sta/Elev= 30
  3986.6 1767.88  4146.5 1765.78  4217.4 1762.85  4268.1 1759.67  4326.4 1760.10
  4450.4 1759.12  4690.4 1759.81  4744.1 1758.78  4825.1 1759.12  4865.7 1757.89
  4906.2 1758.34  4940.9 1757.13  4941.2 1756.63  4944.7 1756.63  4944.9 1757.13
  4948.0 1757.66  4977.1 1757.75  5038.6 1757.33  5071.2 1758.63  5132.0 1758.25
  5380.9 1759.72  5399.1 1759.05  5417.2 1759.59  5422.3 1758.74  5458.7 1759.65
  5463.8 1758.97  5505.3 1759.11  5592.5 1760.25  5606.4 1760.26  5789.9 1762.35
#Mann=7,-1,0
  3986.6    0.07       0  4326.4   0.035       0  4940.9   0.035       0
  4944.9   0.035       0  5071.2    0.07       0  5592.5   0.035       0
  5606.4    0.07       0
Bank Sta=4940.9,4944.9
Exp/Cntr=0.3,0.1

Type RM Length L Ch R = 1,21219,299,299,299
BEGIN DESCRIPTION:
Tributary 1 to Little Elm Cr 21216.53
END DESCRIPTION:
XS GIS Cut Line= 3
      1551626.72      6849858.13      1551557.79      6848990.77
      1551603.22      6848262.48
#Sta/Elev= 30
  4119.2 1765.55  4179.5 1765.43  4320.0 1762.71  4350.1 1762.78  4470.4 1757.91
  4490.5 1755.57  4538.7 1755.14  4538.9 1754.64  4542.4 1754.64  4542.7 1755.14
  4600.8 1755.83  4620.9 1757.78  4641.0 1758.54  4811.5 1757.74  4901.8 1758.08
  4941.9 1757.61  4959.2 1758.07  4988.6 1757.05  5012.1 1756.90  5026.0 1756.07
  5032.1 1756.95  5062.2 1757.33  5332.7 1758.47  5346.9 1757.93  5392.8 1758.85
  5442.9 1758.83  5453.0 1759.52  5523.1 1759.57  5582.9 1760.39  5719.0 1762.10
#Mann=5,-1,0
  4119.2    0.07       0  4538.7   0.035       0  4542.7    0.07       0
  4988.6   0.035       0  5582.9    0.07       0
Bank Sta=4538.7,4542.7
Exp/Cntr=0.3,0.1