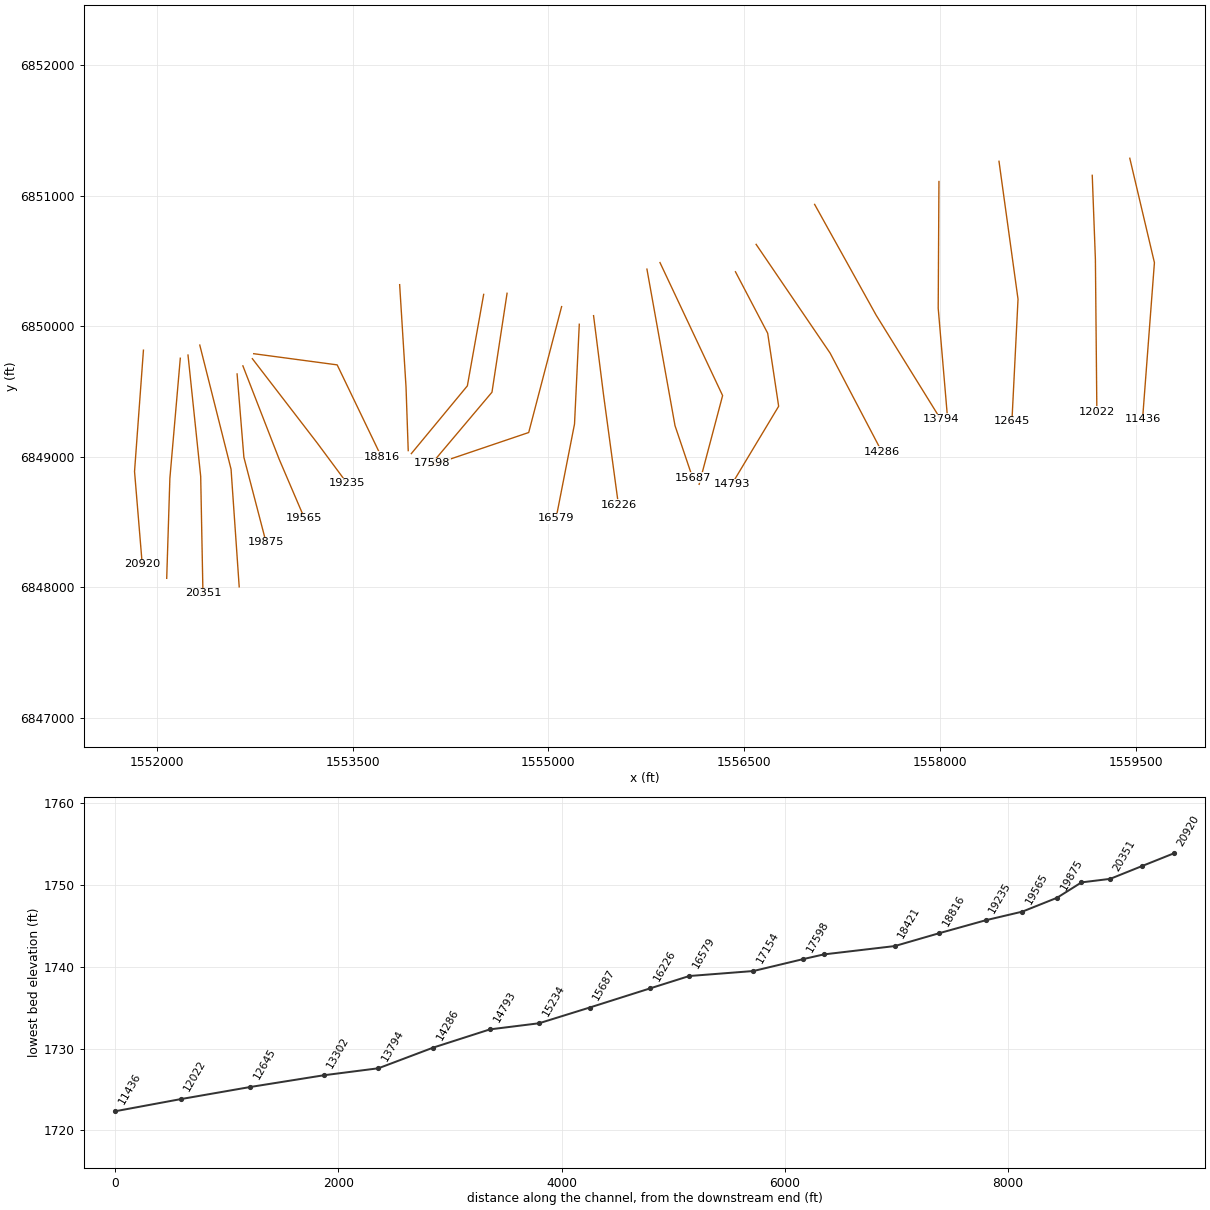
HEC-RAS study Tributary 1 to Little Elm Cr.prj: Tributary 1 to Little Elm Cr Base Level Engineering

--- Tributary 1 to Little Elm Cr.g01 (geometry) --- (continued)

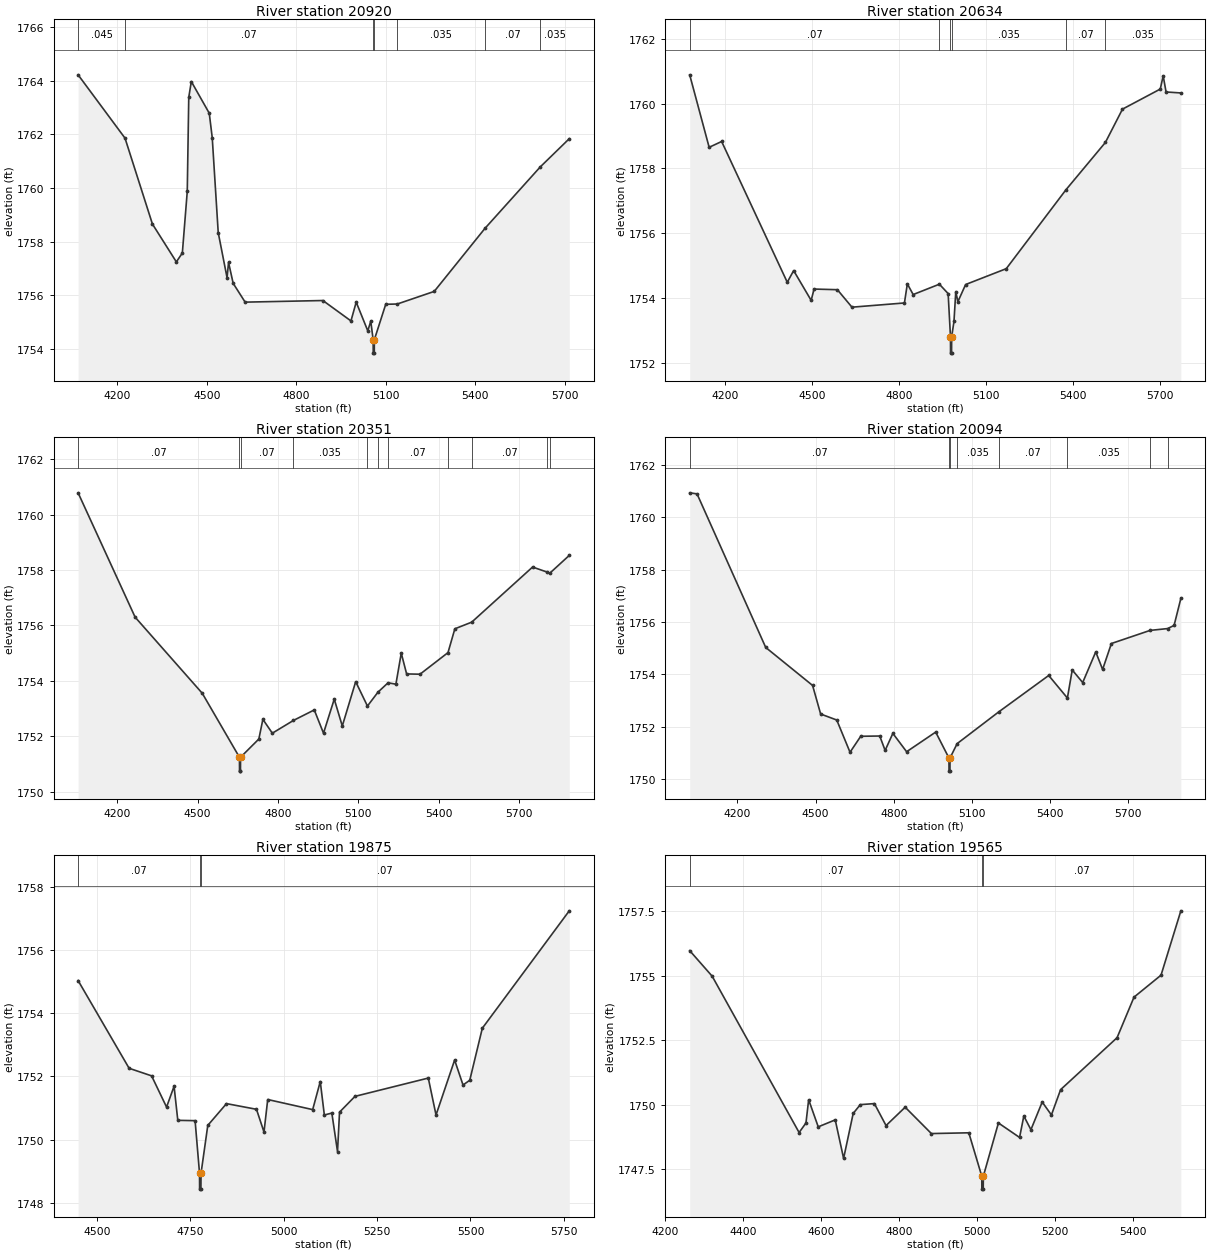
Type RM Length L Ch R = 1,20920,286,286,286
BEGIN DESCRIPTION:
Tributary 1 to Little Elm Cr 20920.13
END DESCRIPTION:
XS GIS Cut Line= 3
      1551896.91      6849816.53      1551828.62      6848886.60
      1551887.65      6848174.78
#Sta/Elev= 30
  4068.5 1764.22  4225.8 1761.86  4317.7 1758.66  4397.9 1757.25  4418.0 1757.58
  4434.5 1759.88  4439.5 1763.38  4448.1 1763.97  4508.2 1762.79  4518.2 1761.88
  4538.3 1758.34  4567.9 1756.66  4572.9 1757.23  4588.4 1756.45  4628.5 1755.75
  4889.2 1755.81  4983.3 1755.05  5000.9 1755.75  5039.7 1754.68  5049.7 1755.04
  5057.7 1754.35  5058.0 1753.85  5061.5 1753.85  5061.7 1754.35  5099.9 1755.67
  5138.6 1755.68  5262.5 1756.15  5432.7 1758.50  5618.1 1760.79  5715.2 1761.84
#Mann=7,-1,0
  4068.5   0.045       0  4225.8    0.07       0  5057.7    0.07       0
  5061.7    0.07       0  5138.6   0.035       0  5432.7    0.07       0
  5618.1   0.035       0
Bank Sta=5057.7,5061.7
Exp/Cntr=0.3,0.1

Type RM Length L Ch R = 1,20634,283,283,283
BEGIN DESCRIPTION:
Tributary 1 to Little Elm Cr 20633.6
END DESCRIPTION:
XS GIS Cut Line= 3
      1552179.32      6849754.70      1552099.46      6848834.52
      1552075.15      6848067.15
#Sta/Elev= 30
  4079.7 1760.89  4146.7 1758.65  4189.7 1758.83  4415.7 1754.48  4437.7 1754.84
  4498.0 1753.92  4508.0 1754.27  4588.3 1754.25  4638.5 1753.71  4819.2 1753.84
  4829.2 1754.43  4849.3 1754.10  4939.5 1754.42  4969.7 1754.13  4977.8 1752.79
  4978.0 1752.29  4981.5 1752.29  4981.8 1752.79  4989.8 1753.27  4996.0 1754.19
  5003.3 1753.88  5029.9 1754.41  5169.9 1754.90  5375.6 1757.34  5511.2 1758.80
  5570.1 1759.83  5700.2 1760.45  5710.2 1760.86  5720.2 1760.36  5771.1 1760.33
#Mann=6,-1,0
  4079.7    0.07       0  4939.5   0.035       0  4977.8   0.035       0
  4981.8   0.035       0  5375.6    0.07       0  5511.2   0.035       0
Bank Sta=4977.8,4981.8
Exp/Cntr=0.3,0.1

Type RM Length L Ch R = 1,20351,257,257,257
BEGIN DESCRIPTION:
Tributary 1 to Little Elm Cr 20350.79
END DESCRIPTION:
XS GIS Cut Line= 3
      1552238.35      6849778.96      1552335.57      6848848.41
      1552352.89      6847951.10
#Sta/Elev= 30
  4054.2 1760.79  4267.0 1756.30  4517.7 1753.55  4656.4 1751.24  4656.7 1750.74
  4660.2 1750.74  4660.4 1751.24  4728.8 1751.90  4743.8 1752.61  4779.1 1752.11
  4857.8 1752.57  4935.6 1752.95  4970.1 1752.11  5010.2 1753.34  5040.2 1752.37
  5090.2 1753.97  5134.1 1753.09  5173.2 1753.59  5211.0 1753.93  5240.3 1753.88
  5260.3 1755.00  5280.3 1754.25  5330.3 1754.24  5434.7 1755.02  5460.3 1755.88
  5523.3 1756.12  5750.4 1758.11  5804.0 1757.93  5814.9 1757.89  5887.3 1758.53
#Mann=11,-1,0
  4054.2    0.07       0  4656.4   0.035       0  4660.4    0.07       0
  4857.8   0.035       0  5134.1    0.07       0  5173.2   0.035       0
  5211.0    0.07       0  5434.7   0.035       0  5523.3    0.07       0
  5804.0   0.035       0  5814.9    0.07       0
Bank Sta=4656.4,4660.4
Exp/Cntr=0.3,0.1

Type RM Length L Ch R = 1,20094,219,219,219
BEGIN DESCRIPTION:
Tributary 1 to Little Elm Cr 20093.89
END DESCRIPTION:
XS GIS Cut Line= 3
      1552328.62      6849855.39      1552568.21      6848903.96
      1552630.65      6848002.05
#Sta/Elev= 30
  4016.9 1760.93  4045.1 1760.89  4308.7 1755.03  4488.6 1753.58  4519.5 1752.49
  4581.4 1752.26  4632.3 1751.03  4673.4 1751.64  4746.4 1751.65  4767.0 1751.10
  4796.7 1751.75  4849.5 1751.05  4961.1 1751.80  5012.0 1750.81  5012.3 1750.31
  5015.8 1750.31  5016.0 1750.81  5043.5 1751.36  5203.0 1752.57  5394.9 1753.96
  5466.6 1753.10  5485.2 1754.17  5525.3 1753.69  5575.4 1754.86  5601.8 1754.19
  5635.5 1755.18  5784.0 1755.68  5851.2 1755.75  5876.1 1755.87  5902.1 1756.90
#Mann=8,-1,0
  4016.9    0.07       0  5012.0    0.07       0  5016.0    0.07       0
  5043.5   0.035       0  5203.0    0.07       0  5466.6   0.035       0
  5784.0    0.07       0  5851.2   0.035       0
Bank Sta=5012,5016
Exp/Cntr=0.3,0.1

Type RM Length L Ch R = 1,19875,310,310,310
BEGIN DESCRIPTION:
Tributary 1 to Little Elm Cr 19795.03
END DESCRIPTION:
XS GIS Cut Line= 3
      1552614.45      6849634.12      1552666.53      6848995.21
      1552836.59      6848342.73
#Sta/Elev= 30
  4449.2 1755.04  4585.8 1752.26  4646.0 1752.02  4686.1 1751.03  4706.2 1751.69
  4716.2 1750.61  4762.5 1750.60  4774.4 1748.93  4774.6 1748.43  4778.1 1748.43
  4778.4 1748.93  4796.5 1750.45  4846.6 1751.14  4926.9 1750.96  4947.0 1750.24
  4957.0 1751.27  5077.4 1750.95  5097.7 1751.84  5108.6 1750.78  5128.7 1750.84
  5143.9 1749.62  5149.3 1750.87  5190.7 1751.37  5387.0 1751.95  5407.7 1750.78
  5457.5 1752.52  5480.0 1751.73  5498.0 1751.88  5531.7 1753.53  5764.5 1757.25
#Mann=3,-1,0
  4449.2    0.07       0  4774.4    0.07       0  4778.4    0.07       0
Bank Sta=4774.4,4778.4
Exp/Cntr=0.3,0.1

Type RM Length L Ch R = 1,19565,330,330,330
BEGIN DESCRIPTION:
Tributary 1 to Little Elm Cr 19504.88
END DESCRIPTION:
XS GIS Cut Line= 3
      1552658.92      6849696.21      1552936.69      6848980.95
      1553130.55      6848527.45
#Sta/Elev= 30
  4262.4 1755.97  4320.1 1754.98  4543.2 1748.93  4560.8 1749.30  4567.7 1750.20
  4592.3 1749.15  4635.9 1749.42  4657.4 1747.93  4682.0 1749.67  4700.3 1750.01
  4736.4 1750.05  4766.3 1749.20  4815.4 1749.91  4882.7 1748.89  4978.7 1748.92
  5012.0 1747.24  5012.2 1746.74  5015.7 1746.74  5016.0 1747.24  5054.7 1749.30
  5109.0 1748.74  5119.9 1749.57  5138.1 1749.04  5167.1 1750.11  5190.7 1749.61
  5214.3 1750.59  5359.2 1752.60  5402.7 1754.17  5472.0 1755.02  5522.9 1757.51
#Mann=3,-1,0
  4262.4    0.07       0  5012.0    0.07       0  5016.0    0.07       0
Bank Sta=5012,5016
Exp/Cntr=0.3,0.1

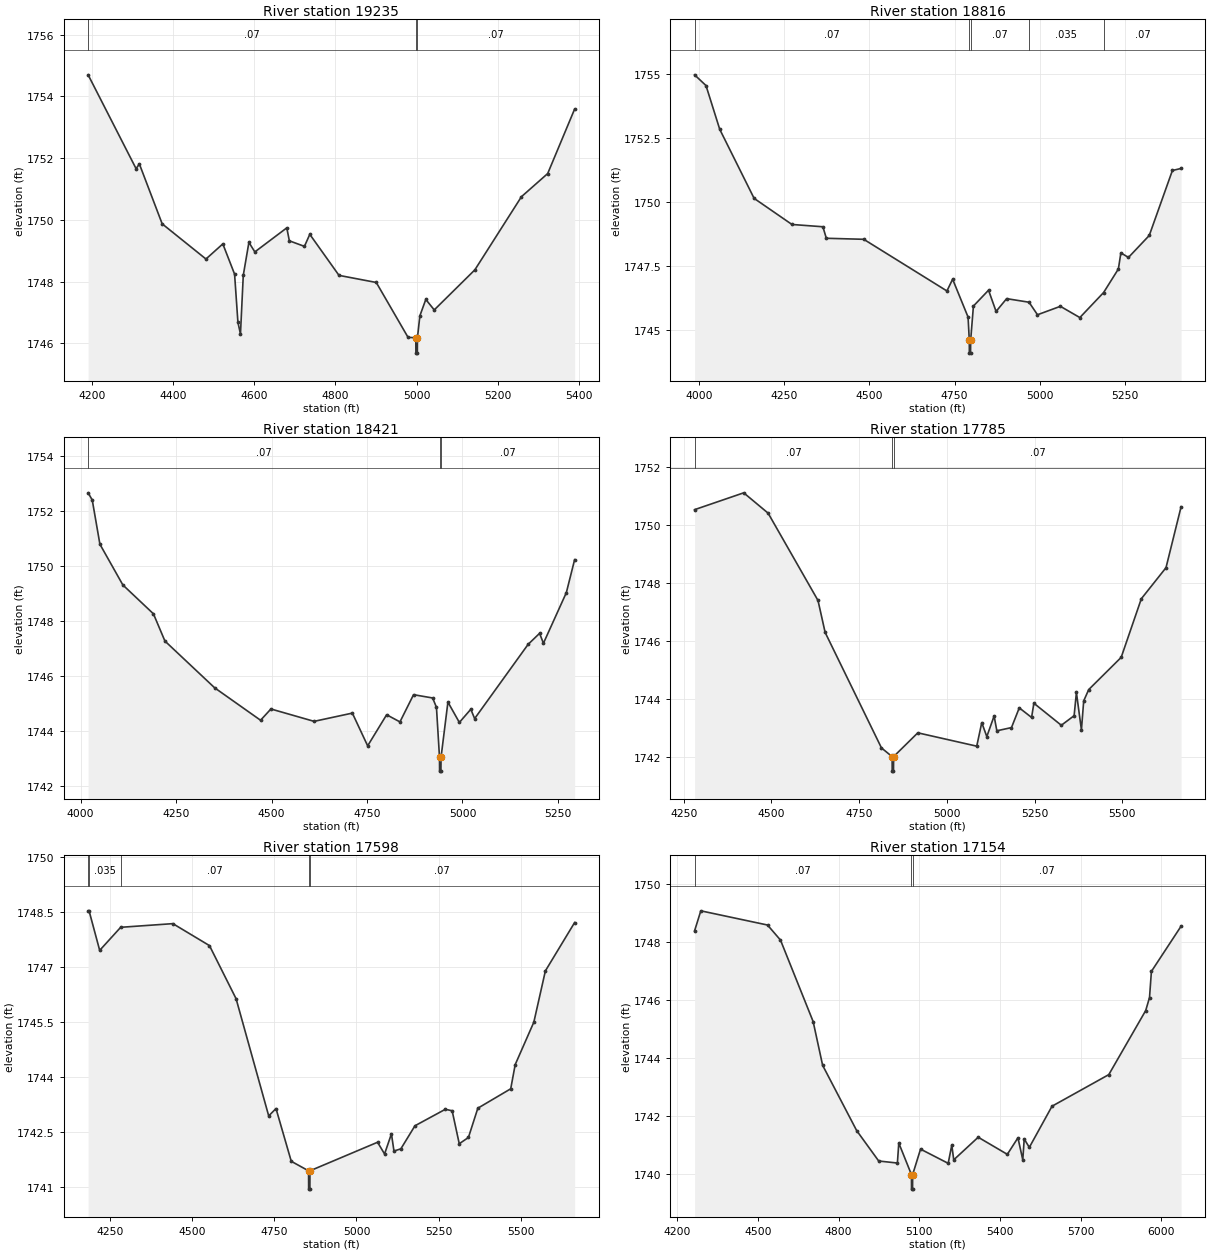
Type RM Length L Ch R = 1,19235,419,419,419
BEGIN DESCRIPTION:
Tributary 1 to Little Elm Cr 19234.69
END DESCRIPTION:
XS GIS Cut Line= 3
      1552731.38      6849751.22      1553227.93      6849105.35
      1553457.09      6848796.33
#Sta/Elev= 30
  4190.2 1754.70  4308.4 1751.66  4316.6 1751.81  4372.8 1749.87  4480.7 1748.73
  4522.3 1749.22  4551.3 1748.24  4559.5 1746.68  4565.8 1746.30  4572.7 1748.20
  4586.6 1749.27  4601.2 1748.96  4680.0 1749.74  4686.3 1749.32  4723.5 1749.14
  4736.7 1749.53  4808.7 1748.20  4900.6 1747.97  4979.0 1746.19  4998.1 1746.18
  4998.3 1745.68  5001.8 1745.68  5002.1 1746.18  5008.1 1746.89  5022.7 1747.42
  5043.5 1747.08  5143.7 1748.38  5258.5 1750.75  5323.2 1751.50  5389.6 1753.59
#Mann=3,-1,0
  4190.2    0.07       0  4998.1    0.07       0  5002.1    0.07       0
Bank Sta=4998.1,5002.1
Exp/Cntr=0.3,0.1

Type RM Length L Ch R = 1,18816,395,395,395
BEGIN DESCRIPTION:
Tributary 1 to Little Elm Cr 18821.18
END DESCRIPTION:
XS GIS Cut Line= 3
      1552741.82      6849789.38      1553381.47      6849703.74
      1553720.47      6848998.77
#Sta/Elev= 30
  3987.0 1754.97  4020.5 1754.55  4060.8 1752.84  4161.7 1750.14  4272.7 1749.12
  4363.5 1749.03  4373.6 1748.58  4483.4 1748.54  4727.5 1746.52  4744.2 1746.98
  4789.5 1745.50  4793.1 1744.59  4793.3 1744.09  4796.8 1744.09  4797.1 1744.59
  4805.2 1745.93  4849.6 1746.55  4871.7 1745.72  4902.7 1746.22  4968.4 1746.08
  4993.2 1745.59  5060.4 1745.92  5117.5 1745.48  5187.3 1746.46  5230.6 1747.38
  5237.9 1748.01  5260.1 1747.83  5321.2 1748.69  5389.1 1751.23  5414.6 1751.31
#Mann=5,-1,0
  3987.0    0.07       0  4793.1   0.035       0  4797.1    0.07       0
  4968.4   0.035       0  5187.3    0.07       0
Bank Sta=4793.1,4797.1
Exp/Cntr=0.3,0.1

Type RM Length L Ch R = 1,18421,636,636,636
BEGIN DESCRIPTION:
Tributary 1 to Little Elm Cr 18419.07
END DESCRIPTION:
XS GIS Cut Line= 3
      1553860.16      6850318.80      1553908.97      6849533.88
      1553925.85      6849046.30
#Sta/Elev= 30
  4019.5 1752.65  4030.3 1752.39  4050.4 1750.78  4110.5 1749.30  4190.6 1748.25
  4220.7 1747.26  4350.9 1745.56  4471.2 1744.38  4498.3 1744.79  4611.4 1744.34
  4711.6 1744.64  4751.7 1743.45  4801.4 1744.58  4836.3 1744.32  4871.9 1745.31
  4921.9 1745.19  4931.9 1744.85  4939.9 1743.03  4940.1 1742.53  4943.6 1742.53
  4943.9 1743.03  4961.9 1745.04  4991.9 1744.30  5021.9 1744.78  5031.9 1744.44
  5172.0 1747.14  5202.0 1747.54  5212.1 1747.18  5272.1 1749.02  5293.8 1750.22
#Mann=3,-1,0
  4019.5    0.07       0  4939.9    0.07       0  4943.9    0.07       0
Bank Sta=4939.9,4943.9
Exp/Cntr=0.3,0.1

Type RM Length L Ch R = 1,17785,187,187,187
BEGIN DESCRIPTION:
Tributary 1 to Little Elm Cr 17784.56
END DESCRIPTION:
XS GIS Cut Line= 3
      1554503.97      6850244.21      1554378.97      6849542.85
      1553949.60      6849023.46
#Sta/Elev= 30
  4281.2 1750.52  4421.2 1751.10  4490.7 1750.40  4632.9 1747.39  4653.2 1746.29
  4813.7 1742.31  4844.1 1742.01  4844.3 1741.51  4848.0 1741.51  4848.3 1742.01
  4917.3 1742.83  5085.2 1742.37  5099.5 1743.18  5113.9 1742.70  5134.7 1743.41
  5142.5 1742.90  5184.2 1743.01  5206.4 1743.69  5241.5 1743.36  5248.0 1743.85
  5326.2 1743.09  5362.7 1743.42  5369.2 1744.22  5383.5 1742.93  5390.0 1743.93
  5404.3 1744.32  5496.8 1745.43  5554.2 1747.45  5624.5 1748.52  5667.5 1750.62
#Mann=3,-1,0
  4281.2    0.07       0  4844.1    0.07       0  4848.3    0.07       0
Bank Sta=4844.1,4848.3
Exp/Cntr=0.3,0.1

Type RM Length L Ch R = 1,17598,444,444,444
BEGIN DESCRIPTION:
Tributary 1 to Little Elm Cr 17607.15
END DESCRIPTION:
XS GIS Cut Line= 3
      1554683.22      6850252.76      1554567.61      6849494.22
      1554108.73      6848949.81
#Sta/Elev= 30
  4184.0 1748.53  4186.9 1748.53  4219.2 1747.45  4283.0 1748.08  4441.7 1748.18
  4553.0 1747.58  4633.9 1746.13  4733.1 1742.93  4755.3 1743.13  4801.7 1741.69
  4854.3 1741.43  4854.6 1740.93  4858.3 1740.93  4858.5 1741.43  5064.1 1742.21
  5085.4 1741.89  5106.3 1742.44  5114.0 1741.97  5134.9 1742.03  5177.8 1742.66
  5270.1 1743.11  5290.9 1743.07  5312.5 1742.17  5340.4 1742.34  5369.0 1743.14
  5469.0 1743.67  5482.6 1744.33  5539.3 1745.49  5574.4 1746.89  5663.3 1748.21
#Mann=5,-1,0
  4184.0    0.07       0  4186.9   0.035       0  4283.0    0.07       0
  4854.3    0.07       0  4858.5    0.07       0
Bank Sta=4854.3,4858.5
Exp/Cntr=0.3,0.1

Type RM Length L Ch R = 1,17154,575,575,575
BEGIN DESCRIPTION:
Tributary 1 to Little Elm Cr 17181.04
END DESCRIPTION:
XS GIS Cut Line= 3
      1555101.18      6850150.45      1554849.09      6849185.23
      1554080.41      6848924.81
#Sta/Elev= 30
  4264.3 1748.39  4287.5 1749.08  4535.6 1748.59  4583.8 1748.07  4705.2 1745.26
  4740.5 1743.75  4867.0 1741.50  4949.0 1740.45  5018.5 1740.38  5023.7 1741.07
  5070.8 1739.98  5071.1 1739.48  5074.9 1739.48  5075.2 1739.98  5104.6 1740.86
  5207.4 1740.37  5220.8 1741.00  5228.0 1740.49  5319.0 1741.27  5427.3 1740.68
  5466.8 1741.25  5484.8 1740.49  5490.1 1741.21  5509.1 1740.92  5593.5 1742.34
  5804.7 1743.43  5941.9 1745.64  5956.1 1746.09  5963.1 1746.99  6073.5 1748.55
#Mann=3,-1,0
  4264.3    0.07       0  5070.8    0.07       0  5075.2    0.07       0
Bank Sta=5070.8,5075.2
Exp/Cntr=0.3,0.1

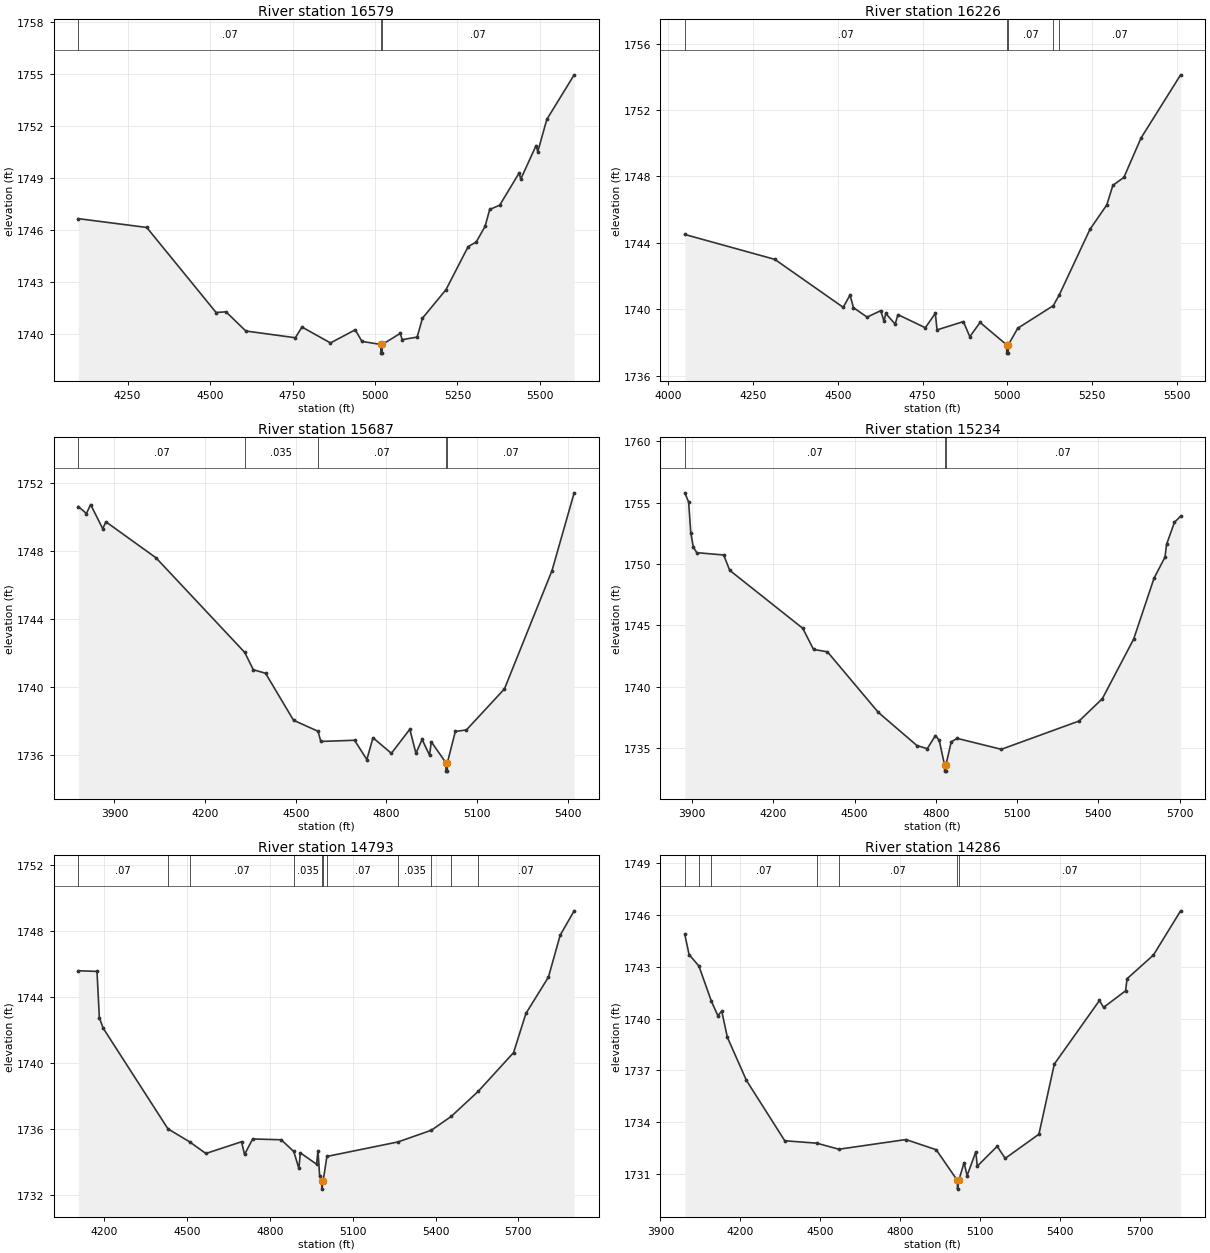
Type RM Length L Ch R = 1,16579,353,353,353
BEGIN DESCRIPTION:
Tributary 1 to Little Elm Cr 16489.21
END DESCRIPTION:
XS GIS Cut Line= 3
      1555236.61      6850015.12      1555200.10      6849250.16
      1555058.44      6848526.63
#Sta/Elev= 30
  4100.6 1746.65  4308.0 1746.14  4518.2 1741.22  4548.2 1741.26  4608.3 1740.15
  4758.5 1739.76  4778.5 1740.38  4865.0 1739.46  4940.0 1740.22  4960.3 1739.55
  5017.5 1739.37  5017.8 1738.87  5021.6 1738.87  5021.9 1739.37  5076.3 1740.01
  5082.6 1739.65  5127.8 1739.80  5143.8 1740.89  5215.1 1742.54  5282.3 1745.03
  5306.8 1745.30  5333.8 1746.21  5347.6 1747.18  5378.1 1747.43  5436.8 1749.29
  5441.9 1748.94  5488.3 1750.88  5493.4 1750.52  5520.8 1752.39  5603.7 1754.97
#Mann=3,-1,0
  4100.6    0.07       0  5017.5    0.07       0  5021.9    0.07       0
Bank Sta=5017.5,5021.9
Exp/Cntr=0.3,0.1

Type RM Length L Ch R = 1,16226,539,539,539
BEGIN DESCRIPTION:
Tributary 1 to Little Elm Cr 16185.951
END DESCRIPTION:
XS GIS Cut Line= 3
      1555346.05      6850081.22      1555423.55      6849465.95
      1555536.41      6848632.28
#Sta/Elev= 30
  4049.2 1744.50  4314.5 1743.00  4516.1 1740.11  4536.2 1740.85  4546.3 1740.09
  4586.6 1739.52  4626.9 1739.91  4636.5 1739.26  4641.5 1739.74  4669.3 1739.10
  4677.4 1739.67  4758.1 1738.88  4787.6 1739.75  4792.7 1738.75  4870.3 1739.25
  4889.3 1738.34  4919.5 1739.20  4997.8 1737.85  4998.2 1737.35  5002.4 1737.35
  5002.8 1737.85  5030.5 1738.85  5135.3 1740.21  5153.4 1740.88  5243.4 1744.81
  5292.9 1746.28  5310.9 1747.46  5343.4 1747.94  5393.8 1750.31  5510.6 1754.12
#Mann=5,-1,0
  4049.2    0.07       0  4997.8    0.07       0  5002.8    0.07       0
  5135.3   0.035       0  5153.4    0.07       0
Bank Sta=4997.8,5002.8
Exp/Cntr=0.3,0.1

Type RM Length L Ch R = 1,15687,453,453,453
BEGIN DESCRIPTION:
Tributary 1 to Little Elm Cr 15687.068
END DESCRIPTION:
XS GIS Cut Line= 3
      1555755.00      6850437.97      1555970.20      6849237.51
      1556104.99      6848838.04
#Sta/Elev= 30
  3780.4 1750.62  3807.2 1750.21  3821.0 1750.74  3861.0 1749.32  3871.8 1749.72
  4037.4 1747.60  4331.2 1742.02  4359.5 1741.00  4400.1 1740.79  4492.7 1738.02
  4573.8 1737.37  4583.0 1736.77  4694.7 1736.84  4735.4 1735.70  4755.7 1736.99
  4816.6 1736.07  4877.6 1737.49  4897.9 1736.07  4918.2 1736.89  4942.9 1735.96
  4948.7 1736.75  4996.9 1735.52  4997.3 1735.02  5001.6 1735.02  5002.0 1735.52
  5028.3 1737.36  5065.0 1737.45  5190.9 1739.87  5348.2 1746.84  5421.6 1751.43
#Mann=5,-1,0
  3780.4    0.07       0  4331.2   0.035       0  4573.8    0.07       0
  4996.9    0.07       0  5002.0    0.07       0
Bank Sta=4996.9,5002
Exp/Cntr=0.3,0.1

Type RM Length L Ch R = 1,15234,441,441,441
BEGIN DESCRIPTION:
Tributary 1 to Little Elm Cr 15234.165
END DESCRIPTION:
XS GIS Cut Line= 3
      1555854.99      6850488.03      1556334.84      6849468.39
      1556154.99      6848787.96
#Sta/Elev= 30
  3873.1 1755.80  3887.3 1755.05  3895.2 1752.54  3904.6 1751.37  3917.3 1750.92
  4016.8 1750.73  4038.9 1749.48  4308.6 1744.75  4348.4 1743.03  4399.8 1742.83
  4587.7 1737.89  4730.0 1735.19  4768.3 1734.93  4798.4 1736.00  4812.6 1735.61
  4832.1 1733.60  4832.5 1733.10  4836.8 1733.10  4837.2 1733.60  4856.8 1735.49
  4878.9 1735.77  5041.8 1734.88  5329.1 1737.19  5414.8 1739.01  5530.4 1743.87
  5605.7 1748.84  5646.0 1750.55  5652.0 1751.60  5681.0 1753.40  5703.8 1753.89
#Mann=3,-1,0
  3873.1    0.07       0  4832.1    0.07       0  4837.2    0.07       0
Bank Sta=4832.1,4837.2
Exp/Cntr=0.3,0.1

Type RM Length L Ch R = 1,14793,507,507,507
BEGIN DESCRIPTION:
Tributary 1 to Little Elm Cr 14744.161
END DESCRIPTION:
XS GIS Cut Line= 4
      1556433.21      6850417.85      1556680.26      6849946.23
      1556764.37      6849386.42      1556405.02      6848788.03
#Sta/Elev= 30
  4105.6 1745.58  4173.2 1745.54  4181.8 1742.73  4195.7 1742.10  4430.4 1736.00
  4508.4 1735.22  4567.7 1734.51  4696.9 1735.22  4707.8 1734.45  4737.3 1735.39
  4840.8 1735.34  4886.2 1734.63  4904.8 1733.60  4909.9 1734.55  4968.8 1733.86
  4973.9 1734.68  4980.0 1733.14  4987.5 1732.85  4987.9 1732.35  4992.7 1732.85
  5006.2 1734.33  5264.1 1735.21  5384.9 1735.92  5457.0 1736.76  5554.3 1738.27
  5682.6 1740.62  5727.2 1742.99  5808.8 1745.19  5851.6 1747.74  5902.1 1749.21
#Mann=11,-1,0
  4105.6    0.07       0  4430.4   0.035       0  4508.4    0.07       0
  4886.2   0.035       0  4987.5   0.035       0  4992.7   0.035       0
  5006.2    0.07       0  5264.1   0.035       0  5384.9    0.07       0
  5457.0   0.035       0  5554.3    0.07       0
Bank Sta=4987.5,4992.7
Exp/Cntr=0.3,0.1

Type RM Length L Ch R = 1,14286,492,492,492
BEGIN DESCRIPTION:
Tributary 1 to Little Elm Cr 14286.446
END DESCRIPTION:
XS GIS Cut Line= 3
      1556591.82      6850627.56      1557158.97      6849793.53
      1557554.98      6849038.03
#Sta/Elev= 30
  3991.4 1744.87  4007.5 1743.71  4044.5 1743.04  4091.4 1741.00  4115.3 1740.18
  4130.2 1740.43  4151.2 1738.92  4223.0 1736.42  4366.7 1732.93  4486.7 1732.79
  4570.0 1732.44  4821.6 1733.00  4935.4 1732.41  5014.9 1730.63  5015.3 1730.13
  5020.1 1730.63  5039.9 1731.66  5051.4 1730.91  5084.0 1732.29  5089.6 1731.46
  5164.3 1732.61  5194.3 1731.91  5321.0 1733.31  5378.8 1737.37  5548.2 1741.05
  5563.7 1740.65  5646.3 1741.61  5651.9 1742.31  5750.9 1743.68  5853.0 1746.24
#Mann=7,-1,0
  3991.4    0.07       0  4044.5   0.035       0  4091.4    0.07       0
  4486.7   0.035       0  4570.0    0.07       0  5014.9    0.07       0
  5020.1    0.07       0
Bank Sta=5014.9,5020.1
Exp/Cntr=0.3,0.1

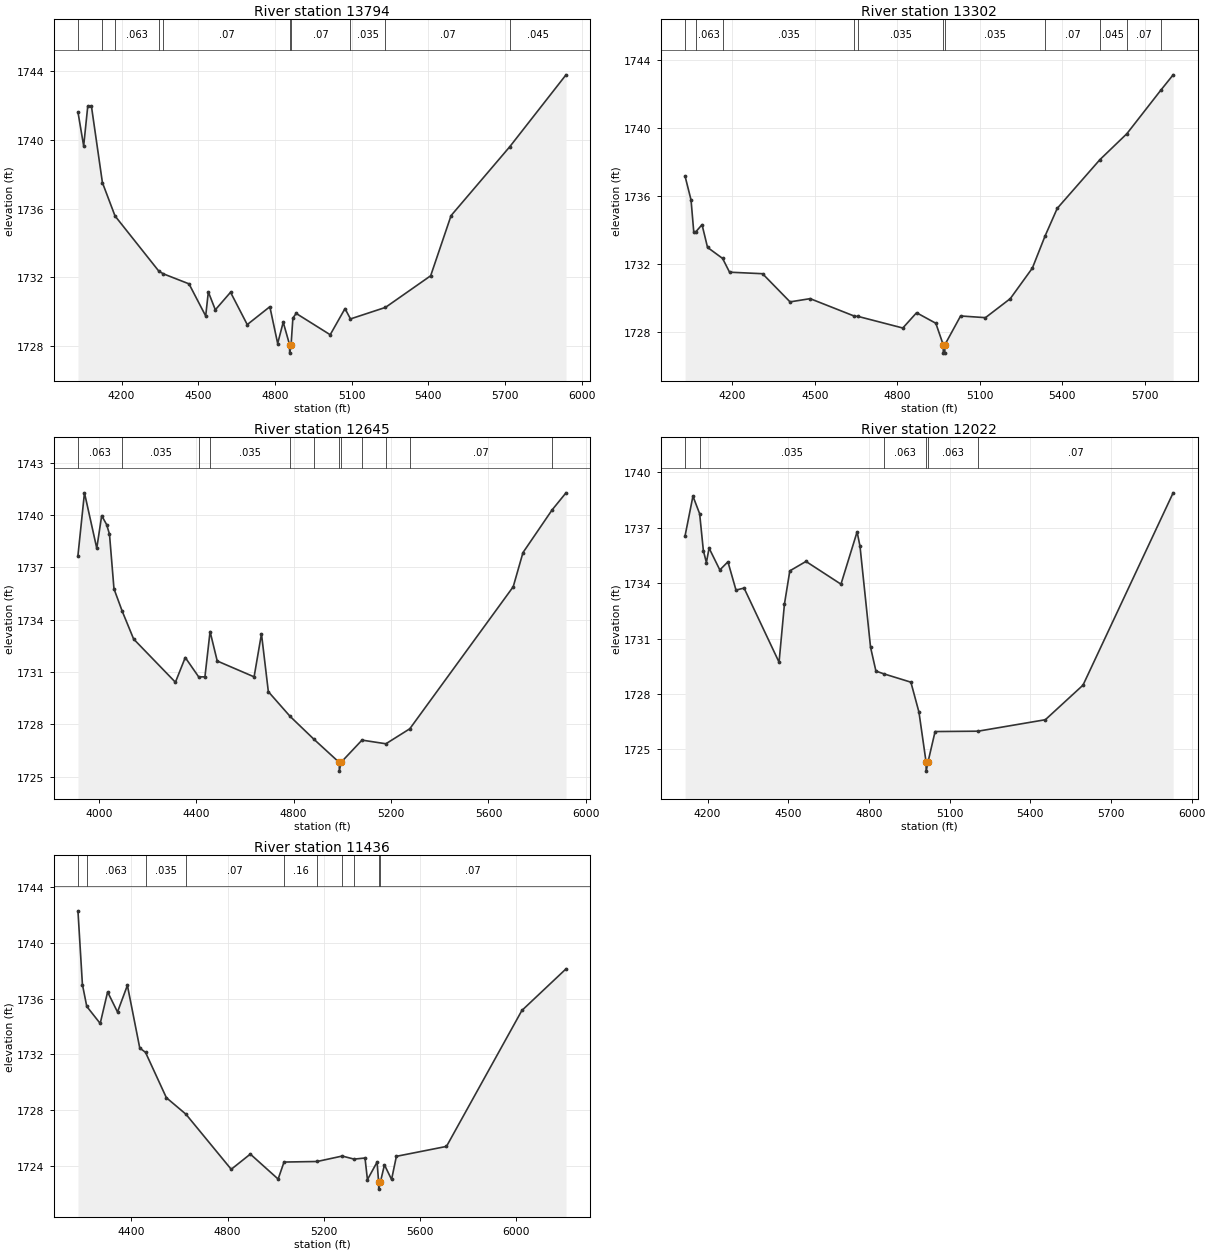
Type RM Length L Ch R = 1,13794,492,492,492
BEGIN DESCRIPTION:
Tributary 1 to Little Elm Cr 13793.575
END DESCRIPTION:
XS GIS Cut Line= 3
      1557040.02      6850934.22      1557510.97      6850085.65
      1558004.98      6849288.04
#Sta/Elev= 30
  4029.5 1741.63  4051.9 1739.65  4067.9 1741.97  4082.4 1741.95  4125.2 1737.52
  4174.5 1735.58  4345.8 1732.37  4364.0 1732.21  4463.8 1731.63  4529.1 1729.76
  4539.4 1731.16  4566.8 1730.12  4626.3 1731.14  4691.6 1729.26  4780.0 1730.30
  4810.6 1728.16  4832.3 1729.40  4857.0 1728.10  4857.5 1727.60  4863.1 1728.10
  4870.1 1729.64  4882.9 1729.91  5016.0 1728.67  5073.9 1730.19  5095.3 1729.59
  5232.1 1730.26  5408.9 1732.10  5488.7 1735.60  5718.4 1739.61  5938.2 1743.79
#Mann=10,-1,0
  4029.5   0.094       0  4125.2   0.035       0  4174.5   0.063       0
  4345.8   0.035       0  4364.0    0.07       0  4857.0    0.07       0
  4863.1    0.07       0  5095.3   0.035       0  5232.1    0.07       0
  5718.4   0.045       0
Bank Sta=4857,4863.1
Exp/Cntr=0.3,0.1

Type RM Length L Ch R = 1,13302,657,657,657
BEGIN DESCRIPTION:
Tributary 1 to Little Elm Cr 13301.906
END DESCRIPTION:
XS GIS Cut Line= 3
      1557992.67      6851109.57      1557986.94      6850138.28
      1558055.00      6849337.97
#Sta/Elev= 30
  4028.7 1737.16  4050.3 1735.77  4060.3 1733.87  4067.2 1733.88  4090.3 1734.31
  4110.3 1732.97  4165.1 1732.32  4190.3 1731.51  4310.3 1731.42  4410.3 1729.76
  4483.4 1729.95  4644.3 1728.92  4658.4 1728.90  4820.3 1728.22  4870.3 1729.12
  4940.3 1728.50  4967.1 1727.24  4967.6 1726.74  4972.9 1726.74  4973.4 1727.24
  5030.4 1728.93  5120.7 1728.83  5211.0 1729.95  5291.3 1731.75  5337.2 1733.63
  5381.7 1735.27  5536.8 1738.14  5634.9 1739.67  5758.1 1742.23  5803.2 1743.14
#Mann=11,-1,0
  4028.7   0.094       0  4067.2   0.063       0  4165.1   0.035       0
  4644.3   0.094       0  4658.4   0.035       0  4967.1   0.035       0
  4973.4   0.035       0  5337.2    0.07       0  5536.8   0.045       0
  5634.9    0.07       0  5758.1   0.045       0
Bank Sta=4967.1,4973.4
Exp/Cntr=0.3,0.1

Type RM Length L Ch R = 1,12645,623,623,623
BEGIN DESCRIPTION:
Tributary 1 to Little Elm Cr 12645.23
END DESCRIPTION:
XS GIS Cut Line= 3
      1558452.76      6851264.59      1558598.59      6850207.35
      1558551.80      6849271.47
#Sta/Elev= 30
  3914.1 1737.68  3940.9 1741.28  3991.4 1738.10  4011.6 1739.97  4031.8 1739.46
  4043.6 1738.91  4062.1 1735.77  4096.1 1734.48  4142.8 1732.89  4314.4 1730.41
  4354.8 1731.83  4409.8 1730.72  4435.6 1730.72  4456.7 1733.32  4486.1 1731.63
  4637.5 1730.72  4667.8 1733.19  4696.0 1729.87  4785.5 1728.45  4883.9 1727.13
  4987.1 1725.81  4987.6 1725.31  4994.3 1725.81  5080.6 1727.09  5178.8 1726.88
  5276.9 1727.74  5701.6 1735.89  5741.7 1737.85  5861.3 1740.30  5918.4 1741.28
#Mann=12,-1,0
  3914.1   0.063       0  4096.1   0.035       0  4409.8   0.063       0
  4456.7   0.035       0  4785.5   0.094       0  4883.9   0.035       0
  4987.1   0.035       0  4994.3   0.035       0  5080.6   0.063       0
  5178.8   0.035       0  5276.9    0.07       0  5861.3   0.045       0
Bank Sta=4987.1,4994.3
Exp/Cntr=0.3,0.1

Type RM Length L Ch R = 1,12022,586,586,586
BEGIN DESCRIPTION:
Tributary 1 to Little Elm Cr 11696.14
END DESCRIPTION:
XS GIS Cut Line= 3
      1559167.32      6851157.15      1559191.53      6850511.33
      1559202.76      6849342.86
#Sta/Elev= 30
  4116.4 1736.56  4145.6 1738.70  4170.5 1737.75  4184.3 1735.76  4195.6 1735.11
  4205.6 1735.89  4245.6 1734.71  4275.7 1735.15  4305.7 1733.62  4335.7 1733.73
  4465.8 1729.72  4485.8 1732.86  4505.8 1734.66  4565.9 1735.17  4696.0 1733.94
  4756.0 1736.77  4766.8 1735.99  4806.0 1730.53  4826.0 1729.24  4855.7 1729.09
  4956.0 1728.64  4986.0 1727.02  5012.4 1724.33  5012.9 1723.83  5019.7 1724.33
  5046.0 1725.97  5205.7 1725.99  5456.0 1726.61  5596.0 1728.48  5931.2 1738.88
#Mann=6,-1,0
  4116.4   0.094       0  4170.5   0.035       0  4855.7   0.063       0
  5012.4   0.063       0  5019.7   0.063       0  5205.7    0.07       0
Bank Sta=5012.4,5019.7
Exp/Cntr=0.3,0.1

Type RM Length L Ch R = 1,11436,685,685,685
BEGIN DESCRIPTION:
Tributary 1 to Little Elm Cr 11435.809
END DESCRIPTION:
XS GIS Cut Line= 3
      1559455.00      6851288.02      1559643.77      6850487.78
      1559552.69      6849285.13
#Sta/Elev= 30
  4177.8 1742.29  4196.4 1737.01  4214.5 1735.44  4270.3 1734.22  4301.1 1736.48
  4342.2 1735.04  4383.3 1736.95  4434.7 1732.46  4458.6 1732.15  4545.3 1728.90
  4626.5 1727.72  4814.8 1723.77  4894.2 1724.86  5009.8 1723.07  5034.2 1724.29
  5171.8 1724.33  5276.1 1724.72  5325.3 1724.50  5370.8 1724.58  5380.9 1723.03
  5421.0 1724.29  5427.4 1722.85  5427.9 1722.35  5434.7 1722.85  5451.6 1724.09
  5481.2 1723.04  5501.2 1724.70  5709.4 1725.41  6022.7 1735.15  6206.1 1738.13
#Mann=10,-1,0
  4177.8    0.07       0  4214.5   0.063       0  4458.6   0.035       0
  4626.5    0.07       0  5034.2    0.16       0  5171.8    0.07       0
  5276.1    0.16       0  5325.3    0.07       0  5427.4    0.07       0
  5434.7    0.07       0
Bank Sta=5427.4,5434.7
Exp/Cntr=0.3,0.1