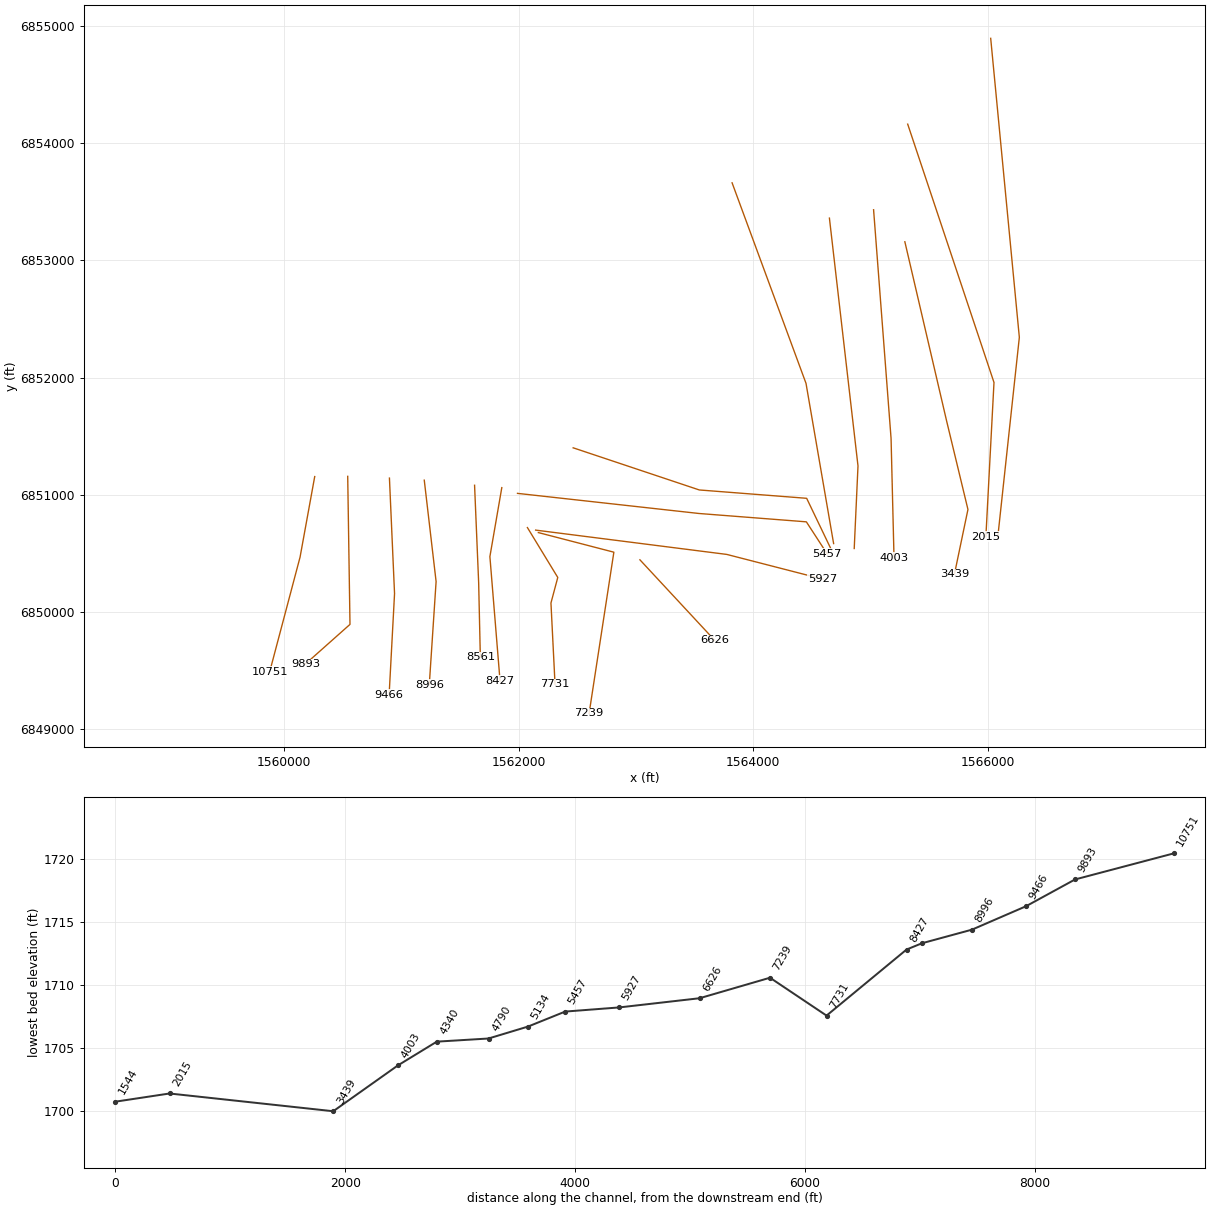
HEC-RAS study Tributary 1 to Little Elm Cr.prj: Tributary 1 to Little Elm Cr Base Level Engineering

--- Tributary 1 to Little Elm Cr.g01 (geometry) --- (continued)

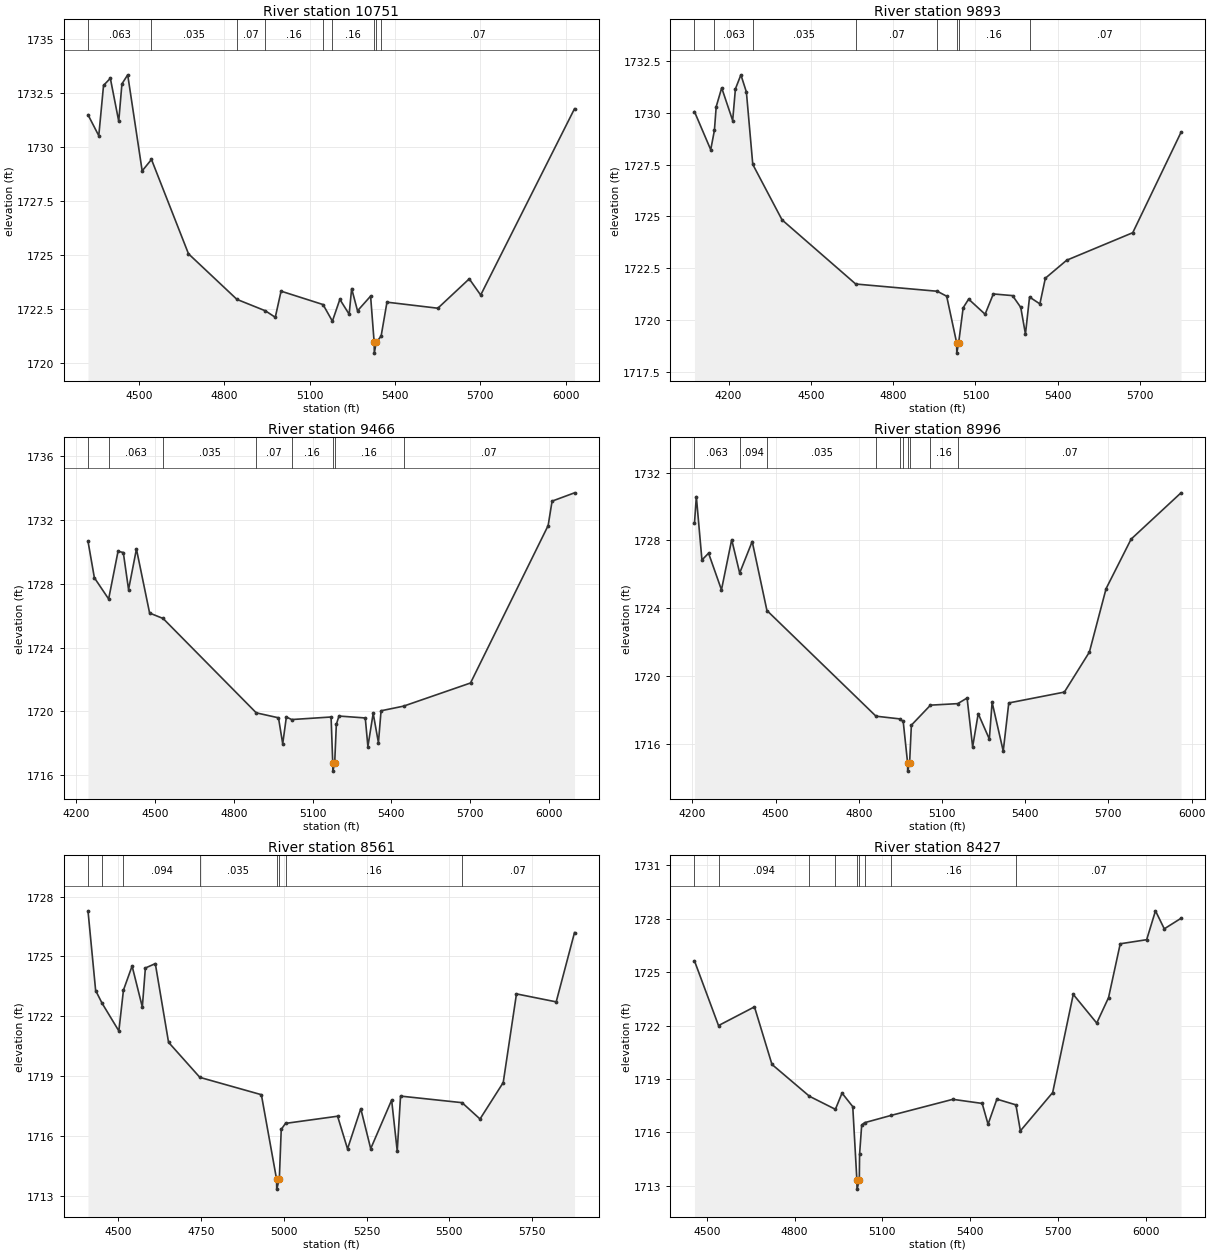
Type RM Length L Ch R = 1,10751,858,858,858
BEGIN DESCRIPTION:
Tributary 1 to Little Elm Cr 10751.43
END DESCRIPTION:
XS GIS Cut Line= 3
      1560260.05      6851155.26      1560135.05      6850467.76
      1559876.51      6849491.17
#Sta/Elev= 30
  4321.7 1731.50  4359.6 1730.53  4376.3 1732.86  4400.2 1733.19  4429.7 1731.20
  4440.9 1732.93  4461.2 1733.35  4512.0 1728.90  4544.7 1729.43  4674.7 1725.06
  4844.8 1722.95  4944.8 1722.42  4979.6 1722.12  4999.9 1723.33  5147.3 1722.71
  5180.2 1721.94  5206.4 1722.95  5239.1 1722.26  5247.8 1723.45  5268.5 1722.42
  5314.4 1723.10  5326.9 1720.96  5327.4 1720.46  5334.2 1720.96  5351.4 1721.25
  5371.9 1722.82  5550.6 1722.54  5660.9 1723.90  5701.1 1723.15  6030.7 1731.78
#Mann=9,-1,0
  4321.7   0.063       0  4544.7   0.035       0  4844.8    0.07       0
  4944.8    0.16       0  5147.3    0.07       0  5180.2    0.16       0
  5326.9    0.07       0  5334.2    0.16       0  5351.4    0.07       0
Bank Sta=5326.9,5334.2
Exp/Cntr=0.3,0.1

Type RM Length L Ch R = 1,9893,427,427,427
BEGIN DESCRIPTION:
Tributary 1 to Little Elm Cr 15.0
END DESCRIPTION:
XS GIS Cut Line= 3
      1560541.44      6851157.18      1560560.85      6849893.67
      1560179.95      6849554.92
#Sta/Elev= 30
  4075.9 1730.06  4135.1 1728.22  4148.5 1729.15  4155.1 1730.30  4175.1 1731.21
  4215.1 1729.63  4225.1 1731.16  4245.1 1731.84  4265.1 1731.01  4288.4 1727.51
  4395.1 1724.83  4663.6 1721.73  4960.9 1721.38  4995.2 1721.14  5031.5 1718.89
  5032.0 1718.39  5038.8 1718.89  5055.2 1720.58  5075.2 1721.00  5135.2 1720.27
  5165.2 1721.25  5235.2 1721.17  5265.2 1720.60  5282.3 1719.31  5297.2 1721.10
  5334.9 1720.77  5354.8 1722.01  5432.6 1722.88  5673.4 1724.21  5849.3 1729.06
#Mann=8,-1,0
  4075.9   0.035       0  4148.5   0.063       0  4288.4   0.035       0
  4663.6    0.07       0  4960.9    0.16       0  5031.5    0.07       0
  5038.8    0.16       0  5297.2    0.07       0
Bank Sta=5031.5,5038.8
Exp/Cntr=0.3,0.1

Type RM Length L Ch R = 1,9466,470,470,470
BEGIN DESCRIPTION:
Tributary 1 to Little Elm Cr 10047.81
END DESCRIPTION:
XS GIS Cut Line= 3
      1560897.29      6851142.27      1560940.80      6850156.11
      1560894.63      6849292.76
#Sta/Elev= 30
  4245.4 1730.66  4269.7 1728.37  4324.0 1727.04  4359.8 1730.03  4379.8 1729.95
  4399.8 1727.63  4429.8 1730.17  4479.9 1726.16  4531.3 1725.82  4885.9 1719.91
  4970.4 1719.60  4986.5 1717.97  5000.4 1719.65  5020.7 1719.49  5170.6 1719.65
  5176.9 1716.76  5177.4 1716.26  5184.3 1716.76  5190.6 1719.19  5200.6 1719.71
  5300.7 1719.59  5310.7 1717.80  5330.8 1719.88  5350.8 1718.04  5360.8 1720.04
  5446.4 1720.33  5701.3 1721.78  5996.7 1731.64  6011.7 1733.17  6097.1 1733.69
#Mann=8,-1,0
  4245.4   0.035       0  4324.0   0.063       0  4531.3   0.035       0
  4885.9    0.07       0  5020.7    0.16       0  5176.9    0.07       0
  5184.3    0.16       0  5446.4    0.07       0
Bank Sta=5176.9,5184.3
Exp/Cntr=0.3,0.1

Type RM Length L Ch R = 1,8996,435,435,435
BEGIN DESCRIPTION:
Tributary 1 to Little Elm Cr 9271.72
END DESCRIPTION:
XS GIS Cut Line= 3
      1561194.26      6851124.67      1561295.20      6850259.24
      1561237.05      6849378.46
#Sta/Elev= 30
  4207.7 1729.02  4214.4 1730.59  4234.6 1726.85  4258.5 1727.25  4305.0 1725.09
  4341.9 1728.05  4370.6 1726.08  4415.8 1727.94  4468.9 1723.87  4862.0 1717.64
  4947.7 1717.48  4960.2 1717.33  4975.9 1714.90  4976.4 1714.40  4983.3 1714.90
  4989.6 1717.11  5058.5 1718.29  5156.8 1718.38  5190.5 1718.71  5210.5 1715.83
  5230.6 1717.79  5270.7 1716.29  5280.7 1718.46  5320.8 1715.58  5340.8 1718.42
  5541.2 1719.06  5631.4 1721.42  5691.6 1725.16  5781.8 1728.08  5961.7 1730.81
#Mann=10,-1,0
  4207.7   0.063       0  4370.6   0.094       0  4468.9   0.035       0
  4862.0    0.16       0  4947.7   0.035       0  4960.2    0.07       0
  4975.9    0.07       0  4983.3    0.07       0  5058.5    0.16       0
  5156.8    0.07       0
Bank Sta=4975.9,4983.3
Exp/Cntr=0.3,0.1

Type RM Length L Ch R = 1,8561,134,134,134
BEGIN DESCRIPTION:
Tributary 1 to Little Elm Cr 8969.18
END DESCRIPTION:
XS GIS Cut Line= 3
      1561623.31      6851081.11      1561658.12      6850249.92
      1561672.54      6849612.71
#Sta/Elev= 30
  4408.9 1727.29  4432.0 1723.29  4451.5 1722.65  4502.1 1721.26  4516.0 1723.31
  4542.1 1724.52  4573.0 1722.46  4582.2 1724.42  4612.2 1724.64  4652.2 1720.69
  4746.7 1718.93  4932.5 1718.06  4978.4 1713.82  4978.9 1713.32  4986.7 1713.82
  4992.5 1716.32  5005.4 1716.62  5162.7 1716.98  5192.7 1715.34  5232.7 1717.36
  5262.7 1715.35  5325.9 1717.79  5342.8 1715.23  5352.8 1717.99  5538.6 1717.66
  5592.8 1716.84  5662.9 1718.67  5702.9 1723.12  5822.9 1722.72  5878.2 1726.20
#Mann=8,-1,0
  4408.9   0.035       0  4451.5   0.063       0  4516.0   0.094       0
  4746.7   0.035       0  4978.4   0.035       0  4986.7   0.035       0
  5005.4    0.16       0  5538.6    0.07       0
Bank Sta=4978.4,4986.7
Exp/Cntr=0.3,0.1

Type RM Length L Ch R = 1,8427,696,696,696
BEGIN DESCRIPTION:
Tributary 1 to Little Elm Cr 8510.58
END DESCRIPTION:
XS GIS Cut Line= 3
      1561855.52      6851060.85      1561753.96      6850472.12
      1561840.50      6849411.07
#Sta/Elev= 30
  4458.3 1725.63  4540.4 1722.00  4663.2 1723.05  4723.0 1719.82  4851.2 1718.03
  4939.7 1717.30  4962.4 1718.21  4999.0 1717.45  5013.1 1713.32  5013.6 1712.82
  5021.4 1713.32  5022.3 1714.77  5029.5 1716.42  5039.6 1716.55  5130.5 1716.96
  5340.8 1717.86  5441.1 1717.63  5461.2 1716.46  5491.3 1717.87  5556.3 1717.55
  5571.6 1716.09  5681.9 1718.24  5752.2 1723.75  5832.4 1722.14  5872.8 1723.57
  5912.7 1726.59  6003.0 1726.82  6033.1 1728.44  6063.2 1727.43  6120.3 1728.02
#Mann=9,-1,0
  4458.3   0.063       0  4540.4   0.094       0  4851.2   0.035       0
  4939.7    0.16       0  5013.1    0.07       0  5021.4    0.16       0
  5039.6   0.035       0  5130.5    0.16       0  5556.3    0.07       0
Bank Sta=5013.1,5021.4
Exp/Cntr=0.3,0.1

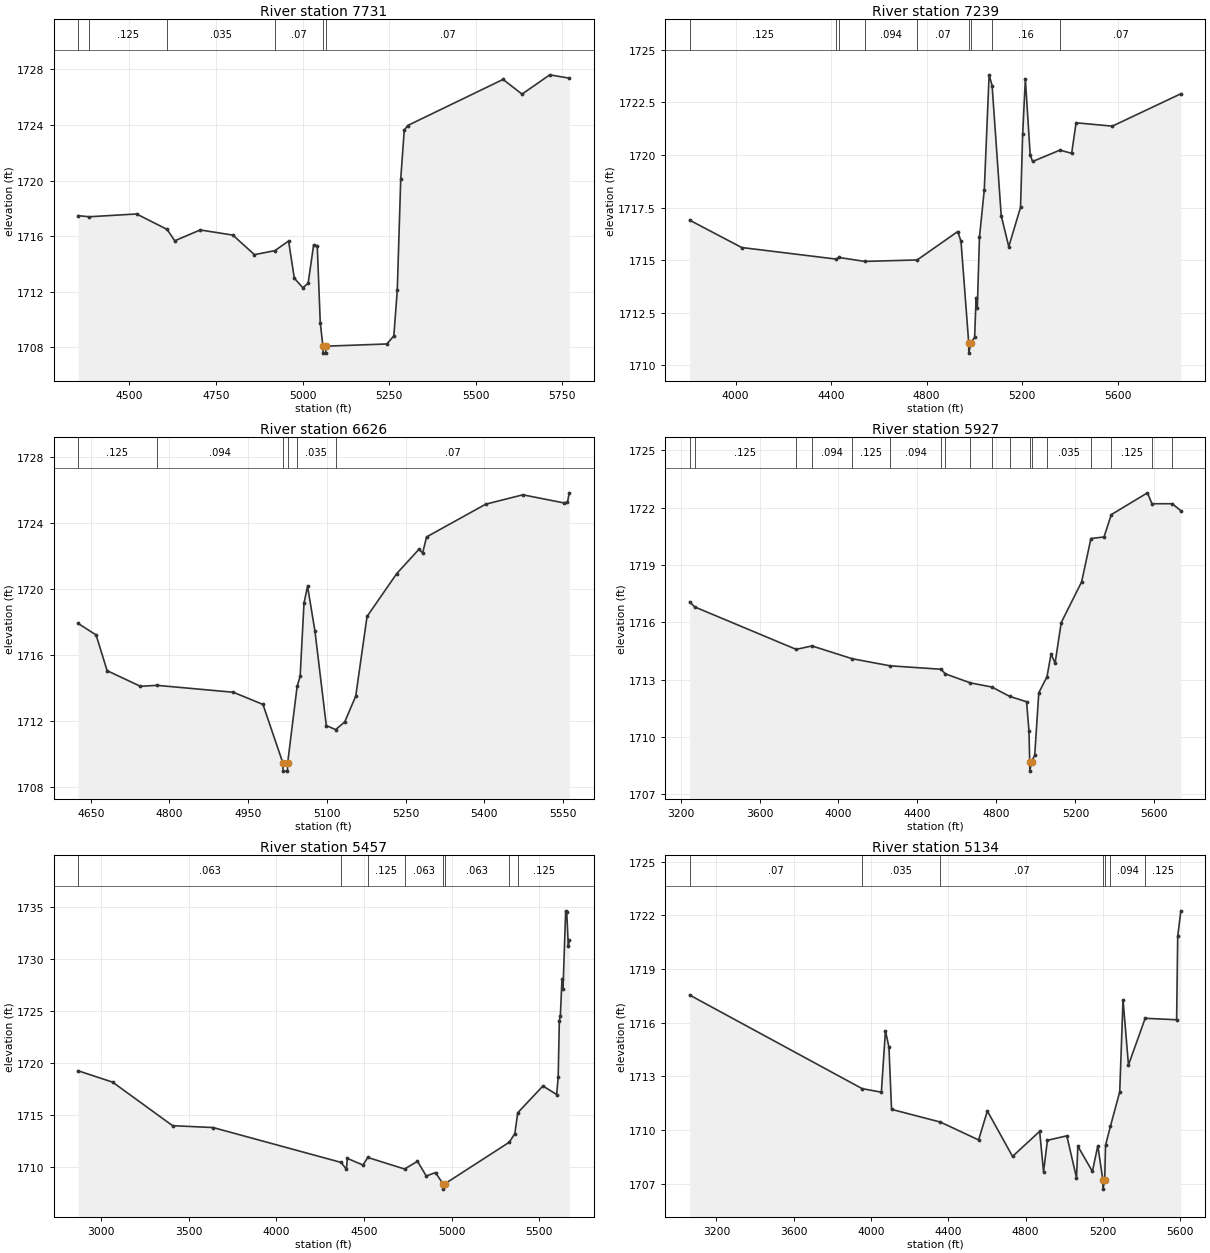
Type RM Length L Ch R = 1,7731,492,492,492
BEGIN DESCRIPTION:
Tributary 1 to Little Elm Cr 7852.01
END DESCRIPTION:
XS GIS Cut Line= 4
      1562073.90      6850720.02      1562332.83      6850294.27
      1562274.73      6850076.34      1562309.56      6849381.65
#Sta/Elev= 30
  4351.5 1717.47  4383.2 1717.39  4520.4 1717.59  4608.7 1716.48  4630.8 1715.66
  4704.4 1716.44  4798.6 1716.07  4861.1 1714.66  4920.0 1714.95  4959.8 1715.64
  4976.3 1712.97  5001.2 1712.27  5016.4 1712.62  5032.2 1715.37  5042.6 1715.31
  5051.3 1709.76  5059.0 1708.07  5059.5 1707.57  5067.0 1707.57  5067.5 1708.07
  5243.9 1708.23  5263.9 1708.81  5273.9 1712.11  5283.9 1720.12  5294.0 1723.62
  5304.0 1723.96  5579.6 1727.28  5634.4 1726.22  5714.5 1727.61  5770.9 1727.37
#Mann=6,-1,0
  4351.5   0.094       0  4383.2   0.125       0  4608.7   0.035       0
  4920.0    0.07       0  5059.0    0.07       0  5067.5    0.07       0
Bank Sta=5059,5067.5
Exp/Cntr=0.3,0.1

Type RM Length L Ch R = 1,7239,613,613,613
BEGIN DESCRIPTION:
Tributary 1 to Little Elm Cr 7428.44
END DESCRIPTION:
XS GIS Cut Line= 3
      1562167.29      6850677.28      1562811.18      6850509.91
      1562600.16      6849134.28
#Sta/Elev= 30
  3807.9 1716.90  4025.7 1715.60  4421.5 1715.05  4431.6 1715.13  4540.7 1714.94
  4760.8 1715.01  4930.4 1716.36  4944.1 1715.90  4976.4 1711.08  4976.9 1710.58
  4985.6 1711.08  5001.2 1711.33  5007.4 1713.22  5012.5 1712.73  5021.4 1716.08
  5041.7 1718.35  5061.9 1723.81  5074.4 1723.30  5112.5 1717.12  5144.2 1715.64
  5193.4 1717.51  5202.4 1720.99  5213.7 1723.61  5233.9 1720.00  5244.0 1719.69
  5358.3 1720.23  5407.6 1720.08  5426.1 1721.53  5577.9 1721.37  5864.9 1722.91
#Mann=9,-1,0
  3807.9   0.125       0  4421.5   0.094       0  4431.6   0.125       0
  4540.7   0.094       0  4760.8    0.07       0  4976.4    0.07       0
  4985.6    0.07       0  5074.4    0.16       0  5358.3    0.07       0
Bank Sta=4976.4,4985.6
Exp/Cntr=0.3,0.1

Type RM Length L Ch R = 1,6626,699,699,699
BEGIN DESCRIPTION:
Tributary 1 to Little Elm Cr 6474.49
END DESCRIPTION:
XS GIS Cut Line= 2
      1563033.50      6850444.80      1563670.45      6849758.54
#Sta/Elev= 30
  4625.8 1717.92  4660.1 1717.22  4681.1 1715.05  4744.7 1714.10  4776.0 1714.16
  4921.6 1713.74  4978.2 1713.00  5016.1 1709.45  5016.6 1708.95  5024.8 1708.95
  5025.3 1709.45  5043.3 1714.09  5049.1 1714.71  5056.4 1719.14  5063.2 1720.18
  5077.4 1717.43  5098.9 1711.72  5116.7 1711.47  5134.1 1711.94  5155.1 1713.51
  5176.6 1718.34  5233.3 1720.95  5275.8 1722.43  5282.6 1722.19  5290.0 1723.17
  5402.8 1725.16  5473.7 1725.73  5551.4 1725.24  5558.7 1725.28  5562.1 1725.85
#Mann=6,-1,0
  4625.8   0.125       0  4776.0   0.094       0  5016.1    0.07       0
  5025.3   0.094       0  5043.3   0.035       0  5116.7    0.07       0
Bank Sta=5016.1,5025.3
Exp/Cntr=0.3,0.1

Type RM Length L Ch R = 1,5927,470,470,470
BEGIN DESCRIPTION:
Tributary 1 to Little Elm Cr 5885.87
END DESCRIPTION:
XS GIS Cut Line= 3
      1562144.07      6850698.34      1563773.97      6850490.94
      1564591.74      6850280.31
#Sta/Elev= 30
  3246.4 1717.08  3272.0 1716.81  3785.7 1714.59  3865.7 1714.77  4069.5 1714.10
  4261.3 1713.73  4519.3 1713.55  4541.0 1713.31  4667.0 1712.84  4776.5 1712.62
  4867.3 1712.13  4952.5 1711.85  4964.7 1710.32  4968.4 1708.72  4968.9 1708.22
  4977.8 1708.72  4993.8 1709.05  5014.4 1712.32  5056.1 1713.16  5076.4 1714.35
  5097.0 1713.87  5128.0 1715.99  5231.3 1718.12  5278.5 1720.39  5344.9 1720.47
  5381.5 1721.64  5564.8 1722.78  5587.5 1722.21  5690.4 1722.21  5733.9 1721.84
#Mann=18,-1,0
  3246.4   0.094       0  3272.0   0.125       0  3785.7   0.063       0
  3865.7   0.094       0  4069.5   0.125       0  4261.3   0.094       0
  4519.3   0.125       0  4541.0   0.094       0  4667.0   0.063       0
  4776.5   0.094       0  4867.3   0.063       0  4968.4   0.063       0
  4977.8   0.063       0  5056.1   0.035       0  5278.5   0.063       0
  5381.5   0.125       0  5587.5   0.094       0  5690.4   0.063       0
Bank Sta=4968.4,4977.8
Exp/Cntr=0.3,0.1

Type RM Length L Ch R = 1,5457,323,323,323
BEGIN DESCRIPTION:
Tributary 1 to Little Elm Cr 5.0
END DESCRIPTION:
XS GIS Cut Line= 4
      1561989.48      6851011.93      1563537.58      6850840.18
      1564452.86      6850768.98      1564630.70      6850495.09
#Sta/Elev= 30
  2868.2 1719.25  3064.9 1718.16  3407.3 1713.98  3638.4 1713.80  4369.3 1710.45
  4399.1 1709.78  4404.2 1710.84  4493.4 1710.20  4520.9 1710.93  4731.0 1709.82
  4804.4 1710.56  4854.5 1709.15  4907.4 1709.48  4950.1 1708.39  4950.6 1707.89
  4959.6 1708.39  5328.1 1712.39  5359.9 1713.22  5376.4 1715.22  5520.1 1717.79
  5598.5 1716.97  5607.3 1718.68  5613.7 1724.04  5619.6 1724.52  5628.8 1728.02
  5634.8 1727.12  5649.9 1734.60  5655.9 1734.50  5665.0 1731.20  5670.4 1731.79
#Mann=8,-1,0
  2868.2   0.063       0  4369.3   0.035       0  4520.9   0.125       0
  4731.0   0.063       0  4950.1   0.063       0  4959.6   0.063       0
  5328.1   0.094       0  5376.4   0.125       0
Bank Sta=4950.1,4959.6
Exp/Cntr=0.3,0.1

Type RM Length L Ch R = 1,5134,344,344,344
BEGIN DESCRIPTION:
Tributary 1 to Little Elm Cr 5120.44
END DESCRIPTION:
XS GIS Cut Line= 4
      1562464.14      6851400.74      1563540.09      6851040.99
      1564455.37      6850969.79      1564667.03      6850528.24
#Sta/Elev= 30
  3061.4 1717.55  3953.7 1712.32  4053.5 1712.12  4074.5 1715.55  4092.7 1714.64
  4106.2 1711.16  4358.8 1710.45  4556.9 1709.45  4602.0 1711.07  4732.4 1708.53
  4872.8 1709.93  4892.9 1707.67  4913.0 1709.43  5013.3 1709.68  5063.4 1707.34
  5070.5 1709.10  5145.7 1707.69  5173.9 1709.13  5199.9 1707.20  5200.4 1706.70
  5209.4 1707.20  5213.7 1709.15  5239.4 1710.23  5287.2 1712.14  5304.3 1717.28
  5332.5 1713.64  5418.8 1716.25  5581.7 1716.17  5587.3 1720.83  5603.6 1722.26
#Mann=7,-1,0
  3061.4    0.07       0  3953.7   0.035       0  4358.8    0.07       0
  5199.9    0.07       0  5209.4    0.07       0  5239.4   0.094       0
  5418.8   0.125       0
Bank Sta=5199.9,5209.4
Exp/Cntr=0.3,0.1

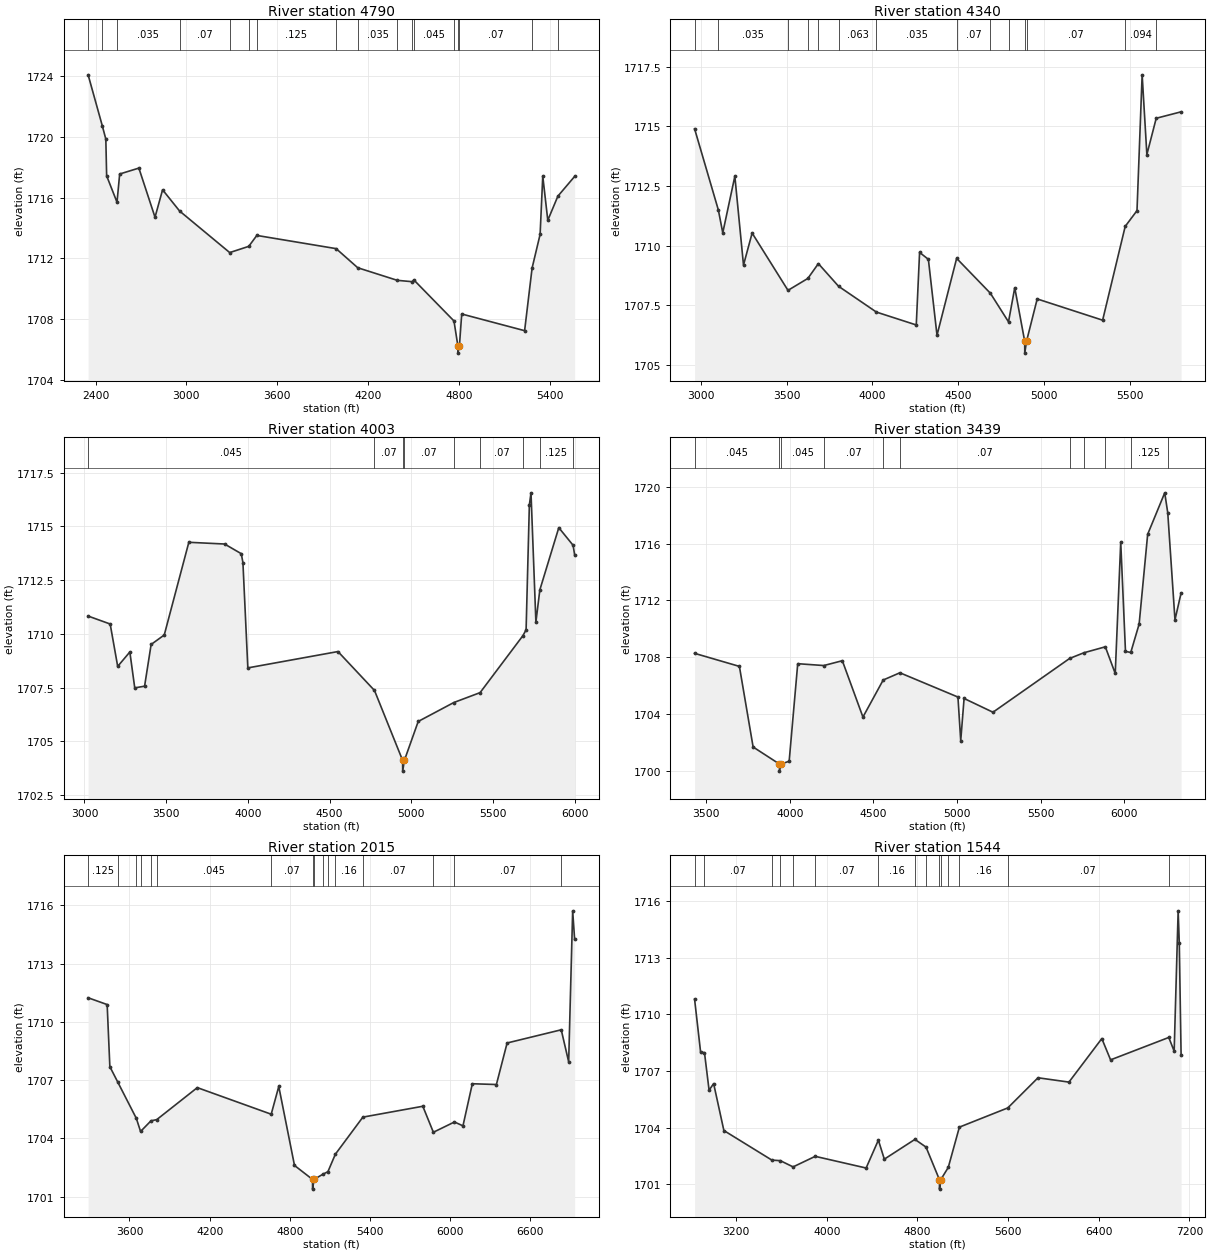
Type RM Length L Ch R = 1,4790,450,450,450
BEGIN DESCRIPTION:
Tributary 1 to Little Elm Cr 4962.47
END DESCRIPTION:
XS GIS Cut Line= 3
      1563819.45      6853662.37      1564449.86      6851950.76
      1564685.30      6850583.50
#Sta/Elev= 30
  2351.2 1724.10  2444.5 1720.75  2468.1 1719.86  2473.5 1717.44  2541.9 1715.70
  2559.5 1717.56  2686.2 1717.95  2792.8 1714.71  2842.7 1716.52  2955.1 1715.12
  3285.9 1712.38  3411.6 1712.79  3464.8 1713.51  3988.3 1712.64  4130.9 1711.38
  4391.8 1710.55  4490.7 1710.46  4501.1 1710.58  4766.2 1707.87  4791.6 1706.25
  4792.1 1705.75  4802.3 1706.25  4817.3 1708.33  5232.5 1707.23  5281.9 1711.36
  5334.8 1713.58  5352.3 1717.42  5385.5 1714.51  5452.1 1716.10  5562.6 1717.40
#Mann=17,-1,0
  2351.2   0.094       0  2444.5   0.063       0  2541.9   0.035       0
  2955.1    0.07       0  3285.9   0.035       0  3411.6   0.094       0
  3464.8   0.125       0  3988.3   0.094       0  4130.9   0.035       0
  4391.8    0.07       0  4490.7   0.035       0  4501.1   0.045       0
  4766.2    0.07       0  4791.6    0.07       0  4802.3    0.07       0
  5281.9   0.094       0  5452.1   0.125       0
Bank Sta=4791.6,4802.3
Exp/Cntr=0.3,0.1

Type RM Length L Ch R = 1,4340,337,337,337
BEGIN DESCRIPTION:
Tributary 1 to Little Elm Cr 4710.38
END DESCRIPTION:
XS GIS Cut Line= 3
      1564649.47      6853361.10      1564893.21      6851245.73
      1564861.00      6850541.33
#Sta/Elev= 30
  2963.5 1714.90  3101.9 1711.50  3127.7 1710.54  3198.1 1712.91  3248.5 1709.19
  3298.8 1710.53  3507.7 1708.13  3623.5 1708.63  3684.7 1709.25  3802.5 1708.30
  4022.7 1707.22  4255.1 1706.68  4274.4 1709.72  4325.6 1709.43  4375.9 1706.25
  4490.3 1709.47  4686.8 1708.01  4792.5 1706.81  4828.9 1708.24  4886.8 1706.00
  4887.3 1705.50  4897.6 1706.00  4959.7 1707.77  5340.9 1706.88  5472.4 1710.81
  5541.1 1711.47  5571.1 1717.16  5598.6 1713.82  5653.1 1715.34  5798.0 1715.61
#Mann=14,-1,0
  2963.5   0.063       0  3101.9   0.035       0  3507.7    0.07       0
  3623.5   0.125       0  3684.7    0.07       0  3802.5   0.063       0
  4022.7   0.035       0  4490.3    0.07       0  4686.8   0.045       0
  4792.5    0.07       0  4886.8    0.07       0  4897.6    0.07       0
  5472.4   0.094       0  5653.1   0.125       0
Bank Sta=4886.8,4897.6
Exp/Cntr=0.3,0.1

Type RM Length L Ch R = 1,4003,564,564,564
BEGIN DESCRIPTION:
Tributary 1 to Little Elm Cr 4003.171
END DESCRIPTION:
XS GIS Cut Line= 3
      1565026.14      6853432.62      1565175.24      6851480.90
      1565200.47      6850461.11
#Sta/Elev= 30
  3022.5 1710.83  3157.5 1710.46  3203.5 1708.49  3277.9 1709.16  3307.9 1707.49
  3368.1 1707.57  3408.2 1709.51  3488.5 1709.95  3638.9 1714.26  3857.7 1714.18
  3959.8 1713.73  3969.9 1713.32  4000.0 1708.42  4551.6 1709.18  4775.2 1707.37
  4947.3 1704.12  4947.8 1703.62  4958.1 1704.12  5042.8 1705.93  5260.7 1706.81
  5421.5 1707.27  5683.7 1709.92  5703.0 1710.19  5723.0 1716.00  5733.0 1716.56
  5763.0 1710.55  5787.2 1712.05  5903.1 1714.94  5990.7 1714.12  6000.0 1713.68
#Mann=9,-1,0
  3022.5   0.045       0  4775.2    0.07       0  4947.3    0.07       0
  4958.1    0.07       0  5260.7    0.16       0  5421.5    0.07       0
  5683.7   0.035       0  5787.2   0.125       0  5990.7   0.094       0
Bank Sta=4947.3,4958.1
Exp/Cntr=0.3,0.1

Type RM Length L Ch R = 1,3439,1424,1424,1424
BEGIN DESCRIPTION:
Tributary 1 to Little Elm Cr 3439.024
END DESCRIPTION:
XS GIS Cut Line= 4
      1565292.83      6853159.21      1565648.96      6851629.82
      1565830.86      6850874.60      1565715.73      6850322.19
#Sta/Elev= 30
  3429.7 1708.27  3697.9 1707.35  3780.0 1701.67  3937.3 1700.47  3937.8 1699.97
  3948.2 1700.47  3995.7 1700.67  4047.0 1707.54  4202.9 1707.41  4313.9 1707.75
  4437.2 1703.78  4558.4 1706.39  4658.3 1706.90  5005.7 1705.19  5022.4 1702.12
  5042.5 1705.09  5215.4 1704.12  5674.1 1707.91  5759.4 1708.31  5887.7 1708.73
  5947.0 1706.85  5979.9 1716.10  6008.3 1708.41  6039.9 1708.33  6090.0 1710.33
  6141.1 1716.66  6243.2 1719.58  6261.3 1718.17  6304.5 1710.63  6341.1 1712.52
#Mann=11,-1,0
  3429.7   0.045       0  3937.3    0.07       0  3948.2   0.045       0
  4202.9    0.07       0  4558.4    0.16       0  4658.3    0.07       0
  5674.1    0.16       0  5759.4    0.07       0  5887.7   0.035       0
  6039.9   0.125       0  6261.3   0.063       0
Bank Sta=3937.3,3948.2
Exp/Cntr=0.3,0.1

Type RM Length L Ch R = 1,2015,471,471,471
BEGIN DESCRIPTION:
Tributary 1 to Little Elm Cr 3.0
END DESCRIPTION:
XS GIS Cut Line= 3
      1565317.07      6854163.14      1566052.98      6851958.51
      1565983.80      6850643.44
#Sta/Elev= 30
  3290.5 1711.24  3433.0 1710.89  3453.2 1707.69  3511.3 1706.91  3651.1 1705.03
  3683.1 1704.35  3761.1 1704.90  3803.9 1704.96  4107.7 1706.61  4660.8 1705.24
  4717.4 1706.67  4835.1 1702.60  4970.0 1701.88  4970.5 1701.38  4981.0 1701.88
  5048.5 1702.15  5085.3 1702.28  5141.0 1703.18  5346.9 1705.09  5795.5 1705.65
  5874.4 1704.31  6032.3 1704.84  6095.9 1704.64  6166.0 1706.81  6346.2 1706.77
  6426.3 1708.91  6831.4 1709.59  6887.0 1707.94  6917.0 1715.72  6931.6 1714.25
#Mann=16,-1,0
  3290.5   0.125       0  3511.3   0.094       0  3651.1   0.045       0
  3683.1   0.035       0  3761.1    0.07       0  3803.9   0.045       0
  4660.8    0.07       0  4970.0    0.07       0  4981.0    0.07       0
  5048.5    0.16       0  5085.3    0.07       0  5141.0    0.16       0
  5346.9    0.07       0  5874.4    0.16       0  6032.3    0.07       0
  6831.4   0.035       0
Bank Sta=4970,4981
Exp/Cntr=0.3,0.1

Type RM Length L Ch R = 1,1544,0,0,0
BEGIN DESCRIPTION:
Tributary 1 to Little Elm Cr 1.0
END DESCRIPTION:
XS GIS Cut Line= 3
      1566024.87      6854895.41      1566269.15      6852343.67
      1566083.44      6850622.26
#Sta/Elev= 30
  2832.2 1710.81  2885.4 1708.00  2919.7 1707.97  2960.2 1705.98  3000.4 1706.33
  3090.8 1703.84  3514.5 1702.27  3589.4 1702.24  3701.7 1701.91  3897.3 1702.47
  4346.5 1701.85  4454.6 1703.33  4507.2 1702.32  4777.3 1703.37  4875.4 1702.96
  4993.8 1701.23  4994.3 1700.73  5005.2 1701.23  5071.6 1701.88  5169.8 1704.02
  5597.1 1705.04  5864.0 1706.64  6137.1 1706.41  6427.2 1708.72  6504.6 1707.59
  7018.4 1708.78  7065.9 1708.05  7101.1 1715.50  7111.2 1713.77  7127.0 1707.86
#Mann=15,-1,0
  2832.2   0.035       0  2919.7    0.07       0  3514.5    0.16       0
  3589.4    0.07       0  3701.7    0.16       0  3897.3    0.07       0
  4454.6    0.16       0  4777.3    0.07       0  4875.4    0.16       0
  4993.8    0.07       0  5005.2    0.16       0  5071.6    0.07       0
  5169.8    0.16       0  5597.1    0.07       0  7018.4   0.035       0
Bank Sta=4993.8,5005.2
Exp/Cntr=0.3,0.1

Chan Stop Cuts=-1