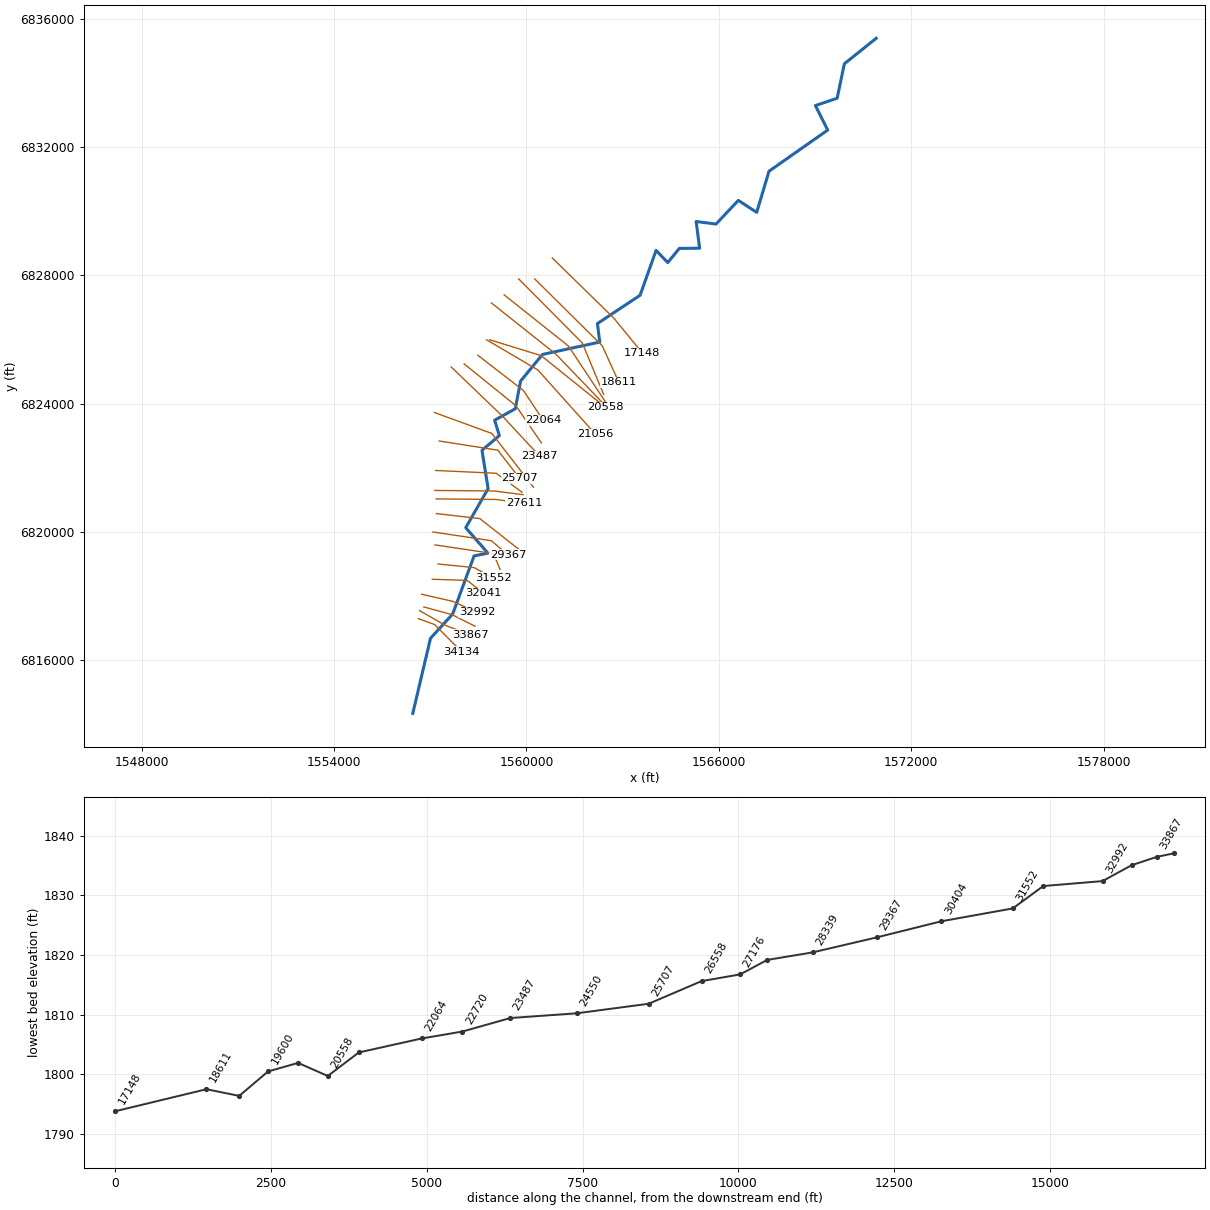
--- T1 to Elm Creek.prj (project) ---

Proj Title=Tributary No. 1 to Elm Creek Base Level Engineering
Current Plan=p01
Default Exp/Contr=0.3,0.1
English Units
Geom File=g01
Flow File=f01
Plan File=p01
Y Axis Title=Elevation
X Axis Title(PF)=Main Channel Distance
X Axis Title(XS)=Station
BEGIN DESCRIPTION:
Tributary No. 1 to Elm Creek
END DESCRIPTION:
DSS Export Rating Curves= 0
DSS Export Rating Curve Sorted= 0
DSS Export Volume Flow Curves= 0
DXF OffsetX= 0
DXF OffsetY= 0
DXF ScaleX= 1
DXF ScaleY= 10

--- T1 to Elm Creek.p01 (plan) ---

Plan Title=Multiple Run
Program Version=4.10
Short Identifier=Multiple
Geom File=g01
Flow File=f01
Subcritical Flow
K Sum by GR= 0
Std Step Tol= 0.01
Critical Tol= 0.01
Num of Std Step Trials= 20
Max Error Tol= 0.3
Flow Tol Ratio= 0.001
Split Flow NTrial= 30
Split Flow Tol= 0.02
Split Flow Ratio= 0.02
Log Output Level= 0
Friction Slope Method= 1
Unsteady Friction Slope Method= 2
Unsteady Bridges Friction Slope Method= 1
Parabolic Critical Depth
Global Vel Dist= 1 , 1 , 1
Global Log Level= 0
CheckData=True
Encroach Param=-1 ,0,0, 0
BEGIN DESCRIPTION:
Multiple Run
END DESCRIPTION:
Computation Interval=1HOUR
Output Interval=1HOUR
Run HTab= 0
Run UNet= 0
Run PostProcess= 0
Run WQNet= 0
UNET Theta= 1
UNET Theta Warmup= 1
UNET ZTol= 0.02
UNET ZSATol= 0.05
UNET MxIter= 20
UNET MaxInSteps= 0
UNET DtIC= 0
UNET DtMin= 0
UNET MaxCRTS= 20
UNET WFStab= 2
UNET SFStab= 1
UNET WFX= 1
UNET SFX= 1
UNET DSS MLevel= 4
UNET DZMax Abort= 100
UNET Convert EG Bridges= 0
UNET Use Existing IB Tables=-1
UNET Froude Reduction=False
UNET Froude Limit= 1
UNET Froude Power= 10
UNET Time Slicing=0,0, 5
UNET Junction Losses=0
Instantaneous Interval=1HOUR
Write IC File= 0
Write IC File at Sim End=0
Echo Input=False
Echo Parameters=False
Echo Output=False
Write Detailed= 0
WQ AD Non Conservative
WQ ULTIMATE=-1
WQ Max Comp Step=1HOUR
WQ Output Interval=15MIN
WQ Output Selected Increments= 0
WQ Output face flow=0
WQ Output face velocity=0
WQ Output face area=0
WQ Output face dispersion=0
WQ Output cell volume=0
WQ Output cell surface area=0
WQ Output cell continuity=0
WQ Output cumulative cell continuity=0
WQ Output face conc=0
WQ Output face dconc_dx=0
WQ Output face courant=0
WQ Output face peclet=0
WQ Output face adv mass=0
WQ Output face disp mass=0
WQ Output cell mass=0
WQ Output cell source sink temp=0
WQ Output cell source sink nsm=0
WQ Output MaxMinRange=-1
WQ Daily Max Min Mean=-1
WQ Daily Range=0
WQ Daily Time=0
WQ Create Restart=0
WQ Fixed Restart=0
WQ System Summary=0
WQ Use Fixed Temperature=0
Sorting and Armoring Iterations= 10
XS Update Threshold= 0.02
Hydraulics Update Threshold= 0.02
Energy Slope Method= 1
Volume Change Method= 0
XS Weighting Method= 0
Number of US Weighted Cross Sections= 1
Number of DS Weighted Cross Sections= 1
Upstream XS Weight=0.25
Main XS Weight=0.5
Downstream XS Weight=0.25
Number of DS XS's Weighted with US Boundary= 1
Upstream Boundary Weight= 1
Weight of XSs Associated with US Boundary= 0
Number of US XS's Weighted with DS Boundary= 1
Downstream Boundary Weight= 0.5
Weight of XSs Associated with DS Boundary= 0.5
Sediment Output Level= 4
Mass or Volume Output= 0
Output Increment Type= 1
Profile and TS Output Increment= 10
XS Output Flag= 0
XS Output Increment= 10
Disregard all LS=0
Disregard all Conn=0
Disregard all Breaches=0
Disregard all Pumps=0

--- T1 to Elm Creek.f01 (steady flow) ---

Flow Title=Multiple
Number of Profiles=7
Profile Names=10-year,25-year,50-year,1pct_min,100-year,1pct_plu,500-year
River Rch & RM= Tributary No. 1 ,Reach-1,34134
     282     388     474     288     574    1145     853
River Rch & RM= Tributary No. 1 ,Reach-1,23487
     457     642     796     489     976    1948    1491
River Rch & RM= Tributary No. 1 ,Reach-1,14267
     496     698     865     532    1062    2119    1622
River Rch & RM= Tributary No. 1 ,Reach-1,6939
     539     760     944     581    1159    2313    1776
Boundary for River Rch & Prof#=Tributary No. 1 ,Reach-1,1
Up Type=0
Dn Type=3
Dn Slope=0.005
Boundary for River Rch & Prof#=Tributary No. 1 ,Reach-1,2
Up Type=0
Dn Type=3
Dn Slope=0.005
Boundary for River Rch & Prof#=Tributary No. 1 ,Reach-1,3
Up Type=0
Dn Type=3
Dn Slope=0.005
Boundary for River Rch & Prof#=Tributary No. 1 ,Reach-1,4
Up Type=0
Dn Type=3
Dn Slope=0.005
Boundary for River Rch & Prof#=Tributary No. 1 ,Reach-1,5
Up Type=0
Dn Type=3
Dn Slope=0.005
Boundary for River Rch & Prof#=Tributary No. 1 ,Reach-1,6
Up Type=0
Dn Type=3
Dn Slope=0.005
Boundary for River Rch & Prof#=Tributary No. 1 ,Reach-1,7
Up Type=0
Dn Type=3
Dn Slope=0.005

--- T1 to Elm Creek.g01 (geometry) ---

Geom Title=Existing Conditions

River Reach=Tributary No. 1 ,Reach-1
Reach XY= 30
      1556455.00      6814338.00      1557007.90      6816680.08
      1557699.17      6817435.70      1558365.94      6819248.02
      1558797.42      6819334.65      1558105.63      6820128.29
      1558803.84      6821347.44      1558613.02      6822541.31
      1559153.61      6822999.48      1559008.08      6823480.32
      1559649.95      6823835.72      1559818.23      6824701.81
      1560498.88      6825529.92      1562285.62      6825917.35
      1562213.02      6826494.34      1563541.63      6827374.22
      1564041.32      6828774.74      1564404.99      6828395.07
      1564766.35      6828836.65      1565399.82      6828843.44
      1565291.36      6829675.06      1565911.76      6829597.12
      1566606.03      6830334.54      1567179.41      6829960.68
      1567563.14      6831244.06      1569394.52      6832528.20
      1569009.96      6833290.53      1569688.55      6833520.86
      1569912.73      6834594.50      1570905.00      6835388.00

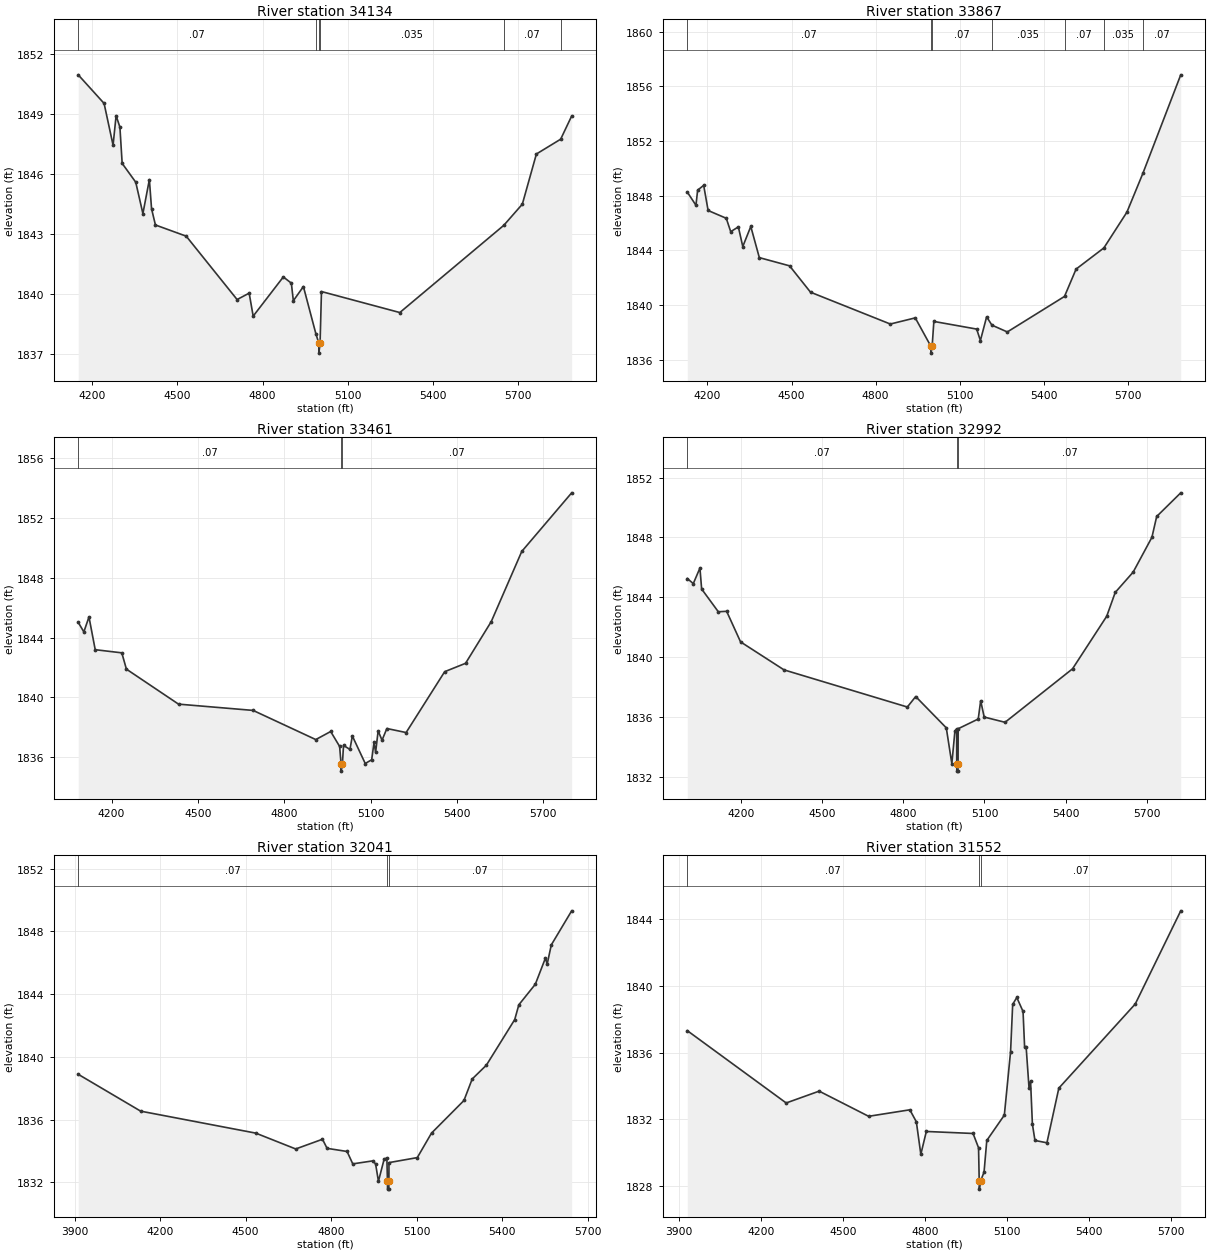
Type RM Length L Ch R = 1,34134,267,267,267
BEGIN DESCRIPTION:
Tributary No. 1 to Elm Creek 39.0
END DESCRIPTION:
XS GIS Cut Line= 3
      1556629.76      6817292.64      1557138.76      6817106.12
      1557980.21      6816257.60
#Sta/Elev= 30
  4150.9 1850.96  4242.0 1849.53  4273.6 1847.44  4284.3 1848.92  4297.7 1848.34
  4305.6 1846.53  4353.4 1845.59  4378.6 1844.02  4401.4 1845.72  4409.1 1844.26
  4422.7 1843.45  4531.1 1842.89  4710.2 1839.72  4752.7 1840.04  4766.8 1838.89
  4872.9 1840.85  4901.2 1840.54  4908.2 1839.66  4943.6 1840.37  4987.7 1838.00
  4997.8 1837.54  4998.1 1837.04  5002.3 1837.54  5007.2 1840.12  5283.0 1839.07
  5648.9 1843.43  5714.3 1844.49  5763.8 1847.00  5849.2 1847.74  5888.0 1848.90
#Mann=6,-1,0
  4150.9    0.07       0  4987.7   0.035       0  4997.8   0.035       0
  5002.3   0.035       0  5648.9    0.07       0  5849.2   0.035       0
Bank Sta=4997.8,5002.3
Exp/Cntr=0.3,0.1

Type RM Length L Ch R = 1,33867,406,406,406
BEGIN DESCRIPTION:
Tributary No. 1 to Elm Creek 38.0
END DESCRIPTION:
XS GIS Cut Line= 3
      1556668.12      6817541.51      1557473.50      6817081.10
      1558254.95      6816788.02
#Sta/Elev= 30
  4127.8 1848.26  4158.8 1847.29  4164.8 1848.40  4186.4 1848.75  4202.2 1846.91
  4267.0 1846.34  4282.9 1845.36  4310.2 1845.71  4326.0 1844.27  4354.6 1845.74
  4385.1 1843.46  4493.0 1842.86  4567.9 1840.93  4852.9 1838.60  4942.0 1839.05
  4997.8 1836.97  4998.1 1836.47  5002.3 1836.97  5008.4 1838.79  5161.3 1838.23
  5174.6 1837.39  5196.9 1839.13  5215.6 1838.52  5270.7 1838.02  5475.0 1840.62
  5516.3 1842.62  5615.6 1844.17  5697.9 1846.79  5754.9 1849.63  5890.1 1856.84
#Mann=7,-1,0
  4127.8    0.07       0  4997.8    0.07       0  5002.3    0.07       0
  5215.6   0.035       0  5475.0    0.07       0  5615.6   0.035       0
  5754.9    0.07       0
Bank Sta=4997.8,5002.3
Exp/Cntr=0.3,0.1

Type RM Length L Ch R = 1,33461,469,469,469
BEGIN DESCRIPTION:
Tributary No. 1 to Elm Creek 37.0
END DESCRIPTION:
XS GIS Cut Line= 3
      1556798.93      6817657.58      1557681.99      6817414.53
      1558396.05      6817055.58
#Sta/Elev= 30
  4084.1 1845.02  4103.7 1844.38  4121.5 1845.38  4143.2 1843.19  4235.6 1842.98
  4251.6 1841.89  4432.7 1839.55  4692.0 1839.13  4909.8 1837.18  4961.6 1837.72
  4992.7 1836.72  4997.6 1835.57  4998.0 1835.07  5002.4 1835.57  5006.2 1836.79
  5028.5 1836.52  5036.9 1837.42  5081.7 1835.58  5104.1 1835.83  5112.2 1836.99
  5117.8 1836.33  5126.5 1837.76  5140.1 1837.14  5156.9 1837.92  5223.8 1837.65
  5357.8 1841.72  5430.4 1842.28  5519.7 1845.07  5625.7 1849.76  5799.2 1853.68
#Mann=3,-1,0
  4084.1    0.07       0  4997.6    0.07       0  5002.4    0.07       0
Bank Sta=4997.6,5002.4
Exp/Cntr=0.3,0.1

Type RM Length L Ch R = 1,32992,951,951,951
BEGIN DESCRIPTION:
Tributary No. 1 to Elm Creek 36.0
END DESCRIPTION:
XS GIS Cut Line= 3
      1556733.38      6818053.18      1557704.99      6817830.09
      1558454.97      6817488.02
#Sta/Elev= 30
  4003.1 1845.26  4025.3 1844.92  4049.8 1845.96  4056.1 1844.56  4117.6 1843.04
  4148.4 1843.07  4199.7 1841.03  4360.1 1839.16  4815.3 1836.68  4846.1 1837.38
  4959.0 1835.29  4979.5 1832.90  4990.9 1835.08  4997.4 1835.23  4997.6 1832.90
  4997.9 1832.40  5002.1 1832.40  5002.5 1832.90  5002.8 1835.23  5076.9 1835.88
  5085.9 1837.10  5098.9 1836.01  5175.9 1835.66  5424.9 1839.23  5551.1 1842.74
  5582.5 1844.33  5648.8 1845.69  5717.9 1848.01  5735.5 1849.40  5824.3 1850.98
#Mann=3,-1,0
  4003.1    0.07       0  4997.6    0.07       0  5002.5    0.07       0
Bank Sta=4997.6,5002.5
Exp/Cntr=0.3,0.1

Type RM Length L Ch R = 1,32041,489,489,489
BEGIN DESCRIPTION:
Tributary No. 1 to Elm Creek 35.0
END DESCRIPTION:
XS GIS Cut Line= 3
      1557062.59      6818519.95      1558149.15      6818485.71
      1558655.02      6818087.98
#Sta/Elev= 30
  3912.9 1838.89  4132.0 1836.54  4535.6 1835.14  4675.7 1834.13  4769.6 1834.75
  4785.7 1834.17  4855.8 1833.97  4875.8 1833.18  4945.8 1833.37  4955.8 1833.18
  4965.8 1832.07  4985.8 1833.48  4995.4 1833.56  4997.4 1832.07  4997.8 1831.57
  5002.2 1831.57  5002.6 1832.07  5002.7 1833.26  5102.1 1833.58  5151.9 1835.14
  5265.7 1837.22  5294.6 1838.59  5344.3 1839.47  5443.8 1842.38  5458.2 1843.32
  5516.0 1844.63  5551.3 1846.29  5557.6 1845.92  5572.1 1847.14  5643.5 1849.31
#Mann=3,-1,0
  3912.9    0.07       0  4997.4    0.07       0  5002.6    0.07       0
Bank Sta=4997.4,5002.6
Exp/Cntr=0.3,0.1

Type RM Length L Ch R = 1,31552,1148,1148,1148
BEGIN DESCRIPTION:
Tributary No. 1 to Elm Creek 34.0
END DESCRIPTION:
XS GIS Cut Line= 3
      1557245.04      6818995.51      1558366.28      6818884.35
      1558960.81      6818558.74
#Sta/Elev= 30
  3929.8 1837.33  4291.5 1832.99  4412.1 1833.70  4593.0 1832.19  4743.7 1832.58
  4767.5 1831.86  4783.9 1829.91  4804.0 1831.28  4974.9 1831.16  4995.0 1830.30
  4997.4 1828.32  4997.8 1827.82  5002.6 1828.32  5015.1 1828.84  5025.1 1830.74
  5089.3 1832.26  5112.1 1836.07  5119.8 1838.91  5134.9 1839.32  5157.7 1838.48
  5163.4 1836.35  5169.1 1836.33  5179.5 1833.91  5185.2 1834.30  5191.9 1831.72
  5201.3 1830.74  5245.0 1830.60  5288.6 1833.88  5568.1 1838.93  5734.4 1844.52
#Mann=3,-1,0
  3929.8    0.07       0  4997.4    0.07       0  5002.6    0.07       0
Bank Sta=4997.4,5002.6
Exp/Cntr=0.3,0.1

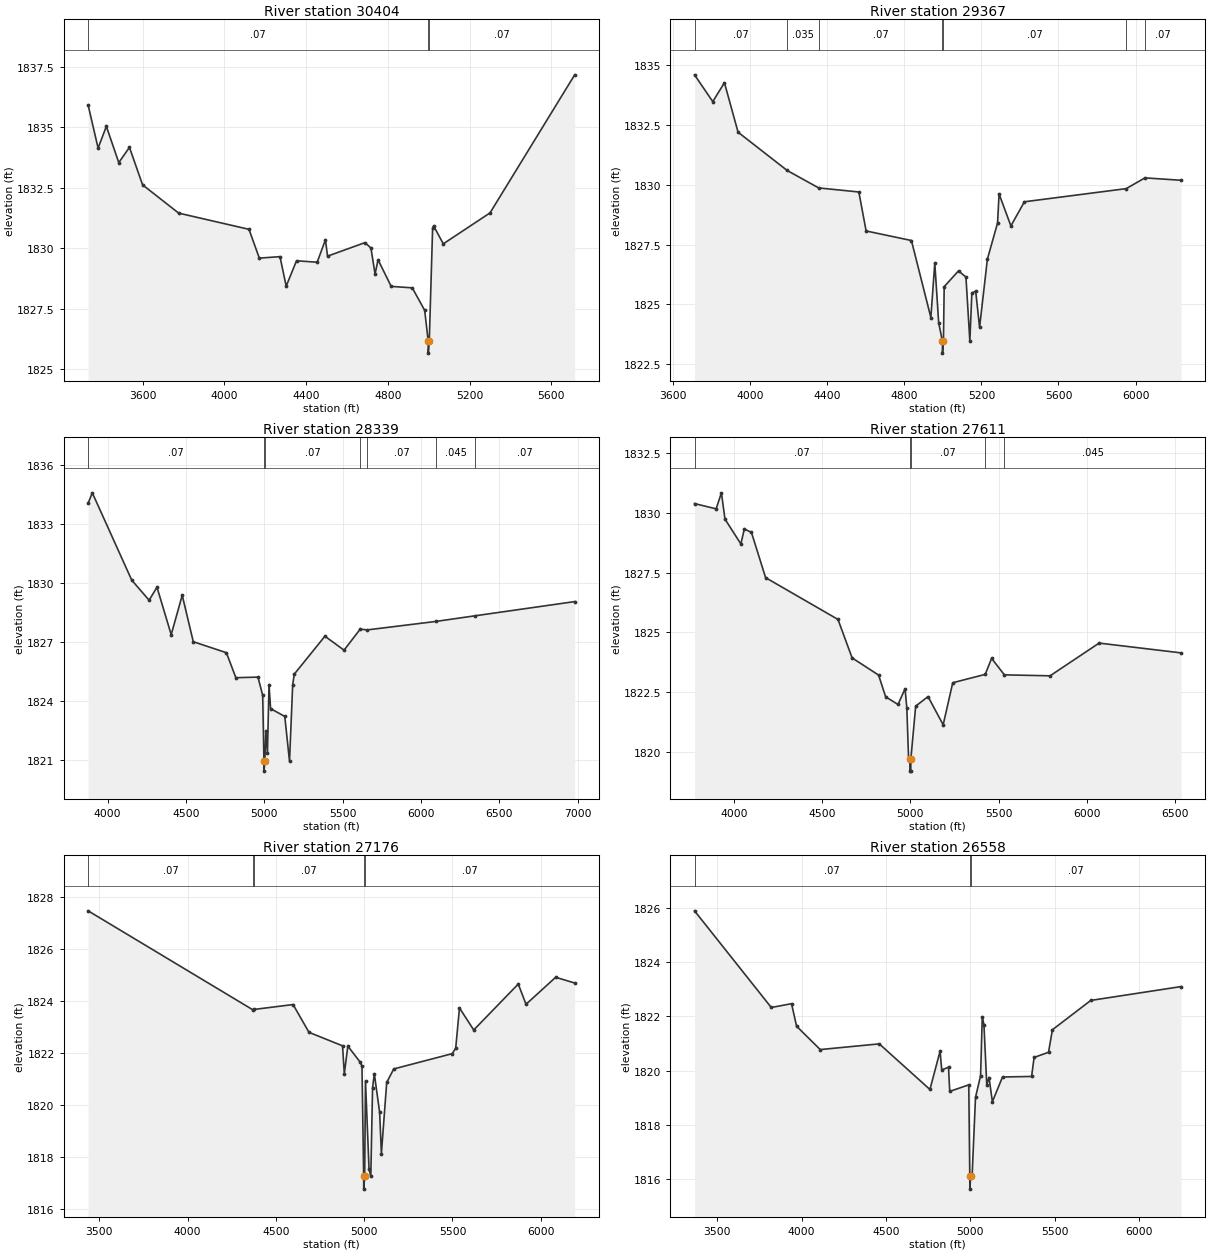
Type RM Length L Ch R = 1,30404,1037,1037,1037
BEGIN DESCRIPTION:
Tributary No. 1 to Elm Creek 33.5
END DESCRIPTION:
XS GIS Cut Line= 3
      1557146.77      6819592.38      1558971.33      6819319.96
      1559176.71      6818825.61
#Sta/Elev= 30
  3333.8 1835.92  3382.6 1834.14  3423.0 1835.04  3483.7 1833.54  3536.0 1834.17
  3600.2 1832.62  3776.9 1831.45  4120.7 1830.78  4171.2 1829.59  4272.3 1829.65
  4302.7 1828.43  4353.2 1829.48  4454.3 1829.42  4494.8 1830.35  4504.9 1829.67
  4687.9 1830.23  4717.2 1830.01  4737.4 1828.93  4752.1 1829.52  4816.3 1828.42
  4919.4 1828.36  4980.1 1827.43  4997.4 1826.16  4997.8 1825.66  5002.6 1826.16
  5019.0 1830.83  5024.1 1830.92  5071.1 1830.18  5299.8 1831.46  5713.9 1837.17
#Mann=3,-1,0
  3333.8    0.07       0  4997.4    0.07       0  5002.6    0.07       0
Bank Sta=4997.4,5002.6
Exp/Cntr=0.3,0.1

Type RM Length L Ch R = 1,29367,1028,1028,1028
BEGIN DESCRIPTION:
Tributary No. 1 to Elm Creek 33.2
END DESCRIPTION:
XS GIS Cut Line= 3
      1557081.38      6819994.90      1558905.88      6819722.48
      1559423.43      6819279.61
#Sta/Elev= 30
  3710.5 1834.60  3805.2 1833.48  3865.8 1834.27  3936.6 1832.20  4191.4 1830.60
  4354.9 1829.87  4563.5 1829.70  4601.3 1828.07  4836.5 1827.67  4937.4 1824.45
  4957.8 1826.73  4978.0 1824.23  4997.4 1823.46  4997.8 1822.96  5002.7 1823.46
  5006.6 1825.74  5080.9 1826.40  5119.6 1826.14  5139.8 1823.46  5150.2 1825.47
  5170.1 1825.55  5190.3 1824.04  5230.8 1826.89  5283.6 1828.40  5291.5 1829.62
  5352.9 1828.28  5422.9 1829.29  5951.5 1829.84  6048.6 1830.29  6236.4 1830.19
#Mann=7,-1,0
  3710.5    0.07       0  4191.4   0.035       0  4354.9    0.07       0
  4997.4    0.07       0  5002.7    0.07       0  5951.5   0.045       0
  6048.6    0.07       0
Bank Sta=4997.4,5002.7
Exp/Cntr=0.3,0.1

Type RM Length L Ch R = 1,28339,728,728,728
BEGIN DESCRIPTION:
Tributary No. 1 to Elm Creek 33.0
END DESCRIPTION:
XS GIS Cut Line= 3
      1557188.50      6820568.38      1558544.30      6820412.70
      1559910.98      6819336.58
#Sta/Elev= 30
  3875.5 1834.07  3902.2 1834.60  4153.8 1830.16  4264.5 1829.14  4314.9 1829.80
  4405.5 1827.39  4475.9 1829.39  4546.4 1827.03  4757.8 1826.47  4818.1 1825.20
  4959.1 1825.23  4989.3 1824.30  4997.3 1820.95  4997.8 1820.45  5002.7 1820.95
  5009.4 1822.48  5019.5 1821.38  5029.5 1824.85  5039.6 1823.63  5130.2 1823.23
  5160.4 1820.95  5180.5 1824.83  5190.6 1825.38  5386.3 1827.31  5508.3 1826.60
  5611.4 1827.67  5655.9 1827.63  6093.1 1828.06  6346.2 1828.35  6979.7 1829.07
#Mann=7,-1,0
  3875.5    0.07       0  4997.3    0.07       0  5002.7    0.07       0
  5611.4   0.045       0  5655.9    0.07       0  6093.1   0.045       0
  6346.2    0.07       0
Bank Sta=4997.3,5002.7
Exp/Cntr=0.3,0.1

Type RM Length L Ch R = 1,27611,435,435,435
BEGIN DESCRIPTION:
Tributary No. 1 to Elm Creek 32.2
END DESCRIPTION:
XS GIS Cut Line= 3
      1557182.56      6821025.56      1559033.80      6821009.06
      1559930.83      6820893.95
#Sta/Elev= 30
  3777.6 1830.39  3900.0 1830.17  3930.0 1830.84  3950.0 1829.74  4040.1 1828.70
  4059.8 1829.33  4100.1 1829.18  4180.1 1827.29  4590.1 1825.54  4670.1 1823.93
  4820.1 1823.21  4860.1 1822.30  4930.1 1821.98  4970.1 1822.64  4980.1 1821.82
  4990.1 1819.69  4997.2 1819.69  4997.7 1819.19  5002.4 1819.19  5002.8 1819.69
  5030.1 1821.91  5100.1 1822.31  5185.8 1821.13  5240.1 1822.89  5424.0 1823.24
  5460.1 1823.91  5532.4 1823.22  5791.4 1823.18  6069.0 1824.55  6533.3 1824.14
#Mann=5,-1,0
  3777.6    0.07       0  4997.2    0.07       0  5002.8    0.07       0
  5424.0   0.035       0  5532.4   0.045       0
Bank Sta=4997.2,5002.8
Exp/Cntr=0.3,0.1

Type RM Length L Ch R = 1,27176,618,618,618
BEGIN DESCRIPTION:
Tributary No. 1 to Elm Creek 32.0
END DESCRIPTION:
XS GIS Cut Line= 3
      1557144.77      6821289.22      1558995.99      6821272.71
      1559891.85      6821157.75
#Sta/Elev= 30
  3437.3 1827.48  4369.1 1823.67  4375.0 1823.68  4597.6 1823.87  4687.6 1822.80
  4877.6 1822.28  4887.6 1821.20  4907.6 1822.27  4977.6 1821.65  4987.6 1821.49
  4997.2 1817.26  4997.7 1816.76  5002.8 1817.26  5007.6 1820.91  5027.6 1817.53
  5037.6 1817.26  5047.6 1820.67  5057.6 1821.20  5087.6 1819.72  5097.6 1818.13
  5127.6 1820.87  5167.6 1821.39  5499.3 1821.98  5518.2 1822.19  5539.6 1823.74
  5620.3 1822.89  5872.4 1824.66  5916.3 1823.88  6084.1 1824.92  6191.8 1824.70
#Mann=5,-1,0
  3437.3    0.07       0  4369.1   0.035       0  4375.0    0.07       0
  4997.2    0.07       0  5002.8    0.07       0
Bank Sta=4997.2,5002.8
Exp/Cntr=0.3,0.1

Type RM Length L Ch R = 1,26558,851,851,851
BEGIN DESCRIPTION:
Tributary No. 1 to Elm Creek 31.5
END DESCRIPTION:
XS GIS Cut Line= 3
      1557170.31      6821912.21      1559055.87      6821826.02
      1559859.49      6821234.12
#Sta/Elev= 30
  3364.8 1825.89  3820.0 1822.33  3940.1 1822.47  3970.1 1821.64  4110.3 1820.78
  4460.6 1820.99  4760.9 1819.31  4821.0 1820.72  4831.0 1820.03  4871.1 1820.13
  4878.3 1819.24  4991.2 1819.48  4997.2 1816.14  4997.7 1815.64  5002.8 1816.14
  5011.2 1816.14  5031.2 1819.02  5061.3 1819.82  5071.3 1821.99  5081.3 1821.69
  5097.9 1819.49  5111.3 1819.75  5131.3 1818.86  5191.4 1819.77  5363.9 1819.79
  5378.6 1820.49  5464.2 1820.68  5487.2 1821.51  5714.8 1822.59  6250.4 1823.10
#Mann=3,-1,0
  3364.8    0.07       0  4997.2    0.07       0  5002.8    0.07       0
Bank Sta=4997.2,5002.8
Exp/Cntr=0.3,0.1

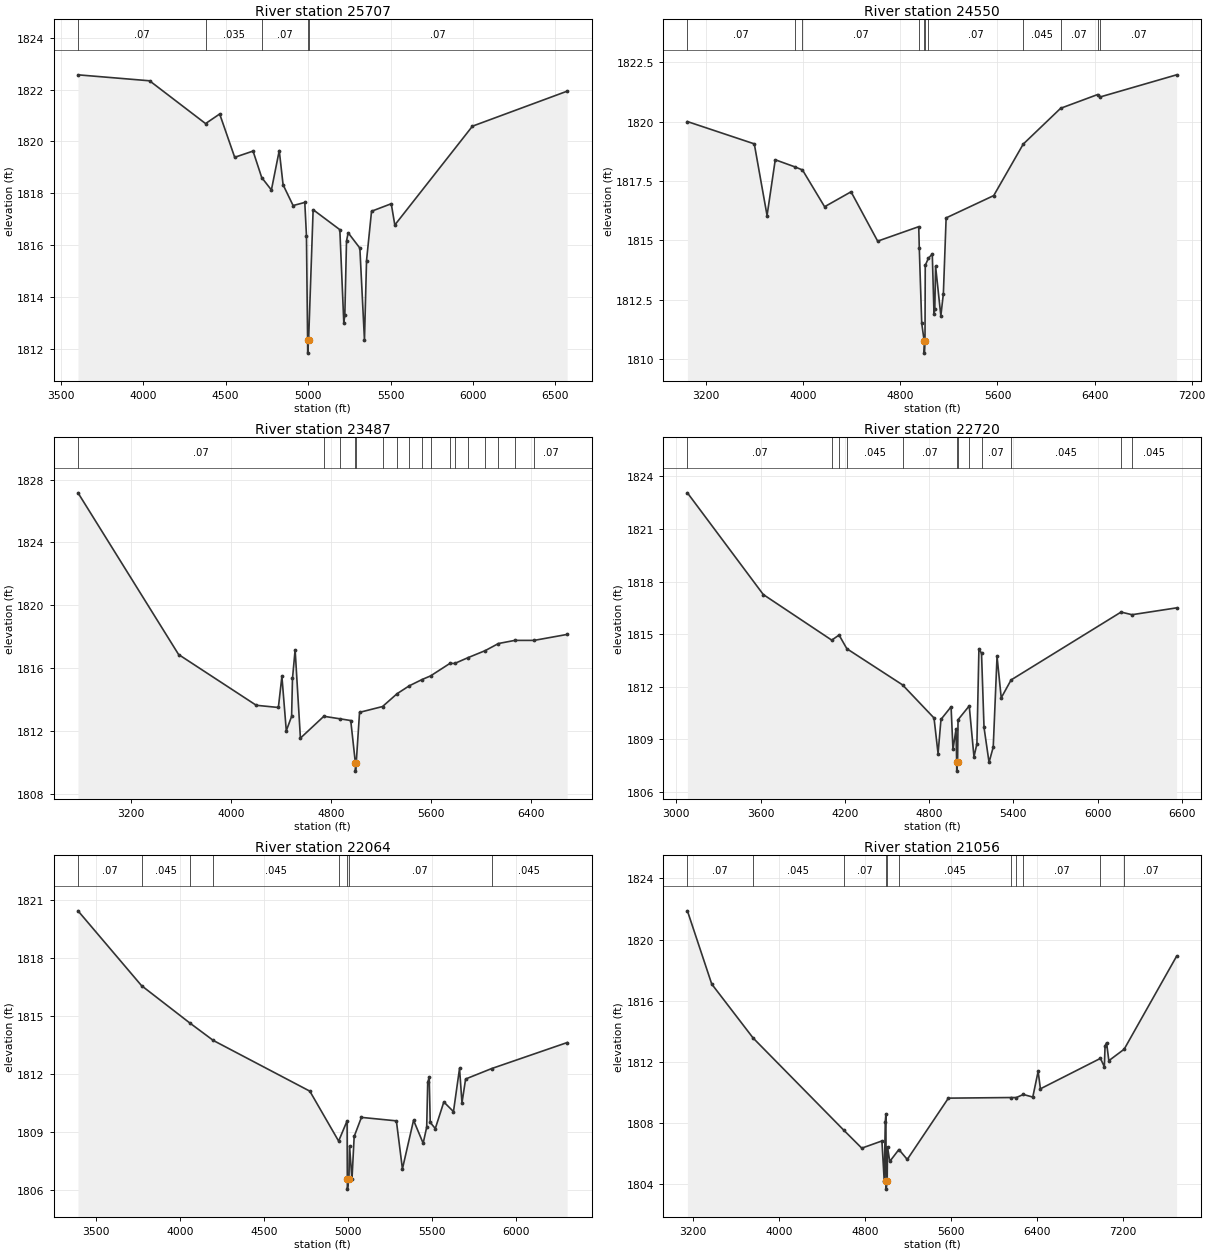
Type RM Length L Ch R = 1,25707,1157,1157,1157
BEGIN DESCRIPTION:
Tributary No. 1 to Elm Creek 31.0
END DESCRIPTION:
XS GIS Cut Line= 3
      1557276.05      6822831.99      1559106.10      6822545.66
      1559788.51      6821664.40
#Sta/Elev= 30
  3604.4 1822.57  4038.6 1822.34  4378.1 1820.69  4463.7 1821.06  4554.8 1819.39
  4666.1 1819.63  4718.6 1818.61  4777.4 1818.13  4825.0 1819.65  4848.3 1818.33
  4909.0 1817.53  4979.9 1817.65  4990.0 1816.37  4997.0 1812.34  4997.5 1811.84
  5003.0 1812.34  5030.5 1817.37  5192.4 1816.60  5216.5 1813.01  5222.8 1813.31
  5232.9 1816.16  5243.0 1816.48  5313.9 1815.89  5341.9 1812.34  5354.4 1815.41
  5384.7 1817.31  5504.3 1817.60  5525.9 1816.78  5996.7 1820.59  6571.3 1821.94
#Mann=5,-1,0
  3604.4    0.07       0  4378.1   0.035       0  4718.6    0.07       0
  4997.0    0.07       0  5003.0    0.07       0
Bank Sta=4997,5003
Exp/Cntr=0.3,0.1

Type RM Length L Ch R = 1,24550,1063,1063,1063
BEGIN DESCRIPTION:
Tributary No. 1 to Elm Creek 30.0
END DESCRIPTION:
XS GIS Cut Line= 3
      1557128.65      6823720.35      1558918.74      6823067.46
      1560219.96      6821388.88
#Sta/Elev= 30
  3046.1 1820.00  3597.0 1819.06  3702.2 1816.04  3769.7 1818.39  3931.7 1818.09
  3994.0 1817.96  4176.2 1816.41  4394.0 1817.04  4613.3 1814.96  4951.5 1815.57
  4956.1 1814.67  4976.2 1811.49  4996.9 1810.74  4997.4 1810.24  5003.1 1810.74
  5005.2 1813.94  5031.4 1814.24  5063.1 1814.42  5077.4 1811.88  5083.9 1812.10
  5090.3 1813.90  5133.7 1811.81  5154.5 1812.75  5177.2 1815.94  5569.2 1816.88
  5812.2 1819.05  6120.5 1820.56  6425.8 1821.14  6447.7 1821.04  7075.4 1821.97
#Mann=11,-1,0
  3046.1    0.07       0  3931.7   0.035       0  3994.0    0.07       0
  4956.1    0.16       0  4996.9    0.07       0  5003.1    0.16       0
  5031.4    0.07       0  5812.2   0.045       0  6120.5    0.07       0
  6425.8   0.045       0  6447.7    0.07       0
Bank Sta=4996.9,5003.1
Exp/Cntr=0.3,0.1

Type RM Length L Ch R = 1,23487,767,767,767
BEGIN DESCRIPTION:
Tributary No. 1 to Elm Creek 29.0
END DESCRIPTION:
XS GIS Cut Line= 3
      1557654.99      6825138.01      1559260.76      6823596.25
      1560414.35      6822356.01
#Sta/Elev= 30
  2773.9 1827.16  3580.1 1816.87  4202.4 1813.64  4379.5 1813.50  4407.8 1815.48
  4443.0 1812.02  4485.5 1812.93  4492.7 1815.35  4513.8 1817.17  4556.2 1811.55
  4744.0 1812.94  4872.5 1812.78  4959.4 1812.67  4996.9 1809.95  4997.4 1809.45
  5003.2 1809.95  5030.0 1813.19  5214.1 1813.56  5331.3 1814.38  5428.6 1814.88
  5531.2 1815.28  5599.2 1815.51  5755.2 1816.31  5792.1 1816.30  5898.9 1816.67
  6037.4 1817.12  6142.8 1817.57  6274.3 1817.77  6429.1 1817.77  6693.8 1818.15
#Mann=17,-1,0
  2773.9    0.07       0  4744.0   0.035       0  4872.5    0.16       0
  4996.9    0.07       0  5003.2    0.16       0  5214.1   0.045       0
  5331.3    0.07       0  5428.6   0.045       0  5531.2    0.07       0
  5599.2   0.045       0  5755.2    0.07       0  5792.1   0.045       0
  5898.9    0.07       0  6037.4   0.045       0  6142.8    0.07       0
  6274.3   0.045       0  6429.1    0.07       0
Bank Sta=4996.9,5003.2
Exp/Cntr=0.3,0.1

Type RM Length L Ch R = 1,22720,656,656,656
BEGIN DESCRIPTION:
Tributary No. 1 to Elm Creek 28.0
END DESCRIPTION:
XS GIS Cut Line= 3
      1558054.98      6825238.01      1559670.14      6823930.63
      1560465.88      6822771.93
#Sta/Elev= 30
  3079.2 1823.06  3619.6 1817.26  4107.0 1814.66  4159.3 1814.95  4214.7 1814.17
  4611.0 1812.11  4835.4 1810.22  4864.2 1808.19  4885.0 1810.14  4956.9 1810.86
  4970.4 1808.43  4992.1 1809.58  4996.8 1807.69  4997.3 1807.19  5003.2 1807.69
  5006.5 1810.12  5086.2 1810.91  5120.0 1808.00  5140.8 1808.75  5155.2 1814.17
  5173.7 1813.91  5191.5 1809.68  5227.3 1807.69  5257.1 1808.56  5284.2 1813.73
  5314.0 1811.37  5384.3 1812.39  6167.4 1816.26  6245.4 1816.11  6562.8 1816.50
#Mann=12,-1,0
  3079.2    0.07       0  4107.0   0.045       0  4159.3    0.07       0
  4214.7   0.045       0  4611.0    0.07       0  4996.8    0.07       0
  5003.2    0.07       0  5086.2    0.16       0  5173.7    0.07       0
  5384.3   0.045       0  6167.4    0.07       0  6245.4   0.045       0
Bank Sta=4996.8,5003.2
Exp/Cntr=0.3,0.1

Type RM Length L Ch R = 1,22064,1008,1008,1008
BEGIN DESCRIPTION:
Tributary No. 1 to Elm Creek 27.0
END DESCRIPTION:
XS GIS Cut Line= 3
      1558485.28      6825503.85      1559905.33      6824405.54
      1560522.45      6823476.68
#Sta/Elev= 30
  3392.9 1820.45  3771.0 1816.57  4058.8 1814.63  4197.7 1813.73  4772.1 1811.10
  4943.6 1808.51  4993.9 1809.56  4995.2 1806.52  4995.7 1806.02  5004.8 1806.52
  5008.4 1808.26  5022.9 1806.52  5036.0 1808.75  5079.1 1809.74  5287.1 1809.56
  5323.1 1807.07  5389.3 1809.59  5446.4 1808.40  5467.5 1809.23  5473.5 1811.55
  5482.5 1811.83  5488.5 1809.48  5518.6 1809.16  5569.4 1810.54  5626.8 1810.04
  5662.9 1812.28  5677.4 1810.49  5699.0 1811.73  5853.6 1812.27  6303.3 1813.62
#Mann=8,-1,0
  3392.9    0.07       0  3771.0   0.045       0  4058.8    0.07       0
  4197.7   0.045       0  4943.6    0.07       0  4995.2    0.07       0
  5004.8    0.07       0  5853.6   0.045       0
Bank Sta=4995.2,5004.8
Exp/Cntr=0.3,0.1

Type RM Length L Ch R = 1,21056,498,498,498
BEGIN DESCRIPTION:
Tributary No. 1 to Elm Creek 26.0
END DESCRIPTION:
XS GIS Cut Line= 3
      1558754.98      6825988.01      1560353.95      6825048.43
      1562155.01      6823037.99
#Sta/Elev= 30
  3145.4 1821.88  3372.0 1817.09  3757.4 1813.56  4600.4 1807.54  4768.6 1806.36
  4956.1 1806.83  4978.0 1804.18  4987.4 1808.09  4993.2 1808.61  4995.2 1804.18
  4995.7 1803.68  5004.9 1804.18  5008.2 1806.44  5029.1 1805.49  5114.2 1806.27
  5192.1 1805.62  5574.9 1809.63  6157.7 1809.67  6208.3 1809.67  6272.3 1809.87
  6360.6 1809.70  6410.3 1811.38  6431.6 1810.24  6990.3 1812.23  7026.7 1811.68
  7033.4 1813.05  7047.6 1813.25  7068.6 1812.08  7211.2 1812.83  7699.2 1818.91
#Mann=11,-1,0
  3145.4    0.07       0  3757.4   0.045       0  4600.4    0.07       0
  4995.2    0.07       0  5004.9    0.07       0  5114.2   0.045       0
  6157.7    0.07       0  6208.3   0.045       0  6272.3    0.07       0
  6990.3   0.035       0  7211.2    0.07       0
Bank Sta=4995.2,5004.9
Exp/Cntr=0.3,0.1

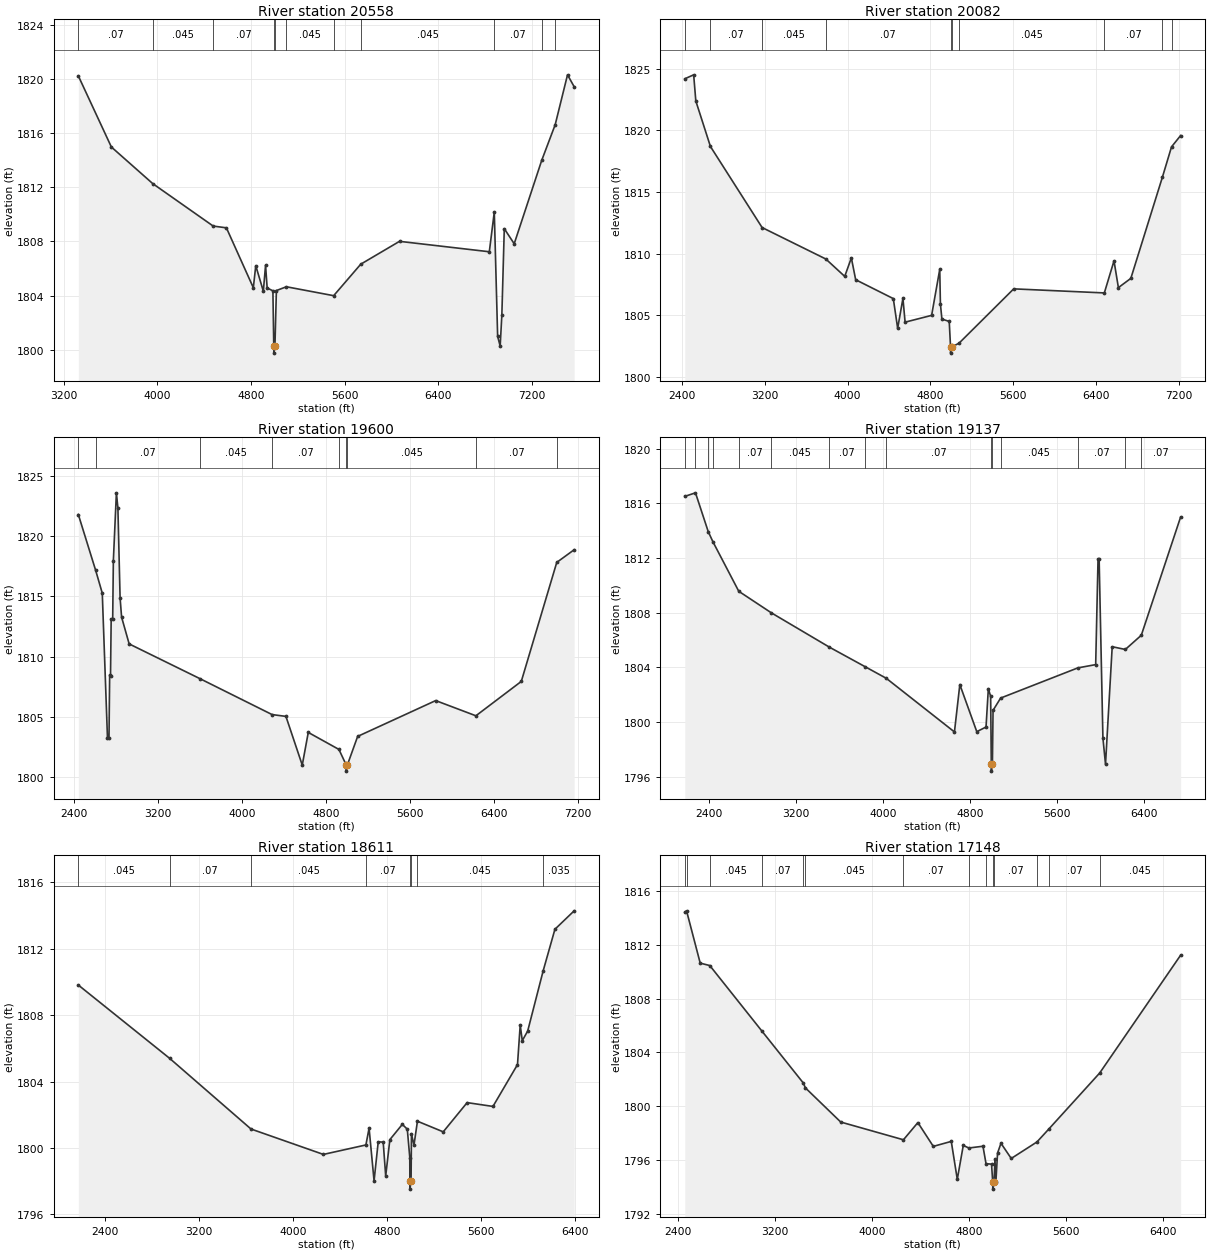
Type RM Length L Ch R = 1,20558,476,476,476
BEGIN DESCRIPTION:
Tributary No. 1 to Elm Creek 25.0
END DESCRIPTION:
XS GIS Cut Line= 3
      1558855.00      6825988.00      1560456.84      6825494.28
      1562454.96      6823888.03
#Sta/Elev= 30
  3323.8 1820.25  3606.3 1814.99  3960.3 1812.28  4477.1 1809.14  4590.0 1809.01
  4820.2 1804.58  4841.1 1806.21  4905.8 1804.32  4924.8 1806.24  4938.5 1804.56
  4987.6 1804.35  4995.1 1800.24  4995.6 1799.74  5004.9 1800.24  5017.4 1804.37
  5102.9 1804.65  5507.2 1803.99  5738.9 1806.32  6070.2 1808.01  6838.2 1807.24
  6880.7 1810.18  6909.4 1800.98  6931.0 1800.26  6945.4 1802.56  6966.2 1808.95
  7051.0 1807.83  7286.2 1814.00  7401.5 1816.64  7506.9 1820.33  7563.7 1819.45
#Mann=11,-1,0
  3323.8    0.07       0  3960.3   0.045       0  4477.1    0.07       0
  4995.1    0.07       0  5004.9    0.07       0  5102.9   0.045       0
  5507.2    0.07       0  5738.9   0.045       0  6880.7    0.07       0
  7286.2   0.035       0  7401.5    0.07       0
Bank Sta=4995.1,5004.9
Exp/Cntr=0.3,0.1

Type RM Length L Ch R = 1,20082,482,482,482
BEGIN DESCRIPTION:
Tributary No. 1 to Elm Creek 24.0
END DESCRIPTION:
XS GIS Cut Line= 3
      1558905.03      6827137.98      1560918.82      6825537.55
      1562455.03      6823937.97
#Sta/Elev= 30
  2427.7 1824.17  2513.4 1824.49  2534.2 1822.37  2675.4 1818.68  3174.6 1812.11
  3790.1 1809.56  3972.8 1808.15  4036.8 1809.65  4078.5 1807.88  4442.1 1806.35
  4484.2 1803.94  4535.1 1806.37  4555.9 1804.44  4812.2 1804.99  4890.7 1808.72
  4897.1 1805.93  4911.5 1804.69  4982.3 1804.50  4995.1 1802.43  4995.6 1801.93
  5004.9 1802.43  5076.4 1802.73  5605.3 1807.14  6480.8 1806.81  6574.2 1809.41
  6616.6 1807.24  6736.8 1807.99  7042.4 1816.21  7129.8 1818.65  7217.8 1819.57
#Mann=10,-1,0
  2427.7   0.035       0  2675.4    0.07       0  3174.6   0.045       0
  3790.1    0.07       0  4995.1    0.07       0  5004.9    0.07       0
  5076.4   0.045       0  6480.8    0.07       0  7042.4   0.035       0
  7129.8    0.07       0
Bank Sta=4995.1,5004.9
Exp/Cntr=0.3,0.1

Type RM Length L Ch R = 1,19600,463,463,463
BEGIN DESCRIPTION:
Tributary No. 1 to Elm Creek 23.0
END DESCRIPTION:
XS GIS Cut Line= 3
      1559305.01      6827387.99      1561307.17      6825794.14
      1562504.98      6823988.03
#Sta/Elev= 30
  2440.9 1821.78  2606.4 1817.14  2669.1 1815.26  2718.8 1803.23  2733.2 1803.26
  2739.6 1808.49  2747.6 1808.38  2754.0 1813.11  2768.4 1813.12  2774.8 1817.96
  2803.7 1823.58  2818.1 1822.32  2838.9 1814.87  2853.3 1813.27  2925.4 1811.05
  3604.5 1808.15  4287.7 1805.19  4419.7 1805.04  4575.4 1801.00  4632.7 1803.71
  4924.8 1802.30  4995.0 1801.00  4995.5 1800.50  5005.0 1801.00  5103.4 1803.38
  5847.3 1806.35  6230.6 1805.09  6663.3 1807.94  7001.3 1817.81  7167.2 1818.86
#Mann=9,-1,0
  2440.9   0.035       0  2606.4    0.07       0  3604.5   0.045       0
  4287.7    0.07       0  4924.8   0.045       0  4995.0   0.045       0
  5005.0   0.045       0  6230.6    0.07       0  7001.3   0.035       0
Bank Sta=4995,5005
Exp/Cntr=0.3,0.1

Type RM Length L Ch R = 1,19137,526,526,526
BEGIN DESCRIPTION:
Tributary No. 1 to Elm Creek 22.0
END DESCRIPTION:
XS GIS Cut Line= 3
      1559755.02      6827887.98      1561740.64      6825888.23
      1562405.02      6824287.96
#Sta/Elev= 30
  2181.9 1816.52  2279.9 1816.78  2397.4 1813.93  2440.4 1813.19  2677.3 1809.57
  2976.7 1807.99  3508.8 1805.48  3836.3 1804.05  4030.7 1803.20  4656.8 1799.27
  4706.2 1802.74  4861.8 1799.29  4946.7 1799.63  4967.9 1802.44  4989.1 1801.87
  4995.0 1796.90  4995.5 1796.40  5005.1 1796.90  5011.1 1800.85  5080.7 1801.75
  5789.1 1803.96  5953.1 1804.20  5974.7 1811.94  5984.8 1811.92  6019.5 1798.83
  6043.3 1796.90  6104.7 1805.51  6225.4 1805.31  6371.8 1806.35  6732.7 1815.01
#Mann=15,-1,0
  2181.9   0.035       0  2279.9   0.094       0  2397.4   0.035       0
  2440.4   0.045       0  2677.3    0.07       0  2976.7   0.045       0
  3508.8    0.07       0  3836.3   0.035       0  4030.7    0.07       0
  4995.0    0.07       0  5005.1    0.07       0  5080.7   0.045       0
  5789.1    0.07       0  6225.4   0.045       0  6371.8    0.07       0
Bank Sta=4995,5005.1
Exp/Cntr=0.3,0.1

Type RM Length L Ch R = 1,18611,1463,1463,1463
BEGIN DESCRIPTION:
Tributary No. 1 to Elm Creek 21.0
END DESCRIPTION:
XS GIS Cut Line= 3
      1560255.00      6827888.00      1562361.72      6825801.39
      1562882.21      6824659.04
#Sta/Elev= 30
  2172.8 1809.81  2949.4 1805.40  3642.5 1801.14  4258.8 1799.61  4620.6 1800.18
  4647.7 1801.19  4690.1 1798.02  4725.5 1800.37  4767.9 1800.35  4789.1 1798.31
  4824.5 1800.50  4930.6 1801.42  4973.0 1801.13  4994.2 1799.42  4994.9 1798.02
  4995.4 1797.52  5005.1 1798.02  5008.3 1800.86  5029.6 1800.16  5059.3 1801.61
  5278.8 1800.97  5482.3 1802.73  5702.1 1802.50  5911.0 1805.02  5934.1 1807.41
  5951.6 1806.46  5997.7 1807.04  6130.0 1810.68  6229.6 1813.17  6393.3 1814.28
#Mann=8,-1,0
  2172.8   0.045       0  2949.4    0.07       0  3642.5   0.045       0
  4620.6    0.07       0  4994.9    0.07       0  5005.1    0.07       0
  5059.3   0.045       0  6130.0   0.035       0
Bank Sta=4994.9,5005.1
Exp/Cntr=0.3,0.1

Type RM Length L Ch R = 1,17148,978,978,978
BEGIN DESCRIPTION:
Tributary No. 1 to Elm Creek 20.0
END DESCRIPTION:
XS GIS Cut Line= 3
      1560805.02      6828537.98      1562725.10      6826662.56
      1563615.64      6825571.98
#Sta/Elev= 30
  2453.4 1814.42  2467.9 1814.53  2580.6 1810.64  2659.6 1810.46  3089.5 1805.59
  3430.9 1801.73  3448.8 1801.36  3740.3 1798.82  4257.8 1797.50  4376.9 1798.78
  4504.2 1797.01  4652.6 1797.38  4702.2 1794.56  4751.6 1797.08  4797.7 1796.89
  4914.2 1797.02  4939.4 1795.72  4984.9 1795.69  4994.9 1794.33  4995.4 1793.83
  5005.1 1794.33  5013.2 1796.04  5020.4 1794.33  5034.5 1796.51  5062.8 1797.24
  5147.5 1796.11  5359.9 1797.34  5458.7 1798.31  5877.8 1802.47  6545.4 1811.23
#Mann=14,-1,0
  2453.4   0.063       0  2467.9   0.035       0  2659.6   0.045       0
  3089.5    0.07       0  3430.9   0.035       0  3448.8   0.045       0
  4257.8    0.07       0  4797.7    0.16       0  4939.4    0.07       0
  4994.9    0.07       0  5005.1    0.07       0  5359.9   0.035       0
  5458.7    0.07       0  5877.8   0.045       0
Bank Sta=4994.9,5005.1
Exp/Cntr=0.3,0.1