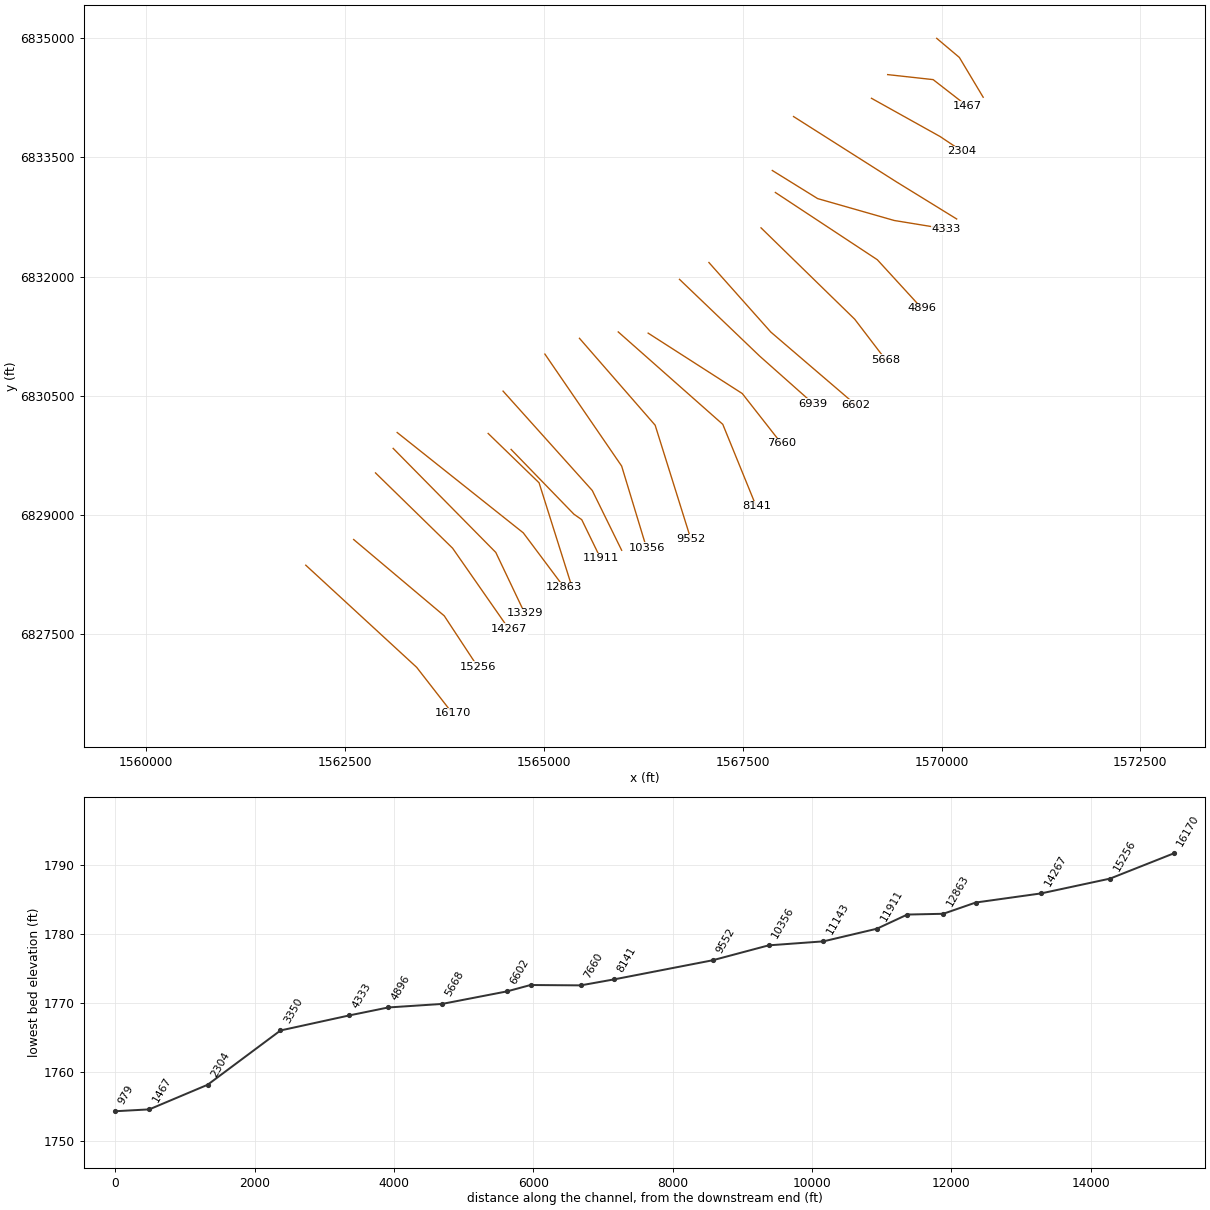
HEC-RAS study T1 to Elm Creek.prj: Tributary No. 1 to Elm Creek Base Level Engineering

--- T1 to Elm Creek.g01 (geometry) --- (continued)

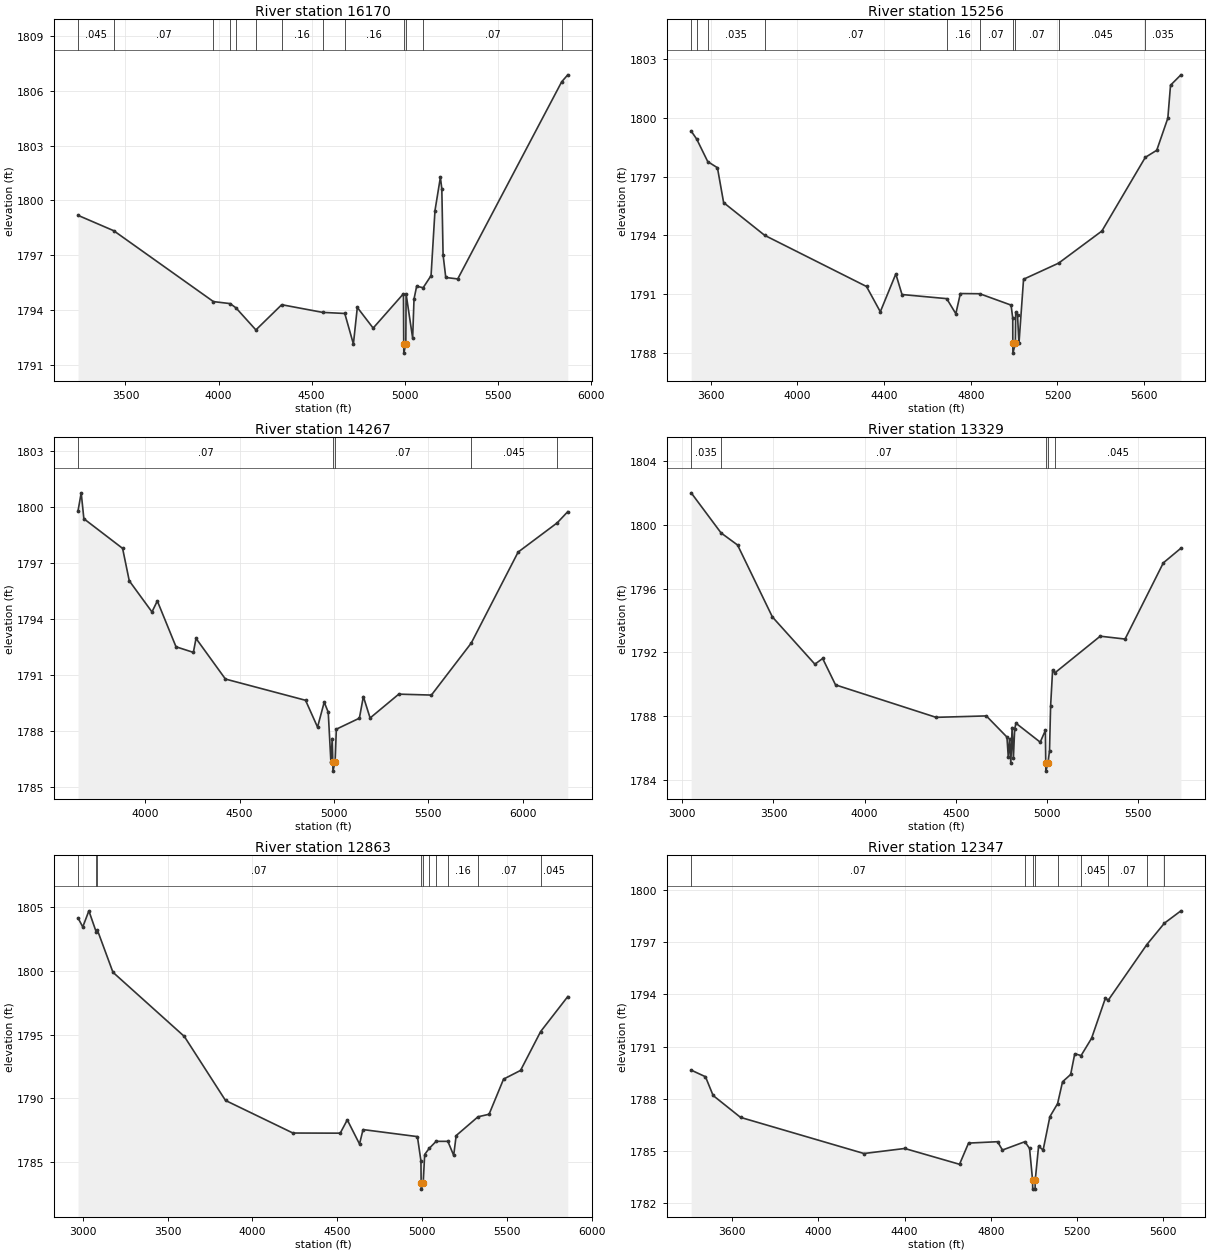
Type RM Length L Ch R = 1,16170,914,914,914
BEGIN DESCRIPTION:
Tributary No. 1 to Elm Creek 19.0
END DESCRIPTION:
XS GIS Cut Line= 3
      1562006.03      6828368.39      1563400.28      6827083.51
      1563850.68      6826503.96
#Sta/Elev= 30
  3245.3 1799.18  3436.8 1798.34  3972.4 1794.46  4062.2 1794.35  4093.2 1794.12
  4200.4 1792.91  4339.2 1794.29  4558.6 1793.87  4677.8 1793.81  4724.1 1792.14
  4745.1 1794.14  4830.2 1793.01  4992.9 1794.89  4994.4 1792.14  4994.9 1791.64
  5005.6 1792.14  5007.1 1794.88  5042.3 1792.46  5049.6 1794.60  5063.8 1795.30
  5098.7 1795.22  5141.1 1795.88  5162.2 1799.44  5191.2 1801.26  5198.9 1800.64
  5205.7 1797.02  5220.1 1795.78  5284.4 1795.70  5842.7 1806.49  5875.3 1806.87
#Mann=13,-1,0
  3245.3   0.045       0  3436.8    0.07       0  3972.4   0.035       0
  4062.2    0.07       0  4093.2   0.035       0  4200.4    0.07       0
  4339.2    0.16       0  4558.6    0.07       0  4677.8    0.16       0
  4994.4    0.07       0  5005.6    0.16       0  5098.7    0.07       0
  5842.7   0.035       0
Bank Sta=4994.4,5005.6
Exp/Cntr=0.3,0.1

Type RM Length L Ch R = 1,15256,989,989,989
BEGIN DESCRIPTION:
Tributary No. 1 to Elm Creek 18.0
END DESCRIPTION:
XS GIS Cut Line= 3
      1562608.01      6828691.52      1563747.14      6827731.20
      1564170.06      6827087.87
#Sta/Elev= 30
  3510.1 1799.32  3535.6 1798.91  3586.6 1797.76  3631.2 1797.45  3659.8 1795.67
  3849.3 1794.00  4319.1 1791.39  4382.8 1790.10  4454.3 1792.03  4482.9 1790.98
  4689.1 1790.77  4731.3 1790.00  4752.1 1791.03  4841.6 1791.02  4986.2 1790.44
  4993.9 1789.76  4994.2 1788.49  4994.7 1787.99  5005.8 1788.49  5007.5 1790.07
  5015.8 1789.94  5022.6 1788.49  5043.7 1791.76  5205.3 1792.58  5405.2 1794.22
  5605.6 1797.98  5658.3 1798.34  5709.5 1799.98  5721.9 1801.66  5769.9 1802.19
#Mann=10,-1,0
  3510.1   0.125       0  3535.6    0.07       0  3586.6   0.035       0
  3849.3    0.07       0  4689.1    0.16       0  4841.6    0.07       0
  4994.2    0.07       0  5005.8    0.07       0  5205.3   0.045       0
  5605.6   0.035       0
Bank Sta=4994.2,5005.8
Exp/Cntr=0.3,0.1

Type RM Length L Ch R = 1,14267,938,938,938
BEGIN DESCRIPTION:
Tributary No. 1 to Elm Creek 17.0
END DESCRIPTION:
XS GIS Cut Line= 3
      1562882.89      6829529.59      1563852.14      6828582.14
      1564559.50      6827566.01
#Sta/Elev= 30
  3644.6 1799.81  3661.4 1800.78  3675.5 1799.39  3880.6 1797.80  3915.9 1796.06
  4036.2 1794.39  4064.5 1794.98  4163.5 1792.52  4255.4 1792.22  4269.5 1792.97
  4425.1 1790.79  4849.5 1789.65  4913.0 1788.21  4948.3 1789.55  4969.6 1789.01
  4983.7 1786.35  4990.7 1787.60  4994.0 1786.35  4994.5 1785.85  5006.0 1786.35
  5012.5 1788.10  5134.6 1788.69  5155.6 1789.85  5191.3 1788.70  5343.2 1789.98
  5516.0 1789.93  5726.9 1792.72  5975.1 1797.60  6182.2 1799.17  6238.1 1799.77
#Mann=5,-1,0
  3644.6    0.07       0  4994.0    0.07       0  5006.0    0.07       0
  5726.9   0.045       0  6182.2    0.07       0
Bank Sta=4994,5006
Exp/Cntr=0.3,0.1

Type RM Length L Ch R = 1,13329,466,466,466
BEGIN DESCRIPTION:
Tributary No. 1 to Elm Creek 16.0
END DESCRIPTION:
XS GIS Cut Line= 3
      1563104.98      6829838.02      1564395.24      6828528.97
      1564759.65      6827762.19
#Sta/Elev= 30
  3048.6 1802.02  3212.5 1799.50  3303.1 1798.74  3494.1 1794.22  3727.4 1791.25
  3769.9 1791.61  3840.6 1789.95  4392.2 1787.91  4667.9 1788.00  4781.1 1786.67
  4788.2 1785.43  4795.2 1786.55  4802.3 1785.03  4809.4 1787.27  4816.5 1785.35
  4823.5 1787.19  4830.6 1787.54  4963.6 1786.35  4991.9 1787.09  4994.0 1785.03
  4994.5 1784.53  5006.1 1785.03  5014.6 1785.82  5020.6 1788.62  5031.6 1790.90
  5043.4 1790.70  5292.8 1793.01  5429.1 1792.83  5639.1 1797.62  5735.6 1798.54
#Mann=5,-1,0
  3048.6   0.035       0  3212.5    0.07       0  4994.0    0.07       0
  5006.1    0.07       0  5043.4   0.045       0
Bank Sta=4994,5006.1
Exp/Cntr=0.3,0.1

Type RM Length L Ch R = 1,12863,516,516,516
BEGIN DESCRIPTION:
Tributary No. 1 to Elm Creek 15.0
END DESCRIPTION:
XS GIS Cut Line= 3
      1563155.01      6830037.99      1564741.27      6828775.09
      1565255.00      6828088.00
#Sta/Elev= 30
  2972.4 1804.12  3000.4 1803.42  3036.3 1804.68  3079.9 1803.01  3086.6 1803.17
  3178.2 1799.87  3598.7 1794.85  3841.3 1789.84  4238.5 1787.29  4517.2 1787.28
  4558.8 1788.32  4630.9 1786.43  4651.7 1787.56  4972.0 1787.01  4992.8 1785.11
  4994.0 1783.40  4994.5 1782.90  5006.1 1783.40  5014.8 1785.61  5040.9 1786.08
  5082.1 1786.64  5151.5 1786.64  5185.7 1785.54  5200.3 1787.09  5328.9 1788.56
  5394.2 1788.76  5479.6 1791.51  5579.7 1792.19  5698.0 1795.23  5857.9 1797.97
#Mann=10,-1,0
  2972.4   0.063       0  3079.9   0.035       0  3086.6    0.07       0
  4994.0    0.07       0  5006.1    0.07       0  5040.9    0.16       0
  5082.1    0.07       0  5151.5    0.16       0  5328.9    0.07       0
  5698.0   0.045       0
Bank Sta=4994,5006.1
Exp/Cntr=0.3,0.1

Type RM Length L Ch R = 1,12347,436,436,436
BEGIN DESCRIPTION:
Tributary No. 1 to Elm Creek 14.0
END DESCRIPTION:
XS GIS Cut Line= 3
      1564299.30      6830026.14      1564939.41      6829405.22
      1565355.00      6828088.01
#Sta/Elev= 30
  3409.4 1789.64  3475.7 1789.26  3511.2 1788.18  3638.5 1786.92  4211.3 1784.84
  4400.4 1785.13  4654.8 1784.22  4696.7 1785.44  4831.4 1785.52  4854.0 1785.04
  4958.2 1785.52  4979.9 1785.13  4994.0 1783.29  4994.5 1782.79  5005.6 1782.79
  5006.1 1783.29  5021.8 1785.26  5042.8 1785.04  5074.2 1786.96  5109.9 1787.71
  5133.0 1788.97  5170.6 1789.39  5189.6 1790.58  5219.1 1790.48  5267.6 1791.47
  5332.3 1793.80  5344.2 1793.65  5524.4 1796.87  5605.8 1798.10  5682.4 1798.81
#Mann=9,-1,0
  3409.4    0.07       0  4958.2    0.16       0  4994.0    0.07       0
  5006.1    0.16       0  5109.9    0.07       0  5219.1   0.045       0
  5344.2    0.07       0  5524.4   0.045       0  5605.8    0.07       0
Bank Sta=4994,5006.1
Exp/Cntr=0.3,0.1

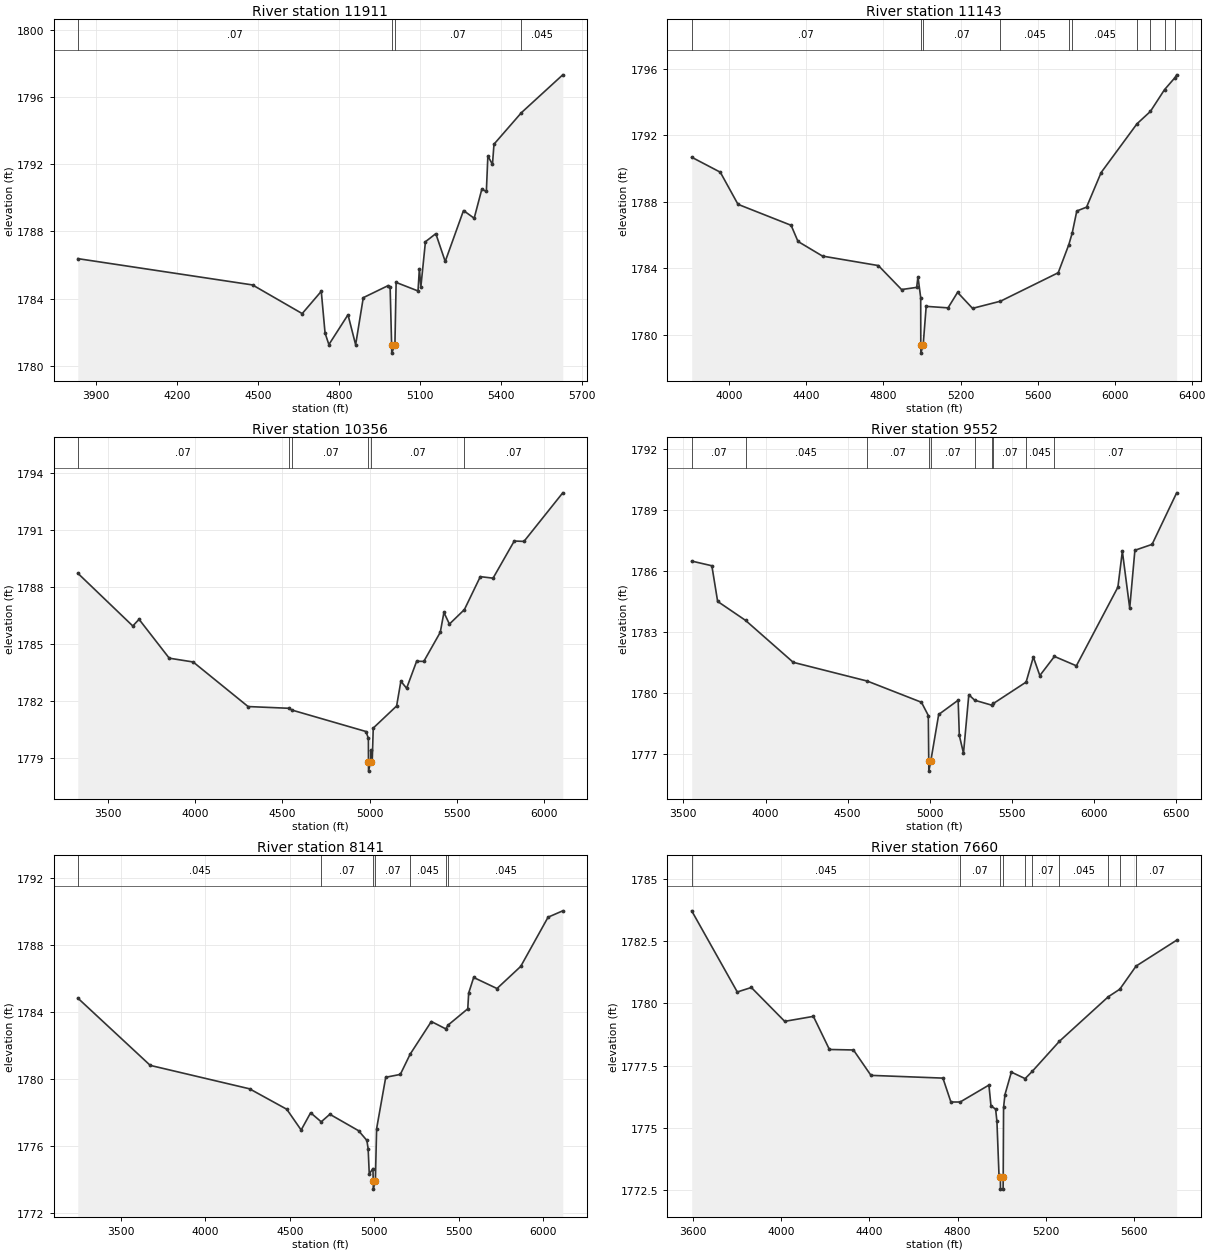
Type RM Length L Ch R = 1,11911,768,768,768
BEGIN DESCRIPTION:
Tributary No. 1 to Elm Creek 13.0
END DESCRIPTION:
XS GIS Cut Line= 4
      1564587.67      6829825.15      1565377.86      6829009.97
      1565475.70      6828941.45      1565712.06      6828455.43
#Sta/Elev= 30
  3832.2 1786.38  4479.0 1784.81  4662.9 1783.10  4733.5 1784.43  4747.5 1781.94
  4761.7 1781.25  4832.4 1783.03  4860.7 1781.24  4889.0 1784.05  4981.0 1784.77
  4988.4 1784.67  4993.9 1781.24  4994.4 1780.74  5006.1 1781.24  5010.6 1784.96
  5091.7 1784.45  5096.6 1785.78  5102.1 1784.69  5119.1 1787.39  5157.5 1787.87
  5192.3 1786.21  5260.0 1789.25  5299.5 1788.79  5327.7 1790.52  5344.6 1790.39
  5350.2 1792.51  5367.2 1792.00  5372.8 1793.21  5474.3 1795.09  5627.4 1797.35
#Mann=4,-1,0
  3832.2    0.07       0  4993.9    0.07       0  5006.1    0.07       0
  5474.3   0.045       0
Bank Sta=4993.9,5006.1
Exp/Cntr=0.3,0.1

Type RM Length L Ch R = 1,11143,787,787,787
BEGIN DESCRIPTION:
Tributary No. 1 to Elm Creek 12.0
END DESCRIPTION:
XS GIS Cut Line= 3
      1564486.64      6830558.81      1565608.07      6829308.60
      1565977.72      6828556.05
#Sta/Elev= 30
  3804.3 1790.68  3952.8 1789.78  4044.7 1787.85  4320.5 1786.59  4356.2 1785.62
  4483.5 1784.74  4773.6 1784.17  4893.9 1782.73  4972.4 1782.86  4979.1 1783.50
  4993.3 1782.24  4993.8 1779.41  4994.3 1778.91  5006.2 1779.41  5021.8 1781.72
  5135.3 1781.63  5184.7 1782.56  5262.5 1781.60  5407.5 1782.03  5707.3 1783.74
  5762.4 1785.43  5780.0 1786.13  5803.8 1787.45  5854.4 1787.68  5930.1 1789.76
  6116.4 1792.69  6185.8 1793.43  6259.2 1794.74  6313.3 1795.46  6322.2 1795.63
#Mann=10,-1,0
  3804.3    0.07       0  4993.8    0.07       0  5006.2    0.07       0
  5407.5   0.045       0  5762.4    0.07       0  5780.0   0.045       0
  6116.4    0.07       0  6185.8   0.045       0  6259.2    0.07       0
  6313.3   0.045       0
Bank Sta=4993.8,5006.2
Exp/Cntr=0.3,0.1

Type RM Length L Ch R = 1,10356,804,804,804
BEGIN DESCRIPTION:
Tributary No. 1 to Elm Creek 11.0
END DESCRIPTION:
XS GIS Cut Line= 3
      1565012.43      6831024.96      1565977.66      6829615.67
      1566290.47      6828584.94
#Sta/Elev= 30
  3324.4 1788.72  3640.3 1785.95  3676.2 1786.30  3849.5 1784.26  3986.9 1784.06
  4302.5 1781.72  4536.2 1781.63  4556.4 1781.53  4979.4 1780.41  4993.4 1780.05
  4993.8 1778.83  4994.3 1778.33  5006.3 1778.83  5006.4 1779.42  5015.3 1778.83
  5021.3 1780.59  5155.5 1781.75  5180.0 1783.05  5212.9 1782.68  5270.5 1784.10
  5311.6 1784.09  5406.3 1785.62  5427.2 1786.66  5458.8 1786.05  5544.8 1786.81
  5636.2 1788.54  5709.4 1788.46  5831.1 1790.41  5887.0 1790.39  6109.7 1792.94
#Mann=6,-1,0
  3324.4    0.07       0  4536.2   0.045       0  4556.4    0.07       0
  4993.8   0.045       0  5006.3    0.07       0  5544.8    0.07       0
Bank Sta=4993.8,5006.3
Exp/Cntr=0.3,0.1

Type RM Length L Ch R = 1,9552,1411,1411,1411
BEGIN DESCRIPTION:
Tributary No. 1 to Elm Creek 10.0
END DESCRIPTION:
XS GIS Cut Line= 3
      1565447.22      6831223.21      1566398.96      6830129.81
      1566848.08      6828695.27
#Sta/Elev= 30
  3550.4 1786.48  3673.2 1786.25  3708.4 1784.50  3878.2 1783.57  4168.8 1781.51
  4619.5 1780.59  4949.3 1779.55  4991.1 1778.90  4993.8 1776.67  4994.3 1776.17
  5006.3 1776.67  5054.3 1778.95  5172.8 1779.65  5180.0 1777.92  5205.3 1777.05
  5237.7 1779.92  5273.6 1779.65  5376.3 1779.41  5387.4 1779.49  5586.5 1780.54
  5630.6 1781.77  5670.1 1780.86  5759.0 1781.80  5892.6 1781.34  6145.4 1785.20
  6172.6 1786.96  6217.4 1784.17  6248.9 1787.01  6353.6 1787.30  6503.2 1789.83
#Mann=10,-1,0
  3550.4    0.07       0  3878.2   0.045       0  4619.5    0.07       0
  4993.8    0.07       0  5006.3    0.07       0  5273.6   0.045       0
  5376.3   0.035       0  5387.4    0.07       0  5586.5   0.045       0
  5759.0    0.07       0
Bank Sta=4993.8,5006.3
Exp/Cntr=0.3,0.1

Type RM Length L Ch R = 1,8141,481,481,481
BEGIN DESCRIPTION:
Tributary No. 1 to Elm Creek 9.0
END DESCRIPTION:
XS GIS Cut Line= 3
      1565934.78      6831303.73      1567249.32      6830140.66
      1567670.17      6829107.49
#Sta/Elev= 30
  3244.8 1784.82  3673.7 1780.80  4261.8 1779.40  4481.8 1778.18  4567.0 1776.94
  4623.1 1777.97  4685.8 1777.43  4736.9 1777.88  4906.7 1776.90  4956.0 1776.32
  4963.6 1775.82  4970.2 1774.32  4992.0 1774.64  4993.6 1773.91  4994.1 1773.41
  5006.4 1773.91  5013.7 1777.02  5067.7 1780.09  5154.0 1780.26  5212.3 1781.47
  5337.6 1783.42  5423.1 1782.98  5437.2 1783.21  5553.3 1784.18  5558.7 1785.12
  5588.2 1786.05  5726.3 1785.39  5866.7 1786.71  6028.7 1789.65  6115.6 1790.03
#Mann=7,-1,0
  3244.8   0.045       0  4685.8    0.07       0  4993.6    0.07       0
  5006.4    0.07       0  5212.3   0.045       0  5423.1    0.07       0
  5437.2   0.045       0
Bank Sta=4993.6,5006.4
Exp/Cntr=0.3,0.1

Type RM Length L Ch R = 1,7660,721,721,721
BEGIN DESCRIPTION:
Tributary No. 1 to Elm Creek 8.0
END DESCRIPTION:
XS GIS Cut Line= 3
      1566310.99      6831288.25      1567494.19      6830528.37
      1567983.14      6829904.04
#Sta/Elev= 30
  3593.8 1783.72  3800.6 1780.46  3864.3 1780.64  4015.6 1779.28  4145.7 1779.48
  4218.4 1778.15  4327.4 1778.13  4406.7 1777.11  4733.0 1777.00  4769.3 1776.04
  4811.3 1776.04  4941.7 1776.72  4950.9 1775.89  4972.1 1775.75  4978.0 1775.26
  4987.3 1773.12  4993.6 1773.04  4994.1 1772.54  5006.0 1772.54  5006.5 1773.04
  5008.1 1775.82  5014.5 1776.34  5043.4 1777.24  5105.8 1776.98  5138.1 1777.27
  5261.4 1778.48  5483.2 1780.27  5535.0 1780.57  5609.0 1781.50  5793.0 1782.54
#Mann=10,-1,0
  3593.8   0.045       0  4811.3    0.07       0  4993.6    0.07       0
  5006.5    0.07       0  5105.8   0.045       0  5138.1    0.07       0
  5261.4   0.045       0  5483.2    0.07       0  5535.0   0.045       0
  5609.0    0.07       0
Bank Sta=4993.6,5006.5
Exp/Cntr=0.3,0.1

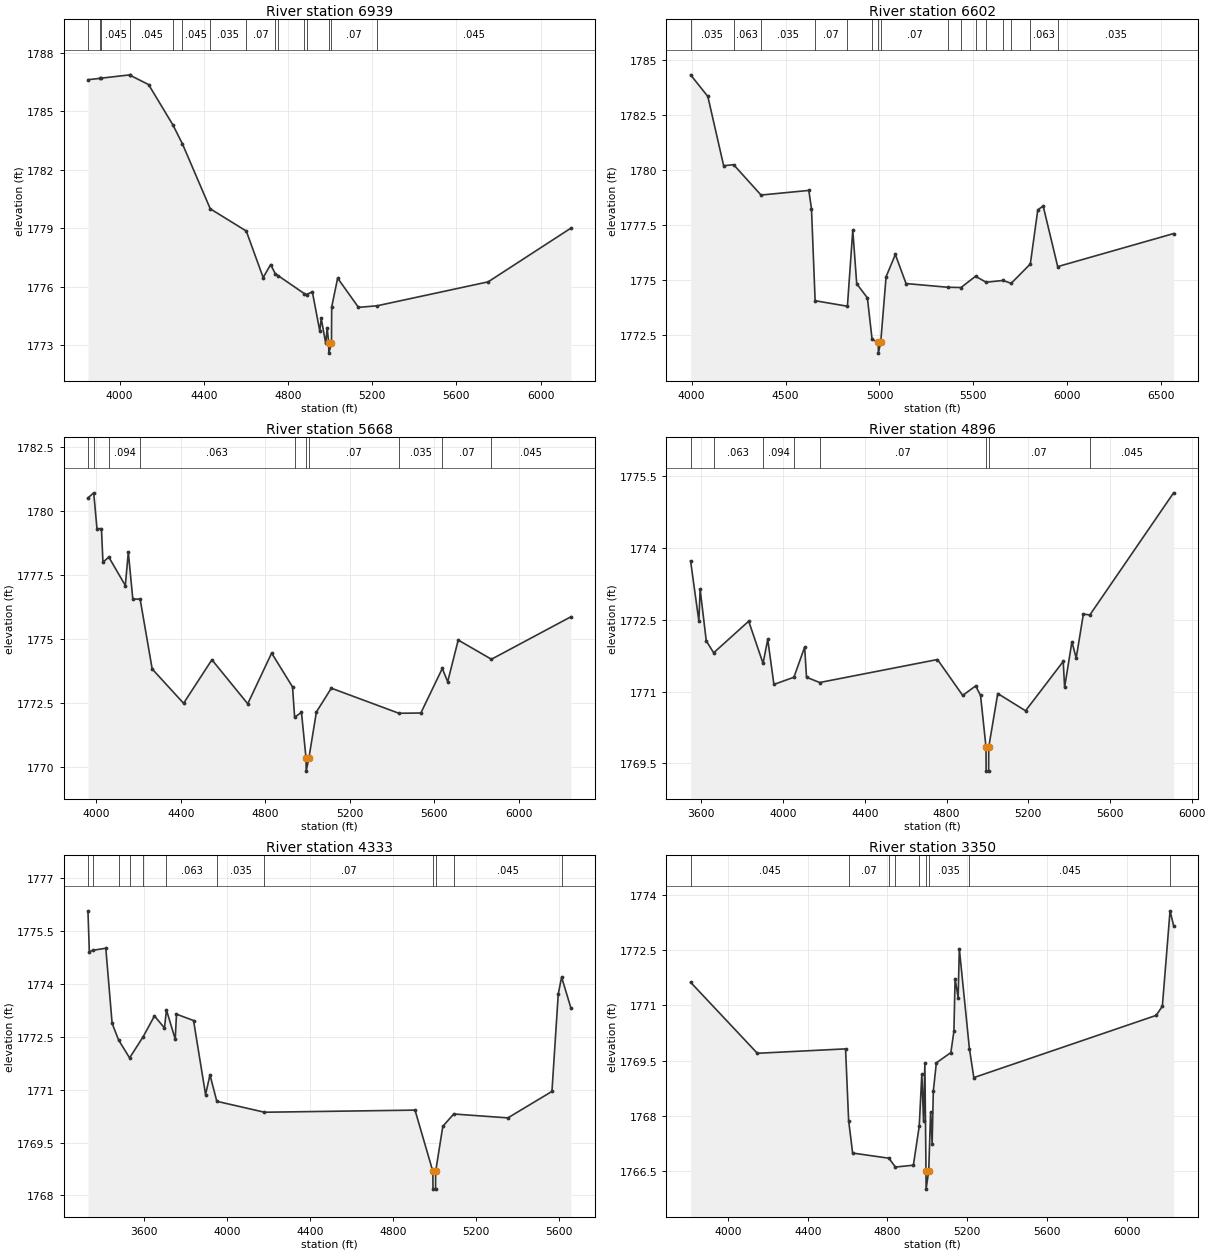
Type RM Length L Ch R = 1,6939,337,337,337
BEGIN DESCRIPTION:
Tributary No. 1 to Elm Creek 7.0
END DESCRIPTION:
XS GIS Cut Line= 3
      1566704.95      6831965.13      1567712.09      6831000.35
      1568384.96      6830402.47
#Sta/Elev= 30
  3849.6 1786.63  3909.2 1786.70  3913.6 1786.71  4050.0 1786.88  4051.2 1786.85
  4137.7 1786.38  4253.1 1784.31  4298.7 1783.33  4430.8 1780.00  4601.8 1778.86
  4682.1 1776.47  4717.6 1777.14  4739.5 1776.67  4754.3 1776.56  4877.1 1775.65
  4888.3 1775.60  4915.7 1775.74  4951.0 1773.73  4957.9 1774.37  4979.3 1773.09
  4986.2 1773.89  4993.5 1773.09  4994.0 1772.59  5006.6 1773.09  5007.6 1774.96
  5035.9 1776.44  5134.9 1774.94  5222.8 1775.02  5751.0 1776.25  6144.4 1779.01
#Mann=16,-1,0
  3849.6   0.045       0  3909.2   0.035       0  3913.6   0.045       0
  4050.0   0.035       0  4051.2   0.045       0  4253.1   0.035       0
  4298.7   0.045       0  4430.8   0.035       0  4601.8    0.07       0
  4739.5   0.045       0  4754.3    0.07       0  4877.1   0.045       0
  4888.3    0.07       0  4993.5    0.07       0  5006.6    0.07       0
  5222.8   0.045       0
Bank Sta=4993.5,5006.6
Exp/Cntr=0.3,0.1

Type RM Length L Ch R = 1,6602,934,934,934
BEGIN DESCRIPTION:
Tributary No. 1 to Elm Creek 6.0
END DESCRIPTION:
XS GIS Cut Line= 3
      1567074.85      6832176.92      1567853.52      6831301.60
      1568916.40      6830390.32
#Sta/Elev= 30
  3994.2 1784.31  4086.0 1783.33  4170.4 1780.18  4223.3 1780.23  4369.3 1778.85
  4623.7 1779.06  4637.9 1778.23  4657.3 1774.05  4829.2 1773.80  4857.8 1777.26
  4878.7 1774.82  4935.6 1774.18  4960.6 1772.29  4993.5 1772.17  4994.0 1771.67
  5006.6 1772.17  5035.1 1775.14  5084.4 1776.15  5141.3 1774.83  5365.5 1774.66
  5434.0 1774.65  5511.3 1775.16  5567.6 1774.89  5657.2 1774.97  5701.2 1774.84
  5803.0 1775.72  5842.8 1778.18  5871.4 1778.35  5948.8 1775.60  6565.8 1777.10
#Mann=16,-1,0
  3994.2   0.035       0  4223.3   0.063       0  4369.3   0.035       0
  4657.3    0.07       0  4829.2   0.035       0  4960.6    0.07       0
  4993.5    0.07       0  5006.6    0.07       0  5365.5   0.035       0
  5434.0    0.07       0  5511.3   0.035       0  5567.6    0.07       0
  5657.2   0.035       0  5701.2    0.07       0  5803.0   0.063       0
  5948.8   0.035       0
Bank Sta=4993.5,5006.6
Exp/Cntr=0.3,0.1

Type RM Length L Ch R = 1,5668,772,772,772
BEGIN DESCRIPTION:
Tributary No. 1 to Elm Creek 5.6
END DESCRIPTION:
XS GIS Cut Line= 3
      1567729.85      6832613.41      1568907.83      6831463.84
      1569297.54      6830952.96
#Sta/Elev= 30
  3960.0 1780.52  3987.4 1780.72  4002.8 1779.32  4024.0 1779.32  4031.1 1778.01
  4058.9 1778.21  4137.1 1777.10  4151.3 1778.40  4172.6 1776.57  4207.2 1776.57
  4264.4 1773.84  4413.1 1772.50  4547.3 1774.20  4717.1 1772.48  4830.3 1774.46
  4929.3 1773.14  4939.2 1771.96  4971.7 1772.14  4993.4 1770.35  4993.9 1769.85
  5006.6 1770.35  5042.4 1772.16  5113.0 1773.09  5433.2 1772.11  5537.3 1772.12
  5638.9 1773.86  5664.4 1773.34  5714.3 1774.97  5871.7 1774.22  6248.5 1775.88
#Mann=10,-1,0
  3960.0   0.094       0  3987.4   0.125       0  4058.9   0.094       0
  4207.2   0.063       0  4939.2    0.07       0  4993.4    0.07       0
  5006.6    0.07       0  5433.2   0.035       0  5638.9    0.07       0
  5871.7   0.045       0
Bank Sta=4993.4,5006.6
Exp/Cntr=0.3,0.1

Type RM Length L Ch R = 1,4896,563,563,563
BEGIN DESCRIPTION:
Tributary No. 1 to Elm Creek 5.3
END DESCRIPTION:
XS GIS Cut Line= 3
      1567910.42      6833058.29      1569192.16      6832212.10
      1569751.52      6831600.88
#Sta/Elev= 30
  3547.2 1773.73  3587.9 1772.47  3593.9 1773.14  3624.0 1772.06  3660.2 1771.81
  3831.7 1772.47  3901.9 1771.59  3925.0 1772.09  3955.1 1771.15  4053.1 1771.30
  4105.6 1771.93  4114.7 1771.30  4179.3 1771.19  4755.8 1771.67  4879.3 1770.92
  4942.7 1771.12  4966.6 1770.92  4993.4 1769.84  4993.9 1769.34  5006.2 1769.34
  5006.7 1769.84  5050.8 1770.96  5186.9 1770.60  5371.3 1771.63  5378.1 1771.09
  5413.9 1772.04  5434.8 1771.70  5470.0 1772.62  5501.5 1772.60  5911.6 1775.15
#Mann=8,-1,0
  3547.2   0.094       0  3660.2   0.063       0  3901.9   0.094       0
  4053.1   0.063       0  4179.3    0.07       0  4993.4    0.07       0
  5006.7    0.07       0  5501.5   0.045       0
Bank Sta=4993.4,5006.7
Exp/Cntr=0.3,0.1

Type RM Length L Ch R = 1,4333,983,983,983
BEGIN DESCRIPTION:
Tributary No. 1 to Elm Creek 5.0
END DESCRIPTION:
XS GIS Cut Line= 4
      1567871.70      6833335.03      1568442.20      6832981.20
      1569404.29      6832705.96      1570055.64      6832599.46
#Sta/Elev= 30
  3328.0 1776.07  3334.8 1774.91  3351.1 1774.95  3414.3 1775.01  3444.7 1772.88
  3475.9 1772.41  3529.1 1771.90  3594.5 1772.50  3649.1 1773.09  3697.4 1772.75
  3707.1 1773.26  3749.4 1772.43  3755.5 1773.14  3837.9 1772.96  3895.9 1770.86
  3917.2 1771.42  3950.1 1770.67  4180.3 1770.36  4907.1 1770.42  4993.3 1768.68
  4993.8 1768.18  5006.2 1768.18  5006.7 1768.68  5041.3 1769.96  5093.9 1770.31
  5355.4 1770.20  5568.2 1770.95  5598.6 1773.71  5614.8 1774.19  5660.0 1773.31
#Mann=12,-1,0
  3328.0   0.045       0  3351.1   0.094       0  3475.9    0.07       0
  3529.1   0.063       0  3594.5   0.035       0  3707.1   0.063       0
  3950.1   0.035       0  4180.3    0.07       0  4993.3    0.07       0
  5006.7    0.07       0  5093.9   0.045       0  5614.8    0.07       0
Bank Sta=4993.3,5006.7
Exp/Cntr=0.3,0.1

Type RM Length L Ch R = 1,3350,1046,1046,1046
BEGIN DESCRIPTION:
Tributary No. 1 to Elm Creek 4.5
END DESCRIPTION:
XS GIS Cut Line= 3
      1568138.94      6834013.61      1569429.44      6833193.63
      1570190.02      6832724.69
#Sta/Elev= 30
  3812.5 1771.63  4147.4 1769.70  4589.8 1769.82  4605.2 1767.87  4625.3 1766.99
  4807.0 1766.85  4839.7 1766.61  4929.9 1766.66  4959.3 1767.72  4972.3 1769.14
  4980.8 1767.87  4987.5 1769.44  4993.2 1766.51  4993.7 1766.01  5006.9 1766.51
  5016.3 1768.11  5024.0 1767.24  5029.9 1768.67  5045.1 1769.44  5118.0 1769.72
  5133.2 1770.30  5139.1 1771.73  5154.4 1771.21  5160.3 1772.54  5210.8 1769.83
  5233.1 1769.04  6147.8 1770.73  6178.6 1770.98  6217.2 1773.57  6235.0 1773.17
#Mann=9,-1,0
  3812.5   0.045       0  4605.2    0.07       0  4807.0   0.045       0
  4839.7    0.07       0  4959.3   0.035       0  4993.2   0.035       0
  5006.9   0.035       0  5210.8   0.045       0  6217.2    0.07       0
Bank Sta=4993.2,5006.9
Exp/Cntr=0.3,0.1

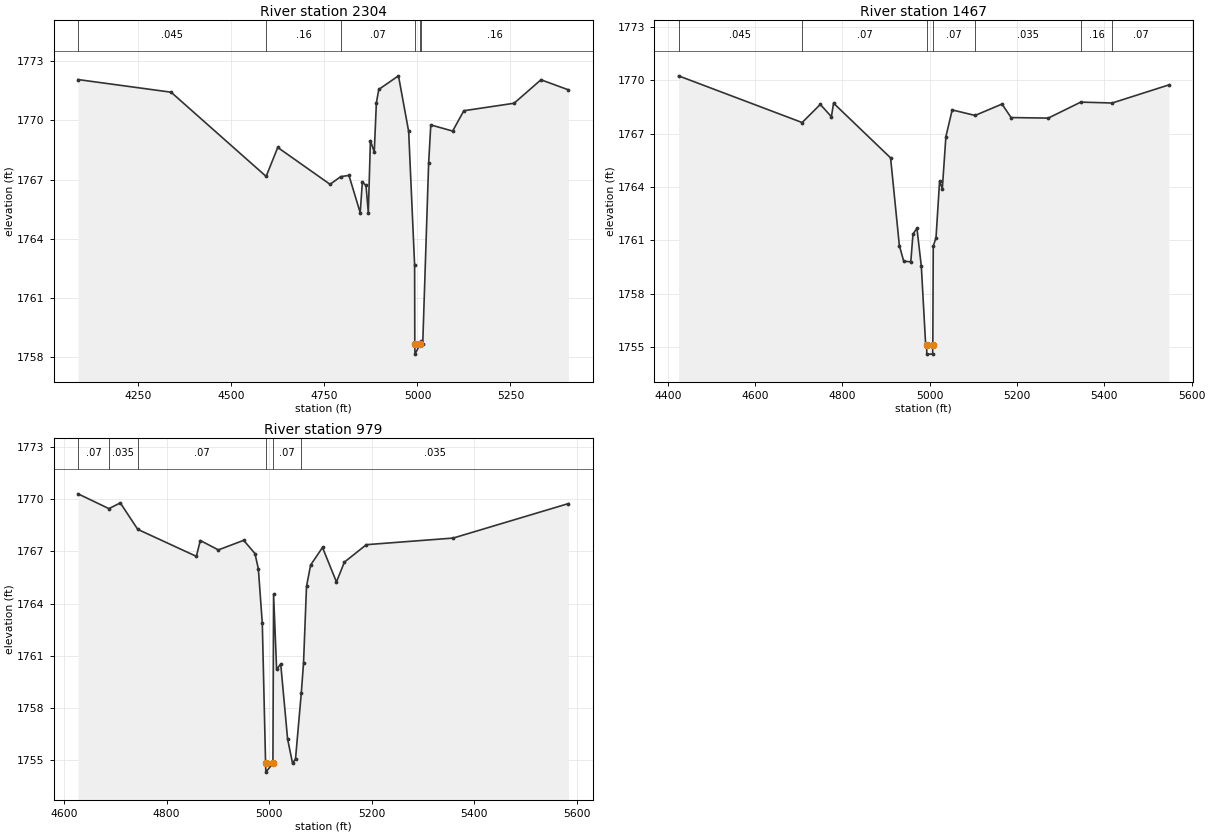
Type RM Length L Ch R = 1,2304,837,837,837
BEGIN DESCRIPTION:
Tributary No. 1 to Elm Creek 4.0
END DESCRIPTION:
XS GIS Cut Line= 3
      1569118.84      6834243.29      1569982.46      6833761.70
      1570256.38      6833578.24
#Sta/Elev= 30
  4087.5 1772.07  4337.6 1771.43  4593.2 1767.16  4624.4 1768.63  4765.0 1766.76
  4793.8 1767.15  4815.9 1767.21  4846.1 1765.32  4851.9 1766.87  4861.7 1766.70
  4867.9 1765.32  4873.6 1768.98  4883.9 1768.39  4889.6 1770.89  4896.0 1771.57
  4949.0 1772.26  4976.4 1769.44  4992.4 1762.67  4992.9 1758.65  4993.4 1758.15
  5007.1 1758.65  5010.5 1758.82  5014.2 1758.65  5030.1 1767.83  5035.9 1769.77
  5094.7 1769.46  5124.7 1770.49  5259.9 1770.87  5332.1 1772.06  5406.0 1771.55
#Mann=6,-1,0
  4087.5   0.045       0  4593.2    0.16       0  4793.8    0.07       0
  4992.9    0.07       0  5007.1    0.07       0  5010.5    0.16       0
Bank Sta=4992.9,5007.1
Exp/Cntr=0.3,0.1

Type RM Length L Ch R = 1,1467,488,488,488
BEGIN DESCRIPTION:
Tributary No. 1 to Elm Creek 3.0
END DESCRIPTION:
XS GIS Cut Line= 3
      1569322.26      6834541.35      1569894.10      6834478.37
      1570326.66      6834142.09
#Sta/Elev= 30
  4424.7 1770.26  4707.8 1767.63  4749.4 1768.65  4774.8 1767.96  4779.8 1768.72
  4910.4 1765.64  4930.5 1760.70  4940.5 1759.82  4956.7 1759.79  4961.7 1761.35
  4970.7 1761.68  4980.8 1759.54  4990.8 1755.09  4992.9 1755.09  4993.4 1754.59
  5006.6 1754.59  5007.1 1755.09  5008.1 1760.68  5014.4 1761.13  5022.6 1764.32
  5028.9 1763.91  5037.1 1766.84  5051.5 1768.34  5103.9 1768.03  5165.6 1768.67
  5186.4 1767.91  5271.5 1767.88  5346.0 1768.78  5418.0 1768.73  5547.9 1769.75
#Mann=7,-1,0
  4424.7   0.045       0  4707.8    0.07       0  4992.9    0.07       0
  5007.1    0.07       0  5103.9   0.035       0  5346.0    0.16       0
  5418.0    0.07       0
Bank Sta=4992.9,5007.1
Exp/Cntr=0.3,0.1

Type RM Length L Ch R = 1,979,459,459,459
BEGIN DESCRIPTION:
Tributary No. 1 to Elm Creek 2.0
END DESCRIPTION:
XS GIS Cut Line= 3
      1569938.94      6834997.76      1570223.79      6834757.27
      1570523.20      6834256.44
#Sta/Elev= 30
  4627.2 1770.30  4687.4 1769.45  4709.6 1769.78  4743.6 1768.26  4857.9 1766.71
  4865.6 1767.62  4900.8 1767.08  4950.2 1767.63  4972.2 1766.87  4978.8 1765.99
  4986.5 1762.86  4992.9 1754.82  4993.4 1754.32  5007.2 1754.82  5008.5 1764.53
  5014.4 1760.22  5022.4 1760.53  5035.8 1756.23  5045.5 1754.82  5051.3 1755.09
  5062.5 1758.85  5066.9 1760.59  5072.7 1764.98  5080.7 1766.21  5103.9 1767.22
  5131.1 1765.24  5146.6 1766.38  5189.4 1767.38  5358.7 1767.76  5583.5 1769.74
#Mann=6,-1,0
  4627.2    0.07       0  4687.4   0.035       0  4743.6    0.07       0
  4992.9    0.07       0  5007.2    0.07       0  5062.5   0.035       0
Bank Sta=4992.9,5007.2
Exp/Cntr=0.3,0.1