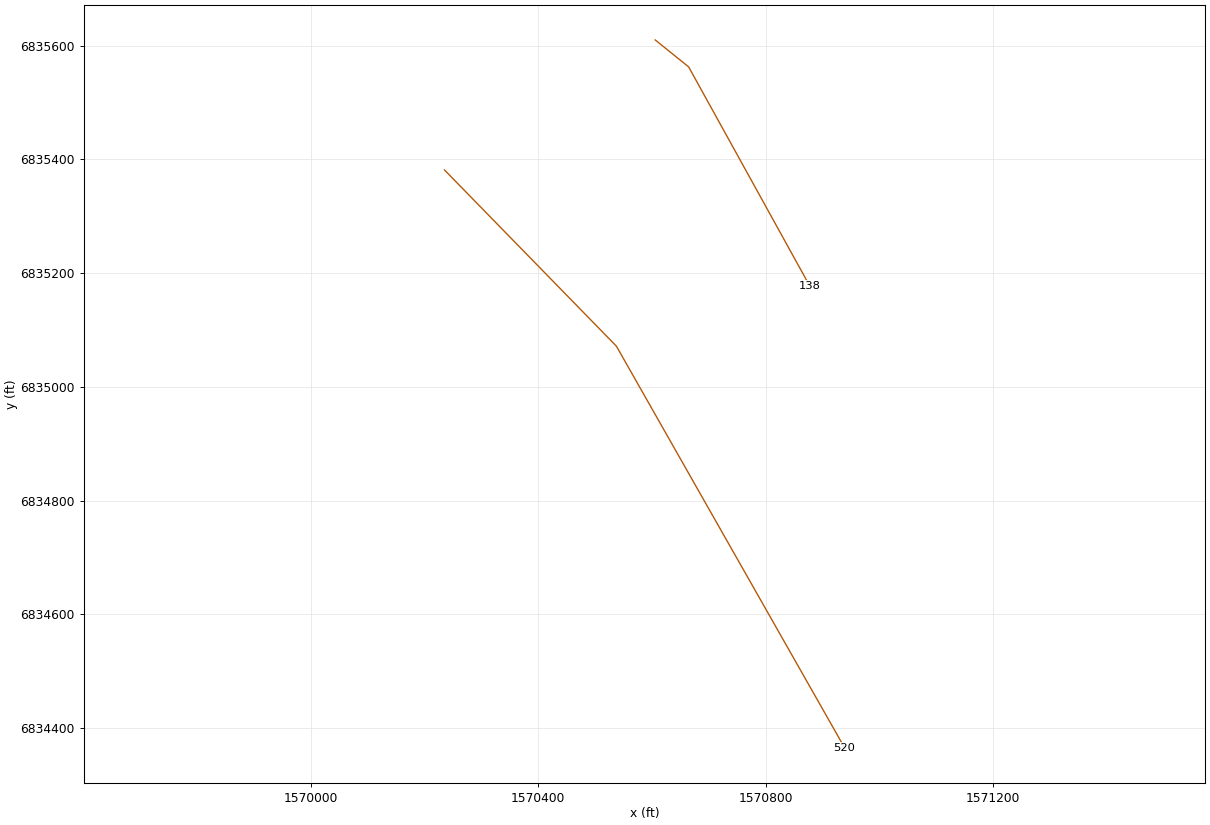
HEC-RAS study T1 to Elm Creek.prj: Tributary No. 1 to Elm Creek Base Level Engineering

--- T1 to Elm Creek.g01 (geometry) --- (continued)

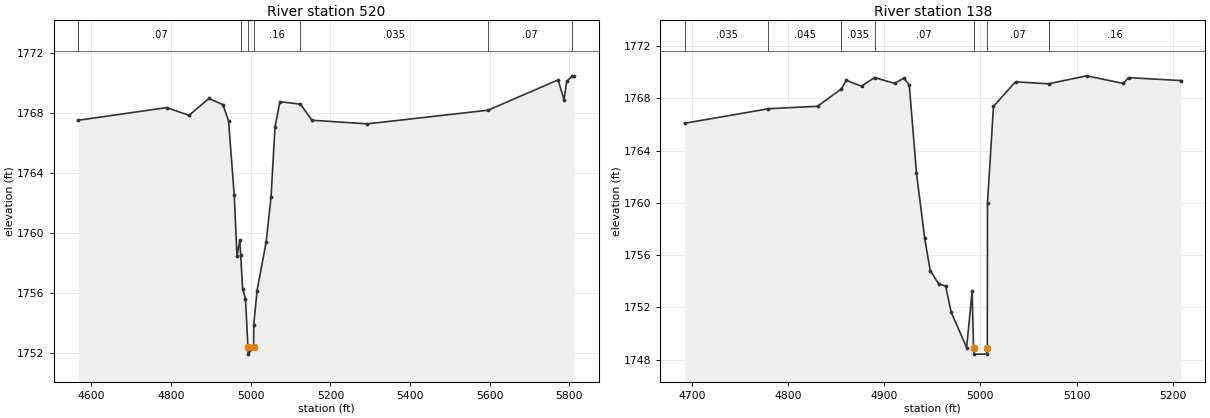
Type RM Length L Ch R = 1,520,382,382,382
BEGIN DESCRIPTION:
Tributary No. 1 to Elm Creek 1.0
END DESCRIPTION:
XS GIS Cut Line= 3
      1570235.15      6835381.48      1570537.47      6835071.63
      1570938.57      6834365.73
#Sta/Elev= 30
  4567.1 1767.51  4788.7 1768.35  4845.3 1767.84  4894.7 1768.96  4930.1 1768.55
  4944.3 1767.47  4958.4 1762.55  4965.4 1758.46  4972.6 1759.53  4974.7 1758.54
  4979.5 1756.28  4986.7 1755.62  4992.9 1752.42  4993.4 1751.92  5007.2 1752.42
  5007.5 1753.87  5015.7 1756.13  5038.7 1759.41  5050.8 1762.36  5060.9 1767.07
  5073.2 1768.75  5124.7 1768.58  5153.7 1767.51  5293.0 1767.27  5595.8 1768.18
  5771.7 1770.20  5786.3 1768.88  5793.3 1770.10  5806.5 1770.44  5811.9 1770.47
#Mann=7,-1,0
  4567.1    0.07       0  4974.7    0.16       0  4992.9    0.07       0
  5007.2    0.16       0  5124.7   0.035       0  5595.8    0.07       0
  5806.5    0.16       0
Bank Sta=4992.9,5007.2
Exp/Cntr=0.3,0.1

Type RM Length L Ch R = 1,138,0,0,0
BEGIN DESCRIPTION:
Tributary No. 1 to Elm Creek 0.5
END DESCRIPTION:
XS GIS Cut Line= 3
      1570605.76      6835610.08      1570664.54      6835562.71
      1570877.33      6835177.80
#Sta/Elev= 30
  4692.8 1766.09  4779.7 1767.20  4830.8 1767.39  4855.3 1768.71  4860.8 1769.37
  4876.5 1768.93  4890.0 1769.59  4910.8 1769.14  4920.4 1769.54  4926.1 1769.02
  4933.6 1762.26  4942.1 1757.30  4947.9 1754.80  4956.5 1753.82  4963.9 1753.62
  4969.6 1751.64  4985.7 1748.92  4991.4 1753.22  4992.9 1748.92  4993.4 1748.42
  5006.7 1748.42  5007.2 1748.92  5007.4 1760.00  5013.6 1767.39  5036.5 1769.26
  5070.8 1769.11  5110.5 1769.72  5148.3 1769.14  5154.0 1769.58  5208.1 1769.36
#Mann=7,-1,0
  4692.8   0.035       0  4779.7   0.045       0  4855.3   0.035       0
  4890.0    0.07       0  4992.9    0.07       0  5007.2    0.07       0
  5070.8    0.16       0
Bank Sta=4992.9,5007.2
Exp/Cntr=0.3,0.1

Chan Stop Cuts=-1