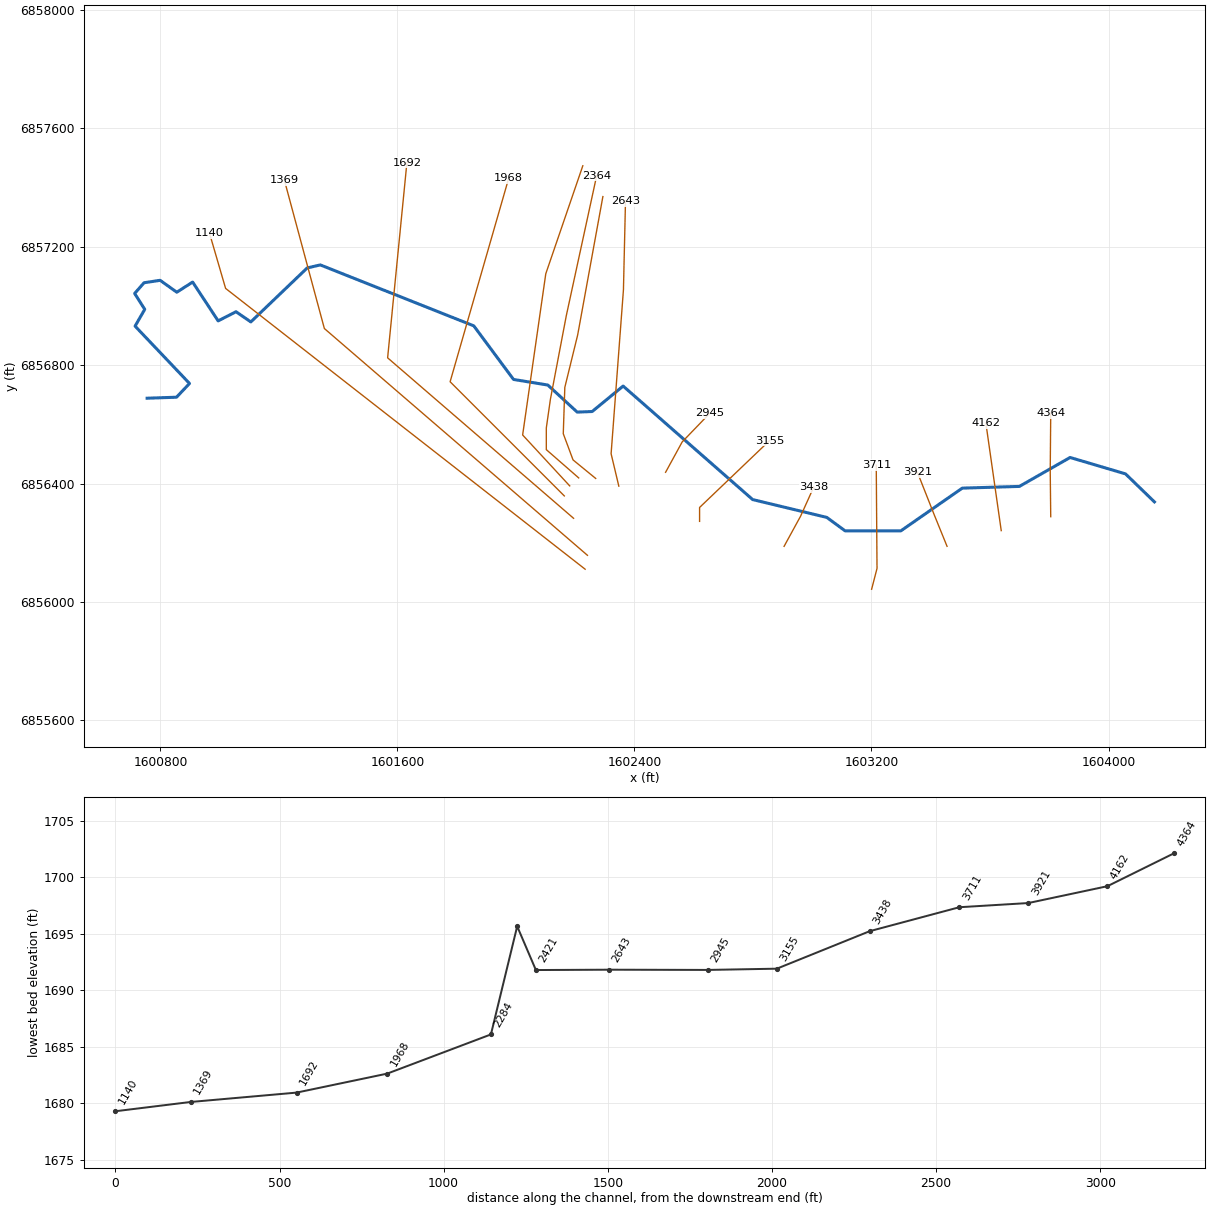
--- Unnamed Tributary 1 to Rainy Cr.prj (project) ---

Proj Title=Unnamed Tributary 1 to Rainy Cr Base Level Engineering
Current Plan=p01
Default Exp/Contr=0.3,0.1
English Units
Geom File=g01
Flow File=f01
Plan File=p01
BEGIN DESCRIPTION:
Unnamed Tributary 1 to Rainy Cr
END DESCRIPTION:

--- Unnamed Tributary 1 to Rainy Cr.p01 (plan) ---

Plan Title=Multiple Run
Short Identifier=Multiple
Geom File=g01
Flow File=f01
Subcritical Flow
K Sum by GR= 0
Std Step Tol= 0.01
Critical Tol= 0.01
Num of Std Step Trials= 20
Max Error Tol= 0.3
Flow Tol Ratio= 0.001
Split Flow NTrial= 30
Split Flow Tol= 0.02
Split Flow Ratio= 0.02
Log Output Level= 0
Friction Slope Method= 1
Unsteady Friction Slope Method= 2
Unsteady Bridges Friction Slope Method= 1
Parabolic Critical Depth
Global Vel Dist=  1 , 1 , 1
Global Log Level= 0
CheckData=True
Encroach Param= -1, 0, 0, 0
BEGIN DESCRIPTION:
Multiple Run
END DESCRIPTION:

--- Unnamed Tributary 1 to Rainy Cr.f01 (steady flow) ---

Flow Title=Multiple
Number of Profiles=7
Profile Names=10-year,25-year,50-year,1pct_min,100-year,1pct_plu,500-year
River Rch & RM= Unnamed Tributar,Reach-1,4364
     127     169     202     151     242     332     348
Boundary for River Rch & Prof#=Unnamed Tributar,Reach-1,1
Up Type=0
Dn Type=3
Dn Slope=0.001
Boundary for River Rch & Prof#=Unnamed Tributar,Reach-1,2
Up Type=0
Dn Type=3
Dn Slope=0.001
Boundary for River Rch & Prof#=Unnamed Tributar,Reach-1,3
Up Type=0
Dn Type=3
Dn Slope=0.001
Boundary for River Rch & Prof#=Unnamed Tributar,Reach-1,4
Up Type=0
Dn Type=3
Dn Slope=0.001
Boundary for River Rch & Prof#=Unnamed Tributar,Reach-1,5
Up Type=0
Dn Type=3
Dn Slope=0.001
Boundary for River Rch & Prof#=Unnamed Tributar,Reach-1,6
Up Type=0
Dn Type=3
Dn Slope=0.001
Boundary for River Rch & Prof#=Unnamed Tributar,Reach-1,7
Up Type=0
Dn Type=3
Dn Slope=0.001

--- Unnamed Tributary 1 to Rainy Cr.g01 (geometry) ---

Geom Title=Existing Conditions

River Reach=Unnamed Tributar,Reach-1
Reach XY= 30
      1604155.00      6856338.00      1604057.45      6856432.54
      1603870.39      6856487.92      1603699.07      6856390.24
      1603506.47      6856384.45      1603299.07      6856240.24
      1603110.94      6856240.26      1603049.02      6856285.64
      1602798.83      6856345.86      1602361.67      6856729.04
      1602257.29      6856643.10      1602206.65      6856641.11
      1602107.42      6856732.46      1601991.67      6856751.39
      1601857.55      6856932.27      1601339.58      6857137.97
      1601295.32      6857127.81      1601105.00      6856945.54
      1601054.99      6856979.94      1600994.68      6856949.10
      1600908.58      6857080.11      1600855.10      6857045.84
      1600798.87      6857086.03      1600744.61      6857077.80
      1600712.88      6857041.66      1600746.94      6856988.01
      1600714.29      6856931.33      1600898.06      6856737.77
      1600854.17      6856691.38      1600755.00      6856688.00

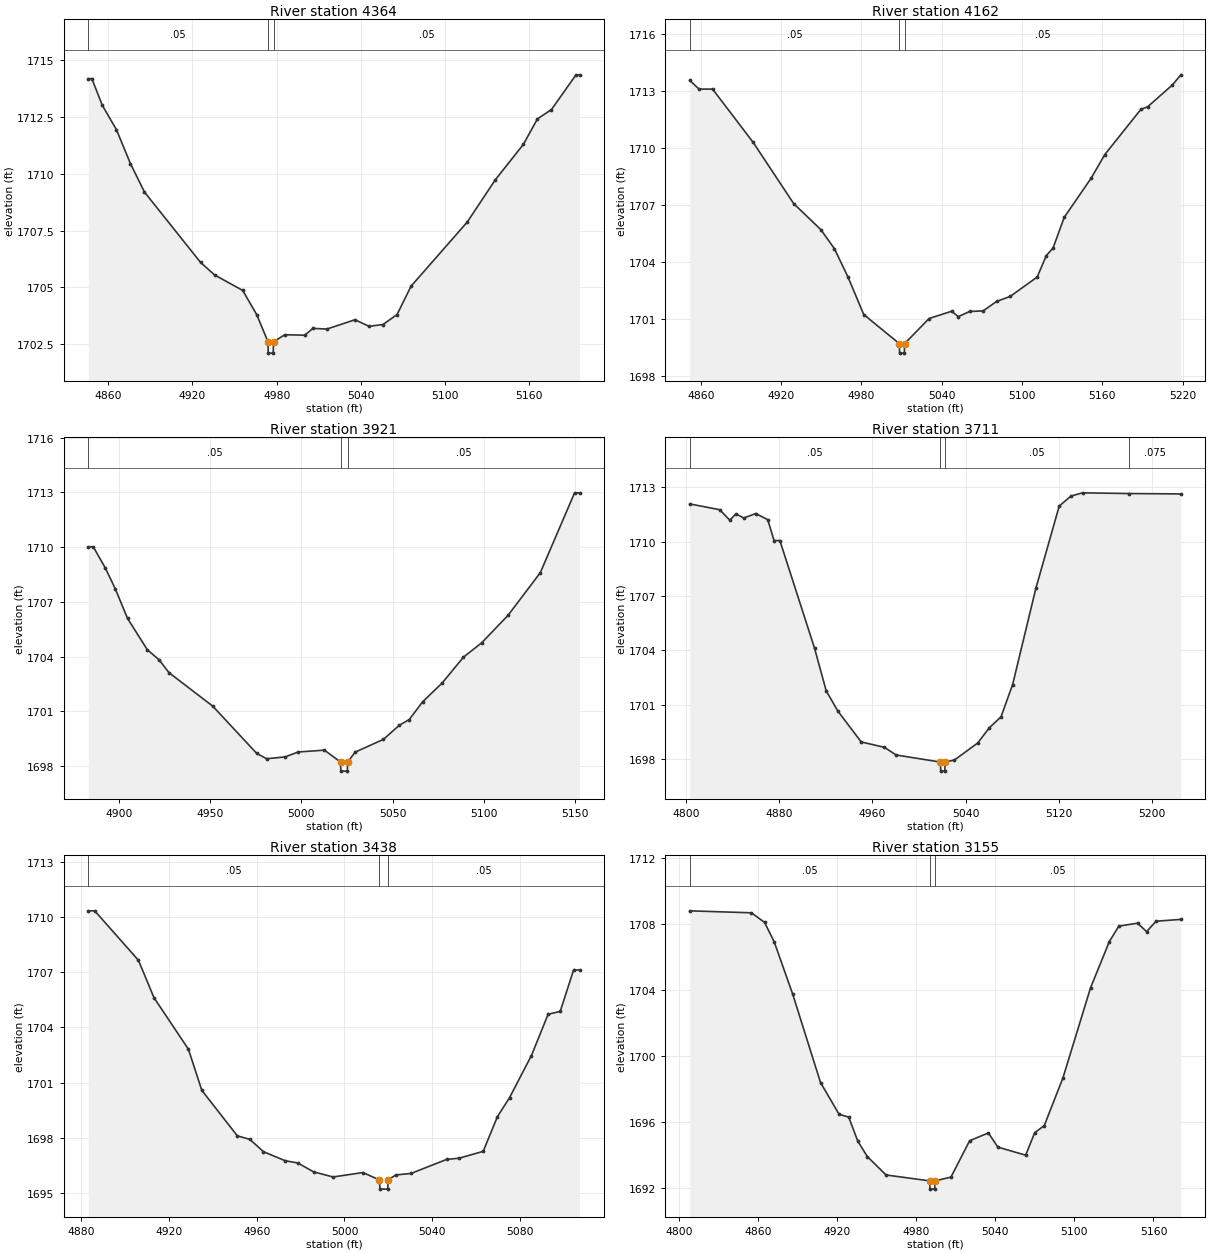
Type RM Length L Ch R = 1,4364,202,202,202
BEGIN DESCRIPTION:
Unnamed Tributary 1 to Rainy Cr 4363.942
END DESCRIPTION:
XS GIS Cut Line= 3
      1603805.00      6856288.03      1603803.28      6856442.22
      1603805.00      6856638.01
#Sta/Elev= 30
  4845.8 1714.19  4848.3 1714.19  4855.8 1713.01  4865.8 1711.95  4875.8 1710.45
  4885.8 1709.20  4925.8 1706.10  4935.8 1705.55  4955.8 1704.87  4965.8 1703.80
  4973.8 1702.61  4974.0 1702.11  4977.5 1702.11  4977.8 1702.61  4985.8 1702.92
  5000.0 1702.90  5005.8 1703.20  5015.8 1703.17  5035.8 1703.58  5045.8 1703.29
  5055.8 1703.37  5065.8 1703.81  5075.8 1705.06  5115.8 1707.88  5135.8 1709.74
  5155.8 1711.30  5165.8 1712.42  5175.8 1712.83  5193.3 1714.36  5195.8 1714.36
#Mann=3,-1,0
  4845.8    0.05       0  4973.8    0.03       0  4977.8    0.05       0
Bank Sta=4973.8,4977.8
Exp/Cntr=0.3,0.1

Type RM Length L Ch R = 1,4162,241,241,241
BEGIN DESCRIPTION:
Mapping XS 0d1da760
END DESCRIPTION:
XS GIS Cut Line= 2
      1603637.91      6856241.03      1603586.03      6856604.25
#Sta/Elev= 30
  4851.7 1713.55  4858.7 1713.09  4868.8 1713.09  4899.1 1710.29  4929.4 1707.07
  4949.7 1705.70  4959.8 1704.70  4969.9 1703.22  4981.7 1701.24  5008.3 1699.71
  5008.5 1699.21  5012.0 1699.21  5012.3 1699.71  5030.5 1701.03  5047.3 1701.41
  5052.4 1701.13  5060.8 1701.40  5070.9 1701.43  5081.0 1701.93  5091.1 1702.19
  5111.3 1703.21  5118.1 1704.34  5123.1 1704.73  5131.5 1706.35  5151.7 1708.42
  5161.8 1709.65  5188.8 1712.03  5193.8 1712.16  5212.3 1713.31  5218.6 1713.84
#Mann=3,-1,0
  4851.7    0.05       0  5008.3    0.05       0  5012.3    0.05       0
Bank Sta=5008.3,5012.3
Exp/Cntr=0.3,0.1

Type RM Length L Ch R = 1,3921,210,210,210
BEGIN DESCRIPTION:
Unnamed Tributary 1 to Rainy Cr 3920.874
END DESCRIPTION:
XS GIS Cut Line= 3
      1603454.98      6856188.04      1603411.05      6856296.16
      1603355.01      6856437.99
#Sta/Elev= 30
  4883.3 1710.02  4886.0 1710.02  4892.6 1708.86  4898.0 1707.73  4904.8 1706.09
  4915.6 1704.38  4922.1 1703.82  4927.5 1703.12  4951.5 1701.28  4975.6 1698.69
  4981.0 1698.40  4991.2 1698.50  4998.3 1698.77  5012.7 1698.87  5021.5 1698.22
  5021.7 1697.72  5025.2 1697.72  5025.5 1698.22  5029.5 1698.76  5045.0 1699.46
  5053.8 1700.24  5059.2 1700.55  5066.5 1701.52  5077.2 1702.55  5088.9 1703.97
  5098.8 1704.75  5113.3 1706.26  5131.0 1708.60  5149.8 1712.98  5152.5 1712.98
#Mann=3,-1,0
  4883.3    0.05       0  5021.5    0.03       0  5025.5    0.05       0
Bank Sta=5021.5,5025.5
Exp/Cntr=0.3,0.1

Type RM Length L Ch R = 1,3711,273,273,273
BEGIN DESCRIPTION:
Mapping XS 7338de03
END DESCRIPTION:
XS GIS Cut Line= 3
      1603200.43      6856043.12      1603218.65      6856113.40
      1603216.04      6856462.39
#Sta/Elev= 30
  4803.2 1712.08  4828.9 1711.76  4837.7 1711.18  4842.9 1711.53  4849.6 1711.30
  4859.9 1711.55  4870.2 1711.21  4875.6 1710.06  4880.6 1710.06  4910.4 1704.12
  4920.4 1701.77  4930.4 1700.66  4950.4 1698.96  4970.4 1698.66  4980.4 1698.24
  5018.4 1697.85  5018.7 1697.35  5022.2 1697.35  5022.4 1697.85  5030.4 1697.96
  5050.4 1698.90  5060.4 1699.74  5070.4 1700.34  5080.4 1702.12  5100.4 1707.44
  5120.4 1711.96  5130.4 1712.51  5140.4 1712.69  5180.5 1712.65  5224.8 1712.63
#Mann=4,-1,0
  4803.2    0.05       0  5018.4    0.03       0  5022.4    0.05       0
  5180.5   0.075       0
Bank Sta=5018.4,5022.4
Exp/Cntr=0.3,0.1

Type RM Length L Ch R = 1,3438,283,283,283
BEGIN DESCRIPTION:
Unnamed Tributary 1 to Rainy Cr 3438.383
END DESCRIPTION:
XS GIS Cut Line= 3
      1602904.98      6856187.96      1602960.97      6856290.35
      1603004.99      6856387.99
#Sta/Elev= 30
  4883.3 1710.33  4886.2 1710.33  4906.1 1707.65  4913.2 1705.62  4928.9 1702.82
  4935.0 1700.59  4951.2 1698.12  4956.9 1697.93  4963.1 1697.26  4973.0 1696.77
  4978.7 1696.65  4985.9 1696.17  4994.8 1695.89  5008.4 1696.13  5015.9 1695.73
  5016.2 1695.23  5019.7 1695.23  5019.9 1695.73  5023.4 1696.00  5030.3 1696.08
  5046.5 1696.84  5052.3 1696.91  5063.2 1697.28  5069.7 1699.16  5075.2 1700.19
  5085.2 1702.48  5092.8 1704.72  5098.3 1704.87  5104.4 1707.12  5107.1 1707.12
#Mann=3,-1,0
  4883.3    0.05       0  5015.9    0.05       0  5019.9    0.05       0
Bank Sta=5015.9,5019.9
Exp/Cntr=0.3,0.1

Type RM Length L Ch R = 1,3155,210,210,210
BEGIN DESCRIPTION:
Mapping XS 5063bdf6
END DESCRIPTION:
XS GIS Cut Line= 3
      1602619.69      6856272.24      1602619.69      6856319.13
      1602855.27      6856544.35
#Sta/Elev= 30
  4808.0 1708.80  4854.9 1708.68  4864.8 1708.10  4872.1 1706.93  4886.2 1703.74
  4907.3 1698.38  4921.4 1696.45  4928.7 1696.28  4935.6 1694.82  4942.8 1693.89
  4957.0 1692.77  4990.2 1692.41  4990.4 1691.91  4993.9 1691.91  4994.2 1692.41
  5006.3 1692.64  5020.5 1694.85  5034.7 1695.32  5041.9 1694.46  5063.0 1693.97
  5069.9 1695.34  5077.1 1695.76  5091.3 1698.66  5112.3 1704.14  5126.5 1706.93
  5133.7 1707.87  5147.9 1708.05  5154.8 1707.54  5162.0 1708.17  5180.8 1708.28
#Mann=3,-1,0
  4808.0    0.05       0  4990.2    0.05       0  4994.2    0.05       0
Bank Sta=4990.2,4994.2
Exp/Cntr=0.3,0.1

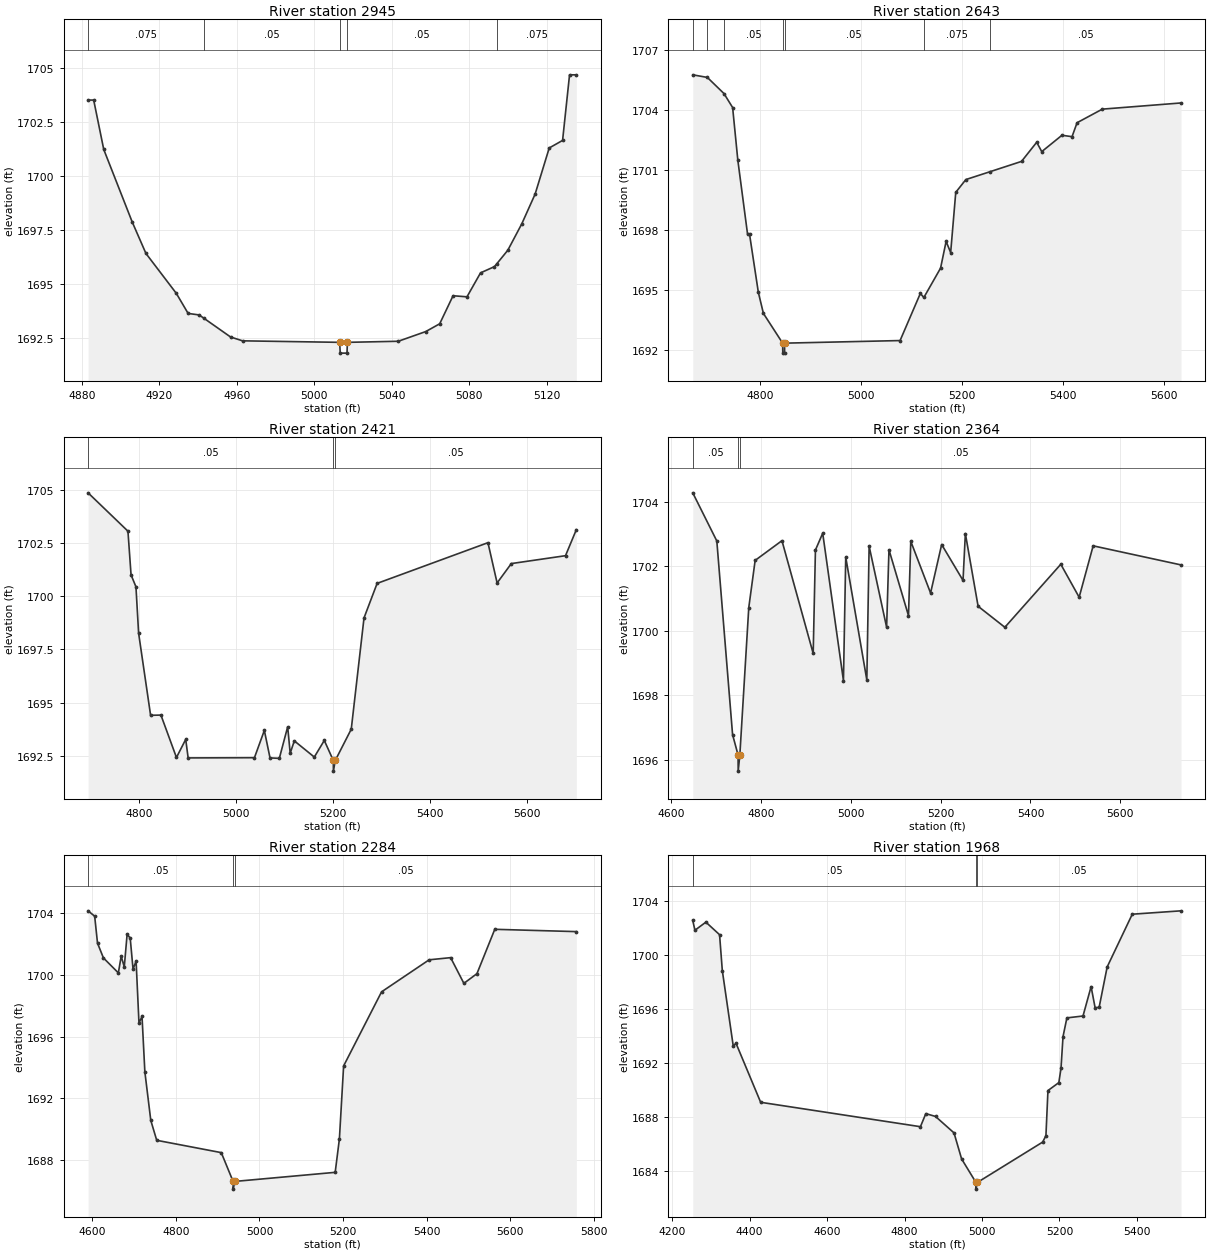
Type RM Length L Ch R = 1,2945,302,302,302
BEGIN DESCRIPTION:
Unnamed Tributary 1 to Rainy Cr 2945.126
END DESCRIPTION:
XS GIS Cut Line= 3
      1602504.98      6856437.96      1602561.05      6856540.53
      1602655.02      6856638.02
#Sta/Elev= 30
  4883.1 1703.53  4886.0 1703.53  4891.2 1701.24  4905.9 1697.88  4913.0 1696.42
  4928.7 1694.57  4934.8 1693.64  4940.5 1693.57  4942.9 1693.42  4956.7 1692.55
  4962.9 1692.37  5013.1 1692.30  5013.4 1691.80  5016.9 1691.80  5017.1 1692.30
  5043.4 1692.35  5057.6 1692.80  5064.8 1693.16  5071.7 1694.46  5078.9 1694.41
  5085.9 1695.52  5093.1 1695.81  5094.2 1695.93  5100.0 1696.57  5107.2 1697.79
  5114.1 1699.17  5121.4 1701.31  5128.3 1701.66  5131.9 1704.70  5135.4 1704.70
#Mann=5,-1,0
  4883.1   0.075       0  4942.9    0.05       0  5013.1    0.03       0
  5017.1    0.05       0  5094.2   0.075       0
Bank Sta=5013.1,5017.1
Exp/Cntr=0.3,0.1

Type RM Length L Ch R = 1,2643,222,222,222
BEGIN DESCRIPTION:
Mapping XS 6e10091e
END DESCRIPTION:
XS GIS Cut Line= 4
      1602347.13      6856391.14      1602321.08      6856500.55
      1602362.74      6857054.37      1602369.67      6857353.84
#Sta/Elev= 30
  4666.8 1705.77  4695.7 1705.64  4728.7 1704.83  4745.8 1704.13  4756.1 1701.49
  4775.4 1697.78  4779.3 1697.78  4796.8 1694.86  4806.8 1693.81  4844.9 1692.32
  4845.2 1691.82  4848.7 1691.82  4848.9 1692.32  5077.6 1692.45  5117.7 1694.81
  5124.7 1694.61  5157.8 1696.08  5168.8 1697.42  5177.8 1696.86  5187.9 1699.88
  5207.9 1700.52  5255.3 1700.91  5318.2 1701.43  5348.3 1702.39  5358.3 1701.92
  5398.3 1702.74  5418.3 1702.67  5428.3 1703.37  5478.3 1704.05  5634.2 1704.36
#Mann=7,-1,0
  4666.8    0.05       0  4695.7   0.075       0  4728.7    0.05       0
  4844.9    0.03       0  4848.9    0.05       0  5124.7   0.075       0
  5255.3    0.05       0
Bank Sta=4844.9,4848.9
Exp/Cntr=0.3,0.1

Type RM Length L Ch R = 1,2421,57,57,57
BEGIN DESCRIPTION:
Mapping XS e1e4fbb5
END DESCRIPTION:
XS GIS Cut Line= 6
      1602269.00      6856417.21      1602192.60      6856479.72
      1602159.62      6856568.26      1602164.83      6856724.51
      1602208.23      6856901.59      1602293.31      6857368.65
#Sta/Elev= 30
  4695.4 1704.85  4777.6 1703.05  4784.0 1701.00  4794.1 1700.44  4799.6 1698.26
  4824.3 1694.41  4845.6 1694.42  4877.6 1692.43  4896.7 1693.28  4901.7 1692.41
  5038.4 1692.42  5058.8 1693.70  5070.5 1692.41  5089.7 1692.39  5106.9 1693.87
  5112.1 1692.63  5120.6 1693.21  5161.8 1692.45  5182.4 1693.23  5201.0 1692.29
  5201.2 1691.79  5205.0 1692.29  5238.0 1693.76  5264.3 1698.98  5291.3 1700.60
  5519.8 1702.51  5538.7 1700.62  5568.0 1701.53  5679.7 1701.90  5702.0 1703.12
#Mann=3,-1,0
  4695.4    0.05       0  5201.0    0.05       0  5205.0    0.05       0
Bank Sta=5201,5205
Exp/Cntr=0.3,0.1

Type RM Length L Ch R = 1,2364,80,80,80
BEGIN DESCRIPTION:
Mapping XS b8fdb6d8
END DESCRIPTION:
XS GIS Cut Line= 6
      1602211.69      6856418.96      1602102.33      6856514.44
      1602102.33      6856587.36      1602116.22      6856684.58
      1602170.04      6856967.56      1602272.46      6857439.75
#Sta/Elev= 30
  4647.6 1704.27  4701.2 1702.78  4736.3 1696.79  4748.5 1696.16  4748.8 1695.66
  4752.5 1696.16  4772.4 1700.72  4786.6 1702.18  4846.3 1702.79  4915.9 1699.30
  4920.9 1702.50  4937.1 1703.02  4983.3 1698.46  4988.4 1702.28  5035.4 1698.48
  5040.5 1702.62  5079.5 1700.11  5084.7 1702.51  5128.2 1700.47  5133.3 1702.77
  5177.4 1701.17  5202.1 1702.67  5249.7 1701.56  5254.9 1703.01  5283.3 1700.76
  5342.9 1700.11  5467.5 1702.06  5508.4 1701.04  5539.6 1702.63  5735.3 1702.04
#Mann=3,-1,0
  4647.6    0.05       0  4748.5    0.05       0  4752.5    0.05       0
Bank Sta=4748.5,4752.5
Exp/Cntr=0.3,0.1

Type RM Length L Ch R = 1,2284,316,316,316
BEGIN DESCRIPTION:
Mapping XS e4c7b1b5
END DESCRIPTION:
XS GIS Cut Line= 4
      1602181.34      6856392.03      1602022.47      6856563.92
      1602100.59      6857108.19      1602225.58      6857472.74
#Sta/Elev= 30
  4589.5 1704.16  4605.3 1703.81  4612.1 1702.06  4626.3 1701.10  4662.0 1700.13
  4668.8 1701.21  4676.2 1700.52  4683.0 1702.64  4690.4 1702.39  4697.2 1700.37
  4704.5 1700.90  4711.4 1696.87  4718.7 1697.30  4725.5 1693.70  4739.7 1690.55
  4753.9 1689.26  4908.5 1688.46  4936.8 1686.59  4937.1 1686.09  4940.8 1686.59
  5181.3 1687.18  5191.4 1689.35  5201.5 1694.09  5292.4 1698.90  5406.3 1700.98
  5457.8 1701.12  5489.5 1699.45  5520.8 1700.08  5563.5 1702.96  5758.8 1702.81
#Mann=3,-1,0
  4589.5    0.05       0  4936.8    0.05       0  4940.8    0.05       0
Bank Sta=4936.8,4940.8
Exp/Cntr=0.3,0.1

Type RM Length L Ch R = 1,1968,276,276,276
BEGIN DESCRIPTION:
Mapping XS 250ffdb4
END DESCRIPTION:
XS GIS Cut Line= 3
      1602163.09      6856358.19      1601777.67      6856743.61
      1601975.60      6857431.13
#Sta/Elev= 30
  4253.2 1702.55  4258.8 1701.82  4287.1 1702.42  4322.4 1701.49  4329.5 1698.83
  4357.8 1693.22  4364.8 1693.44  4428.5 1689.06  4841.0 1687.25  4854.9 1688.22
  4879.9 1688.01  4927.7 1686.79  4947.3 1684.86  4984.2 1683.12  4984.4 1682.62
  4988.2 1683.12  5156.6 1686.11  5165.0 1686.59  5170.2 1689.93  5198.3 1690.52
  5203.9 1691.58  5209.1 1693.93  5219.1 1695.32  5260.7 1695.46  5281.6 1697.64
  5291.9 1696.08  5302.3 1696.10  5323.1 1699.10  5387.9 1703.01  5513.7 1703.26
#Mann=3,-1,0
  4253.2    0.05       0  4984.2    0.05       0  4988.2    0.05       0
Bank Sta=4984.2,4988.2
Exp/Cntr=0.3,0.1

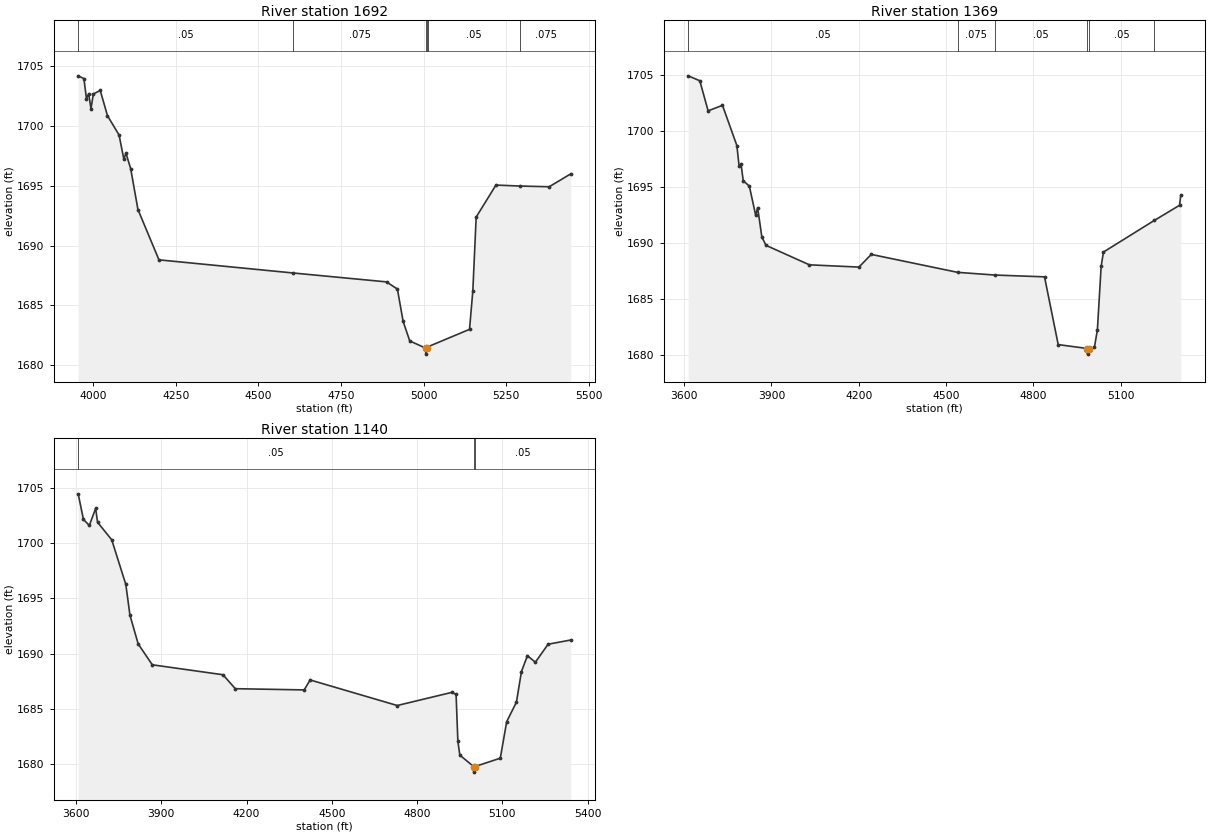
Type RM Length L Ch R = 1,1692,323,323,323
BEGIN DESCRIPTION:
Mapping XS 8cef4535
END DESCRIPTION:
XS GIS Cut Line= 3
      1602194.38      6856282.64      1601566.74      6856824.33
      1601631.83      6857483.05
#Sta/Elev= 30
  3954.8 1704.17  3972.2 1703.94  3979.9 1702.25  3986.5 1702.68  3993.6 1701.43
  4000.7 1702.65  4021.6 1702.95  4043.5 1700.84  4078.6 1699.23  4092.9 1697.23
  4099.5 1697.71  4113.8 1696.41  4135.7 1693.01  4199.3 1688.81  4606.4 1687.71
  4888.0 1686.97  4921.0 1686.37  4938.3 1683.67  4958.4 1682.04  5006.6 1681.44
  5006.9 1680.94  5010.6 1681.44  5013.0 1681.55  5139.3 1683.01  5149.3 1686.23
  5159.4 1692.38  5219.2 1695.05  5292.8 1694.97  5380.4 1694.91  5445.8 1695.99
#Mann=6,-1,0
  3954.8    0.05       0  4606.4   0.075       0  5006.6    0.07       0
  5010.6   0.075       0  5013.0    0.05       0  5292.8   0.075       0
Bank Sta=5006.6,5010.6
Exp/Cntr=0.3,0.1

Type RM Length L Ch R = 1,1369,229,229,229
BEGIN DESCRIPTION:
Mapping XS 2f8aa1a0
END DESCRIPTION:
XS GIS Cut Line= 3
      1602241.23      6856157.66      1601353.20      6856923.29
      1601218.18      6857424.40
#Sta/Elev= 30
  3614.3 1704.92  3654.3 1704.48  3682.8 1701.80  3732.2 1702.29  3781.6 1698.70
  3789.3 1696.85  3795.9 1697.04  3803.5 1695.56  3824.4 1695.09  3846.3 1692.47
  3852.9 1693.17  3867.2 1690.57  3881.4 1689.81  4030.6 1688.07  4200.7 1687.87
  4243.1 1689.00  4539.7 1687.40  4667.0 1687.16  4837.9 1687.00  4884.9 1680.96
  4985.3 1680.61  4985.5 1680.11  4989.3 1680.61  5009.2 1680.71  5019.5 1682.28
  5032.4 1687.94  5040.3 1689.21  5215.0 1692.03  5301.6 1693.38  5305.8 1694.30
#Mann=6,-1,0
  3614.3    0.05       0  4539.7   0.075       0  4667.0    0.05       0
  4985.3    0.03       0  4989.3    0.05       0  5215.0   0.075       0
Bank Sta=4985.3,4989.3
Exp/Cntr=0.3,0.1

Type RM Length L Ch R = 1,1140,0,0,0
BEGIN DESCRIPTION:
Unnamed Tributary 1 to Rainy Cr 2479.423
END DESCRIPTION:
XS GIS Cut Line= 3
      1602233.44      6856110.76      1601019.86      6857058.71
      1600965.63      6857244.64
#Sta/Elev= 30
  3607.3 1704.44  3625.8 1702.13  3646.6 1701.58  3668.8 1703.13  3675.5 1701.87
  3725.3 1700.29  3775.0 1696.25  3789.5 1693.47  3818.4 1690.88  3868.1 1688.99
  4116.9 1688.09  4160.3 1686.83  4402.7 1686.72  4423.5 1687.62  4730.1 1685.31
  4922.7 1686.50  4937.2 1686.31  4943.5 1682.07  4950.4 1680.83  4999.1 1679.79
  4999.4 1679.29  5003.1 1679.79  5092.8 1680.55  5115.3 1683.85  5149.5 1685.61
  5167.3 1688.38  5188.2 1689.81  5216.2 1689.22  5261.1 1690.85  5340.9 1691.23
#Mann=3,-1,0
  3607.3    0.05       0  4999.1    0.05       0  5003.1    0.05       0
Bank Sta=4999.1,5003.1
Exp/Cntr=0.3,0.1

Chan Stop Cuts=-1