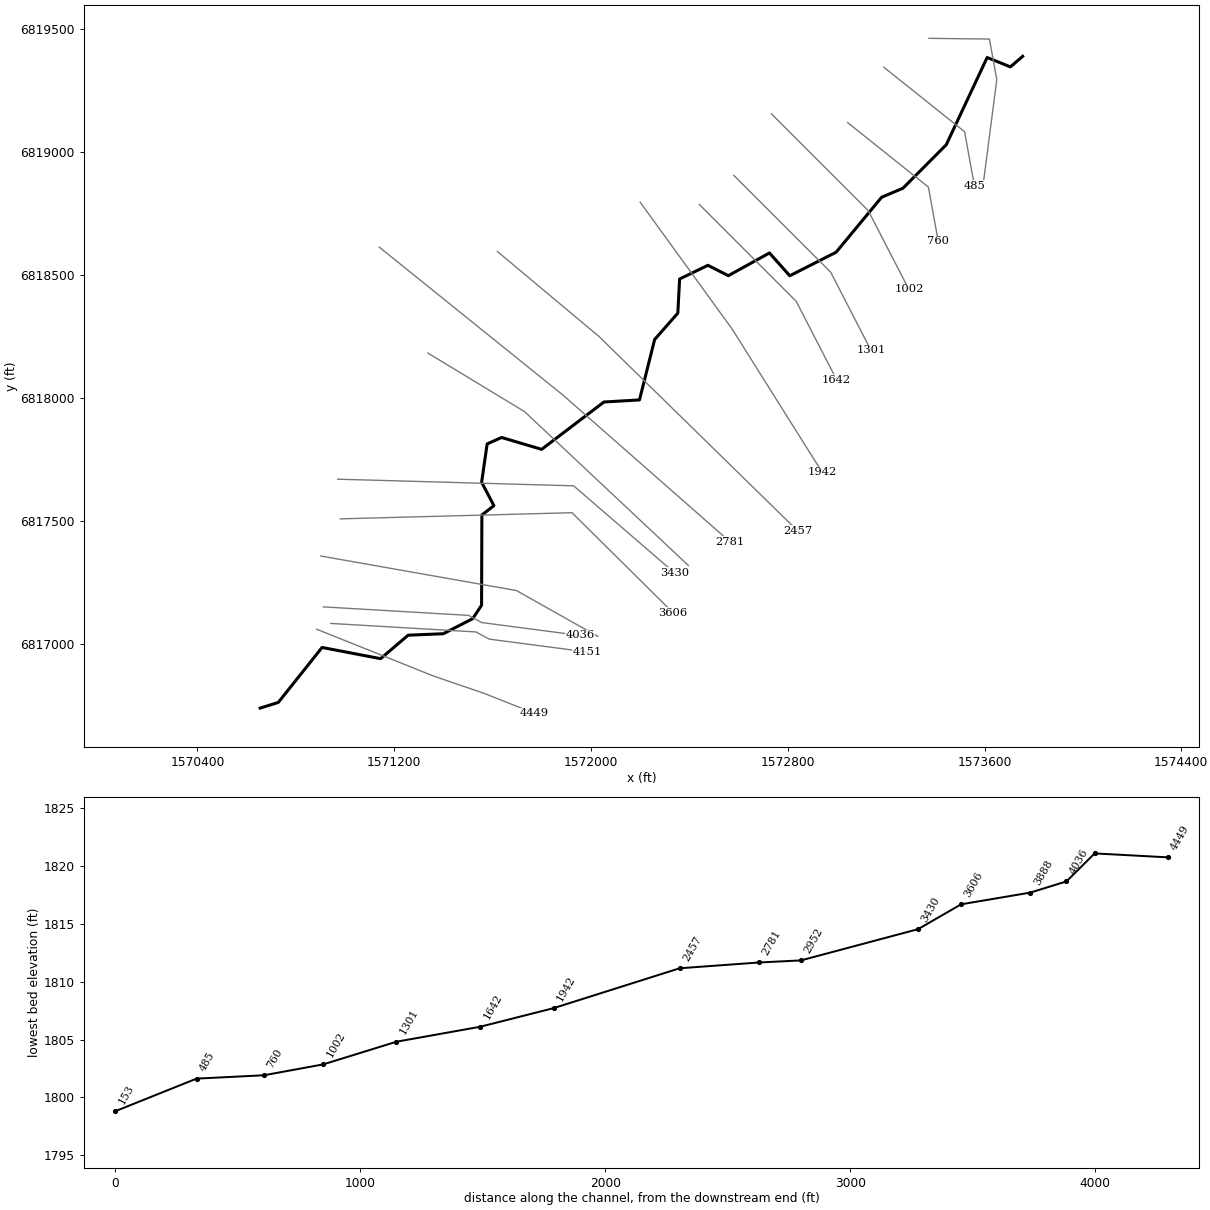
--- Unnamed Tributary to Cat Claw Cr.prj (project) ---

Proj Title=Unnamed Tributary to Cat Claw Cr Base Level Engineering
Current Plan=p01
Default Exp/Contr=0.3,0.1
English Units
Geom File=g01
Flow File=f01
Plan File=p01
Y Axis Title=Elevation
X Axis Title(PF)=Main Channel Distance
X Axis Title(XS)=Station
BEGIN DESCRIPTION:
Unnamed Tributary to Cat Claw Cr
END DESCRIPTION:
DSS Export Rating Curves= 0
DSS Export Rating Curve Sorted= 0
DSS Export Volume Flow Curves= 0
DXF OffsetX= 0
DXF OffsetY= 0
DXF ScaleX= 1
DXF ScaleY= 10

--- Unnamed Tributary to Cat Claw Cr.p01 (plan) ---

Plan Title=Multiple Run
Program Version=4.10
Short Identifier=Multiple
Geom File=g01
Flow File=f01
Subcritical Flow
K Sum by GR= 0
Std Step Tol= 0.01
Critical Tol= 0.01
Num of Std Step Trials= 20
Max Error Tol= 0.3
Flow Tol Ratio= 0.001
Split Flow NTrial= 30
Split Flow Tol= 0.02
Split Flow Ratio= 0.02
Log Output Level= 0
Friction Slope Method= 1
Unsteady Friction Slope Method= 2
Unsteady Bridges Friction Slope Method= 1
Parabolic Critical Depth
Global Vel Dist= 1 , 1 , 1
Global Log Level= 0
CheckData=True
Encroach Param=-1 ,0,0, 0
BEGIN DESCRIPTION:
Multiple Run
END DESCRIPTION:
Computation Interval=1HOUR
Output Interval=1HOUR
Run HTab= 0
Run UNet= 0
Run PostProcess= 0
Run WQNet= 0
UNET Theta= 1
UNET Theta Warmup= 1
UNET ZTol= 0.02
UNET ZSATol= 0.05
UNET MxIter= 20
UNET MaxInSteps= 0
UNET DtIC= 0
UNET DtMin= 0
UNET MaxCRTS= 20
UNET WFStab= 2
UNET SFStab= 1
UNET WFX= 1
UNET SFX= 1
UNET DSS MLevel= 4
UNET DZMax Abort= 100
UNET Convert EG Bridges= 0
UNET Use Existing IB Tables=-1
UNET Froude Reduction=False
UNET Froude Limit= 1
UNET Froude Power= 10
UNET Time Slicing=0,0, 5
UNET Junction Losses=0
Instantaneous Interval=1HOUR
Write IC File= 0
Write IC File at Sim End=0
Echo Input=False
Echo Parameters=False
Echo Output=False
Write Detailed= 0
WQ AD Non Conservative
WQ ULTIMATE=-1
WQ Max Comp Step=1HOUR
WQ Output Interval=15MIN
WQ Output Selected Increments= 0
WQ Output face flow=0
WQ Output face velocity=0
WQ Output face area=0
WQ Output face dispersion=0
WQ Output cell volume=0
WQ Output cell surface area=0
WQ Output cell continuity=0
WQ Output cumulative cell continuity=0
WQ Output face conc=0
WQ Output face dconc_dx=0
WQ Output face courant=0
WQ Output face peclet=0
WQ Output face adv mass=0
WQ Output face disp mass=0
WQ Output cell mass=0
WQ Output cell source sink temp=0
WQ Output cell source sink nsm=0
WQ Output MaxMinRange=-1
WQ Daily Max Min Mean=-1
WQ Daily Range=0
WQ Daily Time=0
WQ Create Restart=0
WQ Fixed Restart=0
WQ System Summary=0
WQ Use Fixed Temperature=0
Sorting and Armoring Iterations= 10
XS Update Threshold= 0.02
Hydraulics Update Threshold= 0.02
Energy Slope Method= 1
Volume Change Method= 0
XS Weighting Method= 0
Number of US Weighted Cross Sections= 1
Number of DS Weighted Cross Sections= 1
Upstream XS Weight=0.25
Main XS Weight=0.5
Downstream XS Weight=0.25
Number of DS XS's Weighted with US Boundary= 1
Upstream Boundary Weight= 1
Weight of XSs Associated with US Boundary= 0
Number of US XS's Weighted with DS Boundary= 1
Downstream Boundary Weight= 0.5
Weight of XSs Associated with DS Boundary= 0.5
Sediment Output Level= 4
Mass or Volume Output= 0
Output Increment Type= 1
Profile and TS Output Increment= 10
XS Output Flag= 0
XS Output Increment= 10
Disregard all LS=0
Disregard all Conn=0
Disregard all Breaches=0
Disregard all Pumps=0

--- Unnamed Tributary to Cat Claw Cr.f01 (steady flow) ---

Flow Title=Multiple
Program Version=4.10
Number of Profiles= 7
Profile Names=10-year,25-year,50-year,1pct_min,100-year,1pct_plu,500-year
River Rch & RM=Unnamed Tributar,Reach-1         ,4449
      49      60      67      38      76     152      98
River Rch & RM=Unnamed Tributar,Reach-1         ,4151
     207     281     341     206     410     819     602
River Rch & RM=Unnamed Tributar,Reach-1         ,1942
     233     319     388     235     469     935     694
Boundary for River Rch & Prof#=Unnamed Tributar,Reach-1         , 1
Up Type= 0
Dn Type= 3
Dn Slope=0.008
Boundary for River Rch & Prof#=Unnamed Tributar,Reach-1         , 2
Up Type= 0
Dn Type= 3
Dn Slope=0.008
Boundary for River Rch & Prof#=Unnamed Tributar,Reach-1         , 3
Up Type= 0
Dn Type= 3
Dn Slope=0.008
Boundary for River Rch & Prof#=Unnamed Tributar,Reach-1         , 4
Up Type= 0
Dn Type= 3
Dn Slope=0.008
Boundary for River Rch & Prof#=Unnamed Tributar,Reach-1         , 5
Up Type= 0
Dn Type= 3
Dn Slope=0.008
Boundary for River Rch & Prof#=Unnamed Tributar,Reach-1         , 6
Up Type= 0
Dn Type= 3
Dn Slope=0.008
Boundary for River Rch & Prof#=Unnamed Tributar,Reach-1         , 7
Up Type= 0
Dn Type= 3
Dn Slope=0.008
DSS Import GetInterval= 0
DSS Import GetPeak= 0
DSS Import FillOption= 0

--- Unnamed Tributary to Cat Claw Cr.g01 (geometry) ---

Geom Title=Existing Conditions

River Reach=Unnamed Tributar,Reach-1
Reach XY= 30
      1570655.00      6816738.00      1570728.52      6816761.02
      1570906.48      6816984.54      1571144.52      6816938.94
      1571256.47      6817034.44      1571399.48      6817040.36
      1571518.64      6817101.44      1571554.96      6817156.11
      1571556.24      6817523.19      1571605.24      6817560.89
      1571555.21      6817656.26      1571577.70      6817812.16
      1571636.47      6817838.28      1571799.11      6817789.97
      1572052.56      6817982.52      1572197.03      6817990.94
      1572258.62      6818236.50      1572352.92      6818343.87
      1572360.18      6818482.59      1572475.19      6818538.23
      1572558.31      6818496.07      1572725.46      6818588.46
      1572808.06      6818495.79      1572996.52      6818591.51
      1573181.53      6818814.98      1573268.21      6818851.63
      1573444.24      6819028.32      1573610.58      6819383.22
      1573705.08      6819344.97      1573755.00      6819388.00

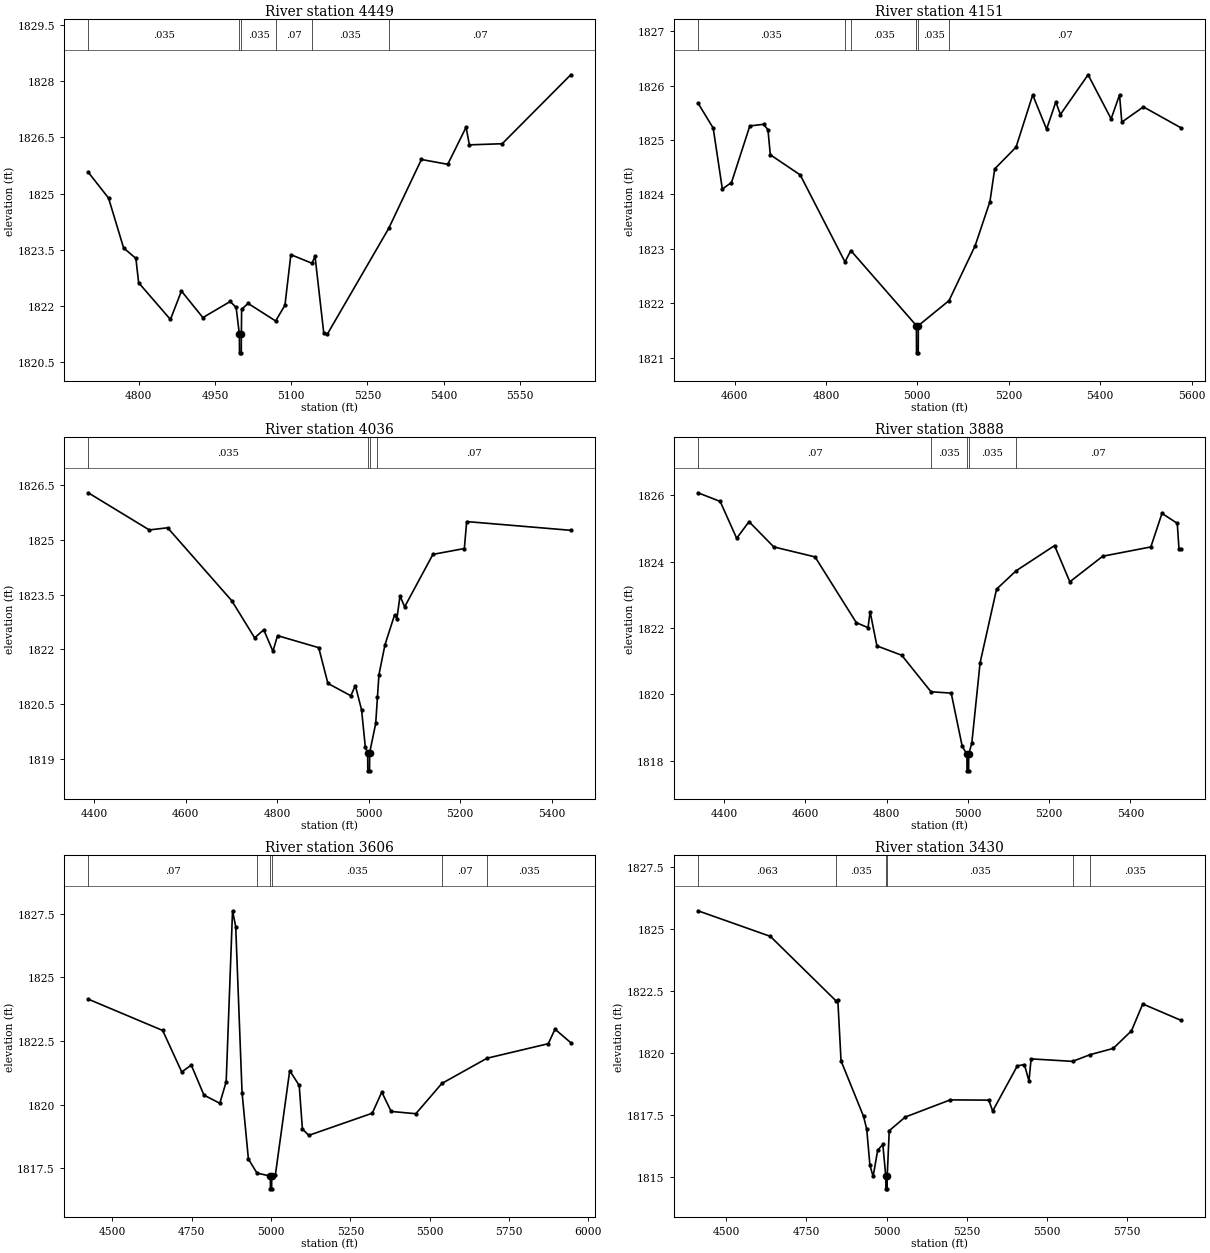
Type RM Length L Ch R = 1,4449,298,298,298
BEGIN DESCRIPTION:
Unnamed Tributary to Cat Claw Cr 10.0
END DESCRIPTION:
XS GIS Cut Line= 4
      1570884.77      6817058.60      1571362.38      6816867.29
      1571565.39      6816797.92      1571770.39      6816716.53
#Sta/Elev= 30
  4700.6 1825.57  4740.6 1824.88  4770.2 1823.55  4794.4 1823.27  4799.8 1822.62
  4862.4 1821.64  4884.0 1822.40  4926.2 1821.69  4980.1 1822.12  4991.7 1821.96
  4998.0 1821.25  4998.3 1820.75  5001.8 1820.75  5002.0 1821.25  5002.5 1821.91
  5015.1 1822.07  5069.4 1821.60  5087.7 1822.02  5099.4 1823.37  5141.0 1823.14
  5146.9 1823.33  5164.1 1821.28  5171.2 1821.25  5291.9 1824.07  5356.3 1825.91
  5408.1 1825.78  5444.2 1826.77  5450.7 1826.30  5515.3 1826.33  5650.2 1828.17
#Mann=6,-1,0
  4700.6   0.035       0  4998.0   0.035       0  5002.0   0.035       0
  5069.4    0.07       0  5141.0   0.035       0  5291.9    0.07       0
Bank Sta=4998,5002
Exp/Cntr=0.3,0.1

Type RM Length L Ch R = 1,4151,115,115,115
BEGIN DESCRIPTION:
Unnamed Tributary to Cat Claw Cr 9.0
END DESCRIPTION:
XS GIS Cut Line= 4
      1570941.79      6817082.23      1571532.32      6817047.63
      1571585.73      6817018.49      1571985.53      6816966.08
#Sta/Elev= 30
  4520.1 1825.68  4553.4 1825.22  4573.4 1824.10  4593.4 1824.22  4633.5 1825.26
  4663.6 1825.29  4673.2 1825.19  4678.3 1824.73  4743.7 1824.36  4841.7 1822.76
  4854.4 1822.97  4997.9 1821.59  4998.2 1821.09  5001.9 1821.09  5002.2 1821.59
  5069.3 1822.05  5126.5 1823.06  5158.8 1823.87  5169.2 1824.47  5215.9 1824.87
  5252.4 1825.83  5282.7 1825.20  5302.9 1825.70  5312.9 1825.47  5373.5 1826.20
  5423.9 1825.39  5442.3 1825.83  5447.3 1825.33  5494.5 1825.61  5575.7 1825.23
#Mann=6,-1,0
  4520.1   0.035       0  4841.7    0.07       0  4854.4   0.035       0
  4997.9   0.035       0  5002.2   0.035       0  5069.3    0.07       0
Bank Sta=4997.9,5002.2
Exp/Cntr=0.3,0.1

Type RM Length L Ch R = 1,4036,148,148,148
BEGIN DESCRIPTION:
Unnamed Tributary to Cat Claw Cr 8.0
END DESCRIPTION:
XS GIS Cut Line= 4
      1570911.63      6817149.49      1571502.18      6817114.89
      1571555.58      6817085.75      1571955.37      6817033.34
#Sta/Elev= 30
  4386.5 1826.30  4520.1 1825.28  4560.2 1825.34  4700.4 1823.34  4750.5 1822.32
  4770.5 1822.54  4790.6 1821.95  4800.6 1822.38  4890.7 1822.05  4910.8 1821.07
  4960.9 1820.73  4970.9 1821.01  4984.5 1820.34  4992.7 1819.32  4997.8 1819.17
  4998.1 1818.67  5001.9 1818.67  5002.2 1819.17  5015.4 1819.97  5019.2 1820.69
  5022.5 1821.31  5035.7 1822.13  5056.7 1822.95  5061.8 1822.85  5068.6 1823.47
  5078.7 1823.17  5140.6 1824.61  5209.3 1824.77  5214.4 1825.51  5442.1 1825.27
#Mann=4,-1,0
  4386.5   0.035       0  4997.8   0.035       0  5002.2   0.035       0
  5019.2    0.07       0
Bank Sta=4997.8,5002.2
Exp/Cntr=0.3,0.1

Type RM Length L Ch R = 1,3888,282,282,282
BEGIN DESCRIPTION:
Unnamed Tributary to Cat Claw Cr 7.0
END DESCRIPTION:
XS GIS Cut Line= 3
      1570901.27      6817356.37      1571696.95      6817215.88
      1572027.60      6817029.39
#Sta/Elev= 30
  4335.9 1826.07  4390.5 1825.81  4431.1 1824.70  4461.5 1825.20  4522.5 1824.44
  4624.0 1824.14  4725.6 1822.16  4754.4 1822.01  4759.5 1822.49  4776.3 1821.46
  4837.3 1821.18  4909.4 1820.08  4959.1 1820.04  4986.2 1818.44  4997.8 1818.20
  4998.1 1817.70  5001.9 1817.70  5002.2 1818.20  5009.9 1818.54  5030.2 1820.95
  5070.8 1823.17  5118.7 1823.72  5213.5 1824.48  5251.1 1823.39  5332.0 1824.16
  5450.5 1824.44  5477.9 1825.45  5515.5 1825.15  5519.8 1824.37  5523.5 1824.37
#Mann=5,-1,0
  4335.9    0.07       0  4909.4   0.035       0  4997.8   0.035       0
  5002.2   0.035       0  5118.7    0.07       0
Bank Sta=4997.8,5002.2
Exp/Cntr=0.3,0.1

Type RM Length L Ch R = 1,3606,176,176,176
BEGIN DESCRIPTION:
Unnamed Tributary to Cat Claw Cr 6.2
END DESCRIPTION:
XS GIS Cut Line= 3
      1570980.54      6817507.41      1571922.74      6817532.36
      1572333.21      6817126.04
#Sta/Elev= 30
  4424.1 1824.14  4658.6 1822.91  4718.7 1821.28  4748.7 1821.55  4788.7 1820.37
  4838.7 1820.05  4858.7 1820.90  4878.7 1827.61  4888.7 1826.99  4908.7 1820.47
  4928.7 1817.86  4955.7 1817.31  4997.8 1817.19  4998.1 1816.69  5001.9 1816.69
  5002.2 1817.19  5013.5 1817.22  5058.8 1821.33  5088.8 1820.75  5098.8 1819.04
  5118.8 1818.79  5318.9 1819.66  5348.9 1820.49  5378.4 1819.73  5456.1 1819.64
  5538.3 1820.83  5680.6 1821.82  5873.4 1822.39  5894.6 1822.96  5944.2 1822.43
#Mann=6,-1,0
  4424.1    0.07       0  4955.7   0.035       0  4997.8   0.035       0
  5002.2   0.035       0  5538.3    0.07       0  5680.6   0.035       0
Bank Sta=4997.8,5002.2
Exp/Cntr=0.3,0.1

Type RM Length L Ch R = 1,3430,478,478,478
BEGIN DESCRIPTION:
Unnamed Tributary to Cat Claw Cr 6.0
END DESCRIPTION:
XS GIS Cut Line= 3
      1570969.67      6817668.68      1571929.24      6817641.73
      1572340.20      6817287.20
#Sta/Elev= 30
  4412.9 1825.73  4638.3 1824.70  4843.1 1822.10  4848.4 1822.13  4858.4 1819.69
  4928.4 1817.46  4938.4 1816.94  4948.4 1815.48  4958.4 1815.04  4972.4 1816.09
  4988.5 1816.33  4997.8 1815.04  4998.1 1814.54  5001.9 1814.54  5002.2 1815.04
  5008.5 1816.88  5058.5 1817.43  5198.5 1818.12  5318.6 1818.11  5330.6 1817.67
  5407.5 1819.49  5429.4 1819.54  5443.7 1818.88  5450.3 1819.77  5579.5 1819.67
  5634.2 1819.94  5705.9 1820.19  5762.9 1820.90  5798.0 1821.98  5915.6 1821.33
#Mann=6,-1,0
  4412.9   0.063       0  4843.1   0.035       0  4997.8   0.035       0
  5002.2   0.035       0  5579.5    0.07       0  5634.2   0.035       0
Bank Sta=4997.8,5002.2
Exp/Cntr=0.3,0.1

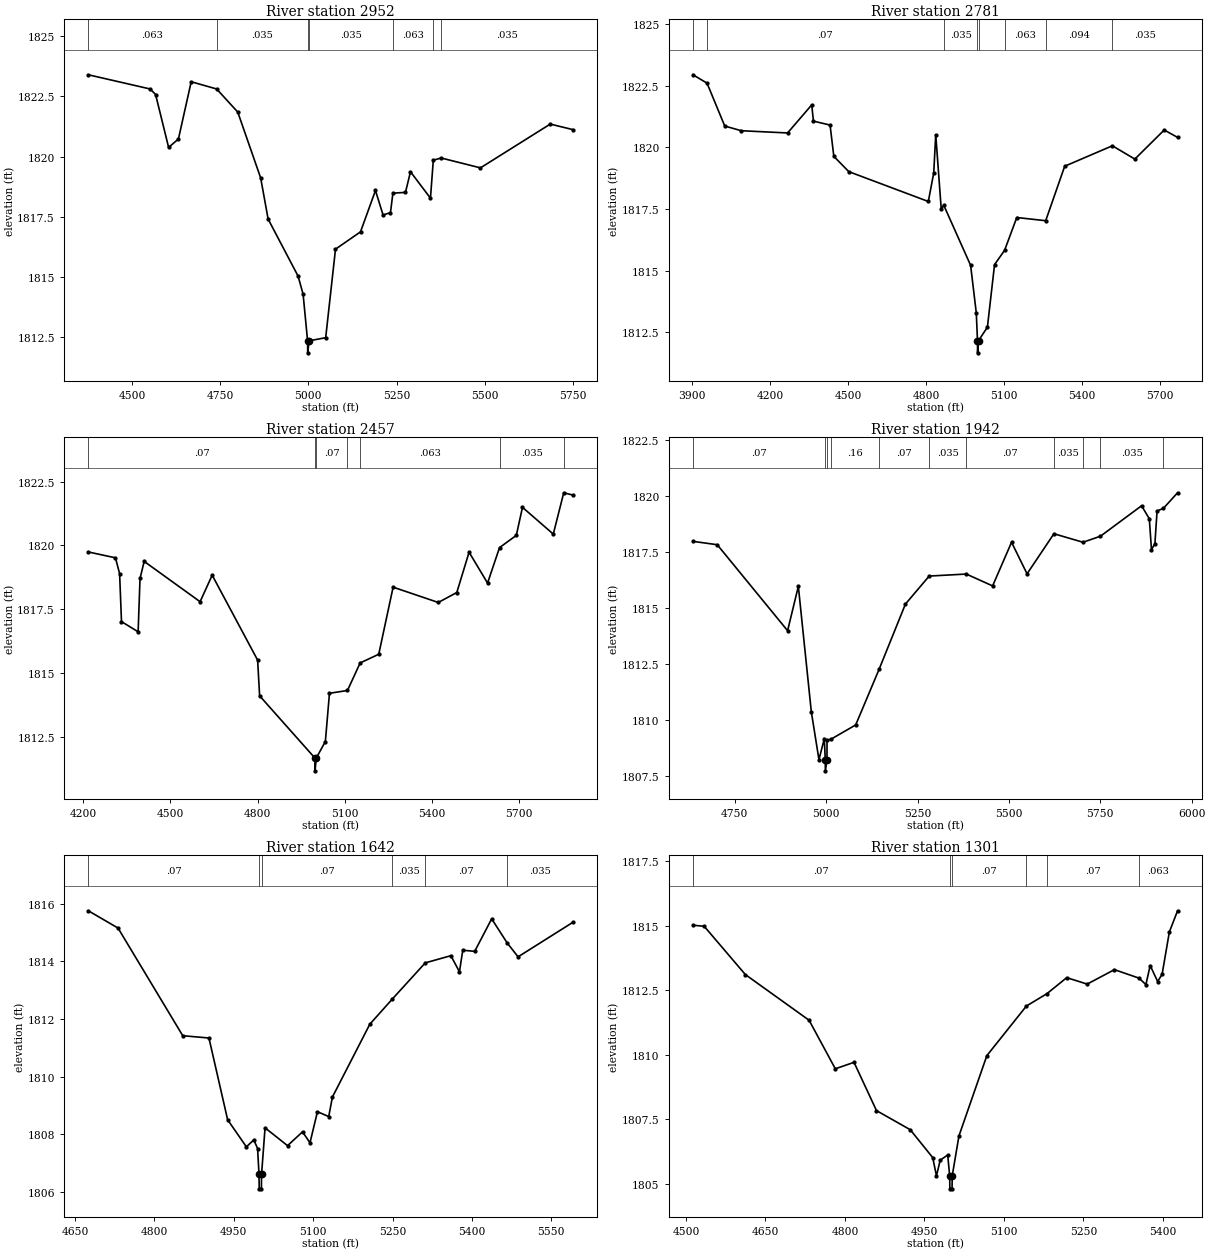
Type RM Length L Ch R = 1,2952,171,171,171
BEGIN DESCRIPTION:
Unnamed Tributary to Cat Claw Cr 5.0
END DESCRIPTION:
XS GIS Cut Line= 3
      1571336.61      6818181.57      1571729.45      6817943.61
      1572395.64      6817317.97
#Sta/Elev= 30
  4376.5 1823.40  4551.6 1822.81  4567.1 1822.58  4604.0 1820.38  4631.8 1820.73
  4668.0 1823.11  4740.1 1822.81  4799.9 1821.85  4864.9 1819.11  4886.0 1817.40
  4970.9 1815.03  4985.1 1814.28  4997.8 1812.34  4998.1 1811.84  5002.2 1812.34
  5049.1 1812.47  5076.9 1816.15  5147.8 1816.87  5190.2 1818.59  5211.7 1817.57
  5232.7 1817.67  5239.6 1818.48  5275.2 1818.51  5289.4 1819.37  5346.0 1818.27
  5354.1 1819.85  5376.5 1819.94  5487.7 1819.53  5685.5 1821.35  5749.7 1821.12
#Mann=7,-1,0
  4376.5   0.063       0  4740.1   0.035       0  4997.8   0.035       0
  5002.2   0.035       0  5239.6   0.063       0  5354.1   0.094       0
  5376.5   0.035       0
Bank Sta=4997.8,5002.2
Exp/Cntr=0.3,0.1

Type RM Length L Ch R = 1,2781,324,324,324
BEGIN DESCRIPTION:
Unnamed Tributary to Cat Claw Cr 4.0
END DESCRIPTION:
XS GIS Cut Line= 3
      1571138.67      6818612.48      1571885.37      6818011.02
      1572563.88      6817415.04
#Sta/Elev= 30
  3904.7 1822.94  3958.7 1822.60  4026.7 1820.86  4090.7 1820.67  4268.2 1820.58
  4361.0 1821.72  4367.4 1821.06  4431.4 1820.90  4445.8 1819.63  4503.4 1819.01
  4808.9 1817.80  4829.7 1818.96  4837.4 1820.51  4858.5 1817.49  4868.1 1817.65
  4971.4 1815.21  4993.2 1813.28  4997.8 1812.16  4998.1 1811.66  5002.2 1812.16
  5035.9 1812.70  5063.4 1815.24  5102.0 1815.82  5148.8 1817.15  5259.9 1817.02
  5332.9 1819.23  5516.1 1820.06  5602.4 1819.52  5715.3 1820.70  5766.6 1820.40
#Mann=8,-1,0
  3904.7   0.094       0  3958.7    0.07       0  4868.1   0.035       0
  4997.8   0.035       0  5002.2   0.035       0  5102.0   0.063       0
  5259.9   0.094       0  5516.1   0.035       0
Bank Sta=4997.8,5002.2
Exp/Cntr=0.3,0.1

Type RM Length L Ch R = 1,2457,515,515,515
BEGIN DESCRIPTION:
Unnamed Tributary to Cat Claw Cr 3.0
END DESCRIPTION:
XS GIS Cut Line= 3
      1571619.72      6818594.03      1572032.68      6818248.67
      1572840.66      6817458.03
#Sta/Elev= 30
  4217.4 1819.74  4310.8 1819.51  4325.1 1818.89  4331.6 1817.01  4388.9 1816.61
  4395.4 1818.70  4409.7 1819.37  4602.3 1817.79  4643.9 1818.83  4800.4 1815.50
  4807.3 1814.10  4997.8 1811.66  4998.1 1811.16  5002.3 1811.66  5033.7 1812.31
  5047.8 1814.20  5109.8 1814.31  5153.5 1815.39  5217.5 1815.73  5267.0 1818.36
  5422.6 1817.76  5486.3 1818.15  5528.6 1819.73  5592.3 1818.52  5633.4 1819.91
  5691.3 1820.39  5712.5 1821.49  5818.6 1820.44  5854.6 1822.06  5886.2 1821.97
#Mann=7,-1,0
  4217.4    0.07       0  4997.8    0.07       0  5002.3    0.07       0
  5109.8   0.035       0  5153.5   0.063       0  5633.4   0.035       0
  5854.6   0.094       0
Bank Sta=4997.8,5002.3
Exp/Cntr=0.3,0.1

Type RM Length L Ch R = 1,1942,300,300,300
BEGIN DESCRIPTION:
Unnamed Tributary to Cat Claw Cr 2.0
END DESCRIPTION:
XS GIS Cut Line= 3
      1572199.79      6818794.85      1572573.21      6818279.88
      1572940.21      6817696.06
#Sta/Elev= 30
  4635.8 1817.96  4702.1 1817.81  4894.6 1813.97  4924.0 1815.95  4959.5 1810.35
  4980.4 1808.21  4995.1 1809.15  4997.6 1808.21  4998.0 1807.71  5002.4 1808.21
  5002.5 1809.07  5014.0 1809.13  5080.9 1809.76  5144.8 1812.24  5217.0 1815.16
  5282.0 1816.41  5383.5 1816.50  5455.5 1815.97  5507.3 1817.92  5549.7 1816.51
  5623.2 1818.30  5702.8 1817.92  5750.5 1818.19  5863.0 1819.55  5884.2 1818.97
  5890.1 1817.59  5899.5 1817.86  5905.4 1819.32  5922.5 1819.43  5961.5 1820.13
#Mann=11,-1,0
  4635.8    0.07       0  4997.6    0.07       0  5002.4    0.07       0
  5014.0    0.16       0  5144.8    0.07       0  5282.0   0.035       0
  5383.5    0.07       0  5623.2   0.035       0  5702.8    0.07       0
  5750.5   0.035       0  5922.5   0.094       0
Bank Sta=4997.6,5002.4
Exp/Cntr=0.3,0.1

Type RM Length L Ch R = 1,1642,341,341,341
BEGIN DESCRIPTION:
Unnamed Tributary to Cat Claw Cr 1.6
END DESCRIPTION:
XS GIS Cut Line= 3
      1572440.34      6818785.61      1572833.98      6818392.11
      1572998.54      6818073.04
#Sta/Elev= 30
  4675.1 1815.76  4731.2 1815.16  4853.5 1811.42  4903.0 1811.34  4938.3 1808.50
  4973.7 1807.56  4987.8 1807.80  4994.9 1807.50  4997.6 1806.60  4998.0 1806.10
  5002.1 1806.10  5002.4 1806.60  5009.0 1808.22  5051.5 1807.60  5079.8 1808.08
  5093.9 1807.70  5108.0 1808.78  5129.3 1808.61  5136.3 1809.29  5207.0 1811.82
  5249.3 1812.69  5311.7 1813.95  5360.1 1814.20  5376.3 1813.64  5382.6 1814.39
  5405.1 1814.35  5437.2 1815.48  5466.6 1814.64  5487.1 1814.16  5590.7 1815.36
#Mann=6,-1,0
  4675.1    0.07       0  4997.6    0.07       0  5002.4    0.07       0
  5249.3   0.035       0  5311.7    0.07       0  5466.6   0.035       0
Bank Sta=4997.6,5002.4
Exp/Cntr=0.3,0.1

Type RM Length L Ch R = 1,1301,299,299,299
BEGIN DESCRIPTION:
Unnamed Tributary to Cat Claw Cr 1.3
END DESCRIPTION:
XS GIS Cut Line= 3
      1572580.83      6818903.62      1572974.47      6818510.13
      1573138.52      6818192.03
#Sta/Elev= 30
  4513.2 1815.02  4534.3 1814.98  4612.0 1813.11  4732.3 1811.34  4781.8 1809.46
  4817.1 1809.71  4859.5 1807.84  4923.2 1807.10  4965.6 1806.02  4972.7 1805.31
  4979.7 1805.92  4993.9 1806.12  4997.6 1805.31  4998.0 1804.81  5002.1 1804.81
  5002.4 1805.31  5015.1 1806.86  5067.8 1809.97  5142.4 1811.89  5181.2 1812.37
  5218.5 1812.99  5257.1 1812.74  5308.5 1813.30  5355.1 1812.97  5367.9 1812.72
  5376.0 1813.46  5390.1 1812.84  5398.5 1813.12  5412.2 1814.76  5427.7 1815.58
#Mann=6,-1,0
  4513.2    0.07       0  4997.6    0.07       0  5002.4    0.07       0
  5142.4    0.16       0  5181.2    0.07       0  5355.1   0.063       0
Bank Sta=4997.6,5002.4
Exp/Cntr=0.3,0.1

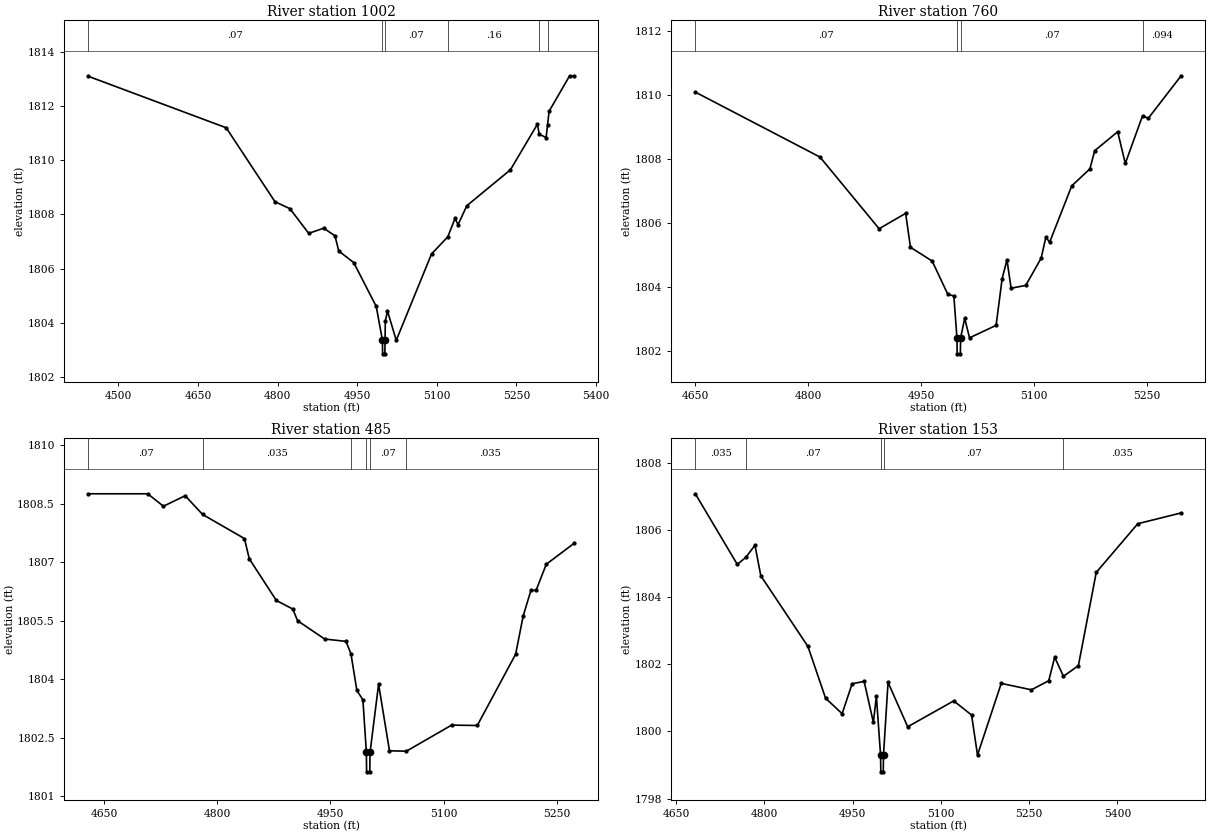
Type RM Length L Ch R = 1,1002,242,242,242
BEGIN DESCRIPTION:
Unnamed Tributary to Cat Claw Cr 1.0
END DESCRIPTION:
XS GIS Cut Line= 3
      1572733.61      6819153.82      1573127.27      6818760.32
      1573291.81      6818441.25
#Sta/Elev= 30
  4443.4 1813.10  4703.1 1811.20  4795.0 1808.47  4823.3 1808.21  4858.6 1807.30
  4886.9 1807.49  4908.1 1807.21  4915.2 1806.65  4943.5 1806.22  4985.9 1804.60
  4997.6 1803.35  4997.9 1802.85  5002.1 1802.85  5002.5 1803.35  5003.0 1804.06
  5007.1 1804.43  5023.6 1803.35  5090.1 1806.54  5120.7 1807.17  5134.4 1807.85
  5140.1 1807.62  5156.6 1808.32  5238.9 1809.65  5289.6 1811.33  5293.1 1810.96
  5306.1 1810.84  5308.7 1811.29  5311.7 1811.81  5350.4 1813.12  5359.0 1813.10
#Mann=6,-1,0
  4443.4    0.07       0  4997.6    0.07       0  5002.5    0.07       0
  5120.7    0.16       0  5293.1   0.094       0  5308.7   0.063       0
Bank Sta=4997.6,5002.5
Exp/Cntr=0.3,0.1

Type RM Length L Ch R = 1,760,275,275,275
BEGIN DESCRIPTION:
Unnamed Tributary to Cat Claw Cr 0.7
END DESCRIPTION:
XS GIS Cut Line= 3
      1573043.40      6819118.50      1573371.74      6818856.17
      1573411.83      6818635.14
#Sta/Elev= 30
  4650.3 1810.09  4815.8 1808.06  4894.3 1805.82  4929.5 1806.30  4935.9 1805.24
  4964.7 1804.81  4985.5 1803.77  4993.5 1803.72  4997.6 1802.41  4997.9 1801.91
  5002.1 1801.91  5002.5 1802.41  5007.9 1803.02  5014.3 1802.41  5049.6 1802.80
  5057.6 1804.26  5064.0 1804.85  5069.5 1803.96  5089.0 1804.05  5109.4 1804.90
  5115.6 1805.55  5120.7 1805.40  5150.0 1807.16  5174.1 1807.69  5180.5 1808.26
  5211.0 1808.85  5221.1 1807.86  5244.0 1809.35  5251.6 1809.27  5295.2 1810.60
#Mann=4,-1,0
  4650.3    0.07       0  4997.6    0.07       0  5002.5    0.07       0
  5244.0   0.094       0
Bank Sta=4997.6,5002.5
Exp/Cntr=0.3,0.1

Type RM Length L Ch R = 1,485,332,332,332
BEGIN DESCRIPTION:
Unnamed Tributary to Cat Claw Cr 0.4
END DESCRIPTION:
XS GIS Cut Line= 3
      1573190.50      6819343.58      1573518.88      6819081.22
      1573558.71      6818861.62
#Sta/Elev= 30
  4629.4 1808.76  4708.0 1808.76  4728.8 1808.44  4757.6 1808.71  4780.6 1808.23
  4836.1 1807.61  4842.5 1807.09  4878.4 1806.02  4900.1 1805.80  4906.5 1805.50
  4942.4 1805.03  4970.6 1804.97  4977.2 1804.65  4985.0 1803.71  4993.0 1803.47
  4997.6 1802.12  4997.9 1801.62  5002.1 1801.62  5002.5 1802.12  5013.8 1803.87
  5028.2 1802.16  5050.6 1802.15  5110.5 1802.82  5144.5 1802.81  5195.3 1804.64
  5205.4 1805.63  5215.6 1806.28  5222.4 1806.28  5235.9 1806.95  5272.9 1807.49
#Mann=6,-1,0
  4629.4    0.07       0  4780.6   0.035       0  4977.2    0.07       0
  4997.6    0.07       0  5002.5    0.07       0  5050.6   0.035       0
Bank Sta=4997.6,5002.5
Exp/Cntr=0.3,0.1

Type RM Length L Ch R = 1,153,0,0,0
BEGIN DESCRIPTION:
Unnamed Tributary to Cat Claw Cr 0.2
END DESCRIPTION:
XS GIS Cut Line= 4
      1573373.72      6819461.07      1573619.73      6819458.08
      1573649.82      6819293.87      1573596.71      6818884.97
#Sta/Elev= 30
  4682.8 1807.07  4754.1 1804.97  4768.7 1805.18  4784.1 1805.54  4794.1 1804.63
  4874.1 1802.53  4904.1 1800.99  4932.2 1800.53  4949.2 1801.42  4969.6 1801.49
  4985.3 1800.27  4990.4 1801.05  4997.5 1799.30  4997.9 1798.80  5002.1 1798.80
  5002.5 1799.30  5010.2 1801.46  5043.6 1800.14  5121.8 1800.91  5152.1 1800.49
  5162.2 1799.30  5202.5 1801.43  5253.8 1801.24  5283.2 1801.51  5293.3 1802.21
  5308.2 1801.64  5333.6 1801.96  5363.9 1804.73  5434.5 1806.18  5508.1 1806.50
#Mann=5,-1,0
  4682.8   0.035       0  4768.7    0.07       0  4997.5    0.07       0
  5002.5    0.07       0  5308.2   0.035       0
Bank Sta=4997.5,5002.5
Exp/Cntr=0.3,0.1

Chan Stop Cuts=-1