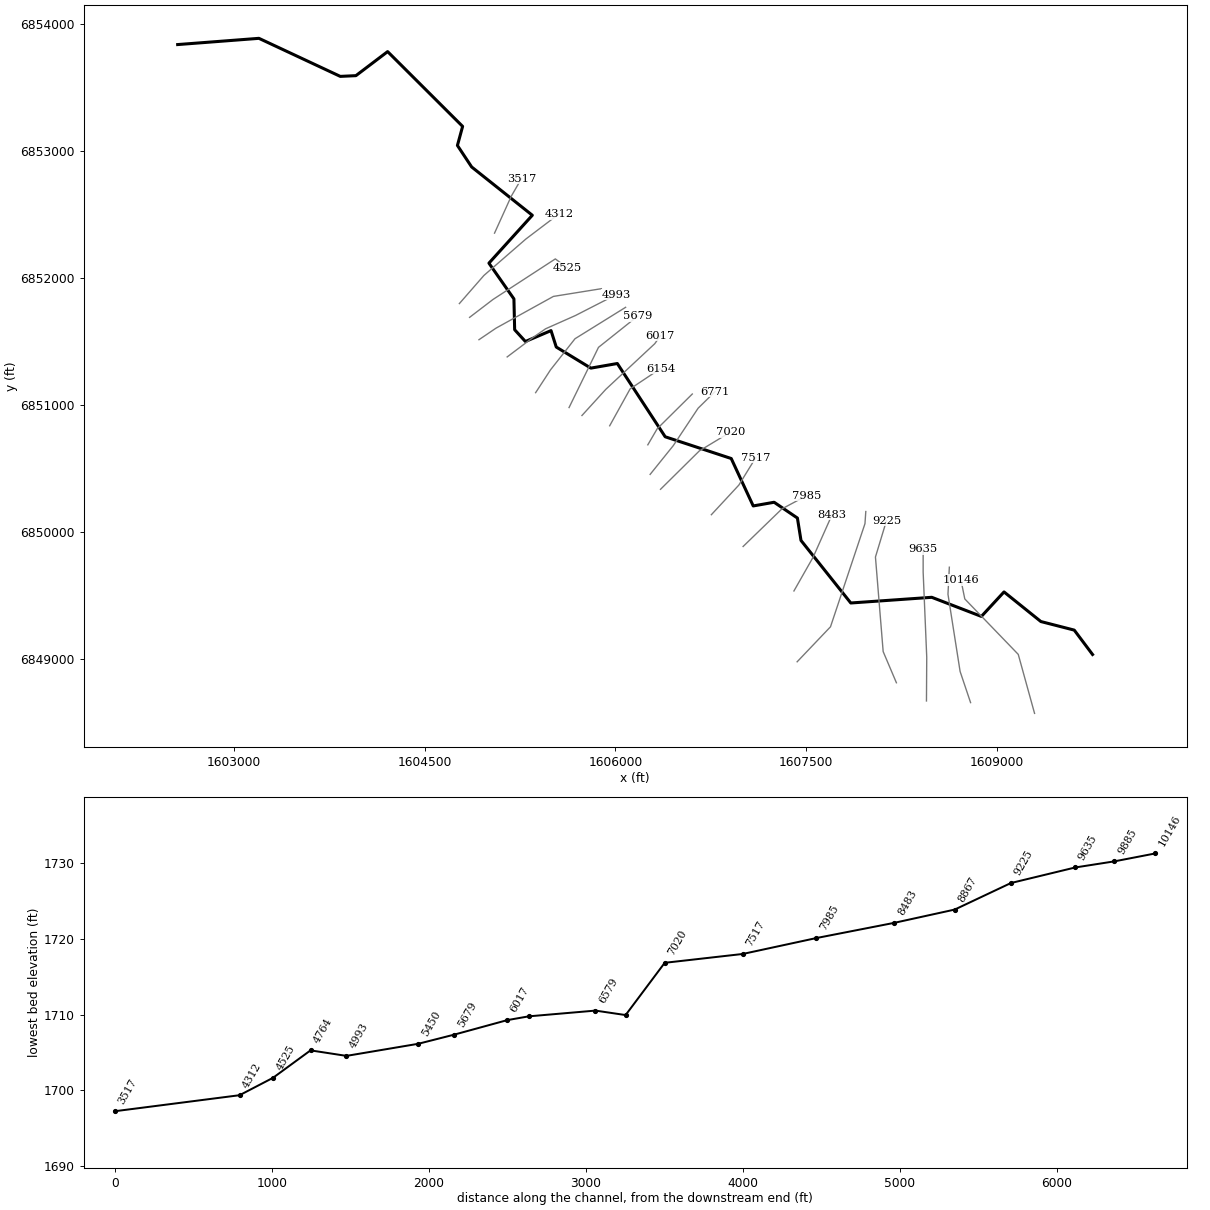
--- Unnamed Tributary to Rainy Cr.prj (project) ---

Proj Title=Unnamed Tributary to Rainy Cr Base Level Engineering
Current Plan=p01
Default Exp/Contr=0.3,0.1
English Units
Geom File=g01
Flow File=f01
Plan File=p01
BEGIN DESCRIPTION:
Unnamed Tributary to Rainy Cr
END DESCRIPTION:

--- Unnamed Tributary to Rainy Cr.p01 (plan) ---

Plan Title=Multiple Run
Short Identifier=Multiple
Geom File=g01
Flow File=f01
Subcritical Flow
K Sum by GR= 0
Std Step Tol= 0.01
Critical Tol= 0.01
Num of Std Step Trials= 20
Max Error Tol= 0.3
Flow Tol Ratio= 0.001
Split Flow NTrial= 30
Split Flow Tol= 0.02
Split Flow Ratio= 0.02
Log Output Level= 0
Friction Slope Method= 1
Unsteady Friction Slope Method= 2
Unsteady Bridges Friction Slope Method= 1
Parabolic Critical Depth
Global Vel Dist=  1 , 1 , 1
Global Log Level= 0
CheckData=True
Encroach Param= -1, 0, 0, 0
BEGIN DESCRIPTION:
Multiple Run
END DESCRIPTION:

--- Unnamed Tributary to Rainy Cr.f01 (steady flow) ---

Flow Title=Multiple
Number of Profiles=7
Profile Names=10-year,25-year,50-year,1pct_min,100-year,1pct_plu,500-year
River Rch & RM= Unnamed Tributar,Reach-1,10146
     171     230     277     207     332     457     483
Boundary for River Rch & Prof#=Unnamed Tributar,Reach-1,1
Up Type=0
Dn Type=3
Dn Slope=0.001
Boundary for River Rch & Prof#=Unnamed Tributar,Reach-1,2
Up Type=0
Dn Type=3
Dn Slope=0.001
Boundary for River Rch & Prof#=Unnamed Tributar,Reach-1,3
Up Type=0
Dn Type=3
Dn Slope=0.001
Boundary for River Rch & Prof#=Unnamed Tributar,Reach-1,4
Up Type=0
Dn Type=3
Dn Slope=0.001
Boundary for River Rch & Prof#=Unnamed Tributar,Reach-1,5
Up Type=0
Dn Type=3
Dn Slope=0.001
Boundary for River Rch & Prof#=Unnamed Tributar,Reach-1,6
Up Type=0
Dn Type=3
Dn Slope=0.001
Boundary for River Rch & Prof#=Unnamed Tributar,Reach-1,7
Up Type=0
Dn Type=3
Dn Slope=0.001

--- Unnamed Tributary to Rainy Cr.g01 (geometry) ---

Geom Title=Existing Conditions

River Reach=Unnamed Tributar,Reach-1
Reach XY= 30
      1609755.00      6849038.00      1609611.06      6849229.86
      1609348.33      6849297.30      1609058.33      6849530.40
      1608880.20      6849337.64      1608489.66      6849488.04
      1607852.34      6849443.33      1607460.48      6849935.55
      1607432.29      6850111.90      1607249.10      6850236.02
      1607084.58      6850207.13      1606911.50      6850580.28
      1606391.73      6850751.42      1606015.00      6851327.94
      1605806.58      6851291.67      1605534.44      6851457.60
      1605493.26      6851586.99      1605291.76      6851501.10
      1605207.05      6851593.84      1605201.25      6851836.45
      1605004.53      6852117.84      1605346.05      6852494.69
      1604868.63      6852874.79      1604756.63      6853044.04
      1604797.52      6853194.06      1604207.43      6853782.60
      1603957.70      6853593.35      1603834.86      6853587.60
      1603194.52      6853887.06      1602555.00      6853838.00

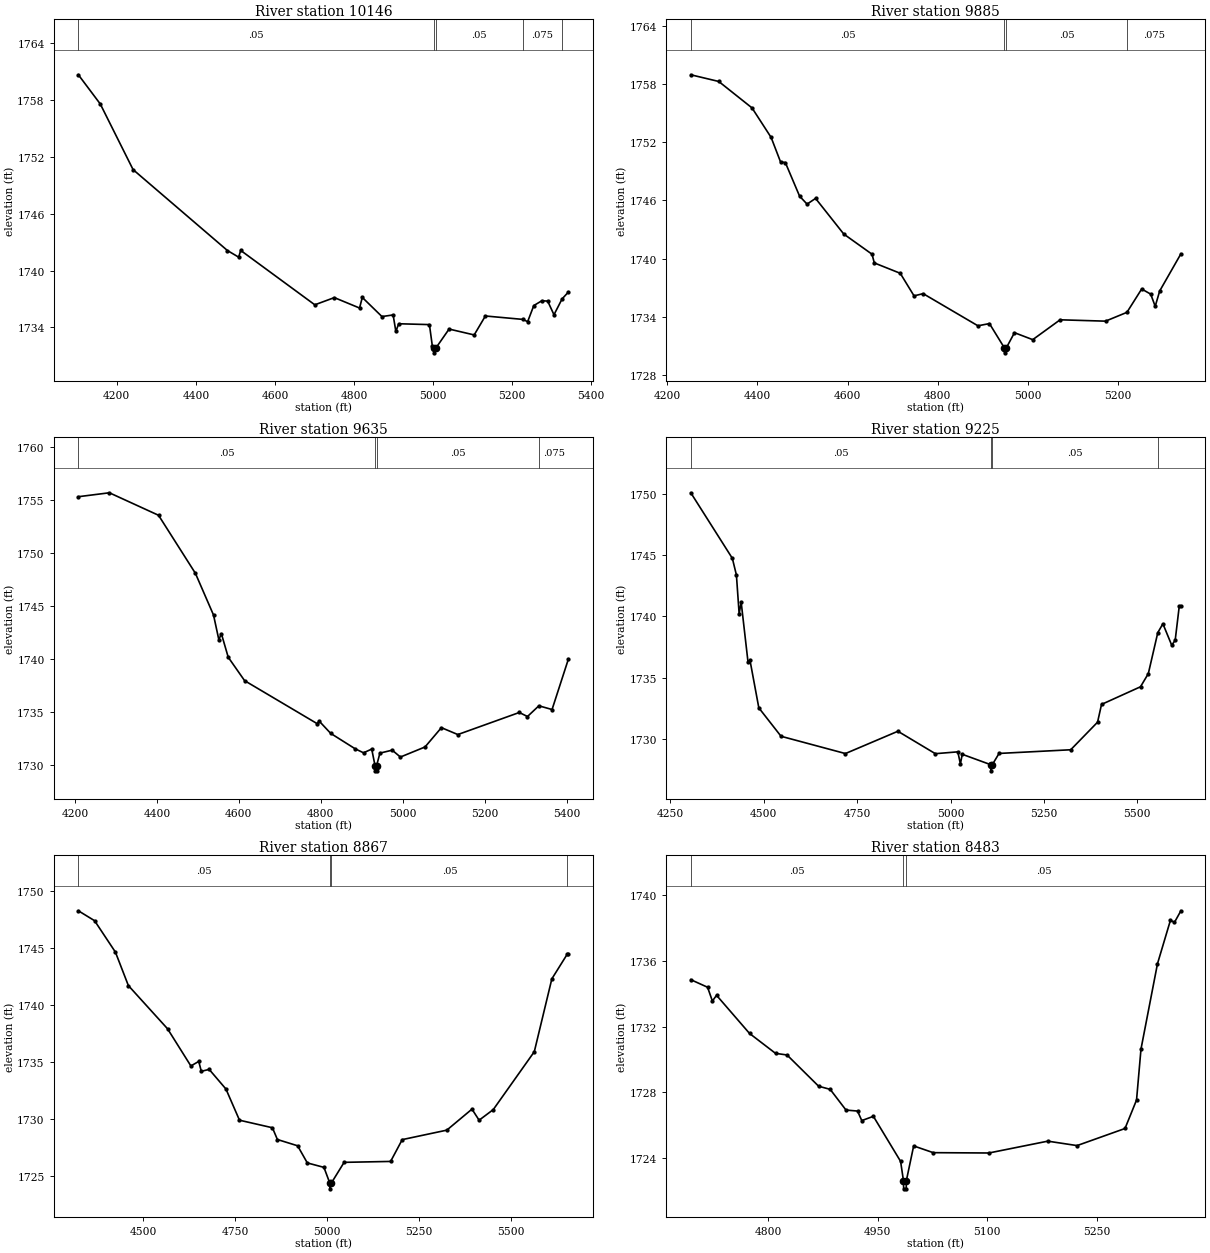
Type RM Length L Ch R = 1,10146,261,261,261
BEGIN DESCRIPTION:
Unnamed Tributary to Rainy Cr 11294.147
END DESCRIPTION:
XS GIS Cut Line= 4
      1609298.63      6848574.59      1609170.35      6849038.81
      1608749.58      6849475.23      1608719.40      6849623.95
#Sta/Elev= 30
  4102.9 1760.67  4158.3 1757.59  4241.3 1750.66  4479.9 1742.12  4508.3 1741.42
  4513.5 1742.13  4700.9 1736.39  4750.3 1737.15  4814.1 1736.05  4821.0 1737.17
  4870.7 1735.15  4899.0 1735.32  4905.9 1733.58  4913.1 1734.39  4990.8 1734.30
  4998.0 1732.09  5003.0 1731.82  5003.2 1731.32  5007.0 1731.82  5040.5 1733.83
  5104.0 1733.21  5132.3 1735.21  5227.0 1734.85  5239.2 1734.61  5254.8 1736.31
  5275.2 1736.82  5289.9 1736.78  5305.8 1735.34  5326.3 1737.01  5342.5 1737.75
#Mann=5,-1,0
  4102.9    0.05       0  5003.0    0.03       0  5007.0    0.05       0
  5227.0   0.075       0  5326.3    0.05       0
Bank Sta=5003,5007
Exp/Cntr=0.3,0.1

Type RM Length L Ch R = 1,9885,250,250,250
BEGIN DESCRIPTION:
Mapping XS 98da8188
END DESCRIPTION:
XS GIS Cut Line= 4
      1608795.15      6848659.26      1608712.69      6848904.49
      1608617.20      6849512.12      1608627.95      6849724.94
#Sta/Elev= 30
  4252.1 1758.97  4314.1 1758.28  4387.9 1755.55  4430.3 1752.50  4451.2 1749.97
  4461.8 1749.91  4493.4 1746.44  4510.0 1745.62  4528.8 1746.21  4591.4 1742.53
  4654.0 1740.45  4659.1 1739.55  4716.6 1738.48  4747.2 1736.15  4767.4 1736.38
  4888.9 1733.06  4914.4 1733.29  4947.7 1730.77  4947.9 1730.27  4951.7 1730.77
  4969.9 1732.35  5010.4 1731.63  5071.1 1733.68  5171.8 1733.54  5219.3 1734.45
  5252.0 1736.86  5272.0 1736.33  5282.0 1735.07  5292.0 1736.66  5339.0 1740.49
#Mann=4,-1,0
  4252.1    0.05       0  4947.7    0.03       0  4951.7    0.05       0
  5219.3   0.075       0
Bank Sta=4947.7,4951.7
Exp/Cntr=0.3,0.1

Type RM Length L Ch R = 1,9635,410,410,410
BEGIN DESCRIPTION:
Mapping XS e5ba63aa
END DESCRIPTION:
XS GIS Cut Line= 4
      1608447.93      6848672.26      1608450.10      6849017.33
      1608421.89      6849685.74      1608421.89      6849868.06
#Sta/Elev= 30
  4208.4 1755.30  4284.1 1755.67  4404.1 1753.55  4494.1 1748.08  4538.4 1744.14
  4551.3 1741.82  4557.5 1742.39  4574.2 1740.17  4614.2 1737.96  4791.2 1733.91
  4796.2 1734.15  4824.4 1732.99  4884.4 1731.53  4904.5 1731.16  4924.5 1731.51
  4932.5 1729.96  4932.7 1729.46  4936.2 1729.46  4936.5 1729.96  4944.5 1731.13
  4974.5 1731.41  4994.5 1730.76  5054.6 1731.71  5094.6 1733.53  5134.7 1732.88
  5284.7 1734.96  5304.7 1734.58  5332.5 1735.59  5364.7 1735.24  5404.8 1740.02
#Mann=4,-1,0
  4208.4    0.05       0  4932.5    0.03       0  4936.5    0.05       0
  5332.5   0.075       0
Bank Sta=4932.5,4936.5
Exp/Cntr=0.3,0.1

Type RM Length L Ch R = 1,9225,358,358,358
BEGIN DESCRIPTION:
Mapping XS 30b450c2
END DESCRIPTION:
XS GIS Cut Line= 4
      1608211.37      6848815.55      1608107.22      6849060.74
      1608046.45      6849805.09      1608133.24      6850091.51
#Sta/Elev= 30
  4304.5 1750.09  4415.8 1744.74  4426.7 1743.38  4434.0 1740.21  4439.4 1741.17
  4457.7 1736.29  4463.1 1736.41  4486.7 1732.54  4546.2 1730.22  4718.6 1728.81
  4859.1 1730.63  4959.4 1728.80  5019.6 1728.95  5026.5 1727.97  5031.5 1728.75
  5107.9 1727.90  5108.2 1727.40  5111.9 1727.90  5130.0 1728.82  5321.9 1729.12
  5393.8 1731.37  5404.4 1732.82  5508.8 1734.26  5529.7 1735.33  5555.1 1738.68
  5568.8 1739.40  5592.4 1737.65  5601.7 1738.06  5612.6 1740.84  5617.0 1740.84
#Mann=4,-1,0
  4304.5    0.05       0  5107.9    0.05       0  5111.9    0.05       0
  5555.1   0.075       0
Bank Sta=5107.9,5111.9
Exp/Cntr=0.3,0.1

Type RM Length L Ch R = 1,8867,384,384,384
BEGIN DESCRIPTION:
Mapping XS b8c65690
END DESCRIPTION:
XS GIS Cut Line= 4
      1607430.16      6848980.46      1607692.72      6849256.05
      1607963.99      6850067.68      1607970.49      6850163.05
#Sta/Elev= 30
  4324.6 1748.24  4368.7 1747.37  4425.3 1744.62  4460.5 1741.69  4566.9 1737.91
  4630.4 1734.65  4651.8 1735.05  4658.7 1734.18  4680.1 1734.35  4725.7 1732.63
  4762.5 1729.90  4852.0 1729.24  4865.5 1728.21  4920.5 1727.66  4946.8 1726.16
  4992.0 1725.77  5008.0 1724.39  5008.2 1723.89  5012.0 1724.39  5046.8 1726.21
  5173.2 1726.29  5204.8 1728.20  5325.9 1729.03  5394.3 1730.87  5413.7 1729.90
  5452.2 1730.83  5563.7 1735.90  5611.4 1742.28  5653.8 1744.47  5656.6 1744.43
#Mann=4,-1,0
  4324.6    0.05       0  5008.0    0.03       0  5012.0    0.05       0
  5653.8   0.075       0
Bank Sta=5008,5012
Exp/Cntr=0.3,0.1

Type RM Length L Ch R = 1,8483,498,498,498
BEGIN DESCRIPTION:
Unnamed Tributary to Rainy Cr 8482.728
END DESCRIPTION:
XS GIS Cut Line= 3
      1607405.00      6849537.99      1607556.17      6849804.04
      1607704.99      6850137.98
#Sta/Elev= 30
  4694.0 1734.86  4717.0 1734.40  4723.6 1733.56  4729.3 1733.91  4774.5 1731.59
  4810.1 1730.38  4825.9 1730.28  4869.2 1728.38  4885.0 1728.19  4906.7 1726.93
  4922.5 1726.87  4928.3 1726.29  4944.2 1726.55  4981.5 1723.81  4985.4 1722.64
  4985.7 1722.14  4989.2 1722.14  4989.4 1722.64  4999.4 1724.75  5026.2 1724.34
  5102.5 1724.32  5183.2 1725.04  5223.3 1724.77  5289.0 1725.81  5304.8 1727.54
  5310.9 1730.64  5333.5 1735.83  5351.3 1738.48  5356.7 1738.34  5365.6 1739.05
#Mann=3,-1,0
  4694.0    0.05       0  4985.4    0.05       0  4989.4    0.05       0
Bank Sta=4985.4,4989.4
Exp/Cntr=0.3,0.1

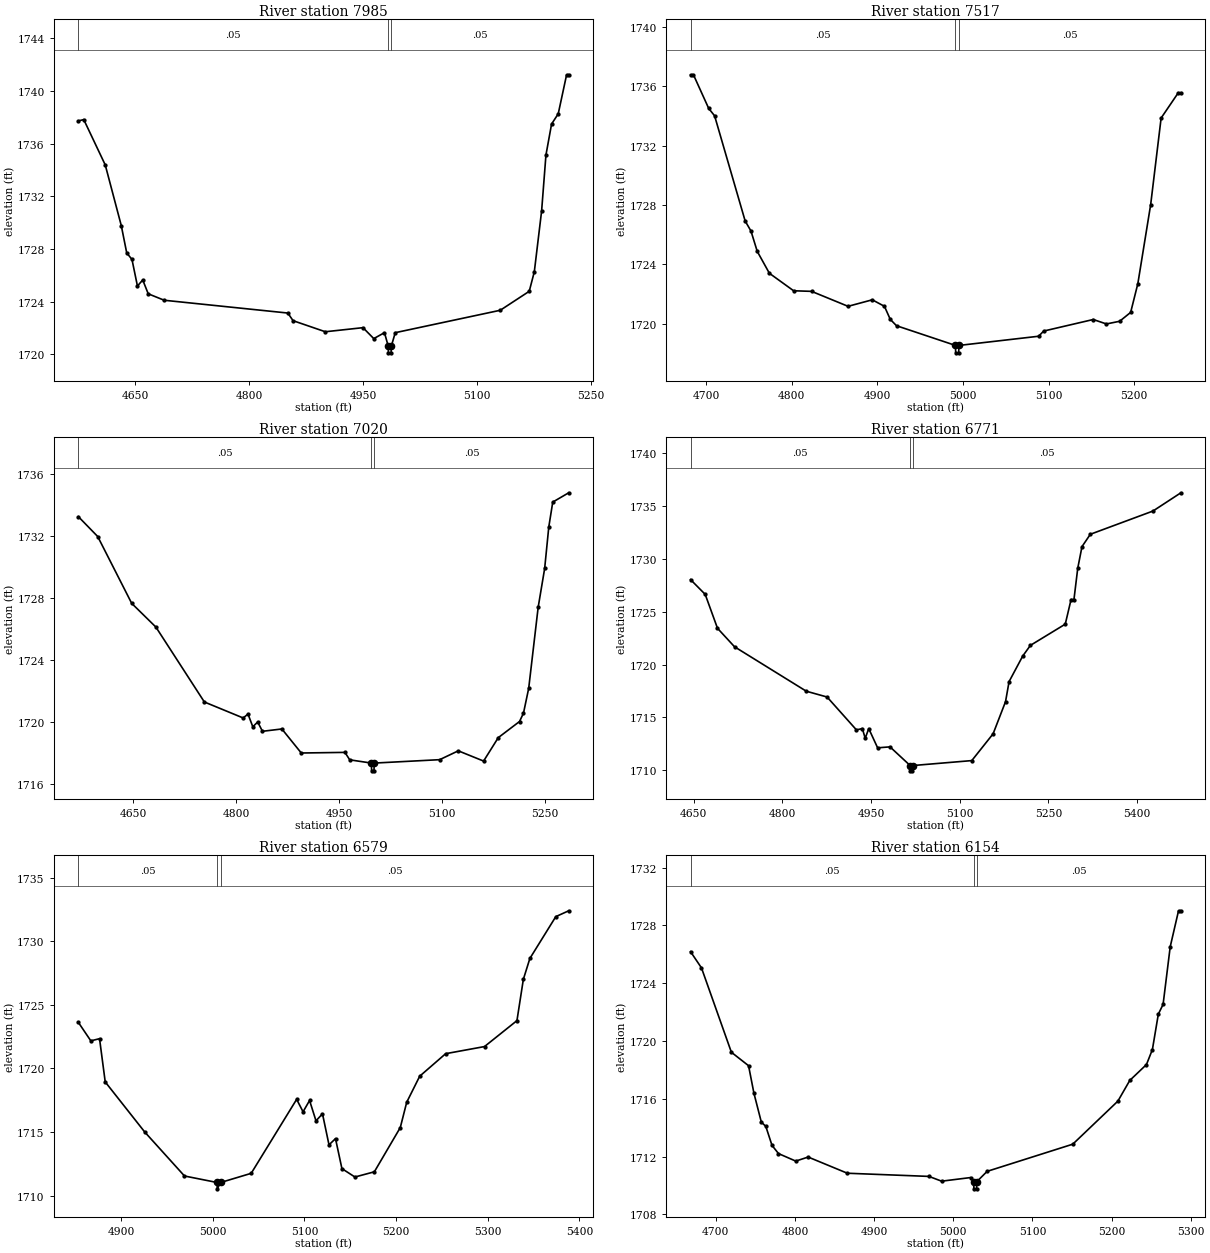
Type RM Length L Ch R = 1,7985,468,468,468
BEGIN DESCRIPTION:
Unnamed Tributary to Rainy Cr 7985.171
END DESCRIPTION:
XS GIS Cut Line= 3
      1607004.99      6849887.99      1607310.36      6850183.88
      1607504.96      6850287.98
#Sta/Elev= 30
  4574.8 1737.72  4581.9 1737.82  4610.2 1734.38  4631.3 1729.78  4638.5 1727.70
  4645.4 1727.21  4652.6 1725.19  4659.6 1725.65  4666.8 1724.60  4687.9 1724.11
  4850.7 1723.14  4857.6 1722.56  4900.1 1721.72  4949.7 1722.03  4963.9 1721.20
  4978.0 1721.65  4983.0 1720.62  4983.2 1720.12  4986.7 1720.12  4987.0 1720.62
  4992.2 1721.65  5130.5 1723.35  5168.7 1724.79  5175.4 1726.28  5185.0 1730.89
  5190.7 1735.13  5198.1 1737.48  5206.9 1738.26  5217.9 1741.22  5220.7 1741.22
#Mann=3,-1,0
  4574.8    0.05       0  4983.0    0.03       0  4987.0    0.05       0
Bank Sta=4983,4987
Exp/Cntr=0.3,0.1

Type RM Length L Ch R = 1,7517,497,497,497
BEGIN DESCRIPTION:
Unnamed Tributary to Rainy Cr 7517.053
END DESCRIPTION:
XS GIS Cut Line= 3
      1606755.01      6850138.01      1606971.46      6850371.25
      1607105.01      6850588.01
#Sta/Elev= 30
  4681.8 1736.79  4685.2 1736.79  4703.0 1734.52  4709.9 1734.02  4745.6 1726.92
  4752.4 1726.24  4759.7 1724.87  4773.9 1723.39  4802.2 1722.21  4823.2 1722.17
  4865.8 1721.16  4894.1 1721.60  4908.3 1721.16  4915.1 1720.28  4922.4 1719.85
  4991.3 1718.52  4991.5 1718.02  4995.0 1718.02  4995.3 1718.52  5088.4 1719.14
  5094.3 1719.49  5152.2 1720.27  5167.6 1719.97  5183.0 1720.15  5195.9 1720.75
  5204.3 1722.69  5219.3 1728.03  5231.5 1733.87  5251.6 1735.58  5254.6 1735.58
#Mann=3,-1,0
  4681.8    0.05       0  4991.3    0.05       0  4995.3    0.05       0
Bank Sta=4991.3,4995.3
Exp/Cntr=0.3,0.1

Type RM Length L Ch R = 1,7020,249,249,249
BEGIN DESCRIPTION:
Unnamed Tributary to Rainy Cr 7020.112
END DESCRIPTION:
XS GIS Cut Line= 3
      1606355.02      6850338.02      1606660.89      6850640.54
      1606905.01      6850788.00
#Sta/Elev= 30
  4569.8 1733.24  4598.0 1731.96  4647.6 1727.65  4682.9 1726.12  4753.6 1721.29
  4810.2 1720.26  4817.3 1720.51  4824.3 1719.69  4831.4 1720.00  4838.4 1719.40
  4866.7 1719.55  4895.0 1718.00  4958.7 1718.04  4965.7 1717.56  4997.4 1717.35
  4997.6 1716.85  5001.1 1716.85  5001.4 1717.35  5096.9 1717.57  5124.1 1718.14
  5161.0 1717.48  5182.4 1718.99  5213.4 1720.03  5219.2 1720.57  5226.8 1722.17
  5240.6 1727.39  5250.1 1729.90  5256.1 1732.57  5261.9 1734.18  5285.2 1734.78
#Mann=3,-1,0
  4569.8    0.05       0  4997.4    0.05       0  5001.4    0.05       0
Bank Sta=4997.4,5001.4
Exp/Cntr=0.3,0.1

Type RM Length L Ch R = 1,6771,192,192,192
BEGIN DESCRIPTION:
Mapping XS a73e20e0
END DESCRIPTION:
XS GIS Cut Line= 4
      1606273.21      6850455.29      1606455.48      6850681.83
      1606650.79      6850976.10      1606783.57      6851106.28
#Sta/Elev= 30
  4644.4 1728.05  4669.2 1726.65  4690.0 1723.44  4718.8 1721.69  4840.3 1717.48
  4875.5 1716.93  4925.1 1713.82  4935.2 1713.94  4940.0 1713.02  4946.0 1713.94
  4961.0 1712.12  4982.0 1712.21  5016.1 1710.44  5016.4 1709.94  5019.9 1709.94
  5020.1 1710.44  5120.4 1710.91  5156.5 1713.45  5177.5 1716.49  5183.5 1718.39
  5206.6 1720.81  5219.6 1721.82  5278.6 1723.83  5288.4 1726.16  5293.3 1726.16
  5299.7 1729.12  5306.9 1731.17  5321.0 1732.34  5427.0 1734.54  5474.3 1736.27
#Mann=3,-1,0
  4644.4    0.05       0  5016.1    0.05       0  5020.1    0.05       0
Bank Sta=5016.1,5020.1
Exp/Cntr=0.3,0.1

Type RM Length L Ch R = 1,6579,425,425,425
BEGIN DESCRIPTION:
Unnamed Tributary to Rainy Cr 6579.207
END DESCRIPTION:
XS GIS Cut Line= 3
      1606255.01      6850688.02      1606328.98      6850814.71
      1606604.98      6851087.98
#Sta/Elev= 30
  4853.3 1723.62  4866.9 1722.17  4876.4 1722.34  4882.6 1718.94  4925.6 1715.01
  4969.1 1711.54  5004.6 1711.03  5004.9 1710.53  5008.6 1711.03  5041.9 1711.75
  5091.5 1717.57  5098.5 1716.59  5105.6 1717.48  5112.6 1715.88  5119.7 1716.43
  5126.8 1713.99  5133.9 1714.48  5140.9 1712.12  5155.1 1711.46  5176.3 1711.87
  5204.6 1715.35  5211.6 1717.34  5225.8 1719.39  5254.1 1721.16  5296.5 1721.72
  5331.9 1723.76  5338.9 1727.01  5346.0 1728.65  5374.3 1731.94  5388.4 1732.40
#Mann=3,-1,0
  4853.3    0.05       0  5004.6    0.05       0  5008.6    0.05       0
Bank Sta=5004.6,5008.6
Exp/Cntr=0.3,0.1

Type RM Length L Ch R = 1,6154,137,137,137
BEGIN DESCRIPTION:
Unnamed Tributary to Rainy Cr 6154.041
END DESCRIPTION:
XS GIS Cut Line= 3
      1605954.98      6850837.96      1606115.76      6851128.32
      1606354.97      6851287.98
#Sta/Elev= 30
  4668.1 1726.18  4681.9 1725.06  4719.7 1719.22  4741.4 1718.29  4748.2 1716.38
  4757.5 1714.39  4763.2 1714.09  4771.0 1712.78  4779.2 1712.21  4801.0 1711.69
  4816.7 1711.97  4866.2 1710.85  4969.3 1710.63  4985.3 1710.30  5021.8 1710.55
  5025.8 1710.27  5026.0 1709.77  5029.5 1709.77  5029.8 1710.27  5042.8 1710.98
  5151.0 1712.86  5208.0 1715.84  5223.0 1717.27  5244.1 1718.37  5251.6 1719.41
  5259.1 1721.86  5265.1 1722.53  5274.1 1726.52  5284.6 1729.01  5287.6 1729.01
#Mann=3,-1,0
  4668.1    0.05       0  5025.8    0.05       0  5029.8    0.05       0
Bank Sta=5025.8,5029.8
Exp/Cntr=0.3,0.1

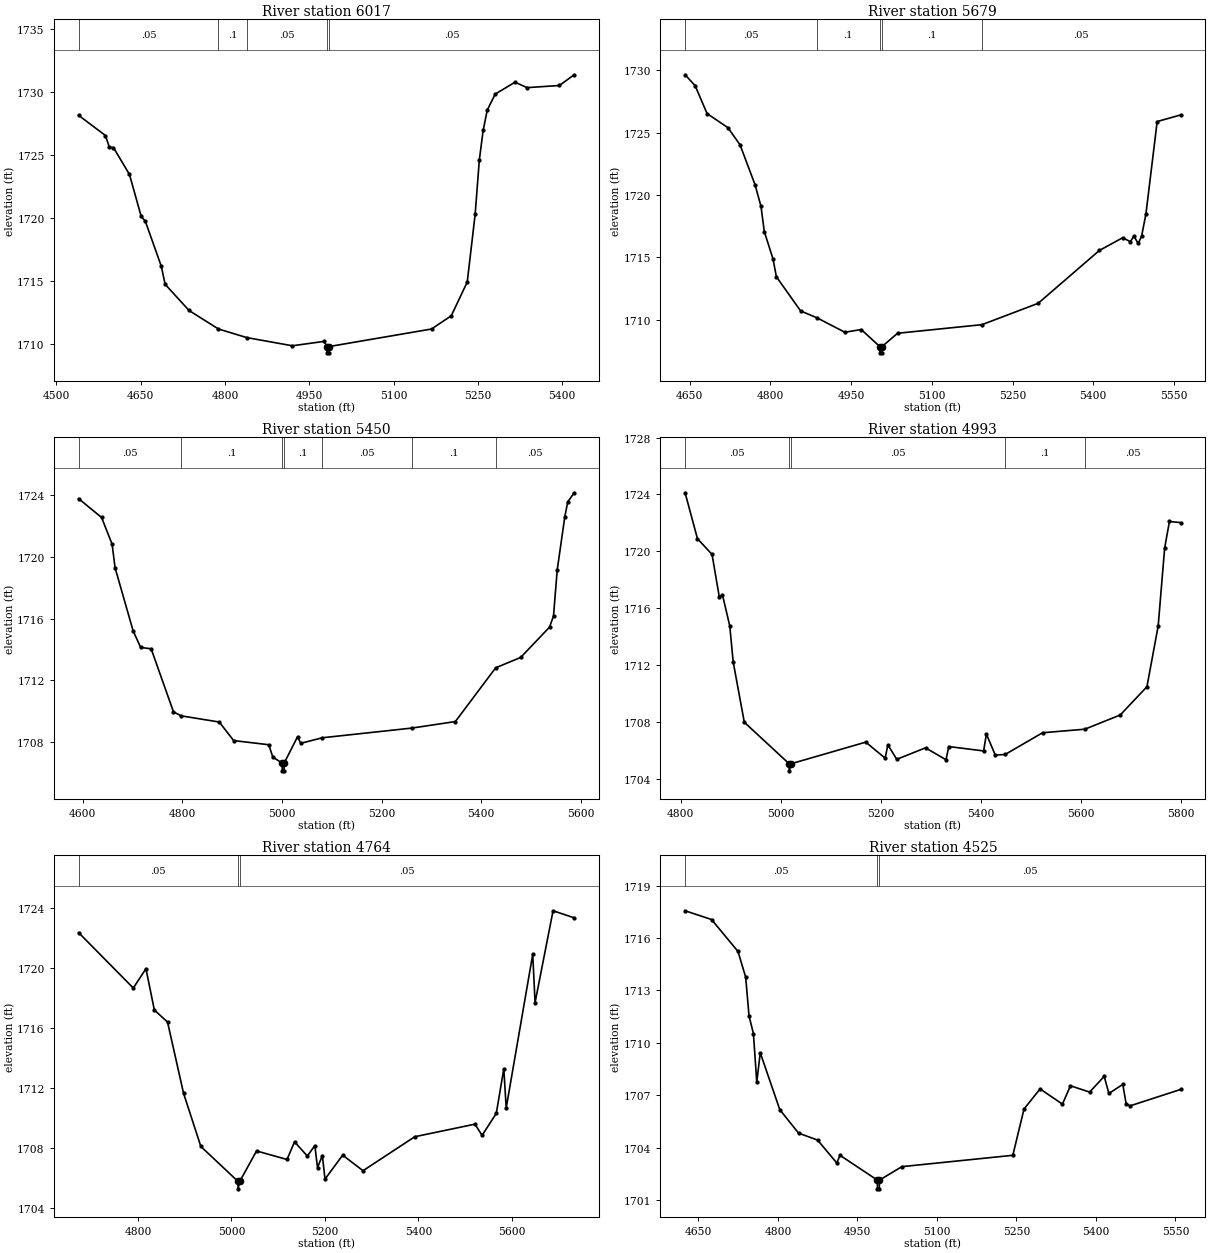
Type RM Length L Ch R = 1,6017,338,338,338
BEGIN DESCRIPTION:
Mapping XS c5f09c5b
END DESCRIPTION:
XS GIS Cut Line= 4
      1605736.73      6850918.81      1605924.23      6851124.54
      1606309.65      6851483.91      1606353.91      6851546.40
#Sta/Elev= 30
  4539.5 1728.11  4587.3 1726.51  4594.1 1725.58  4601.5 1725.55  4629.9 1723.43
  4650.8 1720.10  4658.3 1719.70  4686.6 1716.14  4693.4 1714.71  4736.0 1712.63
  4788.4 1711.16  4838.7 1710.48  4919.9 1709.83  4976.5 1710.18  4981.4 1709.77
  4981.6 1709.27  4985.1 1709.27  4985.4 1709.77  5167.5 1711.16  5202.7 1712.21
  5231.1 1714.89  5245.2 1720.27  5252.6 1724.57  5259.4 1726.91  5266.7 1728.53
  5280.9 1729.80  5316.1 1730.74  5337.6 1730.31  5395.0 1730.48  5421.4 1731.33
#Mann=5,-1,0
  4539.5    0.05       0  4788.4     0.1       0  4838.7    0.05       0
  4981.4    0.05       0  4985.4    0.05       0
Bank Sta=4981.4,4985.4
Exp/Cntr=0.3,0.1

Type RM Length L Ch R = 1,5679,229,229,229
BEGIN DESCRIPTION:
Mapping XS b418c684
END DESCRIPTION:
XS GIS Cut Line= 3
      1605635.17      6850981.32      1605866.94      6851455.27
      1606174.26      6851700.08
#Sta/Elev= 30
  4641.8 1729.65  4660.4 1728.78  4682.6 1726.54  4721.3 1725.41  4743.9 1724.03
  4771.9 1720.81  4782.8 1719.09  4788.9 1717.08  4805.1 1714.88  4811.4 1713.45
  4856.4 1710.71  4886.2 1710.17  4938.7 1709.00  4969.0 1709.22  5003.5 1707.85
  5003.7 1707.35  5007.2 1707.35  5007.5 1707.85  5036.5 1708.92  5193.3 1709.61
  5297.6 1711.32  5411.3 1715.56  5454.6 1716.58  5469.0 1716.26  5475.4 1716.72
  5483.4 1716.12  5489.8 1716.70  5497.9 1718.51  5518.7 1725.90  5562.3 1726.43
#Mann=5,-1,0
  4641.8    0.05       0  4886.2     0.1       0  5003.5    0.07       0
  5007.5     0.1       0  5193.3    0.05       0
Bank Sta=5003.5,5007.5
Exp/Cntr=0.3,0.1

Type RM Length L Ch R = 1,5450,457,457,457
BEGIN DESCRIPTION:
Mapping XS 23072318
END DESCRIPTION:
XS GIS Cut Line= 4
      1605372.15      6851098.49      1605489.34      6851278.18
      1605682.04      6851522.97      1606080.26      6851770.23
#Sta/Elev= 30
  4591.8 1723.76  4637.9 1722.54  4659.0 1720.81  4665.0 1719.28  4701.2 1715.20
  4716.3 1714.13  4737.4 1714.04  4782.2 1709.96  4797.7 1709.70  4874.1 1709.30
  4903.0 1708.10  4973.5 1707.83  4981.6 1707.03  5000.4 1706.64  5000.6 1706.14
  5004.1 1706.14  5004.4 1706.64  5031.3 1708.35  5037.6 1707.92  5080.8 1708.28
  5261.2 1708.91  5348.1 1709.33  5429.0 1712.81  5479.2 1713.48  5537.1 1715.44
  5545.1 1716.16  5552.5 1719.13  5567.8 1722.59  5573.7 1723.55  5586.6 1724.14
#Mann=7,-1,0
  4591.8    0.05       0  4797.7     0.1       0  5000.4    0.07       0
  5004.4     0.1       0  5080.8    0.05       0  5261.2     0.1       0
  5429.0    0.05       0
Bank Sta=5000.4,5004.4
Exp/Cntr=0.3,0.1

Type RM Length L Ch R = 1,4993,229,229,229
BEGIN DESCRIPTION:
Mapping XS 8f0bcb90
END DESCRIPTION:
XS GIS Cut Line= 5
      1605148.15      6851379.72      1605348.71      6851530.79
      1605450.27      6851601.10      1605684.65      6851705.27
      1606004.98      6851869.34
#Sta/Elev= 30
  4809.1 1724.11  4833.8 1720.88  4863.0 1719.77  4877.5 1716.77  4883.8 1716.93
  4898.4 1714.74  4905.3 1712.20  4927.5 1707.96  5017.1 1705.04  5017.4 1704.54
  5021.1 1705.04  5170.4 1706.56  5209.2 1705.43  5214.6 1706.37  5232.4 1705.35
  5289.9 1706.16  5330.9 1705.32  5336.4 1706.25  5406.1 1705.94  5411.6 1707.13
  5429.4 1705.65  5449.1 1705.69  5523.9 1707.22  5608.5 1707.47  5679.3 1708.47
  5732.7 1710.46  5755.2 1714.74  5768.1 1720.21  5777.7 1722.09  5800.1 1722.01
#Mann=5,-1,0
  4809.1    0.05       0  5017.1    0.05       0  5021.1    0.05       0
  5449.1     0.1       0  5608.5    0.05       0
Bank Sta=5017.1,5021.1
Exp/Cntr=0.3,0.1

Type RM Length L Ch R = 1,4764,239,239,239
BEGIN DESCRIPTION:
Mapping XS 6ac5bb17
END DESCRIPTION:
XS GIS Cut Line= 4
      1604926.13      6851515.32      1605060.66      6851606.45
      1605512.05      6851856.02      1605889.61      6851916.78
#Sta/Elev= 30
  4672.8 1722.38  4789.8 1718.68  4816.9 1719.97  4834.9 1717.21  4863.1 1716.41
  4897.4 1711.65  4934.4 1708.10  5013.8 1705.77  5014.0 1705.27  5017.8 1705.77
  5053.6 1707.80  5118.9 1707.23  5134.9 1708.41  5162.4 1707.46  5178.4 1708.16
  5184.1 1706.69  5194.5 1707.49  5200.2 1705.92  5238.0 1707.52  5281.5 1706.48
  5392.3 1708.75  5521.1 1709.59  5536.4 1708.84  5566.8 1710.31  5582.9 1713.29
  5588.0 1710.67  5644.8 1720.93  5649.8 1717.71  5688.3 1723.84  5733.5 1723.37
#Mann=3,-1,0
  4672.8    0.05       0  5013.8    0.05       0  5017.8    0.05       0
Bank Sta=5013.8,5017.8
Exp/Cntr=0.3,0.1

Type RM Length L Ch R = 1,4525,213,213,213
BEGIN DESCRIPTION:
Mapping XS 819b1aa9
END DESCRIPTION:
XS GIS Cut Line= 4
      1604852.36      6851691.12      1605036.79      6851832.15
      1605527.24      6852151.16      1605621.37      6852080.56
#Sta/Elev= 30
  4624.9 1717.56  4674.8 1717.06  4724.7 1715.23  4739.2 1713.76  4745.5 1711.54
  4753.8 1710.53  4760.1 1707.75  4766.7 1709.43  4803.6 1706.17  4839.0 1704.83
  4874.9 1704.43  4911.1 1703.12  4917.1 1703.56  4987.6 1702.14  4987.8 1701.64
  4991.3 1701.64  4991.6 1702.14  5033.9 1702.91  5243.2 1703.56  5264.3 1706.21
  5294.6 1707.36  5336.8 1706.49  5351.9 1707.54  5388.1 1707.18  5415.6 1708.08
  5424.4 1707.10  5450.7 1707.62  5456.9 1706.52  5464.3 1706.39  5559.8 1707.33
#Mann=3,-1,0
  4624.9    0.05       0  4987.6    0.03       0  4991.6    0.05       0
Bank Sta=4987.6,4991.6
Exp/Cntr=0.3,0.1

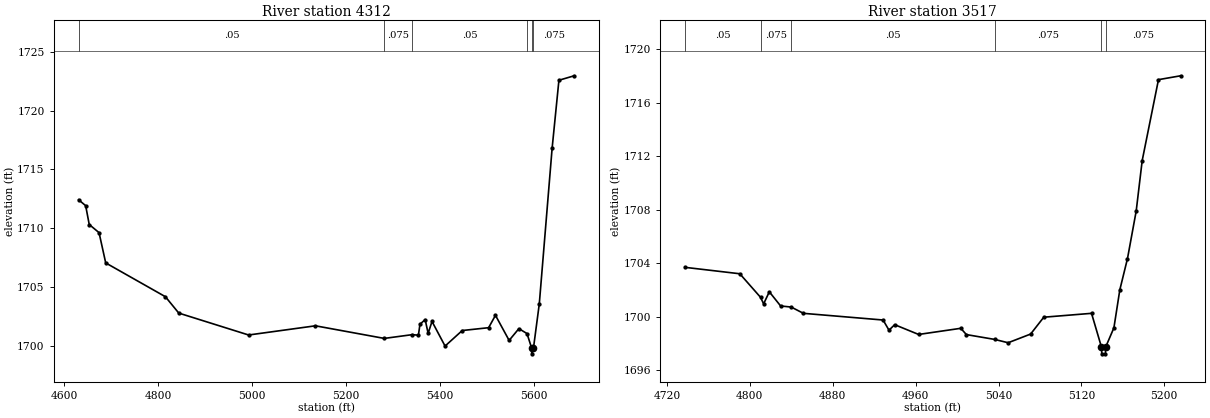
Type RM Length L Ch R = 1,4312,795,795,795
BEGIN DESCRIPTION:
Mapping XS 4cd09097
END DESCRIPTION:
XS GIS Cut Line= 4
      1604772.02      6851799.58      1604965.17      6852020.95
      1605295.04      6852307.41      1605554.18      6852503.92
#Sta/Elev= 30
  4630.2 1712.42  4645.2 1711.92  4652.8 1710.32  4673.7 1709.63  4687.9 1707.06
  4815.1 1704.19  4843.6 1702.80  4992.4 1700.94  5134.8 1701.72  5281.5 1700.65
  5341.3 1700.97  5354.2 1700.92  5357.5 1701.85  5368.6 1702.25  5374.9 1701.08
  5383.2 1702.09  5411.0 1700.00  5447.6 1701.32  5503.8 1701.56  5518.4 1702.61
  5547.5 1700.48  5568.3 1701.48  5585.6 1701.06  5595.4 1699.84  5595.7 1699.34
  5599.4 1699.84  5611.8 1703.59  5639.1 1716.79  5653.6 1722.57  5686.1 1722.95
#Mann=6,-1,0
  4630.2    0.05       0  5281.5   0.075       0  5341.3    0.05       0
  5585.6   0.075       0  5595.4    0.05       0  5599.4   0.075       0
Bank Sta=5595.4,5599.4
Exp/Cntr=0.3,0.1

Type RM Length L Ch R = 1,3517,0,0,0
BEGIN DESCRIPTION:
Unnamed Tributary to Rainy Cr 4734.426
END DESCRIPTION:
XS GIS Cut Line= 3
      1605048.67      6852353.98      1605180.02      6852643.78
      1605260.16      6852782.40
#Sta/Elev= 30
  4737.5 1703.69  4790.3 1703.21  4810.3 1701.45  4813.3 1700.96  4818.8 1701.86
  4829.7 1700.80  4839.9 1700.72  4851.7 1700.25  4928.6 1699.75  4934.3 1698.99
  4939.8 1699.40  4962.9 1698.67  5003.6 1699.13  5009.0 1698.66  5036.2 1698.30
  5049.3 1698.05  5071.0 1698.70  5083.7 1699.96  5129.8 1700.25  5139.4 1697.72
  5139.7 1697.22  5143.2 1697.22  5143.4 1697.72  5151.4 1699.17  5157.1 1702.01
  5164.5 1704.35  5172.9 1707.90  5178.7 1711.68  5194.4 1717.73  5215.8 1718.02
#Mann=6,-1,0
  4737.5    0.05       0  4810.3   0.075       0  4839.9    0.05       0
  5036.2   0.075       0  5139.4    0.03       0  5143.4   0.075       0
Bank Sta=5139.4,5143.4
Exp/Cntr=0.3,0.1

Chan Stop Cuts=-1