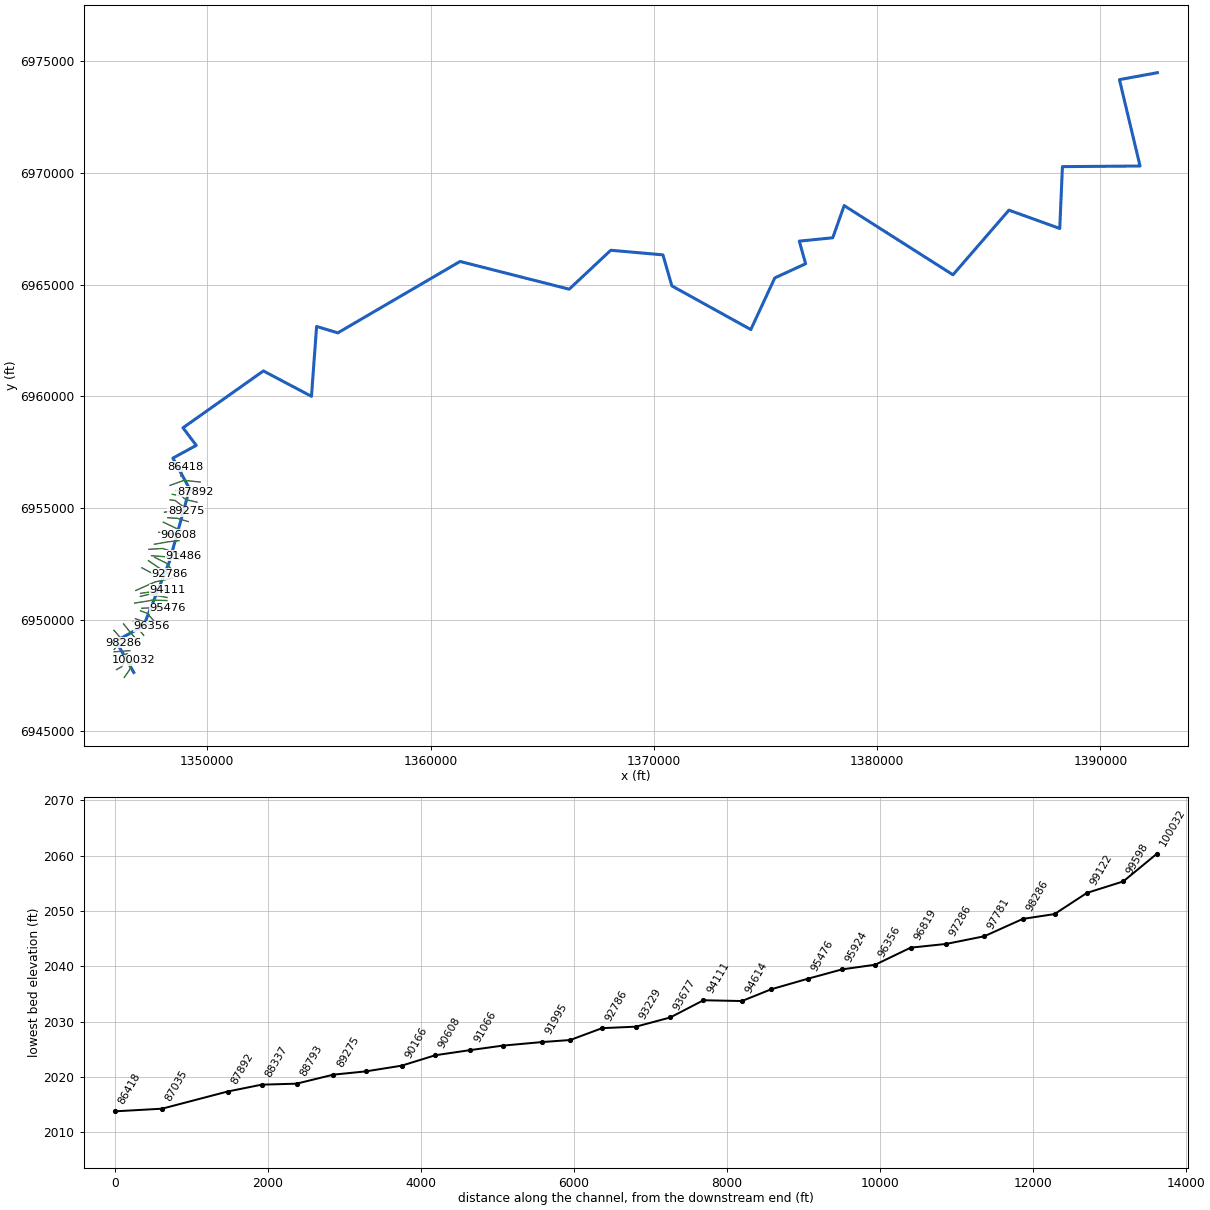
--- Alkali Creek.prj (project) ---

Proj Title=Alkali Creek Base Level Engineering
Current Plan=p01
Default Exp/Contr=0.3,0.1
English Units
Geom File=g01
Flow File=f01
Plan File=p01
Y Axis Title=Elevation
X Axis Title(PF)=Main Channel Distance
X Axis Title(XS)=Station
BEGIN DESCRIPTION:
Alkali Creek
END DESCRIPTION:
DSS Export Rating Curves= 0
DSS Export Rating Curve Sorted= 0
DSS Export Volume Flow Curves= 0
DXF OffsetX= 0
DXF OffsetY= 0
DXF ScaleX= 1
DXF ScaleY= 10

--- Alkali Creek.p01 (plan) ---

Plan Title=Multiple Run
Short Identifier=Multiple
Geom File=g01
Flow File=f01
Subcritical Flow
K Sum by GR= 0
Std Step Tol= 0.01
Critical Tol= 0.01
Num of Std Step Trials= 20
Max Error Tol= 0.3
Flow Tol Ratio= 0.001
Split Flow NTrial= 30
Split Flow Tol= 0.02
Split Flow Ratio= 0.02
Log Output Level= 0
Friction Slope Method= 1
Unsteady Friction Slope Method= 2
Unsteady Bridges Friction Slope Method= 1
Parabolic Critical Depth
Global Vel Dist=  1 , 1 , 1
Global Log Level= 0
CheckData=True
Encroach Param= -1, 0, 0, 0
BEGIN DESCRIPTION:
Multiple Run
END DESCRIPTION:

--- Alkali Creek.f01 (steady flow) ---

Flow Title=Multiple
Program Version=4.10
Number of Profiles= 7
Profile Names=10-year,25-year,50-year,1pct_min,100-year,1pct_plu,500-year
River Rch & RM=Alkali Creek,Reach-1         ,100032
     304     437     550     344     687    1371    1088
River Rch & RM=Alkali Creek,Reach-1         ,97781
     815    1228    1596    1029    2054    4098    3449
River Rch & RM=Alkali Creek,Reach-1         ,92371
     843    1265    1640    1054    2102    4195    3505
River Rch & RM=Alkali Creek,Reach-1         ,85479
    1168    1772    2312    1494    2982    5949    5028
River Rch & RM=Alkali Creek,Reach-1         ,80246
    1186    1794    2335    1505    3004    5993    5039
River Rch & RM=Alkali Creek,Reach-1         ,72427
    1240    1876    2444    1576    3145    6275    5279
River Rch & RM=Alkali Creek,Reach-1         ,70826
    1240    1871    2433    1566    3124    6233    5222
River Rch & RM=Alkali Creek,Reach-1         ,66405
    1304    1970    2565    1652    3296    6577    5521
River Rch & RM=Alkali Creek,Reach-1         ,65314
    1344    2029    2641    1700    3391    6767    5673
River Rch & RM=Alkali Creek,Reach-1         ,60398
    1360    2052    2667    1715    3421    6826    5708
River Rch & RM=Alkali Creek,Reach-1         ,54921
    1395    2099    2724    1747    3486    6956    5793
River Rch & RM=Alkali Creek,Reach-1         ,51065
    1759    2668    3480    2243    4476    8930    7508
River Rch & RM=Alkali Creek,Reach-1         ,40455
    1849    2807    3665    2364    4717    9412    7924
River Rch & RM=Alkali Creek,Reach-1         ,38847
    1834    2779    3622    2333    4654    9287    7792
River Rch & RM=Alkali Creek,Reach-1         ,32414
    1938    2937    3830    2467    4922    9821    8243
River Rch & RM=Alkali Creek,Reach-1         ,26512
    1961    2971    3874    2495    4978    9932    8334
River Rch & RM=Alkali Creek,Reach-1         ,24367
    1970    2983    3889    2504    4996    9967    8358
River Rch & RM=Alkali Creek,Reach-1         ,22763
    2630    4015    5264    3407    6797   13562   11487
River Rch & RM=Alkali Creek,Reach-1         ,19387
    2621    3990    5218    3369    6721   13411   11302
Boundary for River Rch & Prof#=Alkali Creek,Reach-1         , 1
Up Type= 0
Dn Type= 3
Dn Slope=0.002
Boundary for River Rch & Prof#=Alkali Creek,Reach-1         , 2
Up Type= 0
Dn Type= 3
Dn Slope=0.002
Boundary for River Rch & Prof#=Alkali Creek,Reach-1         , 3
Up Type= 0
Dn Type= 3
Dn Slope=0.002
Boundary for River Rch & Prof#=Alkali Creek,Reach-1         , 4
Up Type= 0
Dn Type= 3
Dn Slope=0.002
Boundary for River Rch & Prof#=Alkali Creek,Reach-1         , 5
Up Type= 0
Dn Type= 3
Dn Slope=0.002
Boundary for River Rch & Prof#=Alkali Creek,Reach-1         , 6
Up Type= 0
Dn Type= 3
Dn Slope=0.002
Boundary for River Rch & Prof#=Alkali Creek,Reach-1         , 7
Up Type= 0
Dn Type= 3
Dn Slope=0.002
DSS Import GetInterval= 0
DSS Import GetPeak= 0
DSS Import FillOption= 0

--- Alkali Creek.g01 (geometry) ---

Geom Title=Existing Conditions

River Reach=Alkali Creek,Reach-1
Reach XY= 30
      1346705.00      6947638.00      1345905.00      6949038.00
      1347147.12      6949731.83      1348303.38      6952599.81
      1349205.50      6955858.24      1348457.01      6957232.17
      1349504.61      6957803.28      1348910.35      6958590.70
      1352511.51      6961136.37      1354664.83      6959998.52
      1354894.51      6963127.04      1355846.38      6962840.96
      1361321.03      6966037.84      1366208.39      6964795.76
      1368070.69      6966538.70      1370407.74      6966332.66
      1370809.63      6964942.63      1374344.31      6962988.74
      1375418.39      6965301.34      1376799.54      6965935.55
      1376515.76      6966947.68      1378014.80      6967098.48
      1378525.06      6968538.22      1383399.17      6965440.06
      1385906.45      6968334.47      1388181.94      6967514.14
      1388302.70      6970282.91      1391778.53      6970310.86
      1390855.98      6974177.74      1392555.00      6974488.00

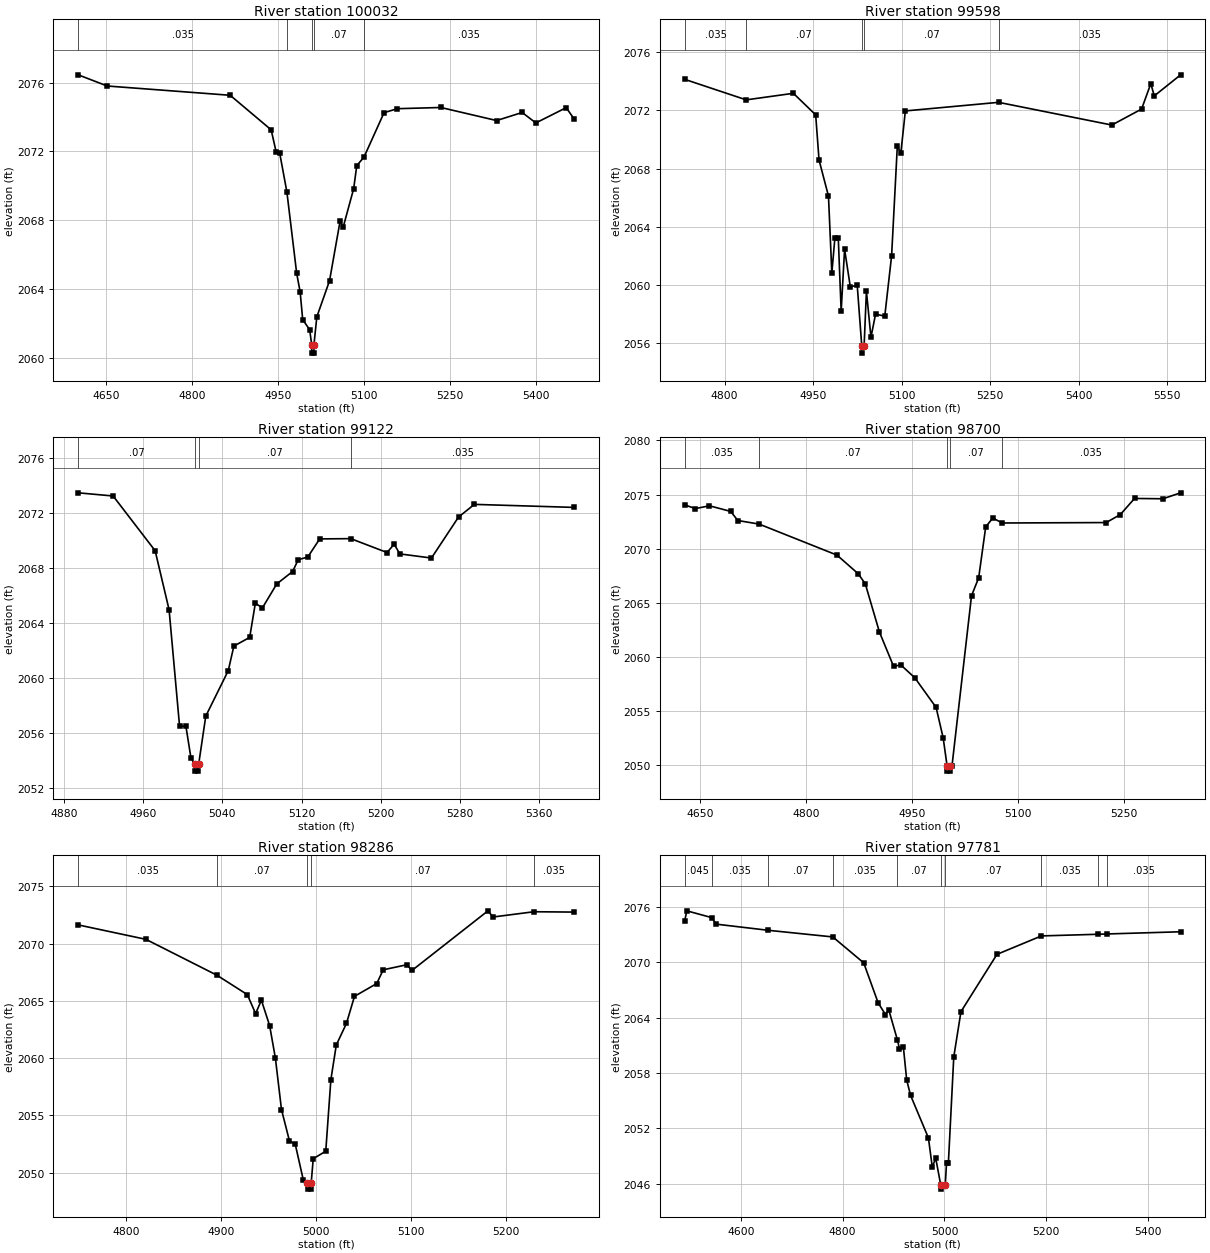
Type RM Length L Ch R = 1,100032,434,434,434
BEGIN DESCRIPTION:
Alkali Creek 113.0
END DESCRIPTION:
XS GIS Cut Line= 3
      1346279.97      6947412.96      1346505.00      6947738.00
      1346686.53      6948173.01
#Sta/Elev= 30
  4600.6 2076.45  4651.3 2075.80  4866.2 2075.26  4937.8 2073.25  4946.6 2071.95
  4952.7 2071.90  4965.3 2069.63  4982.4 2064.90  4988.5 2063.81  4992.9 2062.21
  5005.1 2061.62  5008.6 2060.76  5008.8 2060.26  5012.3 2060.26  5012.6 2060.76
  5017.6 2062.37  5039.8 2064.47  5058.2 2067.93  5063.6 2067.58  5082.0 2069.83
  5087.4 2071.17  5100.0 2071.66  5135.1 2074.25  5158.5 2074.48  5234.3 2074.55
  5331.8 2073.79  5376.5 2074.26  5400.3 2073.65  5453.4 2074.54  5467.3 2073.88
#Mann=5,-1,0
  4600.6   0.035       0  4965.3    0.07       0  5008.6    0.07       0
  5012.6    0.07       0  5100.0   0.035       0
Bank Sta=5008.6,5012.6
Exp/Cntr=0.3,0.1

Type RM Length L Ch R = 1,99598,476,476,476
BEGIN DESCRIPTION:
Alkali Creek 112.0
END DESCRIPTION:
XS GIS Cut Line= 3
      1345929.97      6947762.99      1346155.00      6947888.00
      1346454.99      6948387.99
#Sta/Elev= 30
  4732.3 2074.13  4836.6 2072.72  4916.5 2073.17  4954.3 2071.69  4960.0 2068.59
  4976.0 2066.11  4981.7 2060.82  4986.9 2063.25  4992.6 2063.25  4997.5 2058.20
  5003.3 2062.46  5013.0 2059.87  5024.7 2059.99  5032.4 2055.82  5032.7 2055.32
  5036.4 2055.82  5040.3 2059.57  5048.0 2056.41  5055.8 2058.00  5071.4 2057.86
  5083.0 2062.01  5092.7 2069.56  5098.6 2069.05  5106.3 2071.96  5264.3 2072.55
  5456.2 2070.99  5506.7 2072.09  5522.3 2073.84  5528.1 2072.99  5572.8 2074.44
#Mann=5,-1,0
  4732.3   0.035       0  4836.6    0.07       0  5032.4    0.07       0
  5036.4    0.07       0  5264.3   0.035       0
Bank Sta=5032.4,5036.4
Exp/Cntr=0.3,0.1

Type RM Length L Ch R = 1,99122,422,422,422
BEGIN DESCRIPTION:
Alkali Creek 111.0
END DESCRIPTION:
XS GIS Cut Line= 3
      1345980.02      6948213.02      1346055.00      6948288.00
      1346400.04      6948481.21
#Sta/Elev= 30
  4894.2 2073.47  4929.5 2073.24  4972.0 2069.26  4986.1 2064.97  4996.7 2056.50
  5003.1 2056.50  5008.2 2054.20  5012.0 2053.74  5012.2 2053.24  5015.7 2053.24
  5016.0 2053.74  5023.2 2057.24  5045.9 2060.54  5051.6 2062.33  5067.6 2062.96
  5073.3 2065.44  5080.5 2065.11  5095.0 2066.85  5111.0 2067.75  5116.7 2068.61
  5126.3 2068.80  5138.4 2070.12  5169.8 2070.14  5206.5 2069.13  5213.7 2069.74
  5219.4 2069.03  5251.4 2068.73  5278.8 2071.71  5294.8 2072.63  5395.7 2072.41
#Mann=4,-1,0
  4894.2    0.07       0  5012.0    0.07       0  5016.0    0.07       0
  5169.8   0.035       0
Bank Sta=5012,5016
Exp/Cntr=0.3,0.1

Type RM Length L Ch R = 1,98700,414,414,414
BEGIN DESCRIPTION:
Alkali Creek 110.0
END DESCRIPTION:
XS GIS Cut Line= 3
      1345830.00      6948563.00      1346205.00      6948588.00
      1346530.00      6948613.00
#Sta/Elev= 30
  4628.3 2074.05  4643.3 2073.70  4663.4 2073.96  4693.4 2073.44  4703.5 2072.60
  4733.6 2072.27  4843.8 2069.40  4873.8 2067.68  4883.9 2066.74  4903.9 2062.28
  4924.0 2059.10  4934.0 2059.25  4954.0 2058.05  4984.1 2055.31  4994.1 2052.49
  4999.6 2049.92  4999.9 2049.42  5003.4 2049.42  5003.6 2049.92  5006.6 2049.92
  5034.2 2065.64  5044.3 2067.29  5054.3 2072.01  5064.3 2072.83  5077.6 2072.37
  5224.8 2072.41  5244.8 2073.15  5264.9 2074.64  5305.0 2074.61  5330.1 2075.16
#Mann=5,-1,0
  4628.3   0.035       0  4733.6    0.07       0  4999.6    0.07       0
  5003.6    0.07       0  5077.6   0.035       0
Bank Sta=4999.6,5003.6
Exp/Cntr=0.3,0.1

Type RM Length L Ch R = 1,98286,505,505,505
BEGIN DESCRIPTION:
Alkali Creek 109.0
END DESCRIPTION:
XS GIS Cut Line= 3
      1345830.00      6948663.00      1345974.86      6948867.62
      1346230.01      6948963.00
#Sta/Elev= 30
  4749.3 2071.63  4820.7 2070.37  4895.5 2067.24  4927.7 2065.54  4936.4 2063.88
  4942.5 2065.05  4951.2 2062.84  4957.3 2059.98  4963.7 2055.50  4972.1 2052.76
  4978.2 2052.48  4986.8 2049.32  4991.0 2049.05  4991.2 2048.55  4994.7 2048.55
  4995.0 2049.05  4997.2 2051.21  5010.4 2051.86  5015.8 2058.11  5021.5 2061.14
  5032.2 2063.02  5040.7 2065.39  5064.2 2066.51  5071.0 2067.71  5096.0 2068.15
  5101.3 2067.65  5181.5 2072.86  5186.8 2072.32  5230.0 2072.78  5272.4 2072.75
#Mann=5,-1,0
  4749.3   0.035       0  4895.5    0.07       0  4991.0    0.07       0
  4995.0    0.07       0  5230.0   0.035       0
Bank Sta=4991,4995
Exp/Cntr=0.3,0.1

Type RM Length L Ch R = 1,97781,495,495,495
BEGIN DESCRIPTION:
Alkali Creek 108.0
END DESCRIPTION:
XS GIS Cut Line= 3
      1345816.32      6949525.09      1346155.00      6949138.00
      1346480.03      6948812.97
#Sta/Elev= 30
  4489.8 2074.49  4494.0 2075.58  4543.8 2074.83  4550.9 2074.14  4653.8 2073.47
  4780.7 2072.75  4841.4 2069.94  4869.8 2065.60  4884.1 2064.34  4890.7 2064.83
  4907.7 2061.56  4911.6 2060.63  4919.2 2060.87  4925.8 2057.25  4933.4 2055.58
  4968.5 2050.96  4976.1 2047.79  4982.8 2048.78  4992.5 2045.91  4993.0 2045.41
  5001.6 2045.91  5004.1 2048.25  5007.7 2048.25  5018.3 2059.75  5032.4 2064.65
  5103.1 2070.86  5190.4 2072.86  5302.3 2073.04  5318.3 2073.07  5463.8 2073.31
#Mann=10,-1,0
  4489.8   0.045       0  4543.8   0.035       0  4653.8    0.07       0
  4780.7   0.035       0  4907.7    0.07       0  4992.5    0.07       0
  5001.6    0.07       0  5190.4   0.035       0  5302.3    0.07       0
  5318.3   0.035       0
Bank Sta=4992.5,5001.6
Exp/Cntr=0.3,0.1

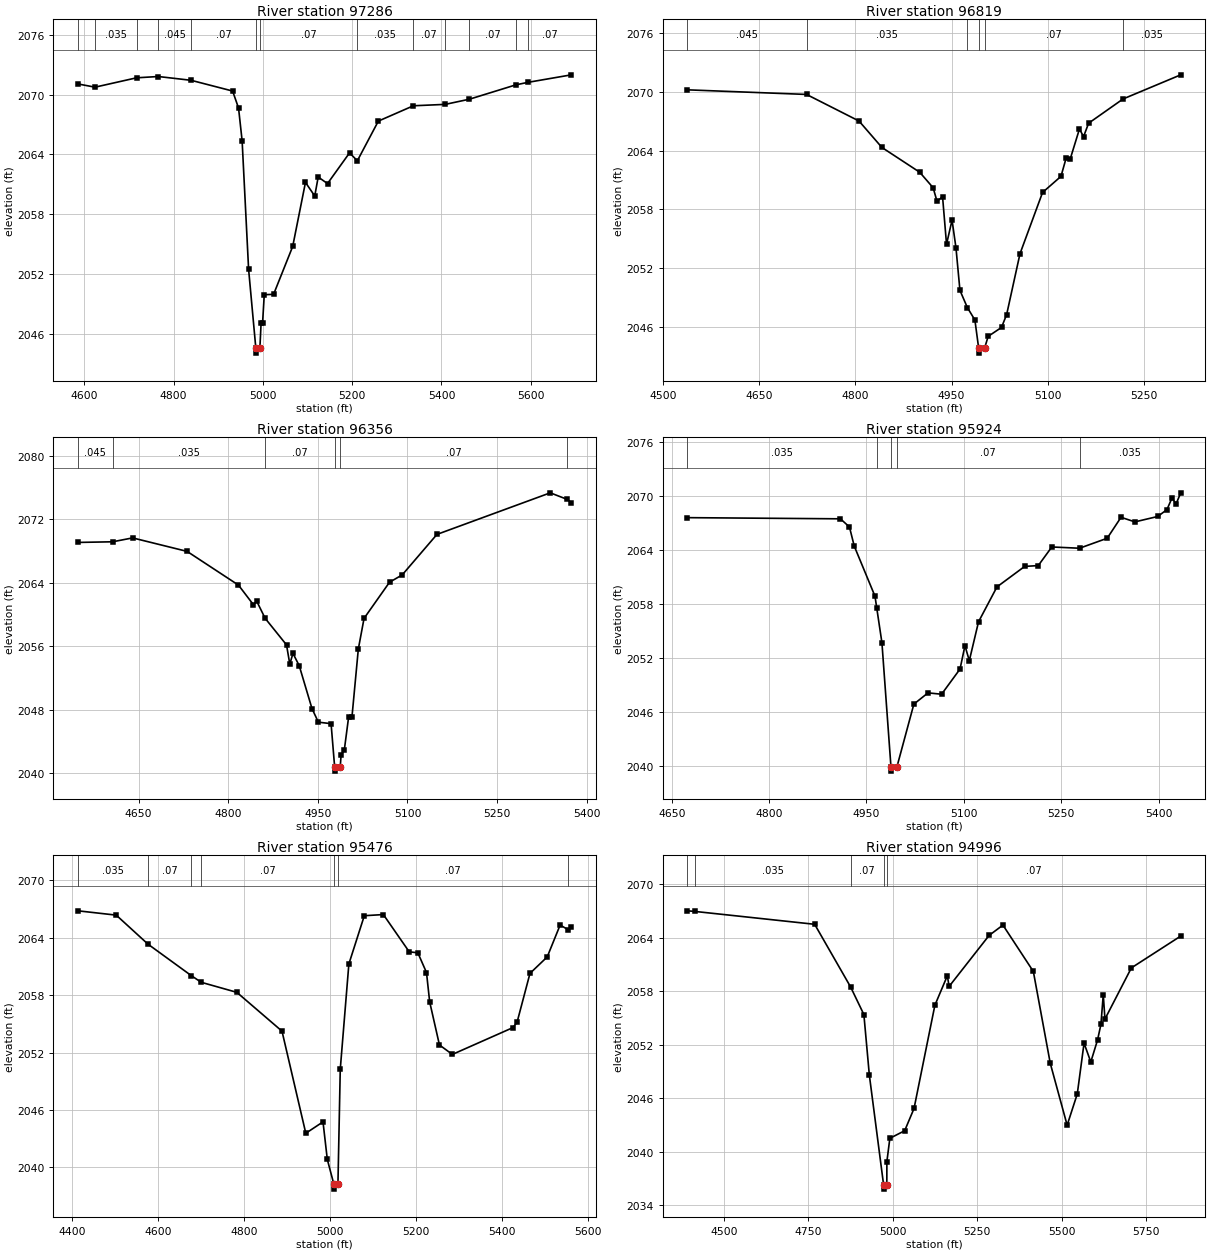
Type RM Length L Ch R = 1,97286,467,467,467
BEGIN DESCRIPTION:
Alkali Creek 107.0
END DESCRIPTION:
XS GIS Cut Line= 3
      1346250.38      6949809.34      1346505.00      6949488.00
      1346955.67      6948958.65
#Sta/Elev= 30
  4585.9 2071.08  4623.9 2070.76  4716.9 2071.70  4765.6 2071.83  4839.1 2071.45
  4932.1 2070.37  4945.4 2068.66  4953.4 2065.37  4967.9 2052.47  4984.1 2044.53
  4984.6 2044.03  4993.2 2044.53  4995.9 2047.06  4999.2 2047.06  5003.0 2049.90
  5023.9 2049.94  5066.7 2054.75  5095.3 2061.19  5116.1 2059.82  5123.8 2061.73
  5144.7 2061.07  5194.1 2064.16  5211.5 2063.36  5258.6 2067.35  5337.1 2068.89
  5408.4 2069.03  5462.6 2069.55  5566.5 2070.99  5593.2 2071.24  5691.1 2072.00
#Mann=13,-1,0
  4585.9   0.045       0  4623.9   0.035       0  4716.9    0.07       0
  4765.6   0.045       0  4839.1    0.07       0  4984.1    0.07       0
  4993.2    0.07       0  5211.5   0.035       0  5337.1    0.07       0
  5408.4   0.035       0  5462.6    0.07       0  5566.5   0.035       0
  5593.2    0.07       0
Bank Sta=4984.1,4993.2
Exp/Cntr=0.3,0.1

Type RM Length L Ch R = 1,96819,463,463,463
BEGIN DESCRIPTION:
Alkali Creek 106.0
END DESCRIPTION:
XS GIS Cut Line= 3
      1346686.54      6949913.56      1346955.00      6949538.00
      1347148.77      6949299.42
#Sta/Elev= 30
  4538.3 2070.19  4724.0 2069.72  4805.8 2067.01  4841.4 2064.32  4900.4 2061.79
  4921.3 2060.21  4927.4 2058.82  4936.0 2059.30  4942.2 2054.45  4950.8 2056.91
  4956.9 2054.09  4963.1 2049.75  4974.7 2047.99  4986.4 2046.73  4992.3 2043.85
  4992.8 2043.35  5001.5 2043.85  5007.1 2045.06  5027.9 2045.97  5035.9 2047.28
  5056.7 2053.48  5091.9 2059.73  5120.6 2061.37  5128.5 2063.20  5135.0 2063.14
  5149.4 2066.20  5155.8 2065.42  5163.7 2066.79  5217.4 2069.26  5307.3 2071.72
#Mann=6,-1,0
  4538.3   0.045       0  4724.0   0.035       0  4974.7    0.07       0
  4992.3    0.07       0  5001.5    0.07       0  5217.4   0.035       0
Bank Sta=4992.3,5001.5
Exp/Cntr=0.3,0.1

Type RM Length L Ch R = 1,96356,432,432,432
BEGIN DESCRIPTION:
Alkali Creek 105.0
END DESCRIPTION:
XS GIS Cut Line= 3
      1346777.74      6950045.90      1347205.00      6949888.00
      1347521.01      6949694.99
#Sta/Elev= 30
  4548.6 2069.09  4606.4 2069.17  4639.9 2069.66  4731.1 2067.96  4817.1 2063.71
  4842.1 2061.24  4847.5 2061.70  4861.7 2059.53  4897.5 2056.18  4903.0 2053.76
  4908.3 2055.11  4918.8 2053.55  4940.1 2048.16  4950.8 2046.44  4972.1 2046.25
  4978.1 2040.77  4978.6 2040.27  4987.4 2040.77  4988.9 2042.36  4994.2 2042.90
  5001.4 2047.05  5007.0 2047.05  5017.7 2055.65  5027.3 2059.52  5069.9 2064.07
  5091.2 2065.00  5149.3 2070.10  5339.0 2075.34  5367.8 2074.50  5374.4 2074.09
#Mann=6,-1,0
  4548.6   0.045       0  4606.4   0.035       0  4861.7    0.07       0
  4978.1    0.07       0  4987.4    0.07       0  5367.8   0.035       0
Bank Sta=4978.1,4987.4
Exp/Cntr=0.3,0.1

Type RM Length L Ch R = 1,95924,448,448,448
BEGIN DESCRIPTION:
Alkali Creek 104.0
END DESCRIPTION:
XS GIS Cut Line= 3
      1347003.42      6950397.46      1347305.00      6950288.00
      1347595.86      6949959.09
#Sta/Elev= 30
  4674.2 2067.61  4909.9 2067.48  4923.8 2066.57  4931.2 2064.44  4963.1 2058.88
  4965.8 2057.58  4973.8 2053.71  4987.7 2039.93  4988.2 2039.43  4997.0 2039.93
  5023.0 2046.88  5044.8 2048.13  5065.7 2047.98  5094.1 2050.78  5101.7 2053.38
  5108.4 2051.71  5122.6 2056.03  5151.0 2059.91  5193.7 2062.19  5214.6 2062.28
  5235.5 2064.35  5278.2 2064.21  5320.8 2065.32  5342.1 2067.65  5363.5 2067.14
  5398.6 2067.74  5412.8 2068.50  5420.4 2069.76  5427.1 2069.17  5434.1 2070.37
#Mann=5,-1,0
  4674.2   0.035       0  4965.8    0.07       0  4987.7    0.07       0
  4997.0    0.07       0  5278.2   0.035       0
Bank Sta=4987.7,4997
Exp/Cntr=0.3,0.1

Type RM Length L Ch R = 1,95476,480,480,480
BEGIN DESCRIPTION:
Alkali Creek 103.0
END DESCRIPTION:
XS GIS Cut Line= 3
      1347066.33      6950512.49      1347655.00      6950538.00
      1348211.10      6950501.71
#Sta/Elev= 30
  4414.8 2066.79  4503.5 2066.34  4577.3 2063.31  4678.1 2060.02  4701.0 2059.33
  4783.8 2058.28  4888.7 2054.23  4944.0 2043.57  4984.0 2044.76  4994.0 2040.84
  5009.3 2038.24  5009.8 2037.74  5018.7 2038.24  5024.1 2050.25  5044.1 2061.24
  5080.0 2066.28  5124.3 2066.40  5184.4 2062.51  5204.4 2062.41  5224.5 2060.35
  5231.9 2057.29  5254.6 2052.79  5284.6 2051.80  5424.9 2054.59  5434.9 2055.14
  5465.0 2060.26  5505.1 2061.98  5535.1 2065.31  5553.2 2064.83  5561.3 2065.12
#Mann=7,-1,0
  4414.8   0.035       0  4577.3    0.07       0  4678.1   0.035       0
  4701.0    0.07       0  5009.3    0.07       0  5018.7    0.07       0
  5553.2   0.035       0
Bank Sta=5009.3,5018.7
Exp/Cntr=0.3,0.1

Type RM Length L Ch R = 1,94996,382,382,382
BEGIN DESCRIPTION:
Alkali Creek 102.0
END DESCRIPTION:
XS GIS Cut Line= 4
      1346742.74      6950743.34      1347355.00      6950838.00
      1347515.91      6950876.35      1348191.16      6950856.22
#Sta/Elev= 30
  4391.6 2067.04  4414.3 2066.97  4768.3 2065.53  4874.6 2058.51  4914.0 2055.41
  4930.2 2048.61  4972.3 2036.33  4972.8 2035.83  4981.9 2036.33  4982.1 2038.92
  4990.9 2041.53  5034.8 2042.38  5062.5 2044.88  5124.2 2056.45  5161.1 2059.76
  5166.3 2058.56  5284.9 2064.29  5325.7 2065.44  5415.7 2060.24  5465.8 2049.94
  5515.8 2043.00  5545.8 2046.51  5565.8 2052.20  5585.8 2050.09  5605.8 2052.56
  5615.8 2054.31  5622.7 2057.64  5627.7 2054.90  5705.9 2060.64  5852.1 2064.21
#Mann=5,-1,0
  4391.6   0.045       0  4414.3   0.035       0  4874.6    0.07       0
  4972.3    0.07       0  4981.9    0.07       0
Bank Sta=4972.3,4981.9
Exp/Cntr=0.3,0.1

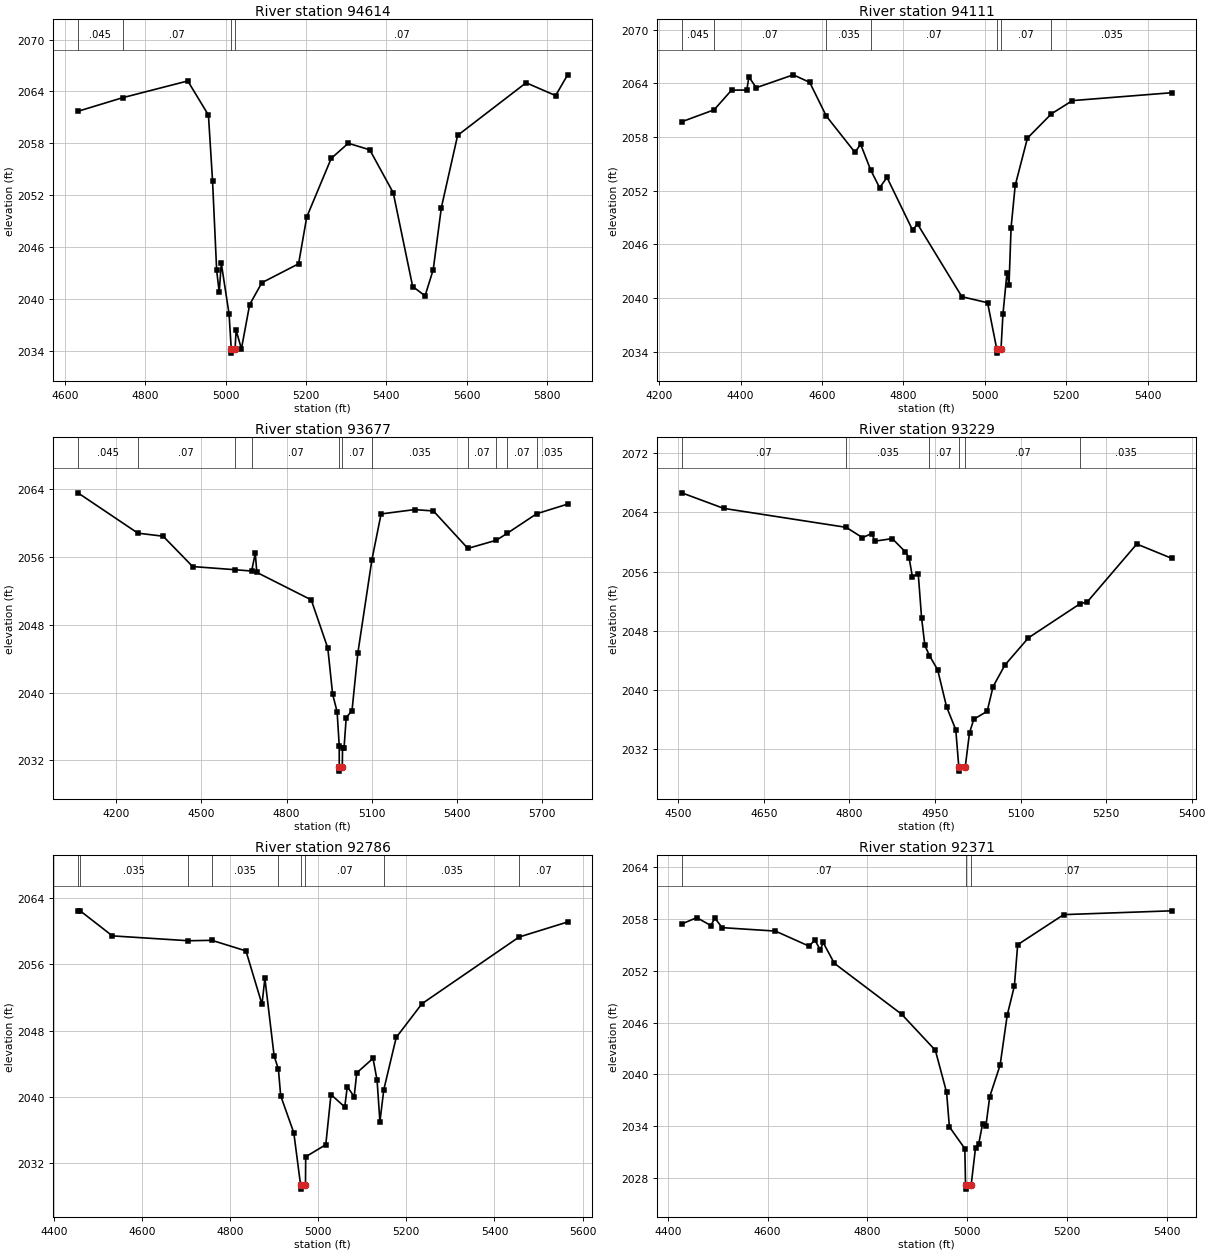
Type RM Length L Ch R = 1,94614,503,503,503
BEGIN DESCRIPTION:
Alkali Creek 101.0
END DESCRIPTION:
XS GIS Cut Line= 3
      1346998.80      6951040.65      1347405.00      6951138.00
      1348194.57      6950995.07
#Sta/Elev= 30
  4631.8 2061.70  4743.8 2063.28  4905.5 2065.21  4957.0 2061.26  4967.2 2053.67
  4977.5 2043.28  4983.9 2040.74  4989.0 2044.11  5008.4 2038.24  5013.8 2034.21
  5014.3 2033.71  5023.4 2034.21  5025.9 2036.35  5039.2 2034.21  5059.7 2039.33
  5090.1 2041.86  5181.6 2044.05  5201.9 2049.46  5262.9 2056.25  5305.4 2058.00
  5358.9 2057.24  5417.4 2052.27  5465.8 2041.42  5496.7 2040.34  5517.0 2043.37
  5537.3 2050.56  5577.8 2058.91  5748.4 2065.00  5821.9 2063.52  5851.9 2065.92
#Mann=4,-1,0
  4631.8   0.045       0  4743.8    0.07       0  5013.8    0.07       0
  5023.4    0.07       0
Bank Sta=5013.8,5023.4
Exp/Cntr=0.3,0.1

Type RM Length L Ch R = 1,94111,434,434,434
BEGIN DESCRIPTION:
Alkali Creek 100.0
END DESCRIPTION:
XS GIS Cut Line= 3
      1347014.01      6951179.54      1347755.00      6951288.00
      1348207.54      6951329.28
#Sta/Elev= 30
  4255.4 2059.70  4334.8 2061.03  4377.7 2063.23  4415.2 2063.24  4420.3 2064.71
  4438.3 2063.50  4529.3 2064.94  4569.7 2064.10  4610.4 2060.34  4680.9 2056.28
  4694.8 2057.19  4719.7 2054.29  4741.5 2052.33  4759.6 2053.48  4822.4 2047.60
  4834.6 2048.27  4943.6 2040.15  5006.8 2039.48  5029.1 2034.35  5029.6 2033.85
  5039.8 2034.35  5044.5 2038.19  5054.4 2042.83  5059.4 2041.44  5064.5 2047.88
  5074.6 2052.58  5104.7 2057.87  5163.5 2060.58  5215.2 2062.06  5458.7 2062.94
#Mann=7,-1,0
  4255.4   0.045       0  4334.8    0.07       0  4610.4   0.035       0
  4719.7    0.07       0  5029.1    0.07       0  5039.8    0.07       0
  5163.5   0.035       0
Bank Sta=5029.1,5039.8
Exp/Cntr=0.3,0.1

Type RM Length L Ch R = 1,93677,448,448,448
BEGIN DESCRIPTION:
Alkali Creek 99.0
END DESCRIPTION:
XS GIS Cut Line= 3
      1346799.16      6951309.76      1347655.00      6951688.00
      1348426.76      6951860.97
#Sta/Elev= 30
  4064.3 2063.58  4275.8 2058.82  4364.8 2058.46  4468.9 2054.88  4617.1 2054.51
  4676.8 2054.35  4689.6 2056.46  4695.1 2054.19  4886.9 2050.95  4945.3 2045.26
  4962.3 2039.83  4978.1 2037.75  4985.6 2033.76  4985.7 2031.24  4986.2 2030.74
  4996.4 2031.24  4997.3 2033.49  5002.6 2033.49  5010.2 2037.05  5030.7 2037.88
  5051.2 2044.67  5100.8 2055.68  5133.2 2061.09  5251.3 2061.60  5317.7 2061.44
  5439.1 2057.02  5539.9 2057.99  5578.6 2058.82  5681.6 2061.11  5790.9 2062.25
#Mann=11,-1,0
  4064.3   0.045       0  4275.8    0.07       0  4617.1   0.035       0
  4676.8    0.07       0  4985.7    0.07       0  4996.4    0.07       0
  5100.8   0.035       0  5439.1    0.07       0  5539.9   0.035       0
  5578.6    0.07       0  5681.6   0.035       0
Bank Sta=4985.7,4996.4
Exp/Cntr=0.3,0.1

Type RM Length L Ch R = 1,93229,443,443,443
BEGIN DESCRIPTION:
Alkali Creek 98.0
END DESCRIPTION:
XS GIS Cut Line= 3
      1347070.36      6952323.22      1347505.00      6952088.00
      1347858.12      6951997.69
#Sta/Elev= 30
  4506.0 2066.64  4579.5 2064.54  4794.4 2061.98  4822.8 2060.59  4839.0 2061.14
  4844.7 2060.12  4875.1 2060.46  4897.9 2058.68  4904.6 2057.86  4910.3 2055.32
  4920.6 2055.71  4926.5 2049.74  4932.2 2046.05  4940.2 2044.68  4954.7 2042.74
  4970.2 2037.78  4986.4 2034.67  4991.8 2029.58  4992.3 2029.08  5002.9 2029.58
  5010.5 2034.26  5018.0 2036.08  5041.5 2037.16  5051.8 2040.48  5072.5 2043.39
  5113.8 2047.07  5204.1 2051.66  5217.0 2051.92  5303.8 2059.73  5364.7 2057.81
#Mann=6,-1,0
  4506.0    0.07       0  4794.4   0.035       0  4940.2    0.07       0
  4991.8    0.07       0  5002.9    0.07       0  5204.1   0.035       0
Bank Sta=4991.8,5002.9
Exp/Cntr=0.3,0.1

Type RM Length L Ch R = 1,92786,415,415,415
BEGIN DESCRIPTION:
Alkali Creek 97.0
END DESCRIPTION:
XS GIS Cut Line= 3
      1347361.24      6952644.35      1347805.00      6952338.00
      1348296.57      6952045.40
#Sta/Elev= 30
  4454.8 2062.46  4459.9 2062.48  4533.0 2059.45  4705.5 2058.86  4759.0 2058.91
  4836.1 2057.63  4872.5 2051.18  4879.1 2054.31  4900.1 2044.91  4909.8 2043.32
  4914.9 2040.11  4944.7 2035.63  4960.1 2029.31  4960.6 2028.81  4971.2 2029.31
  4971.7 2032.72  5017.3 2034.19  5029.1 2040.25  5060.3 2038.75  5066.1 2041.21
  5081.7 2039.99  5087.5 2042.87  5124.5 2044.63  5133.7 2041.96  5140.1 2036.98
  5149.0 2040.86  5177.1 2047.16  5235.5 2051.24  5455.9 2059.31  5566.1 2061.13
#Mann=9,-1,0
  4454.8   0.045       0  4459.9   0.035       0  4705.5    0.07       0
  4759.0   0.035       0  4909.8    0.07       0  4960.1    0.07       0
  4971.2    0.07       0  5149.0   0.035       0  5455.9    0.07       0
Bank Sta=4960.1,4971.2
Exp/Cntr=0.3,0.1

Type RM Length L Ch R = 1,92371,376,376,376
BEGIN DESCRIPTION:
Alkali Creek 96.0
END DESCRIPTION:
XS GIS Cut Line= 3
      1347645.50      6952787.60      1348155.00      6952538.00
      1348424.59      6952223.35
#Sta/Elev= 30
  4427.8 2057.44  4458.0 2058.17  4486.1 2057.25  4494.1 2058.13  4508.6 2057.01
  4615.5 2056.61  4683.0 2054.86  4694.5 2055.57  4705.5 2054.44  4711.1 2055.29
  4733.6 2052.87  4868.6 2046.96  4936.1 2042.78  4958.6 2037.91  4964.2 2033.90
  4995.2 2031.37  4996.6 2027.17  4997.1 2026.67  5007.9 2027.17  5016.6 2031.46
  5023.1 2031.95  5030.8 2034.25  5037.4 2033.97  5045.1 2037.40  5065.9 2041.06
  5080.2 2046.87  5094.5 2050.24  5101.1 2055.03  5193.3 2058.52  5409.5 2058.96
#Mann=3,-1,0
  4427.8    0.07       0  4996.6    0.07       0  5007.9    0.07       0
Bank Sta=4996.6,5007.9
Exp/Cntr=0.3,0.1

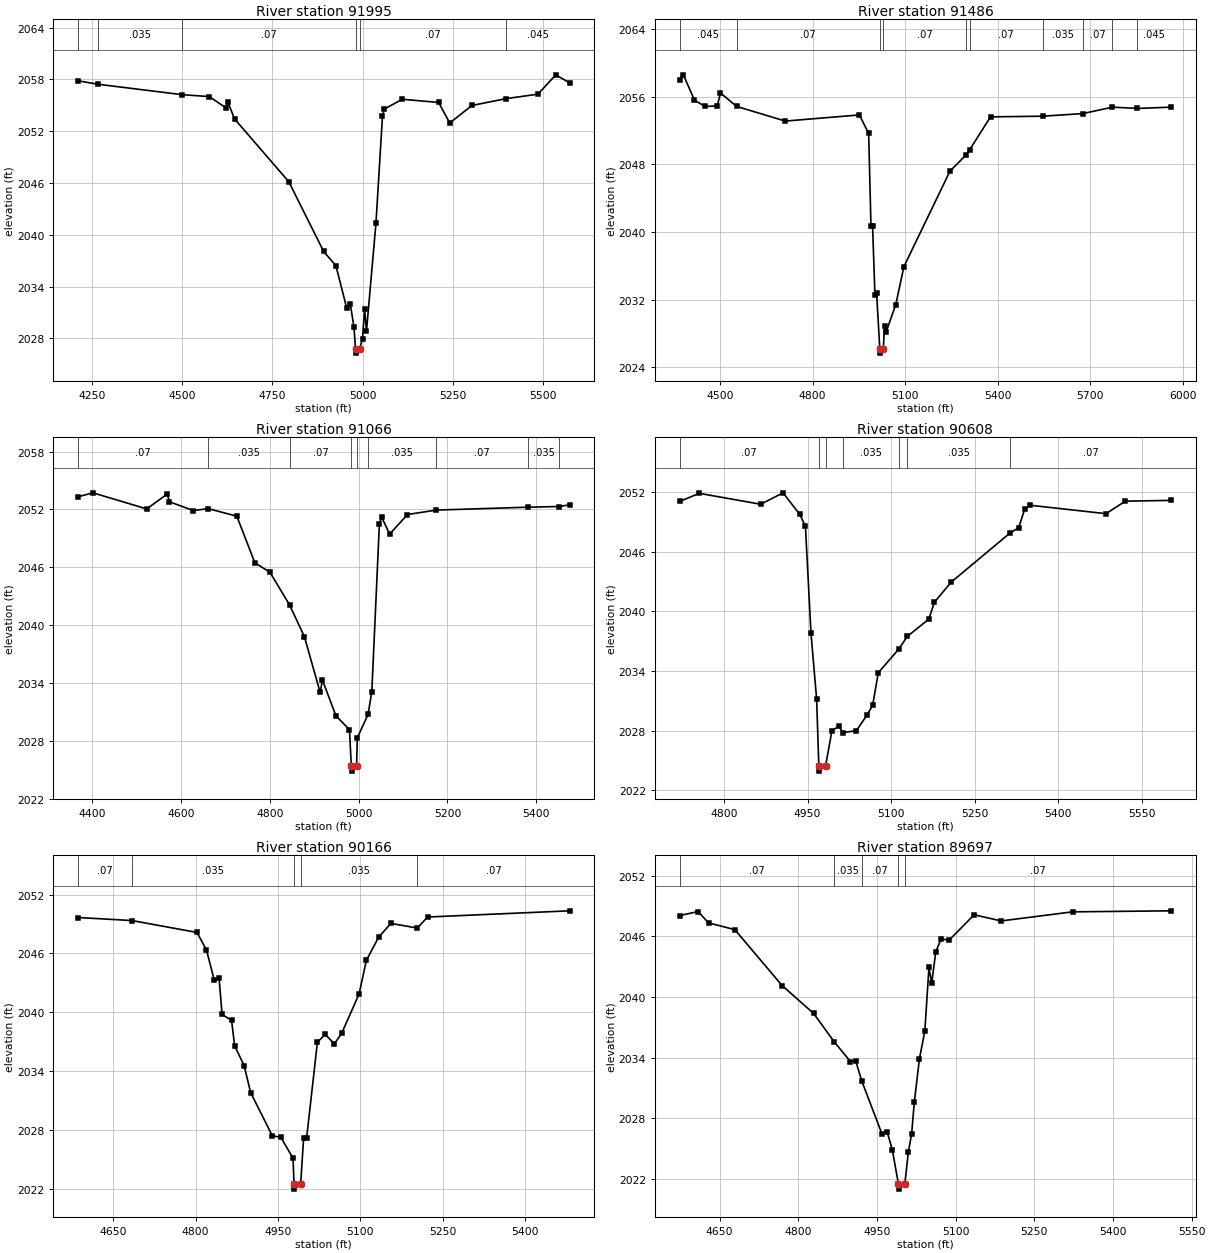
Type RM Length L Ch R = 1,91995,509,509,509
BEGIN DESCRIPTION:
Alkali Creek 95.0
END DESCRIPTION:
XS GIS Cut Line= 3
      1347502.22      6952863.57      1348288.65      6952805.11
      1348849.87      6952685.62
#Sta/Elev= 30
  4211.4 2057.83  4266.5 2057.43  4500.3 2056.22  4575.2 2056.00  4622.0 2054.68
  4627.0 2055.33  4645.4 2053.41  4795.8 2046.13  4892.3 2038.06  4926.2 2036.42
  4956.2 2031.50  4966.3 2031.94  4976.3 2029.28  4980.6 2026.79  4981.1 2026.29
  4992.0 2026.79  5000.0 2027.97  5005.7 2031.45  5010.9 2028.83  5037.2 2041.31
  5055.3 2053.72  5060.4 2054.55  5110.0 2055.69  5211.0 2055.32  5241.7 2052.94
  5303.2 2054.97  5397.4 2055.76  5486.1 2056.28  5535.7 2058.52  5573.8 2057.59
#Mann=6,-1,0
  4211.4    0.07       0  4266.5   0.035       0  4500.3    0.07       0
  4980.6    0.07       0  4992.0    0.07       0  5397.4   0.045       0
Bank Sta=4980.6,4992
Exp/Cntr=0.3,0.1

Type RM Length L Ch R = 1,91486,420,420,420
BEGIN DESCRIPTION:
Alkali Creek 94.0
END DESCRIPTION:
XS GIS Cut Line= 3
      1347382.92      6953150.02      1348005.00      6953188.00
      1348923.71      6952872.24
#Sta/Elev= 30
  4368.4 2057.97  4380.5 2058.62  4416.4 2055.63  4450.6 2054.87  4490.7 2054.94
  4500.7 2056.48  4553.1 2054.88  4711.1 2053.14  4951.6 2053.87  4981.6 2051.67
  4989.1 2040.68  4994.3 2040.68  5002.0 2032.49  5007.3 2032.83  5017.7 2026.15
  5018.2 2025.65  5029.1 2026.15  5033.2 2028.81  5038.5 2028.19  5069.7 2031.41
  5095.7 2035.88  5245.4 2047.21  5297.3 2049.12  5308.8 2049.72  5376.9 2053.64
  5546.0 2053.72  5676.5 2054.03  5772.5 2054.79  5853.5 2054.64  5963.1 2054.79
#Mann=10,-1,0
  4368.4   0.045       0  4553.1    0.07       0  5017.7    0.07       0
  5029.1    0.07       0  5297.3   0.035       0  5308.8    0.07       0
  5546.0   0.035       0  5676.5    0.07       0  5772.5   0.035       0
  5853.5   0.045       0
Bank Sta=5017.7,5029.1
Exp/Cntr=0.3,0.1

Type RM Length L Ch R = 1,91066,458,458,458
BEGIN DESCRIPTION:
Alkali Creek 93.0
END DESCRIPTION:
XS GIS Cut Line= 3
      1347632.50      6953377.89      1348255.00      6953488.00
      1348728.38      6953536.31
#Sta/Elev= 30
  4367.4 2053.31  4401.1 2053.72  4522.3 2052.05  4568.5 2053.59  4573.5 2052.79
  4627.6 2051.88  4660.8 2052.08  4725.4 2051.30  4766.0 2046.47  4800.1 2045.48
  4844.7 2042.06  4877.7 2038.80  4913.3 2033.01  4918.4 2034.30  4948.8 2030.59
  4979.3 2029.15  4983.5 2025.35  4984.0 2024.85  4995.3 2025.35  4997.0 2028.31
  5021.2 2030.73  5029.7 2033.11  5046.8 2050.53  5051.8 2051.20  5069.9 2049.44
  5110.1 2051.47  5175.3 2051.93  5381.8 2052.23  5451.4 2052.30  5475.4 2052.47
#Mann=9,-1,0
  4367.4    0.07       0  4660.8   0.035       0  4844.7    0.07       0
  4983.5    0.07       0  4995.3    0.07       0  5021.2   0.035       0
  5175.3    0.07       0  5381.8   0.035       0  5451.4    0.07       0
Bank Sta=4983.5,4995.3
Exp/Cntr=0.3,0.1

Type RM Length L Ch R = 1,90608,442,442,442
BEGIN DESCRIPTION:
Alkali Creek 92.0
END DESCRIPTION:
XS GIS Cut Line= 3
      1347829.95      6953913.00      1348105.00      6953888.00
      1348706.67      6953807.58
#Sta/Elev= 30
  4720.1 2051.08  4755.3 2051.90  4865.7 2050.80  4905.9 2051.95  4936.0 2049.77
  4946.1 2048.58  4956.1 2037.80  4966.2 2031.18  4970.2 2024.42  4970.7 2023.92
  4982.2 2024.42  4993.8 2028.01  5006.4 2028.44  5013.1 2027.79  5037.8 2028.00
  5056.8 2029.58  5066.9 2030.55  5077.0 2033.83  5113.5 2036.19  5129.0 2037.48
  5167.8 2039.23  5177.9 2040.94  5208.1 2042.96  5314.1 2047.92  5329.2 2048.43
  5340.1 2050.32  5349.4 2050.70  5486.2 2049.85  5520.9 2051.11  5603.3 2051.19
#Mann=7,-1,0
  4720.1    0.07       0  4970.2    0.07       0  4982.2    0.07       0
  5013.1   0.035       0  5113.5    0.07       0  5129.0   0.035       0
  5314.1    0.07       0
Bank Sta=4970.2,4982.2
Exp/Cntr=0.3,0.1

Type RM Length L Ch R = 1,90166,469,469,469
BEGIN DESCRIPTION:
Alkali Creek 91.0
END DESCRIPTION:
XS GIS Cut Line= 3
      1348030.01      6954362.99      1348405.00      6954188.00
      1348836.88      6953974.68
#Sta/Elev= 30
  4585.7 2049.66  4684.1 2049.35  4802.5 2048.14  4819.8 2046.35  4834.0 2043.27
  4842.7 2043.48  4848.2 2039.80  4865.5 2039.19  4871.0 2036.62  4888.4 2034.59
  4900.2 2031.85  4939.6 2027.47  4955.4 2027.29  4977.4 2025.18  4979.3 2022.53
  4979.8 2022.03  4991.3 2022.53  4996.8 2027.28  5002.3 2027.28  5021.8 2036.96
  5036.0 2037.78  5052.8 2036.80  5066.4 2037.92  5097.7 2041.87  5111.0 2045.29
  5133.3 2047.65  5155.7 2049.06  5203.8 2048.59  5222.6 2049.71  5481.2 2050.34
#Mann=5,-1,0
  4585.7    0.07       0  4684.1   0.035       0  4979.3   0.035       0
  4991.3   0.035       0  5203.8    0.07       0
Bank Sta=4979.3,4991.3
Exp/Cntr=0.3,0.1

Type RM Length L Ch R = 1,89697,422,422,422
BEGIN DESCRIPTION:
Alkali Creek 90.0
END DESCRIPTION:
XS GIS Cut Line= 3
      1348229.96      6954563.00      1348655.00      6954538.00
      1349145.05      6954391.34
#Sta/Elev= 30
  4573.7 2048.05  4608.8 2048.45  4628.8 2047.33  4678.9 2046.66  4769.1 2041.13
  4829.2 2038.37  4868.4 2035.57  4899.3 2033.62  4909.3 2033.70  4920.8 2031.71
  4959.4 2026.47  4969.4 2026.67  4979.4 2024.83  4990.9 2021.50  4991.4 2021.00
  5003.0 2021.50  5009.9 2024.70  5016.0 2026.46  5021.2 2029.61  5030.8 2033.85
  5041.2 2036.63  5049.1 2042.93  5054.3 2041.34  5062.1 2044.49  5072.5 2045.75
  5087.4 2045.61  5135.2 2048.13  5186.7 2047.52  5323.1 2048.42  5511.0 2048.52
#Mann=5,-1,0
  4573.7    0.07       0  4868.4   0.035       0  4920.8    0.07       0
  4990.9    0.07       0  5003.0    0.07       0
Bank Sta=4990.9,5003
Exp/Cntr=0.3,0.1

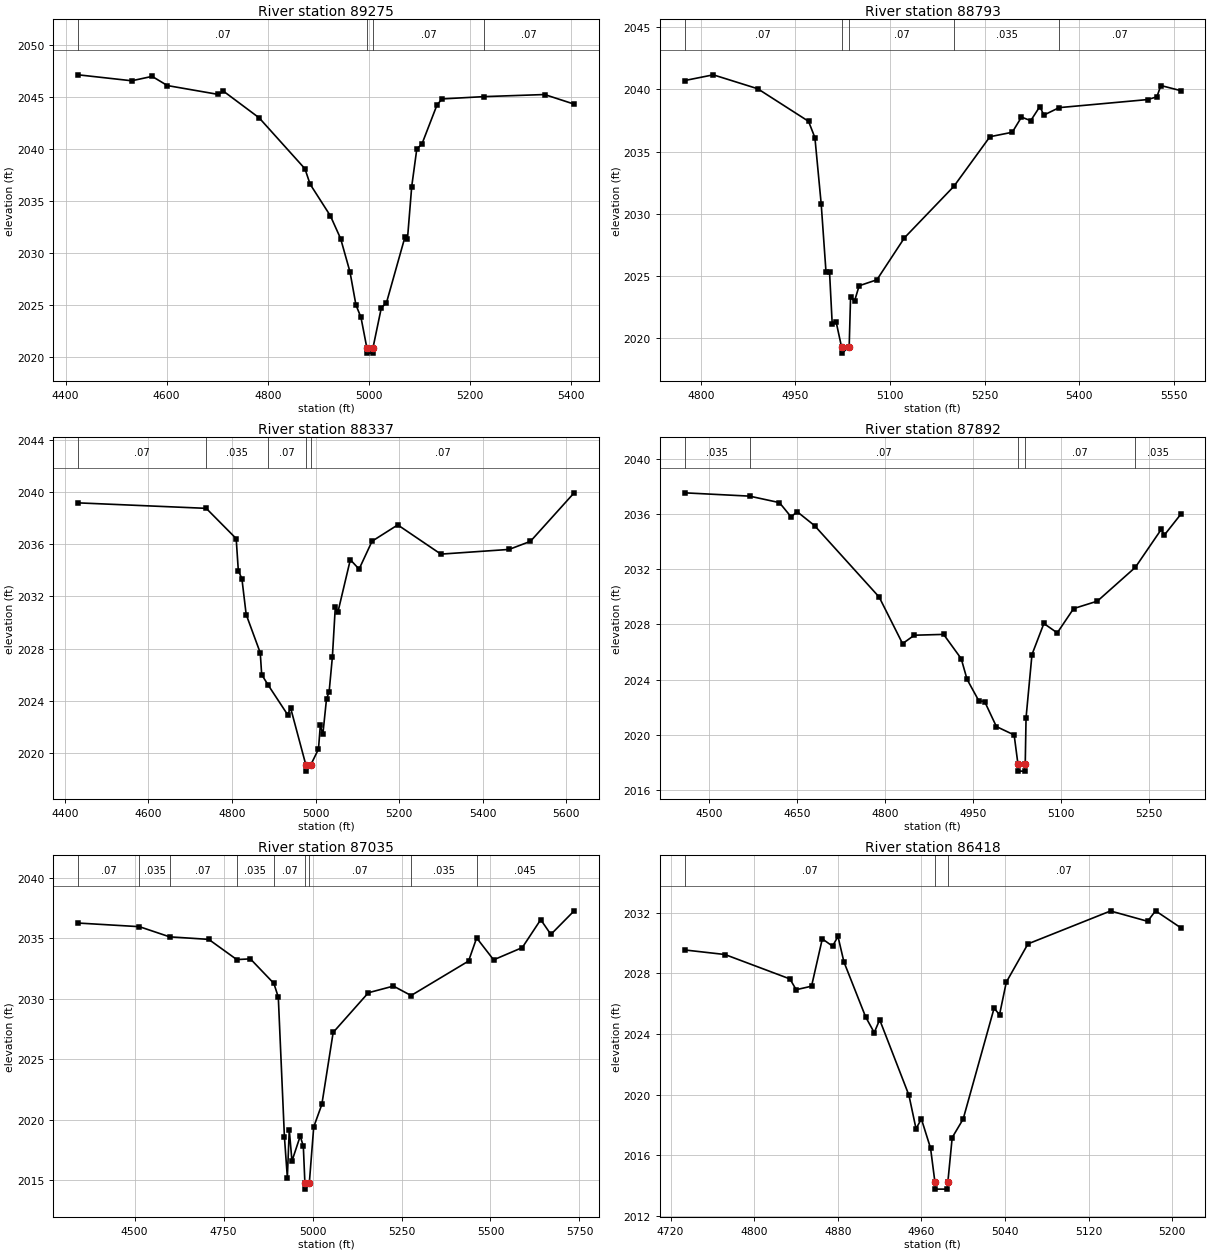
Type RM Length L Ch R = 1,89275,482,482,482
BEGIN DESCRIPTION:
Alkali Creek 89.0
END DESCRIPTION:
XS GIS Cut Line= 3
      1348079.96      6954812.99      1348655.00      6954888.00
      1349055.60      6954858.50
#Sta/Elev= 30
  4424.9 2047.10  4530.8 2046.53  4571.2 2046.95  4601.4 2046.07  4702.3 2045.22
  4712.4 2045.53  4782.9 2042.98  4873.7 2038.09  4883.8 2036.62  4924.1 2033.57
  4944.3 2031.39  4962.8 2028.20  4974.6 2025.03  4984.6 2023.83  4996.2 2020.91
  4996.7 2020.41  5007.8 2020.41  5008.3 2020.91  5024.9 2024.77  5034.9 2025.22
  5071.4 2031.51  5076.5 2031.31  5085.0 2036.39  5095.1 2040.00  5105.1 2040.45
  5135.2 2044.23  5145.2 2044.79  5228.0 2045.01  5348.0 2045.21  5406.5 2044.29
#Mann=4,-1,0
  4424.9    0.07       0  4996.2   0.035       0  5008.3    0.07       0
  5228.0    0.07       0
Bank Sta=4996.2,5008.3
Exp/Cntr=0.3,0.1

Type RM Length L Ch R = 1,88793,456,456,456
BEGIN DESCRIPTION:
Alkali Creek 88.0
END DESCRIPTION:
XS GIS Cut Line= 3
      1348330.00      6955363.00      1348555.00      6955338.00
      1349002.11      6955001.96
#Sta/Elev= 30
  4774.6 2040.71  4819.9 2041.17  4890.3 2040.05  4970.8 2037.43  4980.9 2036.12
  4990.9 2030.77  4998.5 2025.30  5004.1 2025.30  5008.3 2021.15  5014.5 2021.30
  5023.1 2019.28  5023.6 2018.78  5035.2 2019.28  5037.4 2023.26  5043.7 2022.97
  5051.0 2024.20  5079.1 2024.68  5122.8 2028.06  5201.1 2032.20  5258.2 2036.19
  5293.6 2036.55  5308.2 2037.77  5322.8 2037.48  5337.3 2038.62  5343.6 2037.93
  5367.8 2038.53  5508.1 2039.18  5522.7 2039.40  5529.0 2040.31  5560.3 2039.90
#Mann=5,-1,0
  4774.6    0.07       0  5023.1    0.07       0  5035.2    0.07       0
  5201.1   0.035       0  5367.8    0.07       0
Bank Sta=5023.1,5035.2
Exp/Cntr=0.3,0.1

Type RM Length L Ch R = 1,88337,445,445,445
BEGIN DESCRIPTION:
Alkali Creek 87.0
END DESCRIPTION:
XS GIS Cut Line= 5
      1348430.03      6955613.00      1348862.94      6955531.77
      1348955.00      6955438.00      1349053.91      6955370.31
      1349537.07      6955262.84
#Sta/Elev= 30
  4432.2 2039.17  4738.5 2038.75  4810.2 2036.43  4815.3 2033.98  4823.9 2033.35
  4834.1 2030.61  4867.8 2027.67  4871.2 2026.00  4886.3 2025.22  4933.4 2022.92
  4940.4 2023.45  4976.7 2019.10  4977.2 2018.60  4989.0 2019.10  5007.1 2020.29
  5011.5 2022.10  5017.6 2021.43  5026.4 2024.16  5032.5 2024.65  5040.4 2027.36
  5047.4 2031.20  5053.5 2030.78  5083.3 2034.81  5104.3 2034.09  5135.3 2036.23
  5196.8 2037.48  5300.0 2035.24  5463.1 2035.60  5514.3 2036.22  5618.9 2039.94
#Mann=5,-1,0
  4432.2    0.07       0  4738.5   0.035       0  4886.3    0.07       0
  4976.7    0.07       0  4989.0    0.07       0
Bank Sta=4976.7,4989
Exp/Cntr=0.3,0.1

Type RM Length L Ch R = 1,87892,857,857,857
BEGIN DESCRIPTION:
Alkali Creek 86.0
END DESCRIPTION:
XS GIS Cut Line= 3
      1348613.40      6955783.50      1349155.00      6955788.00
      1349455.05      6955737.99
#Sta/Elev= 30
  4457.8 2037.53  4568.5 2037.29  4619.4 2036.82  4639.4 2035.78  4649.4 2036.17
  4679.4 2035.15  4789.4 2029.98  4829.4 2026.60  4849.4 2027.21  4899.4 2027.27
  4929.4 2025.51  4939.4 2024.01  4959.4 2022.46  4969.4 2022.40  4989.4 2020.59
  5019.7 2019.98  5026.2 2017.86  5026.7 2017.36  5038.1 2017.36  5038.6 2017.86
  5040.0 2021.23  5050.1 2025.81  5070.4 2028.06  5093.2 2027.38  5121.1 2029.14
  5161.6 2029.68  5226.4 2032.13  5270.6 2034.88  5275.7 2034.46  5303.6 2035.96
#Mann=5,-1,0
  4457.8   0.035       0  4568.5    0.07       0  5026.2    0.07       0
  5038.6    0.07       0  5226.4   0.035       0
Bank Sta=5026.2,5038.6
Exp/Cntr=0.3,0.1

Type RM Length L Ch R = 1,87035,617,617,617
BEGIN DESCRIPTION:
Alkali Creek 85.0
END DESCRIPTION:
XS GIS Cut Line= 3
      1348329.97      6956012.99      1348955.00      6956238.00
      1349680.03      6956163.00
#Sta/Elev= 30
  4341.8 2036.25  4513.7 2035.95  4598.7 2035.11  4708.5 2034.90  4787.3 2033.23
  4825.4 2033.29  4891.5 2031.26  4903.9 2030.12  4921.1 2018.57  4929.3 2015.22
  4934.7 2019.15  4942.3 2016.58  4965.4 2018.64  4974.2 2017.81  4978.6 2014.76
  4979.1 2014.26  4991.0 2014.76  5003.4 2019.40  5026.2 2021.26  5058.0 2027.21
  5156.9 2030.49  5227.3 2031.04  5276.9 2030.26  5438.4 2033.11  5461.1 2035.02
  5508.8 2033.21  5589.2 2034.22  5641.1 2036.53  5669.6 2035.31  5735.0 2037.26
#Mann=9,-1,0
  4341.8    0.07       0  4513.7   0.035       0  4598.7    0.07       0
  4787.3   0.035       0  4891.5    0.07       0  4978.6    0.07       0
  4991.0    0.07       0  5276.9   0.035       0  5461.1   0.045       0
Bank Sta=4978.6,4991
Exp/Cntr=0.3,0.1

Type RM Length L Ch R = 1,86418,463,463,463
BEGIN DESCRIPTION:
Alkali Creek 84.0
END DESCRIPTION:
XS GIS Cut Line= 3
      1348812.03      6956430.80      1348903.17      6956769.32
      1348999.51      6956847.43
#Sta/Elev= 30
  4733.5 2029.55  4772.0 2029.25  4834.2 2027.64  4840.2 2026.93  4854.9 2027.16
  4865.2 2030.28  4875.0 2029.80  4880.2 2030.44  4885.9 2028.76  4906.7 2025.13
  4914.9 2024.10  4920.1 2024.95  4948.1 2019.97  4954.9 2017.76  4960.0 2018.41
  4968.8 2016.48  4972.9 2014.28  4973.4 2013.78  4984.9 2013.78  4985.4 2014.28
  4989.5 2017.18  5000.0 2018.40  5029.6 2025.71  5034.8 2025.28  5041.3 2027.43
  5062.0 2029.95  5141.0 2032.12  5176.5 2031.44  5184.1 2032.13  5208.1 2031.02
#Mann=3,-1,0
  4733.5    0.07       0  4972.9    0.07       0  4985.4    0.07       0
Bank Sta=4972.9,4985.4
Exp/Cntr=0.3,0.1