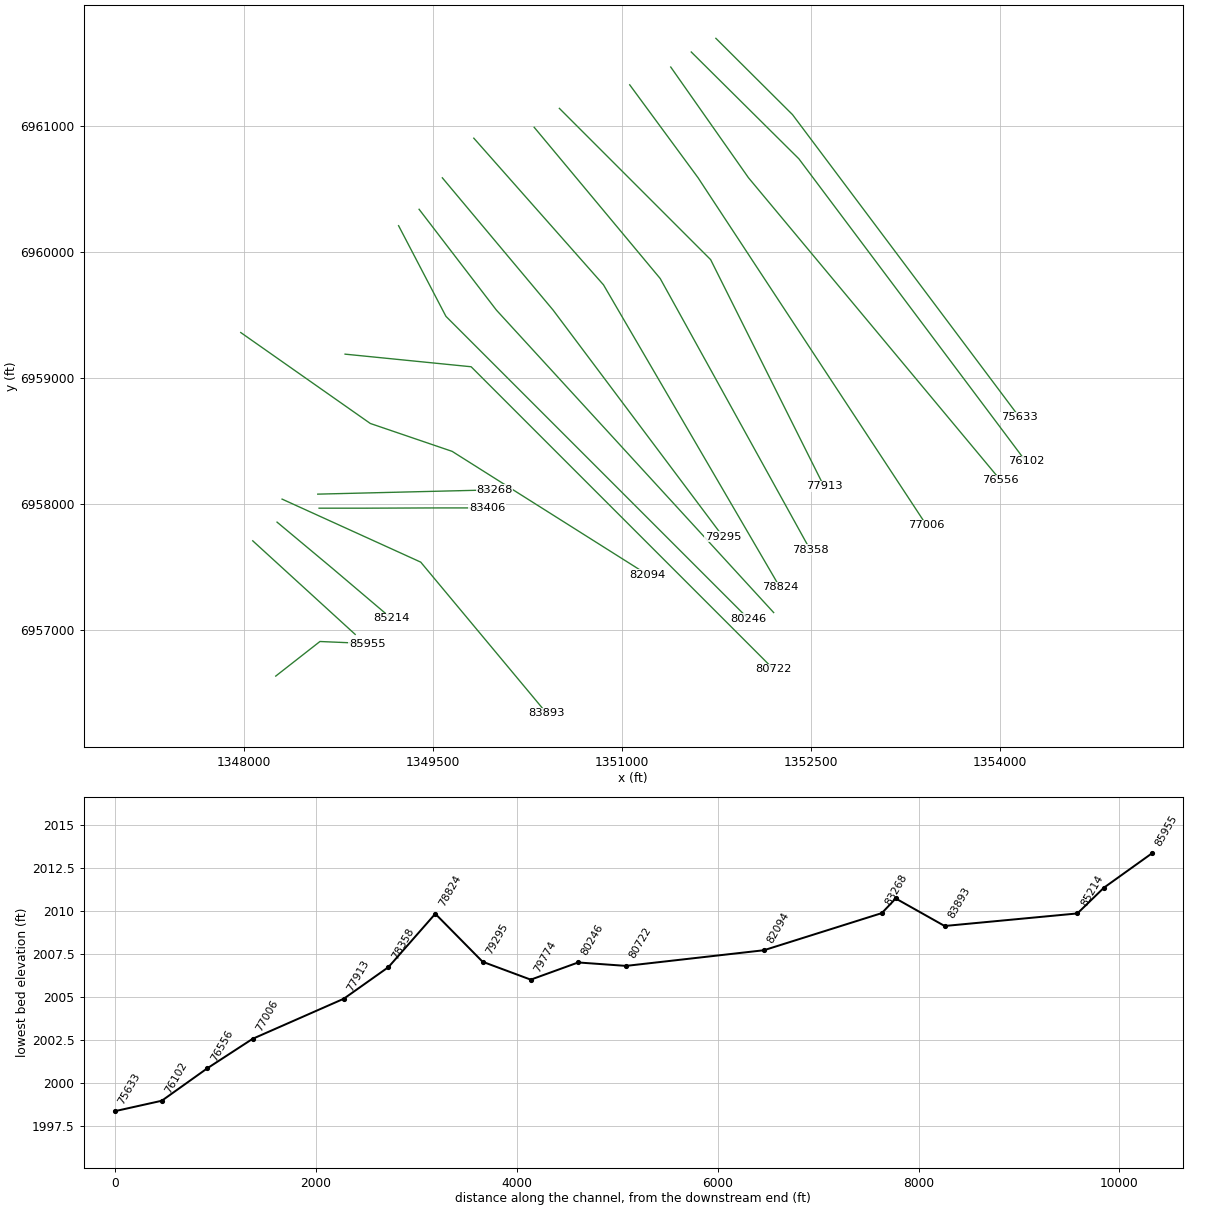
HEC-RAS study Alkali Creek.prj: Alkali Creek Base Level Engineering

--- Alkali Creek.g01 (geometry) --- (continued)

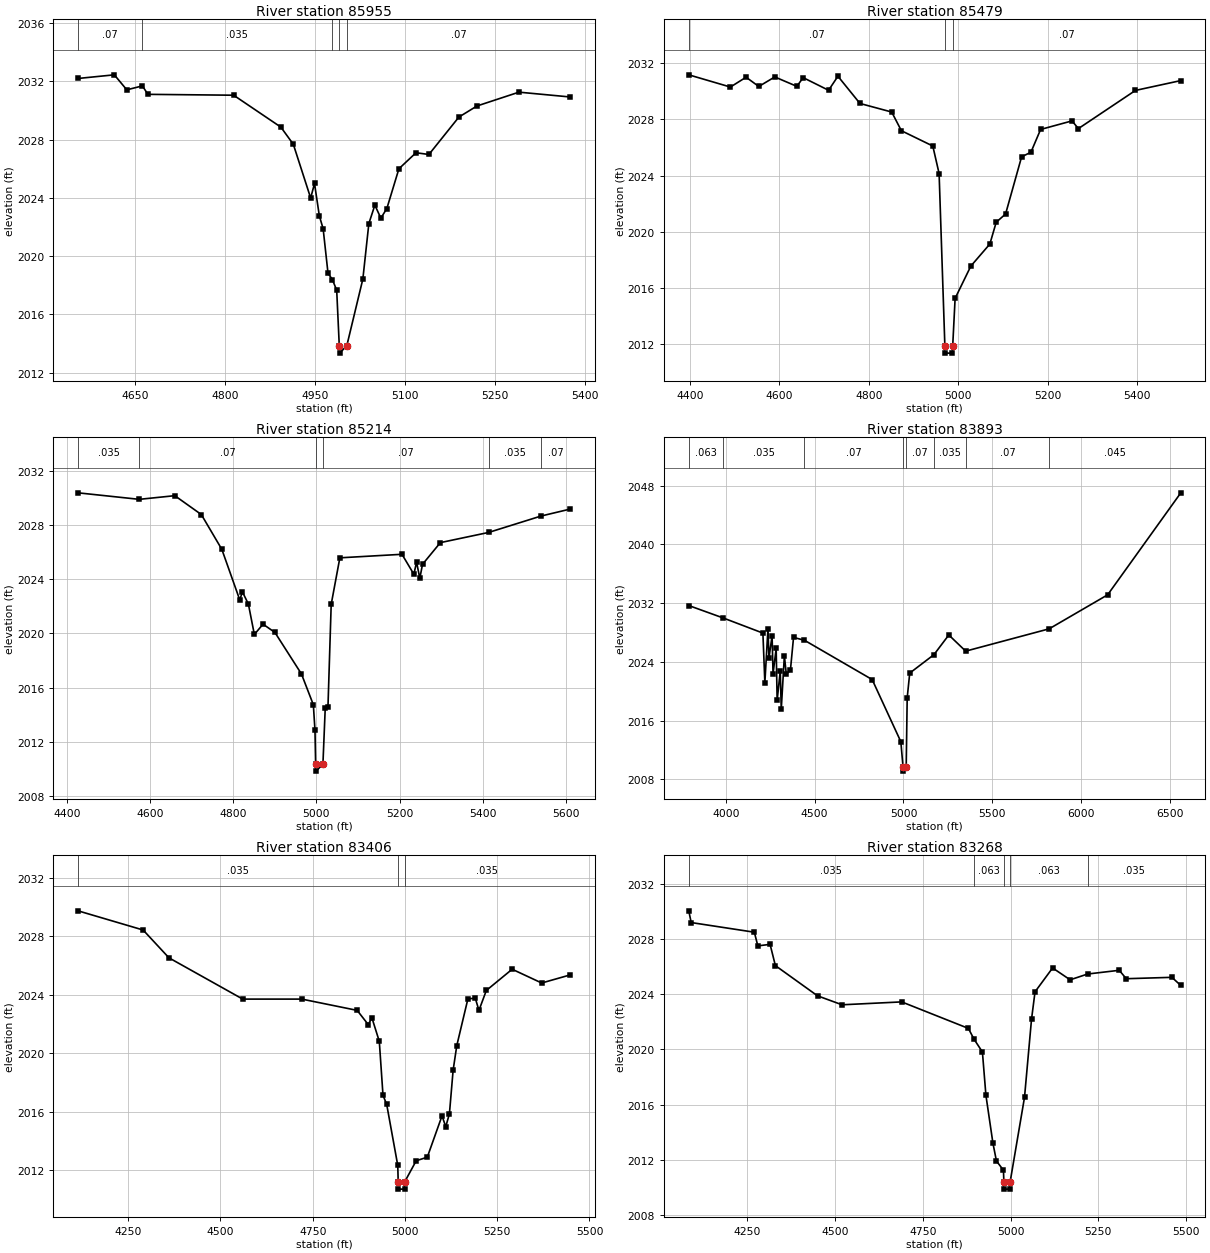
Type RM Length L Ch R = 1,85955,476,476,476
BEGIN DESCRIPTION:
Alkali Creek 83.1
END DESCRIPTION:
XS GIS Cut Line= 3
      1348254.74      6956633.91      1348605.43      6956908.18
      1348980.09      6956892.22
#Sta/Elev= 30
  4554.8 2032.20  4615.3 2032.45  4636.1 2031.42  4662.1 2031.69  4671.3 2031.11
  4814.2 2031.05  4892.9 2028.86  4913.7 2027.68  4942.6 2023.99  4949.0 2024.99
  4957.1 2022.76  4963.4 2021.88  4971.5 2018.83  4978.8 2018.39  4986.0 2017.66
  4990.3 2013.84  4990.8 2013.34  5002.8 2013.84  5029.6 2018.43  5039.6 2022.24
  5049.6 2023.50  5059.6 2022.61  5069.6 2023.27  5089.7 2026.00  5118.2 2027.10
  5139.7 2026.98  5189.7 2029.55  5219.8 2030.31  5289.8 2031.26  5375.0 2030.93
#Mann=5,-1,0
  4554.8    0.07       0  4662.1   0.035       0  4978.8    0.07       0
  4990.3    0.07       0  5002.8    0.07       0
Bank Sta=4990.3,5002.8
Exp/Cntr=0.3,0.1

Type RM Length L Ch R = 1,85479,265,265,265
BEGIN DESCRIPTION:
Alkali Creek 83.2
END DESCRIPTION:
XS GIS Cut Line= 2
      1348072.41      6957706.84      1348884.95      6956964.63
#Sta/Elev= 30
  4397.5 2031.17  4490.6 2030.30  4525.7 2031.00  4554.1 2030.34  4589.9 2031.02
  4639.2 2030.35  4653.4 2030.97  4710.2 2030.07  4731.1 2031.07  4780.4 2029.13
  4851.4 2028.52  4873.0 2027.19  4943.3 2026.10  4957.4 2024.14  4970.3 2011.85
  4970.8 2011.35  4987.3 2011.35  4987.8 2011.85  4993.2 2015.25  5028.4 2017.55
  5070.9 2019.12  5085.1 2020.67  5106.1 2021.26  5141.9 2025.33  5162.8 2025.66
  5184.4 2027.28  5254.7 2027.89  5268.9 2027.34  5396.6 2030.06  5498.0 2030.76
#Mann=3,-1,0
  4397.5    0.07       0  4970.3    0.07       0  4987.8    0.07       0
Bank Sta=4970.3,4987.8
Exp/Cntr=0.3,0.1

Type RM Length L Ch R = 1,85214,1321,1321,1321
BEGIN DESCRIPTION:
Alkali Creek 83.0
END DESCRIPTION:
XS GIS Cut Line= 3
      1348265.13      6957855.27      1348705.00      6957488.00
      1349170.23      6957093.22
#Sta/Elev= 30
  4426.7 2030.36  4574.0 2029.88  4659.4 2030.15  4723.2 2028.76  4772.6 2026.19
  4815.6 2022.47  4822.1 2023.06  4836.4 2022.16  4850.7 2019.92  4871.6 2020.68
  4900.2 2020.07  4964.0 2017.01  4992.6 2014.74  4996.5 2012.86  4998.1 2010.35
  4998.6 2009.85  5015.6 2010.35  5021.2 2014.52  5027.7 2014.54  5035.5 2022.14
  5056.3 2025.57  5205.7 2025.83  5234.3 2024.36  5240.8 2025.25  5248.6 2024.06
  5255.1 2025.09  5298.0 2026.69  5414.0 2027.44  5540.2 2028.65  5609.9 2029.16
#Mann=6,-1,0
  4426.7   0.035       0  4574.0    0.07       0  4998.1    0.07       0
  5015.6    0.07       0  5414.0   0.035       0  5540.2    0.07       0
Bank Sta=4998.1,5015.6
Exp/Cntr=0.3,0.1

Type RM Length L Ch R = 1,83893,487,487,487
BEGIN DESCRIPTION:
Alkali Creek 82.0
END DESCRIPTION:
XS GIS Cut Line= 3
      1348304.99      6958038.00      1349405.00      6957538.00
      1350405.02      6956337.97
#Sta/Elev= 30
  3791.2 2031.67  3985.9 2029.97  4208.6 2027.92  4219.6 2021.16  4237.2 2028.54
  4242.7 2024.50  4260.3 2027.58  4265.7 2022.38  4283.3 2025.82  4288.8 2018.76
  4306.4 2022.77  4311.9 2017.52  4329.5 2024.84  4340.4 2022.31  4363.5 2022.86
  4381.1 2027.33  4442.6 2026.94  4823.8 2021.59  4985.2 2013.13  4997.9 2009.62
  4998.4 2009.12  5015.4 2009.62  5021.0 2019.09  5035.3 2022.47  5171.6 2024.98
  5255.3 2027.66  5350.4 2025.46  5820.4 2028.50  6149.6 2033.13  6561.6 2047.02
#Mann=8,-1,0
  3791.2   0.063       0  3985.9   0.035       0  4442.6    0.07       0
  4997.9    0.07       0  5015.4    0.07       0  5171.6   0.035       0
  5350.4    0.07       0  5820.4   0.045       0
Bank Sta=4997.9,5015.4
Exp/Cntr=0.3,0.1

Type RM Length L Ch R = 1,83406,138,138,138
BEGIN DESCRIPTION:
Alkali Creek 81.0
END DESCRIPTION:
XS GIS Cut Line= 4
      1348598.56      6957965.98      1348973.61      6957965.98
      1349484.46      6957967.85      1349931.86      6957968.14
#Sta/Elev= 30
  4114.1 2029.73  4290.5 2028.42  4360.5 2026.52  4560.5 2023.70  4720.5 2023.70
  4870.5 2022.93  4900.5 2021.96  4910.5 2022.42  4930.5 2020.81  4940.5 2017.13
  4950.5 2016.51  4980.5 2012.34  4981.7 2011.22  4982.2 2010.72  4998.9 2010.72
  4999.4 2011.22  5030.5 2012.66  5060.5 2012.90  5100.5 2015.73  5110.5 2014.98
  5120.5 2015.87  5130.5 2018.84  5140.5 2020.53  5170.5 2023.71  5190.5 2023.77
  5200.5 2022.93  5220.5 2024.29  5290.5 2025.74  5370.5 2024.80  5447.4 2025.35
#Mann=3,-1,0
  4114.1   0.035       0  4981.7   0.035       0  4999.4   0.035       0
Bank Sta=4981.7,4999.4
Exp/Cntr=0.3,0.1

Type RM Length L Ch R = 1,83268,1174,1174,1174
BEGIN DESCRIPTION:
Alkali Creek 80.5
END DESCRIPTION:
XS GIS Cut Line= 2
      1348588.15      6958077.38      1349990.43      6958111.43
#Sta/Elev= 30
  4082.8 2030.04  4089.7 2029.19  4269.7 2028.49  4279.7 2027.50  4314.6 2027.61
  4329.7 2026.07  4449.8 2023.88  4519.8 2023.23  4689.8 2023.44  4879.9 2021.52
  4895.7 2020.75  4919.9 2019.81  4929.9 2016.67  4949.9 2013.20  4959.9 2011.91
  4979.9 2011.24  4981.1 2010.37  4981.6 2009.87  4998.3 2009.87  4998.8 2010.37
  5039.9 2016.52  5059.9 2022.18  5069.9 2024.17  5120.0 2025.90  5170.0 2025.04
  5219.8 2025.46  5310.0 2025.73  5330.0 2025.12  5460.1 2025.22  5485.5 2024.63
#Mann=5,-1,0
  4082.8   0.035       0  4895.7   0.063       0  4981.1   0.063       0
  4998.8   0.063       0  5219.8   0.035       0
Bank Sta=4981.1,4998.8
Exp/Cntr=0.3,0.1

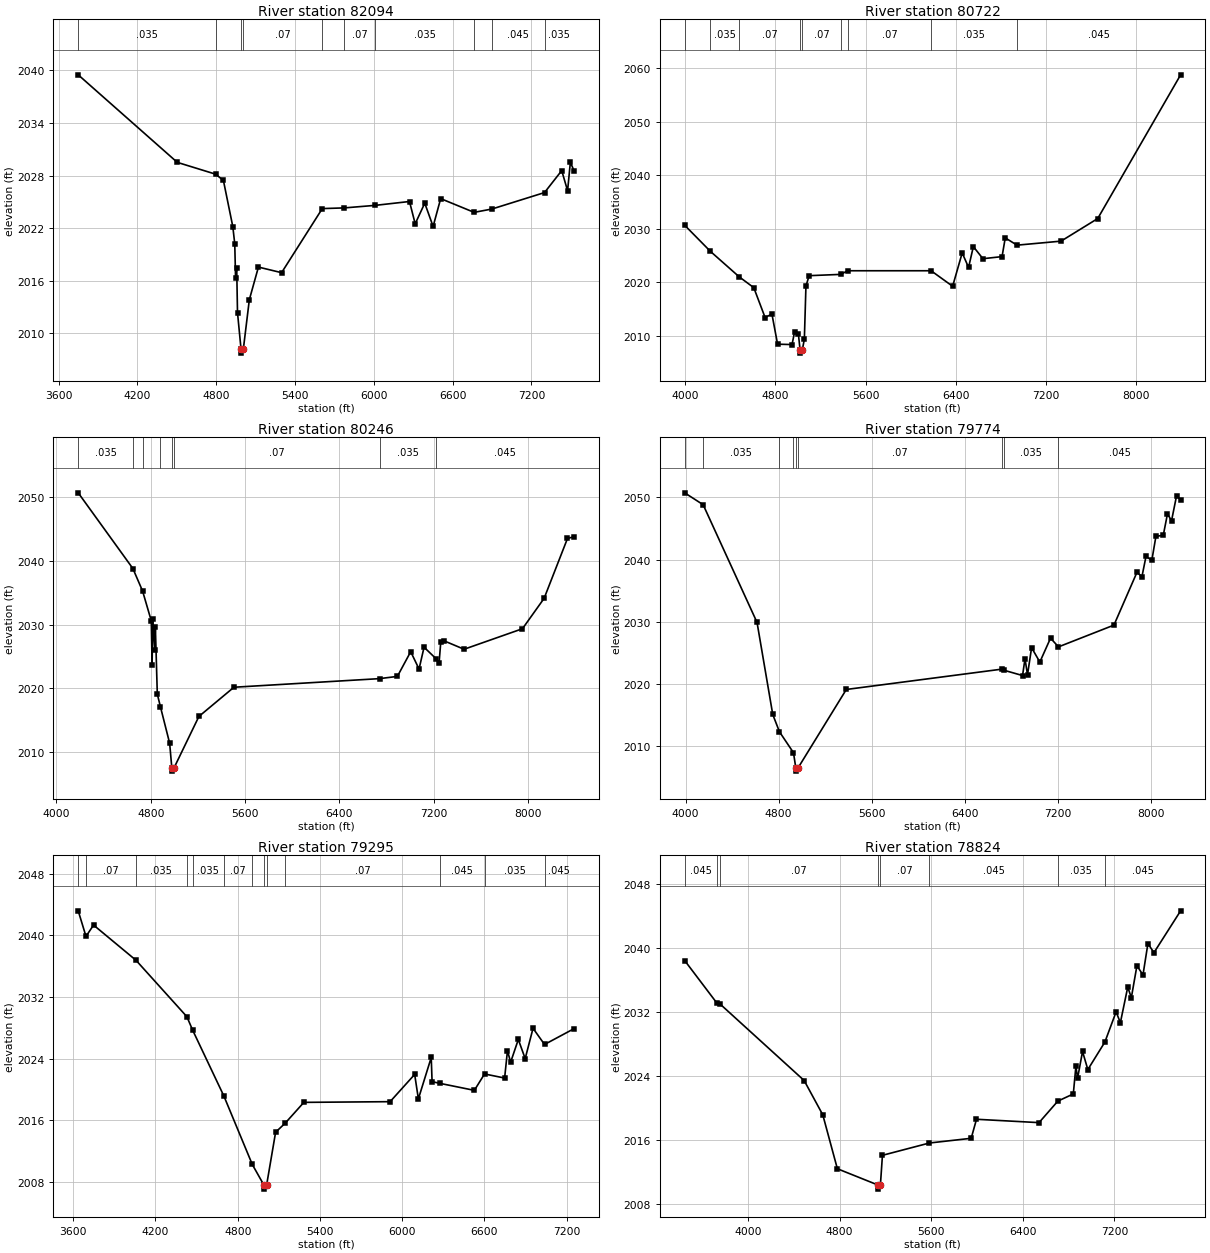
Type RM Length L Ch R = 1,82094,1372,1372,1372
BEGIN DESCRIPTION:
Alkali Creek 80.0
END DESCRIPTION:
XS GIS Cut Line= 4
      1347977.19      6959359.43      1349005.00      6958638.00
      1349654.24      6958416.75      1351204.98      6957438.02
#Sta/Elev= 30
  3749.9 2039.50  4504.1 2029.50  4796.3 2028.15  4855.3 2027.43  4926.8 2022.16
  4941.6 2020.19  4947.7 2016.33  4956.4 2017.46  4962.5 2012.34  4989.1 2008.21
  4989.6 2007.71  5007.3 2008.21  5052.7 2013.82  5121.8 2017.54  5298.1 2016.90
  5608.0 2024.22  5776.7 2024.30  6011.5 2024.59  6271.9 2025.03  6315.1 2022.48
  6388.0 2024.84  6451.6 2022.18  6509.2 2025.36  6763.9 2023.79  6899.0 2024.17
  7299.7 2026.05  7430.7 2028.56  7475.3 2026.26  7496.5 2029.52  7525.3 2028.50
#Mann=10,-1,0
  3749.9   0.035       0  4796.3    0.07       0  4989.1    0.07       0
  5007.3    0.07       0  5608.0   0.035       0  5776.7    0.07       0
  6011.5   0.035       0  6763.9    0.07       0  6899.0   0.045       0
  7299.7   0.035       0
Bank Sta=4989.1,5007.3
Exp/Cntr=0.3,0.1

Type RM Length L Ch R = 1,80722,476,476,476
BEGIN DESCRIPTION:
Alkali Creek 79.0
END DESCRIPTION:
XS GIS Cut Line= 3
      1348805.01      6959188.00      1349805.00      6959088.00
      1352205.01      6956687.99
#Sta/Elev= 30
  3994.9 2030.69  4223.6 2025.80  4478.8 2021.05  4607.9 2019.03  4708.4 2013.44
  4768.7 2014.11  4819.0 2008.47  4947.1 2008.40  4969.7 2010.75  5003.4 2010.39
  5019.1 2007.30  5019.6 2006.80  5037.3 2007.30  5056.4 2009.39  5070.6 2019.34
  5098.9 2021.27  5379.4 2021.51  5440.4 2022.19  6180.6 2022.19  6371.7 2019.29
  6456.5 2025.52  6513.1 2022.81  6555.5 2026.70  6640.4 2024.44  6810.1 2024.83
  6838.4 2028.33  6943.0 2026.97  7333.3 2027.72  7658.6 2031.94  8394.0 2058.79
#Mann=9,-1,0
  3994.9    0.07       0  4223.6   0.035       0  4478.8    0.07       0
  5019.1    0.07       0  5037.3    0.07       0  5379.4   0.035       0
  5440.4    0.07       0  6180.6   0.035       0  6943.0   0.045       0
Bank Sta=5019.1,5037.3
Exp/Cntr=0.3,0.1

Type RM Length L Ch R = 1,80246,472,472,472
BEGIN DESCRIPTION:
Alkali Creek 78.0
END DESCRIPTION:
XS GIS Cut Line= 3
      1349229.31      6960207.14      1349605.00      6959488.00
      1352005.02      6957087.98
#Sta/Elev= 30
  4184.4 2050.66  4648.1 2038.78  4730.3 2035.25  4804.0 2030.58  4810.9 2023.72
  4816.5 2030.84  4833.0 2026.08  4838.6 2029.59  4855.1 2019.08  4881.7 2017.09
  4959.8 2011.37  4978.2 2007.50  4978.7 2007.00  4996.8 2007.50  5207.9 2015.58
  5504.9 2020.16  6739.4 2021.51  6890.8 2021.86  7003.9 2025.74  7074.6 2023.01
  7117.1 2026.44  7222.0 2024.58  7244.4 2023.95  7258.5 2027.18  7286.8 2027.44
  7456.5 2026.12  7951.5 2029.34  8135.3 2034.11  8333.3 2043.50  8389.9 2043.78
#Mann=8,-1,0
  4184.4   0.035       0  4648.1    0.07       0  4730.3   0.035       0
  4881.7    0.07       0  4978.2    0.07       0  4996.8    0.07       0
  6739.4   0.035       0  7222.0   0.045       0
Bank Sta=4978.2,4996.8
Exp/Cntr=0.3,0.1

Type RM Length L Ch R = 1,79774,479,479,479
BEGIN DESCRIPTION:
Alkali Creek 77.0
END DESCRIPTION:
XS GIS Cut Line= 3
      1349392.07      6960337.34      1350005.00      6959538.00
      1352204.97      6957138.04
#Sta/Elev= 30
  3992.6 2050.75  4151.3 2048.84  4614.6 2029.91  4749.7 2015.11  4807.2 2012.33
  4927.9 2008.96  4947.9 2006.50  4948.4 2006.00  4966.6 2006.50  5381.9 2019.13
  6719.4 2022.40  6735.7 2022.23  6896.9 2021.37  6917.9 2024.07  6939.5 2021.49
  6974.6 2025.85  7045.5 2023.54  7137.4 2027.38  7205.7 2025.98  7682.5 2029.48
  7880.4 2037.97  7923.0 2037.26  7958.1 2040.53  8008.1 2039.89  8043.2 2043.74
  8106.7 2043.94  8142.5 2047.36  8177.6 2046.27  8220.2 2050.22  8255.6 2049.63
#Mann=9,-1,0
  3992.6    0.07       0  4151.3   0.035       0  4807.2    0.16       0
  4927.9    0.07       0  4947.9    0.07       0  4966.6    0.07       0
  6719.4   0.045       0  6735.7   0.035       0  7205.7   0.045       0
Bank Sta=4947.9,4966.6
Exp/Cntr=0.3,0.1

Type RM Length L Ch R = 1,79295,471,471,471
BEGIN DESCRIPTION:
Alkali Creek 76.0
END DESCRIPTION:
XS GIS Cut Line= 3
      1349576.52      6960586.92      1350455.00      6959538.00
      1351805.00      6957738.00
#Sta/Elev= 30
  3636.4 2043.19  3693.1 2039.87  3748.4 2041.34  4057.8 2036.77  4429.1 2029.44
  4471.6 2027.68  4699.0 2019.14  4906.5 2010.24  4992.0 2007.54  4992.5 2007.04
  5010.7 2007.54  5076.5 2014.43  5147.1 2015.62  5282.7 2018.31  5911.9 2018.40
  6091.1 2021.94  6118.1 2018.76  6211.9 2024.14  6218.1 2021.00  6274.8 2020.78
  6526.5 2019.87  6600.8 2022.00  6747.3 2021.47  6768.1 2025.03  6791.1 2023.52
  6847.3 2026.48  6897.3 2023.99  6954.6 2027.93  7038.5 2025.83  7254.6 2027.89
#Mann=13,-1,0
  3636.4   0.045       0  3693.1    0.07       0  4057.8   0.035       0
  4429.1    0.07       0  4471.6   0.035       0  4699.0    0.07       0
  4906.5    0.16       0  4992.0    0.07       0  5010.7    0.16       0
  5147.1    0.07       0  6274.8   0.045       0  6600.8   0.035       0
  7038.5   0.045       0
Bank Sta=4992,5010.7
Exp/Cntr=0.3,0.1

Type RM Length L Ch R = 1,78824,466,466,466
BEGIN DESCRIPTION:
Alkali Creek 75.0
END DESCRIPTION:
XS GIS Cut Line= 3
      1349826.11      6960901.56      1350855.00      6959738.00
      1352255.00      6957338.01
#Sta/Elev= 30
  3446.9 2038.43  3727.5 2033.12  3751.3 2033.05  4490.3 2023.42  4653.1 2019.13
  4780.5 2012.38  5137.5 2010.33  5138.0 2009.83  5156.3 2010.33  5174.2 2014.06
  5584.1 2015.60  5949.4 2016.19  5995.7 2018.57  6541.9 2018.15  6706.1 2020.84
  6841.3 2021.74  6864.0 2025.21  6878.5 2023.69  6921.9 2027.05  6968.2 2024.79
  7117.0 2028.23  7215.1 2032.01  7252.3 2030.65  7316.8 2035.11  7348.2 2033.79
  7397.0 2037.78  7449.9 2036.63  7492.9 2040.55  7545.8 2039.42  7778.6 2044.65
#Mann=8,-1,0
  3446.9   0.045       0  3727.5   0.035       0  3751.3    0.07       0
  5137.5    0.07       0  5156.3    0.07       0  5584.1   0.045       0
  6706.1   0.035       0  7117.0   0.045       0
Bank Sta=5137.5,5156.3
Exp/Cntr=0.3,0.1

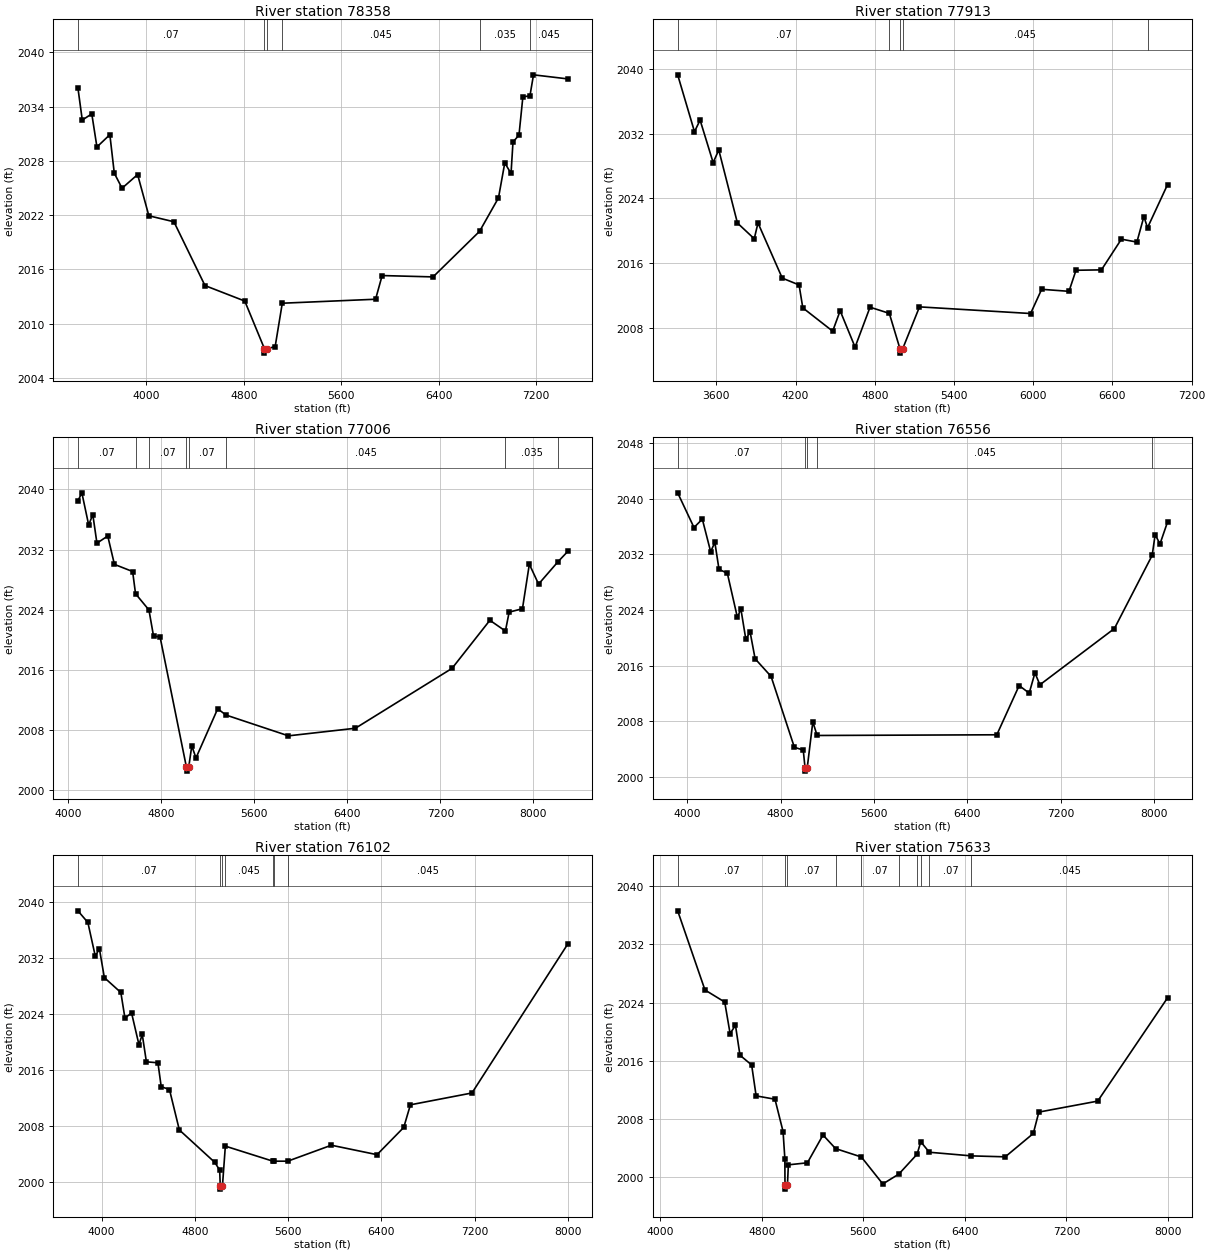
Type RM Length L Ch R = 1,78358,445,445,445
BEGIN DESCRIPTION:
Alkali Creek 74.0
END DESCRIPTION:
XS GIS Cut Line= 3
      1350305.01      6960987.99      1351305.00      6959788.00
      1352495.40      6957635.47
#Sta/Elev= 30
  3437.6 2036.07  3473.4 2032.51  3551.5 2033.19  3593.8 2029.53  3699.9 2030.89
  3736.3 2026.63  3800.1 2024.97  3927.7 2026.48  4020.1 2021.92  4225.8 2021.26
  4480.9 2014.20  4807.6 2012.49  4968.8 2007.23  4969.3 2006.73  4987.6 2007.23
  5056.9 2007.44  5115.6 2012.25  5881.5 2012.69  5935.4 2015.31  6353.4 2015.16
  6735.3 2020.20  6890.6 2023.90  6942.3 2027.77  6993.7 2026.60  7009.7 2030.07
  7059.0 2030.85  7090.8 2035.06  7149.1 2035.20  7178.1 2037.51  7459.4 2037.06
#Mann=6,-1,0
  3437.6    0.07       0  4968.8    0.07       0  4987.6    0.07       0
  5115.6   0.045       0  6735.3   0.035       0  7149.1   0.045       0
Bank Sta=4968.8,4987.6
Exp/Cntr=0.3,0.1

Type RM Length L Ch R = 1,77913,907,907,907
BEGIN DESCRIPTION:
Alkali Creek 73.0
END DESCRIPTION:
XS GIS Cut Line= 3
      1350504.97      6961138.03      1351705.00      6959938.00
      1352605.02      6958137.97
#Sta/Elev= 30
  3307.1 2039.25  3434.4 2032.23  3476.9 2033.66  3575.8 2028.41  3618.3 2029.98
  3759.7 2020.95  3887.0 2019.01  3915.3 2020.96  4099.1 2014.15  4226.4 2013.31
  4254.7 2010.48  4480.9 2007.60  4537.5 2010.12  4650.6 2005.63  4763.8 2010.56
  4909.8 2009.80  4991.2 2005.39  4991.7 2004.89  5010.1 2005.39  5138.4 2010.60
  5979.7 2009.78  6063.5 2012.77  6270.4 2012.52  6323.5 2015.12  6516.3 2015.17
  6667.3 2018.96  6784.7 2018.60  6837.8 2021.75  6865.2 2020.37  7016.7 2025.69
#Mann=5,-1,0
  3307.1    0.07       0  4909.8   0.045       0  4991.2   0.045       0
  5010.1   0.045       0  6865.2   0.035       0
Bank Sta=4991.2,5010.1
Exp/Cntr=0.3,0.1

Type RM Length L Ch R = 1,77006,450,450,450
BEGIN DESCRIPTION:
Alkali Creek 72.0
END DESCRIPTION:
XS GIS Cut Line= 3
      1351063.08      6961324.76      1351605.00      6960588.00
      1353416.99      6957831.89
#Sta/Elev= 30
  4081.8 2038.48  4115.8 2039.55  4174.4 2035.28  4209.9 2036.66  4245.4 2032.86
  4338.5 2033.81  4395.8 2030.04  4552.4 2029.09  4577.4 2026.14  4692.7 2023.98
  4732.2 2020.51  4788.5 2020.39  5015.5 2003.06  5016.0 2002.56  5034.5 2003.06
  5061.2 2005.92  5097.3 2004.31  5284.1 2010.85  5354.5 2010.02  5892.7 2007.25
  6468.4 2008.26  7299.6 2016.22  7625.0 2022.61  7758.5 2021.18  7790.7 2023.69
  7905.2 2024.15  7964.4 2030.06  8043.8 2027.42  8211.9 2030.41  8294.8 2031.76
#Mann=8,-1,0
  4081.8    0.07       0  4577.4   0.035       0  4692.7    0.07       0
  5015.5    0.07       0  5034.5    0.07       0  5354.5   0.045       0
  7758.5   0.035       0  8211.9   0.045       0
Bank Sta=5015.5,5034.5
Exp/Cntr=0.3,0.1

Type RM Length L Ch R = 1,76556,454,454,454
BEGIN DESCRIPTION:
Alkali Creek 71.0
END DESCRIPTION:
XS GIS Cut Line= 3
      1351388.63      6961465.78      1352005.00      6960588.00
      1354005.02      6958187.98
#Sta/Elev= 30
  3918.9 2040.82  4058.6 2035.84  4130.1 2037.04  4201.5 2032.36  4237.3 2033.71
  4273.0 2029.83  4344.4 2029.27  4430.7 2022.92  4460.3 2024.15  4502.7 2019.80
  4539.4 2020.83  4582.3 2016.99  4719.1 2014.45  4918.7 2004.27  4994.7 2003.88
  5010.0 2001.35  5010.5 2000.85  5029.0 2001.35  5076.7 2007.93  5113.5 2005.97
  6653.1 2006.07  6844.5 2013.14  6930.4 2012.05  6979.8 2014.96  7022.1 2013.25
  7660.6 2021.33  7984.3 2031.85  8009.5 2034.81  8051.1 2033.48  8115.6 2036.63
#Mann=5,-1,0
  3918.9    0.07       0  5010.0    0.07       0  5029.0    0.07       0
  5113.5   0.045       0  7984.3   0.035       0
Bank Sta=5010,5029
Exp/Cntr=0.3,0.1

Type RM Length L Ch R = 1,76102,469,469,469
BEGIN DESCRIPTION:
Alkali Creek 70.0
END DESCRIPTION:
XS GIS Cut Line= 3
      1351551.36      6961585.16      1352405.00      6960738.00
      1354205.03      6958337.96
#Sta/Elev= 30
  3796.6 2038.70  3882.0 2037.04  3945.6 2032.23  3981.0 2033.28  4023.5 2029.16
  4164.9 2027.04  4200.2 2023.38  4256.8 2024.13  4320.4 2019.58  4348.7 2021.05
  4384.1 2017.14  4483.1 2017.00  4511.3 2013.59  4582.1 2013.18  4666.9 2007.41
  4971.0 2002.78  5012.8 2001.68  5017.9 1999.46  5018.4 1998.96  5036.9 1999.46
  5061.5 2005.10  5471.5 2002.94  5476.7 2002.95  5596.6 2002.95  5971.1 2005.23
  6362.8 2003.88  6592.0 2007.77  6649.3 2011.00  7177.4 2012.69  7999.3 2033.96
#Mann=7,-1,0
  3796.6    0.07       0  5017.9    0.07       0  5036.9    0.07       0
  5061.5   0.045       0  5471.5   0.035       0  5476.7    0.07       0
  5596.6   0.045       0
Bank Sta=5017.9,5036.9
Exp/Cntr=0.3,0.1

Type RM Length L Ch R = 1,75633,3206,3206,3206
BEGIN DESCRIPTION:
Alkali Creek 69.0
END DESCRIPTION:
XS GIS Cut Line= 3
      1351746.72      6961693.63      1352355.00      6961088.00
      1354155.02      6958687.97
#Sta/Elev= 30
  4137.7 2036.61  4352.6 2025.73  4508.2 2024.07  4550.6 2019.74  4593.0 2020.87
  4628.4 2016.76  4720.3 2015.42  4755.7 2011.17  4904.1 2010.71  4967.8 2006.27
  4981.9 2002.55  4983.0 1998.85  4983.5 1998.35  5002.1 1998.85  5009.6 2001.69
  5159.6 2001.97  5282.5 2005.79  5381.6 2003.92  5584.4 2002.77  5753.4 1999.06
  5879.8 2000.42  6023.6 2003.15  6052.4 2004.86  6120.0 2003.42  6451.9 2002.92
  6717.9 2002.79  6938.8 2006.00  6982.5 2008.94  7446.1 2010.45  7996.1 2024.64
#Mann=10,-1,0
  4137.7    0.07       0  4983.0    0.07       0  5002.1    0.07       0
  5381.6   0.045       0  5584.4    0.07       0  5879.8   0.035       0
  6023.6    0.07       0  6052.4   0.035       0  6120.0    0.07       0
  6451.9   0.045       0
Bank Sta=4983,5002.1
Exp/Cntr=0.3,0.1