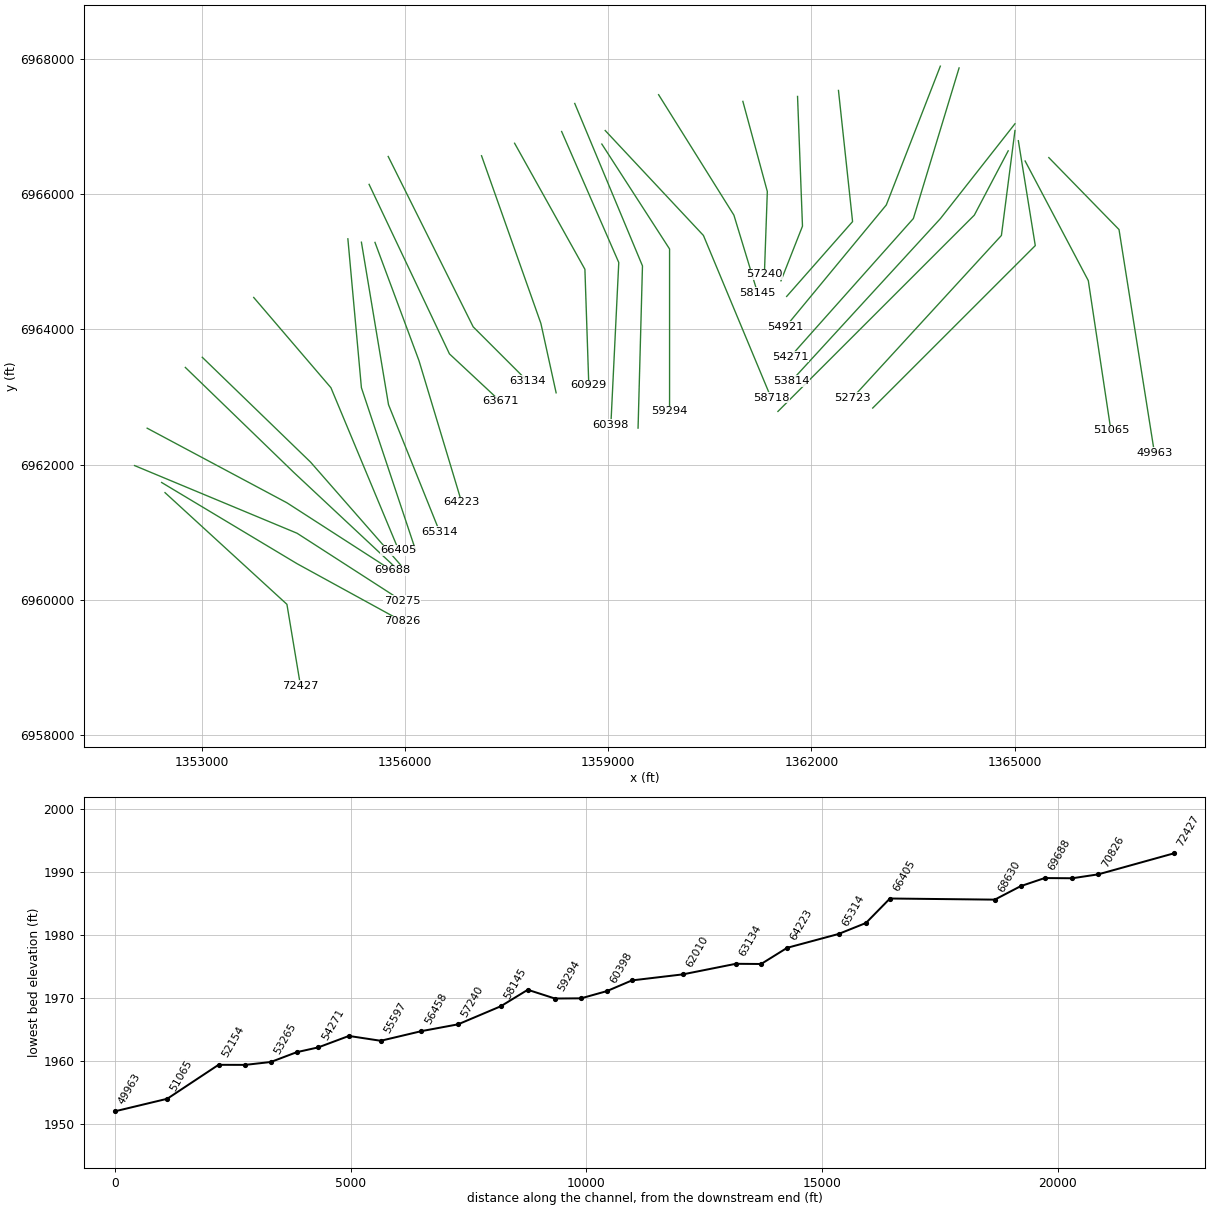
HEC-RAS study Alkali Creek.prj: Alkali Creek Base Level Engineering

--- Alkali Creek.g01 (geometry) --- (continued)

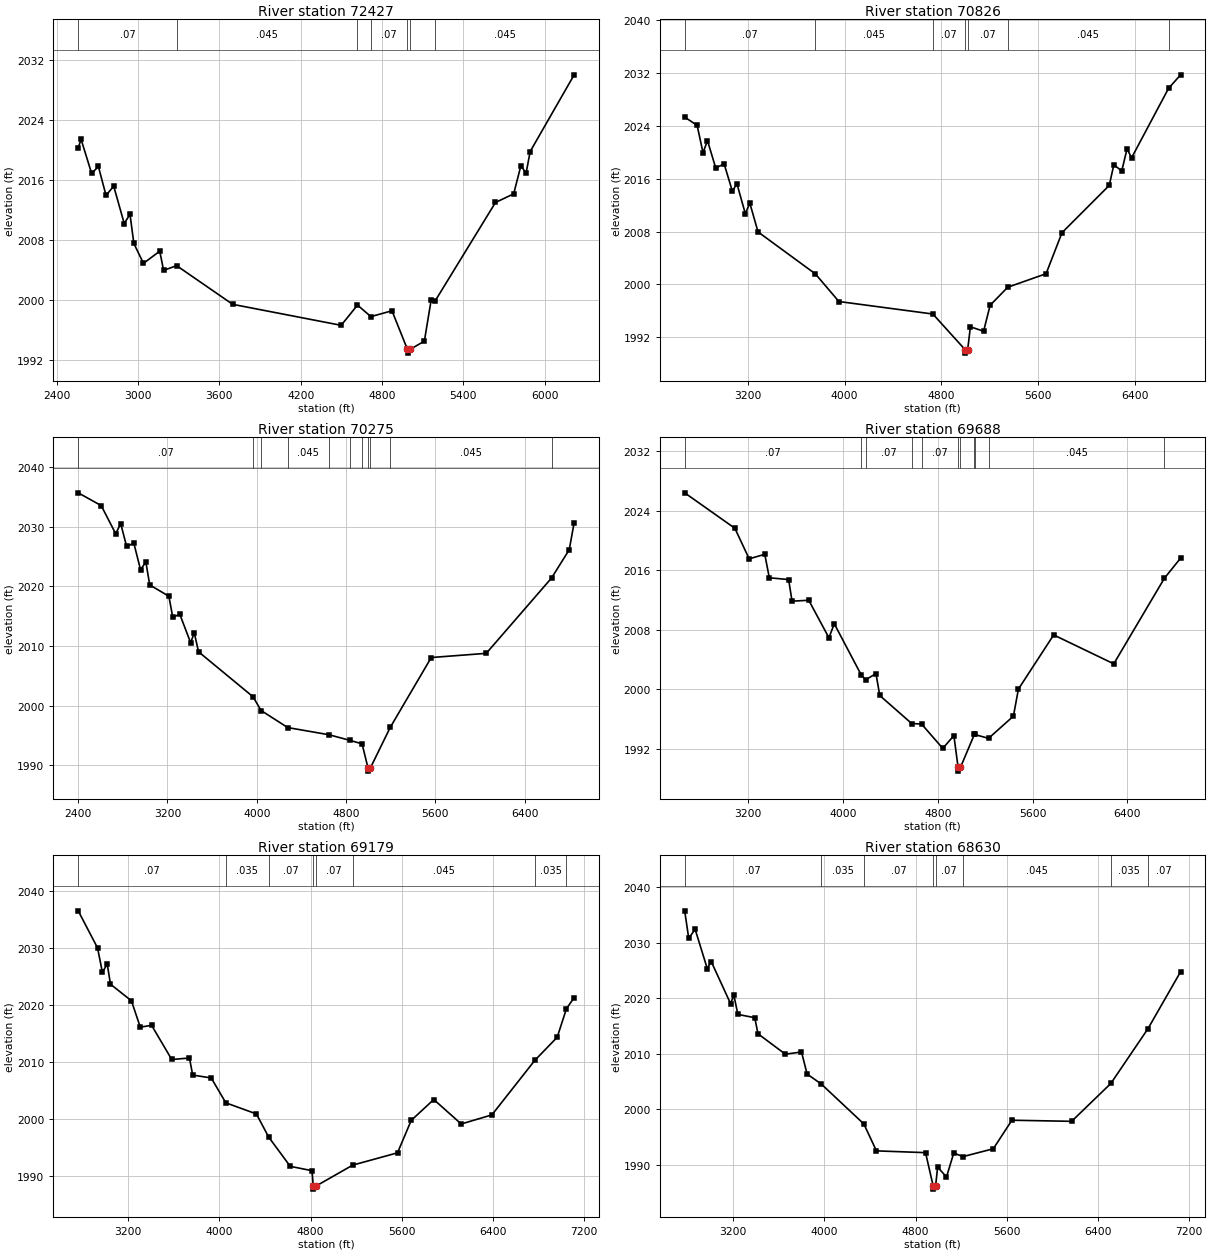
Type RM Length L Ch R = 1,72427,1601,1601,1601
BEGIN DESCRIPTION:
Alkali Creek 68.0
END DESCRIPTION:
XS GIS Cut Line= 3
      1352454.98      6961588.02      1354255.00      6959938.00
      1354455.00      6958738.01
#Sta/Elev= 30
  2558.7 2020.36  2580.0 2021.47  2657.7 2016.92  2707.6 2017.85  2763.8 2013.99
  2820.5 2015.23  2898.2 2010.24  2940.7 2011.48  2969.1 2007.58  3040.0 2004.93
  3160.2 2006.55  3188.6 2003.99  3284.7 2004.62  3698.2 1999.46  4498.3 1996.66
  4618.9 1999.36  4717.9 1997.82  4873.2 1998.60  4987.3 1993.45  4987.8 1992.95
  5007.1 1993.45  5112.1 1994.55  5162.8 2000.09  5191.5 1999.91  5636.7 2013.05
  5771.0 2014.20  5824.3 2017.97  5862.3 2016.95  5892.7 2019.85  6217.1 2030.08
#Mann=7,-1,0
  2558.7    0.07       0  3284.7   0.045       0  4618.9   0.035       0
  4717.9    0.07       0  4987.3    0.07       0  5007.1    0.07       0
  5191.5   0.045       0
Bank Sta=4987.3,5007.1
Exp/Cntr=0.3,0.1

Type RM Length L Ch R = 1,70826,551,551,551
BEGIN DESCRIPTION:
Alkali Creek 67.0
END DESCRIPTION:
XS GIS Cut Line= 3
      1352405.03      6961737.98      1354405.00      6960538.00
      1355954.99      6959688.01
#Sta/Elev= 30
  2677.3 2025.29  2780.3 2024.04  2828.9 2019.90  2865.8 2021.74  2933.8 2017.61
  3003.8 2018.21  3071.8 2014.07  3108.8 2015.25  3178.7 2010.69  3215.7 2012.30
  3283.7 2007.94  3757.5 2001.60  3952.3 1997.42  4729.3 1995.53  4996.7 1990.12
  4997.2 1989.62  5016.7 1990.12  5039.5 1993.60  5148.5 1992.93  5202.5 1996.85
  5348.1 1999.58  5665.1 2001.62  5796.6 2007.82  6187.4 2014.97  6225.3 2018.09
  6290.7 2017.15  6334.3 2020.49  6372.2 2019.14  6677.7 2029.64  6777.4 2031.68
#Mann=7,-1,0
  2677.3    0.07       0  3757.5   0.045       0  4729.3    0.07       0
  4996.7    0.07       0  5016.7    0.07       0  5348.1   0.045       0
  6677.7   0.035       0
Bank Sta=4996.7,5016.7
Exp/Cntr=0.3,0.1

Type RM Length L Ch R = 1,70275,587,587,587
BEGIN DESCRIPTION:
Alkali Creek 66.0
END DESCRIPTION:
XS GIS Cut Line= 3
      1352004.97      6961988.01      1354405.00      6960988.00
      1355954.99      6959988.01
#Sta/Elev= 30
  2399.9 2035.69  2605.8 2033.55  2735.8 2028.83  2780.7 2030.52  2833.8 2026.69
  2898.3 2027.25  2958.4 2022.79  3006.1 2024.09  3040.7 2020.24  3212.4 2018.34
  3247.6 2014.78  3309.9 2015.34  3407.4 2010.54  3439.9 2012.21  3478.4 2009.02
  3966.4 2001.48  4038.7 1999.17  4277.3 1996.31  4648.1 1995.10  4835.2 1994.16
  4943.8 1993.58  4997.5 1989.50  4998.0 1989.00  5017.5 1989.50  5196.1 1996.33
  5563.9 2008.06  6056.8 2008.76  6642.0 2021.40  6800.6 2026.15  6844.5 2030.70
#Mann=11,-1,0
  2399.9    0.07       0  3966.4   0.035       0  4038.7    0.07       0
  4277.3   0.045       0  4648.1    0.07       0  4835.2   0.035       0
  4943.8    0.07       0  4997.5    0.07       0  5017.5    0.07       0
  5196.1   0.045       0  6642.0   0.035       0
Bank Sta=4997.5,5017.5
Exp/Cntr=0.3,0.1

Type RM Length L Ch R = 1,69688,509,509,509
BEGIN DESCRIPTION:
Alkali Creek 65.0
END DESCRIPTION:
XS GIS Cut Line= 3
      1352191.59      6962540.00      1354255.00      6961438.00
      1355804.97      6960438.02
#Sta/Elev= 30
  2665.4 2026.38  3089.0 2021.62  3209.4 2017.52  3341.1 2018.13  3379.3 2014.98
  3542.2 2014.74  3571.2 2011.84  3712.3 2011.96  3882.3 2006.92  3927.3 2008.81
  4156.2 2001.90  4191.2 2001.28  4279.1 2002.12  4311.1 1999.18  4580.4 1995.42
  4663.7 1995.35  4842.9 1992.08  4936.6 1993.80  4971.9 1989.53  4972.4 1989.03
  4992.0 1989.53  5109.1 1993.95  5110.4 1993.95  5228.8 1993.43  5438.6 1996.41
  5480.8 2000.04  5778.2 2007.31  6285.3 2003.43  6712.5 2014.92  6849.2 2017.62
#Mann=11,-1,0
  2665.4    0.07       0  4156.2   0.035       0  4191.2    0.07       0
  4580.4   0.035       0  4663.7    0.07       0  4971.9    0.07       0
  4992.0    0.07       0  5109.1   0.045       0  5110.4   0.035       0
  5228.8   0.045       0  6712.5   0.035       0
Bank Sta=4971.9,4992
Exp/Cntr=0.3,0.1

Type RM Length L Ch R = 1,69179,549,549,549
BEGIN DESCRIPTION:
Alkali Creek 64.0
END DESCRIPTION:
XS GIS Cut Line= 3
      1352755.01      6963437.99      1354355.00      6961888.00
      1355905.03      6960437.97
#Sta/Elev= 30
  2761.7 2036.56  2931.4 2030.05  2973.8 2025.77  3016.2 2027.24  3044.5 2023.69
  3228.4 2020.78  3306.1 2016.15  3405.2 2016.48  3582.1 2010.48  3737.5 2010.74
  3765.8 2007.75  3928.6 2007.24  4056.5 2002.88  4324.5 2000.93  4433.1 1996.85
  4621.6 1991.74  4812.5 1990.97  4823.7 1988.24  4824.2 1987.74  4844.0 1988.24
  5169.3 1991.95  5562.6 1994.11  5682.8 1999.80  5880.6 2003.46  6121.4 1999.17
  6390.1 2000.76  6767.0 2010.33  6963.1 2014.38  7044.3 2019.39  7111.9 2021.34
#Mann=8,-1,0
  2761.7    0.07       0  4056.5   0.035       0  4433.1    0.07       0
  4823.7    0.07       0  4844.0    0.07       0  5169.3   0.045       0
  6767.0   0.035       0  7044.3    0.07       0
Bank Sta=4823.7,4844
Exp/Cntr=0.3,0.1

Type RM Length L Ch R = 1,68630,2225,2225,2225
BEGIN DESCRIPTION:
Alkali Creek 63.0
END DESCRIPTION:
XS GIS Cut Line= 3
      1353005.00      6963588.00      1354605.00      6962038.00
      1356005.00      6960438.00
#Sta/Elev= 30
  2772.8 2035.72  2808.2 2030.79  2864.8 2032.38  2970.8 2025.33  3006.2 2026.57
  3176.0 2018.99  3204.3 2020.56  3239.6 2017.07  3388.0 2016.47  3416.3 2013.58
  3656.8 2009.90  3798.3 2010.30  3847.7 2006.32  3970.8 2004.55  4346.1 1997.33
  4456.0 1992.49  4887.4 1992.17  4954.9 1986.10  4955.4 1985.60  4975.3 1986.10
  4993.4 1989.56  5071.2 1987.79  5134.8 1992.10  5216.2 1991.46  5482.2 1992.87
  5645.4 1998.01  6169.8 1997.81  6513.9 2004.63  6839.8 2014.49  7126.5 2024.76
#Mann=8,-1,0
  2772.8    0.07       0  3970.8   0.035       0  4346.1    0.07       0
  4954.9    0.07       0  4975.3    0.07       0  5216.2   0.045       0
  6513.9   0.035       0  6839.8    0.07       0
Bank Sta=4954.9,4975.3
Exp/Cntr=0.3,0.1

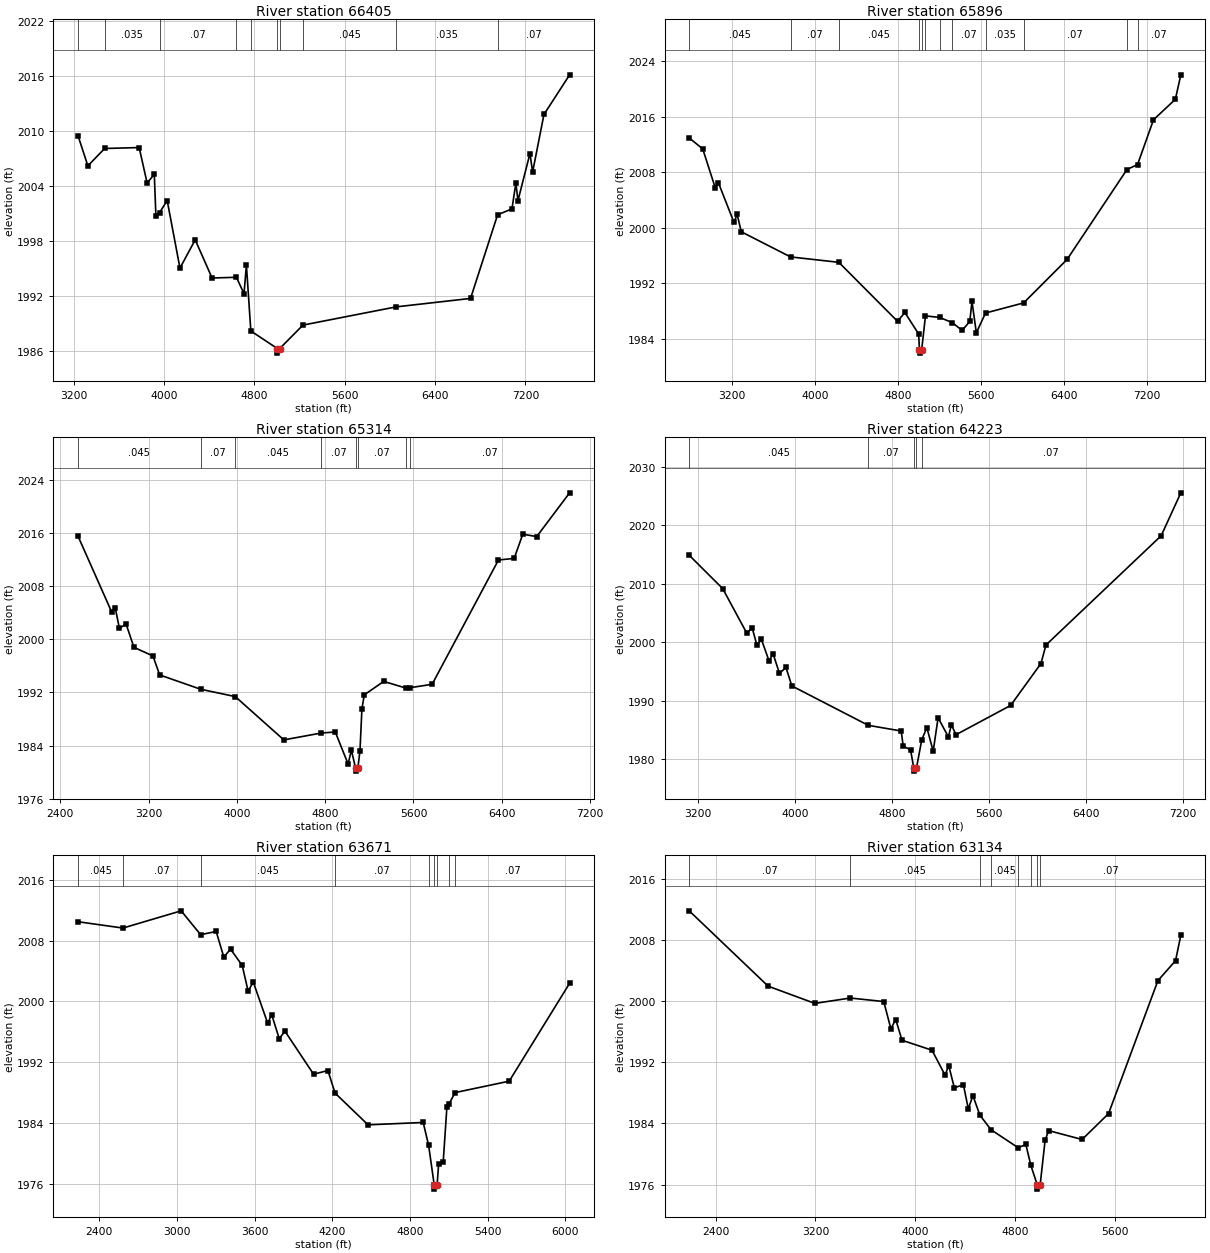
Type RM Length L Ch R = 1,66405,509,509,509
BEGIN DESCRIPTION:
Alkali Creek 62.0
END DESCRIPTION:
XS GIS Cut Line= 3
      1353764.90      6964471.46      1354905.00      6963138.00
      1355905.00      6960738.01
#Sta/Elev= 30
  3237.0 2009.52  3324.4 2006.22  3473.2 2008.12  3778.9 2008.22  3849.2 2004.35
  3912.8 2005.30  3927.1 2000.72  3959.5 2001.12  4027.0 2002.44  4140.1 1995.06
  4275.1 1998.15  4424.4 1993.98  4640.0 1994.06  4707.6 1992.27  4728.5 1995.40
  4767.8 1988.20  5002.4 1986.28  5002.9 1985.78  5023.8 1986.28  5229.5 1988.84
  6055.0 1990.83  6713.9 1991.75  6953.4 2000.88  7080.6 2001.53  7115.3 2004.35
  7133.7 2002.43  7239.9 2007.56  7263.7 2005.55  7363.9 2011.83  7591.4 2016.16
#Mann=10,-1,0
  3237.0    0.07       0  3473.2   0.035       0  3959.5    0.07       0
  4640.0   0.035       0  4767.8    0.07       0  5002.4    0.07       0
  5023.8    0.07       0  5229.5   0.045       0  6055.0   0.035       0
  6953.4    0.07       0
Bank Sta=5002.4,5023.8
Exp/Cntr=0.3,0.1

Type RM Length L Ch R = 1,65896,582,582,582
BEGIN DESCRIPTION:
Alkali Creek 61.0
END DESCRIPTION:
XS GIS Cut Line= 3
      1355155.00      6965338.04      1355355.00      6963138.00
      1356154.99      6960738.03
#Sta/Elev= 30
  2786.8 2012.96  2917.4 2011.37  3037.9 2005.75  3068.0 2006.50  3218.6 2000.75
  3248.7 2001.94  3288.9 1999.41  3763.7 1995.78  4229.0 1995.00  4795.1 1986.48
  4865.4 1987.76  4998.5 1984.65  5006.3 1982.39  5006.8 1981.89  5027.7 1982.39
  5064.3 1987.27  5200.6 1987.04  5323.2 1986.29  5417.5 1985.17  5491.3 1986.46
  5512.4 1989.35  5554.6 1984.83  5643.0 1987.68  6010.5 1989.14  6429.5 1995.42
  7006.5 2008.40  7108.7 2009.12  7262.2 2015.58  7473.0 2018.54  7525.7 2022.07
#Mann=12,-1,0
  2786.8   0.045       0  3763.7    0.07       0  4229.0   0.045       0
  5006.3   0.045       0  5027.7   0.045       0  5064.3    0.07       0
  5200.6   0.045       0  5323.2    0.07       0  5643.0   0.035       0
  6010.5    0.07       0  7006.5   0.035       0  7108.7    0.07       0
Bank Sta=5006.3,5027.7
Exp/Cntr=0.3,0.1

Type RM Length L Ch R = 1,65314,1091,1091,1091
BEGIN DESCRIPTION:
Alkali Creek 60.0
END DESCRIPTION:
XS GIS Cut Line= 3
      1355355.00      6965287.97      1355755.00      6962888.00
      1356509.49      6961011.69
#Sta/Elev= 30
  2560.0 2015.58  2864.1 2004.18  2897.1 2004.80  2935.1 2001.67  2995.9 2002.32
  3066.9 1998.81  3239.2 1997.51  3300.0 1994.65  3671.0 1992.49  3985.3 1991.38
  4425.4 1984.85  4765.9 1985.89  4891.7 1986.04  5007.9 1981.21  5037.4 1983.31
  5075.0 1980.64  5075.5 1980.14  5096.6 1980.64  5115.4 1983.21  5133.2 1989.57
  5154.8 1991.65  5330.4 1993.67  5535.1 1992.65  5567.8 1992.72  5769.1 1993.23
  6370.4 2011.98  6512.8 2012.22  6590.8 2015.87  6717.1 2015.51  7015.4 2022.11
#Mann=8,-1,0
  2560.0   0.045       0  3671.0    0.07       0  3985.3   0.045       0
  4765.9    0.07       0  5075.0    0.07       0  5096.6    0.07       0
  5535.1   0.035       0  5567.8    0.07       0
Bank Sta=5075,5096.6
Exp/Cntr=0.3,0.1

Type RM Length L Ch R = 1,64223,552,552,552
BEGIN DESCRIPTION:
Alkali Creek 59.0
END DESCRIPTION:
XS GIS Cut Line= 3
      1355555.27      6965285.28      1356205.00      6963538.00
      1356835.67      6961444.08
#Sta/Elev= 30
  3128.4 2014.85  3404.2 2009.15  3600.7 2001.61  3648.3 2002.35  3686.4 1999.47
  3723.0 2000.48  3787.0 1996.75  3819.0 1998.03  3872.3 1994.65  3925.7 1995.67
  3973.9 1992.51  4603.8 1985.77  4875.2 1984.80  4891.7 1982.22  4952.4 1981.57
  4979.1 1978.44  4979.6 1977.94  5000.8 1978.44  5044.7 1983.31  5086.6 1985.38
  5138.8 1981.34  5179.3 1987.07  5264.1 1983.79  5288.8 1985.85  5327.0 1984.17
  5776.9 1989.17  6026.5 1996.33  6068.3 1999.51  7017.2 2018.18  7179.4 2025.52
#Mann=5,-1,0
  3128.4   0.045       0  4603.8    0.07       0  4979.1   0.035       0
  5000.8    0.07       0  5044.7    0.07       0
Bank Sta=4979.1,5000.8
Exp/Cntr=0.3,0.1

Type RM Length L Ch R = 1,63671,537,537,537
BEGIN DESCRIPTION:
Alkali Creek 58.0
END DESCRIPTION:
XS GIS Cut Line= 3
      1355468.48      6966142.44      1356655.00      6963638.00
      1357404.99      6962938.01
#Sta/Elev= 30
  2235.2 2010.47  2582.1 2009.64  3032.1 2011.90  3182.0 2008.77  3302.4 2009.19
  3361.6 2005.82  3413.1 2006.88  3503.6 2004.73  3549.1 2001.36  3589.0 2002.55
  3700.8 1997.12  3731.0 1998.29  3789.3 1995.12  3833.6 1996.10  4054.9 1990.45
  4165.5 1990.94  4220.4 1987.98  4475.4 1983.81  4901.4 1984.12  4943.3 1981.12
  4987.0 1975.87  4987.5 1975.37  5008.8 1975.87  5020.4 1978.63  5056.1 1978.96
  5084.4 1986.13  5100.7 1986.53  5147.3 1988.04  5565.6 1989.54  6032.4 2002.39
#Mann=9,-1,0
  2235.2   0.045       0  2582.1    0.07       0  3182.0   0.045       0
  4220.4    0.07       0  4943.3   0.035       0  4987.0   0.035       0
  5008.8   0.035       0  5100.7   0.035       0  5147.3    0.07       0
Bank Sta=4987,5008.8
Exp/Cntr=0.3,0.1

Type RM Length L Ch R = 1,63134,1124,1124,1124
BEGIN DESCRIPTION:
Alkali Creek 57.0
END DESCRIPTION:
XS GIS Cut Line= 3
      1355750.60      6966554.75      1357005.00      6964038.00
      1357804.99      6963238.01
#Sta/Elev= 30
  2188.0 2011.78  2821.2 2001.93  3195.5 1999.68  3480.7 2000.38  3748.6 1999.92
  3805.4 1996.37  3844.6 1997.57  3894.9 1994.86  4135.5 1993.56  4240.3 1990.30
  4269.8 1991.55  4314.6 1988.64  4387.3 1989.06  4426.5 1985.90  4463.7 1987.62
  4519.6 1985.07  4609.1 1983.16  4827.1 1980.81  4888.3 1981.24  4928.1 1978.53
  4980.6 1975.90  4981.1 1975.40  5002.6 1975.90  5042.5 1981.76  5070.7 1983.05
  5339.4 1981.89  5551.6 1985.27  5947.6 2002.66  6089.0 2005.26  6131.4 2008.59
#Mann=8,-1,0
  2188.0    0.07       0  3480.7   0.045       0  4519.6    0.07       0
  4609.1   0.045       0  4827.1   0.035       0  4928.1    0.07       0
  4980.6    0.07       0  5002.6    0.07       0
Bank Sta=4980.6,5002.6
Exp/Cntr=0.3,0.1

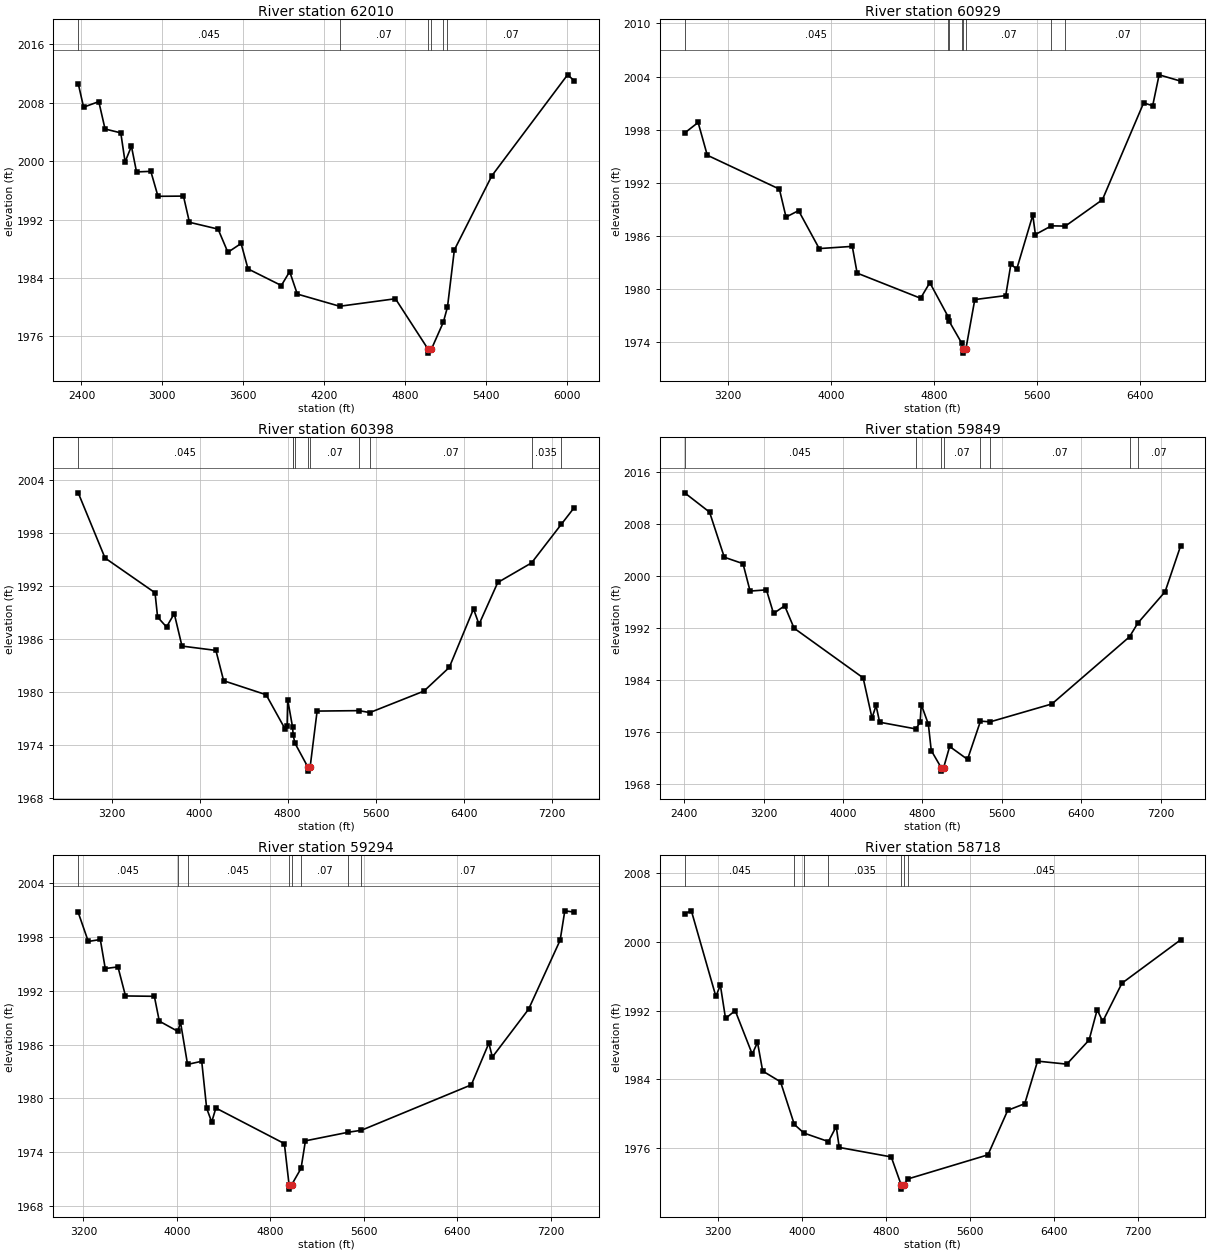
Type RM Length L Ch R = 1,62010,1081,1081,1081
BEGIN DESCRIPTION:
Alkali Creek 56.0
END DESCRIPTION:
XS GIS Cut Line= 3
      1357128.64      6966565.61      1358005.00      6964088.00
      1358229.99      6963063.03
#Sta/Elev= 30
  2375.7 2010.65  2415.6 2007.41  2528.3 2008.17  2574.7 2004.42  2691.4 2003.89
  2723.2 1999.91  2770.3 2002.06  2808.1 1998.54  2914.1 1998.62  2967.2 1995.20
  3156.1 1995.23  3200.5 1991.64  3412.7 1990.71  3485.5 1987.53  3583.5 1988.74
  3634.7 1985.26  3881.9 1982.98  3943.7 1984.89  4000.2 1981.81  4314.3 1980.14
  4727.9 1981.17  4971.5 1974.22  4972.0 1973.72  4993.6 1974.22  5083.1 1977.96
  5113.9 1980.04  5164.7 1987.85  5442.8 1998.01  6004.2 2011.84  6053.1 2011.05
#Mann=6,-1,0
  2375.7   0.045       0  4314.3    0.07       0  4971.5    0.07       0
  4993.6    0.07       0  5083.1   0.035       0  5113.9    0.07       0
Bank Sta=4971.5,4993.6
Exp/Cntr=0.3,0.1

Type RM Length L Ch R = 1,60929,531,531,531
BEGIN DESCRIPTION:
Alkali Creek 55.0
END DESCRIPTION:
XS GIS Cut Line= 3
      1357616.90      6966750.11      1358655.00      6964888.00
      1358712.77      6963171.20
#Sta/Elev= 30
  2863.8 1997.63  2968.2 1998.82  3039.1 1995.12  3599.0 1991.29  3650.5 1988.13
  3747.7 1988.86  3908.1 1984.57  4164.8 1984.82  4202.5 1981.80  4695.1 1978.96
  4766.7 1980.72  4909.1 1976.87  4916.0 1976.38  5012.7 1973.93  5024.5 1973.26
  5025.0 1972.76  5047.0 1973.26  5115.8 1978.81  5355.9 1979.26  5396.0 1982.81
  5441.3 1982.25  5566.1 1988.36  5586.1 1986.16  5710.8 1987.14  5818.6 1987.11
  6106.4 1990.09  6426.5 2001.03  6496.6 2000.71  6546.6 2004.20  6713.5 2003.49
#Mann=8,-1,0
  2863.8   0.045       0  4909.1    0.07       0  4916.0   0.045       0
  5012.7    0.07       0  5024.5   0.045       0  5047.0    0.07       0
  5710.8   0.035       0  5818.6    0.07       0
Bank Sta=5024.5,5047
Exp/Cntr=0.3,0.1

Type RM Length L Ch R = 1,60398,549,549,549
BEGIN DESCRIPTION:
Alkali Creek 54.0
END DESCRIPTION:
XS GIS Cut Line= 3
      1358311.36      6966923.69      1359155.00      6964988.00
      1359038.36      6962594.28
#Sta/Elev= 30
  2897.2 2002.53  3141.0 1995.16  3595.3 1991.23  3618.8 1988.48  3699.9 1987.36
  3770.2 1988.87  3840.5 1985.20  4148.8 1984.71  4219.1 1981.28  4605.1 1979.70
  4779.7 1975.78  4796.0 1976.13  4801.5 1979.13  4845.7 1976.03  4851.2 1975.15
  4866.4 1974.24  4982.9 1971.56  4983.4 1971.06  5005.7 1971.56  5068.8 1977.85
  5449.6 1977.90  5547.8 1977.68  6040.0 1980.11  6270.2 1982.79  6490.5 1989.40
  6540.6 1987.66  6710.8 1992.39  7018.4 1994.61  7287.2 1998.95  7405.3 2000.85
#Mann=10,-1,0
  2897.2   0.045       0  4845.7    0.07       0  4851.2   0.045       0
  4866.4    0.07       0  4982.9    0.07       0  5005.7    0.07       0
  5449.6   0.035       0  5547.8    0.07       0  7018.4   0.035       0
  7287.2    0.07       0
Bank Sta=4982.9,5005.7
Exp/Cntr=0.3,0.1

Type RM Length L Ch R = 1,59849,555,555,555
BEGIN DESCRIPTION:
Alkali Creek 53.0
END DESCRIPTION:
XS GIS Cut Line= 3
      1358505.01      6967337.97      1359505.00      6964938.00
      1359439.87      6962541.55
#Sta/Elev= 30
  2403.8 2012.82  2654.6 2009.84  2803.0 2002.89  2991.5 2001.90  3063.0 1997.67
  3227.6 1997.86  3299.1 1994.22  3411.3 1995.40  3506.1 1991.95  4202.1 1984.29
  4291.5 1978.10  4332.1 1980.03  4368.4 1977.45  4732.3 1976.42  4776.3 1977.43
  4787.6 1980.18  4859.1 1977.15  4888.4 1973.09  4989.7 1970.41  4990.2 1969.91
  5012.5 1970.41  5073.8 1973.71  5253.9 1971.72  5384.3 1977.62  5482.2 1977.51
  6104.2 1980.27  6886.0 1990.62  6970.1 1992.74  7244.6 1997.57  7401.1 2004.64
#Mann=8,-1,0
  2403.8   0.045       0  4732.3    0.07       0  4989.7    0.07       0
  5012.5    0.07       0  5384.3   0.035       0  5482.2    0.07       0
  6886.0   0.035       0  6970.1    0.07       0
Bank Sta=4989.7,5012.5
Exp/Cntr=0.3,0.1

Type RM Length L Ch R = 1,59294,576,576,576
BEGIN DESCRIPTION:
Alkali Creek 52.0
END DESCRIPTION:
XS GIS Cut Line= 3
      1358904.98      6966738.03      1359905.00      6965188.00
      1359905.00      6962788.02
#Sta/Elev= 30
  3155.3 2000.76  3241.5 1997.52  3344.4 1997.74  3386.7 1994.50  3495.5 1994.68
  3560.0 1991.44  3807.0 1991.40  3849.3 1988.63  4007.9 1987.49  4030.8 1988.51
  4091.1 1983.80  4212.3 1984.15  4254.5 1978.91  4297.8 1977.37  4333.5 1978.93
  4919.7 1974.96  4959.8 1970.38  4960.3 1969.88  4982.7 1970.38  5062.5 1972.20
  5099.9 1975.27  5467.3 1976.23  5579.4 1976.45  6519.9 1981.52  6669.9 1986.17
  6699.9 1984.62  7009.9 1989.96  7279.9 1997.66  7319.9 2000.94  7399.9 2000.80
#Mann=8,-1,0
  3155.3   0.045       0  4007.9   0.035       0  4091.1   0.045       0
  4959.8   0.045       0  4982.7   0.045       0  5062.5    0.07       0
  5467.3   0.035       0  5579.4    0.07       0
Bank Sta=4959.8,4982.7
Exp/Cntr=0.3,0.1

Type RM Length L Ch R = 1,58718,573,573,573
BEGIN DESCRIPTION:
Alkali Creek 51.0
END DESCRIPTION:
XS GIS Cut Line= 3
      1358955.02      6966937.98      1360405.00      6965388.00
      1361405.01      6962987.97
#Sta/Elev= 30
  2882.0 2003.25  2945.7 2003.58  3179.2 1993.64  3221.7 1994.96  3271.1 1991.08
  3362.9 1992.00  3525.6 1986.94  3575.4 1988.32  3624.7 1984.98  3794.7 1983.73
  3926.0 1978.78  4017.5 1977.78  4250.7 1976.79  4325.2 1978.54  4353.6 1976.11
  4848.9 1975.01  4943.4 1971.77  4943.9 1971.27  4966.3 1971.77  5009.6 1972.46
  5769.8 1975.25  5958.3 1980.42  6120.3 1981.19  6242.2 1986.13  6520.6 1985.78
  6732.9 1988.58  6809.8 1992.09  6862.9 1990.74  7046.0 1995.18  7604.5 2000.21
#Mann=7,-1,0
  2882.0   0.045       0  3926.0   0.035       0  4017.5   0.045       0
  4250.7   0.035       0  4943.4   0.035       0  4966.3   0.035       0
  5009.6   0.045       0
Bank Sta=4943.4,4966.3
Exp/Cntr=0.3,0.1

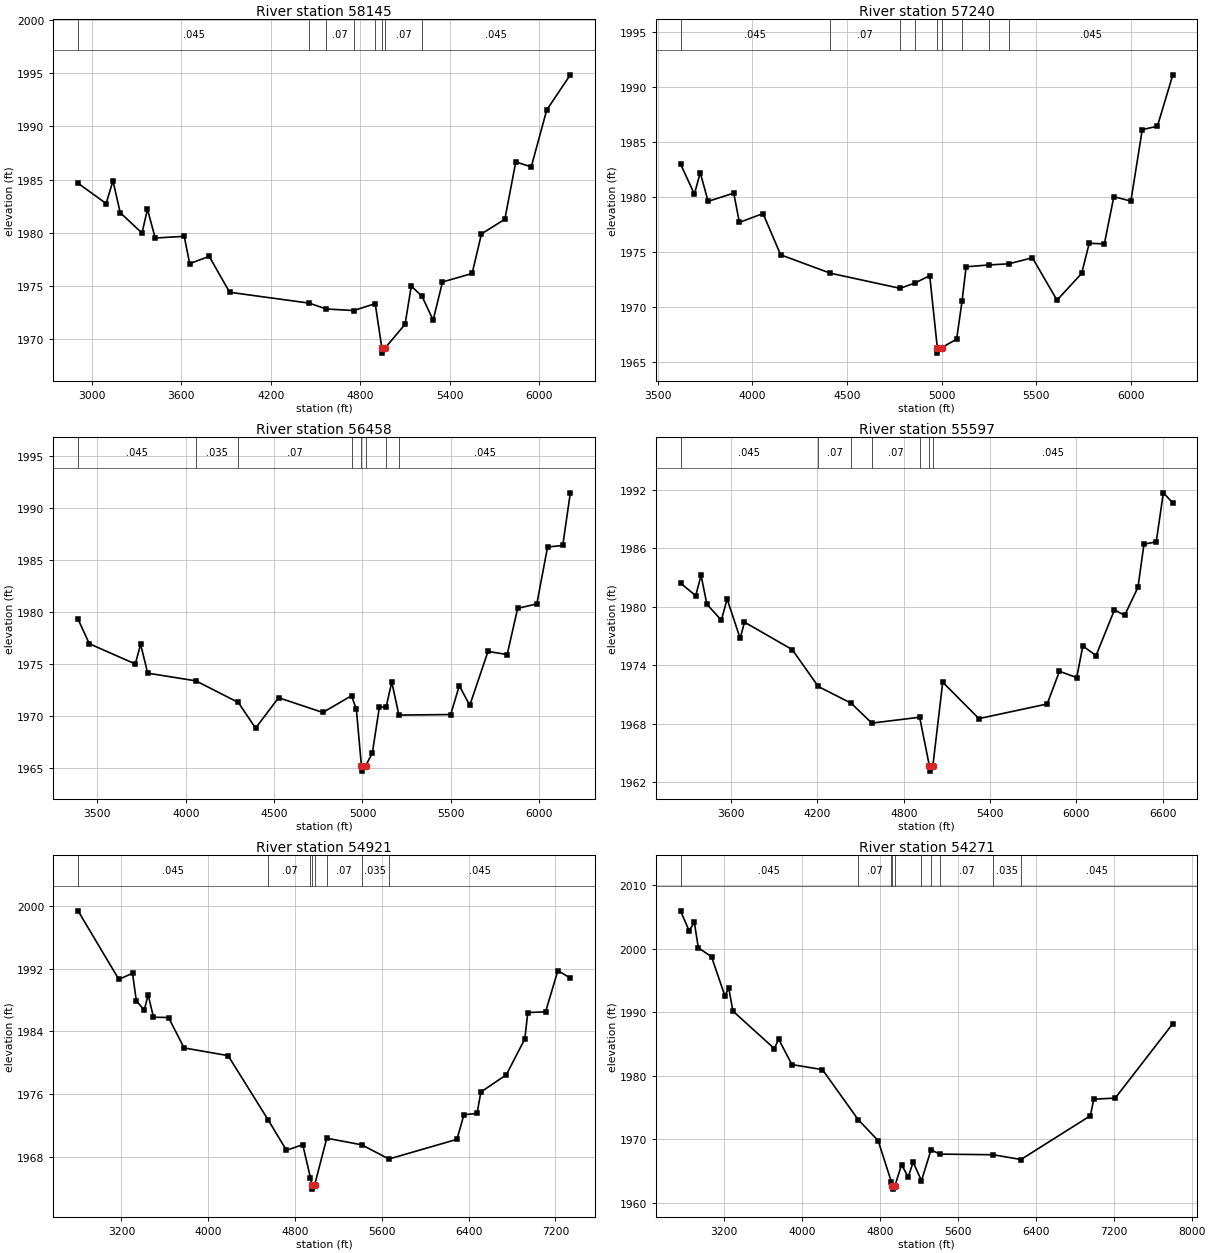
Type RM Length L Ch R = 1,58145,905,905,905
BEGIN DESCRIPTION:
Alkali Creek 50.0
END DESCRIPTION:
XS GIS Cut Line= 3
      1359743.24      6967467.49      1360855.00      6965688.00
      1361204.99      6964538.02
#Sta/Elev= 30
  2907.7 1984.65  3096.0 1982.74  3142.0 1984.88  3190.3 1981.88  3336.6 1979.96
  3373.1 1982.20  3425.0 1979.49  3619.6 1979.65  3656.2 1977.08  3787.1 1977.76
  3923.9 1974.38  4457.3 1973.36  4570.8 1972.81  4755.4 1972.66  4899.8 1973.31
  4944.2 1969.15  4944.7 1968.65  4967.5 1969.15  5100.0 1971.37  5141.8 1974.96
  5213.9 1974.00  5288.2 1971.76  5350.9 1975.35  5549.5 1976.15  5612.2 1979.88
  5769.0 1981.26  5842.2 1986.66  5946.0 1986.19  6049.7 1991.55  6208.0 1994.86
#Mann=8,-1,0
  2907.7   0.045       0  4457.3   0.035       0  4570.8    0.07       0
  4755.4   0.035       0  4899.8    0.07       0  4944.2    0.07       0
  4967.5    0.07       0  5213.9   0.045       0
Bank Sta=4944.2,4967.5
Exp/Cntr=0.3,0.1

Type RM Length L Ch R = 1,57240,782,782,782
BEGIN DESCRIPTION:
Alkali Creek 49.0
END DESCRIPTION:
XS GIS Cut Line= 3
      1360987.50      6967368.72      1361348.57      6966036.59
      1361305.20      6964816.66
#Sta/Elev= 30
  3619.8 1983.01  3693.1 1980.26  3724.2 1982.21  3765.6 1979.60  3901.2 1980.35
  3930.7 1977.68  4055.7 1978.49  4148.9 1974.73  4411.0 1973.06  4779.9 1971.68
  4857.6 1972.16  4936.4 1972.83  4976.5 1966.28  4977.0 1965.78  4999.8 1966.28
  5078.6 1967.05  5107.3 1970.52  5128.7 1973.64  5250.3 1973.81  5353.4 1973.91
  5478.9 1974.46  5609.0 1970.60  5739.1 1973.04  5779.1 1975.78  5859.1 1975.73
  5909.2 1980.03  5999.2 1979.62  6059.3 1986.13  6139.3 1986.44  6220.7 1991.12
#Mann=9,-1,0
  3619.8   0.045       0  4411.0    0.07       0  4779.9   0.035       0
  4857.6    0.07       0  4976.5    0.07       0  4999.8    0.07       0
  5107.3   0.035       0  5250.3    0.07       0  5353.4   0.045       0
Bank Sta=4976.5,4999.8
Exp/Cntr=0.3,0.1

Type RM Length L Ch R = 1,56458,861,861,861
BEGIN DESCRIPTION:
Alkali Creek 48.5
END DESCRIPTION:
XS GIS Cut Line= 3
      1361794.70      6967441.87      1361867.62      6965525.18
      1361549.96      6964718.02
#Sta/Elev= 30
  3390.6 1979.30  3454.5 1976.94  3714.7 1974.99  3744.7 1976.89  3784.8 1974.11
  4057.6 1973.37  4297.6 1971.29  4395.2 1968.82  4525.3 1971.75  4775.5 1970.33
  4938.2 1971.94  4965.6 1970.62  4994.0 1965.19  4994.5 1964.69  5017.3 1965.19
  5055.7 1966.42  5095.7 1970.85  5133.8 1970.86  5165.8 1973.26  5206.1 1970.08
  5499.1 1970.13  5547.7 1972.90  5607.2 1971.02  5710.2 1976.20  5818.6 1975.90
  5878.1 1980.34  5986.5 1980.77  6047.2 1986.24  6133.1 1986.39  6176.1 1991.45
#Mann=8,-1,0
  3390.6   0.045       0  4057.6   0.035       0  4297.6    0.07       0
  4938.2    0.16       0  4994.0    0.07       0  5017.3    0.16       0
  5133.8    0.07       0  5206.1   0.045       0
Bank Sta=4994,5017.3
Exp/Cntr=0.3,0.1

Type RM Length L Ch R = 1,55597,676,676,676
BEGIN DESCRIPTION:
Alkali Creek 48.0
END DESCRIPTION:
XS GIS Cut Line= 3
      1362398.95      6967530.20      1362607.29      6965592.71
      1361633.84      6964486.63
#Sta/Elev= 30
  3248.0 1982.42  3353.6 1981.13  3391.0 1983.22  3431.3 1980.26  3531.8 1978.62
  3572.1 1980.79  3662.6 1976.76  3692.8 1978.42  4024.7 1975.61  4205.6 1971.83
  4434.0 1970.12  4577.7 1968.08  4910.4 1968.68  4978.5 1963.66  4979.0 1963.16
  5001.9 1963.66  5070.7 1972.27  5322.5 1968.54  5796.9 1970.04  5882.2 1973.39
  6002.2 1972.74  6044.5 1975.98  6136.5 1975.00  6264.6 1979.68  6335.2 1979.12
  6427.8 1981.98  6469.6 1986.41  6554.9 1986.65  6604.3 1991.67  6670.1 1990.64
#Mann=7,-1,0
  3248.0   0.045       0  4205.6    0.07       0  4434.0   0.035       0
  4577.7    0.07       0  4910.4   0.045       0  4978.5   0.045       0
  5001.9   0.045       0
Bank Sta=4978.5,5001.9
Exp/Cntr=0.3,0.1

Type RM Length L Ch R = 1,54921,650,650,650
BEGIN DESCRIPTION:
Alkali Creek 47.0
END DESCRIPTION:
XS GIS Cut Line= 3
      1363902.93      6967888.96      1363105.00      6965838.00
      1361616.49      6964034.82
#Sta/Elev= 30
  2799.3 1999.35  3175.9 1990.62  3301.6 1991.41  3336.8 1987.88  3410.4 1986.72
  3445.6 1988.69  3494.7 1985.81  3633.4 1985.77  3777.4 1981.90  4182.8 1980.92
  4553.1 1972.72  4721.0 1968.87  4870.9 1969.59  4942.0 1965.38  4955.6 1964.43
  4956.1 1963.93  4980.1 1964.43  5092.5 1970.41  5415.3 1969.57  5665.1 1967.76
  6293.1 1970.27  6356.9 1973.40  6478.1 1973.56  6513.3 1976.29  6747.8 1978.48
  6918.5 1983.04  6945.8 1986.40  7110.0 1986.50  7223.3 1991.74  7338.2 1990.79
#Mann=8,-1,0
  2799.3   0.045       0  4553.1    0.07       0  4942.0    0.05       0
  4955.6    0.05       0  4980.1    0.05       0  5092.5    0.07       0
  5415.3   0.035       0  5665.1   0.045       0
Bank Sta=4955.6,4980.1
Exp/Cntr=0.3,0.1

Type RM Length L Ch R = 1,54271,457,457,457
BEGIN DESCRIPTION:
Alkali Creek 46.0
END DESCRIPTION:
XS GIS Cut Line= 3
      1364179.99      6967862.96      1363505.00      6965638.00
      1361689.70      6963597.64
#Sta/Elev= 30
  2750.3 2005.98  2839.1 2002.83  2892.3 2004.18  2933.1 2000.16  3069.0 1998.74
  3204.8 1992.63  3246.6 1993.75  3288.4 1990.18  3713.2 1984.27  3758.7 1985.74
  3894.5 1981.74  4208.0 1980.95  4574.8 1973.07  4780.1 1969.76  4914.7 1963.31
  4927.3 1962.61  4927.8 1962.11  4951.8 1962.61  5020.8 1965.95  5089.2 1964.02
  5139.4 1966.37  5225.1 1963.44  5323.3 1968.31  5412.7 1967.63  5960.7 1967.53
  6246.8 1966.78  6959.7 1973.68  6994.8 1976.29  7214.7 1976.46  7806.4 1988.19
#Mann=10,-1,0
  2750.3   0.045       0  4574.8    0.07       0  4914.7    0.05       0
  4927.3    0.05       0  4951.8    0.05       0  5225.1    0.07       0
  5323.3    0.05       0  5412.7    0.07       0  5960.7   0.035       0
  6246.8   0.045       0
Bank Sta=4927.3,4951.8
Exp/Cntr=0.3,0.1

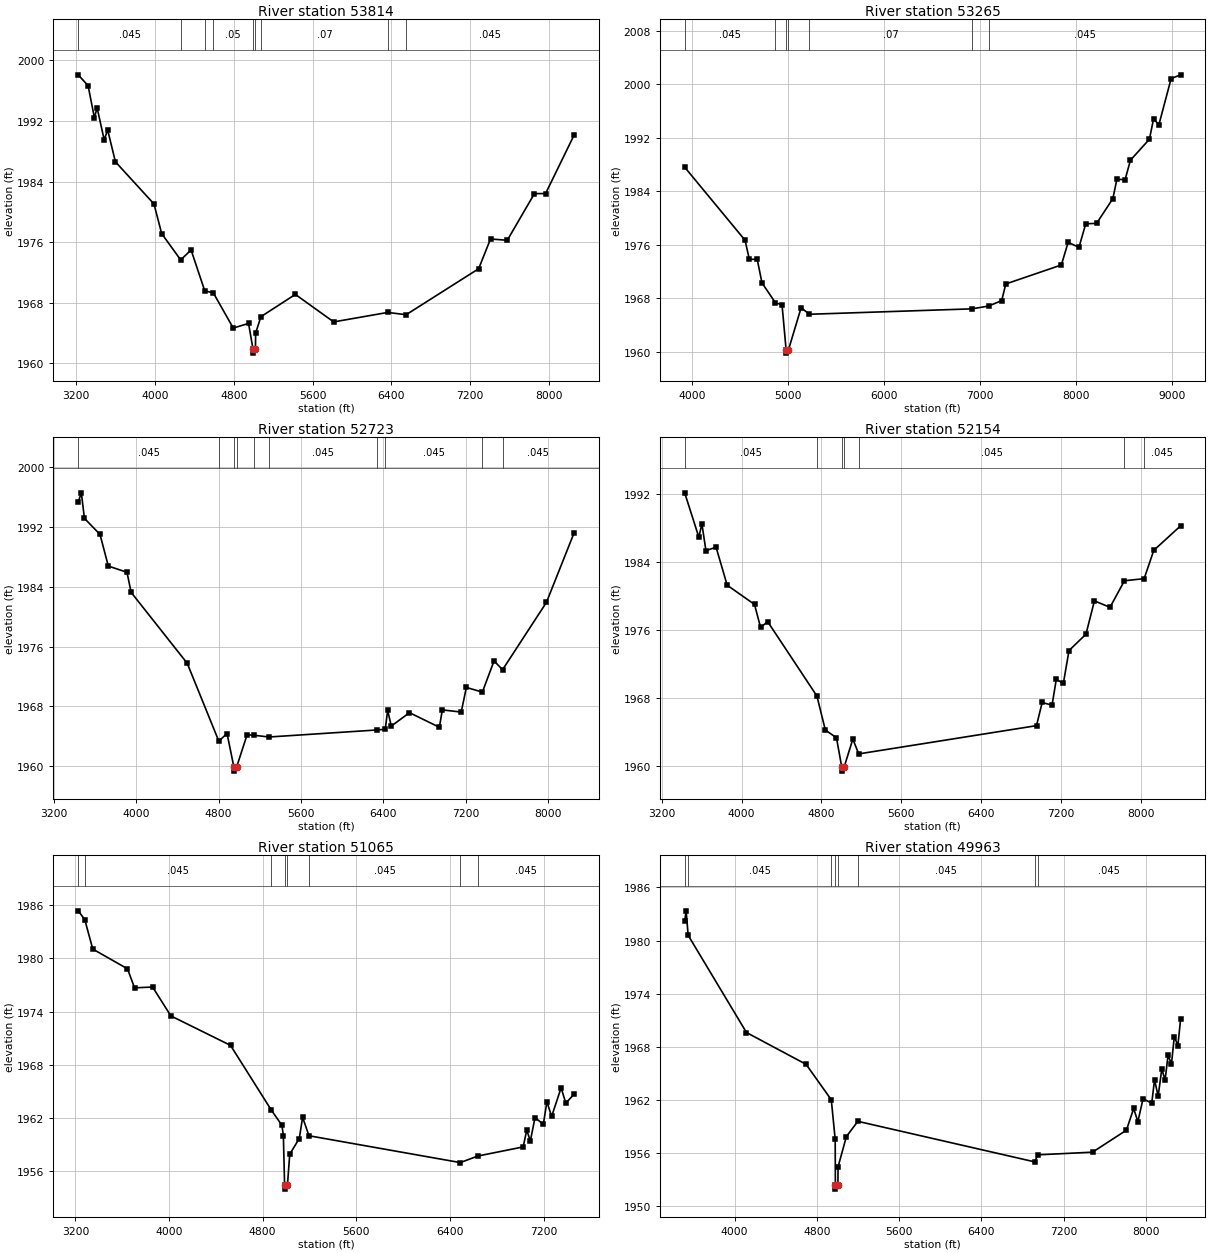
Type RM Length L Ch R = 1,53814,549,549,549
BEGIN DESCRIPTION:
Alkali Creek 45.0
END DESCRIPTION:
XS GIS Cut Line= 3
      1365005.02      6967038.03      1363905.00      6965638.00
      1361704.97      6963237.97
#Sta/Elev= 30
  3219.3 1998.08  3319.6 1996.65  3383.8 1992.41  3411.0 1993.74  3483.2 1989.50
  3518.5 1990.80  3597.1 1986.60  3988.5 1981.04  4067.1 1977.12  4260.1 1973.65
  4365.4 1974.97  4504.3 1969.57  4591.1 1969.31  4793.7 1964.66  4949.2 1965.27
  4994.6 1961.85  4995.1 1961.35  5019.2 1961.85  5021.1 1964.00  5074.8 1966.16
  5424.3 1969.10  5813.7 1965.47  6362.3 1966.72  6549.3 1966.42  7285.9 1972.49
  7406.2 1976.42  7576.3 1976.24  7852.0 1982.40  7965.4 1982.41  8255.6 1990.14
#Mann=9,-1,0
  3219.3   0.045       0  4260.1    0.05       0  4504.3    0.07       0
  4591.1    0.05       0  4994.6    0.05       0  5019.2    0.05       0
  5074.8    0.07       0  6362.3   0.035       0  6549.3   0.045       0
Bank Sta=4994.6,5019.2
Exp/Cntr=0.3,0.1

Type RM Length L Ch R = 1,53265,542,542,542
BEGIN DESCRIPTION:
Alkali Creek 44.0
END DESCRIPTION:
XS GIS Cut Line= 3
      1364905.01      6966638.03      1364405.00      6965688.00
      1361505.00      6962788.00
#Sta/Elev= 30
  3918.5 1987.59  4548.8 1976.66  4592.9 1973.82  4675.4 1973.81  4725.1 1970.29
  4866.1 1967.31  4934.2 1967.03  4976.9 1960.29  4977.4 1959.79  5001.6 1960.29
  5133.5 1966.58  5220.2 1965.60  6915.8 1966.41  7090.1 1966.83  7226.5 1967.65
  7269.0 1970.13  7848.8 1972.97  7919.5 1976.35  8032.6 1975.61  8103.3 1979.13
  8216.5 1979.19  8386.2 1982.89  8428.6 1985.80  8513.5 1985.71  8570.0 1988.64
  8768.0 1991.78  8810.5 1994.78  8867.0 1993.96  8994.3 2000.84  9093.3 2001.40
#Mann=7,-1,0
  3918.5   0.045       0  4866.1    0.05       0  4976.9    0.05       0
  5001.6    0.05       0  5220.2    0.07       0  6915.8   0.035       0
  7090.1   0.045       0
Bank Sta=4976.9,5001.6
Exp/Cntr=0.3,0.1

Type RM Length L Ch R = 1,52723,569,569,569
BEGIN DESCRIPTION:
Alkali Creek 43.0
END DESCRIPTION:
XS GIS Cut Line= 3
      1365005.00      6966937.97      1364805.00      6965388.00
      1362604.99      6962987.99
#Sta/Elev= 30
  3436.9 1995.36  3467.1 1996.60  3497.4 1993.18  3648.6 1991.03  3729.3 1986.79
  3910.8 1985.96  3951.1 1983.27  4496.2 1973.77  4802.5 1963.36  4883.1 1964.36
  4950.2 1959.83  4950.7 1959.33  4974.9 1959.83  5077.7 1964.20  5147.4 1964.13
  5290.4 1963.90  6337.4 1964.84  6419.9 1964.93  6443.5 1967.47  6478.7 1965.36
  6655.7 1967.16  6946.1 1965.20  6974.5 1967.53  7158.2 1967.24  7208.2 1970.54
  7363.8 1969.91  7477.0 1974.09  7559.9 1972.91  7986.3 1981.93  8255.5 1991.26
#Mann=10,-1,0
  3436.9   0.045       0  4802.5    0.05       0  4950.2    0.05       0
  4974.9    0.05       0  5147.4    0.07       0  5290.4   0.045       0
  6337.4    0.07       0  6419.9   0.045       0  7363.8   0.035       0
  7559.9   0.045       0
Bank Sta=4950.2,4974.9
Exp/Cntr=0.3,0.1

Type RM Length L Ch R = 1,52154,1089,1089,1089
BEGIN DESCRIPTION:
Alkali Creek 42.0
END DESCRIPTION:
XS GIS Cut Line= 3
      1365054.99      6966788.04      1365305.00      6965238.00
      1362904.99      6962837.99
#Sta/Elev= 30
  3430.8 1992.14  3572.7 1986.91  3603.0 1988.49  3643.6 1985.32  3744.8 1985.74
  3856.3 1981.25  4129.8 1978.99  4190.5 1976.27  4261.4 1976.96  4754.4 1968.19
  4838.8 1964.18  4950.2 1963.27  5002.6 1959.84  5003.1 1959.34  5027.4 1959.84
  5114.0 1963.12  5172.8 1961.37  6952.5 1964.70  7009.1 1967.43  7108.1 1967.11
  7150.5 1970.16  7221.2 1969.68  7277.8 1973.55  7447.5 1975.48  7532.3 1979.41
  7687.9 1978.64  7832.7 1981.78  8029.8 1982.02  8126.3 1985.36  8395.0 1988.25
#Mann=7,-1,0
  3430.8   0.045       0  4754.4    0.05       0  5002.6    0.05       0
  5027.4    0.05       0  5172.8   0.045       0  7832.7   0.035       0
  8029.8   0.045       0
Bank Sta=5002.6,5027.4
Exp/Cntr=0.3,0.1

Type RM Length L Ch R = 1,51065,1102,1102,1102
BEGIN DESCRIPTION:
Alkali Creek 41.0
END DESCRIPTION:
XS GIS Cut Line= 3
      1365155.02      6966487.97      1366088.02      6964720.14
      1366421.49      6962507.66
#Sta/Elev= 30
  3224.2 1985.38  3279.9 1984.40  3348.5 1981.06  3645.1 1978.83  3705.5 1976.68
  3859.6 1976.77  4015.7 1973.51  4525.3 1970.18  4872.2 1962.90  4965.0 1961.14
  4976.8 1959.93  4987.0 1954.44  4987.5 1953.94  5011.8 1954.44  5031.1 1957.89
  5112.5 1959.65  5141.2 1962.06  5195.1 1959.97  6487.8 1956.94  6638.2 1957.68
  7025.4 1958.71  7055.7 1960.62  7086.1 1959.37  7126.5 1962.03  7197.3 1961.25
  7227.7 1963.81  7268.1 1962.15  7349.0 1965.38  7389.5 1963.65  7460.6 1964.68
#Mann=8,-1,0
  3224.2    0.07       0  3279.9   0.045       0  4872.2    0.07       0
  4987.0    0.07       0  5011.8    0.07       0  5195.1   0.045       0
  6487.8    0.07       0  6638.2   0.045       0
Bank Sta=4987,5011.8
Exp/Cntr=0.3,0.1

Type RM Length L Ch R = 1,49963,1653,1653,1653
BEGIN DESCRIPTION:
Alkali Creek 40.0
END DESCRIPTION:
XS GIS Cut Line= 3
      1365504.97      6966538.03      1366541.37      6965475.06
      1367064.22      6962177.25
#Sta/Elev= 30
  3515.4 1982.18  3529.5 1983.36  3549.2 1980.60  4116.4 1969.63  4696.4 1966.04
  4941.4 1962.04  4979.3 1957.57  4981.1 1952.46  4981.6 1951.96  5005.9 1952.46
  5007.2 1954.47  5088.1 1957.89  5199.5 1959.61  6918.0 1955.04  6952.7 1955.83
  7482.3 1956.13  7811.7 1958.61  7882.6 1961.06  7923.1 1959.56  7973.7 1962.16
  8058.2 1961.65  8085.1 1964.30  8120.5 1962.45  8156.0 1965.52  8187.9 1964.25
  8216.7 1967.05  8250.2 1966.09  8277.5 1969.18  8312.5 1968.16  8339.0 1971.17
#Mann=8,-1,0
  3515.4    0.07       0  3549.2   0.045       0  4941.4    0.07       0
  4981.1    0.07       0  5005.9    0.07       0  5199.5   0.045       0
  6918.0    0.07       0  6952.7   0.045       0
Bank Sta=4981.1,5005.9
Exp/Cntr=0.3,0.1