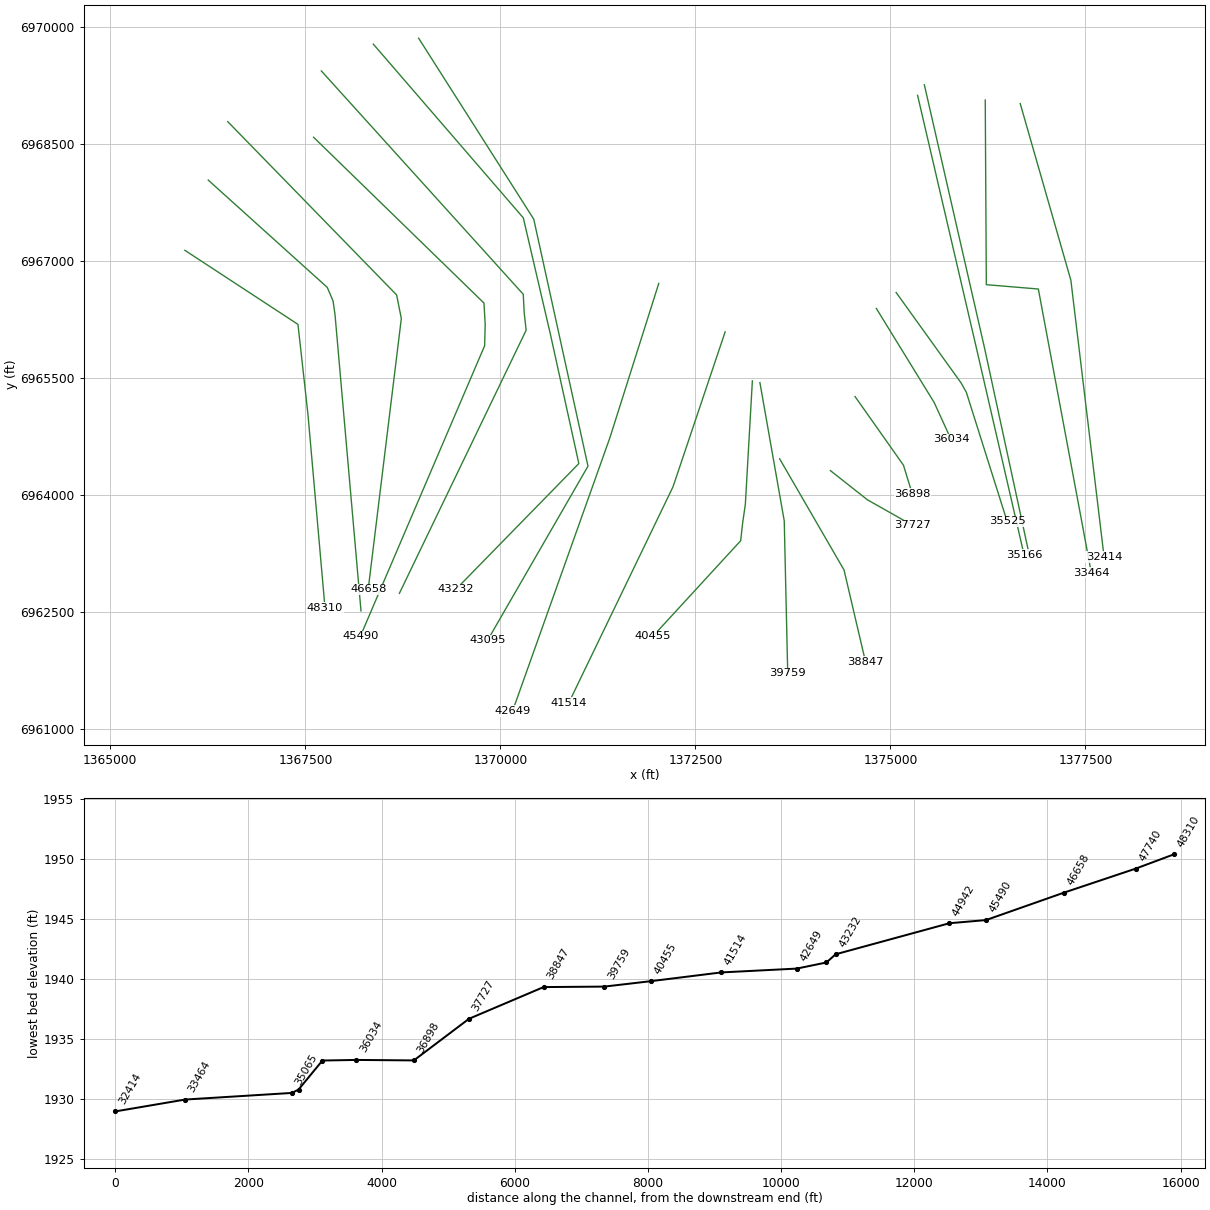
HEC-RAS study Alkali Creek.prj: Alkali Creek Base Level Engineering

--- Alkali Creek.g01 (geometry) --- (continued)

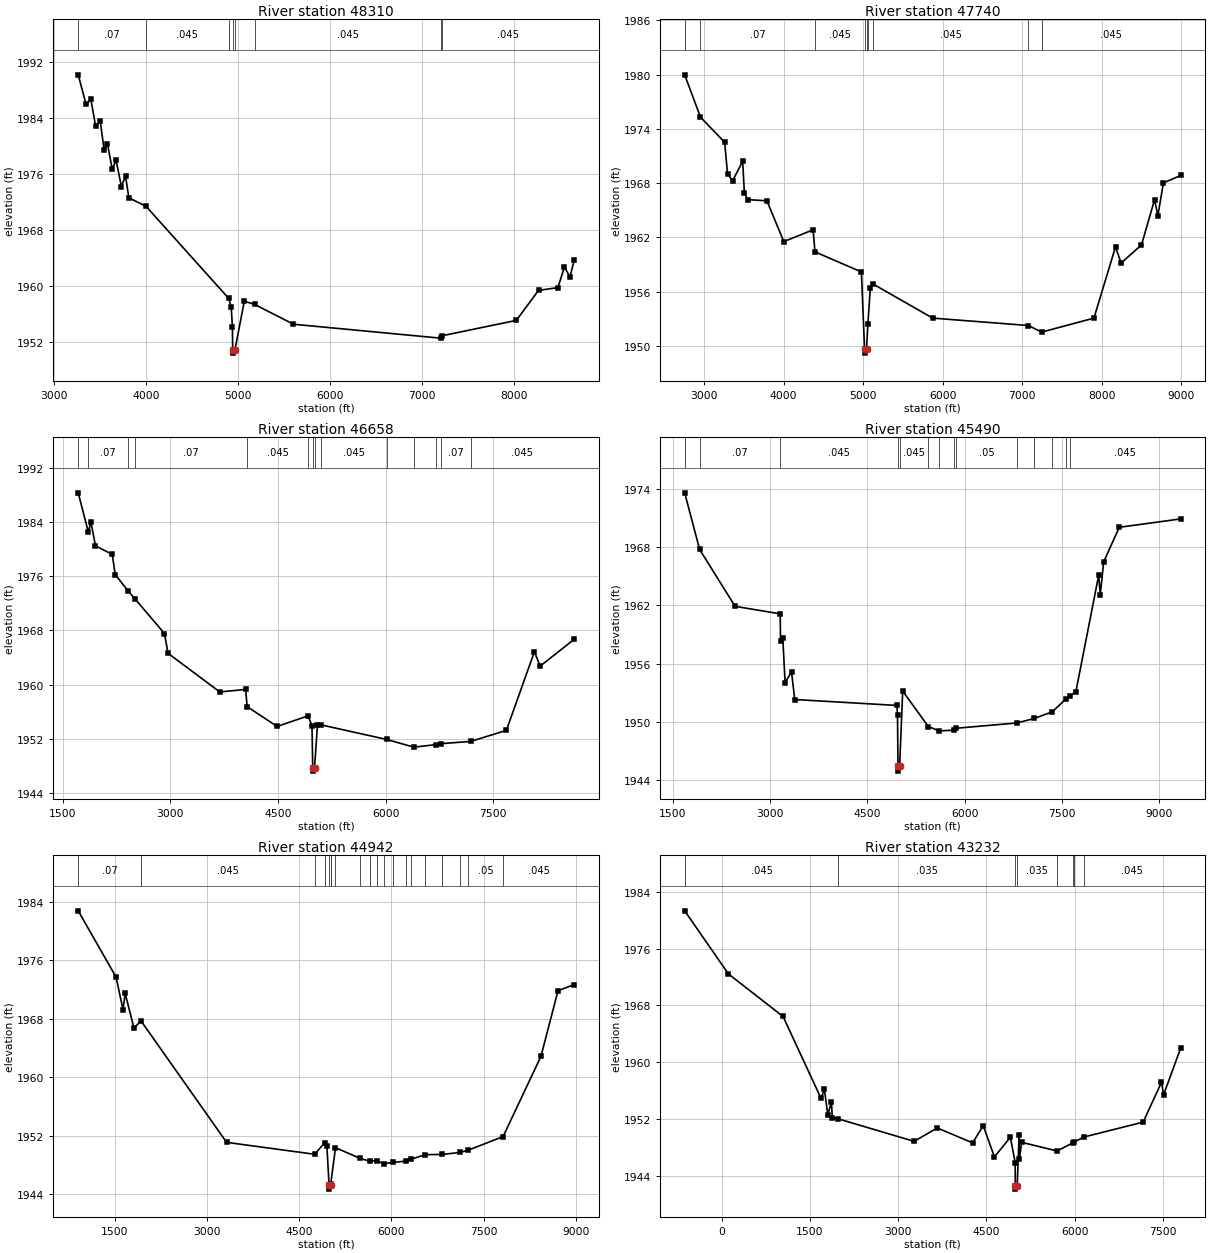
Type RM Length L Ch R = 1,48310,570,570,570
BEGIN DESCRIPTION:
Alkali Creek 39.0
END DESCRIPTION:
XS GIS Cut Line= 4
      1365955.02      6967137.99      1367405.00      6966188.00
      1367532.47      6965039.59      1367751.69      6962552.57
#Sta/Elev= 30
  3266.8 1990.18  3352.7 1985.94  3403.9 1986.72  3455.2 1982.86  3505.9 1983.55
  3548.7 1979.43  3584.8 1980.30  3636.1 1976.70  3678.3 1977.98  3735.5 1974.21
  3780.8 1975.71  3816.7 1972.60  4002.0 1971.40  4902.1 1958.21  4928.5 1956.97
  4941.4 1954.08  4944.1 1950.90  4944.6 1950.40  4969.0 1950.90  5070.7 1957.83
  5182.9 1957.36  5604.0 1954.53  7201.9 1952.54  7220.1 1952.89  8024.5 1955.08
  8265.5 1959.37  8476.3 1959.76  8546.6 1962.72  8606.8 1961.27  8652.4 1963.66
#Mann=8,-1,0
  3266.8    0.07       0  4002.0   0.045       0  4902.1   0.035       0
  4944.1   0.035       0  4969.0   0.035       0  5182.9   0.045       0
  7201.9    0.07       0  7220.1   0.045       0
Bank Sta=4944.1,4969
Exp/Cntr=0.3,0.1

Type RM Length L Ch R = 1,47740,1082,1082,1082
BEGIN DESCRIPTION:
Alkali Creek 38.0
END DESCRIPTION:
XS GIS Cut Line= 5
      1366254.98      6968038.02      1367780.00      6966663.00
      1367855.00      6966488.00      1367880.00      6966313.00
      1368212.97      6962512.41
#Sta/Elev= 30
  2756.5 1979.97  2954.5 1975.30  3259.1 1972.52  3295.0 1969.06  3358.5 1968.25
  3485.6 1970.42  3507.2 1966.91  3549.8 1966.18  3790.5 1966.05  4002.7 1961.54
  4371.2 1962.85  4394.9 1960.41  4978.5 1958.19  5018.1 1949.72  5018.6 1949.22
  5043.1 1949.72  5060.0 1952.43  5091.2 1956.46  5128.0 1956.84  5874.7 1953.09
  7078.2 1952.27  7244.0 1951.54  7902.5 1953.09  8173.5 1960.96  8243.8 1959.17
  8499.8 1961.17  8665.4 1966.19  8705.5 1964.38  8775.8 1968.03  8992.2 1968.85
#Mann=9,-1,0
  2756.5   0.035       0  2954.5    0.07       0  4394.9   0.045       0
  5018.1   0.045       0  5043.1   0.045       0  5060.0   0.035       0
  5128.0   0.045       0  7078.2    0.07       0  7244.0   0.045       0
Bank Sta=5018.1,5043.1
Exp/Cntr=0.3,0.1

Type RM Length L Ch R = 1,46658,1168,1168,1168
BEGIN DESCRIPTION:
Alkali Creek 37.0
END DESCRIPTION:
XS GIS Cut Line= 5
      1366504.98      6968788.03      1368669.75      6966565.46
      1368705.00      6966388.00      1368730.00      6966263.00
      1368305.00      6962787.98
#Sta/Elev= 30
  1716.5 1988.33  1857.5 1982.54  1893.4 1984.03  1956.9 1980.50  2190.4 1979.24
  2232.9 1976.25  2409.0 1973.86  2505.1 1972.70  2918.7 1967.54  2968.3 1964.62
  3689.5 1958.91  4050.1 1959.28  4070.8 1956.74  4488.6 1953.81  4918.6 1955.37
  4974.4 1953.94  4985.0 1947.71  4985.5 1947.21  5010.0 1947.71  5051.0 1954.00
  5099.0 1954.05  6015.3 1951.89  6394.6 1950.75  6699.1 1951.12  6773.2 1951.27
  7186.1 1951.60  7683.7 1953.23  8074.3 1964.85  8154.9 1962.73  8628.4 1966.68
#Mann=14,-1,0
  1716.5   0.035       0  1857.5    0.07       0  2409.0   0.035       0
  2505.1    0.07       0  4070.8   0.045       0  4918.6    0.07       0
  4985.0    0.07       0  5010.0    0.07       0  5099.0   0.045       0
  6015.3    0.05       0  6394.6    0.07       0  6699.1   0.035       0
  6773.2    0.07       0  7186.1   0.045       0
Bank Sta=4985,5010
Exp/Cntr=0.3,0.1

Type RM Length L Ch R = 1,45490,548,548,548
BEGIN DESCRIPTION:
Alkali Creek 36.0
END DESCRIPTION:
XS GIS Cut Line= 5
      1367604.98      6968588.02      1369789.54      6966461.29
      1369805.00      6966188.00      1369798.22      6965914.42
      1368205.01      6962188.03
#Sta/Elev= 30
  1681.9 1973.61  1912.5 1967.77  2459.9 1961.91  3154.9 1961.14  3160.0 1958.36
  3195.3 1958.60  3230.7 1954.05  3329.6 1955.17  3379.2 1952.31  4954.4 1951.70
  4964.4 1950.74  4971.9 1945.43  4972.4 1944.93  4996.9 1945.43  5044.5 1953.18
  5440.4 1949.52  5608.8 1949.08  5841.3 1949.15  5868.3 1949.35  6803.8 1949.89
  7074.2 1950.36  7350.6 1951.04  7558.4 1952.34  7618.7 1952.63  7715.7 1953.12
  8067.8 1965.14  8091.0 1963.08  8144.0 1966.49  8384.7 1970.06  9330.8 1970.92
#Mann=14,-1,0
  1681.9   0.035       0  1912.5    0.07       0  3154.9   0.045       0
  4971.9   0.045       0  4996.9   0.045       0  5440.4   0.035       0
  5608.8    0.05       0  5841.3   0.035       0  5868.3    0.05       0
  6803.8   0.035       0  7074.2    0.05       0  7350.6   0.045       0
  7558.4    0.05       0  7618.7   0.045       0
Bank Sta=4971.9,4996.9
Exp/Cntr=0.3,0.1

Type RM Length L Ch R = 1,44942,1710,1710,1710
BEGIN DESCRIPTION:
Alkali Creek 35.0
END DESCRIPTION:
XS GIS Cut Line= 5
      1367705.02      6969437.98      1370293.01      6966574.14
      1370305.00      6966338.00      1370330.00      6966113.00
      1368705.01      6962738.02
#Sta/Elev= 30
   903.7 1982.75  1519.8 1973.68  1632.6 1969.23  1668.5 1971.44  1809.7 1966.73
  1927.0 1967.67  3317.7 1951.07  4749.6 1949.44  4912.6 1951.01  4950.0 1950.54
  4985.1 1945.17  4985.6 1944.67  5010.1 1945.17  5012.6 1945.44  5089.5 1950.34
  5488.6 1948.88  5647.2 1948.49  5757.3 1948.58  5872.9 1948.16  6026.8 1948.32
  6230.1 1948.50  6316.7 1948.75  6547.4 1949.39  6823.9 1949.41  7112.5 1949.69
  7246.3 1949.99  7816.3 1951.86  8432.3 1962.84  8709.4 1971.81  8972.3 1972.66
#Mann=20,-1,0
   903.7    0.07       0  1927.0   0.045       0  4749.6    0.07       0
  4912.6   0.045       0  4985.1   0.045       0  5010.1   0.045       0
  5012.6    0.07       0  5089.5   0.045       0  5488.6   0.035       0
  5647.2    0.07       0  5757.3   0.035       0  5872.9   0.035       0
  6026.8    0.05       0  6230.1   0.035       0  6316.7    0.05       0
  6547.4   0.035       0  6823.9    0.05       0  7112.5   0.035       0
  7246.3    0.05       0  7816.3   0.045       0
Bank Sta=4985.1,5010.1
Exp/Cntr=0.3,0.1

Type RM Length L Ch R = 1,43232,137,137,137
BEGIN DESCRIPTION:
Alkali Creek 34.5
END DESCRIPTION:
XS GIS Cut Line= 5
      1368371.13      6969781.88      1370293.71      6967554.08
      1370640.93      6966061.03      1371005.52      6964403.04
      1369431.46      6962791.77
#Sta/Elev= 30
  -625.7 1981.33   117.5 1972.43  1045.6 1966.43  1691.0 1954.88  1747.7 1956.15
  1804.7 1952.60  1868.4 1954.31  1882.6 1952.13  1986.8 1951.98  3272.4 1948.82
  3666.1 1950.71  4266.1 1948.60  4446.3 1951.03  4636.7 1946.62  4907.6 1949.40
  4989.5 1945.80  4991.0 1942.58  4991.5 1942.08  5023.4 1942.58  5056.1 1949.67
  5061.2 1946.38  5099.9 1948.68  5703.1 1947.46  5976.6 1948.65  5990.6 1948.71
  6157.5 1949.43  7163.7 1951.53  7474.9 1957.15  7510.3 1955.37  7800.0 1961.95
#Mann=8,-1,0
  -625.7   0.045       0  1986.8   0.035       0  4991.0   0.035       0
  5023.4   0.035       0  5703.1    0.07       0  5976.6    0.05       0
  5990.6   0.035       0  6157.5   0.045       0
Bank Sta=4991,5023.4
Exp/Cntr=0.3,0.1

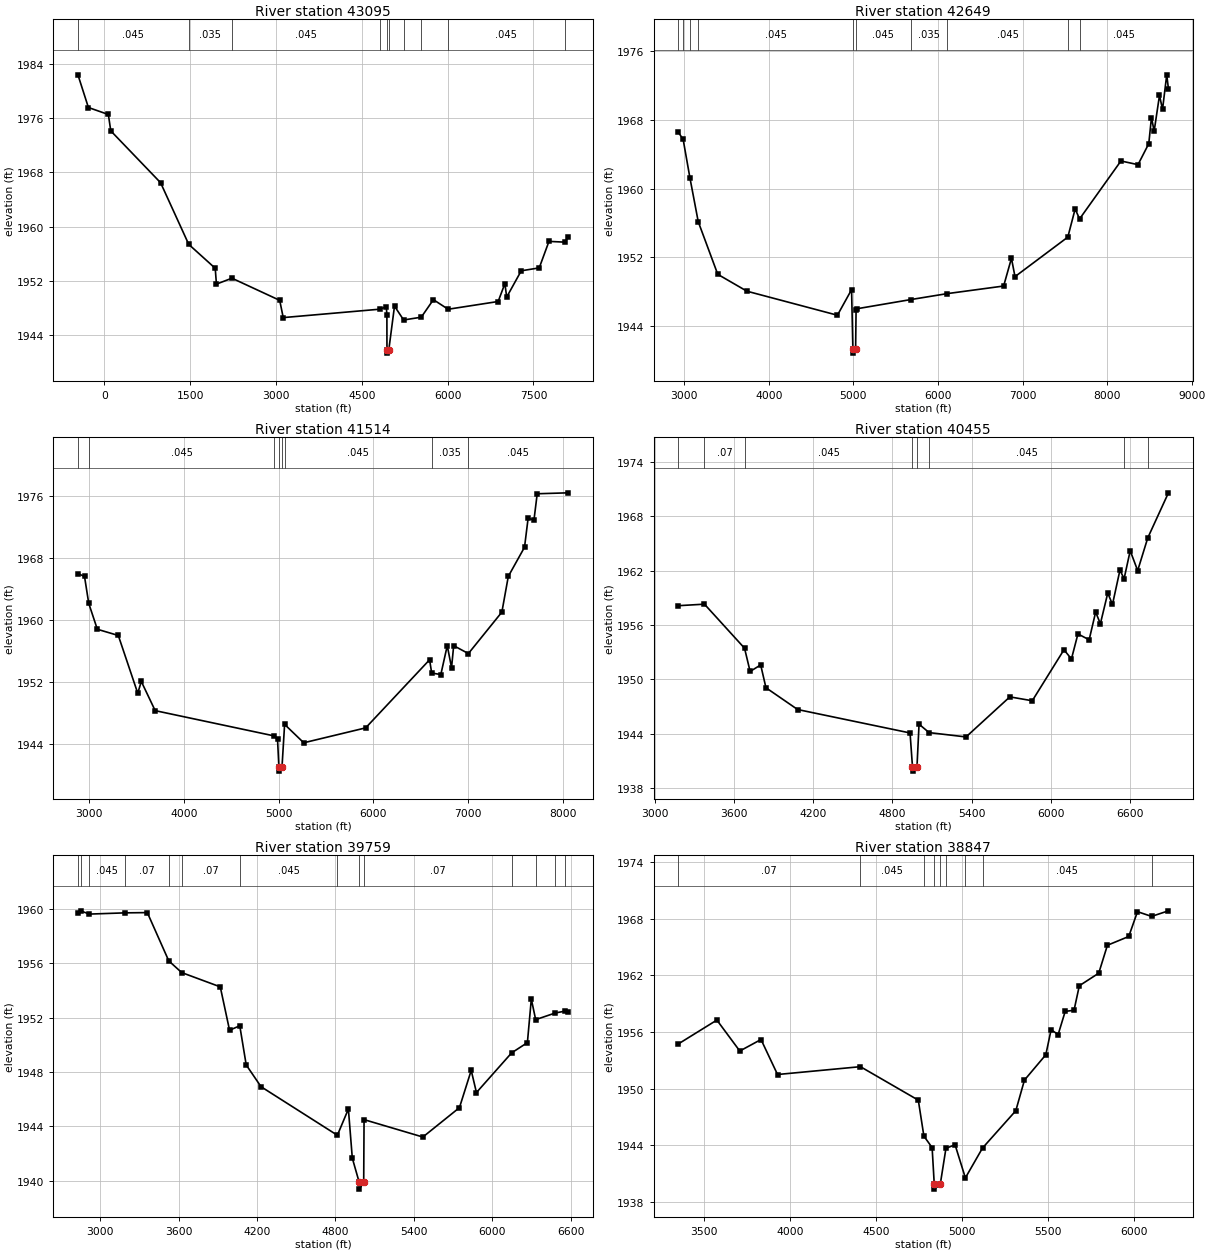
Type RM Length L Ch R = 1,43095,446,446,446
BEGIN DESCRIPTION:
Alkali Creek 34.3
END DESCRIPTION:
XS GIS Cut Line= 4
      1368952.17      6969857.90      1370427.67      6967536.89
      1371122.80      6964369.28      1369835.91      6962136.60
#Sta/Elev= 30
  -462.5 1982.37  -279.5 1977.56    69.4 1976.53   111.7 1974.12   982.2 1966.49
  1474.7 1957.41  1937.5 1953.89  1958.6 1951.56  2229.9 1952.43  3064.8 1949.17
  3126.2 1946.63  4815.8 1947.87  4928.1 1948.23  4938.3 1947.04  4939.6 1941.90
  4940.1 1941.40  4972.0 1941.90  5071.4 1948.32  5231.0 1946.28  5539.3 1946.69
  5751.2 1949.27  6008.8 1947.86  6883.3 1949.00  7001.1 1951.64  7032.6 1949.65
  7286.7 1953.52  7601.5 1953.95  7771.5 1957.85  8043.5 1957.74  8107.8 1958.46
#Mann=10,-1,0
  -462.5   0.045       0  1474.7   0.035       0  2229.9   0.045       0
  4815.8   0.035       0  4939.6   0.035       0  4972.0   0.035       0
  5231.0   0.045       0  5539.3   0.035       0  6008.8   0.045       0
  8043.5   0.035       0
Bank Sta=4939.6,4972
Exp/Cntr=0.3,0.1

Type RM Length L Ch R = 1,42649,1135,1135,1135
BEGIN DESCRIPTION:
Alkali Creek 34.0
END DESCRIPTION:
XS GIS Cut Line= 3
      1372030.01      6966713.04      1371405.00      6964738.00
      1370156.06      6961229.02
#Sta/Elev= 30
  2928.4 1966.55  2986.9 1965.72  3067.8 1961.22  3165.7 1956.15  3396.5 1950.04
  3741.3 1948.08  4811.2 1945.29  4978.6 1948.26  4993.9 1941.39  4994.4 1940.89
  5026.3 1941.39  5031.8 1945.88  5040.9 1946.04  5679.7 1947.11  6110.4 1947.80
  6776.2 1948.68  6868.7 1951.90  6910.6 1949.77  7535.1 1954.36  7621.8 1957.63
  7674.0 1956.47  8163.1 1963.20  8364.8 1962.77  8492.2 1965.21  8524.0 1968.24
  8555.8 1966.66  8618.8 1970.81  8654.9 1969.19  8704.4 1973.20  8724.6 1971.59
#Mann=10,-1,0
  2928.4    0.07       0  2986.9   0.045       0  3067.8    0.07       0
  3165.7   0.045       0  4993.9   0.045       0  5026.3   0.045       0
  5679.7   0.035       0  6110.4   0.045       0  7535.1   0.035       0
  7674.0   0.045       0
Bank Sta=4993.9,5026.3
Exp/Cntr=0.3,0.1

Type RM Length L Ch R = 1,41514,1059,1059,1059
BEGIN DESCRIPTION:
Alkali Creek 33.5
END DESCRIPTION:
XS GIS Cut Line= 3
      1372881.10      6966091.91      1372212.63      6964104.32
      1370875.81      6961332.65
#Sta/Elev= 30
  2880.8 1966.01  2950.3 1965.64  2994.8 1962.18  3085.4 1958.84  3306.9 1958.04
  3512.2 1950.60  3549.6 1952.12  3696.0 1948.36  4953.3 1945.10  4987.1 1944.73
  5001.9 1941.07  5002.4 1940.57  5034.4 1941.07  5062.0 1946.59  5264.0 1944.22
  5917.4 1946.14  6592.1 1954.91  6614.3 1953.20  6710.7 1953.01  6778.6 1956.73
  6823.8 1953.89  6846.4 1956.73  7001.5 1955.71  7355.0 1961.05  7422.8 1965.65
  7593.9 1969.40  7631.9 1973.13  7693.8 1972.91  7727.9 1976.29  8055.0 1976.41
#Mann=8,-1,0
  2880.8    0.07       0  2994.8   0.045       0  4953.3    0.07       0
  5001.9    0.07       0  5034.4    0.07       0  5062.0   0.045       0
  6614.3   0.035       0  7001.5   0.045       0
Bank Sta=5001.9,5034.4
Exp/Cntr=0.3,0.1

Type RM Length L Ch R = 1,40455,696,696,696
BEGIN DESCRIPTION:
Alkali Creek 33.0
END DESCRIPTION:
XS GIS Cut Line= 5
      1373230.00      6965463.02      1373140.24      6963883.17
      1373105.00      6963638.00      1373080.00      6963413.00
      1371954.99      6962187.99
#Sta/Elev= 30
  3174.3 1958.13  3373.8 1958.30  3677.9 1953.43  3720.2 1950.86  3800.3 1951.58
  3840.4 1949.06  4080.8 1946.65  4933.7 1944.06  4952.0 1940.34  4952.7 1939.84
  4986.3 1940.34  5001.9 1945.03  5078.2 1944.10  5358.4 1943.62  5690.7 1948.05
  5860.9 1947.62  6101.4 1953.26  6158.1 1952.24  6207.4 1955.01  6292.5 1954.36
  6341.8 1957.43  6377.6 1956.13  6433.7 1959.53  6469.5 1958.27  6526.2 1962.07
  6557.6 1961.11  6603.9 1964.21  6660.6 1962.01  6737.0 1965.62  6894.0 1970.61
#Mann=8,-1,0
  3174.3   0.045       0  3373.8    0.07       0  3677.9   0.045       0
  4952.0    0.07       0  4986.3   0.045       0  5078.2   0.045       0
  6557.6   0.035       0  6737.0   0.045       0
Bank Sta=4952,4986.3
Exp/Cntr=0.3,0.1

Type RM Length L Ch R = 1,39759,912,912,912
BEGIN DESCRIPTION:
Alkali Creek 32.1
END DESCRIPTION:
XS GIS Cut Line= 3
      1373326.75      6965441.22      1373638.70      6963667.58
      1373683.26      6961715.66
#Sta/Elev= 30
  2828.2 1959.67  2849.5 1959.85  2914.7 1959.61  3187.2 1959.70  3359.5 1959.72
  3523.7 1956.17  3622.7 1955.31  3917.9 1954.26  3989.0 1951.07  4067.2 1951.40
  4116.5 1948.52  4230.0 1946.92  4814.4 1943.35  4898.7 1945.28  4928.7 1941.67
  4981.5 1939.89  4982.2 1939.39  5015.9 1939.89  5018.7 1944.50  5468.9 1943.22
  5748.9 1945.38  5839.0 1948.12  5879.0 1946.49  6148.7 1949.41  6269.1 1950.16
  6299.1 1953.36  6332.5 1951.85  6482.6 1952.34  6559.1 1952.48  6581.5 1952.38
#Mann=14,-1,0
  2828.2   0.045       0  2849.5    0.07       0  2914.7   0.045       0
  3187.2    0.07       0  3523.7   0.045       0  3622.7    0.07       0
  4067.2   0.045       0  4814.4    0.07       0  4981.5   0.045       0
  5015.9    0.07       0  6148.7   0.035       0  6332.5   0.045       0
  6482.6    0.07       0  6559.1   0.045       0
Bank Sta=4981.5,5015.9
Exp/Cntr=0.3,0.1

Type RM Length L Ch R = 1,38847,1120,1120,1120
BEGIN DESCRIPTION:
Alkali Creek 32.0
END DESCRIPTION:
XS GIS Cut Line= 3
      1373579.99      6964463.01      1374405.00      6963038.00
      1374679.99      6961863.05
#Sta/Elev= 30
  3348.7 1954.73  3574.0 1957.27  3707.4 1953.99  3830.9 1955.21  3927.0 1951.50
  4409.4 1952.33  4746.3 1948.78  4778.8 1944.97  4826.7 1943.75  4839.2 1939.85
  4839.9 1939.35  4874.0 1939.85  4907.1 1943.67  4960.1 1944.06  5020.2 1940.54
  5120.1 1943.71  5313.7 1947.66  5364.1 1950.91  5488.3 1953.59  5519.1 1956.24
  5560.2 1955.74  5601.2 1958.19  5652.6 1958.31  5683.4 1960.91  5796.4 1962.24
  5846.8 1965.20  5971.0 1966.13  6021.9 1968.76  6103.9 1968.26  6202.0 1968.85
#Mann=9,-1,0
  3348.7    0.07       0  4409.4   0.045       0  4778.8    0.07       0
  4839.2   0.045       0  4874.0    0.07       0  4907.1   0.045       0
  5020.2    0.07       0  5120.1   0.045       0  6103.9   0.035       0
Bank Sta=4839.2,4874
Exp/Cntr=0.3,0.1

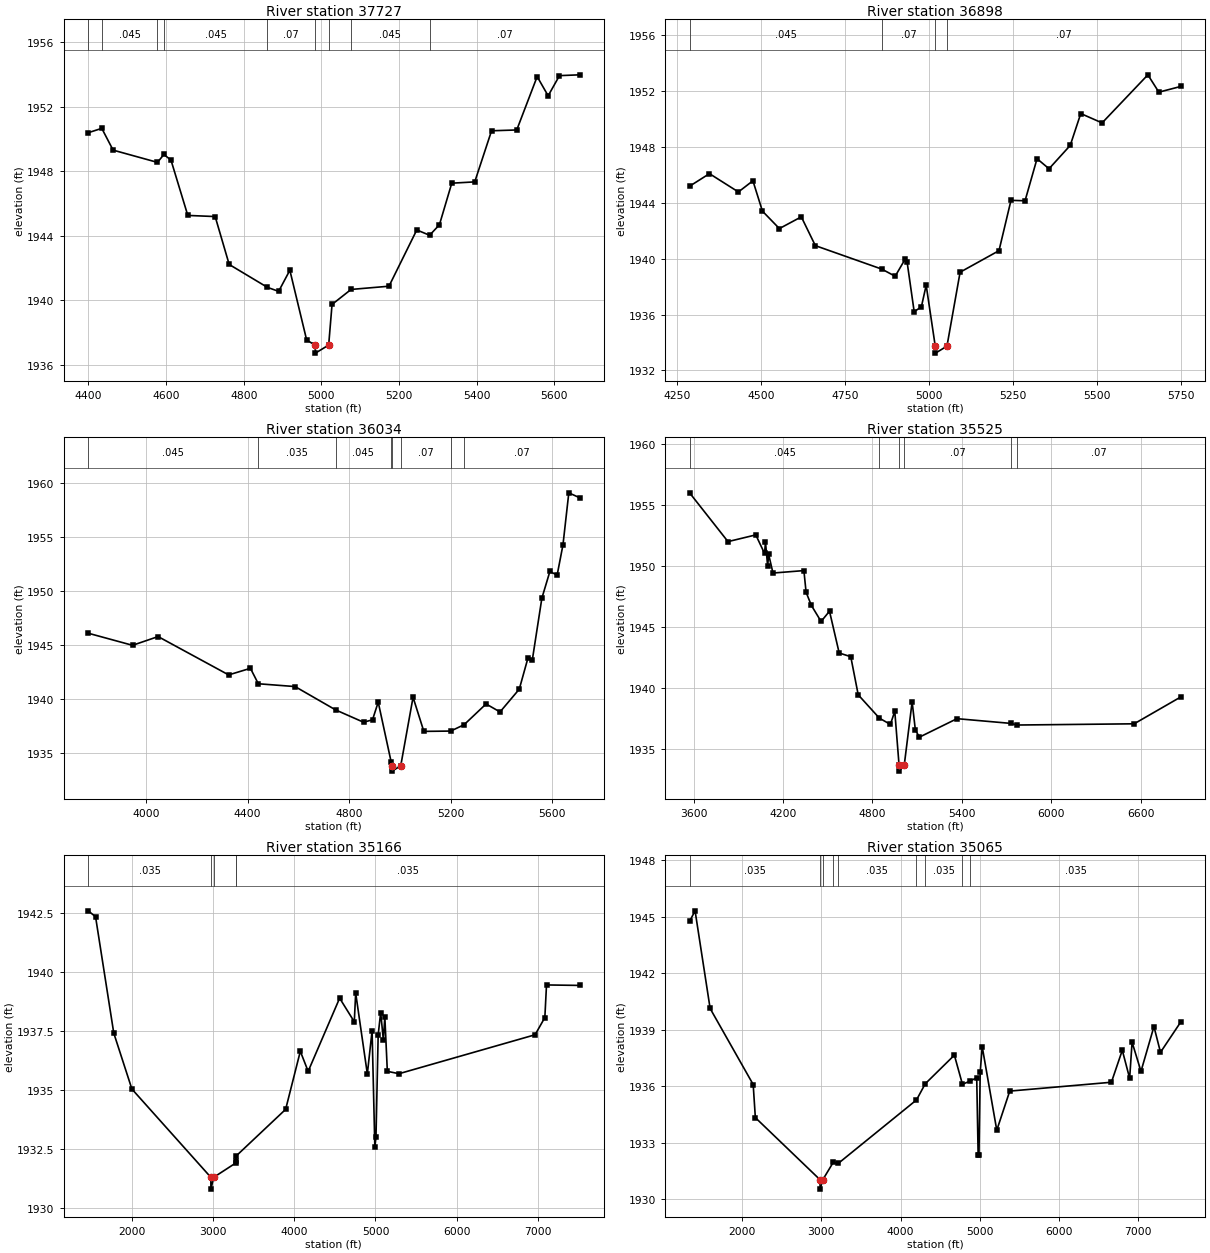
Type RM Length L Ch R = 1,37727,829,829,829
BEGIN DESCRIPTION:
Alkali Creek 31.0
END DESCRIPTION:
XS GIS Cut Line= 3
      1374230.03      6964312.98      1374705.00      6963938.00
      1375279.96      6963613.02
#Sta/Elev= 30
  4399.4 1950.38  4434.3 1950.65  4463.5 1949.30  4577.8 1948.54  4594.3 1949.03
  4612.6 1948.68  4655.9 1945.25  4726.4 1945.18  4762.5 1942.21  4860.9 1940.79
  4889.9 1940.54  4918.8 1941.85  4962.1 1937.52  4983.9 1937.21  4984.7 1936.71
  5018.8 1937.21  5027.5 1939.73  5076.5 1940.66  5174.2 1940.86  5245.8 1944.35
  5278.8 1944.02  5304.1 1944.67  5335.9 1947.25  5395.1 1947.33  5438.4 1950.50
  5503.3 1950.55  5555.9 1953.86  5584.2 1952.67  5613.4 1953.92  5665.0 1953.97
#Mann=9,-1,0
  4399.4    0.07       0  4434.3   0.045       0  4577.8    0.07       0
  4594.3   0.045       0  4860.9    0.07       0  4983.9    0.07       0
  5018.8    0.07       0  5076.5   0.045       0  5278.8    0.07       0
Bank Sta=4983.9,5018.8
Exp/Cntr=0.3,0.1

Type RM Length L Ch R = 1,36898,864,864,864
BEGIN DESCRIPTION:
Alkali Creek 30.6
END DESCRIPTION:
XS GIS Cut Line= 3
      1374546.40      6965262.15      1375167.00      6964381.91
      1375279.99      6964013.05
#Sta/Elev= 30
  4287.8 1945.18  4347.0 1946.08  4433.2 1944.77  4476.4 1945.57  4504.7 1943.40
  4555.2 1942.15  4620.5 1942.99  4662.3 1940.93  4860.2 1939.25  4900.0 1938.74
  4929.1 1939.94  4935.7 1939.73  4956.6 1936.20  4978.1 1936.56  4992.3 1938.10
  5019.3 1933.74  5020.0 1933.24  5054.2 1933.74  5093.3 1939.03  5209.1 1940.57
  5244.8 1944.17  5286.7 1944.14  5322.4 1947.15  5358.1 1946.43  5421.2 1948.10
  5452.6 1950.38  5516.1 1949.71  5652.4 1953.15  5685.1 1951.91  5750.6 1952.32
#Mann=4,-1,0
  4287.8   0.045       0  4860.2    0.07       0  5019.3    0.07       0
  5054.2    0.07       0
Bank Sta=5019.3,5054.2
Exp/Cntr=0.3,0.1

Type RM Length L Ch R = 1,36034,509,509,509
BEGIN DESCRIPTION:
Alkali Creek 30.2
END DESCRIPTION:
XS GIS Cut Line= 3
      1374818.98      6966392.62      1375561.63      6965184.23
      1375776.74      6964712.96
#Sta/Elev= 30
  3771.5 1946.05  3946.2 1944.93  4046.9 1945.74  4325.0 1942.19  4410.8 1942.80
  4441.9 1941.37  4586.8 1941.11  4746.5 1938.95  4856.5 1937.81  4892.0 1938.03
  4914.5 1939.67  4965.6 1934.12  4968.4 1933.78  4969.2 1933.28  5003.3 1933.78
  5051.8 1940.12  5094.3 1936.96  5200.3 1936.99  5253.1 1937.58  5339.6 1939.50
  5394.6 1938.76  5470.5 1940.87  5504.5 1943.74  5522.0 1943.59  5559.5 1949.29
  5591.1 1951.77  5619.7 1951.43  5642.7 1954.23  5665.7 1959.05  5707.9 1958.60
#Mann=8,-1,0
  3771.5   0.045       0  4441.9   0.035       0  4746.5   0.045       0
  4965.6    0.07       0  4968.4    0.07       0  5003.3    0.07       0
  5200.3   0.045       0  5253.1    0.07       0
Bank Sta=4968.4,5003.3
Exp/Cntr=0.3,0.1

Type RM Length L Ch R = 1,35525,359,359,359
BEGIN DESCRIPTION:
Alkali Creek 30.0
END DESCRIPTION:
XS GIS Cut Line= 4
      1375072.83      6966597.03      1375905.00      6965438.00
      1375972.93      6965317.27      1376494.69      6963664.96
#Sta/Elev= 30
  3572.7 1955.99  3830.6 1952.00  4017.2 1952.55  4076.2 1951.03  4082.3 1951.97
  4097.0 1949.97  4103.2 1950.97  4132.7 1949.43  4340.2 1949.63  4354.9 1947.86
  4390.5 1946.78  4455.6 1945.47  4512.1 1946.31  4577.1 1942.89  4654.8 1942.59
  4704.9 1939.47  4847.2 1937.56  4921.0 1937.05  4950.3 1938.13  4979.0 1933.73
  4979.7 1933.23  5014.0 1933.73  5066.8 1938.90  5088.5 1936.59  5115.9 1936.01
  5368.0 1937.52  5733.1 1937.13  5769.2 1937.00  6557.3 1937.10  6870.8 1939.30
#Mann=6,-1,0
  3572.7   0.045       0  4847.2    0.07       0  4979.0    0.07       0
  5014.0    0.07       0  5733.1   0.035       0  5769.2    0.07       0
Bank Sta=4979,5014
Exp/Cntr=0.3,0.1

Type RM Length L Ch R = 1,35166,101,101,101
BEGIN DESCRIPTION:
Alkali Creek 29.5
END DESCRIPTION:
XS GIS Cut Line= 3
      1375347.95      6969125.81      1376096.46      6965908.23
      1376713.20      6963231.98
#Sta/Elev= 30
  1462.6 1942.60  1552.8 1942.35  1777.1 1937.42  2000.3 1935.05  2972.6 1931.31
  2973.4 1930.81  3007.6 1931.31  3276.2 1931.91  3278.6 1932.02  3286.0 1932.22
  3893.6 1934.19  4074.4 1936.65  4170.8 1935.80  4558.5 1938.90  4739.1 1937.90
  4756.1 1939.12  4899.7 1935.69  4958.1 1937.52  4992.1 1932.58  5006.0 1933.01
  5033.2 1937.35  5063.9 1938.29  5096.7 1937.14  5115.2 1938.10  5146.0 1935.80
  5289.7 1935.70  6965.7 1937.35  7085.6 1938.08  7106.1 1939.46  7512.5 1939.44
#Mann=6,-1,0
  1462.6   0.035       0  2972.6   0.035       0  3007.6   0.035       0
  3276.2    0.07       0  3278.6   0.045       0  3286.0   0.035       0
Bank Sta=2972.6,3007.6
Exp/Cntr=0.3,0.1

Type RM Length L Ch R = 1,35065,1601,1601,1601
BEGIN DESCRIPTION:
Alkali Creek 29.4
END DESCRIPTION:
XS GIS Cut Line= 3
      1375434.58      6969261.06      1376206.05      6965885.45
      1376785.31      6963205.99
#Sta/Elev= 30
  1335.8 1944.76  1405.3 1945.32  1595.4 1940.13  2139.1 1936.09  2166.4 1934.33
  2983.2 1931.03  2984.0 1930.53  3018.2 1931.03  3149.6 1931.95  3214.4 1931.90
  4201.4 1935.27  4312.1 1936.13  4679.7 1937.65  4781.8 1936.10  4881.4 1936.28
  4961.9 1936.45  4980.0 1932.33  4990.2 1932.34  5006.0 1936.75  5031.2 1938.10
  5215.3 1933.66  5379.0 1935.74  6662.9 1936.21  6800.4 1937.91  6893.2 1936.42
  6923.9 1938.34  7036.4 1936.79  7200.1 1939.17  7282.6 1937.80  7539.8 1939.42
#Mann=9,-1,0
  1335.8   0.035       0  2983.2   0.035       0  3018.2   0.035       0
  3149.6    0.07       0  3214.4   0.035       0  4201.4   0.045       0
  4312.1   0.035       0  4781.8    0.07       0  4881.4   0.035       0
Bank Sta=2983.2,3018.2
Exp/Cntr=0.3,0.1

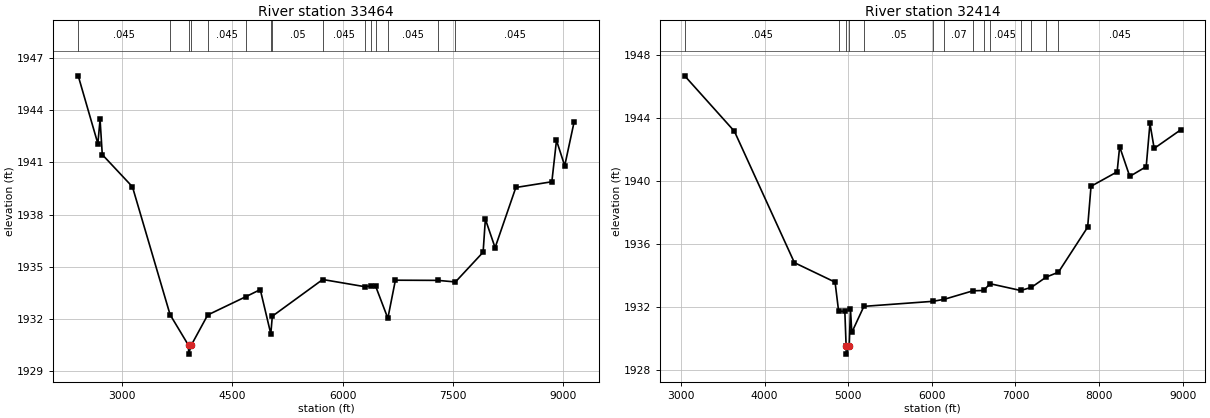
Type RM Length L Ch R = 1,33464,1050,1050,1050
BEGIN DESCRIPTION:
Alkali Creek 29.3
END DESCRIPTION:
XS GIS Cut Line= 4
      1376215.42      6969065.02      1376229.31      6966697.01
      1376895.97      6966641.45      1377574.97      6963001.88
#Sta/Elev= 30
  2405.5 1945.98  2672.5 1942.08  2702.5 1943.47  2732.5 1941.45  3142.5 1939.60
  3653.8 1932.25  3905.0 1930.48  3905.8 1929.98  3940.0 1930.48  4165.0 1932.23
  4687.3 1933.29  4879.6 1933.69  5022.8 1931.14  5043.1 1932.16  5728.2 1934.27
  6296.8 1933.86  6387.3 1933.90  6445.8 1933.90  6613.1 1932.04  6715.6 1934.23
  7291.6 1934.22  7531.7 1934.13  7907.8 1935.84  7938.3 1937.74  8070.6 1936.10
  8352.4 1939.56  8841.9 1939.89  8904.7 1942.27  9016.6 1940.81  9144.9 1943.34
#Mann=15,-1,0
  2405.5   0.045       0  3653.8    0.07       0  3905.0    0.07       0
  3940.0    0.07       0  4165.0   0.045       0  4687.3    0.07       0
  5022.8   0.045       0  5043.1    0.05       0  5728.2   0.045       0
  6296.8    0.07       0  6387.3   0.045       0  6445.8    0.07       0
  6613.1   0.045       0  7291.6    0.07       0  7531.7   0.045       0
Bank Sta=3905,3940
Exp/Cntr=0.3,0.1

Type RM Length L Ch R = 1,32414,849,849,849
BEGIN DESCRIPTION:
Alkali Creek 29.2
END DESCRIPTION:
XS GIS Cut Line= 3
      1376663.73      6969019.80      1377313.03      6966753.59
      1377739.00      6963203.85
#Sta/Elev= 30
  3043.1 1946.70  3637.9 1943.17  4355.7 1934.81  4842.1 1933.57  4884.6 1931.72
  4959.0 1931.71  4974.4 1929.49  4975.3 1928.99  5011.1 1929.49  5026.5 1931.84
  5042.2 1930.37  5186.9 1932.03  6012.6 1932.35  6148.8 1932.48  6492.0 1933.02
  6617.8 1933.04  6696.6 1933.47  7062.0 1933.04  7191.0 1933.24  7369.7 1933.90
  7513.7 1934.20  7863.6 1937.07  7903.9 1939.67  8216.1 1940.59  8246.4 1942.19
  8367.2 1940.30  8564.0 1940.92  8608.9 1943.67  8659.3 1942.08  8975.7 1943.26
#Mann=14,-1,0
  3043.1   0.045       0  4884.6    0.07       0  4974.4    0.07       0
  5011.1    0.07       0  5186.9    0.05       0  6012.6   0.045       0
  6148.8    0.07       0  6492.0   0.045       0  6617.8    0.07       0
  6696.6   0.045       0  7062.0    0.07       0  7191.0   0.045       0
  7369.7    0.07       0  7513.7   0.045       0
Bank Sta=4974.4,5011.1
Exp/Cntr=0.3,0.1