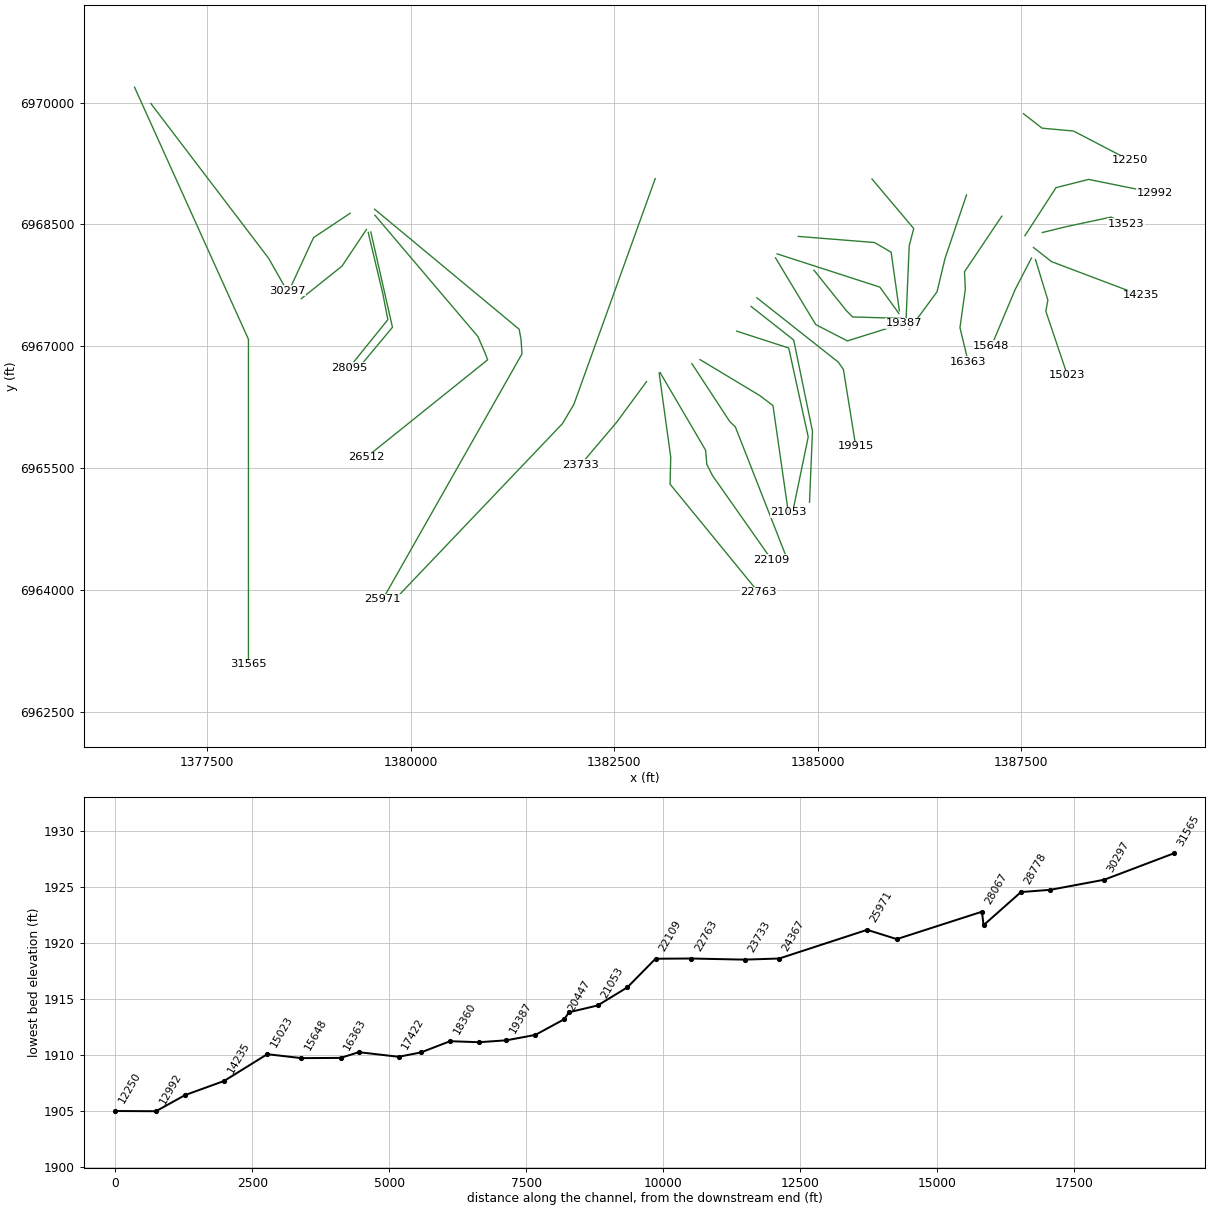
HEC-RAS study Alkali Creek.prj: Alkali Creek Base Level Engineering

--- Alkali Creek.g01 (geometry) --- (continued)

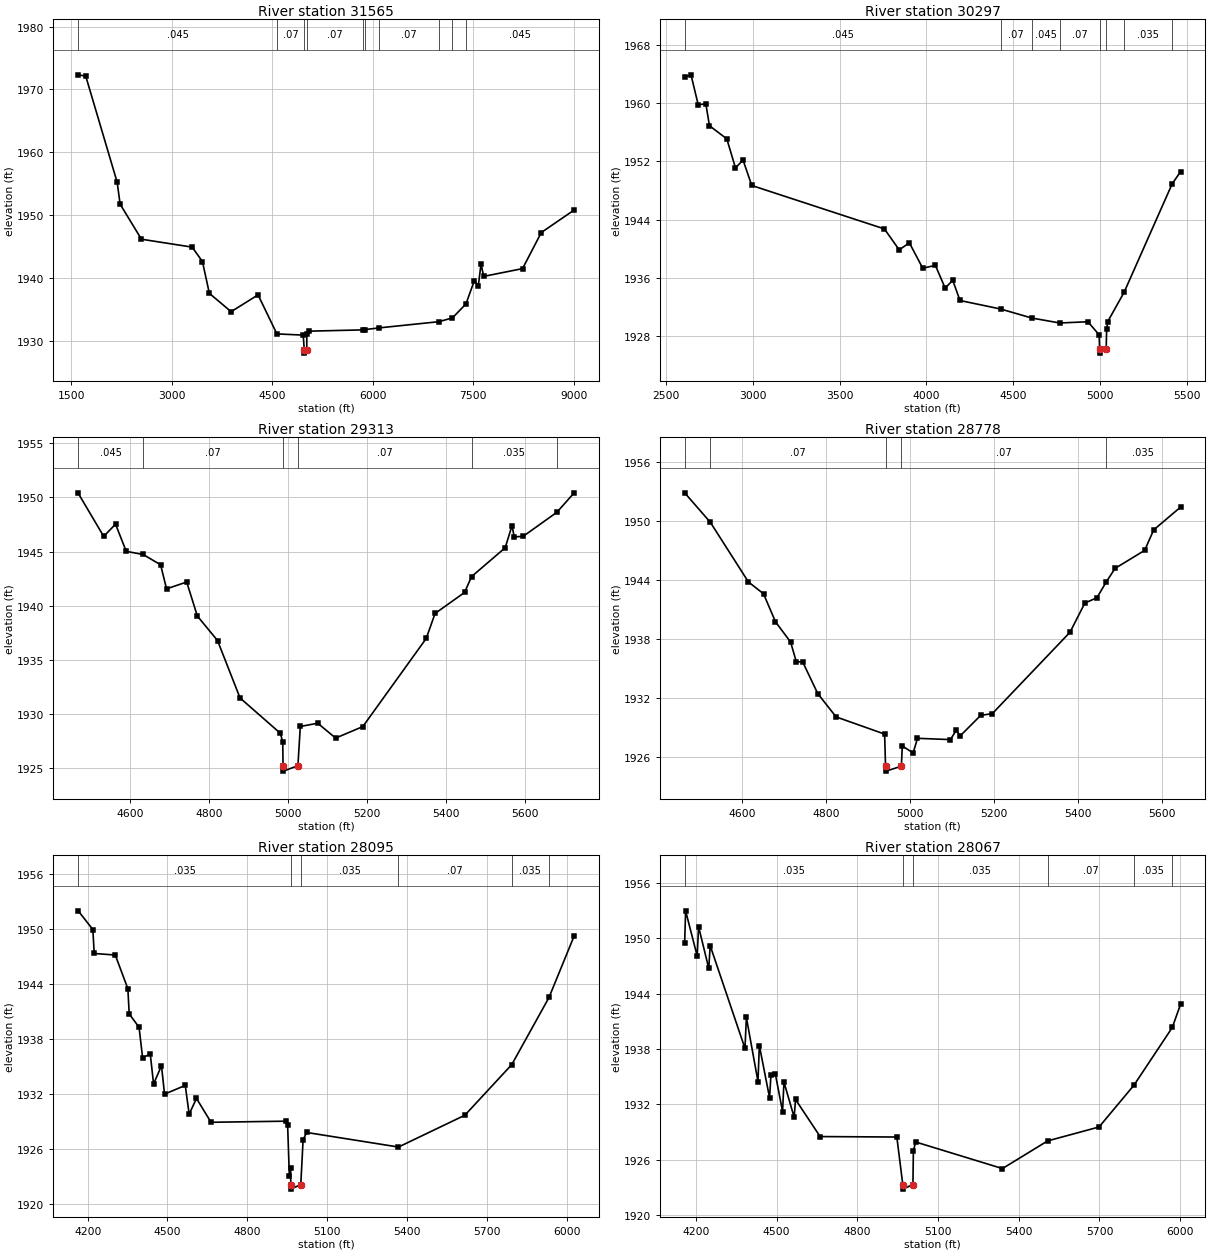
Type RM Length L Ch R = 1,31565,1268,1268,1268
BEGIN DESCRIPTION:
Alkali Creek 28.0
END DESCRIPTION:
XS GIS Cut Line= 3
      1376605.01      6970187.97      1378005.00      6967088.00
      1378005.00      6963088.04
#Sta/Elev= 30
  1602.4 1972.32  1714.6 1972.12  2183.9 1955.20  2227.8 1951.72  2546.0 1946.14
  3303.1 1944.88  3456.1 1942.59  3559.6 1937.52  3884.6 1934.60  4286.1 1937.28
  4567.6 1931.06  4959.9 1930.87  4976.6 1928.50  4977.5 1928.00  5013.4 1928.50
  5013.8 1931.10  5053.8 1931.50  5846.6 1931.70  5884.1 1931.75  6093.4 1932.02
  6987.8 1933.01  7188.1 1933.62  7389.4 1935.84  7513.8 1939.54  7573.8 1938.74
  7613.8 1942.20  7653.8 1940.22  8233.8 1941.46  8513.8 1947.21  9003.8 1950.79
#Mann=10,-1,0
  1602.4   0.045       0  4567.6    0.07       0  4976.6    0.07       0
  5013.4    0.07       0  5846.6    0.07       0  5884.1   0.045       0
  6093.4    0.07       0  6987.8   0.045       0  7188.1    0.07       0
  7389.4   0.045       0
Bank Sta=4976.6,5013.4
Exp/Cntr=0.3,0.1

Type RM Length L Ch R = 1,30297,984,984,984
BEGIN DESCRIPTION:
Alkali Creek 27.0
END DESCRIPTION:
XS GIS Cut Line= 3
      1376804.99      6969988.01      1378252.72      6968084.29
      1378480.24      6967683.42
#Sta/Elev= 30
  2609.3 1963.58  2645.7 1963.88  2687.3 1959.75  2730.9 1959.91  2751.8 1956.89
  2851.6 1955.08  2901.5 1951.10  2945.1 1952.17  2995.0 1948.68  3758.2 1942.71
  3843.4 1939.83  3901.6 1940.81  3978.7 1937.31  4051.3 1937.71  4107.5 1934.58
  4151.1 1935.66  4192.8 1932.88  4426.5 1931.71  4606.1 1930.47  4766.8 1929.79
  4928.8 1929.96  4993.3 1928.16  4996.1 1926.15  4997.1 1925.65  5033.5 1926.15
  5036.5 1928.96  5042.7 1929.99  5136.5 1933.99  5413.2 1948.90  5461.9 1950.59
#Mann=8,-1,0
  2609.3   0.045       0  4426.5    0.07       0  4606.1   0.045       0
  4766.8    0.07       0  4996.1    0.07       0  5033.5    0.07       0
  5136.5   0.035       0  5413.2    0.07       0
Bank Sta=4996.1,5033.5
Exp/Cntr=0.3,0.1

Type RM Length L Ch R = 1,29313,535,535,535
BEGIN DESCRIPTION:
Alkali Creek 26.0
END DESCRIPTION:
XS GIS Cut Line= 3
      1379254.98      6968637.99      1378805.00      6968338.00
      1378505.00      6967688.00
#Sta/Elev= 30
  4467.6 1950.39  4532.2 1946.41  4562.2 1947.54  4589.3 1945.03  4632.1 1944.74
  4676.4 1943.79  4691.4 1941.57  4742.5 1942.20  4769.5 1939.06  4820.6 1936.80
  4877.7 1931.50  4979.9 1928.24  4985.9 1927.42  4986.6 1925.25  4987.5 1924.75
  5024.3 1925.25  5030.4 1928.87  5074.5 1929.17  5119.9 1927.80  5188.8 1928.86
  5349.4 1936.99  5371.9 1939.30  5446.7 1941.24  5464.3 1942.70  5549.5 1945.36
  5566.9 1947.41  5572.4 1946.36  5595.3 1946.42  5680.7 1948.64  5724.3 1950.43
#Mann=6,-1,0
  4467.6   0.045       0  4632.1    0.07       0  4986.6    0.07       0
  5024.3    0.07       0  5464.3   0.035       0  5680.7    0.07       0
Bank Sta=4986.6,5024.3
Exp/Cntr=0.3,0.1

Type RM Length L Ch R = 1,28778,683,683,683
BEGIN DESCRIPTION:
Alkali Creek 25.0
END DESCRIPTION:
XS GIS Cut Line= 3
      1379455.01      6968438.01      1379155.00      6967988.00
      1378654.97      6967587.98
#Sta/Elev= 30
  4464.1 1952.88  4525.2 1949.88  4615.9 1943.81  4651.9 1942.60  4680.4 1939.75
  4716.5 1937.68  4730.0 1935.67  4745.0 1935.68  4781.1 1932.44  4824.7 1930.07
  4940.3 1928.32  4942.5 1925.05  4943.5 1924.55  4980.2 1925.05  4982.4 1927.11
  5008.2 1926.40  5018.6 1927.89  5097.0 1927.76  5111.4 1928.74  5119.4 1928.10
  5169.0 1930.22  5197.0 1930.41  5381.9 1938.69  5417.2 1941.66  5446.0 1942.20
  5467.9 1943.79  5489.2 1945.19  5559.6 1947.02  5581.2 1949.11  5645.3 1951.43
#Mann=5,-1,0
  4464.1   0.035       0  4525.2    0.07       0  4942.5    0.07       0
  4980.2    0.07       0  5467.9   0.035       0
Bank Sta=4942.5,4980.2
Exp/Cntr=0.3,0.1

Type RM Length L Ch R = 1,28095,28,28,28
BEGIN DESCRIPTION:
Alkali Creek 24.0
END DESCRIPTION:
XS GIS Cut Line= 4
      1379476.53      6968403.43      1379656.43      6967648.69
      1379718.44      6967329.31      1379240.22      6966735.96
#Sta/Elev= 30
  4164.6 1951.94  4219.6 1949.90  4224.7 1947.29  4303.8 1947.12  4351.1 1943.45
  4356.2 1940.70  4393.2 1939.24  4406.6 1935.90  4435.3 1936.34  4447.7 1933.06
  4477.5 1935.05  4488.9 1931.95  4566.8 1932.90  4581.4 1929.77  4609.0 1931.48
  4663.6 1928.88  4943.4 1929.00  4951.4 1928.56  4957.8 1923.07  4962.9 1923.88
  4963.1 1922.09  4964.0 1921.59  5000.8 1922.09  5009.5 1926.95  5022.7 1927.77
  5367.9 1926.18  5617.3 1929.65  5793.5 1935.17  5933.4 1942.49  6027.9 1949.20
#Mann=6,-1,0
  4164.6   0.035       0  4963.1   0.035       0  5000.8   0.035       0
  5367.9    0.07       0  5793.5   0.035       0  5933.4    0.07       0
Bank Sta=4963.1,5000.8
Exp/Cntr=0.3,0.1

Type RM Length L Ch R = 1,28067,1555,1555,1555
BEGIN DESCRIPTION:
Alkali Creek 23.5
END DESCRIPTION:
XS GIS Cut Line= 3
      1379509.41      6968406.96      1379775.02      6967235.12
      1379364.18      6966742.26
#Sta/Elev= 30
  4158.3 1949.53  4161.7 1952.98  4204.8 1948.08  4209.9 1951.27  4247.9 1946.73
  4253.0 1949.21  4382.4 1938.06  4387.6 1941.42  4430.7 1934.47  4435.8 1938.37
  4473.8 1932.71  4478.9 1935.17  4495.6 1935.24  4522.1 1931.21  4527.2 1934.42
  4565.2 1930.59  4570.3 1932.52  4661.7 1928.50  4946.8 1928.45  4968.9 1923.30
  4969.9 1922.80  5006.6 1923.30  5008.3 1926.97  5016.9 1927.91  5339.3 1925.03
  5507.3 1928.03  5698.4 1929.54  5828.3 1934.08  5970.6 1940.33  6001.5 1942.87
#Mann=6,-1,0
  4158.3   0.035       0  4968.9   0.035       0  5006.6   0.035       0
  5507.3    0.07       0  5828.3   0.035       0  5970.6    0.07       0
Bank Sta=4968.9,5006.6
Exp/Cntr=0.3,0.1

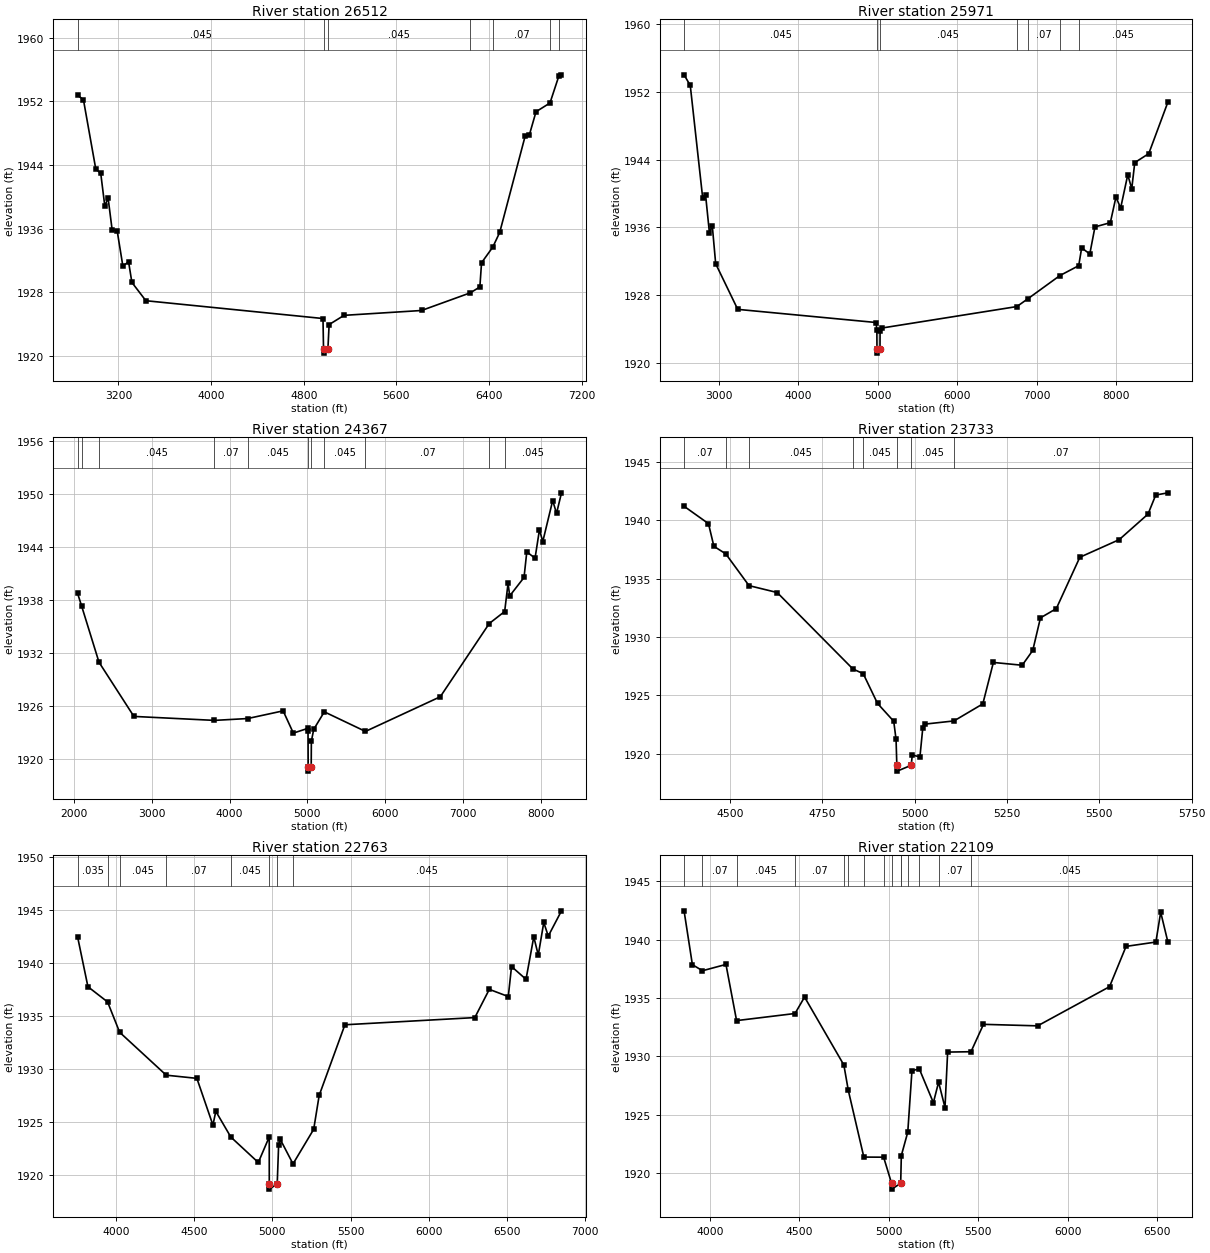
Type RM Length L Ch R = 1,26512,541,541,541
BEGIN DESCRIPTION:
Alkali Creek 23.0
END DESCRIPTION:
XS GIS Cut Line= 5
      1379559.39      6968613.50      1380825.07      6967121.69
      1380905.00      6966938.00      1380944.86      6966835.23
      1379455.02      6965638.02
#Sta/Elev= 30
  2847.8 1952.77  2898.0 1952.22  3004.6 1943.50  3047.4 1942.96  3082.6 1938.84
  3111.1 1939.85  3146.2 1935.82  3189.1 1935.75  3238.5 1931.30  3287.9 1931.83
  3316.5 1929.24  3437.3 1926.94  4966.6 1924.70  4971.2 1920.85  4972.1 1920.35
  5009.0 1920.85  5019.5 1923.94  5148.4 1925.10  5817.2 1925.71  6238.5 1927.93
  6321.2 1928.67  6335.6 1931.71  6432.3 1933.67  6492.4 1935.52  6713.2 1947.69
  6748.4 1947.78  6806.0 1950.70  6926.6 1951.80  7001.8 1955.13  7026.0 1955.34
#Mann=7,-1,0
  2847.8   0.045       0  4971.2   0.045       0  5009.0   0.045       0
  6238.5   0.035       0  6432.3    0.07       0  6926.6    0.16       0
  7001.8    0.07       0
Bank Sta=4971.2,5009
Exp/Cntr=0.3,0.1

Type RM Length L Ch R = 1,25971,1604,1604,1604
BEGIN DESCRIPTION:
Alkali Creek 22.0
END DESCRIPTION:
XS GIS Cut Line= 5
      1379555.02      6968687.98      1381332.36      6967210.92
      1381355.00      6967088.00      1381367.08      6966908.84
      1379655.01      6963888.01
#Sta/Elev= 30
  2563.7 1953.99  2641.7 1952.74  2797.7 1939.50  2833.8 1939.87  2883.3 1935.32
  2918.5 1936.22  2961.4 1931.72  3238.8 1926.34  4979.3 1924.79  4989.5 1923.85
  4990.7 1921.68  4991.7 1921.18  5028.6 1921.68  5029.7 1923.81  5059.8 1924.15
  6750.8 1926.67  6893.9 1927.62  7291.4 1930.32  7528.9 1931.49  7565.9 1933.59
  7668.3 1932.87  7733.2 1936.06  7926.6 1936.56  7997.2 1939.58  8056.4 1938.29
  8145.8 1942.20  8196.3 1940.57  8233.9 1943.64  8410.1 1944.70  8651.5 1950.79
#Mann=7,-1,0
  2563.7   0.045       0  4990.7   0.045       0  5028.6   0.045       0
  6750.8   0.035       0  6893.9    0.07       0  7291.4   0.035       0
  7528.9   0.045       0
Bank Sta=4990.7,5028.6
Exp/Cntr=0.3,0.1

Type RM Length L Ch R = 1,24367,634,634,634
BEGIN DESCRIPTION:
Alkali Creek 21.0
END DESCRIPTION:
XS GIS Cut Line= 5
      1383004.41      6969064.13      1382108.86      6966576.49
      1382005.00      6966288.00      1381864.37      6966050.62
      1379805.03      6963888.03
#Sta/Elev= 30
  2049.7 1938.76  2100.9 1937.34  2324.4 1930.96  2772.4 1924.82  3806.7 1924.37
  4233.5 1924.58  4688.5 1925.45  4819.6 1922.93  5003.2 1923.46  5008.1 1923.12
  5010.0 1919.12  5011.0 1918.62  5048.9 1919.12  5050.9 1922.02  5081.6 1923.36
  5217.2 1925.34  5745.4 1923.12  6706.3 1927.05  7335.1 1935.35  7532.7 1936.71
  7576.3 1939.90  7597.7 1938.48  7781.4 1940.57  7816.9 1943.47  7922.9 1942.75
  7979.5 1945.98  8022.0 1944.63  8149.4 1949.29  8198.8 1947.83  8262.4 1950.16
#Mann=11,-1,0
  2049.7    0.07       0  2100.9   0.035       0  2324.4   0.045       0
  3806.7    0.07       0  4233.5   0.045       0  5010.0   0.045       0
  5048.9   0.045       0  5217.2   0.045       0  5745.4    0.07       0
  7335.1   0.035       0  7532.7   0.045       0
Bank Sta=5010,5048.9
Exp/Cntr=0.3,0.1

Type RM Length L Ch R = 1,23733,970,970,970
BEGIN DESCRIPTION:
Alkali Creek 20.5
END DESCRIPTION:
XS GIS Cut Line= 3
      1382898.09      6966567.68      1382528.51      6966065.02
      1382085.28      6965541.70
#Sta/Elev= 30
  4376.1 1941.21  4442.2 1939.72  4456.8 1937.78  4489.0 1937.13  4551.9 1934.41
  4628.1 1933.82  4833.1 1927.27  4861.0 1926.87  4899.7 1924.32  4943.6 1922.79
  4949.9 1921.23  4952.0 1919.02  4953.0 1918.52  4990.9 1919.02  4993.8 1919.90
  5014.5 1919.74  5022.2 1922.21  5028.8 1922.55  5106.6 1922.82  5184.7 1924.28
  5213.3 1927.83  5291.3 1927.59  5319.9 1928.86  5340.7 1931.65  5383.6 1932.44
  5447.3 1936.84  5553.9 1938.35  5631.9 1940.54  5652.7 1942.17  5685.8 1942.36
#Mann=8,-1,0
  4376.1    0.07       0  4489.0   0.035       0  4551.9   0.045       0
  4833.1    0.07       0  4861.0   0.045       0  4952.0   0.045       0
  4990.9   0.045       0  5106.6    0.07       0
Bank Sta=4952,4990.9
Exp/Cntr=0.3,0.1

Type RM Length L Ch R = 1,22763,654,654,654
BEGIN DESCRIPTION:
Alkali Creek 20.0
END DESCRIPTION:
XS GIS Cut Line= 4
      1383052.50      6966673.37      1383194.86      6965639.06
      1383187.05      6965305.73      1384272.97      6963976.76
#Sta/Elev= 30
  3754.8 1942.48  3820.8 1937.77  3946.4 1936.33  4023.6 1933.46  4321.5 1929.40
  4517.3 1929.10  4619.9 1924.68  4638.4 1925.98  4734.3 1923.55  4910.0 1921.14
  4980.0 1923.56  4980.2 1919.12  4981.2 1918.62  5031.0 1919.12  5040.0 1922.80
  5050.0 1923.34  5132.0 1921.01  5264.2 1924.28  5299.3 1927.49  5463.8 1934.17
  6294.4 1934.85  6387.0 1937.52  6508.3 1936.84  6529.1 1939.68  6621.7 1938.47
  6671.3 1942.49  6700.0 1940.76  6735.2 1943.85  6763.9 1942.56  6848.5 1944.95
#Mann=8,-1,0
  3754.8   0.035       0  3946.4    0.07       0  4023.6   0.045       0
  4321.5    0.07       0  4734.3   0.045       0  4980.2   0.045       0
  5031.0   0.045       0  5132.0   0.045       0
Bank Sta=4980.2,5031
Exp/Cntr=0.3,0.1

Type RM Length L Ch R = 1,22109,513,513,513
BEGIN DESCRIPTION:
Alkali Creek 19.0
END DESCRIPTION:
XS GIS Cut Line= 5
      1383064.09      6966679.02      1383623.98      6965722.64
      1383638.09      6965550.11      1383707.79      6965412.48
      1384436.26      6964374.12
#Sta/Elev= 30
  3856.7 1942.48  3903.2 1937.86  3959.7 1937.34  4090.8 1937.88  4150.2 1933.06
  4476.8 1933.67  4530.0 1935.08  4749.7 1929.25  4774.4 1927.08  4861.3 1921.35
  4971.9 1921.34  5016.3 1919.10  5017.3 1918.60  5067.2 1919.10  5070.8 1921.48
  5106.8 1923.49  5130.1 1928.75  5170.9 1928.93  5249.9 1926.02  5279.1 1927.78
  5314.8 1925.60  5329.6 1930.36  5460.1 1930.39  5529.9 1932.74  5832.5 1932.61
  6234.3 1935.97  6326.7 1939.43  6493.2 1939.80  6520.2 1942.36  6560.7 1939.78
#Mann=15,-1,0
  3856.7   0.035       0  3959.7    0.07       0  4150.2   0.045       0
  4476.8    0.07       0  4749.7    0.16       0  4774.4    0.07       0
  4861.3   0.045       0  4971.9    0.07       0  5016.3    0.07       0
  5067.2    0.07       0  5070.8   0.045       0  5106.8    0.07       0
  5170.9   0.045       0  5279.1    0.07       0  5460.1   0.045       0
Bank Sta=5016.3,5067.2
Exp/Cntr=0.3,0.1

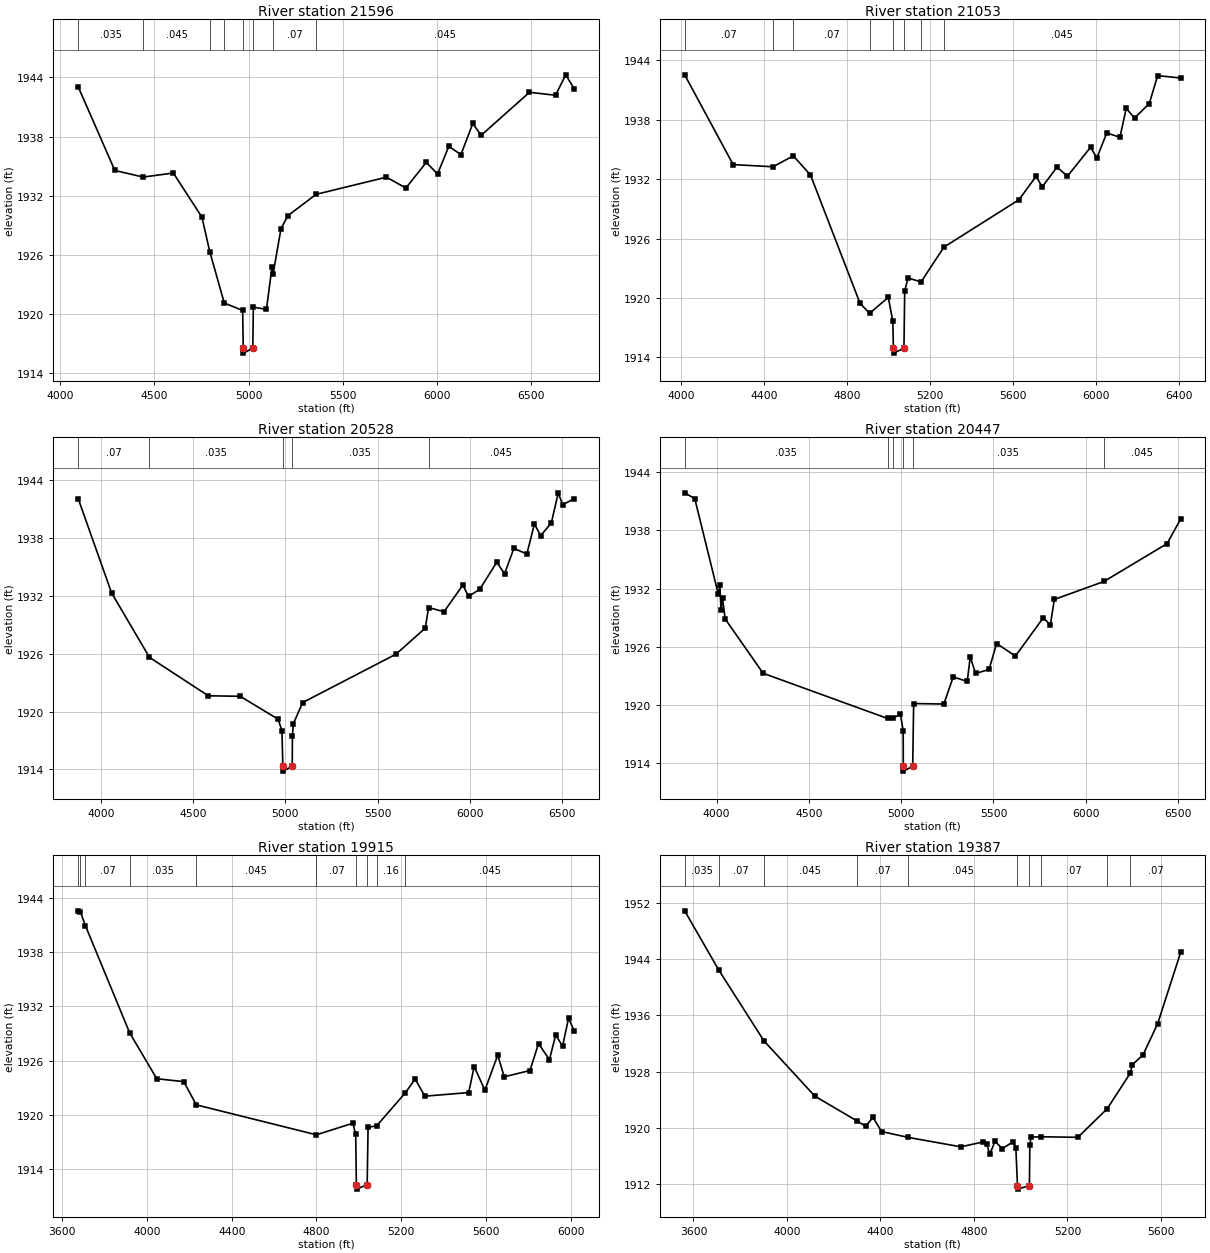
Type RM Length L Ch R = 1,21596,543,543,543
BEGIN DESCRIPTION:
Alkali Creek 18.0
END DESCRIPTION:
XS GIS Cut Line= 4
      1383454.99      6966788.01      1383920.57      6966075.79
      1383988.93      6966010.69      1384604.98      6964438.04
#Sta/Elev= 30
  4094.8 1943.03  4289.3 1934.56  4439.9 1933.89  4600.0 1934.30  4751.9 1929.83
  4793.6 1926.33  4870.6 1921.13  4968.4 1920.37  4971.2 1916.55  4972.2 1916.05
  5022.1 1916.55  5025.0 1920.71  5094.6 1920.48  5124.4 1924.81  5130.1 1924.09
  5171.9 1928.66  5208.5 1929.98  5358.6 1932.14  5732.1 1933.88  5835.2 1932.78
  5943.8 1935.38  6003.4 1934.20  6063.3 1937.00  6127.7 1936.17  6190.7 1939.32
  6235.1 1938.12  6491.8 1942.48  6630.1 1942.18  6684.4 1944.25  6729.1 1942.85
#Mann=8,-1,0
  4094.8   0.035       0  4439.9   0.045       0  4793.6    0.07       0
  4870.6   0.045       0  4971.2   0.045       0  5022.1   0.045       0
  5130.1    0.07       0  5358.6   0.045       0
Bank Sta=4971.2,5022.1
Exp/Cntr=0.3,0.1

Type RM Length L Ch R = 1,21053,525,525,525
BEGIN DESCRIPTION:
Alkali Creek 17.0
END DESCRIPTION:
XS GIS Cut Line= 4
      1383555.04      6966837.98      1384288.84      6966396.05
      1384451.60      6966272.35      1384640.20      6964958.65
#Sta/Elev= 30
  4018.8 1942.55  4252.2 1933.48  4444.2 1933.26  4542.1 1934.36  4624.6 1932.43
  4863.5 1919.45  4909.5 1918.46  4999.3 1920.06  5021.3 1917.63  5023.8 1914.93
  5024.8 1914.43  5074.7 1914.93  5078.3 1920.71  5094.3 1922.03  5157.0 1921.62
  5267.1 1925.14  5628.1 1929.92  5710.6 1932.28  5740.9 1931.24  5811.6 1933.22
  5862.1 1932.31  5973.3 1935.23  6003.6 1934.15  6051.4 1936.68  6114.7 1936.24
  6145.0 1939.16  6185.4 1938.18  6256.1 1939.65  6296.5 1942.47  6407.0 1942.23
#Mann=8,-1,0
  4018.8    0.07       0  4444.2   0.035       0  4542.1    0.07       0
  4909.5   0.045       0  5023.8   0.045       0  5074.7   0.045       0
  5157.0    0.07       0  5267.1   0.045       0
Bank Sta=5023.8,5074.7
Exp/Cntr=0.3,0.1

Type RM Length L Ch R = 1,20528,81,81,81
BEGIN DESCRIPTION:
Alkali Creek 16.0
END DESCRIPTION:
XS GIS Cut Line= 4
      1384005.00      6967188.00      1384645.14      6966980.26
      1384884.72      6965886.51      1384702.90      6965006.69
#Sta/Elev= 30
  3875.6 1942.10  4056.7 1932.32  4262.2 1925.63  4581.6 1921.64  4754.4 1921.59
  4960.4 1919.21  4980.9 1918.02  4986.1 1914.32  4987.1 1913.82  5037.0 1914.32
  5037.9 1917.50  5043.0 1918.73  5093.5 1920.94  5599.8 1925.96  5758.7 1928.66
  5776.9 1930.80  5860.8 1930.37  5962.9 1933.14  5993.5 1931.96  6054.8 1932.70
  6146.7 1935.51  6189.2 1934.30  6239.4 1936.94  6310.1 1936.36  6350.9 1939.47
  6385.0 1938.27  6442.8 1939.58  6480.4 1942.71  6504.1 1941.47  6566.7 1942.10
#Mann=5,-1,0
  3875.6    0.07       0  4262.2   0.035       0  4986.1   0.035       0
  5037.0   0.035       0  5776.9   0.045       0
Bank Sta=4986.1,5037
Exp/Cntr=0.3,0.1

Type RM Length L Ch R = 1,20447,532,532,532
BEGIN DESCRIPTION:
Alkali Creek 15.5
END DESCRIPTION:
XS GIS Cut Line= 4
      1384182.04      6967492.28      1384705.90      6967079.22
      1384937.13      6965957.09      1384900.67      6965084.68
#Sta/Elev= 30
  3827.5 1941.87  3882.2 1941.27  4010.0 1931.40  4018.0 1932.35  4024.4 1929.78
  4032.5 1931.00  4046.9 1928.88  4252.1 1923.29  4926.6 1918.63  4954.3 1918.64
  4996.2 1919.09  5010.9 1917.34  5011.6 1913.71  5012.6 1913.21  5062.5 1913.71
  5067.6 1920.17  5231.0 1920.12  5282.0 1922.91  5357.9 1922.45  5373.9 1924.97
  5403.1 1923.27  5476.0 1923.68  5516.9 1926.35  5619.0 1925.06  5769.5 1929.00
  5807.9 1928.26  5829.6 1930.89  6098.1 1932.74  6440.1 1936.64  6513.5 1939.16
#Mann=6,-1,0
  3827.5   0.035       0  4926.6    0.07       0  4954.3   0.035       0
  5011.6   0.035       0  5062.5   0.035       0  6098.1   0.045       0
Bank Sta=5011.6,5062.5
Exp/Cntr=0.3,0.1

Type RM Length L Ch R = 1,19915,528,528,528
BEGIN DESCRIPTION:
Alkali Creek 15.0
END DESCRIPTION:
XS GIS Cut Line= 4
      1384254.07      6967597.77      1385254.47      6966806.90
      1385317.40      6966716.50      1385469.11      6965771.80
#Sta/Elev= 30
  3674.8 1942.58  3685.4 1942.46  3708.6 1940.95  3917.7 1929.09  4045.7 1924.01
  4173.1 1923.69  4232.6 1921.12  4799.6 1917.81  4972.1 1919.09  4985.3 1917.85
  4988.5 1912.30  4989.5 1911.80  5039.5 1912.30  5043.7 1918.64  5084.3 1918.80
  5218.9 1922.43  5266.0 1923.97  5311.9 1922.08  5518.8 1922.48  5544.8 1925.36
  5595.5 1922.74  5656.2 1926.63  5686.6 1924.22  5808.2 1924.92  5848.7 1927.89
  5900.4 1926.12  5929.7 1928.86  5962.3 1927.61  5990.5 1930.70  6017.0 1929.33
#Mann=10,-1,0
  3674.8    0.07       0  3685.4   0.035       0  3708.6    0.07       0
  3917.7   0.035       0  4232.6   0.045       0  4799.6    0.07       0
  4988.5    0.07       0  5039.5    0.07       0  5084.3    0.16       0
  5218.9   0.045       0
Bank Sta=4988.5,5039.5
Exp/Cntr=0.3,0.1

Type RM Length L Ch R = 1,19387,501,501,501
BEGIN DESCRIPTION:
Alkali Creek 14.0
END DESCRIPTION:
XS GIS Cut Line= 4
      1384482.32      6968089.78      1384977.13      6967268.58
      1385365.58      6967068.06      1386058.75      6967284.22
#Sta/Elev= 30
  3562.4 1950.86  3707.7 1942.48  3901.2 1932.40  4119.4 1924.53  4298.2 1921.04
  4336.9 1920.25  4368.0 1921.51  4404.9 1919.50  4518.8 1918.67  4743.8 1917.33
  4839.0 1918.02  4855.5 1917.67  4867.6 1916.26  4890.1 1918.10  4922.0 1917.07
  4968.2 1918.08  4979.4 1917.18  4986.4 1911.82  4987.4 1911.32  5037.4 1911.82
  5039.2 1917.56  5044.4 1918.71  5087.4 1918.76  5244.7 1918.68  5370.3 1922.74
  5469.2 1927.80  5477.5 1929.00  5523.3 1930.37  5586.2 1934.83  5684.4 1944.94
#Mann=10,-1,0
  3562.4   0.035       0  3707.7    0.07       0  3901.2   0.045       0
  4298.2    0.07       0  4518.8   0.045       0  4986.4   0.045       0
  5037.4   0.045       0  5087.4    0.07       0  5370.3    0.16       0
  5469.2    0.07       0
Bank Sta=4986.4,5037.4
Exp/Cntr=0.3,0.1

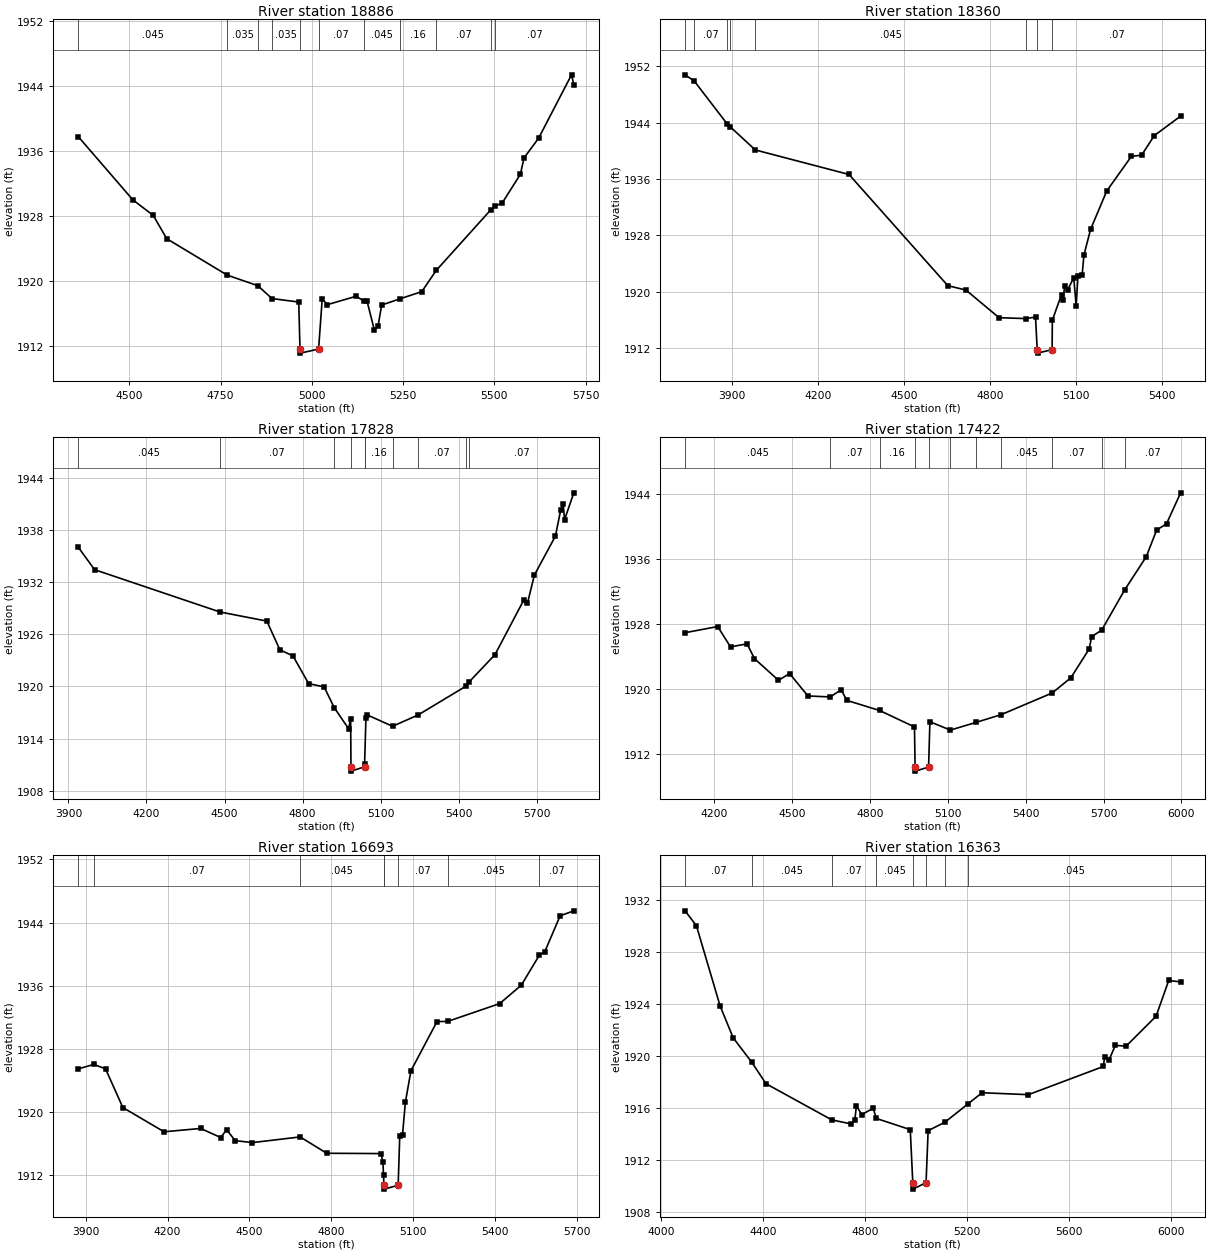
Type RM Length L Ch R = 1,18886,526,526,526
BEGIN DESCRIPTION:
Alkali Creek 13.0
END DESCRIPTION:
XS GIS Cut Line= 5
      1384954.97      6967938.04      1385283.87      6967526.91
      1385355.00      6967438.00      1385430.00      6967363.00
      1386041.29      6967344.29
#Sta/Elev= 30
  4359.9 1937.78  4509.6 1930.00  4565.6 1928.08  4602.5 1925.22  4768.3 1920.74
  4852.1 1919.44  4890.9 1917.86  4964.2 1917.43  4967.6 1911.65  4968.6 1911.15
  5018.6 1911.65  5028.5 1917.81  5042.7 1917.11  5121.3 1918.14  5142.4 1917.57
  5151.3 1917.56  5171.4 1913.98  5181.4 1914.45  5191.4 1917.06  5241.6 1917.83
  5301.4 1918.71  5340.7 1921.31  5490.0 1928.75  5502.6 1929.24  5521.5 1929.60
  5571.5 1933.14  5581.5 1935.15  5621.6 1937.59  5711.6 1945.37  5717.9 1944.17
#Mann=11,-1,0
  4359.9   0.045       0  4768.3   0.035       0  4852.1    0.07       0
  4890.9   0.035       0  4967.6   0.035       0  5018.6    0.07       0
  5142.4   0.045       0  5241.6    0.16       0  5340.7    0.07       0
  5490.0    0.16       0  5502.6    0.07       0
Bank Sta=4967.6,5018.6
Exp/Cntr=0.3,0.1

Type RM Length L Ch R = 1,18360,532,532,532
BEGIN DESCRIPTION:
Alkali Creek 12.0
END DESCRIPTION:
XS GIS Cut Line= 3
      1384502.74      6968138.30      1385765.23      6967729.58
      1386000.36      6967403.52
#Sta/Elev= 30
  3736.1 1950.81  3767.9 1949.95  3883.9 1943.79  3893.8 1943.42  3981.2 1940.13
  4308.3 1936.64  4652.9 1920.83  4716.0 1920.21  4831.6 1916.28  4924.7 1916.15
  4958.8 1916.37  4964.8 1911.74  4965.8 1911.24  5016.8 1911.74  5017.5 1915.91
  5049.5 1919.57  5054.8 1918.79  5060.4 1920.75  5071.2 1920.27  5092.1 1921.95
  5100.7 1918.01  5106.8 1922.17  5121.5 1922.32  5127.7 1925.18  5151.0 1928.85
  5207.4 1934.30  5293.3 1939.22  5328.9 1939.38  5373.1 1942.17  5465.1 1944.94
#Mann=8,-1,0
  3736.1   0.035       0  3767.9    0.07       0  3883.9   0.045       0
  3893.8    0.07       0  3981.2   0.045       0  4924.7    0.07       0
  4964.8    0.07       0  5016.8    0.07       0
Bank Sta=4964.8,5016.8
Exp/Cntr=0.3,0.1

Type RM Length L Ch R = 1,17828,406,406,406
BEGIN DESCRIPTION:
Alkali Creek 11.0
END DESCRIPTION:
XS GIS Cut Line= 4
      1384762.35      6968353.09      1385698.62      6968278.04
      1385903.78      6968159.13      1386005.00      6967438.00
#Sta/Elev= 30
  3937.7 1936.07  4000.6 1933.47  4482.5 1928.59  4662.7 1927.54  4712.8 1924.22
  4763.0 1923.53  4823.2 1920.33  4882.8 1919.95  4921.9 1917.55  4976.8 1915.13
  4984.7 1916.23  4986.0 1910.74  4987.0 1910.24  5038.0 1910.74  5038.3 1911.05
  5043.5 1916.42  5049.3 1916.71  5145.8 1915.41  5244.2 1916.72  5426.5 1920.01
  5441.1 1920.56  5539.4 1923.67  5650.4 1929.99  5664.0 1929.57  5690.8 1932.85
  5771.6 1937.34  5791.8 1940.34  5801.6 1941.04  5806.6 1939.22  5842.3 1942.33
#Mann=10,-1,0
  3937.7   0.045       0  4482.5    0.07       0  4921.9    0.16       0
  4986.0   0.045       0  5038.0    0.16       0  5038.3    0.16       0
  5145.8   0.045       0  5244.2    0.07       0  5426.5   0.045       0
  5441.1    0.07       0
Bank Sta=4986,5038
Exp/Cntr=0.3,0.1

Type RM Length L Ch R = 1,17422,729,729,729
BEGIN DESCRIPTION:
Alkali Creek 10.3
END DESCRIPTION:
XS GIS Cut Line= 4
      1385668.63      6969058.79      1386181.55      6968449.93
      1386126.00      6968238.13      1386087.80      6967345.73
#Sta/Elev= 30
  4088.6 1926.92  4214.4 1927.68  4263.8 1925.17  4327.5 1925.55  4356.1 1923.72
  4448.5 1921.05  4491.4 1921.88  4561.6 1919.12  4647.5 1919.00  4690.3 1919.89
  4711.1 1918.58  4837.5 1917.33  4972.1 1915.30  4974.4 1910.35  4975.4 1909.85
  5026.4 1910.35  5031.5 1915.94  5110.2 1914.91  5208.2 1915.85  5306.3 1916.82
  5502.5 1919.49  5574.2 1921.36  5644.3 1924.89  5654.3 1926.43  5693.3 1927.25
  5781.0 1932.18  5864.5 1936.29  5904.5 1939.58  5942.5 1940.35  5996.9 1944.17
#Mann=11,-1,0
  4088.6   0.045       0  4647.5    0.07       0  4837.5    0.16       0
  4974.4    0.07       0  5026.4    0.16       0  5110.2    0.16       0
  5208.2    0.07       0  5306.3   0.045       0  5502.5    0.07       0
  5693.3   0.045       0  5781.0    0.07       0
Bank Sta=4974.4,5026.4
Exp/Cntr=0.3,0.1

Type RM Length L Ch R = 1,16693,330,330,330
BEGIN DESCRIPTION:
Alkali Creek 10.25
END DESCRIPTION:
XS GIS Cut Line= 4
      1386830.01      6968863.04      1386565.56      6968080.15
      1386467.57      6967671.18      1386130.00      6967213.00
#Sta/Elev= 30
  3872.7 1925.48  3930.3 1926.05  3973.0 1925.48  4036.3 1920.59  4187.3 1917.52
  4321.3 1917.94  4395.2 1916.79  4416.3 1917.79  4448.0 1916.40  4511.3 1916.15
  4685.9 1916.87  4783.5 1914.80  4982.2 1914.76  4989.2 1913.74  4991.4 1912.06
  4993.1 1910.76  4994.1 1910.26  5045.1 1910.76  5050.9 1916.99  5061.1 1917.16
  5071.5 1921.26  5092.0 1925.25  5187.4 1931.47  5226.4 1931.49  5417.2 1933.75
  5496.2 1936.07  5562.4 1939.87  5582.2 1940.30  5638.6 1944.86  5688.7 1945.49
#Mann=8,-1,0
  3872.7   0.045       0  3930.3    0.07       0  4685.9   0.045       0
  4991.4    0.07       0  4993.1    0.07       0  5045.1    0.07       0
  5226.4   0.045       0  5562.4    0.07       0
Bank Sta=4993.1,5045.1
Exp/Cntr=0.3,0.1

Type RM Length L Ch R = 1,16363,715,715,715
BEGIN DESCRIPTION:
Alkali Creek 10.2
END DESCRIPTION:
XS GIS Cut Line= 5
      1387263.61      6968601.88      1386805.25      6967917.82
      1386815.67      6967706.01      1386749.70      6967230.32
      1386850.20      6966814.43
#Sta/Elev= 30
  4093.9 1931.17  4138.5 1930.03  4231.6 1923.84  4282.6 1921.40  4355.5 1919.52
  4411.7 1917.86  4669.4 1915.08  4744.8 1914.77  4759.8 1915.06  4765.9 1916.16
  4786.9 1915.49  4831.9 1915.97  4844.0 1915.19  4977.2 1914.33  4987.1 1910.25
  4988.1 1909.75  5039.1 1910.25  5047.3 1914.25  5113.0 1914.90  5202.4 1916.29
  5258.6 1917.17  5440.4 1917.02  5734.5 1919.19  5739.6 1919.95  5756.1 1919.67
  5781.5 1920.82  5823.4 1920.75  5941.2 1923.06  5990.8 1925.81  6037.5 1925.70
#Mann=8,-1,0
  4093.9    0.07       0  4355.5   0.045       0  4669.4    0.07       0
  4844.0   0.045       0  4987.1   0.045       0  5039.1   0.045       0
  5113.0    0.07       0  5202.4   0.045       0
Bank Sta=4987.1,5039.1
Exp/Cntr=0.3,0.1

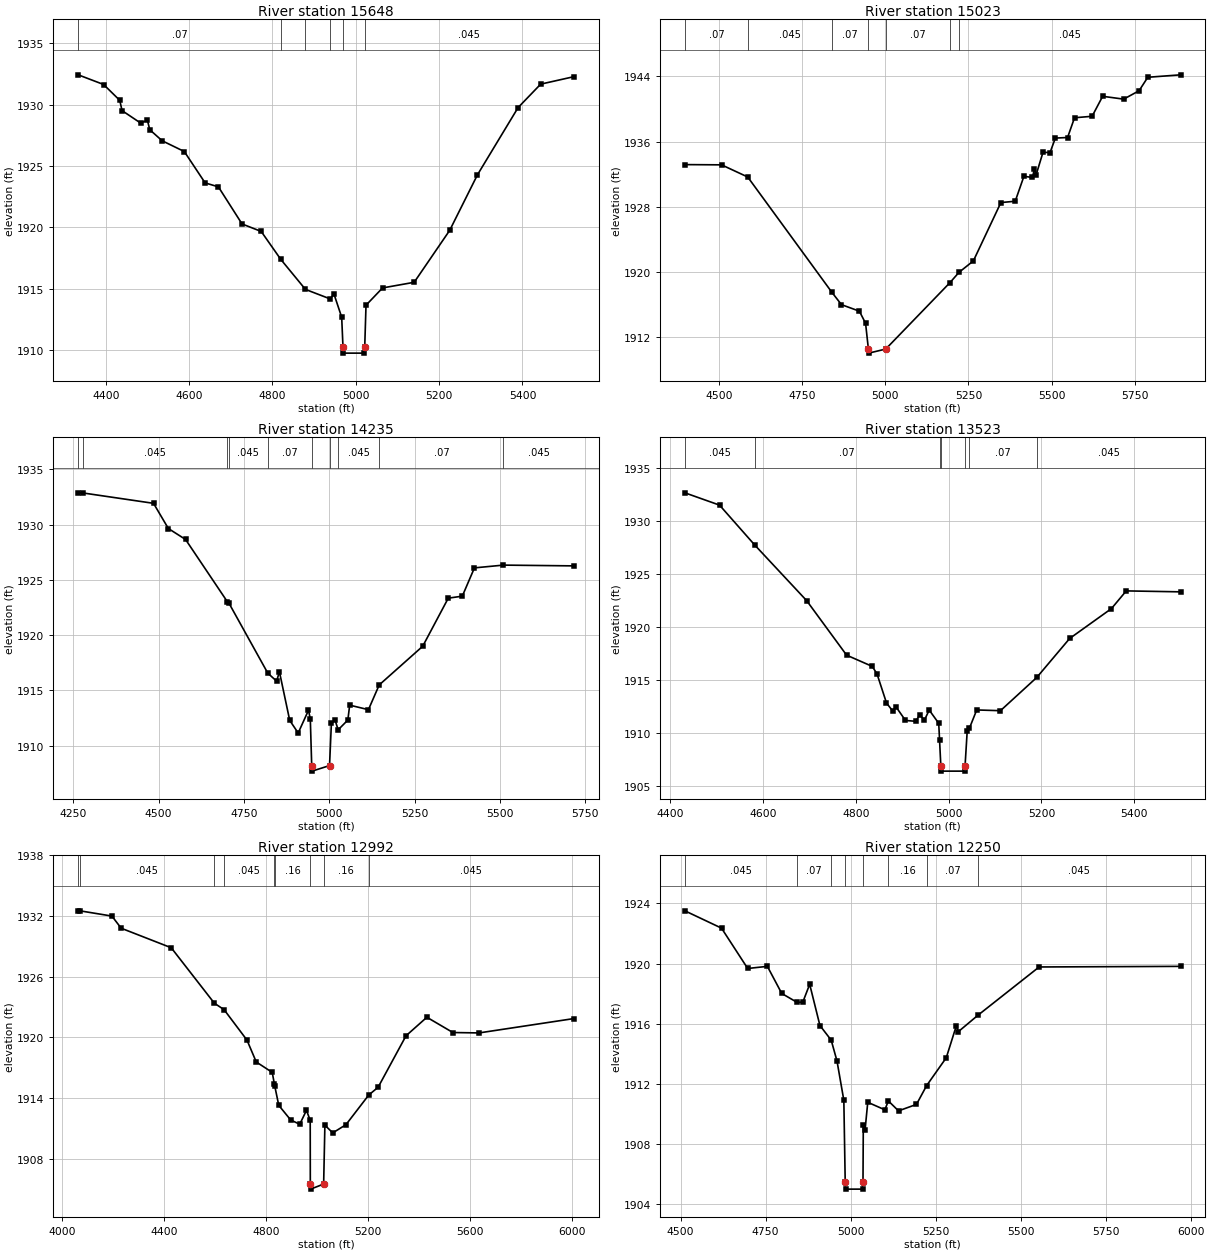
Type RM Length L Ch R = 1,15648,625,625,625
BEGIN DESCRIPTION:
Alkali Creek 10.1
END DESCRIPTION:
XS GIS Cut Line= 3
      1387628.16      6968086.98      1387428.28      6967700.19
      1387135.99      6967004.48
#Sta/Elev= 30
  4333.6 1932.44  4394.6 1931.65  4433.3 1930.36  4438.9 1929.52  4483.2 1928.51
  4499.8 1928.72  4505.4 1927.96  4535.1 1927.06  4588.3 1926.18  4638.3 1923.62
  4670.1 1923.30  4726.9 1920.27  4772.9 1919.66  4819.9 1917.38  4879.1 1914.93
  4938.1 1914.16  4947.8 1914.53  4966.1 1912.66  4969.2 1910.23  4970.3 1909.73
  5020.4 1909.73  5021.4 1910.23  5024.5 1913.64  5064.2 1915.05  5140.1 1915.51
  5225.4 1919.75  5292.0 1924.28  5389.6 1929.77  5443.8 1931.68  5523.6 1932.29
#Mann=6,-1,0
  4333.6    0.07       0  4819.9   0.045       0  4879.1    0.07       0
  4938.1   0.045       0  4969.2   0.045       0  5021.4   0.045       0
Bank Sta=4969.2,5021.4
Exp/Cntr=0.3,0.1

Type RM Length L Ch R = 1,15023,788,788,788
BEGIN DESCRIPTION:
Alkali Creek 10.0
END DESCRIPTION:
XS GIS Cut Line= 4
      1387677.74      6968068.41      1387830.08      6967570.16
      1387805.00      6967433.01      1388070.25      6966645.63
#Sta/Elev= 30
  4396.9 1933.18  4507.2 1933.15  4585.9 1931.66  4839.3 1917.52  4867.9 1916.02
  4921.8 1915.22  4940.4 1913.74  4948.9 1910.58  4949.9 1910.08  5001.1 1910.58
  5193.9 1918.70  5221.5 1919.98  5264.7 1921.38  5347.5 1928.53  5390.6 1928.69
  5416.8 1931.75  5442.5 1931.60  5448.3 1932.66  5453.6 1931.95  5474.2 1934.69
  5495.3 1934.65  5511.3 1936.43  5548.1 1936.50  5569.0 1938.92  5621.9 1939.10
  5653.6 1941.55  5716.9 1941.20  5763.2 1942.23  5789.4 1943.88  5888.2 1944.18
#Mann=7,-1,0
  4396.9    0.07       0  4585.9   0.045       0  4839.3    0.07       0
  4948.9   0.045       0  5001.1    0.07       0  5193.9    0.07       0
  5221.5   0.045       0
Bank Sta=4948.9,5001.1
Exp/Cntr=0.3,0.1

Type RM Length L Ch R = 1,14235,712,712,712
BEGIN DESCRIPTION:
Alkali Creek 9.8
END DESCRIPTION:
XS GIS Cut Line= 3
      1387653.41      6968216.87      1387874.89      6968042.95
      1388969.12      6967628.47
#Sta/Elev= 30
  4264.8 1932.87  4278.4 1932.86  4485.4 1931.92  4528.8 1929.64  4579.2 1928.65
  4701.3 1923.03  4706.2 1922.89  4820.1 1916.55  4845.9 1915.83  4854.0 1916.69
  4884.2 1912.28  4909.0 1911.14  4939.2 1913.20  4944.5 1912.41  4948.6 1908.19
  4949.6 1907.69  5000.8 1908.19  5006.3 1912.06  5017.0 1912.30  5026.1 1911.43
  5054.4 1912.31  5059.8 1913.66  5114.7 1913.25  5146.3 1915.49  5273.7 1918.99
  5348.5 1923.34  5389.6 1923.52  5425.1 1926.08  5510.0 1926.33  5716.5 1926.26
#Mann=10,-1,0
  4264.8    0.07       0  4278.4   0.045       0  4701.3    0.07       0
  4706.2   0.045       0  4820.1    0.07       0  4948.6    0.07       0
  5000.8    0.07       0  5026.1   0.045       0  5146.3    0.07       0
  5510.0   0.045       0
Bank Sta=4948.6,5000.8
Exp/Cntr=0.3,0.1

Type RM Length L Ch R = 1,13523,531,531,531
BEGIN DESCRIPTION:
Alkali Creek 9.7
END DESCRIPTION:
XS GIS Cut Line= 4
      1387762.58      6968400.84      1388052.65      6968472.51
      1388606.96      6968590.55      1388790.20      6968505.61
#Sta/Elev= 30
  4432.2 1932.68  4506.8 1931.52  4582.1 1927.78  4694.4 1922.51  4780.4 1917.37
  4835.6 1916.31  4845.9 1915.60  4866.3 1912.86  4879.5 1912.11  4886.8 1912.49
  4907.2 1911.21  4929.1 1911.13  4937.9 1911.73  4948.1 1911.25  4958.3 1912.19
  4978.8 1910.94  4980.6 1909.34  4983.3 1906.93  4984.3 1906.43  5034.5 1906.43
  5035.5 1906.93  5040.1 1910.21  5045.0 1910.49  5060.6 1912.20  5111.7 1912.13
  5190.0 1915.27  5260.7 1918.94  5350.7 1921.76  5382.6 1923.43  5499.7 1923.34
#Mann=7,-1,0
  4432.2   0.045       0  4582.1    0.07       0  4980.6    0.16       0
  4983.3    0.07       0  5035.5    0.16       0  5045.0    0.07       0
  5190.0   0.045       0
Bank Sta=4983.3,5035.5
Exp/Cntr=0.3,0.1

Type RM Length L Ch R = 1,12992,742,742,742
BEGIN DESCRIPTION:
Alkali Creek 9.6
END DESCRIPTION:
XS GIS Cut Line= 4
      1387548.28      6968362.00      1387930.34      6968952.97
      1388330.92      6969054.09      1389139.64      6968890.32
#Sta/Elev= 30
  4064.4 1932.47  4071.2 1932.50  4196.5 1931.98  4232.8 1930.78  4428.8 1928.85
  4597.7 1923.37  4635.9 1922.73  4725.6 1919.72  4761.9 1917.56  4824.5 1916.53
  4833.0 1915.37  4834.4 1915.18  4850.1 1913.27  4896.7 1911.83  4932.2 1911.40
  4958.6 1912.78  4973.3 1911.78  4973.7 1905.49  4974.7 1904.99  5025.9 1905.49
  5030.8 1911.31  5061.7 1910.55  5113.3 1911.36  5202.9 1914.30  5239.3 1915.06
  5348.7 1920.15  5430.3 1921.98  5532.3 1920.47  5634.4 1920.43  6006.4 1921.85
#Mann=9,-1,0
  4064.4    0.07       0  4071.2   0.045       0  4597.7    0.07       0
  4635.9   0.045       0  4833.0    0.07       0  4834.4    0.16       0
  4973.7    0.07       0  5025.9    0.16       0  5202.9   0.045       0
Bank Sta=4973.7,5025.9
Exp/Cntr=0.3,0.1

Type RM Length L Ch R = 1,12250,690,690,690
BEGIN DESCRIPTION:
Alkali Creek 9.5
END DESCRIPTION:
XS GIS Cut Line= 4
      1387529.98      6969863.02      1387758.83      6969684.36
      1388144.62      6969649.31      1388836.12      6969289.55
#Sta/Elev= 30
  4512.7 1923.50  4620.3 1922.35  4697.3 1919.67  4755.1 1919.81  4797.4 1918.01
  4843.1 1917.41  4859.4 1917.44  4879.5 1918.62  4909.6 1915.88  4942.7 1914.91
  4959.8 1913.52  4979.9 1910.91  4983.9 1905.51  4984.9 1905.01  5035.1 1905.01
  5036.2 1905.51  5037.1 1909.24  5042.2 1908.92  5050.2 1910.78  5100.4 1910.28
  5110.8 1910.87  5140.6 1910.21  5193.4 1910.64  5223.3 1911.89  5281.0 1913.74
  5310.8 1915.88  5316.4 1915.47  5374.5 1916.57  5554.0 1919.77  5969.9 1919.81
#Mann=8,-1,0
  4512.7   0.045       0  4843.1    0.07       0  4942.7    0.16       0
  4983.9    0.07       0  5036.2    0.16       0  5110.8    0.16       0
  5223.3    0.07       0  5374.5   0.045       0
Bank Sta=4983.9,5036.2
Exp/Cntr=0.3,0.1