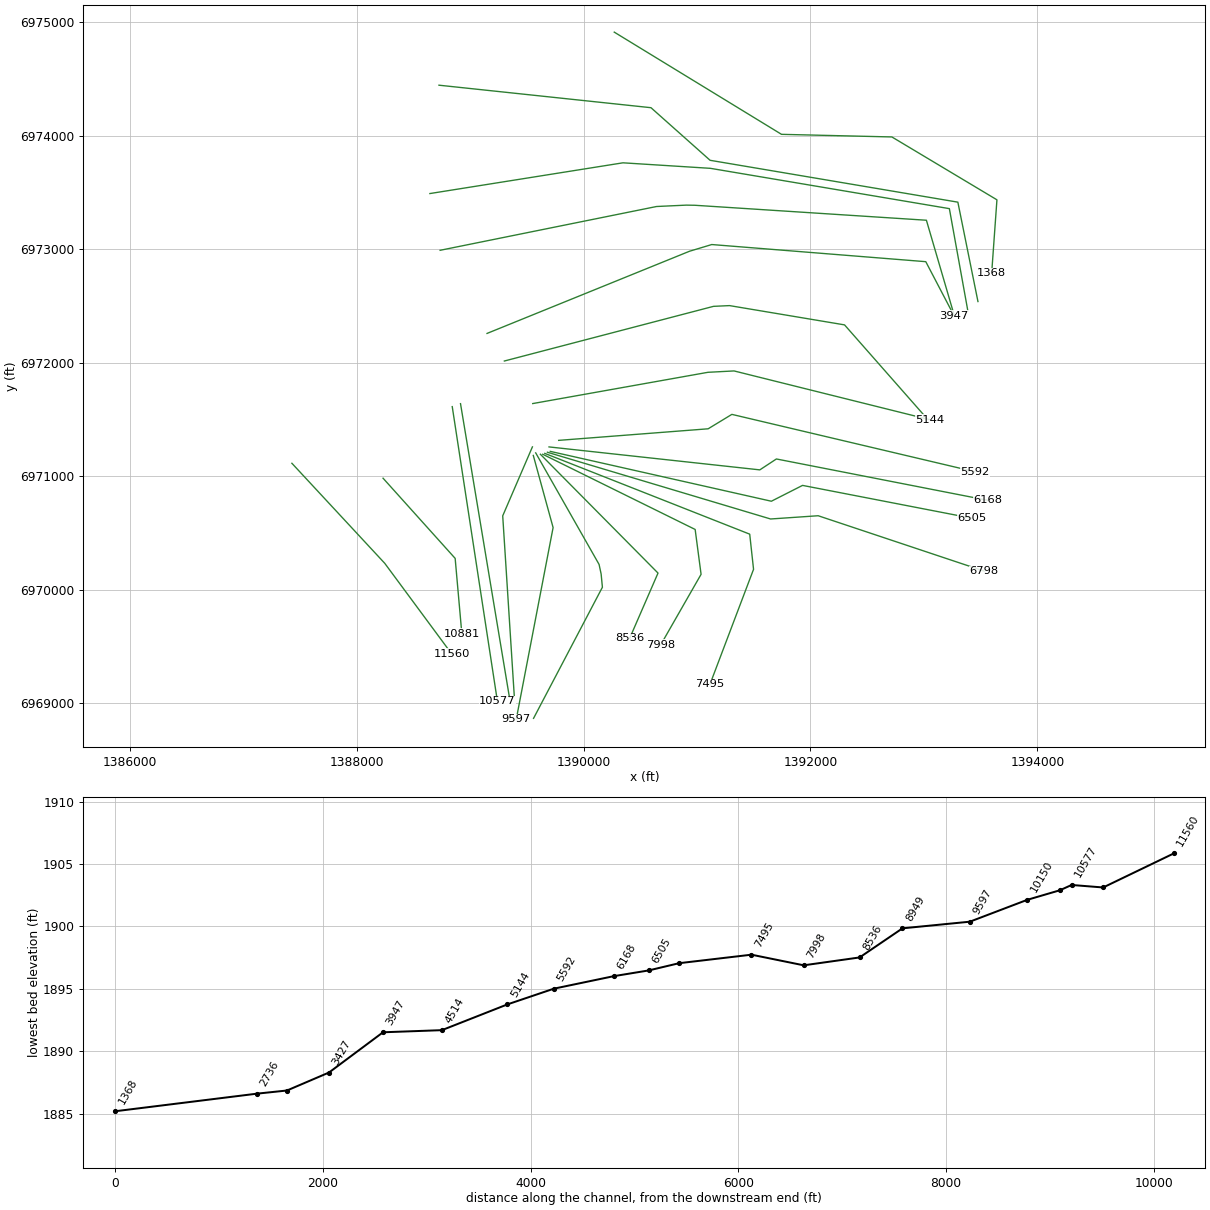
HEC-RAS study Alkali Creek.prj: Alkali Creek Base Level Engineering

--- Alkali Creek.g01 (geometry) --- (continued)

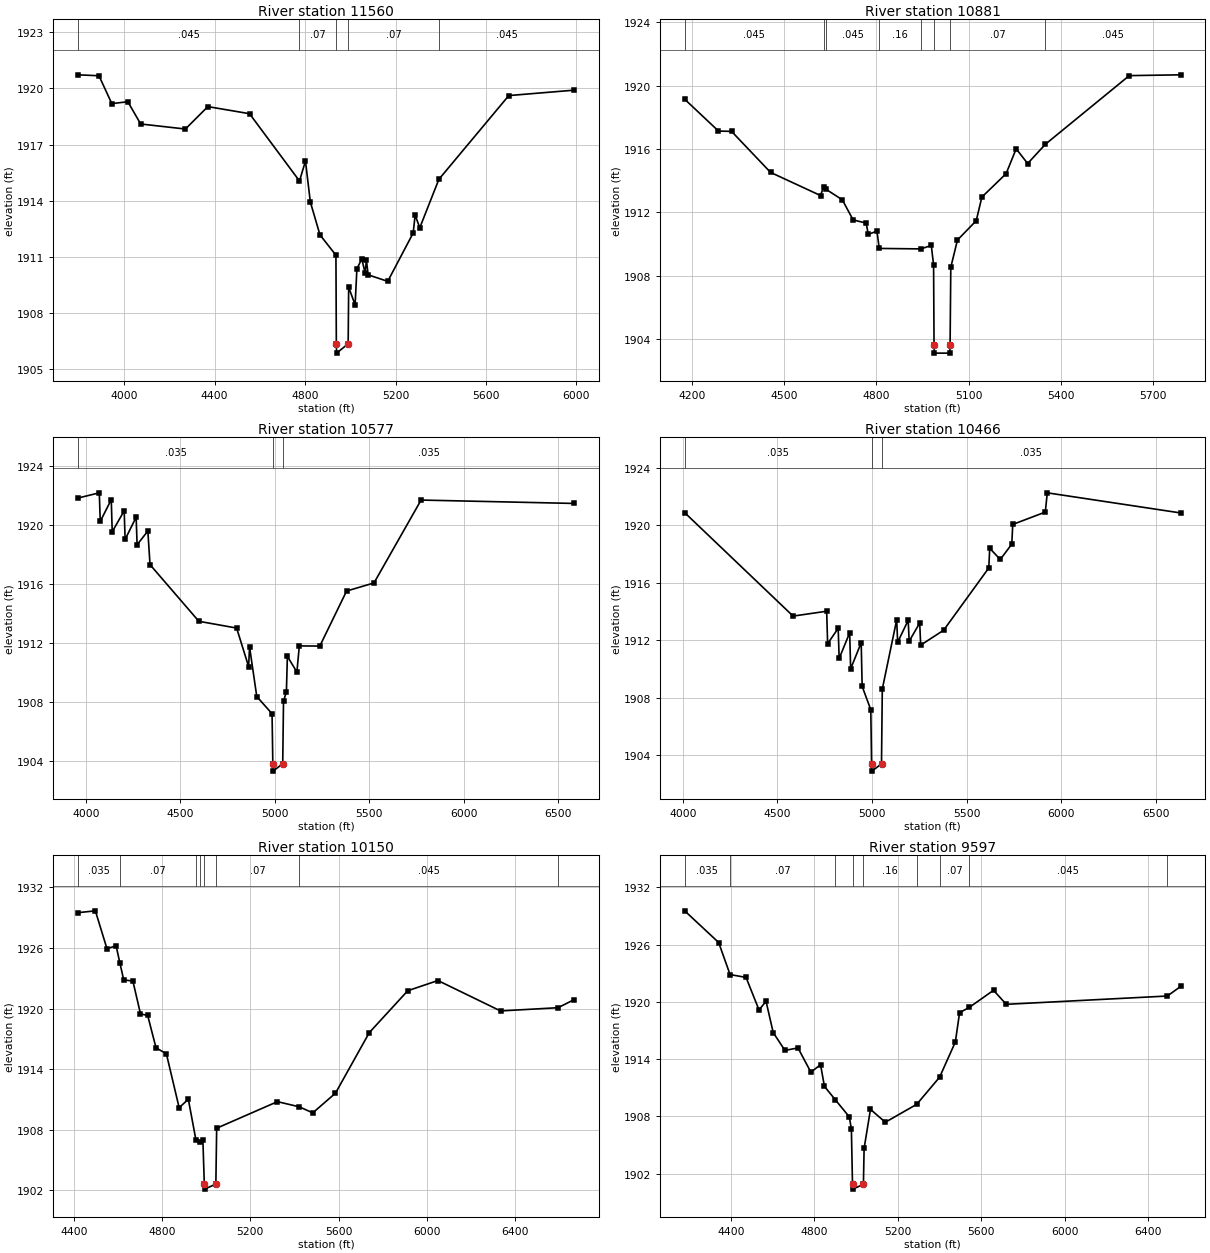
Type RM Length L Ch R = 1,11560,679,679,679
BEGIN DESCRIPTION:
Alkali Creek 9.4
END DESCRIPTION:
XS GIS Cut Line= 3
      1387430.01      6971112.99      1388248.25      6970231.54
      1388836.53      6969435.65
#Sta/Elev= 30
  3797.3 1920.73  3889.1 1920.68  3945.8 1919.19  4016.7 1919.29  4073.4 1918.10
  4271.2 1917.83  4370.4 1919.03  4554.6 1918.65  4775.5 1915.05  4801.9 1916.12
  4823.4 1913.93  4865.9 1912.17  4936.6 1911.08  4938.4 1906.34  4939.5 1905.84
  4990.7 1906.34  4992.9 1909.37  5021.4 1908.42  5029.3 1910.35  5050.7 1910.88
  5065.3 1910.15  5071.5 1910.80  5079.0 1910.03  5165.5 1909.68  5278.2 1912.27
  5286.6 1913.22  5307.4 1912.55  5391.7 1915.14  5700.8 1919.62  5989.7 1919.91
#Mann=5,-1,0
  3797.3   0.045       0  4775.5    0.07       0  4938.4    0.07       0
  4990.7    0.07       0  5391.7   0.045       0
Bank Sta=4938.4,4990.7
Exp/Cntr=0.3,0.1

Type RM Length L Ch R = 1,10881,304,304,304
BEGIN DESCRIPTION:
Alkali Creek 9.3
END DESCRIPTION:
XS GIS Cut Line= 3
      1388233.30      6970981.60      1388868.71      6970275.02
      1388927.56      6969611.39
#Sta/Elev= 30
  4174.8 1919.15  4285.0 1917.14  4327.6 1917.12  4454.7 1914.53  4617.6 1913.07
  4627.8 1913.63  4635.0 1913.47  4688.6 1912.80  4723.8 1911.53  4766.4 1911.33
  4773.1 1910.62  4801.5 1910.82  4808.9 1909.73  4944.9 1909.70  4978.6 1909.92
  4986.1 1908.69  4987.6 1903.62  4988.6 1903.12  5038.9 1903.12  5039.9 1903.62
  5042.2 1908.54  5063.9 1910.26  5125.1 1911.48  5143.4 1912.97  5222.5 1914.45
  5255.3 1916.02  5292.7 1915.09  5350.7 1916.31  5624.0 1920.64  5791.3 1920.69
#Mann=8,-1,0
  4174.8   0.045       0  4627.8    0.07       0  4635.0   0.045       0
  4808.9    0.16       0  4944.9    0.07       0  4987.6    0.07       0
  5039.9    0.07       0  5350.7   0.045       0
Bank Sta=4987.6,5039.9
Exp/Cntr=0.3,0.1

Type RM Length L Ch R = 1,10577,111,111,111
BEGIN DESCRIPTION:
Alkali Creek 9.25
END DESCRIPTION:
XS GIS Cut Line= 2
      1388842.95      6971612.45      1389240.81      6969016.96
#Sta/Elev= 30
  3959.2 1921.84  4070.8 1922.19  4075.9 1920.25  4134.2 1921.73  4139.2 1919.55
  4202.6 1920.97  4207.6 1919.03  4265.9 1920.54  4271.0 1918.67  4327.9 1919.60
  4339.4 1917.32  4597.9 1913.48  4798.0 1913.02  4861.4 1910.41  4866.4 1911.74
  4904.6 1908.38  4985.5 1907.21  4989.6 1903.82  4990.7 1903.32  5042.0 1903.82
  5046.2 1908.07  5061.5 1908.69  5066.6 1911.10  5117.0 1910.04  5129.9 1911.81
  5238.4 1911.80  5380.1 1915.53  5525.2 1916.08  5774.6 1921.70  6585.0 1921.47
#Mann=3,-1,0
  3959.2   0.035       0  4989.6   0.035       0  5042.0   0.035       0
Bank Sta=4989.6,5042
Exp/Cntr=0.3,0.1

Type RM Length L Ch R = 1,10466,316,316,316
BEGIN DESCRIPTION:
Alkali Creek 9.22
END DESCRIPTION:
XS GIS Cut Line= 2
      1388915.86      6971638.54      1389346.60      6969052.36
#Sta/Elev= 30
  4009.6 1920.89  4582.8 1913.69  4760.2 1914.03  4765.3 1911.77  4821.1 1912.84
  4826.2 1910.74  4881.9 1912.53  4887.0 1910.02  4942.8 1911.84  4947.8 1908.80
  4993.5 1907.17  4997.7 1903.40  4998.8 1902.90  5050.1 1903.40  5054.3 1908.61
  5130.4 1913.43  5135.5 1911.87  5191.2 1913.40  5196.3 1911.94  5252.1 1913.21
  5257.2 1911.67  5378.8 1912.71  5617.2 1917.04  5622.2 1918.41  5678.0 1917.63
  5738.9 1918.70  5743.9 1920.07  5916.0 1920.93  5926.5 1922.27  6631.4 1920.87
#Mann=3,-1,0
  4009.6   0.035       0  4997.7   0.035       0  5050.1   0.035       0
Bank Sta=4997.7,5050.1
Exp/Cntr=0.3,0.1

Type RM Length L Ch R = 1,10150,553,553,553
BEGIN DESCRIPTION:
Alkali Creek 9.2
END DESCRIPTION:
XS GIS Cut Line= 3
      1389549.46      6971257.53      1389287.76      6970649.76
      1389389.48      6969064.54
#Sta/Elev= 30
  4419.0 1929.50  4496.8 1929.68  4549.3 1925.94  4590.9 1926.21  4608.4 1924.49
  4625.4 1922.84  4667.0 1922.73  4701.6 1919.48  4734.2 1919.32  4772.0 1916.12
  4819.0 1915.53  4877.0 1910.19  4918.6 1911.03  4952.8 1907.03  4973.4 1906.82
  4984.7 1906.98  4991.1 1902.63  4992.1 1902.13  5043.5 1902.63  5047.2 1908.16
  5323.0 1910.79  5421.7 1910.28  5483.3 1909.68  5586.3 1911.63  5739.6 1917.62
  5914.2 1921.77  6051.1 1922.78  6335.1 1919.77  6596.2 1920.09  6669.2 1920.89
#Mann=8,-1,0
  4419.0   0.035       0  4608.4    0.07       0  4952.8    0.16       0
  4973.4    0.07       0  4991.1    0.07       0  5043.5    0.07       0
  5421.7   0.045       0  6596.2   0.035       0
Bank Sta=4991.1,5043.5
Exp/Cntr=0.3,0.1

Type RM Length L Ch R = 1,9597,648,648,648
BEGIN DESCRIPTION:
Alkali Creek 9.1
END DESCRIPTION:
XS GIS Cut Line= 3
      1389557.29      6971182.04      1389731.83      6970546.51
      1389406.84      6968856.13
#Sta/Elev= 30
  4176.9 1929.55  4340.0 1926.23  4394.7 1922.87  4471.5 1922.57  4533.7 1919.16
  4567.4 1920.07  4601.8 1916.79  4658.1 1914.92  4720.7 1915.18  4782.6 1912.64
  4829.1 1913.42  4847.7 1911.15  4899.4 1909.76  4966.8 1907.96  4977.0 1906.69
  4982.4 1900.88  4983.4 1900.38  5034.8 1900.88  5038.1 1904.65  5068.7 1908.74
  5139.9 1907.39  5290.7 1909.27  5400.4 1912.11  5476.0 1915.80  5496.4 1918.88
  5542.3 1919.42  5659.3 1921.22  5720.4 1919.75  6493.5 1920.62  6557.3 1921.62
#Mann=9,-1,0
  4176.9   0.035       0  4394.7    0.07       0  4899.4    0.16       0
  4982.4    0.07       0  5034.8    0.16       0  5290.7   0.045       0
  5400.4    0.07       0  5542.3   0.045       0  6493.5   0.035       0
Bank Sta=4982.4,5034.8
Exp/Cntr=0.3,0.1

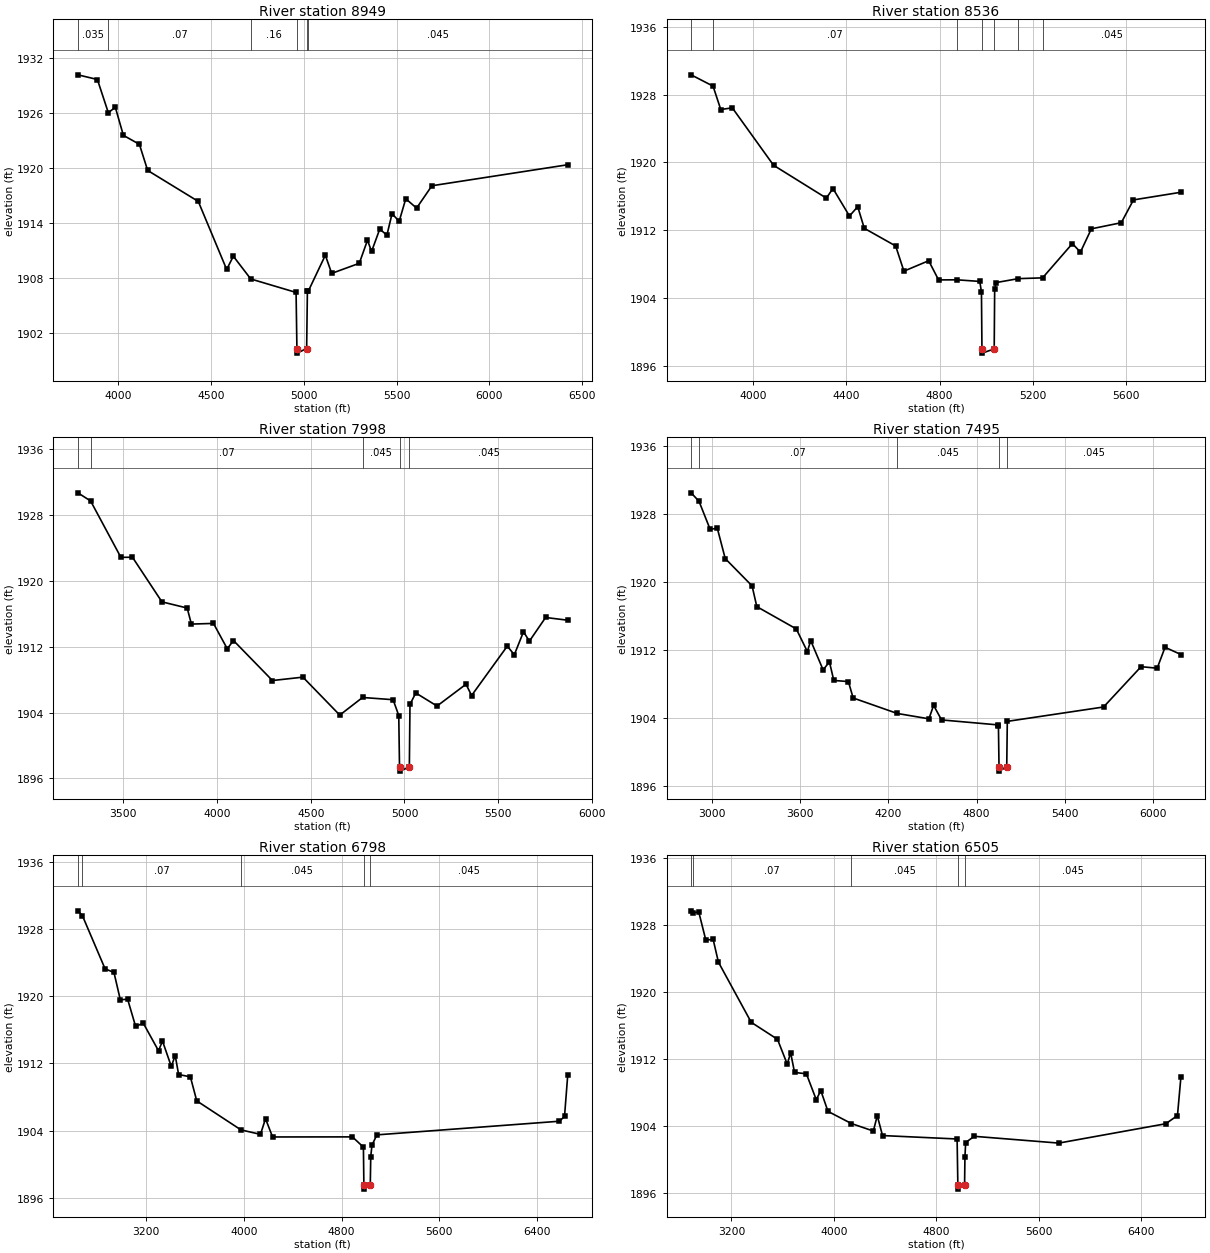
Type RM Length L Ch R = 1,8949,413,413,413
BEGIN DESCRIPTION:
Alkali Creek 9.0
END DESCRIPTION:
XS GIS Cut Line= 5
      1389578.40      6971204.77      1390136.78      6970222.10
      1390155.00      6970138.00      1390166.29      6970020.71
      1389559.57      6968865.57
#Sta/Elev= 30
  3783.3 1930.21  3888.3 1929.70  3947.1 1926.08  3984.9 1926.67  4028.2 1923.61
  4114.6 1922.63  4159.1 1919.78  4431.8 1916.40  4584.7 1908.98  4620.7 1910.42
  4714.5 1907.94  4958.7 1906.47  4963.2 1900.35  4964.2 1899.85  5015.6 1900.35
  5019.7 1906.67  5024.7 1906.62  5116.3 1910.53  5150.6 1908.55  5299.3 1909.65
  5343.4 1912.17  5365.4 1910.94  5409.5 1913.38  5448.0 1912.72  5475.7 1915.06
  5514.1 1914.23  5549.7 1916.69  5607.9 1915.67  5690.5 1918.11  6422.2 1920.40
#Mann=6,-1,0
  3783.3   0.035       0  3947.1    0.07       0  4714.5    0.16       0
  4963.2    0.07       0  5015.6    0.16       0  5024.7   0.045       0
Bank Sta=4963.2,5015.6
Exp/Cntr=0.3,0.1

Type RM Length L Ch R = 1,8536,538,538,538
BEGIN DESCRIPTION:
Alkali Creek 8.5
END DESCRIPTION:
XS GIS Cut Line= 3
      1389619.78      6971192.48      1390656.25      6970145.59
      1390406.87      6969571.49
#Sta/Elev= 30
  3734.8 1930.32  3828.8 1928.99  3861.9 1926.23  3911.3 1926.43  4088.2 1919.66
  4314.4 1915.79  4342.7 1916.92  4413.4 1913.68  4448.8 1914.78  4477.0 1912.23
  4611.4 1910.15  4646.8 1907.18  4752.9 1908.41  4795.3 1906.15  4874.8 1906.16
  4972.0 1905.97  4979.1 1904.71  4981.2 1898.02  4982.2 1897.52  5033.7 1898.02
  5035.7 1905.09  5042.8 1905.84  5137.1 1906.30  5241.0 1906.39  5368.8 1910.43
  5403.2 1909.42  5450.1 1912.17  5578.3 1912.89  5630.6 1915.58  5833.9 1916.48
#Mann=7,-1,0
  3734.8   0.035       0  3828.8    0.07       0  4874.8   0.045       0
  4981.2   0.045       0  5033.7   0.045       0  5137.1    0.07       0
  5241.0   0.045       0
Bank Sta=4981.2,5033.7
Exp/Cntr=0.3,0.1

Type RM Length L Ch R = 1,7998,503,503,503
BEGIN DESCRIPTION:
Alkali Creek 8.4
END DESCRIPTION:
XS GIS Cut Line= 4
      1389640.59      6971192.48      1390983.61      6970529.93
      1391035.82      6970134.62      1390680.02      6969513.04
#Sta/Elev= 30
  3258.4 1930.71  3326.1 1929.72  3487.6 1922.87  3549.4 1922.88  3706.5 1917.46
  3841.2 1916.71  3863.7 1914.76  3981.5 1914.84  4055.0 1911.76  4088.2 1912.76
  4295.9 1907.90  4458.6 1908.31  4655.1 1903.70  4776.6 1905.84  4939.5 1905.57
  4969.7 1903.65  4973.7 1897.39  4974.8 1896.89  5026.2 1897.39  5029.5 1905.00
  5060.5 1906.39  5173.8 1904.80  5328.4 1907.45  5358.2 1906.08  5548.6 1912.08
  5586.0 1911.03  5634.9 1913.82  5666.6 1912.69  5752.9 1915.56  5870.9 1915.23
#Mann=5,-1,0
  3258.4   0.035       0  3326.1    0.07       0  4776.6   0.045       0
  4973.7   0.045       0  5026.2   0.045       0
Bank Sta=4973.7,5026.2
Exp/Cntr=0.3,0.1

Type RM Length L Ch R = 1,7495,697,697,697
BEGIN DESCRIPTION:
Alkali Creek 8.3
END DESCRIPTION:
XS GIS Cut Line= 4
      1389658.89      6971200.26      1391464.42      6970488.48
      1391498.21      6970178.77      1391114.78      6969166.89
#Sta/Elev= 30
  2857.2 1930.46  2910.9 1929.47  2986.7 1926.17  3035.5 1926.30  3089.5 1922.73
  3272.2 1919.52  3304.5 1917.08  3573.2 1914.46  3648.4 1911.80  3671.5 1913.08
  3755.9 1909.64  3798.8 1910.59  3828.6 1908.40  3927.9 1908.27  3960.2 1906.34
  4260.5 1904.52  4476.1 1903.89  4508.0 1905.47  4562.1 1903.76  4943.0 1903.18
  4949.3 1903.05  4953.3 1898.24  4954.3 1897.74  5005.8 1898.24  5009.7 1903.59
  5665.0 1905.28  5920.3 1910.02  6030.0 1909.84  6083.5 1912.30  6191.6 1911.45
#Mann=5,-1,0
  2857.2   0.035       0  2910.9    0.07       0  4260.5   0.045       0
  4953.3   0.045       0  5005.8   0.045       0
Bank Sta=4953.3,5005.8
Exp/Cntr=0.3,0.1

Type RM Length L Ch R = 1,6798,293,293,293
BEGIN DESCRIPTION:
Alkali Creek 8.2
END DESCRIPTION:
XS GIS Cut Line= 4
      1389681.82      6971210.27      1391648.44      6970622.16
      1392067.60      6970650.84      1393529.96      6970163.01
#Sta/Elev= 30
  2639.5 1930.14  2676.2 1929.57  2862.0 1923.25  2935.1 1922.81  2987.3 1919.55
  3046.7 1919.65  3112.5 1916.40  3175.1 1916.79  3300.4 1913.50  3332.5 1914.67
  3404.8 1911.65  3437.0 1912.94  3464.9 1910.68  3561.3 1910.41  3613.5 1907.55
  3976.1 1904.10  4135.7 1903.57  4177.1 1905.43  4235.0 1903.26  4889.2 1903.27
  4979.4 1902.05  4983.2 1897.56  4984.3 1897.06  5035.7 1897.56  5039.5 1900.93
  5049.6 1902.28  5089.7 1903.51  6585.4 1905.13  6627.6 1905.70  6653.9 1910.61
#Mann=5,-1,0
  2639.5   0.035       0  2676.2    0.07       0  3976.1   0.045       0
  4983.2   0.045       0  5035.7   0.045       0
Bank Sta=4983.2,5035.7
Exp/Cntr=0.3,0.1

Type RM Length L Ch R = 1,6505,337,337,337
BEGIN DESCRIPTION:
Alkali Creek 8.1
END DESCRIPTION:
XS GIS Cut Line= 4
      1389706.99      6971217.98      1391655.09      6970778.63
      1391930.00      6970918.19      1393421.52      6970629.18
#Sta/Elev= 30
  2884.7 1929.73  2901.2 1929.48  2944.2 1929.61  2999.4 1926.24  3056.9 1926.31
  3097.9 1923.60  3354.2 1916.41  3559.2 1914.38  3635.4 1911.41  3661.7 1912.78
  3692.5 1910.42  3784.8 1910.26  3861.8 1907.17  3897.5 1908.25  3953.3 1905.77
  4135.9 1904.32  4307.6 1903.42  4338.3 1905.25  4379.3 1902.88  4961.7 1902.47
  4967.5 1896.98  4968.6 1896.48  5020.0 1896.98  5022.9 1900.33  5028.5 1902.05
  5095.3 1902.79  5755.4 1901.98  6590.6 1904.29  6682.3 1905.27  6709.3 1909.90
#Mann=5,-1,0
  2884.7   0.035       0  2901.2    0.07       0  4135.9   0.045       0
  4967.5   0.045       0  5020.0   0.045       0
Bank Sta=4967.5,5020
Exp/Cntr=0.3,0.1

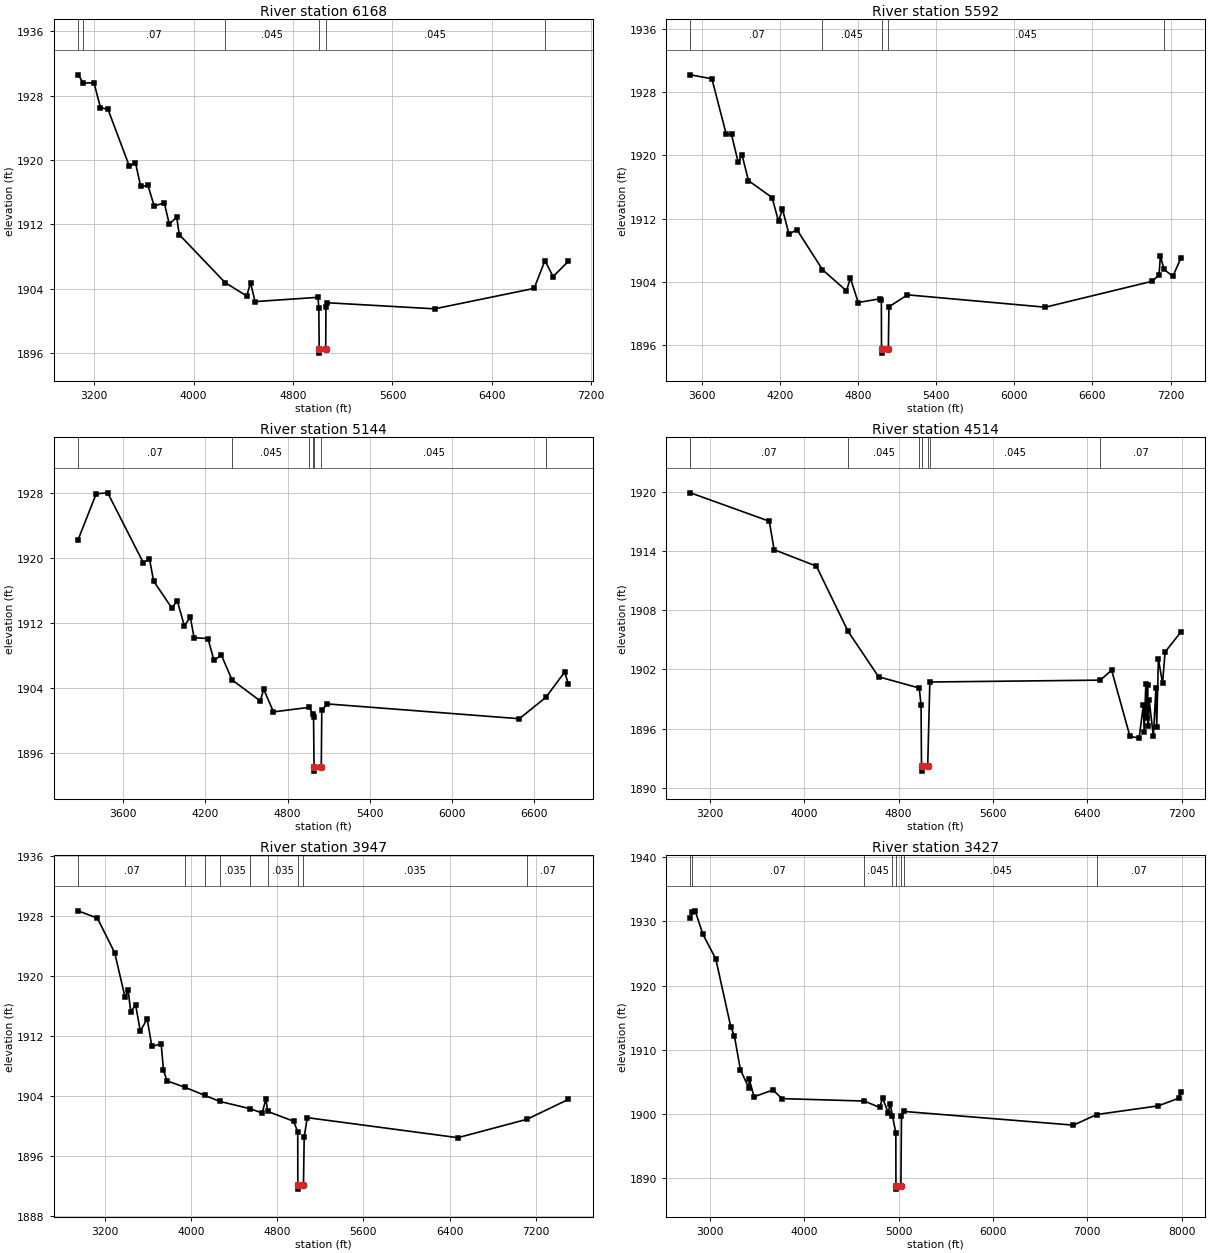
Type RM Length L Ch R = 1,6168,576,576,576
BEGIN DESCRIPTION:
Alkali Creek 8.0
END DESCRIPTION:
XS GIS Cut Line= 4
      1389695.77      6971257.26      1391553.44      6971055.00
      1391699.53      6971151.05      1393566.20      6970786.04
#Sta/Elev= 30
  3070.5 1930.58  3114.1 1929.57  3198.8 1929.58  3250.8 1926.50  3311.1 1926.30
  3483.3 1919.22  3532.4 1919.65  3574.7 1916.72  3633.0 1916.84  3683.3 1914.27
  3763.8 1914.70  3804.0 1912.07  3864.4 1912.88  3884.5 1910.74  4252.9 1904.79
  4427.7 1903.11  4457.9 1904.78  4494.4 1902.42  5000.8 1902.95  5007.6 1901.61
  5010.5 1896.52  5011.5 1896.02  5063.0 1896.52  5064.8 1901.78  5072.7 1902.28
  5938.7 1901.52  6739.7 1904.06  6826.5 1907.51  6892.5 1905.52  7016.0 1907.44
#Mann=6,-1,0
  3070.5   0.035       0  3114.1    0.07       0  4252.9   0.045       0
  5010.5   0.045       0  5063.0   0.045       0  6826.5    0.07       0
Bank Sta=5010.5,5063
Exp/Cntr=0.3,0.1

Type RM Length L Ch R = 1,5592,448,448,448
BEGIN DESCRIPTION:
Alkali Creek 7.0
END DESCRIPTION:
XS GIS Cut Line= 4
      1389780.91      6971314.98      1391098.15      6971416.98
      1391307.19      6971544.05      1393448.23      6971038.62
#Sta/Elev= 30
  3513.3 1930.16  3677.9 1929.66  3788.2 1922.63  3828.3 1922.63  3879.9 1919.09
  3908.6 1920.08  3958.7 1916.80  4139.8 1914.66  4189.4 1911.67  4219.5 1913.22
  4269.7 1910.03  4329.8 1910.63  4526.9 1905.56  4711.0 1902.88  4741.1 1904.49
  4801.2 1901.41  4971.2 1901.89  4979.0 1901.68  4980.1 1895.52  4981.1 1895.02
  5032.6 1895.52  5037.1 1900.87  5179.6 1902.38  6237.9 1900.82  7059.9 1904.10
  7111.3 1904.91  7121.6 1907.31  7149.1 1905.59  7217.8 1904.72  7279.0 1907.03
#Mann=5,-1,0
  3513.3    0.07       0  4526.9   0.045       0  4980.1   0.045       0
  5032.6   0.045       0  7149.1    0.07       0
Bank Sta=4980.1,5032.6
Exp/Cntr=0.3,0.1

Type RM Length L Ch R = 1,5144,630,630,630
BEGIN DESCRIPTION:
Alkali Creek 6.0
END DESCRIPTION:
XS GIS Cut Line= 4
      1389552.34      6971639.32      1391095.91      6971914.76
      1391326.43      6971926.85      1393051.15      6971497.26
#Sta/Elev= 30
  3272.7 1922.22  3404.9 1927.89  3488.7 1928.01  3748.4 1919.41  3793.5 1919.87
  3823.9 1917.15  3956.0 1913.84  3996.6 1914.72  4047.4 1911.66  4091.9 1912.67
  4118.5 1910.19  4220.1 1910.07  4263.6 1907.40  4317.5 1908.04  4395.4 1904.99
  4602.0 1902.39  4626.4 1903.84  4697.5 1901.05  4958.5 1901.61  4985.2 1900.80
  4989.9 1900.40  4993.7 1894.26  4994.7 1893.76  5046.3 1894.26  5050.0 1901.26
  5091.6 1902.03  6490.6 1900.21  6684.1 1902.84  6821.0 1905.95  6848.9 1904.45
#Mann=7,-1,0
  3272.7    0.07       0  4395.4   0.045       0  4958.5    0.07       0
  4985.2   0.045       0  4993.7   0.045       0  5046.3   0.045       0
  6684.1    0.07       0
Bank Sta=4993.7,5046.3
Exp/Cntr=0.3,0.1

Type RM Length L Ch R = 1,4514,567,567,567
BEGIN DESCRIPTION:
Alkali Creek 5.0
END DESCRIPTION:
XS GIS Cut Line= 5
      1389302.31      6972014.31      1391145.38      6972496.04
      1391286.44      6972502.55      1392300.06      6972332.69
      1393015.75      6971519.40
#Sta/Elev= 30
  3035.3 1919.90  3703.6 1917.02  3744.0 1914.14  4102.8 1912.47  4370.8 1905.87
  4629.8 1901.26  4974.7 1900.12  4990.0 1898.36  4993.7 1892.20  4994.7 1891.70
  5046.3 1892.20  5064.3 1900.73  6509.8 1900.92  6605.2 1901.93  6760.8 1895.22
  6838.6 1895.05  6874.6 1898.39  6881.3 1895.65  6895.5 1900.53  6902.2 1897.10
  6909.8 1900.40  6916.4 1896.28  6924.0 1898.87  6959.1 1895.23  6980.9 1900.09
  6987.6 1896.21  7001.8 1903.08  7036.9 1900.60  7058.7 1903.77  7192.6 1905.80
#Mann=7,-1,0
  3035.3    0.07       0  4370.8   0.045       0  4974.7    0.07       0
  4993.7    0.07       0  5046.3    0.07       0  5064.3   0.045       0
  6509.8    0.07       0
Bank Sta=4993.7,5046.3
Exp/Cntr=0.3,0.1

Type RM Length L Ch R = 1,3947,520,520,520
BEGIN DESCRIPTION:
Alkali Creek 4.0
END DESCRIPTION:
XS GIS Cut Line= 5
      1389149.58      6972257.38      1390934.30      6972981.75
      1391130.15      6973040.67      1393016.07      6972889.64
      1393264.03      6972415.34
#Sta/Elev= 30
  2947.9 1928.64  3127.1 1927.67  3288.3 1923.05  3384.2 1917.13  3413.6 1918.03
  3437.7 1915.17  3482.6 1916.11  3526.2 1912.62  3590.5 1914.22  3633.7 1910.55
  3720.0 1910.91  3741.6 1907.41  3774.0 1905.97  3942.1 1905.11  4123.5 1904.04
  4266.3 1903.22  4545.6 1902.26  4658.9 1901.68  4693.9 1903.55  4710.3 1901.89
  4950.4 1900.59  4989.6 1899.17  4990.2 1892.03  4991.2 1891.53  5042.8 1892.03
  5049.5 1898.50  5078.5 1901.06  6477.9 1898.39  7119.1 1900.84  7505.7 1903.50
#Mann=9,-1,0
  2947.9    0.07       0  3942.1   0.035       0  4123.5    0.07       0
  4266.3   0.035       0  4545.6   0.045       0  4710.3   0.035       0
  4990.2   0.035       0  5042.8   0.035       0  7119.1    0.07       0
Bank Sta=4990.2,5042.8
Exp/Cntr=0.3,0.1

Type RM Length L Ch R = 1,3427,405,405,405
BEGIN DESCRIPTION:
Alkali Creek 3.0
END DESCRIPTION:
XS GIS Cut Line= 6
      1388736.34      6972990.01      1390643.50      6973375.85
      1390905.00      6973388.00      1390980.97      6973386.76
      1393021.47      6973254.86      1393266.40      6972417.67
#Sta/Elev= 30
  2791.6 1930.47  2807.8 1931.46  2841.2 1931.63  2922.9 1927.99  3059.7 1924.15
  3218.7 1913.59  3257.5 1912.14  3320.8 1906.91  3409.7 1904.07  3414.8 1905.42
  3465.5 1902.69  3668.4 1903.75  3759.5 1902.40  4634.6 1902.02  4799.0 1901.02
  4829.0 1902.51  4887.7 1900.20  4909.1 1901.63  4933.2 1899.71  4969.2 1897.07
  4970.4 1888.81  4971.4 1888.31  5023.0 1888.81  5029.2 1899.74  5057.5 1900.40
  6852.9 1898.27  7099.8 1899.92  7751.4 1901.27  7972.8 1902.48  7992.2 1903.50
#Mann=8,-1,0
  2791.6   0.035       0  2807.8    0.07       0  4634.6   0.045       0
  4933.2    0.07       0  4970.4    0.07       0  5023.0    0.07       0
  5057.5   0.045       0  7099.8    0.07       0
Bank Sta=4970.4,5023
Exp/Cntr=0.3,0.1

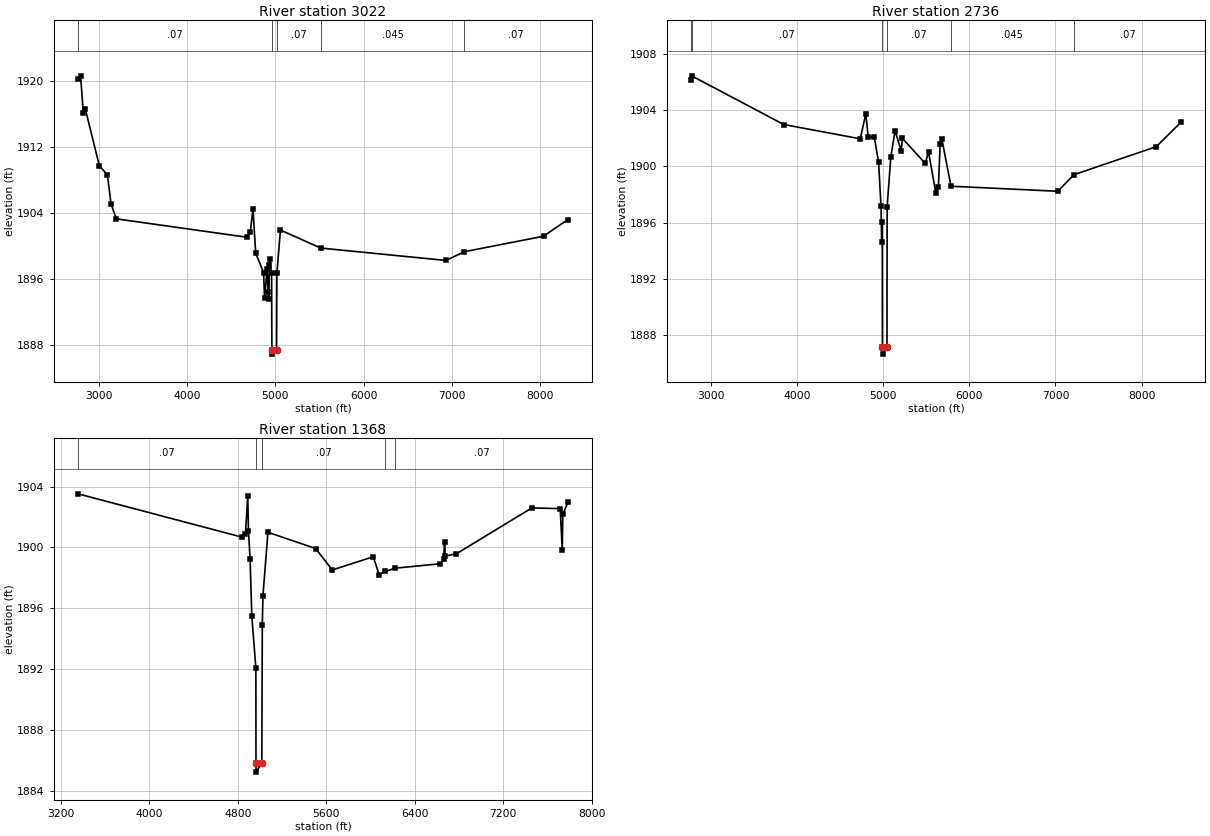
Type RM Length L Ch R = 1,3022,286,286,286
BEGIN DESCRIPTION:
Alkali Creek 2.0
END DESCRIPTION:
XS GIS Cut Line= 6
      1388646.14      6973490.03      1390347.49      6973760.85
      1391118.33      6973712.24      1392968.15      6973400.19
      1393223.83      6973357.06      1393386.55      6972456.64
#Sta/Elev= 30
  2768.2 1920.26  2797.4 1920.65  2827.8 1916.16  2851.9 1916.57  3010.1 1909.71
  3100.7 1908.63  3141.7 1905.10  3202.5 1903.29  4678.9 1901.06  4718.9 1901.75
  4749.0 1904.52  4779.3 1899.13  4869.2 1896.77  4879.3 1893.67  4909.3 1897.21
  4919.3 1894.46  4928.9 1893.57  4933.9 1897.70  4939.4 1898.38  4959.4 1896.68
  4963.1 1887.37  4964.1 1886.87  5015.9 1887.37  5019.5 1896.68  5059.6 1901.93
  5517.7 1899.74  6933.3 1898.24  7141.5 1899.30  8037.8 1901.18  8313.6 1903.20
#Mann=5,-1,0
  2768.2    0.07       0  4963.1    0.07       0  5015.9    0.07       0
  5517.7   0.045       0  7141.5    0.07       0
Bank Sta=4963.1,5015.9
Exp/Cntr=0.3,0.1

Type RM Length L Ch R = 1,2736,1368,1368,1368
BEGIN DESCRIPTION:
Alkali Creek 1.0
END DESCRIPTION:
XS GIS Cut Line= 5
      1388725.95      6974444.88      1390594.34      6974246.60
      1391115.17      6973783.06      1393298.66      6973414.13
      1393475.77      6972538.31
#Sta/Elev= 30
  2772.2 1906.16  2778.3 1906.46  3847.2 1902.99  4735.3 1901.97  4799.2 1903.76
  4827.3 1902.13  4898.4 1902.08  4947.7 1900.31  4976.2 1897.15  4983.7 1894.58
  4990.4 1896.03  4992.4 1887.12  4993.4 1886.62  5045.2 1887.12  5047.2 1897.13
  5089.9 1900.67  5139.2 1902.56  5210.3 1901.12  5224.5 1902.00  5490.1 1900.21
  5527.2 1901.05  5611.8 1898.12  5642.2 1898.55  5662.5 1901.63  5682.8 1901.93
  5788.2 1898.59  7028.0 1898.23  7213.9 1899.41  8170.4 1901.41  8456.3 1903.15
#Mann=6,-1,0
  2772.2   0.035       0  2778.3    0.07       0  4992.4    0.07       0
  5045.2    0.07       0  5788.2   0.045       0  7213.9    0.07       0
Bank Sta=4992.4,5045.2
Exp/Cntr=0.3,0.1

Type RM Length L Ch R = 1,1368,331,331,331
BEGIN DESCRIPTION:
Alkali Creek 0.5
END DESCRIPTION:
XS GIS Cut Line= 5
      1390270.72      6974912.47      1391744.49      6974011.84
      1392717.38      6973988.79      1393642.98      6973434.83
      1393596.63      6972788.84
#Sta/Elev= 30
  3357.0 1903.52  4838.7 1900.67  4869.5 1900.89  4890.8 1903.35  4897.3 1901.06
  4912.1 1899.23  4927.5 1895.47  4964.3 1892.05  4965.1 1885.81  4966.1 1885.21
  5017.9 1885.81  5022.4 1894.90  5028.2 1896.83  5073.1 1900.99  5504.8 1899.92
  5654.9 1898.51  6025.0 1899.38  6077.9 1898.20  6131.2 1898.41  6225.6 1898.63
  6632.4 1898.92  6660.6 1899.20  6669.3 1900.34  6675.2 1899.42  6777.1 1899.58
  7457.9 1902.59  7714.4 1902.55  7733.0 1899.85  7738.0 1902.16  7783.7 1902.96
#Mann=5,-1,0
  3357.0    0.07       0  4965.1    0.07       0  5017.9    0.07       0
  6131.2   0.045       0  6225.6    0.07       0
Bank Sta=4965.1,5017.9
Exp/Cntr=0.3,0.1