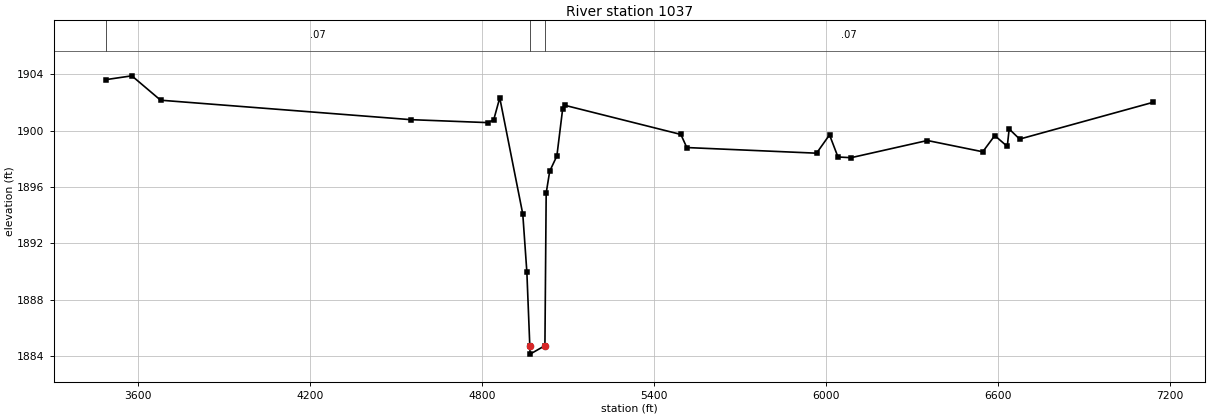
HEC-RAS study Alkali Creek.prj: Alkali Creek Base Level Engineering

--- Alkali Creek.g01 (geometry) --- (continued)

Type RM Length L Ch R = 1,1037,0,0,0
BEGIN DESCRIPTION:
Alkali Creek 0.2
END DESCRIPTION:
XS GIS Cut Line= 5
      1390566.12      6975102.44      1391903.28      6974278.03
      1392957.76      6973997.12      1393338.66      6973724.27
      1393745.19      6973391.87
#Sta/Elev= 30
  3486.7 1903.62  3577.2 1903.89  3677.7 1902.16  4550.6 1900.78  4819.1 1900.57
  4840.4 1900.75  4861.7 1902.33  4942.1 1894.08  4956.3 1889.98  4966.6 1884.74
  4967.6 1884.14  5019.4 1884.74  5023.8 1895.57  5036.1 1897.12  5061.1 1898.20
  5081.2 1901.52  5090.4 1901.79  5494.0 1899.73  5514.7 1898.80  5967.7 1898.40
  6013.0 1899.70  6042.5 1898.13  6088.1 1898.08  6354.6 1899.30  6548.0 1898.50
  6589.8 1899.65  6633.6 1898.88  6640.1 1900.12  6676.7 1899.40  7142.5 1902.01
#Mann=3,-1,0
  3486.7    0.07       0  4966.6    0.07       0  5019.4    0.07       0
Bank Sta=4966.6,5019.4
Exp/Cntr=0.3,0.1

Chan Stop Cuts=-1