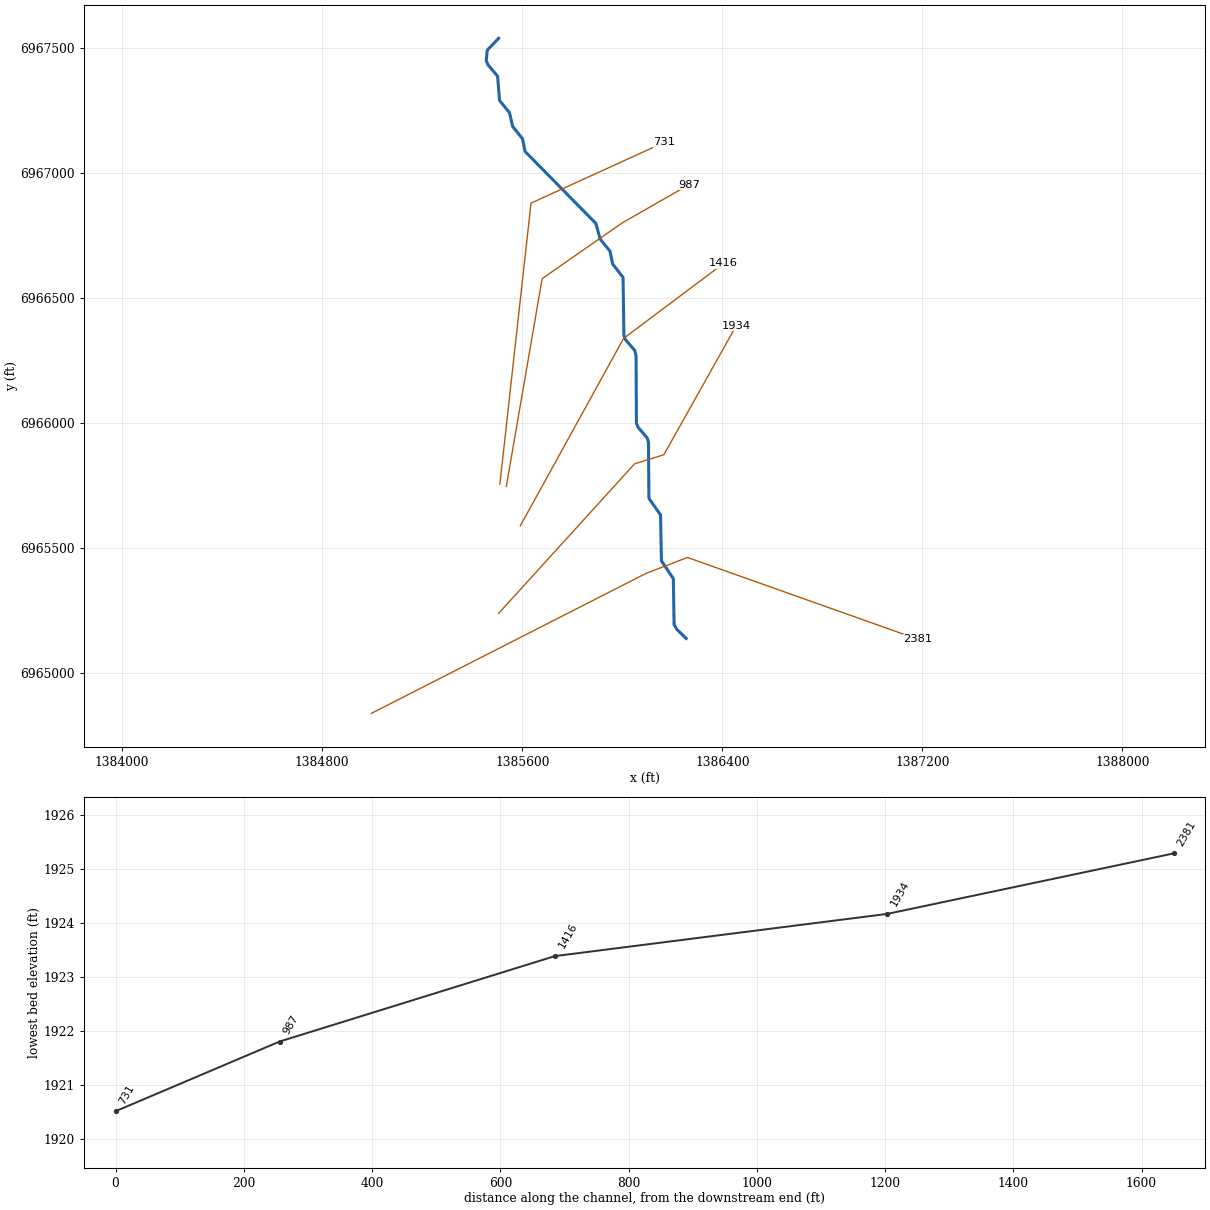
--- Alkali Creek Trib 01.prj (project) ---

Proj Title=Alkali Creek Trib 01 Base Level Engineering
Current Plan=p01
Default Exp/Contr=0.3,0.1
English Units
Geom File=g01
Flow File=f01
Plan File=p01
BEGIN DESCRIPTION:
Alkali Creek Trib 01
END DESCRIPTION:

--- Alkali Creek Trib 01.p01 (plan) ---

Plan Title=Multiple Run
Short Identifier=Multiple
Geom File=g01
Flow File=f01
Subcritical Flow
K Sum by GR= 0
Std Step Tol= 0.01
Critical Tol= 0.01
Num of Std Step Trials= 20
Max Error Tol= 0.3
Flow Tol Ratio= 0.001
Split Flow NTrial= 30
Split Flow Tol= 0.02
Split Flow Ratio= 0.02
Log Output Level= 0
Friction Slope Method= 1
Unsteady Friction Slope Method= 2
Unsteady Bridges Friction Slope Method= 1
Parabolic Critical Depth
Global Vel Dist=  1 , 1 , 1
Global Log Level= 0
CheckData=True
Encroach Param= -1, 0, 0, 0
BEGIN DESCRIPTION:
Multiple Run
END DESCRIPTION:

--- Alkali Creek Trib 01.f01 (steady flow) ---

Flow Title=Multiple
Number of Profiles=7
Profile Names=10-year,25-year,50-year,1pct_min,100-year,1pct_plu,500-year
River Rch & RM= Alkali Creek Tri,Reach-1,2381
     206     284     347     211     420     838     625
Boundary for River Rch & Prof#=Alkali Creek Tri,Reach-1,1
Up Type=0
Dn Type=3
Dn Slope=0.005
Boundary for River Rch & Prof#=Alkali Creek Tri,Reach-1,2
Up Type=0
Dn Type=3
Dn Slope=0.005
Boundary for River Rch & Prof#=Alkali Creek Tri,Reach-1,3
Up Type=0
Dn Type=3
Dn Slope=0.005
Boundary for River Rch & Prof#=Alkali Creek Tri,Reach-1,4
Up Type=0
Dn Type=3
Dn Slope=0.005
Boundary for River Rch & Prof#=Alkali Creek Tri,Reach-1,5
Up Type=0
Dn Type=3
Dn Slope=0.005
Boundary for River Rch & Prof#=Alkali Creek Tri,Reach-1,6
Up Type=0
Dn Type=3
Dn Slope=0.005
Boundary for River Rch & Prof#=Alkali Creek Tri,Reach-1,7
Up Type=0
Dn Type=3
Dn Slope=0.005

--- Alkali Creek Trib 01.g01 (geometry) ---

Geom Title=Existing Conditions

River Reach=Alkali Creek Tri,Reach-1
Reach XY= 30
      1386255.00      6965138.00      1386217.92      6965174.50
      1386206.89      6965193.78      1386203.78      6965377.49
      1386156.22      6965448.51      1386152.74      6965632.06
      1386106.22      6965698.50      1386104.48      6965922.78
      1386099.25      6965940.33      1386063.14      6965981.94
      1386056.22      6965998.50      1386054.93      6966267.97
      1386049.25      6966290.33      1386013.14      6966331.94
      1386006.22      6966348.50      1386002.76      6966582.07
      1385961.12      6966635.82      1385950.84      6966686.28
      1385911.10      6966735.81      1385894.24      6966797.68
      1385610.83      6967085.70      1385600.81      6967136.26
      1385561.08      6967185.80      1385548.88      6967240.18
      1385508.83      6967289.58      1385501.13      6967386.42
      1385462.82      6967432.05      1385455.68      6967448.63
      1385459.61      6967490.37      1385505.00      6967538.00

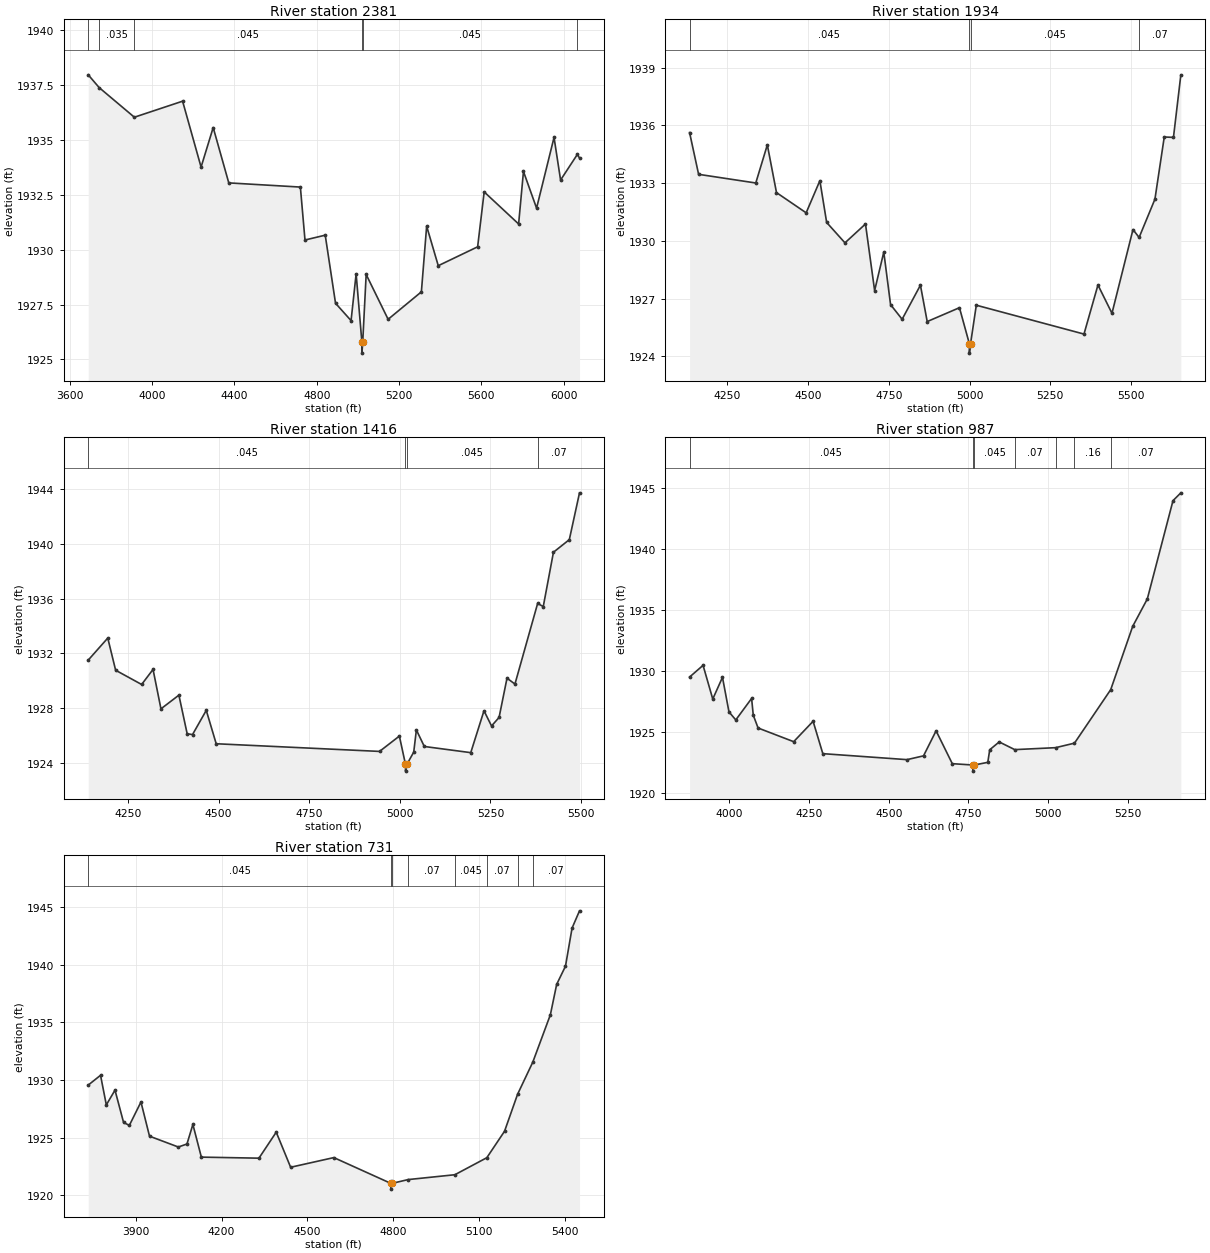
Type RM Length L Ch R = 1,2381,447,447,447
BEGIN DESCRIPTION:
Alkali Creek Trib 01 4.0
END DESCRIPTION:
XS GIS Cut Line= 4
      1384996.29      6964838.48      1386094.15      6965398.03
      1386260.17      6965462.05      1387181.67      6965134.95
#Sta/Elev= 30
  3689.1 1937.96  3742.1 1937.38  3913.3 1936.03  4147.8 1936.76  4237.6 1933.76
  4296.5 1935.56  4372.3 1933.04  4720.3 1932.85  4742.7 1930.44  4841.1 1930.66
  4891.2 1927.56  4966.7 1926.77  4991.3 1928.90  5019.3 1925.79  5019.5 1925.29
  5023.3 1925.79  5040.1 1928.87  5146.8 1926.83  5308.5 1928.08  5334.1 1931.07
  5390.5 1929.27  5581.9 1930.13  5613.7 1932.63  5781.1 1931.17  5804.7 1933.56
  5868.4 1931.89  5953.3 1935.11  5985.1 1933.17  6066.8 1934.34  6077.1 1934.17
#Mann=6,-1,0
  3689.1   0.045       0  3742.1   0.035       0  3913.3   0.045       0
  5019.3   0.045       0  5023.3   0.045       0  6066.8   0.035       0
Bank Sta=5019.3,5023.3
Exp/Cntr=0.3,0.1

Type RM Length L Ch R = 1,1934,518,518,518
BEGIN DESCRIPTION:
Alkali Creek Trib 01 3.0
END DESCRIPTION:
XS GIS Cut Line= 4
      1385505.01      6965238.01      1386048.85      6965836.33
      1386166.04      6965872.78      1386455.01      6966388.01
#Sta/Elev= 30
  4132.5 1935.63  4160.5 1933.46  4337.6 1933.01  4373.4 1934.99  4401.8 1932.51
  4493.7 1931.46  4536.2 1933.13  4557.2 1930.96  4613.9 1929.90  4677.5 1930.88
  4705.8 1927.42  4734.2 1929.42  4755.2 1926.69  4791.0 1925.93  4847.7 1927.70
  4868.7 1925.81  4968.6 1926.53  4999.1 1924.67  4999.4 1924.17  5003.1 1924.67
  5020.8 1926.66  5354.4 1925.16  5397.7 1927.71  5441.1 1926.24  5506.2 1930.59
  5525.2 1930.18  5574.2 1932.17  5603.1 1935.40  5631.6 1935.38  5654.5 1938.63
#Mann=4,-1,0
  4132.5   0.045       0  4999.1   0.045       0  5003.1   0.045       0
  5525.2    0.07       0
Bank Sta=4999.1,5003.1
Exp/Cntr=0.3,0.1

Type RM Length L Ch R = 1,1416,429,429,429
BEGIN DESCRIPTION:
Alkali Creek Trib 01 2.0
END DESCRIPTION:
XS GIS Cut Line= 3
      1385592.27      6965588.97      1386005.00      6966338.00
      1386404.99      6966637.99
#Sta/Elev= 30
  4140.5 1931.50  4194.4 1933.11  4216.1 1930.76  4287.8 1929.72  4319.3 1930.82
  4341.1 1927.94  4390.6 1928.94  4413.4 1926.12  4428.2 1926.06  4466.1 1927.83
  4493.5 1925.39  4944.1 1924.83  4998.8 1925.95  5015.6 1923.89  5015.8 1923.39
  5019.6 1923.89  5038.4 1924.78  5045.7 1926.40  5067.6 1925.19  5195.7 1924.74
  5232.2 1927.80  5253.0 1926.69  5273.8 1927.31  5295.7 1930.18  5317.6 1929.75
  5380.2 1935.64  5395.7 1935.41  5423.8 1939.38  5467.6 1940.30  5495.7 1943.72
#Mann=4,-1,0
  4140.5   0.045       0  5015.6   0.045       0  5019.6   0.045       0
  5380.2    0.07       0
Bank Sta=5015.6,5019.6
Exp/Cntr=0.3,0.1

Type RM Length L Ch R = 1,987,256,256,256
BEGIN DESCRIPTION:
Alkali Creek Trib 01 1.0
END DESCRIPTION:
XS GIS Cut Line= 4
      1385536.04      6965746.32      1385679.27      6966577.07
      1385999.70      6966800.05      1386266.08      6966952.50
#Sta/Elev= 30
  3875.7 1929.51  3918.0 1930.47  3948.4 1927.71  3978.9 1929.49  3999.2 1926.66
  4020.6 1926.00  4070.2 1927.76  4075.4 1926.39  4090.5 1925.34  4202.1 1924.22
  4263.0 1925.89  4293.5 1923.24  4557.3 1922.75  4609.2 1923.06  4648.6 1925.11
  4699.4 1922.42  4764.2 1922.31  4764.5 1921.81  4768.2 1922.31  4810.7 1922.53
  4816.8 1923.56  4846.5 1924.20  4895.2 1923.57  5023.3 1923.73  5082.5 1924.10
  5196.1 1928.48  5265.0 1933.66  5310.8 1935.90  5391.4 1943.95  5416.0 1944.59
#Mann=7,-1,0
  3875.7   0.045       0  4764.2    0.07       0  4768.2   0.045       0
  4895.2    0.07       0  5023.3   0.045       0  5082.5    0.16       0
  5196.1    0.07       0
Bank Sta=4764.2,4768.2
Exp/Cntr=0.3,0.1

Type RM Length L Ch R = 1,731,0,0,0
BEGIN DESCRIPTION:
Alkali Creek Trib 01 0.5
END DESCRIPTION:
XS GIS Cut Line= 3
      1385510.25      6965755.22      1385634.67      6966878.91
      1386167.62      6967121.94
#Sta/Elev= 30
  3734.0 1929.56  3777.0 1930.41  3797.2 1927.84  3827.5 1929.12  3857.5 1926.31
  3877.7 1926.06  3918.2 1928.09  3948.1 1925.12  4048.7 1924.18  4078.9 1924.44
  4099.6 1926.14  4129.2 1923.30  4330.4 1923.21  4390.8 1925.47  4441.1 1922.42
  4592.0 1923.26  4791.2 1921.02  4791.5 1920.52  4795.2 1921.02  4851.8 1921.35
  5014.8 1921.77  5126.5 1923.25  5188.4 1925.55  5233.9 1928.76  5287.2 1931.56
  5348.5 1935.67  5370.5 1938.31  5401.3 1939.89  5424.3 1943.20  5450.3 1944.70
#Mann=8,-1,0
  3734.0   0.045       0  4791.2    0.07       0  4795.2   0.045       0
  4851.8    0.07       0  5014.8   0.045       0  5126.5    0.07       0
  5233.9    0.16       0  5287.2    0.07       0
Bank Sta=4791.2,4795.2
Exp/Cntr=0.3,0.1

Chan Stop Cuts=-1