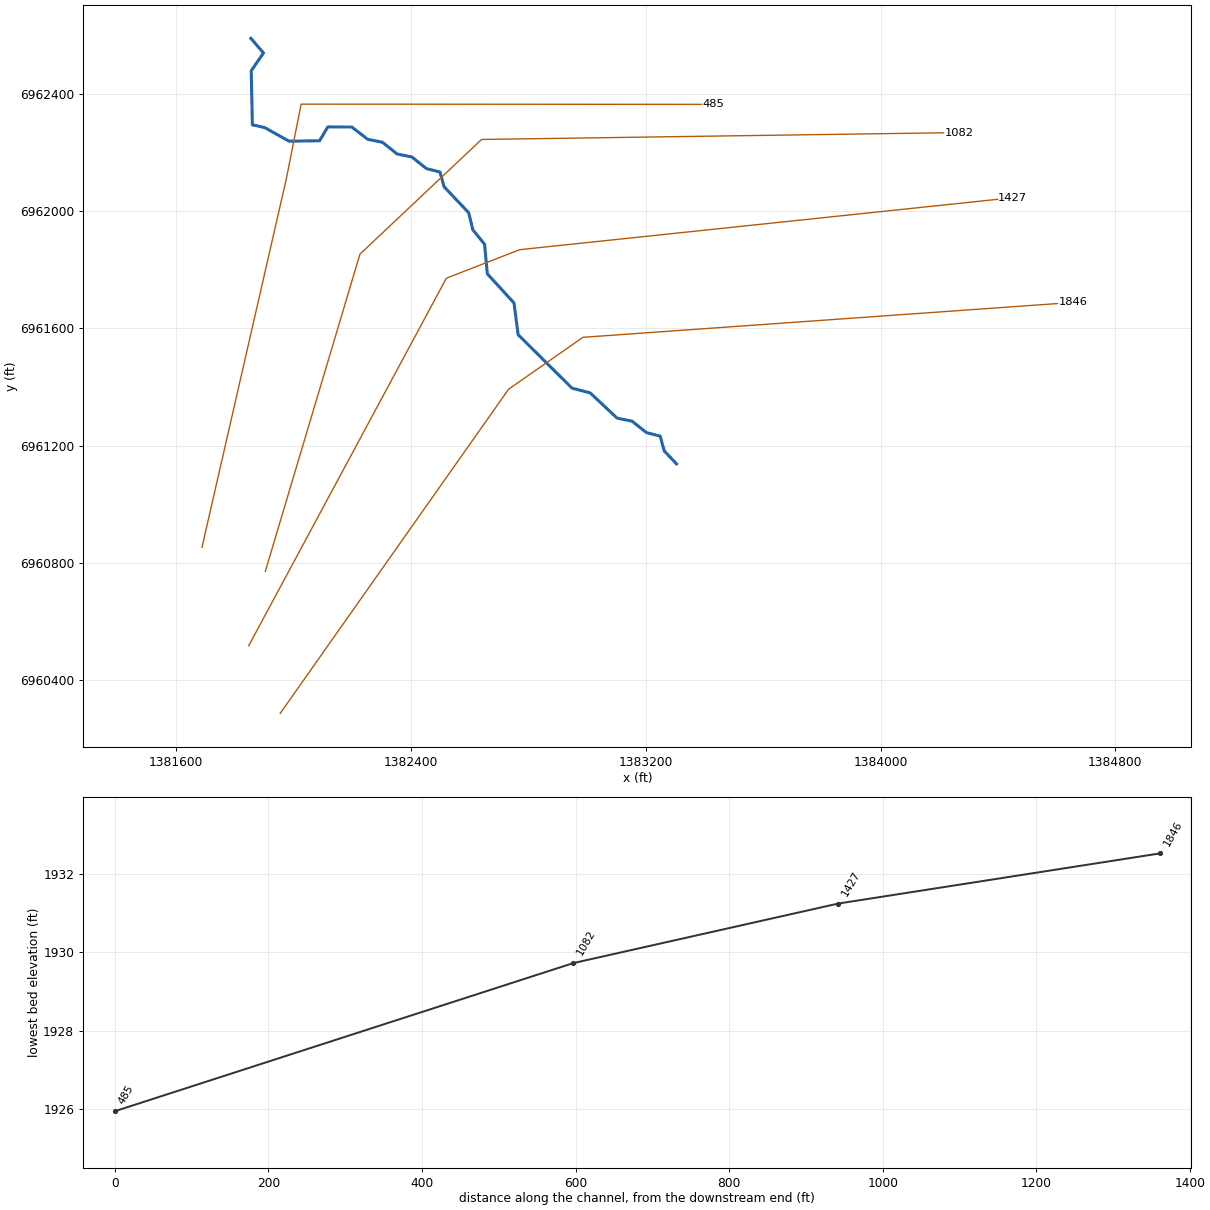
--- Alkali Creek Trib 02-01.prj (project) ---

Proj Title=Alkali Creek Trib 02-01 Base Level Engineering
Current Plan=p01
Default Exp/Contr=0.3,0.1
English Units
Geom File=g01
Flow File=f01
Plan File=p01
BEGIN DESCRIPTION:
Alkali Creek Trib 02-01
END DESCRIPTION:

--- Alkali Creek Trib 02-01.p01 (plan) ---

Plan Title=Multiple Run
Short Identifier=Multiple
Geom File=g01
Flow File=f01
Subcritical Flow
K Sum by GR= 0
Std Step Tol= 0.01
Critical Tol= 0.01
Num of Std Step Trials= 20
Max Error Tol= 0.3
Flow Tol Ratio= 0.001
Split Flow NTrial= 30
Split Flow Tol= 0.02
Split Flow Ratio= 0.02
Log Output Level= 0
Friction Slope Method= 1
Unsteady Friction Slope Method= 2
Unsteady Bridges Friction Slope Method= 1
Parabolic Critical Depth
Global Vel Dist=  1 , 1 , 1
Global Log Level= 0
CheckData=True
Encroach Param= -1, 0, 0, 0
BEGIN DESCRIPTION:
Multiple Run
END DESCRIPTION:

--- Alkali Creek Trib 02-01.f01 (steady flow) ---

Flow Title=Multiple
Number of Profiles=7
Profile Names=10-year,25-year,50-year,1pct_min,100-year,1pct_plu,500-year
River Rch & RM= Alkali Creek Tri,Reach-1,1846
     203     277     337     204     407     812     600
Boundary for River Rch & Prof#=Alkali Creek Tri,Reach-1,1
Up Type=0
Dn Type=3
Dn Slope=0.005
Boundary for River Rch & Prof#=Alkali Creek Tri,Reach-1,2
Up Type=0
Dn Type=3
Dn Slope=0.005
Boundary for River Rch & Prof#=Alkali Creek Tri,Reach-1,3
Up Type=0
Dn Type=3
Dn Slope=0.005
Boundary for River Rch & Prof#=Alkali Creek Tri,Reach-1,4
Up Type=0
Dn Type=3
Dn Slope=0.005
Boundary for River Rch & Prof#=Alkali Creek Tri,Reach-1,5
Up Type=0
Dn Type=3
Dn Slope=0.005
Boundary for River Rch & Prof#=Alkali Creek Tri,Reach-1,6
Up Type=0
Dn Type=3
Dn Slope=0.005
Boundary for River Rch & Prof#=Alkali Creek Tri,Reach-1,7
Up Type=0
Dn Type=3
Dn Slope=0.005

--- Alkali Creek Trib 02-01.g01 (geometry) ---

Geom Title=Existing Conditions

River Reach=Alkali Creek Tri,Reach-1
Reach XY= 30
      1383305.00      6961138.00      1383263.12      6961182.30
      1383249.58      6961232.52      1383203.14      6961244.22
      1383153.29      6961283.82      1383102.71      6961293.85
      1383011.04      6961379.82      1382948.95      6961396.16
      1382765.52      6961578.21      1382751.37      6961686.50
      1382660.54      6961785.58      1382651.17      6961886.41
      1382611.14      6961935.83      1382596.84      6961994.05
      1382513.30      6962082.26      1382499.39      6962132.41
      1382453.15      6962144.24      1382403.31      6962183.85
      1382352.81      6962194.08      1382303.28      6962233.84
      1382252.82      6962244.12      1382198.95      6962285.89
      1382117.02      6962286.15      1382089.04      6962238.94
      1381984.88      6962237.59      1381902.81      6962283.60
      1381860.17      6962293.41      1381856.31      6962477.58
      1381898.09      6962538.14      1381855.00      6962588.00

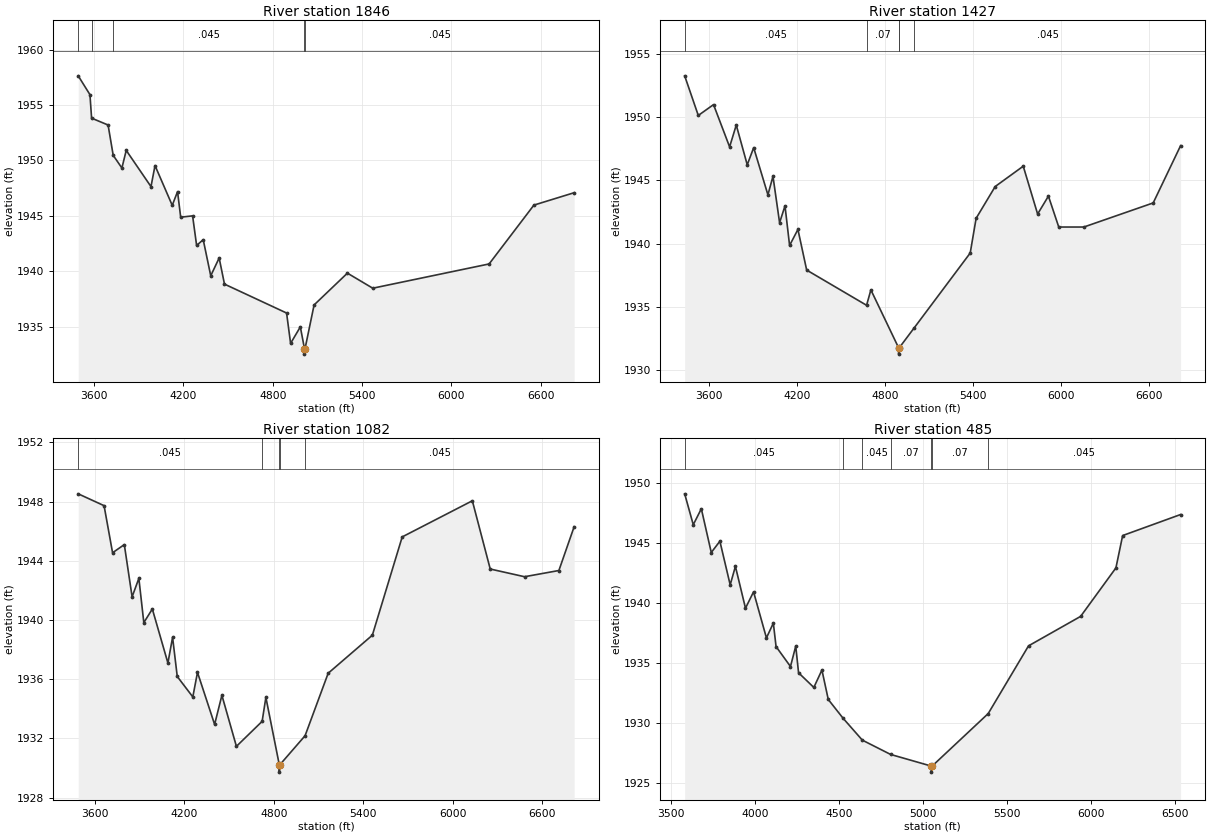
Type RM Length L Ch R = 1,1846,419,419,419
BEGIN DESCRIPTION:
Alkali Creek Trib 02-01 2.0
END DESCRIPTION:
XS GIS Cut Line= 4
      1381954.97      6960287.96      1382732.82      6961392.23
      1382986.29      6961569.31      1384654.95      6961688.00
#Sta/Elev= 30
  3492.8 1957.64  3571.7 1955.94  3582.7 1953.82  3693.6 1953.20  3728.0 1950.46
  3786.4 1949.32  3815.5 1950.91  3981.9 1947.64  4008.9 1949.54  4124.7 1945.95
  4160.4 1947.19  4181.4 1944.88  4261.5 1945.00  4288.5 1942.33  4332.9 1942.85
  4383.4 1939.59  4440.0 1941.20  4475.7 1938.84  4893.1 1936.23  4920.1 1933.49
  4985.5 1934.98  5013.2 1933.02  5013.4 1932.52  5017.2 1933.02  5078.0 1936.96
  5301.8 1939.83  5472.2 1938.47  6254.2 1940.66  6555.0 1945.97  6825.6 1947.09
#Mann=5,-1,0
  3492.8   0.045       0  3582.7   0.035       0  3728.0   0.045       0
  5013.2   0.045       0  5017.2   0.045       0
Bank Sta=5013.2,5017.2
Exp/Cntr=0.3,0.1

Type RM Length L Ch R = 1,1427,345,345,345
BEGIN DESCRIPTION:
Alkali Creek Trib 02-01 1.0
END DESCRIPTION:
XS GIS Cut Line= 4
      1381847.70      6960518.40      1382521.01      6961770.70
      1382771.01      6961867.92      1384450.74      6962044.92
#Sta/Elev= 30
  3434.6 1953.29  3527.3 1950.15  3631.2 1951.01  3740.7 1947.66  3786.1 1949.39
  3860.9 1946.24  3904.7 1947.60  4001.8 1943.86  4036.2 1945.33  4081.3 1941.65
  4118.1 1942.99  4149.4 1939.85  4206.2 1941.12  4265.8 1937.90  4674.0 1935.11
  4703.3 1936.33  4892.3 1931.74  4892.5 1931.24  4896.4 1931.74  4999.6 1933.34
  5380.1 1939.25  5420.3 1942.00  5550.4 1944.52  5741.4 1946.13  5839.4 1942.34
  5913.0 1943.76  5983.4 1941.31  6154.3 1941.31  6626.9 1943.22  6813.7 1947.76
#Mann=5,-1,0
  3434.6   0.045       0  4674.0    0.07       0  4892.3   0.045       0
  4896.4    0.07       0  4999.6   0.045       0
Bank Sta=4892.3,4896.4
Exp/Cntr=0.3,0.1

Type RM Length L Ch R = 1,1082,597,597,597
BEGIN DESCRIPTION:
Alkali Creek Trib 02-01 0.5
END DESCRIPTION:
XS GIS Cut Line= 4
      1381904.28      6960771.90      1382226.54      6961852.51
      1382640.95      6962243.46      1384267.32      6962266.92
#Sta/Elev= 30
  3489.8 1948.52  3663.1 1947.72  3720.1 1944.54  3798.8 1945.09  3851.0 1941.56
  3896.3 1942.81  3929.5 1939.82  3986.6 1940.74  4091.0 1937.09  4122.3 1938.83
  4153.6 1936.18  4257.9 1934.80  4289.2 1936.46  4404.0 1932.94  4452.8 1934.91
  4550.1 1931.46  4722.5 1933.15  4747.6 1934.77  4837.4 1930.22  4837.7 1929.72
  4841.5 1930.22  5010.3 1932.18  5165.1 1936.40  5461.2 1938.97  5661.3 1945.61
  6131.3 1948.05  6251.3 1943.44  6481.3 1942.92  6711.4 1943.34  6813.7 1946.30
#Mann=5,-1,0
  3489.8   0.045       0  4722.5    0.07       0  4837.4    0.07       0
  4841.5    0.07       0  5010.3   0.045       0
Bank Sta=4837.4,4841.5
Exp/Cntr=0.3,0.1

Type RM Length L Ch R = 1,485,0,0,0
BEGIN DESCRIPTION:
Alkali Creek Trib 02-01 0.3
END DESCRIPTION:
XS GIS Cut Line= 4
      1381688.49      6960853.74      1381975.45      6962107.40
      1382026.27      6962363.78      1383430.01      6962363.00
#Sta/Elev= 30
  3581.3 1949.08  3632.4 1946.51  3680.4 1947.84  3739.5 1944.20  3790.8 1945.14
  3852.1 1941.51  3883.2 1943.05  3943.1 1939.57  3991.1 1940.93  4067.8 1937.10
  4108.9 1938.33  4125.1 1936.38  4210.9 1934.72  4242.2 1936.42  4259.0 1934.20
  4349.9 1932.98  4398.0 1934.43  4435.8 1931.98  4523.9 1930.42  4638.4 1928.60
  4806.9 1927.41  5049.4 1926.44  5049.7 1925.94  5053.6 1926.44  5387.6 1930.81
  5627.5 1936.44  5937.5 1938.89  6147.5 1942.92  6187.5 1945.61  6532.5 1947.36
#Mann=7,-1,0
  3581.3   0.045       0  4523.9    0.07       0  4638.4   0.045       0
  4806.9    0.07       0  5049.4    0.07       0  5053.6    0.07       0
  5387.6   0.045       0
Bank Sta=5049.4,5053.6
Exp/Cntr=0.3,0.1

Chan Stop Cuts=-1