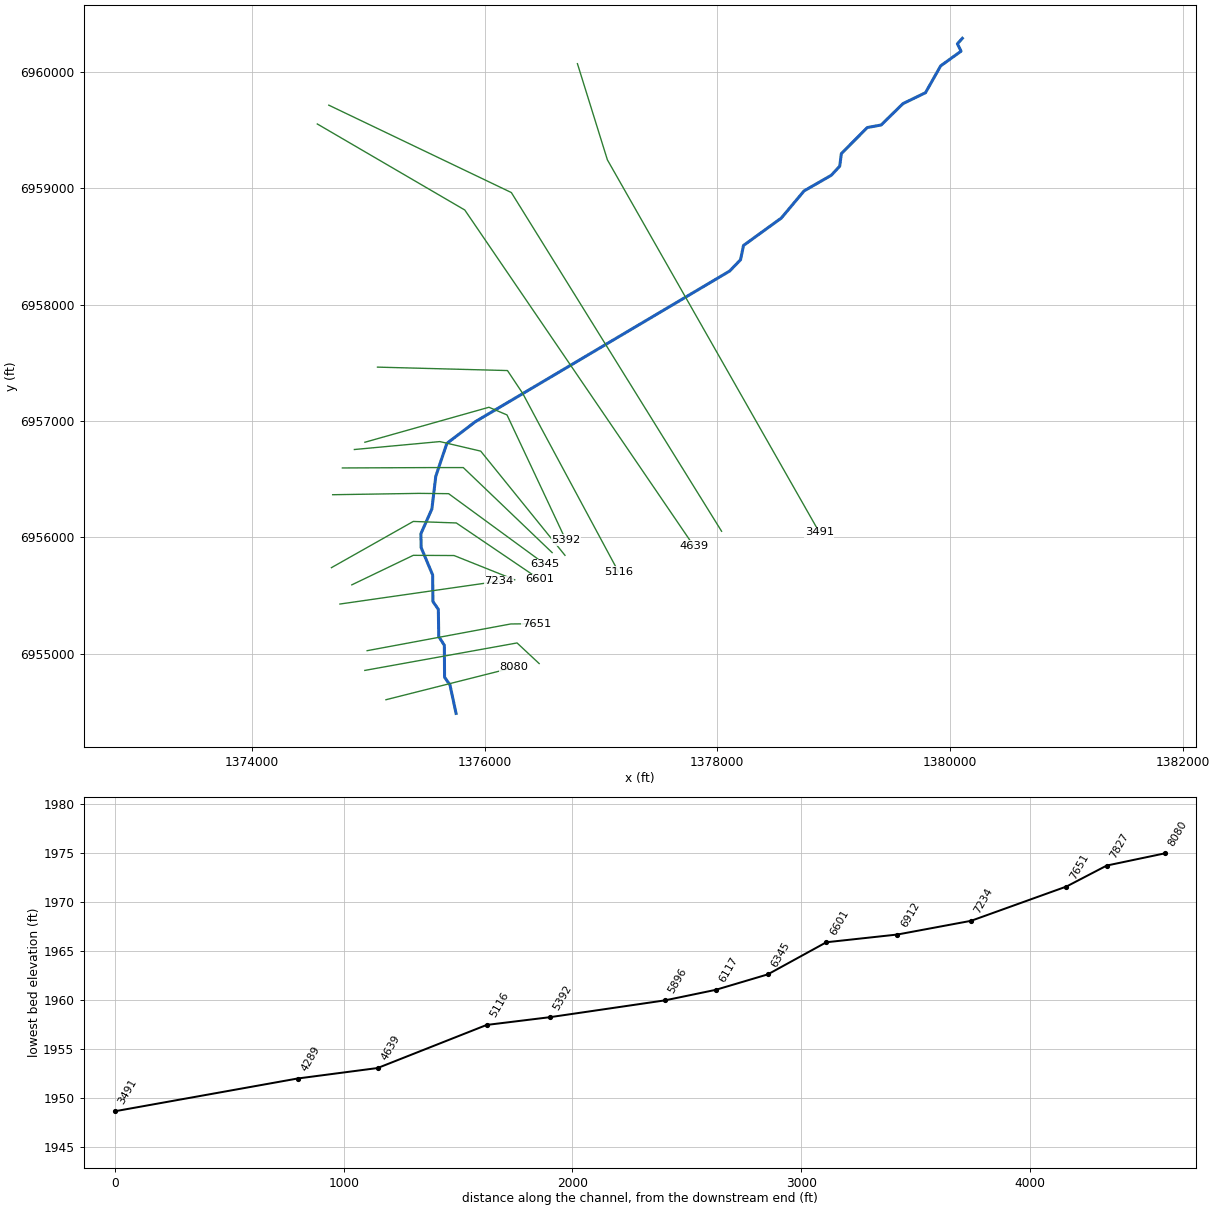
--- Alkali Creek Trib 02-02.prj (project) ---

Proj Title=Alkali Creek Trib 02-02 Base Level Engineering
Current Plan=p01
Default Exp/Contr=0.3,0.1
English Units
Geom File=g01
Flow File=f01
Plan File=p01
BEGIN DESCRIPTION:
Alkali Creek Trib 02-02
END DESCRIPTION:

--- Alkali Creek Trib 02-02.p01 (plan) ---

Plan Title=Multiple Run
Short Identifier=Multiple
Geom File=g01
Flow File=f01
Subcritical Flow
K Sum by GR= 0
Std Step Tol= 0.01
Critical Tol= 0.01
Num of Std Step Trials= 20
Max Error Tol= 0.3
Flow Tol Ratio= 0.001
Split Flow NTrial= 30
Split Flow Tol= 0.02
Split Flow Ratio= 0.02
Log Output Level= 0
Friction Slope Method= 1
Unsteady Friction Slope Method= 2
Unsteady Bridges Friction Slope Method= 1
Parabolic Critical Depth
Global Vel Dist=  1 , 1 , 1
Global Log Level= 0
CheckData=True
Encroach Param= -1, 0, 0, 0
BEGIN DESCRIPTION:
Multiple Run
END DESCRIPTION:

--- Alkali Creek Trib 02-02.f01 (steady flow) ---

Flow Title=Multiple
Number of Profiles=7
Profile Names=10-year,25-year,50-year,1pct_min,100-year,1pct_plu,500-year
River Rch & RM= Alkali Creek Tri,Reach-1,8080
     291     413     515     320     639    1274     993
River Rch & RM= Alkali Creek Tri,Reach-1,6601
     471     686     871     550    1097    2188    1760
Boundary for River Rch & Prof#=Alkali Creek Tri,Reach-1,1
Up Type=0
Dn Type=3
Dn Slope=0.005
Boundary for River Rch & Prof#=Alkali Creek Tri,Reach-1,2
Up Type=0
Dn Type=3
Dn Slope=0.005
Boundary for River Rch & Prof#=Alkali Creek Tri,Reach-1,3
Up Type=0
Dn Type=3
Dn Slope=0.005
Boundary for River Rch & Prof#=Alkali Creek Tri,Reach-1,4
Up Type=0
Dn Type=3
Dn Slope=0.005
Boundary for River Rch & Prof#=Alkali Creek Tri,Reach-1,5
Up Type=0
Dn Type=3
Dn Slope=0.005
Boundary for River Rch & Prof#=Alkali Creek Tri,Reach-1,6
Up Type=0
Dn Type=3
Dn Slope=0.005
Boundary for River Rch & Prof#=Alkali Creek Tri,Reach-1,7
Up Type=0
Dn Type=3
Dn Slope=0.005

--- Alkali Creek Trib 02-02.g01 (geometry) ---

Geom Title=Existing Conditions

River Reach=Alkali Creek Tri,Reach-1
Reach XY= 30
      1375755.00      6954488.00      1375702.73      6954732.06
      1375656.22      6954798.50      1375654.48      6955072.78
      1375606.22      6955148.50      1375602.74      6955382.06
      1375556.22      6955448.50      1375553.78      6955677.50
      1375454.82      6955912.93      1375452.92      6956032.14
      1375547.22      6956244.36      1375580.82      6956525.52
      1375675.75      6956807.37      1375921.46      6956994.68
      1378105.00      6958288.00      1378199.48      6958385.57
      1378224.61      6958508.20      1378549.38      6958743.62
      1378745.32      6958977.22      1378978.52      6959110.99
      1379051.39      6959189.49      1379065.52      6959297.79
      1379288.25      6959521.54      1379407.43      6959543.52
      1379595.32      6959727.24      1379788.58      6959820.92
      1379918.61      6960051.24      1380093.97      6960177.67
      1380062.53      6960241.32      1380105.00      6960288.00

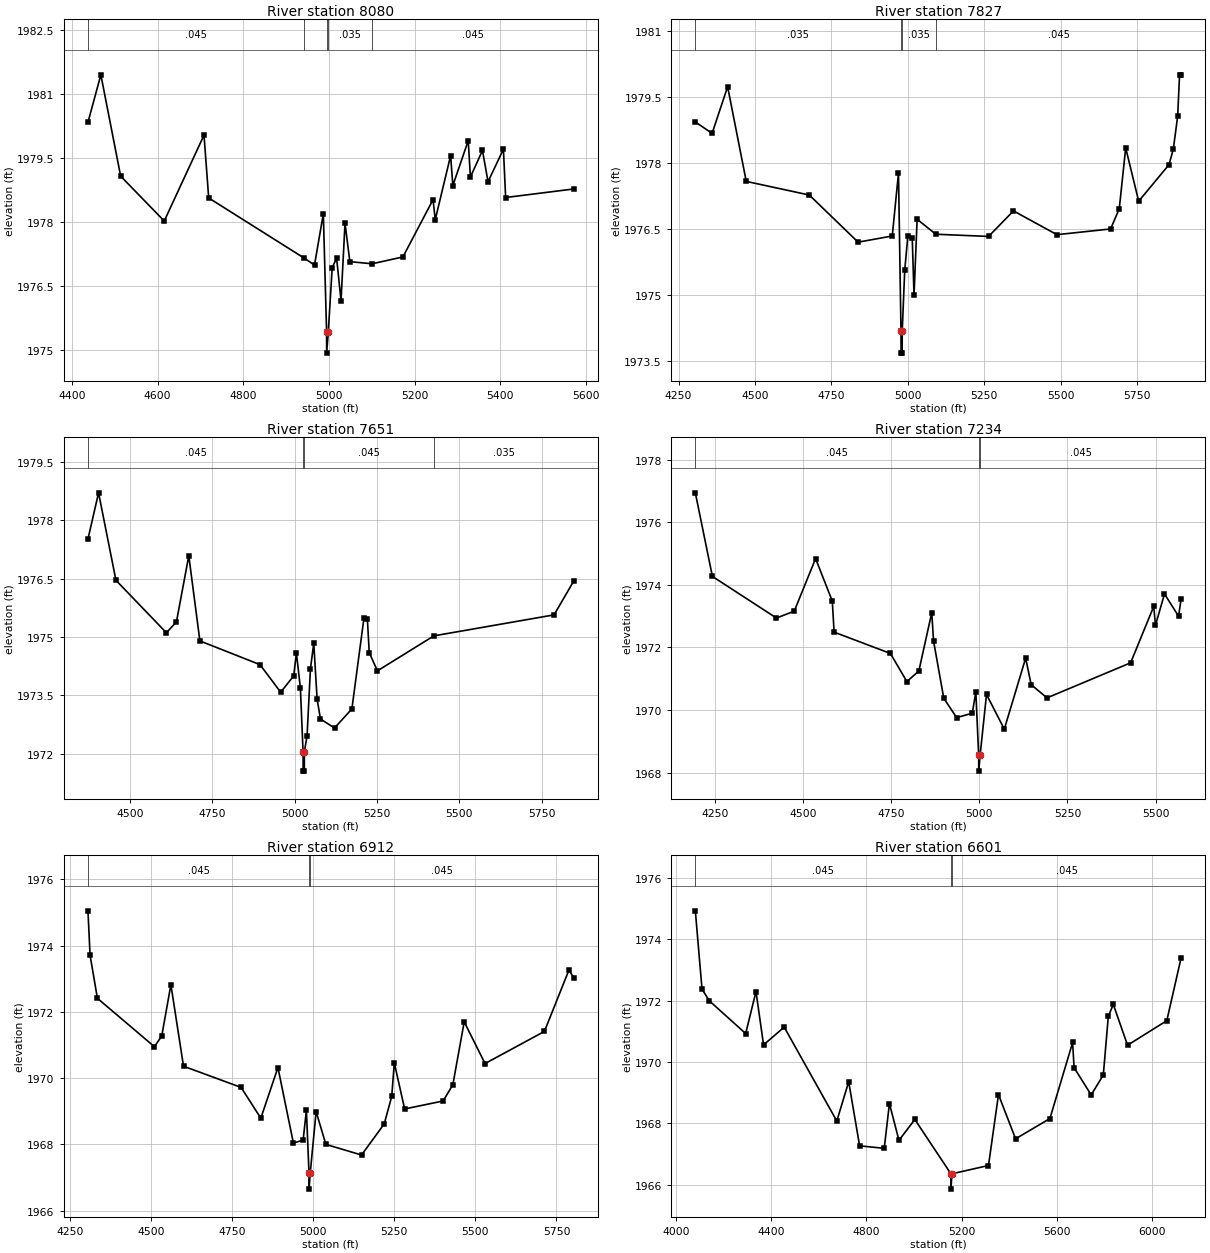
Type RM Length L Ch R = 1,8080,253,253,253
BEGIN DESCRIPTION:
Alkali Creek Trib 02-02 12.0
END DESCRIPTION:
XS GIS Cut Line= 2
      1375152.46      6954605.21      1376251.51      6954882.54
#Sta/Elev= 30
  4437.7 1980.33  4467.8 1981.44  4514.0 1979.07  4615.7 1978.02  4708.5 1980.03
  4719.4 1978.56  4941.1 1977.16  4966.3 1976.99  4986.9 1978.19  4994.5 1975.43
  4994.7 1974.93  4998.5 1975.43  5007.6 1976.93  5017.9 1977.15  5028.2 1976.16
  5037.5 1977.97  5048.8 1977.07  5100.7 1977.02  5172.6 1977.18  5242.9 1978.52
  5248.0 1978.05  5283.9 1979.55  5289.1 1978.85  5325.0 1979.90  5330.1 1979.05
  5358.2 1979.67  5371.2 1978.94  5407.1 1979.70  5412.3 1978.57  5571.2 1978.77
#Mann=5,-1,0
  4437.7   0.045       0  4941.1   0.035       0  4994.5   0.035       0
  4998.5   0.035       0  5100.7   0.045       0
Bank Sta=4994.5,4998.5
Exp/Cntr=0.3,0.1

Type RM Length L Ch R = 1,7827,176,176,176
BEGIN DESCRIPTION:
Alkali Creek Trib 02-02 11.0
END DESCRIPTION:
XS GIS Cut Line= 3
      1374971.12      6954857.15      1376279.06      6955093.17
      1376469.00      6954916.01
#Sta/Elev= 30
  4305.0 1978.94  4359.8 1978.68  4410.6 1979.74  4471.5 1977.59  4677.8 1977.28
  4837.3 1976.21  4949.1 1976.35  4969.4 1977.78  4977.6 1974.19  4977.9 1973.69
  4981.4 1973.69  4981.6 1974.19  4989.8 1975.57  4999.9 1976.34  5014.4 1976.31
  5020.2 1975.00  5030.4 1976.73  5091.5 1976.39  5264.1 1976.34  5345.4 1976.92
  5487.7 1976.38  5663.2 1976.51  5691.5 1976.97  5712.5 1978.35  5755.0 1977.14
  5854.2 1977.97  5868.4 1978.33  5882.5 1979.07  5888.7 1980.01  5893.8 1980.01
#Mann=4,-1,0
  4305.0   0.035       0  4977.6   0.035       0  4981.6   0.035       0
  5091.5   0.045       0
Bank Sta=4977.6,4981.6
Exp/Cntr=0.3,0.1

Type RM Length L Ch R = 1,7651,417,417,417
BEGIN DESCRIPTION:
Alkali Creek Trib 02-02 10.0
END DESCRIPTION:
XS GIS Cut Line= 3
      1374990.80      6955026.64      1376225.14      6955256.29
      1376444.81      6955258.33
#Sta/Elev= 30
  4372.1 1977.52  4404.3 1978.71  4457.1 1976.46  4610.3 1975.11  4640.8 1975.39
  4678.3 1977.09  4712.0 1974.90  4894.5 1974.29  4957.4 1973.58  4996.8 1974.00
  5005.1 1974.59  5017.2 1973.69  5025.3 1972.05  5025.6 1971.55  5029.1 1971.55
  5029.3 1972.05  5037.5 1972.46  5047.7 1974.18  5057.8 1974.84  5068.0 1973.40
  5078.2 1972.89  5120.8 1972.66  5173.6 1973.15  5210.4 1975.50  5220.6 1975.46
  5226.3 1974.60  5251.1 1974.13  5422.5 1975.03  5787.5 1975.57  5847.3 1976.44
#Mann=4,-1,0
  4372.1   0.045       0  5025.3   0.045       0  5029.3   0.045       0
  5422.5   0.035       0
Bank Sta=5025.3,5029.3
Exp/Cntr=0.3,0.1

Type RM Length L Ch R = 1,7234,322,322,322
BEGIN DESCRIPTION:
Alkali Creek Trib 02-02 9.0
END DESCRIPTION:
XS GIS Cut Line= 2
      1374757.12      6955427.49      1376121.73      6955623.39
#Sta/Elev= 30
  4194.0 1976.94  4242.4 1974.27  4424.2 1972.94  4474.7 1973.16  4535.3 1974.84
  4582.7 1973.48  4587.8 1972.49  4747.5 1971.81  4794.4 1970.91  4828.3 1971.25
  4864.9 1973.11  4870.0 1972.21  4899.0 1970.38  4935.5 1969.76  4979.9 1969.90
  4990.0 1970.58  4998.1 1968.55  4998.3 1968.05  5002.1 1968.55  5020.3 1970.50
  5070.8 1969.39  5131.4 1971.66  5147.1 1970.81  5192.0 1970.39  5429.3 1971.51
  5494.8 1973.31  5499.8 1972.71  5525.4 1973.71  5565.3 1973.00  5572.6 1973.55
#Mann=3,-1,0
  4194.0   0.045       0  4998.1   0.045       0  5002.1   0.045       0
Bank Sta=4998.1,5002.1
Exp/Cntr=0.3,0.1

Type RM Length L Ch R = 1,6912,311,311,311
BEGIN DESCRIPTION:
Alkali Creek Trib 02-02 8.0
END DESCRIPTION:
XS GIS Cut Line= 4
      1374859.53      6955592.40      1375387.34      6955845.89
      1375738.04      6955844.15      1376258.89      6955635.81
#Sta/Elev= 30
  4306.0 1975.05  4312.5 1973.71  4335.1 1972.41  4510.7 1970.95  4533.4 1971.27
  4561.6 1972.82  4600.5 1970.36  4778.0 1969.72  4838.8 1968.79  4891.5 1970.32
  4939.2 1968.04  4969.2 1968.13  4979.2 1969.03  4987.2 1967.15  4987.4 1966.65
  4991.2 1967.15  5009.2 1968.99  5039.2 1968.00  5149.2 1967.68  5219.2 1968.62
  5242.2 1969.45  5250.2 1970.46  5282.0 1969.07  5400.5 1969.31  5430.6 1969.80
  5465.6 1971.70  5529.8 1970.44  5712.8 1971.41  5788.7 1973.27  5803.2 1973.02
#Mann=3,-1,0
  4306.0   0.045       0  4987.2   0.045       0  4991.2   0.045       0
Bank Sta=4987.2,4991.2
Exp/Cntr=0.3,0.1

Type RM Length L Ch R = 1,6601,256,256,256
BEGIN DESCRIPTION:
Alkali Creek Trib 02-02 7.0
END DESCRIPTION:
XS GIS Cut Line= 4
      1374684.25      6955740.01      1375387.39      6956137.06
      1375757.15      6956124.09      1376471.20      6955640.11
#Sta/Elev= 30
  4082.0 1974.93  4110.0 1972.38  4140.3 1972.00  4293.4 1970.93  4336.7 1972.30
  4368.5 1970.56  4455.1 1971.14  4676.1 1968.08  4726.0 1969.36  4771.9 1967.27
  4875.3 1967.19  4897.1 1968.65  4937.1 1967.45  5003.8 1968.13  5155.2 1966.36
  5155.5 1965.86  5159.4 1966.36  5313.1 1966.63  5355.1 1968.94  5426.9 1967.50
  5571.0 1968.16  5666.5 1970.64  5672.5 1969.82  5744.4 1968.93  5795.3 1969.58
  5816.3 1971.49  5837.3 1971.88  5897.1 1970.55  6061.9 1971.35  6122.1 1973.40
#Mann=3,-1,0
  4082.0   0.045       0  5155.2   0.045       0  5159.4   0.045       0
Bank Sta=5155.2,5159.4
Exp/Cntr=0.3,0.1

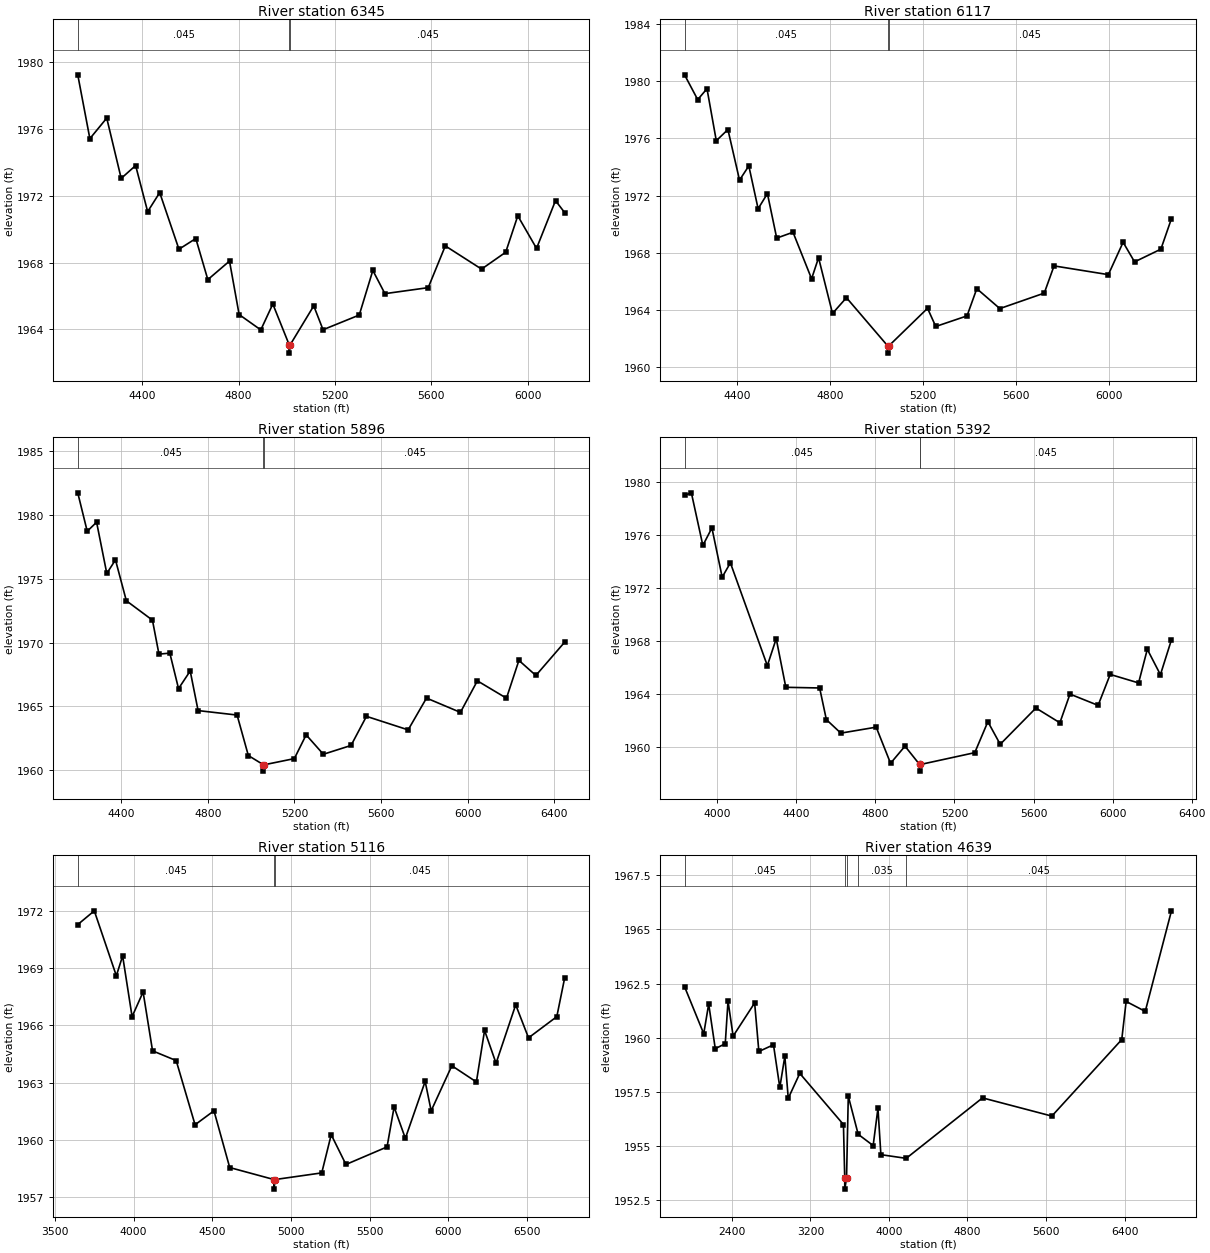
Type RM Length L Ch R = 1,6345,228,228,228
BEGIN DESCRIPTION:
Alkali Creek Trib 02-02 6.0
END DESCRIPTION:
XS GIS Cut Line= 4
      1374694.66      6956366.72      1375435.38      6956378.26
      1375691.11      6956375.69      1376519.31      6955769.49
#Sta/Elev= 30
  4131.5 1979.24  4181.8 1975.42  4251.9 1976.65  4311.9 1973.04  4371.9 1973.81
  4421.9 1971.05  4471.9 1972.19  4551.9 1968.80  4621.9 1969.44  4671.9 1966.98
  4761.9 1968.09  4801.9 1964.89  4891.9 1963.97  4941.9 1965.52  5009.8 1963.08
  5010.1 1962.58  5014.1 1963.08  5111.9 1965.41  5150.5 1963.98  5301.0 1964.86
  5357.4 1967.53  5407.6 1966.14  5587.5 1966.50  5658.5 1969.00  5809.1 1967.61
  5909.4 1968.62  5959.6 1970.80  6037.5 1968.85  6116.3 1971.71  6154.4 1970.99
#Mann=3,-1,0
  4131.5   0.045       0  5009.8   0.045       0  5014.1   0.045       0
Bank Sta=5009.8,5014.1
Exp/Cntr=0.3,0.1

Type RM Length L Ch R = 1,6117,221,221,221
BEGIN DESCRIPTION:
Alkali Creek Trib 02-02 5.5
END DESCRIPTION:
XS GIS Cut Line= 4
      1374778.35      6956596.69      1375523.02      6956599.81
      1375817.03      6956599.90      1376580.49      6955869.30
#Sta/Elev= 30
  4172.5 1980.43  4229.1 1978.70  4269.1 1979.46  4309.1 1975.83  4359.1 1976.61
  4409.1 1973.08  4449.1 1974.07  4489.1 1971.08  4529.1 1972.14  4569.1 1969.03
  4639.2 1969.44  4719.2 1966.19  4749.2 1967.66  4809.2 1963.77  4869.2 1964.87
  5047.0 1961.50  5047.3 1961.00  5051.3 1961.50  5218.2 1964.13  5253.5 1962.86
  5388.1 1963.60  5430.2 1965.50  5529.3 1964.11  5720.5 1965.19  5762.6 1967.09
  5996.3 1966.48  6059.8 1968.74  6109.2 1967.37  6222.4 1968.26  6267.9 1970.39
#Mann=3,-1,0
  4172.5   0.045       0  5047.0   0.045       0  5051.3   0.045       0
Bank Sta=5047,5051.3
Exp/Cntr=0.3,0.1

Type RM Length L Ch R = 1,5896,504,504,504
BEGIN DESCRIPTION:
Alkali Creek Trib 02-02 5.0
END DESCRIPTION:
XS GIS Cut Line= 4
      1374881.52      6956755.13      1375615.97      6956823.29
      1375966.77      6956741.29      1376690.82      6955845.99
#Sta/Elev= 30
  4199.0 1981.72  4242.7 1978.71  4286.0 1979.42  4333.1 1975.41  4373.2 1976.47
  4423.4 1973.27  4544.0 1971.75  4574.1 1969.09  4624.3 1969.17  4664.5 1966.39
  4718.4 1967.77  4754.9 1964.67  4935.0 1964.32  4987.0 1961.15  5056.7 1960.43
  5056.9 1959.93  5061.0 1960.43  5199.5 1960.91  5254.0 1962.77  5333.5 1961.25
  5461.4 1961.94  5532.6 1964.22  5725.2 1963.16  5810.0 1965.65  5966.7 1964.53
  6045.0 1967.00  6179.4 1965.64  6236.9 1968.60  6315.2 1967.42  6448.3 1970.03
#Mann=3,-1,0
  4199.0   0.045       0  5056.7   0.045       0  5061.0   0.045       0
Bank Sta=5056.7,5061
Exp/Cntr=0.3,0.1

Type RM Length L Ch R = 1,5392,276,276,276
BEGIN DESCRIPTION:
Alkali Creek Trib 02-02 4.0
END DESCRIPTION:
XS GIS Cut Line= 4
      1374971.79      6956817.62      1376037.60      6957118.17
      1376192.62      6957052.30      1376698.09      6955977.43
#Sta/Elev= 30
  3834.2 1978.97  3868.7 1979.16  3926.8 1975.20  3972.6 1976.52  4024.6 1972.81
  4066.1 1973.89  4253.1 1966.15  4298.0 1968.18  4346.6 1964.52  4517.7 1964.47
  4551.7 1962.09  4624.9 1961.07  4803.8 1961.52  4876.5 1958.80  4949.5 1960.09
  5023.5 1958.71  5023.8 1958.21  5027.8 1958.71  5302.6 1959.60  5368.9 1961.93
  5431.3 1960.23  5612.0 1962.96  5733.2 1961.85  5784.3 1964.01  5926.6 1963.16
  5987.8 1965.49  6131.4 1964.85  6175.6 1967.38  6241.9 1965.47  6297.8 1968.10
#Mann=3,-1,0
  3834.2   0.045       0  5023.5   0.045       0  5027.8   0.045       0
Bank Sta=5023.5,5027.8
Exp/Cntr=0.3,0.1

Type RM Length L Ch R = 1,5116,477,477,477
BEGIN DESCRIPTION:
Alkali Creek Trib 02-02 3.0
END DESCRIPTION:
XS GIS Cut Line= 5
      1375080.02      6957463.00      1376196.80      6957433.56
      1376328.55      6957235.80      1376481.09      6956949.62
      1377150.49      6955703.99
#Sta/Elev= 30
  3645.2 1971.27  3750.2 1971.99  3890.3 1968.59  3930.3 1969.63  3990.3 1966.45
  4060.3 1967.74  4120.3 1964.66  4270.4 1964.15  4390.4 1960.79  4510.5 1961.52
  4610.5 1958.55  4892.6 1957.92  4892.9 1957.42  4897.0 1957.92  5195.1 1958.27
  5255.3 1960.27  5348.8 1958.71  5610.0 1959.63  5654.8 1961.72  5726.3 1960.08
  5852.1 1963.06  5890.2 1961.52  6021.7 1963.88  6177.6 1963.03  6229.5 1965.73
  6302.5 1964.01  6427.3 1967.07  6508.7 1965.34  6688.4 1966.45  6738.4 1968.48
#Mann=3,-1,0
  3645.2   0.045       0  4892.6   0.045       0  4897.0   0.045       0
Bank Sta=4892.6,4897
Exp/Cntr=0.3,0.1

Type RM Length L Ch R = 1,4639,350,350,350
BEGIN DESCRIPTION:
Alkali Creek Trib 02-02 2.0
END DESCRIPTION:
XS GIS Cut Line= 3
      1374562.63      6959552.32      1375830.00      6958813.00
      1377797.03      6955927.29
#Sta/Elev= 30
  1918.4 1962.36  2113.8 1960.19  2164.3 1961.56  2231.3 1959.50  2333.0 1959.73
  2361.1 1961.70  2413.2 1960.08  2632.3 1961.61  2675.3 1959.37  2824.2 1959.68
  2888.7 1957.71  2939.9 1959.15  2974.7 1957.21  3092.1 1958.36  3536.9 1956.00
  3550.0 1953.52  3550.5 1953.02  3568.3 1953.52  3586.2 1957.31  3687.0 1955.55
  3839.5 1955.03  3888.4 1956.75  3918.2 1954.61  4176.2 1954.44  4953.5 1957.23
  5659.5 1956.39  6371.6 1959.92  6416.4 1961.68  6610.9 1961.22  6878.0 1965.86
#Mann=5,-1,0
  1918.4   0.045       0  3550.0   0.045       0  3568.3   0.045       0
  3687.0   0.035       0  4176.2   0.045       0
Bank Sta=3550,3568.3
Exp/Cntr=0.3,0.1

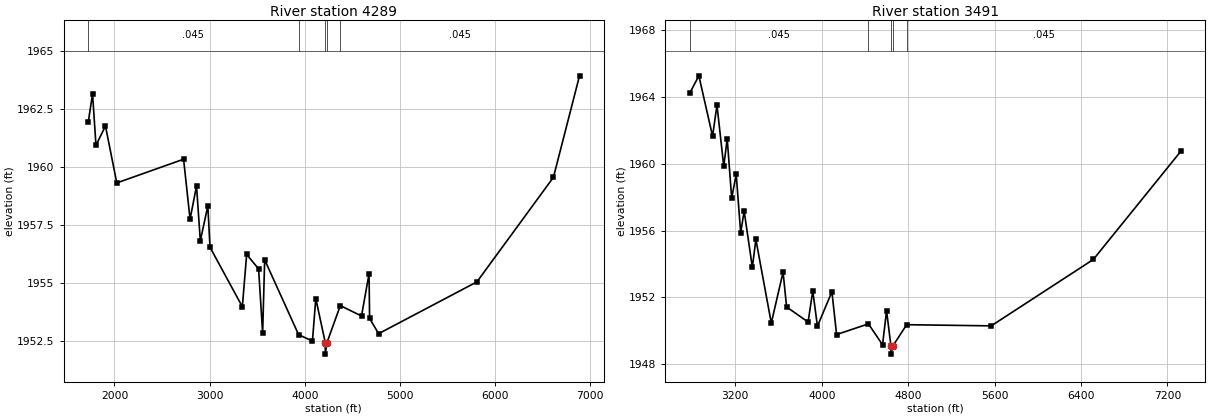
Type RM Length L Ch R = 1,4289,798,798,798
BEGIN DESCRIPTION:
Alkali Creek Trib 02-02 1.0
END DESCRIPTION:
XS GIS Cut Line= 3
      1374661.57      6959713.79      1376230.00      6958963.00
      1378036.37      6956052.68
#Sta/Elev= 30
  1724.5 1961.93  1769.9 1963.15  1805.9 1960.94  1905.7 1961.77  2024.8 1959.32
  2726.9 1960.34  2794.9 1957.76  2862.9 1959.19  2902.7 1956.83  2981.8 1958.33
  3004.5 1956.55  3344.5 1953.99  3389.8 1956.24  3515.3 1955.62  3557.8 1952.85
  3579.1 1956.01  3935.6 1952.79  4081.3 1952.51  4116.6 1954.34  4216.0 1952.45
  4216.5 1951.95  4234.3 1952.45  4374.4 1954.04  4597.2 1953.59  4676.3 1955.41
  4682.2 1953.49  4776.7 1952.83  5810.1 1955.06  6614.4 1959.56  6888.7 1963.93
#Mann=5,-1,0
  1724.5   0.045       0  3935.6   0.035       0  4216.0   0.045       0
  4234.3   0.035       0  4374.4   0.045       0
Bank Sta=4216,4234.3
Exp/Cntr=0.3,0.1

Type RM Length L Ch R = 1,3491,0,0,0
BEGIN DESCRIPTION:
Alkali Creek Trib 02-02 0.5
END DESCRIPTION:
XS GIS Cut Line= 3
      1376797.89      6960070.11      1377055.25      6959243.89
      1378876.03      6956044.03
#Sta/Elev= 30
  2777.0 1964.20  2863.0 1965.25  2989.9 1961.64  3030.6 1963.50  3093.4 1959.84
  3125.2 1961.50  3166.7 1957.94  3208.6 1959.36  3250.1 1955.85  3282.0 1957.17
  3358.1 1953.80  3390.6 1955.47  3533.3 1950.47  3642.4 1953.51  3675.1 1951.43
  3874.0 1950.53  3917.2 1952.39  3960.4 1950.28  4094.5 1952.34  4137.7 1949.78
  4432.3 1950.42  4562.9 1949.17  4600.3 1951.20  4640.5 1949.11  4641.0 1948.61
  4659.7 1949.11  4786.1 1950.37  5568.9 1950.30  6514.0 1954.27  7324.0 1960.74
#Mann=5,-1,0
  2777.0   0.045       0  4432.3   0.035       0  4640.5   0.045       0
  4659.7   0.035       0  4786.1   0.045       0
Bank Sta=4640.5,4659.7
Exp/Cntr=0.3,0.1

Chan Stop Cuts=-1