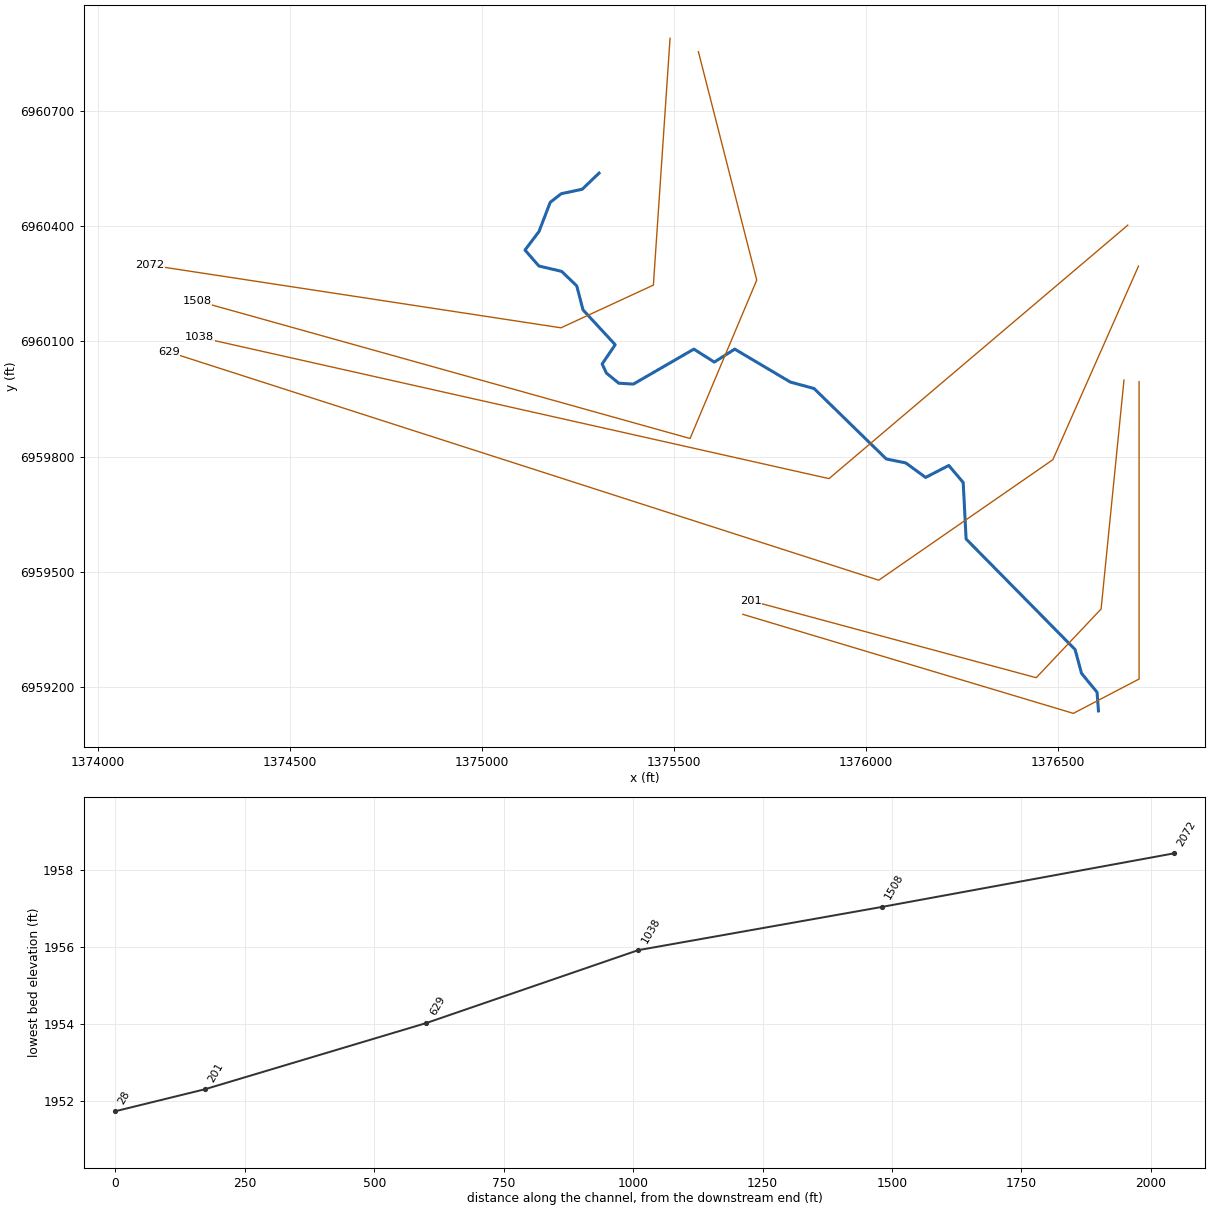
--- Alkali Creek Trib 02-03.prj (project) ---

Proj Title=Alkali Creek Trib 02-03 Base Level Engineering
Current Plan=p01
Default Exp/Contr=0.3,0.1
English Units
Geom File=g01
Flow File=f01
Plan File=p01
BEGIN DESCRIPTION:
Alkali Creek Trib 02-03
END DESCRIPTION:

--- Alkali Creek Trib 02-03.p01 (plan) ---

Plan Title=Multiple Run
Short Identifier=Multiple
Geom File=g01
Flow File=f01
Subcritical Flow
K Sum by GR= 0
Std Step Tol= 0.01
Critical Tol= 0.01
Num of Std Step Trials= 20
Max Error Tol= 0.3
Flow Tol Ratio= 0.001
Split Flow NTrial= 30
Split Flow Tol= 0.02
Split Flow Ratio= 0.02
Log Output Level= 0
Friction Slope Method= 1
Unsteady Friction Slope Method= 2
Unsteady Bridges Friction Slope Method= 1
Parabolic Critical Depth
Global Vel Dist=  1 , 1 , 1
Global Log Level= 0
CheckData=True
Encroach Param= -1, 0, 0, 0
BEGIN DESCRIPTION:
Multiple Run
END DESCRIPTION:

--- Alkali Creek Trib 02-03.f01 (steady flow) ---

Flow Title=Multiple
Number of Profiles=7
Profile Names=10-year,25-year,50-year,1pct_min,100-year,1pct_plu,500-year
River Rch & RM= Alkali Creek Tri,Reach-1,2072
     203     280     343     209     416     831     623
Boundary for River Rch & Prof#=Alkali Creek Tri,Reach-1,1
Up Type=0
Dn Type=3
Dn Slope=0.005
Boundary for River Rch & Prof#=Alkali Creek Tri,Reach-1,2
Up Type=0
Dn Type=3
Dn Slope=0.005
Boundary for River Rch & Prof#=Alkali Creek Tri,Reach-1,3
Up Type=0
Dn Type=3
Dn Slope=0.005
Boundary for River Rch & Prof#=Alkali Creek Tri,Reach-1,4
Up Type=0
Dn Type=3
Dn Slope=0.005
Boundary for River Rch & Prof#=Alkali Creek Tri,Reach-1,5
Up Type=0
Dn Type=3
Dn Slope=0.005
Boundary for River Rch & Prof#=Alkali Creek Tri,Reach-1,6
Up Type=0
Dn Type=3
Dn Slope=0.005
Boundary for River Rch & Prof#=Alkali Creek Tri,Reach-1,7
Up Type=0
Dn Type=3
Dn Slope=0.005

--- Alkali Creek Trib 02-03.g01 (geometry) ---

Geom Title=Existing Conditions

River Reach=Alkali Creek Tri,Reach-1
Reach XY= 30
      1375305.00      6960538.00      1375261.11      6960495.95
      1375206.34      6960484.29      1375177.82      6960461.86
      1375148.56      6960385.72      1375112.20      6960337.70
      1375148.33      6960296.16      1375207.49      6960282.25
      1375246.96      6960244.33      1375263.20      6960181.97
      1375346.98      6960091.32      1375313.08      6960041.10
      1375324.21      6960017.40      1375356.17      6959991.12
      1375394.20      6959988.70      1375551.77      6960079.77
      1375605.00      6960046.03      1375658.23      6960079.77
      1375802.81      6959994.11      1375864.68      6959977.24
      1376052.71      6959793.81      1376103.35      6959783.56
      1376155.10      6959745.78      1376215.38      6959776.92
      1376252.93      6959732.54      1376260.47      6959585.55
      1376544.25      6959297.69      1376560.97      6959235.76
      1376601.40      6959186.51      1376605.00      6959138.00

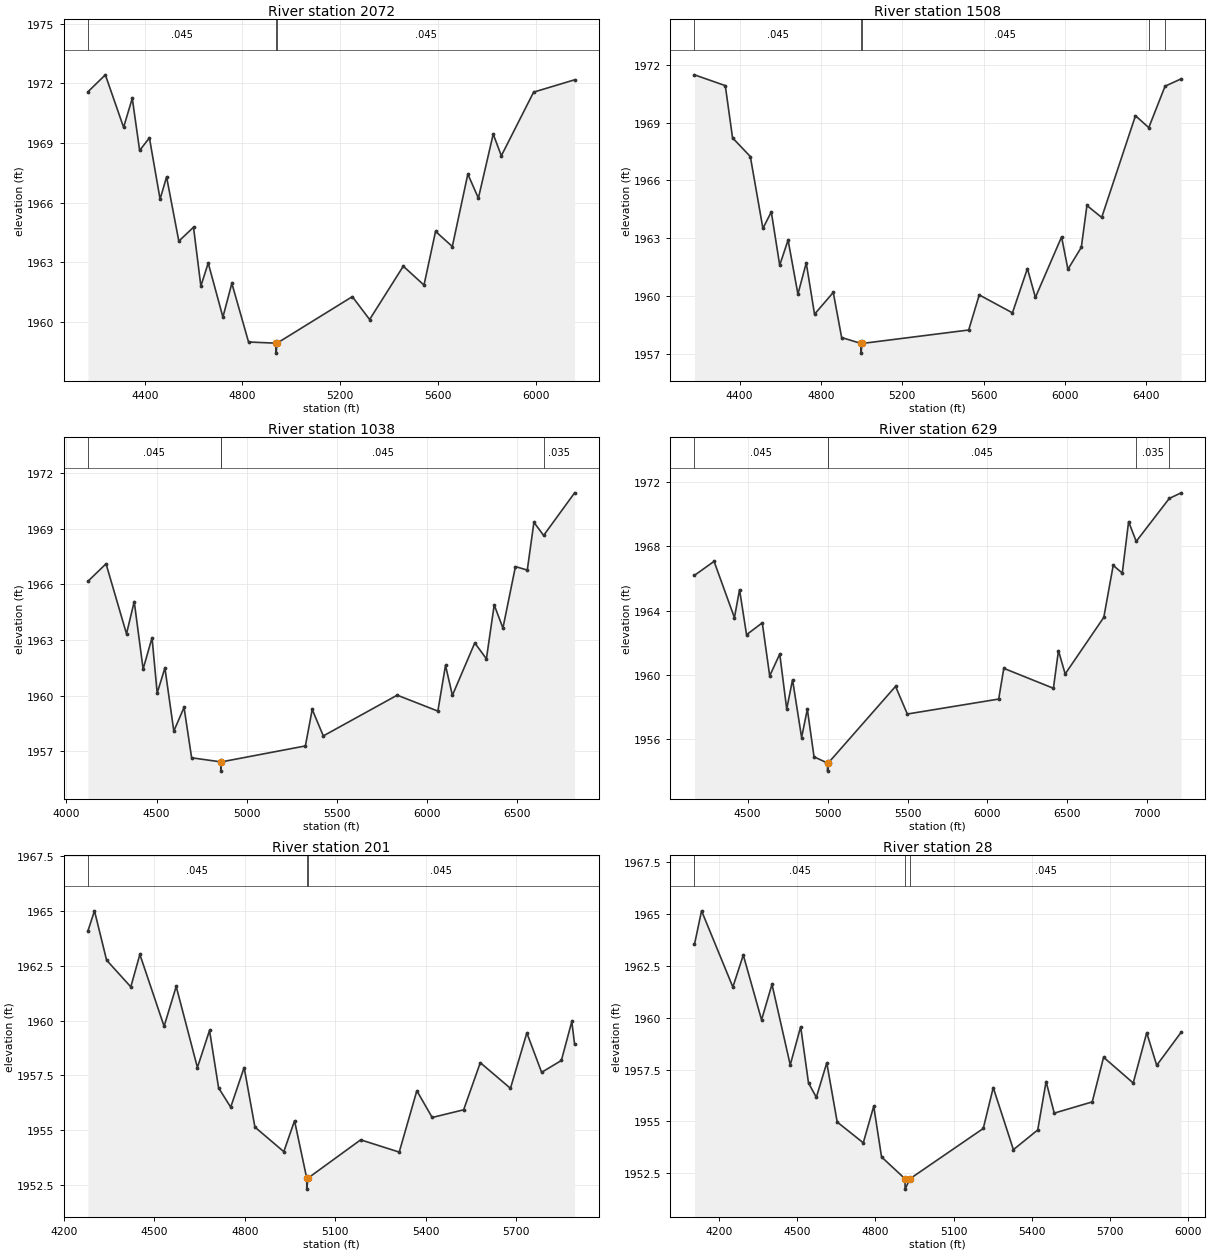
Type RM Length L Ch R = 1,2072,564,564,564
BEGIN DESCRIPTION:
Alkali Creek Trib 02-03 4.0
END DESCRIPTION:
XS GIS Cut Line= 4
      1375489.79      6960888.83      1375446.39      6960246.45
      1375205.94      6960135.29      1374135.66      6960298.53
#Sta/Elev= 30
  4167.8 1971.57  4238.8 1972.42  4313.5 1969.78  4349.0 1971.24  4379.1 1968.62
  4419.2 1969.25  4462.8 1966.17  4489.4 1967.29  4539.5 1964.06  4599.6 1964.76
  4629.7 1961.80  4659.8 1962.96  4719.9 1960.24  4756.5 1961.94  4824.8 1958.99
  4937.4 1958.93  4937.7 1958.43  4941.4 1958.93  5249.5 1961.27  5320.3 1960.12
  5458.1 1962.80  5542.8 1961.85  5590.1 1964.55  5658.7 1963.79  5722.2 1967.43
  5765.4 1966.22  5826.1 1969.44  5859.3 1968.35  5991.4 1971.55  6159.2 1972.17
#Mann=3,-1,0
  4167.8   0.045       0  4937.4   0.045       0  4941.4   0.045       0
Bank Sta=4937.4,4941.4
Exp/Cntr=0.3,0.1

Type RM Length L Ch R = 1,1508,470,470,470
BEGIN DESCRIPTION:
Alkali Creek Trib 02-03 3.0
END DESCRIPTION:
XS GIS Cut Line= 4
      1375563.57      6960854.11      1375715.48      6960259.47
      1375541.87      6959847.14      1374258.98      6960205.38
#Sta/Elev= 30
  4178.0 1971.48  4329.6 1970.92  4365.3 1968.21  4452.7 1967.24  4514.6 1963.51
  4555.9 1964.37  4597.2 1961.60  4638.4 1962.91  4686.8 1960.10  4727.7 1961.72
  4768.5 1959.06  4860.6 1960.19  4901.8 1957.85  4997.5 1957.54  4997.7 1957.04
  5001.5 1957.54  5526.6 1958.24  5578.5 1960.06  5741.8 1959.13  5815.4 1961.43
  5854.7 1959.93  5983.4 1963.07  6014.6 1961.39  6080.5 1962.53  6108.0 1964.70
  6180.7 1964.08  6346.8 1969.36  6412.2 1968.74  6492.3 1970.89  6571.1 1971.27
#Mann=5,-1,0
  4178.0   0.045       0  4997.5   0.045       0  5001.5   0.045       0
  6412.2   0.035       0  6492.3   0.045       0
Bank Sta=4997.5,5001.5
Exp/Cntr=0.3,0.1

Type RM Length L Ch R = 1,1038,409,409,409
BEGIN DESCRIPTION:
Alkali Creek Trib 02-03 2.0
END DESCRIPTION:
XS GIS Cut Line= 3
      1376681.36      6960402.42      1375903.56      6959742.69
      1374264.69      6960110.74
#Sta/Elev= 30
  4119.4 1966.17  4219.5 1967.11  4333.0 1963.33  4375.8 1965.07  4425.2 1961.43
  4474.7 1963.12  4503.2 1960.13  4546.1 1961.49  4595.5 1958.08  4652.2 1959.36
  4694.3 1956.64  4856.0 1956.42  4856.3 1955.92  4860.0 1956.42  5325.4 1957.28
  5363.3 1959.25  5424.8 1957.82  5834.8 1960.02  6060.3 1959.16  6102.7 1961.63
  6140.9 1960.01  6265.2 1962.84  6329.6 1961.98  6372.9 1964.89  6421.3 1963.64
  6490.7 1966.96  6556.4 1966.77  6593.2 1969.35  6647.1 1968.64  6819.0 1970.94
#Mann=4,-1,0
  4119.4   0.045       0  4856.0   0.045       0  4860.0   0.045       0
  6647.1   0.035       0
Bank Sta=4856,4860
Exp/Cntr=0.3,0.1

Type RM Length L Ch R = 1,629,428,428,428
BEGIN DESCRIPTION:
Alkali Creek Trib 02-03 1.0
END DESCRIPTION:
XS GIS Cut Line= 4
      1376709.26      6960295.92      1376486.30      6959791.90
      1376033.07      6959478.25      1374184.78      6960072.56
#Sta/Elev= 30
  4167.1 1966.20  4289.7 1967.07  4417.1 1963.57  4449.1 1965.31  4492.9 1962.51
  4591.3 1963.25  4637.7 1959.95  4700.6 1961.31  4744.1 1957.89  4780.6 1959.71
  4837.3 1956.12  4873.1 1957.88  4915.0 1954.92  4999.5 1954.53  4999.8 1954.03
  5003.5 1954.53  5424.9 1959.30  5498.5 1957.58  6070.0 1958.51  6102.0 1960.42
  6412.3 1959.18  6443.9 1961.52  6485.9 1960.07  6727.5 1963.59  6786.4 1966.82
  6843.0 1966.34  6882.7 1969.54  6930.2 1968.31  7136.9 1970.98  7210.9 1971.33
#Mann=5,-1,0
  4167.1   0.045       0  4999.5   0.045       0  5003.5   0.045       0
  6930.2   0.035       0  7136.9   0.045       0
Bank Sta=4999.5,5003.5
Exp/Cntr=0.3,0.1

Type RM Length L Ch R = 1,201,173,173,173
BEGIN DESCRIPTION:
Alkali Creek Trib 02-03 0.5
END DESCRIPTION:
XS GIS Cut Line= 4
      1376671.50      6959999.37      1376611.89      6959403.26
      1376443.00      6959224.44      1375699.31      6959424.94
#Sta/Elev= 30
  4279.5 1964.10  4301.0 1965.01  4341.2 1962.76  4421.6 1961.54  4451.7 1963.02
  4532.1 1959.74  4572.3 1961.56  4642.7 1957.86  4682.9 1959.55  4713.0 1956.93
  4753.2 1956.05  4797.8 1957.86  4833.6 1955.14  4929.5 1954.02  4965.1 1955.43
  5005.6 1952.81  5005.8 1952.31  5009.6 1952.81  5184.6 1954.56  5312.6 1954.00
  5371.1 1956.80  5422.0 1955.58  5526.4 1955.93  5581.7 1958.08  5681.8 1956.91
  5736.2 1959.44  5785.3 1957.64  5850.8 1958.18  5885.5 1959.96  5894.8 1958.91
#Mann=3,-1,0
  4279.5   0.045       0  5005.6   0.045       0  5009.6   0.045       0
Bank Sta=5005.6,5009.6
Exp/Cntr=0.3,0.1

Type RM Length L Ch R = 1,28,0,0,0
BEGIN DESCRIPTION:
Alkali Creek Trib 02-03 0.4
END DESCRIPTION:
XS GIS Cut Line= 4
      1376710.80      6959995.19      1376710.80      6959221.00
      1376539.60      6959131.57      1375679.25      6959389.42
#Sta/Elev= 30
  4106.6 1963.52  4133.8 1965.14  4253.8 1961.47  4293.8 1963.01  4363.8 1959.89
  4403.8 1961.60  4473.8 1957.72  4513.8 1959.56  4543.8 1956.85  4573.8 1956.16
  4613.8 1957.82  4653.8 1954.97  4753.8 1953.97  4793.8 1955.73  4823.8 1953.29
  4913.6 1952.24  4914.1 1951.74  4932.8 1952.24  5213.7 1954.66  5252.0 1956.63
  5329.3 1953.64  5422.6 1954.59  5454.6 1956.92  5485.9 1955.40  5631.5 1955.94
  5675.0 1958.09  5788.6 1956.85  5840.4 1959.27  5878.7 1957.70  5972.1 1959.29
#Mann=3,-1,0
  4106.6   0.045       0  4913.6   0.045       0  4932.8   0.045       0
Bank Sta=4913.6,4932.8
Exp/Cntr=0.3,0.1

Chan Stop Cuts=-1