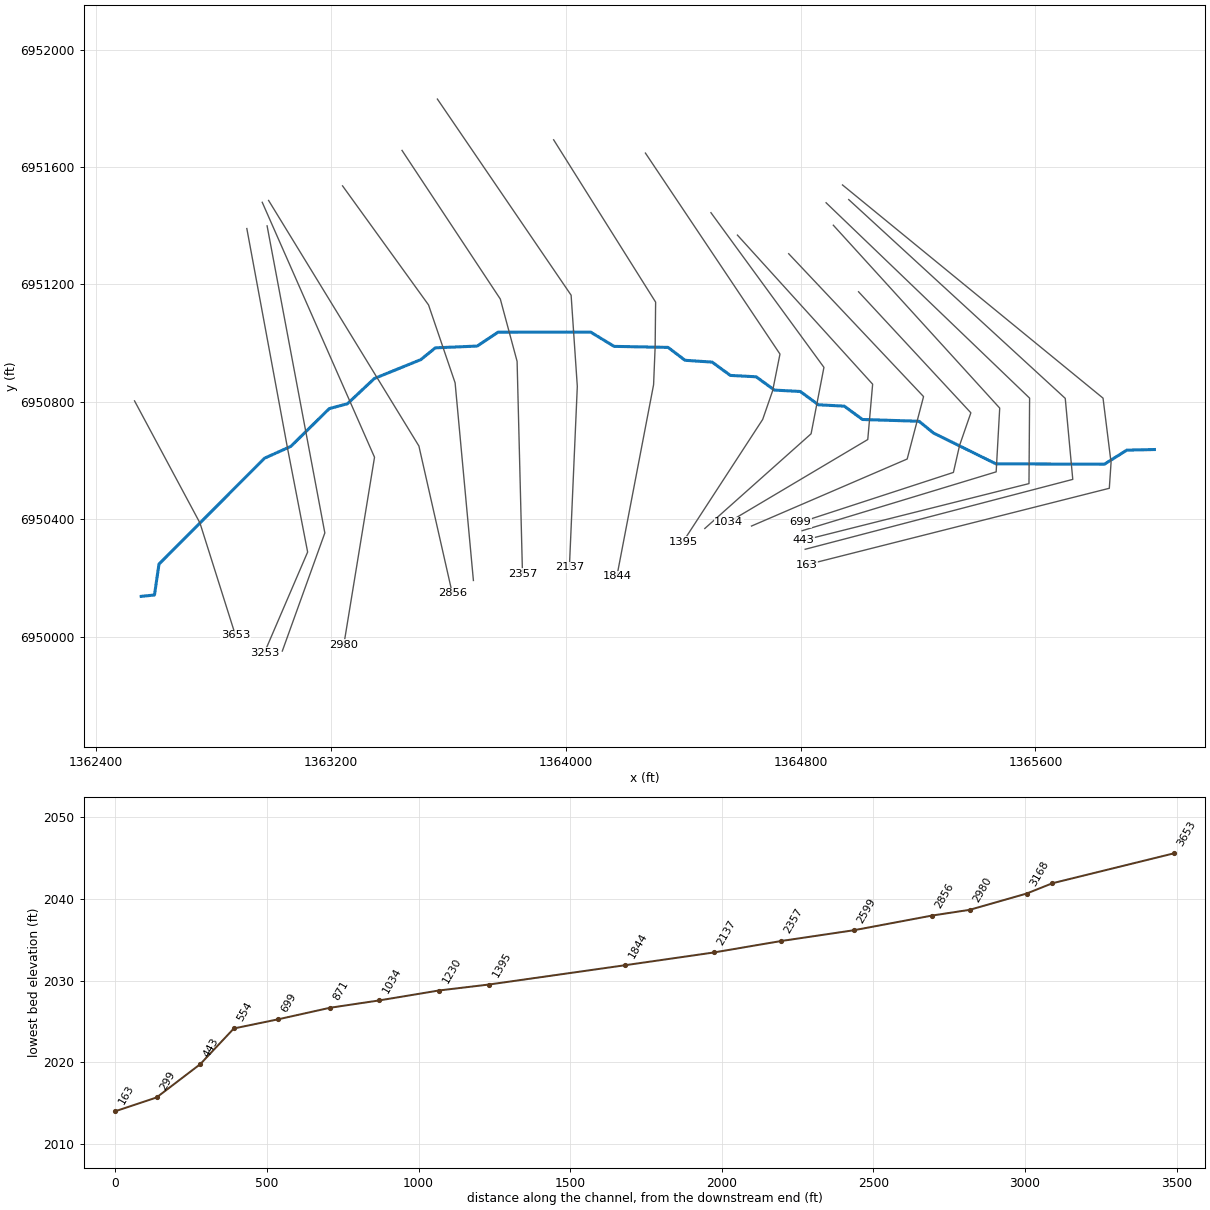
--- Alkali Creek Trib 02-05.prj (project) ---

Proj Title=Alkali Creek Trib 02-05 Base Level Engineering
Current Plan=p01
Default Exp/Contr=0.3,0.1
English Units
Geom File=g01
Flow File=f01
Plan File=p01
BEGIN DESCRIPTION:
Alkali Creek Trib 02-05
END DESCRIPTION:

--- Alkali Creek Trib 02-05.p01 (plan) ---

Plan Title=Multiple Run
Short Identifier=Multiple
Geom File=g01
Flow File=f01
Subcritical Flow
K Sum by GR= 0
Std Step Tol= 0.01
Critical Tol= 0.01
Num of Std Step Trials= 20
Max Error Tol= 0.3
Flow Tol Ratio= 0.001
Split Flow NTrial= 30
Split Flow Tol= 0.02
Split Flow Ratio= 0.02
Log Output Level= 0
Friction Slope Method= 1
Unsteady Friction Slope Method= 2
Unsteady Bridges Friction Slope Method= 1
Parabolic Critical Depth
Global Vel Dist=  1 , 1 , 1
Global Log Level= 0
CheckData=True
Encroach Param= -1, 0, 0, 0
BEGIN DESCRIPTION:
Multiple Run
END DESCRIPTION:

--- Alkali Creek Trib 02-05.f01 (steady flow) ---

Flow Title=Multiple
Number of Profiles=7
Profile Names=10-year,25-year,50-year,1pct_min,100-year,1pct_plu,500-year
River Rch & RM= Alkali Creek Tri,Reach-1,3653
     322     457     572     355     709    1414    1103
Boundary for River Rch & Prof#=Alkali Creek Tri,Reach-1,1
Up Type=0
Dn Type=3
Dn Slope=0.005
Boundary for River Rch & Prof#=Alkali Creek Tri,Reach-1,2
Up Type=0
Dn Type=3
Dn Slope=0.005
Boundary for River Rch & Prof#=Alkali Creek Tri,Reach-1,3
Up Type=0
Dn Type=3
Dn Slope=0.005
Boundary for River Rch & Prof#=Alkali Creek Tri,Reach-1,4
Up Type=0
Dn Type=3
Dn Slope=0.005
Boundary for River Rch & Prof#=Alkali Creek Tri,Reach-1,5
Up Type=0
Dn Type=3
Dn Slope=0.005
Boundary for River Rch & Prof#=Alkali Creek Tri,Reach-1,6
Up Type=0
Dn Type=3
Dn Slope=0.005
Boundary for River Rch & Prof#=Alkali Creek Tri,Reach-1,7
Up Type=0
Dn Type=3
Dn Slope=0.005

--- Alkali Creek Trib 02-05.g01 (geometry) ---

Geom Title=Existing Conditions

River Reach=Alkali Creek Tri,Reach-1
Reach XY= 30
      1362555.00      6950138.00      1362600.25      6950142.68
      1362615.50      6950247.77      1362974.84      6950608.38
      1363064.68      6950648.78      1363195.32      6950777.22
      1363257.28      6950793.87      1363348.95      6950879.84
      1363507.18      6950944.12      1363556.56      6950984.24
      1363699.06      6950990.27      1363770.22      6951037.48
      1364084.97      6951037.93      1364165.51      6950989.22
      1364349.06      6950985.74      1364406.60      6950941.86
      1364499.03      6950935.65      1364560.97      6950890.35
      1364649.03      6950885.65      1364710.97      6950840.35
      1364799.03      6950835.65      1364860.97      6950790.35
      1364949.02      6950785.64      1365010.94      6950740.26
      1365203.45      6950734.25      1365252.82      6950694.12
      1365465.50      6950589.20      1365834.97      6950588.06
      1365910.87      6950635.90      1366005.00      6950638.00

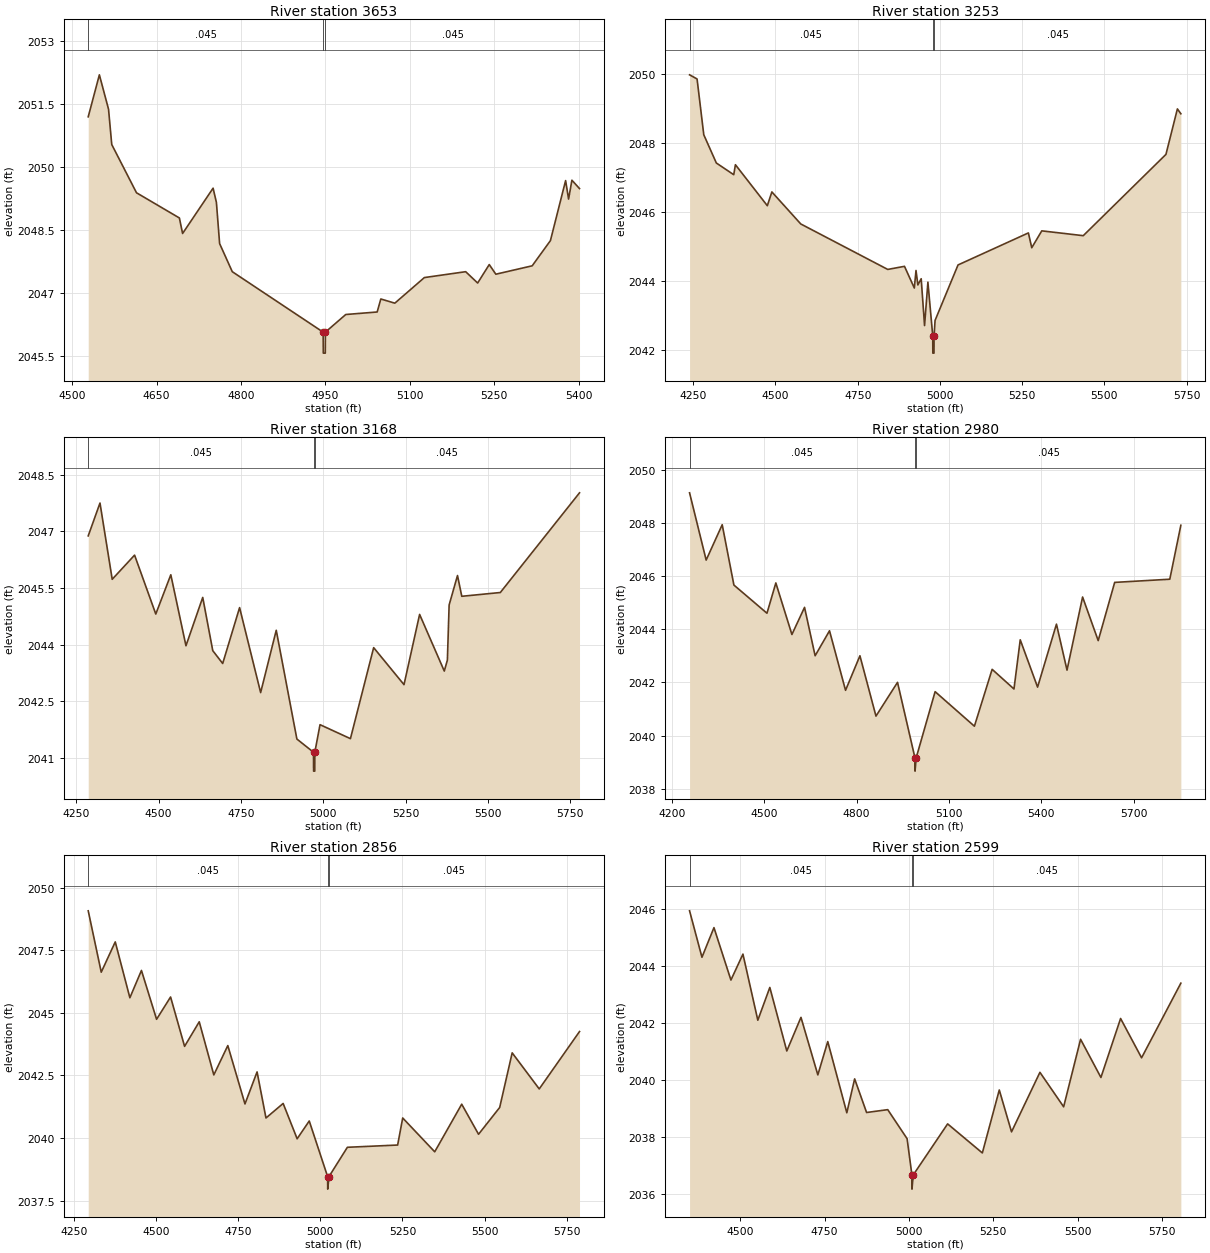
Type RM Length L Ch R = 1,3653,400,400,400
BEGIN DESCRIPTION:
Alkali Creek Trib 02-05 3.0
END DESCRIPTION:
XS GIS Cut Line= 3
      1362532.33      6950803.61      1362755.00      6950388.00
      1362876.04      6950005.08
#Sta/Elev= 30
  4528.5 2051.19  4548.3 2052.19  4564.6 2051.37  4570.3 2050.53  4614.3 2049.38
  4690.5 2048.78  4696.2 2048.41  4750.4 2049.49  4756.3 2049.15  4762.0 2048.17
  4784.5 2047.50  4946.0 2046.06  4946.3 2045.56  4949.8 2045.56  4950.0 2046.06
  4986.2 2046.48  5042.0 2046.54  5048.5 2046.85  5073.4 2046.75  5125.9 2047.36
  5199.3 2047.50  5220.6 2047.23  5241.2 2047.67  5252.9 2047.44  5317.5 2047.64
  5349.9 2048.24  5376.9 2049.67  5382.2 2049.23  5388.1 2049.68  5401.6 2049.48
#Mann=3,-1,0
  4528.5   0.045       0  4946.0   0.045       0  4950.0   0.045       0
Bank Sta=4946,4950
Exp/Cntr=0.3,0.1

Type RM Length L Ch R = 1,3253,85,85,85
BEGIN DESCRIPTION:
Alkali Creek Trib 02-05 3.1
END DESCRIPTION:
XS GIS Cut Line= 4
      1362914.69      6951390.44      1363053.35      6950641.98
      1363121.72      6950288.89      1362974.56      6949946.41
#Sta/Elev= 30
  4238.8 2049.99  4261.6 2049.87  4282.0 2048.25  4320.2 2047.43  4373.1 2047.09
  4378.2 2047.38  4475.2 2046.19  4489.0 2046.59  4576.9 2045.66  4841.3 2044.34
  4892.2 2044.43  4922.1 2043.80  4927.2 2044.31  4932.9 2043.89  4943.0 2044.07
  4953.2 2042.71  4963.4 2043.97  4978.1 2042.41  4978.4 2041.91  4981.9 2041.91
  4982.1 2042.41  4985.2 2042.86  5055.0 2044.47  5268.9 2045.40  5279.1 2044.97
  5309.6 2045.46  5435.7 2045.32  5687.1 2047.68  5721.9 2049.00  5732.4 2048.86
#Mann=3,-1,0
  4238.8   0.045       0  4978.1   0.045       0  4982.1   0.045       0
Bank Sta=4978.1,4982.1
Exp/Cntr=0.3,0.1

Type RM Length L Ch R = 1,3168,188,188,188
BEGIN DESCRIPTION:
Alkali Creek Trib 02-05 3.2
END DESCRIPTION:
XS GIS Cut Line= 3
      1362983.70      6951399.57      1363180.31      6950354.00
      1363035.50      6949951.77
#Sta/Elev= 30
  4286.5 2046.88  4322.2 2047.75  4359.3 2045.73  4427.2 2046.37  4491.6 2044.81
  4537.2 2045.85  4583.2 2043.97  4634.1 2045.25  4664.6 2043.84  4694.7 2043.50
  4746.0 2044.98  4809.9 2042.73  4857.3 2044.38  4919.9 2041.50  4970.4 2041.15
  4970.7 2040.65  4974.2 2040.65  4974.4 2041.15  4990.2 2041.88  5082.5 2041.51
  5153.0 2043.92  5245.1 2042.94  5292.5 2044.80  5367.4 2043.30  5376.8 2043.59
  5382.1 2045.05  5407.5 2045.83  5420.5 2045.28  5537.5 2045.38  5777.9 2048.02
#Mann=3,-1,0
  4286.5   0.045       0  4970.4   0.045       0  4974.4   0.045       0
Bank Sta=4970.4,4974.4
Exp/Cntr=0.3,0.1

Type RM Length L Ch R = 1,2980,124,124,124
BEGIN DESCRIPTION:
Alkali Creek Trib 02-05 4.15
END DESCRIPTION:
XS GIS Cut Line= 3
      1362967.17      6951479.76      1363349.48      6950611.72
      1363244.94      6949973.11
#Sta/Elev= 30
  4257.5 2049.13  4311.4 2046.60  4363.5 2047.93  4401.5 2045.66  4508.9 2044.60
  4537.7 2045.74  4589.9 2043.80  4630.9 2044.82  4665.3 2043.00  4712.0 2043.94
  4764.1 2041.70  4810.8 2043.00  4862.9 2040.73  4932.9 2042.00  4989.5 2039.16
  4989.8 2038.66  4993.5 2039.16  5055.0 2041.65  5182.6 2040.35  5240.2 2042.49
  5311.1 2041.75  5331.5 2043.60  5387.8 2041.82  5449.1 2044.19  5483.4 2042.46
  5534.0 2045.21  5584.7 2043.57  5638.2 2045.76  5817.2 2045.88  5853.1 2047.91
#Mann=3,-1,0
  4257.5   0.045       0  4989.5   0.045       0  4993.5   0.045       0
Bank Sta=4989.5,4993.5
Exp/Cntr=0.3,0.1

Type RM Length L Ch R = 1,2856,257,257,257
BEGIN DESCRIPTION:
Alkali Creek Trib 02-05 2.5
END DESCRIPTION:
XS GIS Cut Line= 3
      1362988.85      6951486.05      1363500.56      6950650.01
      1363614.21      6950148.54
#Sta/Elev= 30
  4294.4 2049.07  4334.0 2046.62  4376.6 2047.83  4421.1 2045.60  4456.3 2046.69
  4502.3 2044.74  4544.9 2045.63  4587.5 2043.66  4632.1 2044.64  4676.4 2042.52
  4719.0 2043.69  4771.2 2041.36  4808.0 2042.64  4835.1 2040.80  4887.3 2041.38
  4929.9 2039.97  4966.7 2040.68  5022.6 2038.46  5022.9 2037.96  5026.7 2038.46
  5082.7 2039.63  5235.6 2039.72  5251.0 2040.80  5348.4 2039.45  5430.5 2041.35
  5481.7 2040.15  5546.0 2041.22  5584.0 2043.40  5666.3 2041.96  5788.8 2044.25
#Mann=3,-1,0
  4294.4   0.045       0  5022.6   0.045       0  5026.7   0.045       0
Bank Sta=5022.6,5026.7
Exp/Cntr=0.3,0.1

Type RM Length L Ch R = 1,2599,242,242,242
BEGIN DESCRIPTION:
Alkali Creek Trib 02-05 3.15
END DESCRIPTION:
XS GIS Cut Line= 4
      1363240.62      6951535.72      1363533.40      6951130.34
      1363623.86      6950865.00      1363686.17      6950192.07
#Sta/Elev= 30
  4349.8 2045.94  4386.5 2044.31  4422.1 2045.35  4472.4 2043.51  4508.0 2044.42
  4552.1 2042.10  4587.7 2043.25  4638.0 2041.02  4680.0 2042.20  4730.0 2040.18
  4759.4 2041.35  4815.9 2038.85  4839.1 2040.04  4874.5 2038.86  4937.2 2038.96
  4994.6 2037.94  5008.8 2036.67  5009.0 2036.17  5012.9 2036.67  5114.7 2038.46
  5217.6 2037.44  5267.8 2039.65  5304.1 2038.18  5388.3 2040.27  5458.6 2039.06
  5508.8 2041.43  5569.1 2040.09  5627.4 2042.16  5689.6 2040.78  5806.0 2043.40
#Mann=3,-1,0
  4349.8   0.045       0  5008.8   0.045       0  5012.9   0.045       0
Bank Sta=5008.8,5012.9
Exp/Cntr=0.3,0.1

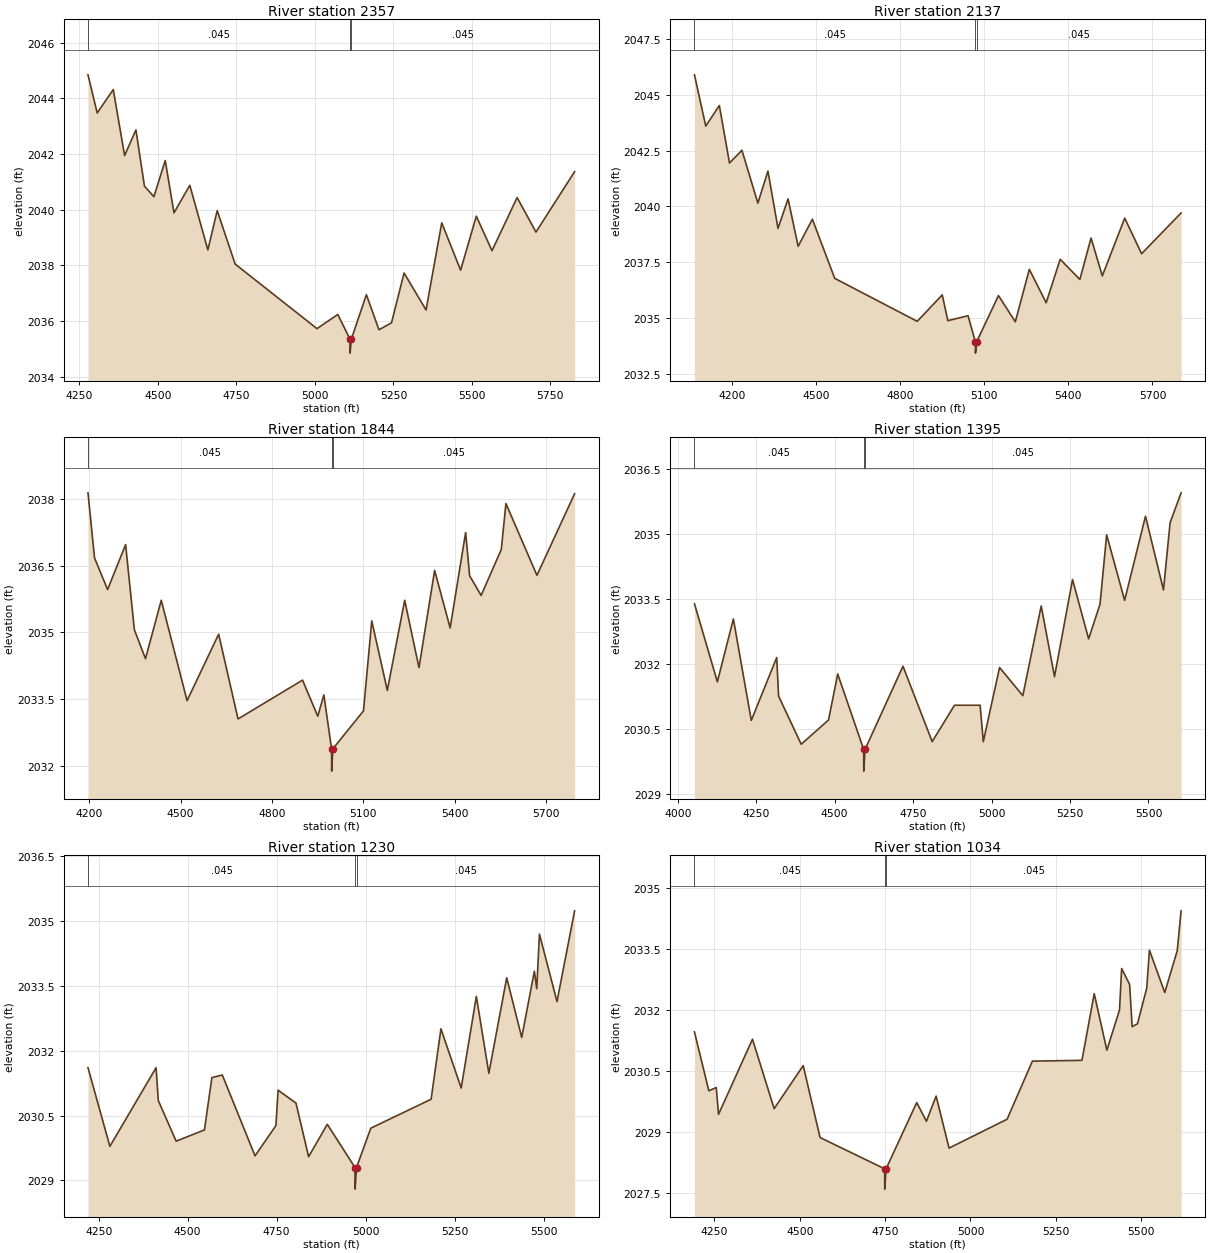
Type RM Length L Ch R = 1,2357,220,220,220
BEGIN DESCRIPTION:
Alkali Creek Trib 02-05 2.1
END DESCRIPTION:
XS GIS Cut Line= 4
      1363443.14      6951656.43      1363777.80      6951150.35
      1363834.94      6950938.13      1363853.28      6950214.97
#Sta/Elev= 30
  4277.3 2044.84  4306.6 2043.47  4357.8 2044.31  4393.9 2041.94  4430.0 2042.86
  4457.1 2040.84  4487.2 2040.46  4523.3 2041.76  4551.2 2039.88  4601.5 2040.87
  4659.1 2038.55  4688.8 2039.96  4746.0 2038.04  5006.7 2035.72  5072.9 2036.23
  5111.8 2035.34  5112.1 2034.84  5116.0 2035.34  5164.0 2036.94  5204.0 2035.68
  5244.0 2035.93  5284.0 2037.72  5354.0 2036.39  5404.0 2039.52  5464.1 2037.82
  5514.1 2039.76  5564.1 2038.52  5644.1 2040.43  5704.1 2039.19  5827.2 2041.36
#Mann=3,-1,0
  4277.3   0.045       0  5111.8   0.045       0  5116.0   0.045       0
Bank Sta=5111.8,5116
Exp/Cntr=0.3,0.1

Type RM Length L Ch R = 1,2137,293,293,293
BEGIN DESCRIPTION:
Alkali Creek Trib 02-05 2.15
END DESCRIPTION:
XS GIS Cut Line= 4
      1363563.55      6951831.27      1364018.85      6951163.51
      1364039.96      6950852.94      1364013.00      6950237.23
#Sta/Elev= 30
  4066.2 2045.88  4106.5 2043.59  4154.9 2044.51  4191.2 2041.94  4235.5 2042.51
  4292.4 2040.15  4328.3 2041.58  4364.2 2039.02  4400.1 2040.34  4436.0 2038.22
  4486.8 2039.43  4566.4 2036.79  4860.8 2034.87  4950.1 2036.05  4970.1 2034.90
  5042.1 2035.12  5068.3 2033.95  5068.6 2033.45  5072.5 2033.95  5150.6 2036.02
  5210.7 2034.85  5260.7 2037.19  5320.8 2035.70  5370.8 2037.64  5440.9 2036.74
  5480.9 2038.59  5521.0 2036.90  5601.0 2039.48  5661.1 2037.89  5802.0 2039.71
#Mann=3,-1,0
  4066.2   0.045       0  5068.3   0.045       0  5072.5   0.045       0
Bank Sta=5068.3,5072.5
Exp/Cntr=0.3,0.1

Type RM Length L Ch R = 1,1844,449,449,449
BEGIN DESCRIPTION:
Alkali Creek Trib 02-05 2.0
END DESCRIPTION:
XS GIS Cut Line= 5
      1363959.38      6951692.56      1364306.61      6951139.87
      1364305.00      6950988.00      1364299.67      6950858.62
      1364174.68      6950206.47
#Sta/Elev= 30
  4195.8 2038.13  4217.3 2036.67  4260.2 2035.96  4319.3 2036.97  4348.1 2035.06
  4384.6 2034.41  4436.4 2035.72  4521.2 2033.47  4624.9 2034.96  4688.5 2033.06
  4900.4 2033.93  4950.4 2033.12  4970.4 2033.60  4995.7 2032.39  4996.0 2031.89
  5000.0 2032.39  5100.5 2033.24  5127.7 2035.26  5178.8 2033.70  5235.9 2035.72
  5282.8 2034.21  5334.2 2036.39  5385.1 2035.10  5436.0 2037.24  5449.1 2036.27
  5486.9 2035.83  5553.1 2036.86  5568.3 2037.89  5670.2 2036.28  5793.9 2038.11
#Mann=3,-1,0
  4195.8   0.045       0  4995.7   0.045       0  5000.0   0.045       0
Bank Sta=4995.7,5000
Exp/Cntr=0.3,0.1

Type RM Length L Ch R = 1,1395,165,165,165
BEGIN DESCRIPTION:
Alkali Creek Trib 02-05 1.0
END DESCRIPTION:
XS GIS Cut Line= 5
      1364271.91      6951647.37      1364730.00      6950963.00
      1364705.00      6950838.00      1364671.20      6950740.56
      1364400.37      6950324.49
#Sta/Elev= 30
  4053.3 2033.39  4126.3 2031.59  4177.3 2033.04  4234.4 2030.70  4315.4 2032.15
  4321.4 2031.26  4393.5 2030.15  4480.5 2030.71  4509.8 2031.77  4592.5 2030.03
  4592.8 2029.53  4596.8 2030.03  4717.7 2031.95  4810.8 2030.21  4881.9 2031.05
  4963.5 2031.05  4973.7 2030.21  5025.5 2031.92  5099.6 2031.27  5158.2 2033.34
  5200.6 2031.71  5258.0 2033.95  5309.3 2032.58  5345.6 2033.38  5366.7 2034.98
  5424.0 2033.47  5490.5 2035.41  5547.8 2033.71  5568.9 2035.26  5603.9 2035.95
#Mann=3,-1,0
  4053.3   0.045       0  4592.5   0.045       0  4596.8   0.045       0
Bank Sta=4592.5,4596.8
Exp/Cntr=0.3,0.1

Type RM Length L Ch R = 1,1230,196,196,196
BEGIN DESCRIPTION:
Alkali Creek Trib 02-05 0.9
END DESCRIPTION:
XS GIS Cut Line= 4
      1364494.96      6951444.44      1364879.70      6950917.77
      1364835.98      6950691.63      1364474.08      6950369.13
#Sta/Elev= 30
  4220.1 2031.61  4281.6 2029.79  4411.4 2031.61  4417.6 2030.85  4467.8 2029.91
  4547.3 2030.17  4568.2 2031.38  4597.5 2031.44  4689.4 2029.57  4748.1 2030.27
  4754.3 2031.09  4804.5 2030.79  4840.0 2029.55  4892.5 2030.30  4970.3 2029.30
  4970.6 2028.80  4974.6 2029.30  5014.7 2030.21  5184.2 2030.88  5211.8 2032.51
  5268.7 2031.14  5311.3 2033.26  5346.4 2031.48  5396.6 2033.69  5438.8 2032.31
  5474.3 2033.84  5481.0 2033.44  5488.6 2034.70  5537.9 2033.14  5587.4 2035.24
#Mann=3,-1,0
  4220.1   0.045       0  4970.3   0.045       0  4974.6   0.045       0
Bank Sta=4970.3,4974.6
Exp/Cntr=0.3,0.1

Type RM Length L Ch R = 1,1034,163,163,163
BEGIN DESCRIPTION:
Alkali Creek Trib 02-05 0.85
END DESCRIPTION:
XS GIS Cut Line= 4
      1364585.22      6951368.07      1365045.54      6950860.48
      1365028.95      6950672.03      1364555.33      6950390.68
#Sta/Elev= 30
  4191.5 2031.46  4233.6 2030.01  4255.3 2030.09  4262.0 2029.43  4361.4 2031.28
  4424.9 2029.57  4510.0 2030.63  4559.4 2028.86  4748.5 2028.09  4748.8 2027.59
  4752.8 2028.09  4842.5 2029.72  4870.9 2029.26  4899.3 2029.88  4937.2 2028.60
  5107.2 2029.31  5181.3 2030.74  5326.4 2030.76  5362.4 2032.40  5399.4 2031.01
  5436.5 2032.00  5442.7 2033.02  5466.0 2032.63  5473.5 2031.59  5489.1 2031.66
  5516.3 2032.54  5524.1 2033.47  5569.0 2032.43  5605.6 2033.46  5616.8 2034.44
#Mann=3,-1,0
  4191.5   0.045       0  4748.5   0.045       0  4752.8   0.045       0
Bank Sta=4748.5,4752.8
Exp/Cntr=0.3,0.1

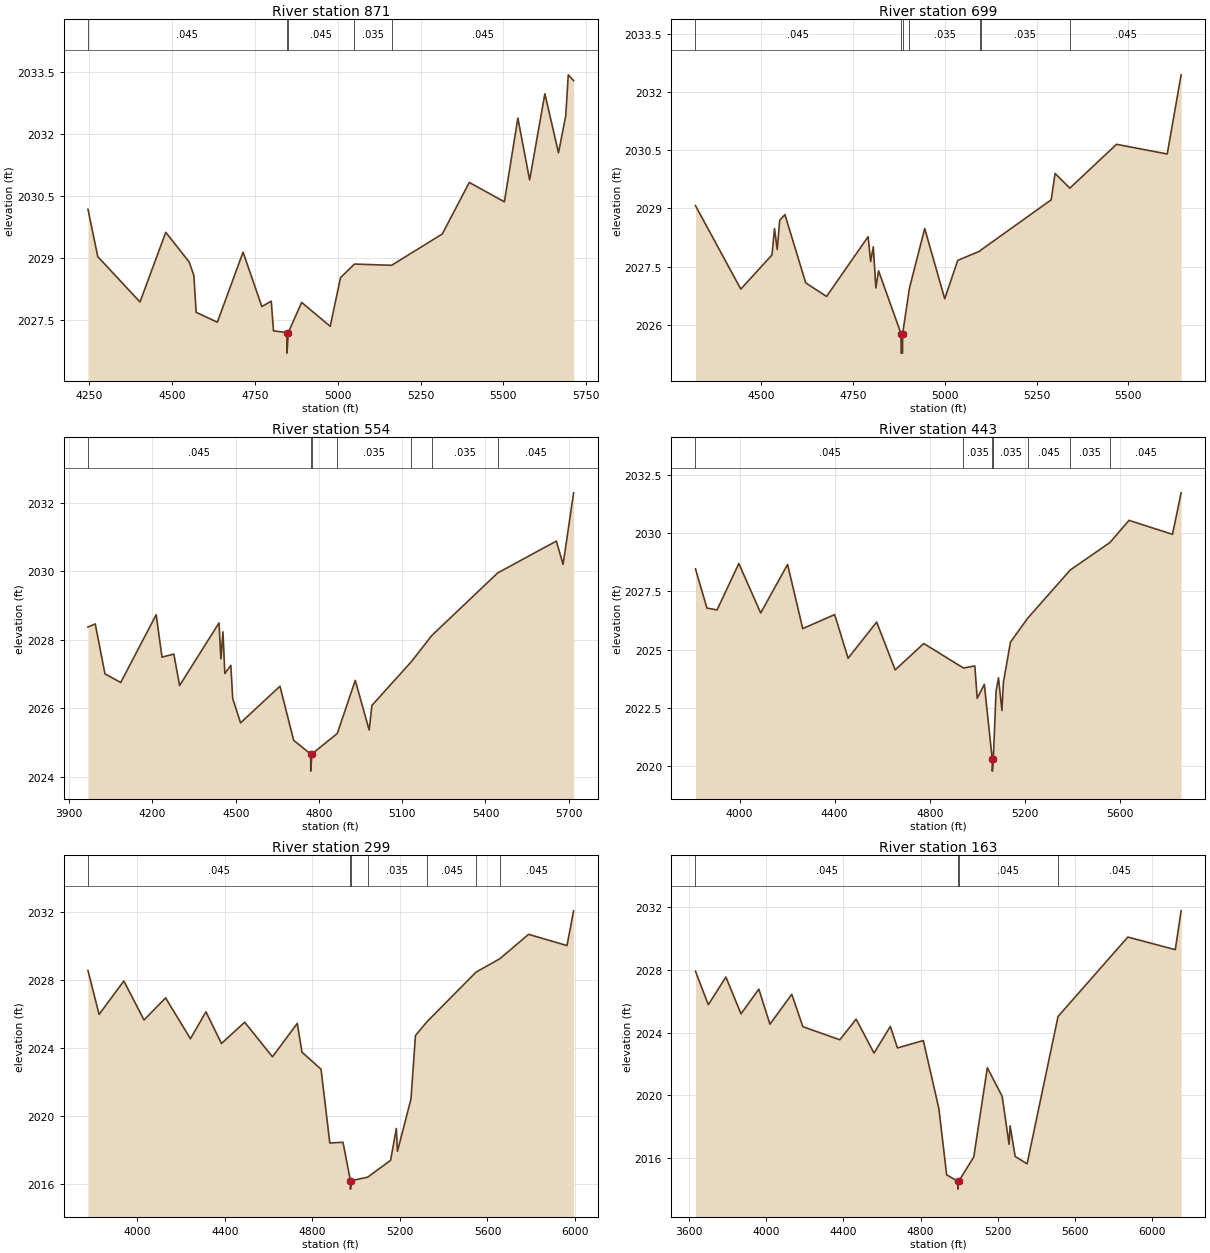
Type RM Length L Ch R = 1,871,172,172,172
BEGIN DESCRIPTION:
Alkali Creek Trib 02-05 0.8
END DESCRIPTION:
XS GIS Cut Line= 4
      1364759.73      6951304.67      1365218.91      6950818.27
      1365163.13      6950605.69      1364633.14      6950377.50
#Sta/Elev= 30
  4246.2 2030.18  4275.9 2029.03  4403.3 2027.93  4481.0 2029.62  4551.8 2028.90
  4565.9 2028.57  4572.8 2027.68  4636.7 2027.44  4714.4 2029.14  4771.0 2027.82
  4799.4 2027.95  4806.2 2027.23  4846.6 2027.19  4846.9 2026.69  4850.9 2027.19
  4891.2 2027.92  4977.4 2027.34  5008.4 2028.52  5050.6 2028.85  5162.6 2028.82
  5315.6 2029.58  5397.1 2030.83  5503.0 2030.36  5543.7 2032.39  5579.2 2030.89
  5625.2 2032.98  5666.3 2031.55  5688.1 2032.44  5695.8 2033.44  5711.9 2033.30
#Mann=5,-1,0
  4246.2   0.045       0  4846.6   0.045       0  4850.9   0.045       0
  5050.6   0.035       0  5162.6   0.045       0
Bank Sta=4846.6,4850.9
Exp/Cntr=0.3,0.1

Type RM Length L Ch R = 1,699,145,145,145
BEGIN DESCRIPTION:
Alkali Creek Trib 02-05 0.5
END DESCRIPTION:
XS GIS Cut Line= 5
      1364997.57      6951175.20      1365380.00      6950763.00
      1365341.62      6950652.25      1365320.50      6950560.01
      1364798.48      6950389.78
#Sta/Elev= 30
  4320.5 2029.07  4444.0 2026.92  4529.0 2027.80  4535.8 2028.48  4543.2 2027.94
  4550.0 2028.69  4564.2 2028.84  4620.9 2027.08  4677.6 2026.73  4790.9 2028.27
  4797.8 2027.63  4805.1 2028.01  4811.9 2026.95  4819.3 2027.39  4880.6 2025.77
  4880.9 2025.27  4884.6 2025.27  4884.9 2025.77  4903.6 2026.95  4945.1 2028.48
  4999.6 2026.67  5035.1 2027.66  5095.8 2027.90  5097.4 2027.92  5289.7 2029.22
  5300.3 2029.90  5340.5 2029.52  5467.7 2030.65  5605.8 2030.40  5643.7 2032.44
#Mann=7,-1,0
  4320.5   0.045       0  4880.6   0.035       0  4884.9   0.045       0
  4903.6   0.035       0  5095.8   0.045       0  5097.4   0.035       0
  5340.5   0.045       0
Bank Sta=4880.6,4884.9
Exp/Cntr=0.3,0.1

Type RM Length L Ch R = 1,554,111,111,111
BEGIN DESCRIPTION:
Alkali Creek Trib 02-05 0.7
END DESCRIPTION:
XS GIS Cut Line= 4
      1364911.69      6951401.73      1365478.22      6950779.07
      1365466.16      6950561.97      1364805.34      6950361.52
#Sta/Elev= 30
  3967.7 2028.37  3994.0 2028.46  4029.1 2027.00  4085.9 2026.75  4213.6 2028.73
  4234.5 2027.49  4277.1 2027.58  4298.0 2026.66  4439.9 2028.49  4446.7 2027.44
  4454.1 2028.23  4460.9 2027.01  4482.5 2027.25  4489.3 2026.28  4517.6 2025.57
  4659.5 2026.64  4708.9 2025.06  4770.2 2024.66  4770.5 2024.16  4774.5 2024.66
  4866.1 2025.26  4930.8 2026.81  4980.9 2025.36  4990.9 2026.08  5133.2 2027.36
  5206.4 2028.12  5444.0 2029.95  5655.2 2030.88  5679.6 2030.20  5717.5 2032.29
#Mann=7,-1,0
  3967.7   0.045       0  4770.2   0.035       0  4774.5   0.045       0
  4866.1   0.035       0  5133.2   0.045       0  5206.4   0.035       0
  5444.0   0.045       0
Bank Sta=4770.2,4774.5
Exp/Cntr=0.3,0.1

Type RM Length L Ch R = 1,443,144,144,144
BEGIN DESCRIPTION:
Alkali Creek Trib 02-05 0.3
END DESCRIPTION:
XS GIS Cut Line= 4
      1364887.08      6951478.20      1365580.00      6950813.00
      1365577.87      6950521.98      1364809.72      6950328.94
#Sta/Elev= 30
  3814.4 2028.46  3862.6 2026.78  3905.1 2026.70  3996.9 2028.69  4088.8 2026.57
  4202.0 2028.65  4265.8 2025.90  4400.1 2026.50  4456.7 2024.63  4576.8 2026.18
  4654.8 2024.13  4774.9 2025.26  4942.2 2024.21  4989.9 2024.30  4999.9 2022.91
  5029.9 2023.51  5063.3 2020.29  5063.6 2019.79  5067.6 2020.29  5079.2 2023.21
  5089.5 2023.79  5103.9 2022.39  5110.2 2023.60  5139.9 2025.32  5212.7 2026.35
  5391.2 2028.41  5558.5 2029.59  5638.7 2030.54  5821.6 2029.94  5858.0 2031.72
#Mann=7,-1,0
  3814.4   0.045       0  4942.2   0.035       0  5063.3   0.035       0
  5067.6   0.035       0  5212.7   0.045       0  5391.2   0.035       0
  5558.5   0.045       0
Bank Sta=5063.3,5067.6
Exp/Cntr=0.3,0.1

Type RM Length L Ch R = 1,299,136,136,136
BEGIN DESCRIPTION:
Alkali Creek Trib 02-05 0.6
END DESCRIPTION:
XS GIS Cut Line= 4
      1364964.12      6951489.00      1365701.35      6950812.24
      1365726.98      6950536.34      1364815.78      6950298.33
#Sta/Elev= 30
  3774.0 2028.56  3825.0 2025.98  3938.1 2027.94  4030.3 2025.65  4128.9 2026.95
  4242.4 2024.55  4313.3 2026.13  4384.2 2024.27  4490.3 2025.52  4617.3 2023.49
  4730.7 2025.45  4752.3 2023.76  4839.3 2022.76  4879.4 2018.43  4939.7 2018.47
  4973.5 2016.22  4973.8 2015.72  4977.8 2016.22  5052.2 2016.42  5157.2 2017.41
  5183.4 2019.28  5188.6 2017.94  5250.3 2021.01  5270.9 2024.74  5322.9 2025.54
  5547.6 2028.46  5656.9 2029.25  5787.7 2030.68  5963.4 2030.02  5993.6 2032.06
#Mann=7,-1,0
  3774.0   0.045       0  4973.5   0.045       0  4977.8   0.045       0
  5052.2   0.035       0  5322.9   0.045       0  5547.6   0.035       0
  5656.9   0.045       0
Bank Sta=4973.5,4977.8
Exp/Cntr=0.3,0.1

Type RM Length L Ch R = 1,163,0,0,0
BEGIN DESCRIPTION:
Alkali Creek Trib 02-05 0.4
END DESCRIPTION:
XS GIS Cut Line= 5
      1364942.92      6951538.87      1365830.00      6950813.00
      1365857.35      6950593.71      1365851.41      6950506.03
      1364820.69      6950245.57
#Sta/Elev= 30
  3632.8 2027.90  3699.4 2025.77  3790.6 2027.53  3868.8 2025.19  3961.4 2026.76
  4018.9 2024.53  4132.3 2026.43  4189.7 2024.37  4381.3 2023.54  4466.0 2024.85
  4558.6 2022.69  4643.3 2024.39  4680.0 2023.02  4814.3 2023.49  4894.9 2019.16
  4935.2 2014.95  4992.8 2014.54  4993.2 2014.04  4997.8 2014.54  5075.9 2016.09
  5146.1 2021.76  5223.1 2019.94  5258.9 2016.89  5264.1 2018.07  5290.5 2016.12
  5352.3 2015.65  5512.8 2025.02  5874.5 2030.07  6120.7 2029.27  6151.0 2031.74
#Mann=4,-1,0
  3632.8   0.045       0  4992.8   0.035       0  4997.8   0.045       0
  5512.8   0.045       0
Bank Sta=4992.8,4997.8
Exp/Cntr=0.3,0.1

Chan Stop Cuts=-1