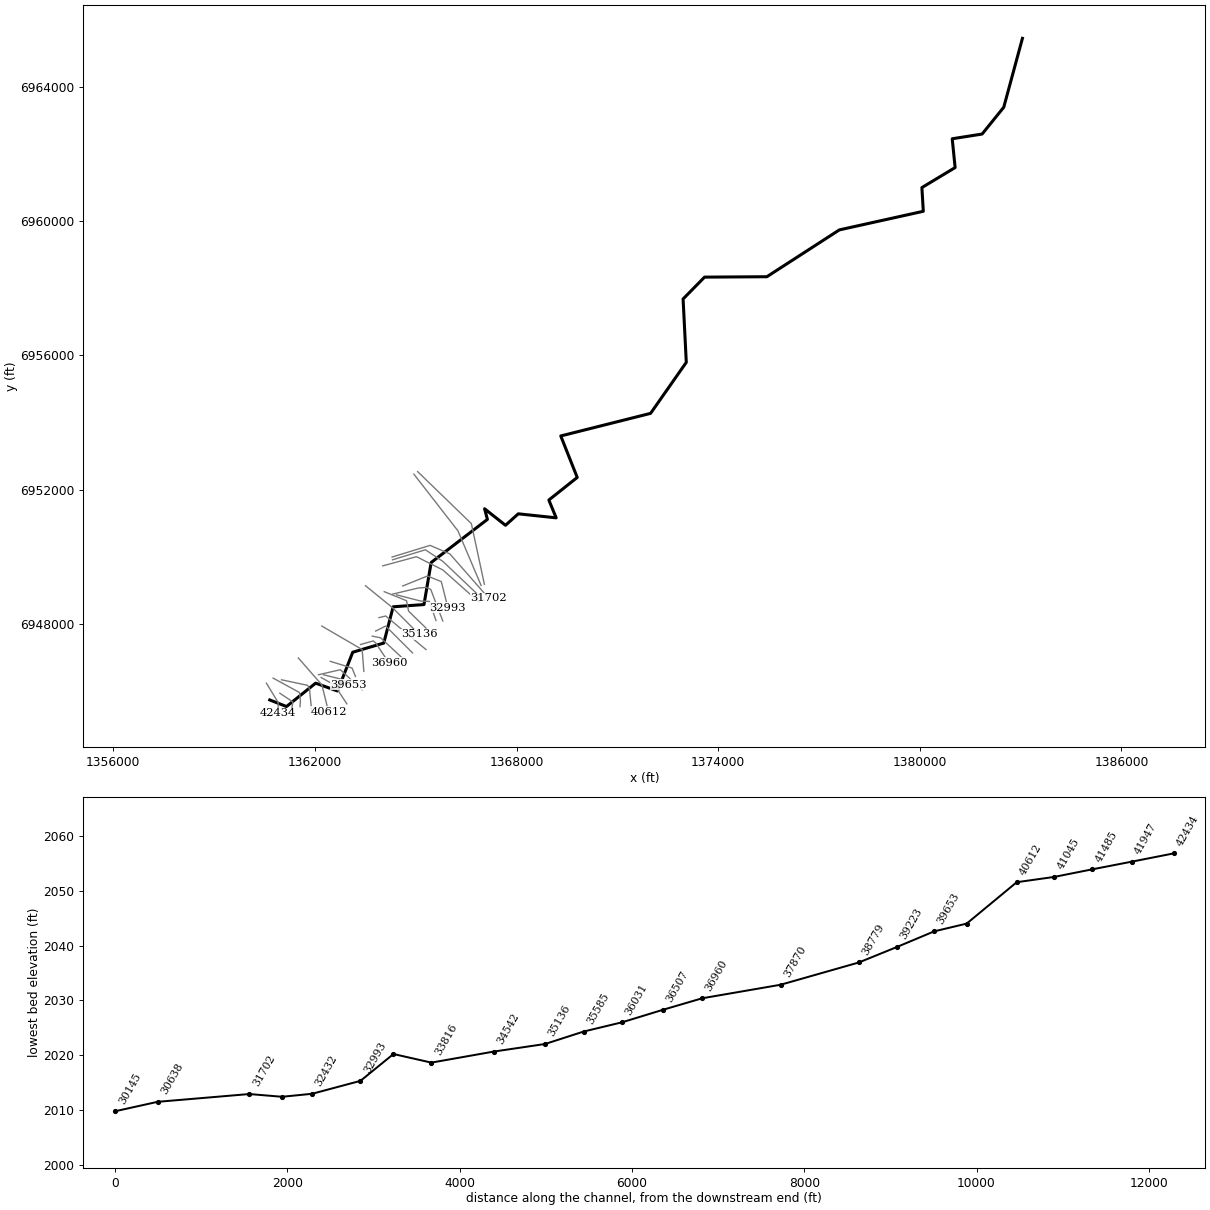
--- Alkali Creek Trib 02.prj (project) ---

Proj Title=Alkali Creek Trib 02 Base Level Engineering
Current Plan=p01
Default Exp/Contr=0.3,0.1
English Units
Geom File=g01
Flow File=f01
Plan File=p01
Y Axis Title=Elevation
X Axis Title(PF)=Main Channel Distance
X Axis Title(XS)=Station
BEGIN DESCRIPTION:
Alkali Creek Trib 02
END DESCRIPTION:
DSS Export Rating Curves= 0
DSS Export Rating Curve Sorted= 0
DSS Export Volume Flow Curves= 0
DXF OffsetX= 0
DXF OffsetY= 0
DXF ScaleX= 1
DXF ScaleY= 10

--- Alkali Creek Trib 02.p01 (plan) ---

Plan Title=Multiple Run
Short Identifier=Multiple
Geom File=g01
Flow File=f01
Subcritical Flow
K Sum by GR= 0
Std Step Tol= 0.01
Critical Tol= 0.01
Num of Std Step Trials= 20
Max Error Tol= 0.3
Flow Tol Ratio= 0.001
Split Flow NTrial= 30
Split Flow Tol= 0.02
Split Flow Ratio= 0.02
Log Output Level= 0
Friction Slope Method= 1
Unsteady Friction Slope Method= 2
Unsteady Bridges Friction Slope Method= 1
Parabolic Critical Depth
Global Vel Dist=  1 , 1 , 1
Global Log Level= 0
CheckData=True
Encroach Param= -1, 0, 0, 0
BEGIN DESCRIPTION:
Multiple Run
END DESCRIPTION:

--- Alkali Creek Trib 02.f01 (steady flow) ---

Flow Title=Multiple
Program Version=4.10
Number of Profiles= 7
Profile Names=10-year,25-year,50-year,1pct_min,100-year,1pct_plu,500-year
River Rch & RM=Alkali Creek Tri,Reach-1         ,42434
     392     563     708     442     882    1760    1389
River Rch & RM=Alkali Creek Tri,Reach-1         ,30638
     666     981    1255     795    1587    3166    2575
River Rch & RM=Alkali Creek Tri,Reach-1         ,25383
     681    1002    1280     811    1618    3227    2619
River Rch & RM=Alkali Creek Tri,Reach-1         ,22334
     764    1128    1445     918    1831    3653    2979
River Rch & RM=Alkali Creek Tri,Reach-1         ,20019
     837    1239    1591    1011    2018    4026    3294
River Rch & RM=Alkali Creek Tri,Reach-1         ,16250
     900    1336    1718    1094    2183    4356    3575
River Rch & RM=Alkali Creek Tri,Reach-1         ,12626
     895    1329    1708    1087    2170    4329    3549
River Rch & RM=Alkali Creek Tri,Reach-1         ,11130
    1237    1858    2407    1543    3079    6143    5108
River Rch & RM=Alkali Creek Tri,Reach-1         ,2837
    1321    1987    2577    1653    3299    6582    5480
Boundary for River Rch & Prof#=Alkali Creek Tri,Reach-1         , 1
Up Type= 0
Dn Type= 3
Dn Slope=0.002
Boundary for River Rch & Prof#=Alkali Creek Tri,Reach-1         , 2
Up Type= 0
Dn Type= 3
Dn Slope=0.002
Boundary for River Rch & Prof#=Alkali Creek Tri,Reach-1         , 3
Up Type= 0
Dn Type= 3
Dn Slope=0.002
Boundary for River Rch & Prof#=Alkali Creek Tri,Reach-1         , 4
Up Type= 0
Dn Type= 3
Dn Slope=0.002
Boundary for River Rch & Prof#=Alkali Creek Tri,Reach-1         , 5
Up Type= 0
Dn Type= 3
Dn Slope=0.002
Boundary for River Rch & Prof#=Alkali Creek Tri,Reach-1         , 6
Up Type= 0
Dn Type= 3
Dn Slope=0.002
Boundary for River Rch & Prof#=Alkali Creek Tri,Reach-1         , 7
Up Type= 0
Dn Type= 3
Dn Slope=0.002
DSS Import GetInterval= 0
DSS Import GetPeak= 0
DSS Import FillOption= 0

--- Alkali Creek Trib 02.g01 (geometry) ---

Geom Title=Existing Conditions
Program Version=4.10

River Reach=Alkali Creek Tri,Reach-1
Reach XY= 30
        1360655.        6945738.      1361153.55      6945541.53
      1362020.22      6946237.51      1362671.79      6946004.39
      1363124.21      6947158.58      1364047.55      6947431.31
      1364327.55      6948511.84      1365244.81      6948578.27
      1365457.81      6949830.05       1367132.5      6951114.05
      1367048.43      6951430.31      1367670.22      6950938.49
      1368051.36      6951280.24      1369178.85      6951160.18
      1368960.69      6951690.57      1369805.54      6952362.87
      1369315.82      6953598.32      1371988.58       6954271.2
      1373051.17      6955789.58      1372955.98      6957677.72
      1373594.82      6958327.68      1375449.13      6958339.56
      1377606.56      6959734.24        1380105.        6960288.
      1380062.81      6960994.19      1381051.86      6961589.64
      1380965.43      6962447.79        1381855.        6962588.
      1382499.17       6963385.7        1383055.        6965438.

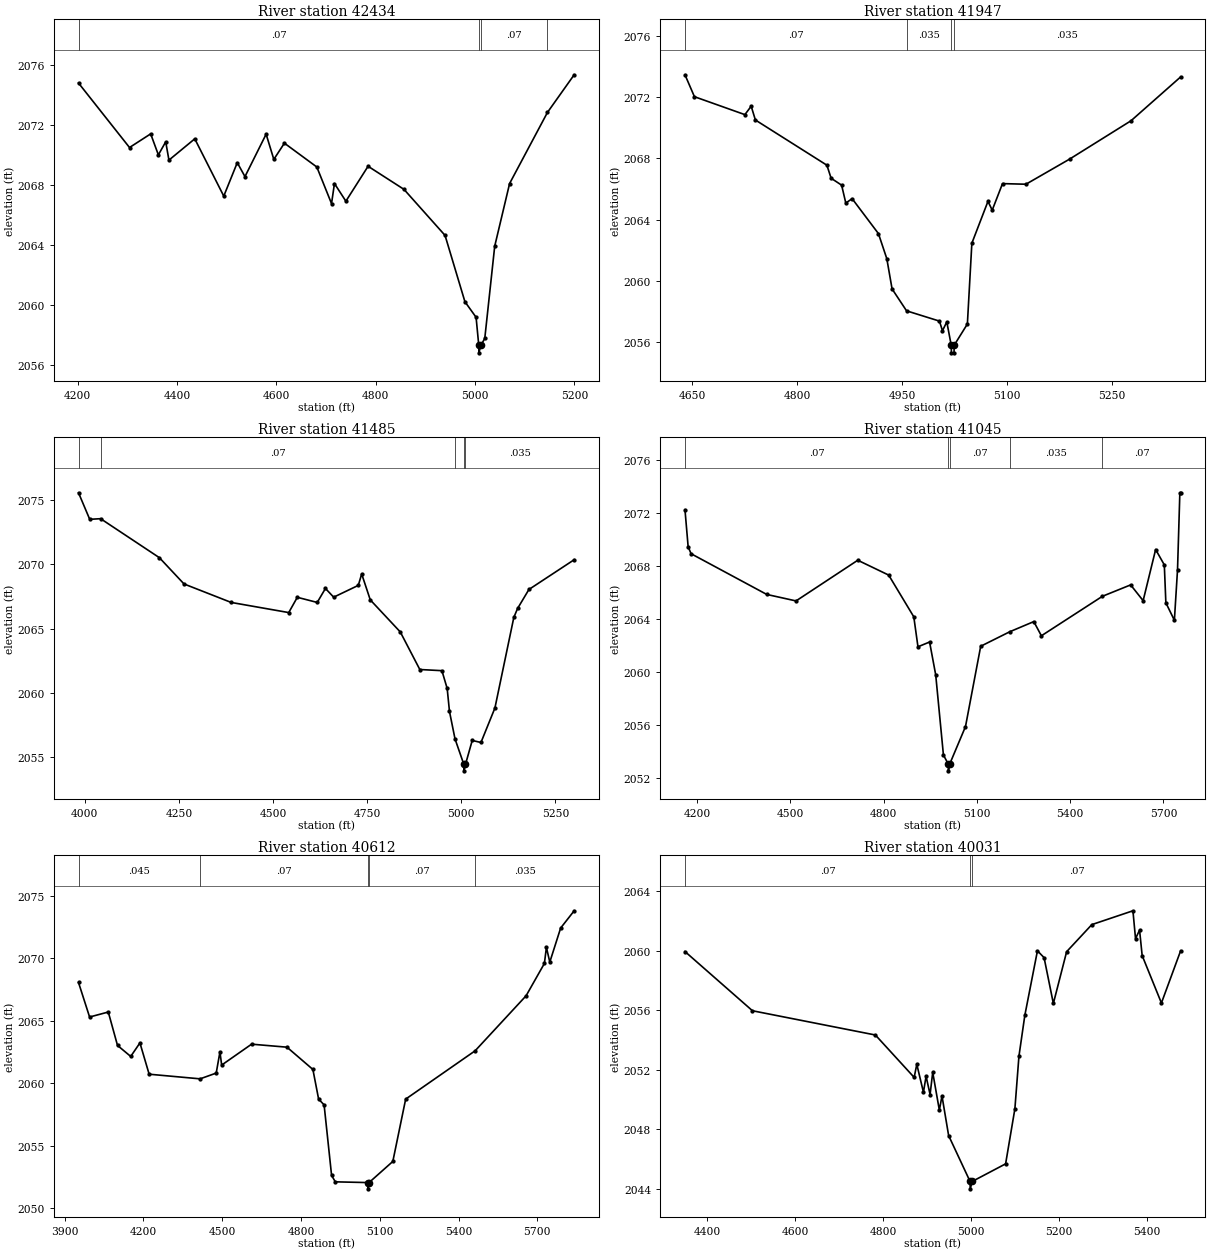
Type RM Length L Ch R = 1 ,42434   ,487,487,487
BEGIN DESCRIPTION:
Alkali Creek Trib 02 50.0
END DESCRIPTION:
XS GIS Cut Line= 4
        1360555.      6946237.99      1360904.93      6945662.67
        1360905.        6945538.        1360905.      6945337.96
#Sta/Elev= 30
  4201.5 2074.82  4304.2 2070.52  4346.8 2071.43  4362.3 2070.03  4377.1  2070.9
  4383.6 2069.68  4435.6  2071.1    4494 2067.28  4521.2 2069.51  4536.7 2068.58
  4579.3 2071.41  4594.8 2069.73  4616.1 2070.81  4681.4 2069.22    4711 2066.78
  4716.9 2068.12  4739.9 2066.94  4784.6 2069.27  4856.9 2067.73  4939.6 2064.66
  4979.6 2060.24  5002.1  2059.2  5007.5 2057.33  5007.7 2056.83  5011.7 2057.33
  5019.6 2057.79  5039.6 2063.94  5069.6 2068.12  5145.8 2072.86  5199.6 2075.37
#Mann= 4 ,-1 , 0
  4201.5     .07       0  5007.5     .07       0  5011.7     .07       0
  5145.8    .035       0
Bank Sta=5007.5,5011.7
XS Rating Curve= 0 ,0
Exp/Cntr=0.3,0.1

Type RM Length L Ch R = 1 ,41947   ,462,462,462
BEGIN DESCRIPTION:
Alkali Creek Trib 02 49.0
END DESCRIPTION:
XS GIS Cut Line= 5
      1360955.02      6945937.99      1361182.43      6945786.38
        1361255.        6945738.      1361342.43      6945674.82
      1361304.99      6945437.96
#Sta/Elev= 30
  4639.5 2073.46    4653 2072.03  4725.1 2070.86  4734.1 2071.41  4740.1 2070.51
  4842.3 2067.56  4848.3 2066.71  4863.3 2066.26  4869.3 2065.09  4878.3 2065.38
  4915.9  2063.1  4927.9 2061.46  4935.4 2059.49  4956.1 2058.06  5003.1 2057.39
  5007.4 2056.76  5013.6 2057.34  5019.9 2055.82  5020.2 2055.32  5023.9 2055.32
  5024.2 2055.82    5043  2057.2  5049.4 2062.47  5072.4  2065.2  5078.5 2064.63
  5093.2 2066.36  5126.7 2066.32  5189.1 2067.96  5276.8 2070.46  5347.7 2073.32
#Mann= 4 ,-1 , 0
  4639.5     .07       0  4956.1    .035       0  5019.9    .035       0
  5024.2    .035       0
Bank Sta=5019.9,5024.2
XS Rating Curve= 0 ,0
Exp/Cntr=0.3,0.1

Type RM Length L Ch R = 1 ,41485   ,440,440,440
BEGIN DESCRIPTION:
Alkali Creek Trib 02 48.0
END DESCRIPTION:
XS GIS Cut Line= 5
      1360755.03      6946387.98      1361538.62      6945959.55
        1361555.        6945838.      1361566.39       6945721.7
        1361555.      6945538.01
#Sta/Elev= 30
  3983.4 2075.59  4013.2 2073.52  4042.1 2073.57  4198.2 2070.53  4263.7 2068.48
  4388.9 2067.04  4541.8 2066.25  4564.6 2067.44  4617.5 2067.04  4639.3 2068.13
  4661.2 2067.45  4726.6 2068.37  4735.6 2069.26  4758.4 2067.24  4838.1 2064.74
    4890 2061.81  4948.7 2061.72  4962.7 2060.33  4968.8 2058.54  4983.5  2056.4
    5007 2054.41  5007.3 2053.91  5011.3 2054.41  5029.2 2056.28  5052.4 2056.12
  5089.5 2058.81  5139.7 2065.87  5149.7 2066.57  5179.8 2068.05    5300 2070.37
#Mann= 5 ,-1 , 0
  3983.4    .045       0  4042.1     .07       0  4983.5    .035       0
    5007    .035       0  5011.3    .035       0
Bank Sta=5007,5011.3
XS Rating Curve= 0 ,0
Exp/Cntr=0.3,0.1

Type RM Length L Ch R = 1 ,41045   ,433,433,433
BEGIN DESCRIPTION:
Alkali Creek Trib 02 47.0
END DESCRIPTION:
XS GIS Cut Line= 5
      1361004.99        6946338.      1361774.73      6946174.82
        1361805.        6946138.      1361837.23      6946060.24
        1361905.      6945388.04
#Sta/Elev= 30
    4161 2072.23  4171.2 2069.43  4180.7 2068.91    4424 2065.84  4518.2 2065.35
  4716.8 2068.42  4816.2  2067.3    4897 2064.15  4910.4 2061.89  4947.8 2062.25
  4967.5 2059.77  4992.3 2053.73    5008 2053.03  5008.3 2052.53  5012.3 2053.03
  5063.3 2055.87  5112.2 2061.93  5206.2 2063.03    5283 2063.79  5307.4 2062.72
  5503.7  2065.7  5594.5 2066.56  5634.7 2065.37  5674.9 2069.23  5702.8 2068.07
  5707.8 2065.21  5735.2 2063.89  5745.3  2067.7  5752.8 2073.51  5755.3 2073.51
#Mann= 5 ,-1 , 0
    4161     .07       0    5008     .07       0  5012.3     .07       0
  5206.2    .035       0  5503.7     .07       0
Bank Sta=5008,5012.3
XS Rating Curve= 0 ,0
Exp/Cntr=0.3,0.1

Type RM Length L Ch R = 1 ,40612   ,581,581,581
BEGIN DESCRIPTION:
Alkali Creek Trib 02 46.0
END DESCRIPTION:
XS GIS Cut Line= 3
      1361505.02      6946987.97        1362205.        6946188.
        1362405.        6945388.
#Sta/Elev= 30
  3952.8 2068.06    3995  2065.3  4066.2  2065.7  4101.3 2063.03  4151.6 2062.15
  4186.7 2063.23  4221.8 2060.73  4415.9 2060.36  4477.2 2060.82  4491.4 2062.51
    4498 2061.46  4611.9 2063.13  4746.7 2062.89  4845.4 2061.11  4867.2 2058.74
  4888.1 2058.28  4916.6 2052.64  4930.8 2052.13  5054.9 2052.07  5055.2 2051.57
  5059.2 2052.07  5149.8 2053.76  5198.7 2058.74  5463.2  2062.6  5657.4    2067
    5727 2069.58  5734.7 2070.86  5747.6 2069.69  5788.9 2072.41  5840.4 2073.79
#Mann= 5 ,-1 , 0
  3952.8    .045       0  4415.9     .07       0  5054.9     .07       0
  5059.2     .07       0  5463.2    .035       0
Bank Sta=5054.9,5059.2
XS Rating Curve= 0 ,0
Exp/Cntr=0.3,0.1

Type RM Length L Ch R = 1 ,40031   ,378,378,378
BEGIN DESCRIPTION:
Alkali Creek Trib 02 45.5
END DESCRIPTION:
XS GIS Cut Line= 3
      1362183.42      6946407.06      1362583.97      6946179.17
      1362948.93       6945621.4
#Sta/Elev= 30
  4349.2 2059.96  4502.7 2055.98  4782.3 2054.35  4870.5  2051.5  4876.5 2052.38
  4891.6  2050.5  4897.6 2051.58  4906.7 2050.35  4912.7 2051.84  4927.8  2049.3
  4933.8 2050.25  4948.9 2047.59  4997.6 2044.51    4998 2044.01  5002.7 2044.51
  5078.5 2045.69  5099.6 2049.39  5108.8 2052.92  5122.2 2055.67  5150.9 2060.01
    5166 2059.55  5187.1 2056.47  5217.3 2059.95  5274.6 2061.77  5368.1  2062.7
    5374 2060.83  5383.2  2061.4  5389.1 2059.69  5432.9  2056.5  5476.6 2060.01
#Mann= 3 ,-1 , 0
  4349.2     .07       0  4997.6     .07       0  5002.7     .07       0
Bank Sta=4997.6,5002.7
XS Rating Curve= 0 ,0
Exp/Cntr=0.3,0.1

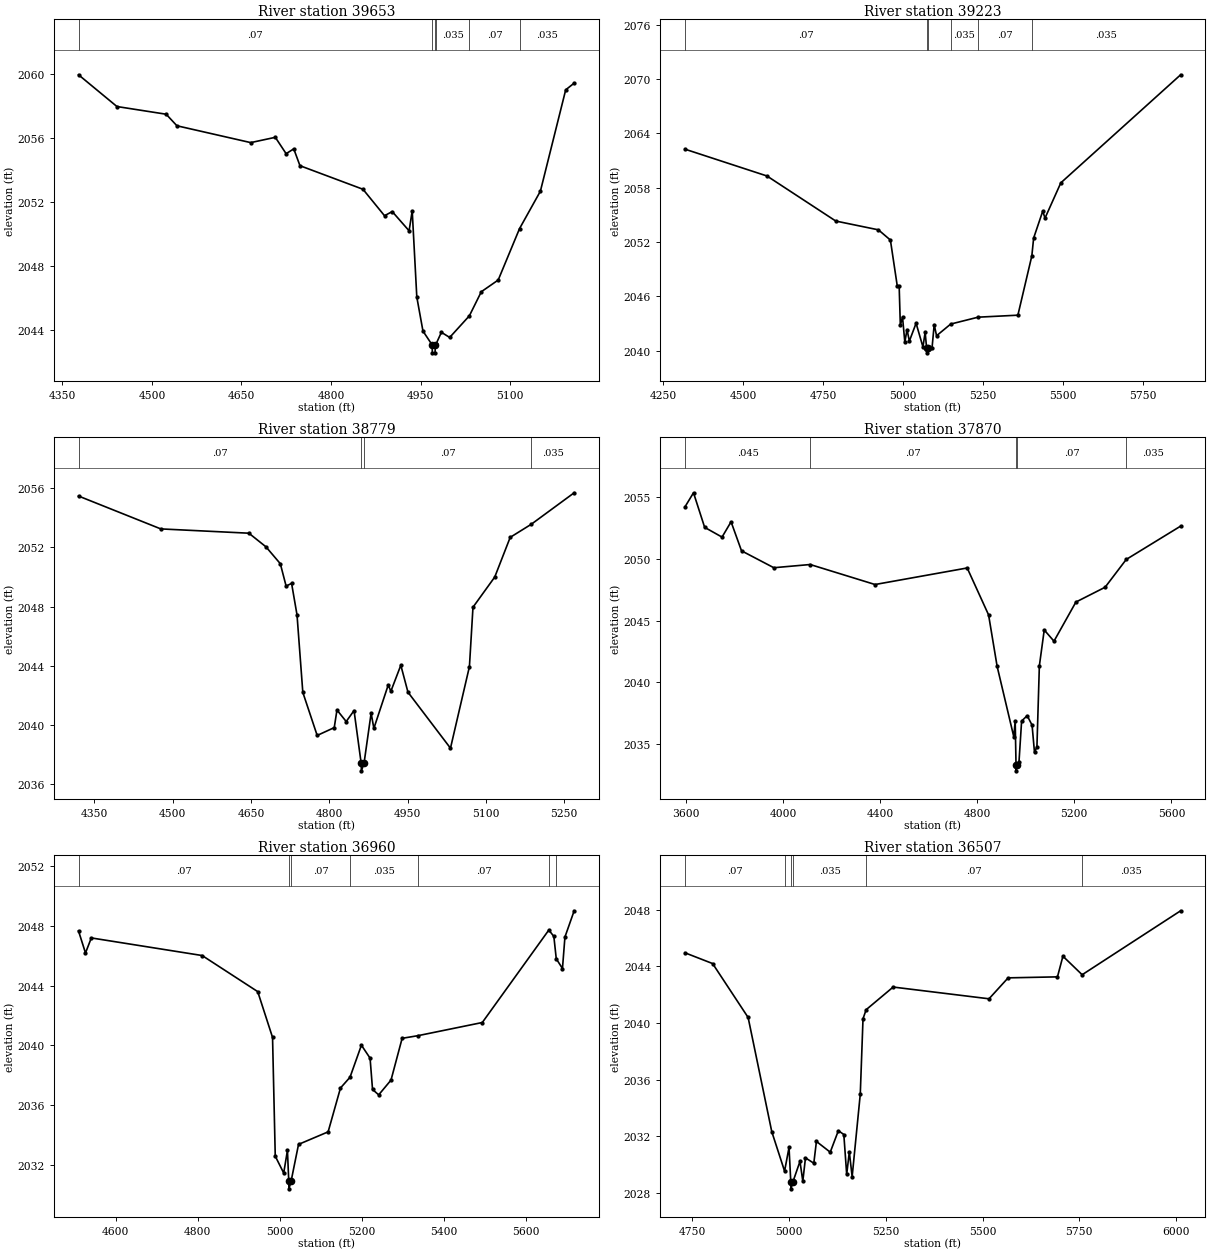
Type RM Length L Ch R = 1 ,39653   ,430,430,430
BEGIN DESCRIPTION:
Alkali Creek Trib 02 45.0
END DESCRIPTION:
XS GIS Cut Line= 3
      1362255.02      6946487.99        1362855.        6946338.
      1363005.02      6946187.98
#Sta/Elev= 30
  4376.9 2059.93  4441.3 2057.95  4523.8 2057.47  4541.8 2056.75  4665.5  2055.7
  4706.7 2056.03  4724.8 2055.01  4737.6 2055.31    4748 2054.26  4853.6 2052.79
  4889.7 2051.14  4902.6  2051.4  4930.9  2050.2  4936.1 2051.45  4943.8 2046.07
  4954.1 2043.95  4969.4 2043.09  4969.9 2042.59  4974.4 2042.59  4974.8 2043.09
  4976.4 2043.17    4985 2043.87  4998.9 2043.55  5031.9  2044.9  5051.9  2046.4
  5080.2 2047.13    5116 2050.34  5150.9 2052.67  5193.3 2058.99  5207.5 2059.41
#Mann= 6 ,-1 , 0
  4376.9     .07       0  4969.4    .035       0  4974.8     .07       0
  4976.4    .035       0  5031.9     .07       0    5116    .035       0
Bank Sta=4969.4,4974.8
XS Rating Curve= 0 ,0
Exp/Cntr=0.3,0.1

Type RM Length L Ch R = 1 ,39223   ,444,444,444
BEGIN DESCRIPTION:
Alkali Creek Trib 02 44.0
END DESCRIPTION:
XS GIS Cut Line= 3
        1362105.        6946488.        1362755.        6946638.
      1363405.02      6946037.98
#Sta/Elev= 30
  4317.5 2062.25  4574.1 2059.29  4789.6 2054.31    4923 2053.34  4960.6 2052.21
    4982 2047.16    4988 2047.16  4991.7 2042.79  4998.5 2043.72  5005.8 2040.92
  5012.6 2042.32    5020 2041.05    5041 2043.02  5062.5  2040.4  5069.4 2042.03
    5074 2040.25  5074.5 2039.75  5079.4 2040.25  5090.9 2040.27  5097.7 2042.87
  5105.1 2041.64  5149.4 2042.93  5235.2 2043.69  5359.7 2043.91  5403.4 2050.47
    5409 2052.43  5437.4 2055.39  5444.7 2054.64  5494.1 2058.53  5869.2 2070.47
#Mann= 6 ,-1 , 0
  4317.5     .07       0    5074     .07       0  5079.4     .07       0
  5149.4    .035       0  5235.2     .07       0  5403.4    .035       0
Bank Sta=5074,5079.4
XS Rating Curve= 0 ,0
Exp/Cntr=0.3,0.1

Type RM Length L Ch R = 1 ,38779   ,909,909,909
BEGIN DESCRIPTION:
Alkali Creek Trib 02 43.0
END DESCRIPTION:
XS GIS Cut Line= 3
      1362454.99        6946888.        1363105.        6946688.
      1363204.98      6946438.04
#Sta/Elev= 30
  4319.6 2055.47  4477.2 2053.25  4645.9 2052.96  4678.6 2052.04  4706.1  2050.9
  4717.2 2049.39  4727.7 2049.57  4738.1 2047.44  4749.2 2042.21  4776.7  2039.3
  4809.4 2039.83  4814.6 2041.02  4832.3 2040.24  4847.3 2040.98    4861 2037.41
  4861.4 2036.91  4866.4 2037.41    4880  2040.8  4885.3 2039.78  4912.7  2042.7
  4917.9 2042.29  4936.9 2044.04  4950.6 2042.22    5032 2038.44  5068.3 2043.95
  5075.1 2047.96  5116.8    2050  5146.4 2052.68  5186.6 2053.56  5268.9 2055.69
#Mann= 4 ,-1 , 0
  4319.6     .07       0    4861     .07       0  4866.4     .07       0
  5186.6    .035       0
Bank Sta=4861,4866.4
XS Rating Curve= 0 ,0
Exp/Cntr=0.3,0.1

Type RM Length L Ch R = 1 ,37870   ,910,910,910
BEGIN DESCRIPTION:
Alkali Creek Trib 02 42.0
END DESCRIPTION:
XS GIS Cut Line= 3
        1362205.        6947938.        1363405.        6947238.
        1363455.      6946587.96
#Sta/Elev= 30
  3596.7 2054.22  3631.8 2055.36  3677.7 2052.56  3749.3 2051.77  3786.5 2053.01
  3829.5 2050.66  3962.6 2049.29  4112.3 2049.55  4379.4 2047.93  4758.9 2049.27
    4847 2045.47  4882.2  2041.3  4950.8  2035.6  4956.6 2036.88    4960 2033.34
  4960.5 2032.84  4965.5 2033.34  4972.3 2033.59    4983 2036.87    5006 2037.31
  5026.1 2036.54  5036.1 2034.33  5046.1 2034.79  5056.1 2041.34  5076.2 2044.25
  5116.3 2043.34  5206.6 2046.51  5326.9 2047.71  5413.9 2049.96  5637.9 2052.66
#Mann= 5 ,-1 , 0
  3596.7    .045       0  4112.3     .07       0    4960     .07       0
  4965.5     .07       0  5413.9    .035       0
Bank Sta=4960,4965.5
XS Rating Curve= 0 ,0
Exp/Cntr=0.3,0.1

Type RM Length L Ch R = 1 ,36960   ,453,453,453
BEGIN DESCRIPTION:
Alkali Creek Trib 02 41.0
END DESCRIPTION:
XS GIS Cut Line= 4
        1363355.        6947388.      1363738.38      6947495.77
        1363805.        6947438.      1364204.98      6946838.03
#Sta/Elev= 30
  4509.8 2047.66  4526.8 2046.18    4541 2047.19    4811 2046.01  4946.4 2043.59
  4982.5 2040.52  4989.1 2032.56  5009.7 2031.43  5018.8 2032.95    5022 2030.87
  5022.4 2030.37  5027.6 2030.87  5045.8 2033.35  5117.9 2034.19    5148 2037.13
  5171.2 2037.85    5199    2040  5220.1 2039.13  5226.1 2037.03  5241.1 2036.67
  5271.1 2037.66  5298.2 2040.46  5337.2 2040.64  5493.5 2041.52  5655.6 2047.72
  5667.8 2047.29  5673.7 2045.79  5688.8 2045.14  5694.8 2047.25  5717.3 2049.01
#Mann= 7 ,-1 , 0
  4509.8     .07       0    5022     .07       0  5027.6     .07       0
  5171.2    .035       0  5337.2     .07       0  5655.6    .035       0
  5673.7     .07       0
Bank Sta=5022,5027.6
XS Rating Curve= 0 ,0
Exp/Cntr=0.3,0.1

Type RM Length L Ch R = 1 ,36507   ,476,476,476
BEGIN DESCRIPTION:
Alkali Creek Trib 02 40.0
END DESCRIPTION:
XS GIS Cut Line= 3
      1363705.01        6947638.        1363955.        6947588.
      1364705.03      6946887.97
#Sta/Elev= 30
  4730.8 2044.96  4802.2  2044.2    4894 2040.39  4955.1 2032.32  4988.2 2029.53
  4999.7 2031.21  5004.2 2028.78  5004.6 2028.28  5009.8 2028.78    5028 2030.22
  5035.3 2028.82  5042.2 2030.47  5063.7 2030.09  5070.5 2031.63  5106.2 2030.87
  5127.2 2032.39  5141.3 2032.12  5148.7  2029.3  5155.5 2030.89  5162.8 2029.14
  5183.8 2034.97  5190.9  2040.3    5199 2040.94  5268.8 2042.54  5516.5 2041.71
  5565.9 2043.19  5693.4 2043.26  5707.5 2044.72  5757.2 2043.41  6011.7 2047.93
#Mann= 6 ,-1 , 0
  4730.8     .07       0  4988.2    .035       0  5004.2    .035       0
  5009.8    .035       0    5199     .07       0  5757.2    .035       0
Bank Sta=5004.2,5009.8
XS Rating Curve= 0 ,0
Exp/Cntr=0.3,0.1

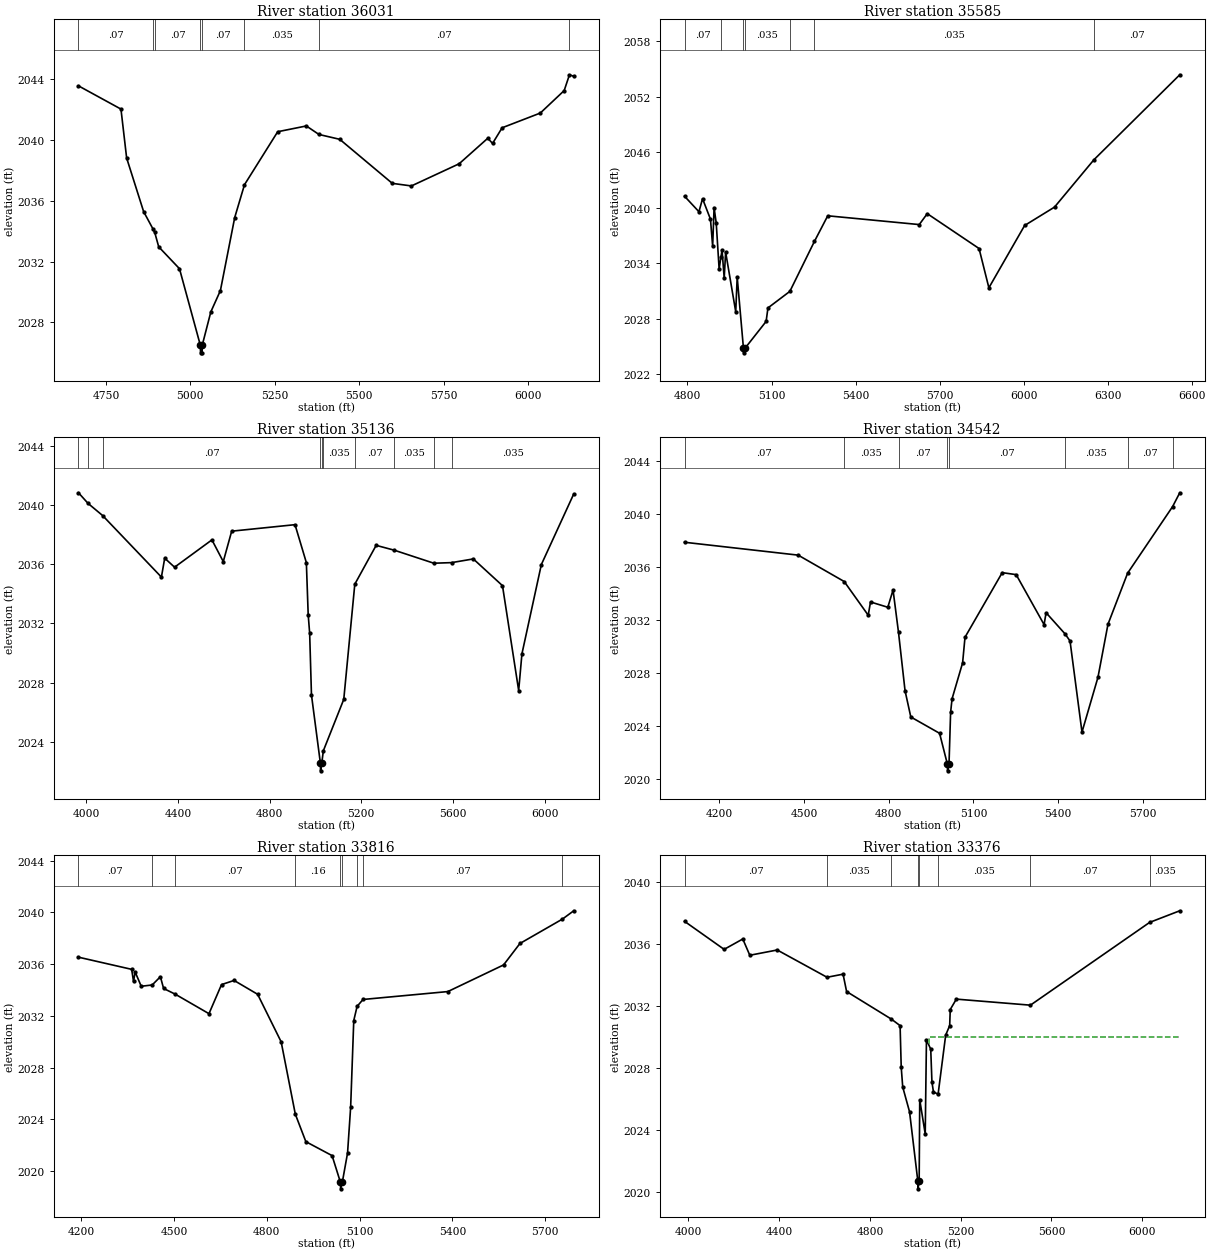
Type RM Length L Ch R = 1 ,36031   ,446,446,446
BEGIN DESCRIPTION:
Alkali Creek Trib 02 39.0
END DESCRIPTION:
XS GIS Cut Line= 3
      1363804.99      6947787.99        1364105.        6947938.
        1364905.        6947138.
#Sta/Elev= 30
  4668.7 2043.57  4794.5 2042.04  4811.3 2038.82  4861.6 2035.29    4889 2034.16
  4894.5 2033.92  4906.3 2032.97  4967.8 2031.53  5029.6 2026.49  5030.1 2025.99
  5034.8 2025.99  5035.2 2026.49  5060.7 2028.69    5089 2030.09  5131.4  2034.9
  5160.3 2037.06  5258.7 2040.55  5343.5 2040.93  5380.9 2040.37  5442.5 2040.05
  5598.1 2037.15  5654.7 2036.98  5796.1 2038.44  5880.9 2040.12  5895.1 2039.78
  5923.4 2040.81  6036.5 2041.78  6107.2 2043.26  6122.8  2044.3  6135.5  2044.2
#Mann= 8 ,-1 , 0
  4668.7     .07       0    4889    .035       0  4894.5     .07       0
  5029.6     .07       0  5035.2     .07       0  5160.3    .035       0
  5380.9     .07       0  6122.8    .035       0
Bank Sta=5029.6,5035.2
XS Rating Curve= 0 ,0
Exp/Cntr=0.3,0.1

Type RM Length L Ch R = 1 ,35585   ,449,449,449
BEGIN DESCRIPTION:
Alkali Creek Trib 02 38.0
END DESCRIPTION:
XS GIS Cut Line= 3
      1363905.05      6948188.01        1364105.        6948238.
      1365305.03      6947237.97
#Sta/Elev= 30
  4789.4 2041.25  4840.9 2039.57  4853.8 2040.98  4882.1 2038.76  4889.9 2035.83
    4895 2040.02  4902.7 2038.32    4913 2033.38  4919.8 2034.72  4923.4 2035.43
  4931.1 2032.38  4936.2 2035.21  4972.3 2028.74  4977.5  2032.5  4999.8  2024.8
  5000.3  2024.3  5005.5  2024.8  5080.8  2027.7  5087.3 2029.16  5165.5 2030.95
  5253.1 2036.35  5300.8 2039.13  5627.5 2038.18  5656.1 2039.36    5841 2035.59
  5876.1 2031.34  6003.7 2038.08  6110.4 2040.07    6251 2045.19  6557.6 2054.39
#Mann= 7 ,-1 , 0
  4789.4     .07       0  4919.8    .035       0  4999.8    .035       0
  5005.5    .035       0  5165.5     .07       0  5253.1    .035       0
    6251     .07       0
Bank Sta=4999.8,5005.5
XS Rating Curve= 0 ,0
Exp/Cntr=0.3,0.1

Type RM Length L Ch R = 1 ,35136   ,594,594,594
BEGIN DESCRIPTION:
Alkali Creek Trib 02 37.0
END DESCRIPTION:
XS GIS Cut Line= 3
        1363505.        6949138.        1364305.        6948488.
      1365104.97      6947688.03
#Sta/Elev= 30
  3965.5 2040.85  4007.3 2040.13  4070.7 2039.31  4327.5 2035.14  4341.9 2036.42
    4385 2035.81    4548 2037.66  4597.6 2036.19  4634.3 2038.25  4910.8 2038.69
  4960.3 2036.12  4968.3  2032.6  4974.7 2031.34  4982.6 2027.16  5021.7 2022.52
  5022.2 2022.02  5027.4 2022.52  5034.5 2023.38  5123.6 2026.86  5171.8 2034.66
    5265 2037.29  5344.4 2036.96  5516.8 2036.08  5594.2 2036.12  5689.2 2036.37
  5816.5 2034.56  5887.2 2027.46  5901.4 2029.94  5986.2 2035.99  6127.6 2040.77
#Mann= 10 ,-1 , 0
  3965.5     .07       0  4007.3    .045       0  4070.7     .07       0
  5021.7     .07       0  5027.4     .07       0  5034.5    .035       0
  5171.8     .07       0  5344.4    .035       0  5516.8     .07       0
  5594.2    .035       0
Bank Sta=5021.7,5027.4
XS Rating Curve= 0 ,0
Exp/Cntr=0.3,0.1

Type RM Length L Ch R = 1 ,34542   ,726,726,726
BEGIN DESCRIPTION:
Alkali Creek Trib 02 36.5
END DESCRIPTION:
XS GIS Cut Line= 4
      1364061.79      6948962.12      1364724.71      6948692.81
      1364786.86      6948382.06      1365304.78      6947877.94
#Sta/Elev= 30
    4076 2037.87  4478.8  2036.9    4642 2034.91  4727.1 2032.37  4735.2 2033.37
  4796.5 2032.97  4815.1 2034.27  4834.4 2031.08  4857.6 2026.68    4878  2024.7
    4980 2023.47  5007.7 2021.14  5008.2 2020.64  5013.4 2021.14  5019.1 2025.05
  5024.2 2026.07  5061.6 2028.78  5070.1 2030.71    5202 2035.58  5251.4 2035.43
  5350.4 2031.66  5357.4 2032.56  5424.4 2030.97  5442.3 2030.43  5484.7 2023.56
  5541.3 2027.69  5576.8 2031.69  5646.4 2035.54  5805.9 2040.56  5831.2  2041.6
#Mann= 8 ,-1 , 0
    4076     .07       0    4642    .035       0  4834.4     .07       0
  5007.7     .07       0  5013.4     .07       0  5424.4    .035       0
  5646.4     .07       0  5805.9    .035       0
Bank Sta=5007.7,5013.4
XS Rating Curve= 0 ,0
Exp/Cntr=0.3,0.1

Type RM Length L Ch R = 1 ,33816   ,440,440,440
BEGIN DESCRIPTION:
Alkali Creek Trib 02 36.0
END DESCRIPTION:
XS GIS Cut Line= 4
      1364428.67      6948867.79      1365140.49      6948683.76
      1365402.64      6948673.35      1365602.29      6948103.91
#Sta/Elev= 30
  4191.2 2036.54    4363  2035.6  4369.2 2034.66  4374.3  2035.4    4394 2034.29
  4429.4 2034.39    4456 2035.03  4466.3 2034.12  4503.8 2033.68    4613 2032.17
  4653.6 2034.42  4694.2 2034.74  4770.3 2033.67  4846.4 2029.99  4892.1  2024.4
  4926.2 2022.27    5011 2021.19  5038.1 2019.12  5038.6 2018.62    5044 2019.12
    5061 2021.39    5071 2024.94  5081.1 2031.64  5091.9 2032.74  5111.2 2033.27
  5385.2 2033.88  5565.3 2035.94  5618.3  2037.6  5755.8 2039.49  5792.2 2040.13
#Mann= 9 ,-1 , 0
  4191.2     .07       0  4429.4    .035       0  4503.8     .07       0
  4892.1     .16       0  5038.1     .07       0    5044     .16       0
  5091.9    .035       0  5111.2     .07       0  5755.8    .035       0
Bank Sta=5038.1,5044
XS Rating Curve= 0 ,0
Exp/Cntr=0.3,0.1

Type RM Length L Ch R = 1 ,33376   ,383,383,383
BEGIN DESCRIPTION:
Alkali Creek Trib 02 35.0
END DESCRIPTION:
XS GIS Cut Line= 5
      1364305.02        6948888.      1365077.45      6949071.29
        1365305.        6949088.      1365444.63      6949032.23
      1365805.01      6948087.97
#Sta/Elev= 30
  3982.8 2037.45  4157.5 2035.64  4239.7 2036.31  4270.6 2035.26  4391.5  2035.6
  4611.1 2033.84  4681.7 2034.04  4697.3 2032.92  4894.7 2031.14  4933.1 2030.72
  4938.1 2028.03  4944.7 2026.76  4974.8 2025.16  5011.3 2020.69  5011.8 2020.19
  5017.2 2020.69  5019.7 2025.94  5043.9 2023.73  5049.3 2029.81  5068.2  2029.2
  5073.5 2027.08  5080.2 2026.44  5100.7  2026.3  5134.1 2030.11  5151.7 2030.72
  5154.2 2031.76  5181.1 2032.43  5507.6 2032.04  6033.1 2037.38  6165.9 2038.13
#Mann= 8 ,-1 , 0
  3982.8     .07       0  4611.1    .035       0  4894.7     .16       0
  5011.3     .07       0  5017.2     .16       0  5100.7    .035       0
  5507.6     .07       0  6033.1    .035       0
#XS Ineff= 2 , 0
       0                  5058.7       0 2029.96
Permanent Ineff=
       F       F
Bank Sta=5011.3,5017.2
XS Rating Curve= 0 ,0
Exp/Cntr=0.3,0.1

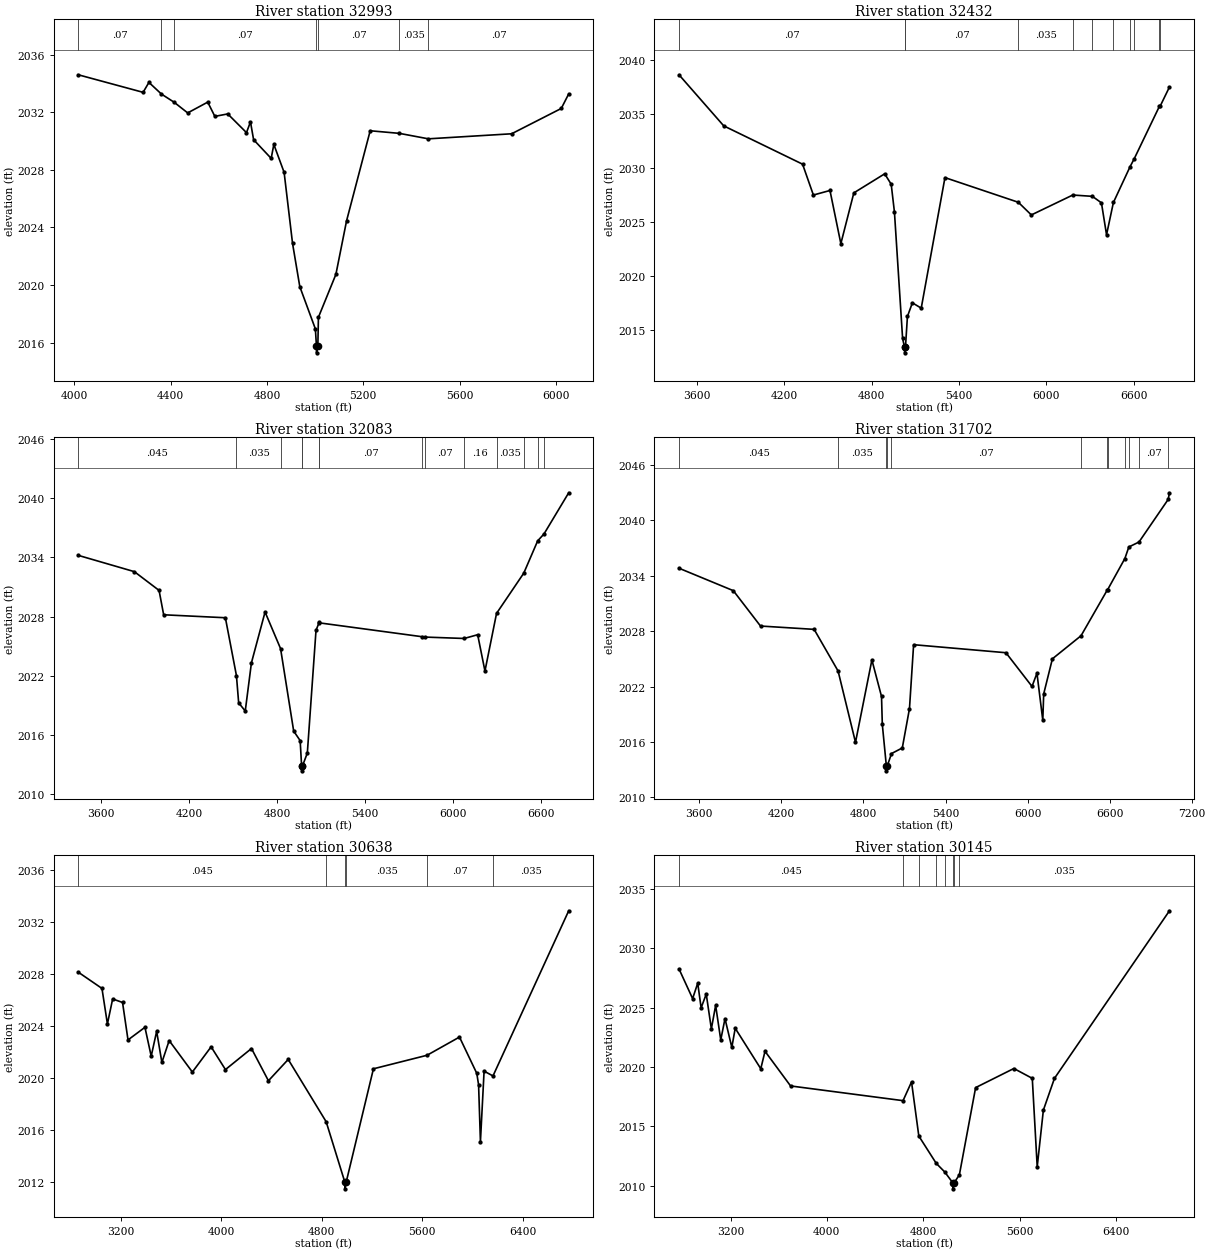
Type RM Length L Ch R = 1 ,32993   ,561,561,561
BEGIN DESCRIPTION:
Alkali Creek Trib 02 34.0
END DESCRIPTION:
XS GIS Cut Line= 4
      1364612.23      6949131.35      1365346.57      6949428.21
      1365760.63      6949261.54        1365955.        6948488.
#Sta/Elev= 30
  4016.7 2034.61  4285.9 2033.39  4310.1 2034.08    4362 2033.27  4414.9  2032.7
    4471 2031.96  4554.2 2032.71  4583.7 2031.72  4637.3 2031.89  4715.1 2030.59
  4731.6 2031.34  4744.6  2030.1  4817.6  2028.8  4828.6 2029.77  4871.3 2027.83
  4906.3 2022.89  4936.4 2019.89  5001.1 2016.95  5005.4 2015.79  5005.8 2015.29
  5011.3 2015.79  5013.7 2017.76  5086.2 2020.74  5130.5 2024.46  5228.6 2030.72
  5349.5 2030.54  5470.1 2030.16  5815.6 2030.51  6021.8 2032.27  6052.7 2033.28
#Mann= 7 ,-1 , 0
  4016.7     .07       0    4362    .035       0  4414.9     .07       0
  5005.4     .07       0  5011.3     .07       0  5349.5    .035       0
  5470.1     .07       0
Bank Sta=5005.4,5011.3
XS Rating Curve= 0 ,0
Exp/Cntr=0.3,0.1

Type RM Length L Ch R = 1 ,32432   ,349,349,349
BEGIN DESCRIPTION:
Alkali Creek Trib 02 33.0
END DESCRIPTION:
XS GIS Cut Line= 4
      1364018.42      6949730.28      1365021.05      6950003.73
       1365807.5      6949607.89      1366889.74      6948642.72
#Sta/Elev= 30
  3476.1 2038.62  3783.5  2033.9  4325.1 2030.36  4399.4 2027.51  4513.4 2027.93
  4588.1 2023.02  4677.4 2027.71  4889.2 2029.47    4934 2028.51  4956.3 2025.94
  5012.4 2014.26  5025.9 2013.43  5026.4 2012.93  5031.9 2013.43  5045.6 2016.29
  5079.5 2017.55  5140.4 2017.06  5303.4 2029.12  5807.5 2026.84  5896.9 2025.67
  6181.5 2027.51  6316.1 2027.39  6378.5 2026.79  6413.6 2023.84  6460.7 2026.82
  6575.7 2030.14  6603.4 2030.85  6776.3 2035.69  6781.6 2035.71  6845.9 2037.49
#Mann= 11 ,-1 , 0
  3476.1     .07       0  5025.9     .07       0  5031.9     .07       0
  5807.5    .035       0  6181.5     .07       0  6316.1     .16       0
  6460.7     .07       0  6575.7    .035       0  6603.4     .07       0
  6776.3    .035       0  6781.6     .07       0
Bank Sta=5025.9,5031.9
XS Rating Curve= 0 ,0
Exp/Cntr=0.3,0.1

Type RM Length L Ch R = 1 ,32083   ,381,381,381
BEGIN DESCRIPTION:
Alkali Creek Trib 02 32.0
END DESCRIPTION:
XS GIS Cut Line= 4
      1364307.49      6949909.97      1365286.67      6950209.46
      1365810.11       6949860.5      1367039.25      6948693.85
#Sta/Elev= 30
  3442.7 2034.21  3825.5 2032.56  3994.3 2030.66  4025.7 2028.19  4446.9 2027.89
  4522.4 2022.03  4537.6 2019.27  4582.6 2018.44  4624.7 2023.32  4717.8 2028.47
  4823.7 2024.76  4913.1 2016.41  4957.4 2015.44  4967.2 2012.88  4967.7 2012.38
  4973.2 2012.88  5006.3 2014.18  5065.6 2026.62  5087.1 2027.41  5089.1 2027.37
  5788.6 2025.97  5811.9 2025.93  6076.8 2025.79    6169 2026.17  6218.7 2022.49
  6297.8 2028.33  6483.7 2032.41  6578.6 2035.68  6621.8 2036.38  6790.4 2040.55
#Mann= 14 ,-1 , 0
  3442.7    .045       0  4522.4    .035       0  4823.7     .07       0
  4967.2     .07       0  4973.2     .07       0  5087.1    .035       0
  5089.1     .07       0  5788.6    .035       0  5811.9     .07       0
  6076.8     .16       0  6297.8    .035       0  6483.7     .07       0
  6578.6    .035       0  6621.8     .07       0
Bank Sta=4967.2,4973.2
XS Rating Curve= 0 ,0
Exp/Cntr=0.3,0.1

Type RM Length L Ch R = 1 ,31702   ,1064,1064,1064
BEGIN DESCRIPTION:
Alkali Creek Trib 02 31.0
END DESCRIPTION:
XS GIS Cut Line= 4
      1364295.34      6949993.31       1365427.3      6950340.53
       1366014.1      6950087.06      1367176.31       6948761.8
#Sta/Elev= 30
  3451.3 2034.82  3848.4 2032.39  4047.2 2028.56  4439.3  2028.2  4614.4 2023.69
  4741.7 2015.97  4861.6 2024.89    4932 2020.93  4937.8  2017.9  4967.5 2013.38
    4968 2012.88  4973.5 2013.38  5004.9 2014.75  5083.9 2015.36  5136.4 2019.62
  5166.6 2026.54  5841.6 2025.67  6032.3 2022.02  6068.4 2023.45  6111.1 2018.36
  6117.7 2021.21  6181.3 2025.01  6390.8 2027.51  6584.1  2032.5  6584.9 2032.49
  6711.2 2035.87  6740.2 2037.12  6814.5 2037.66  7027.8 2042.27  7037.2 2042.99
#Mann= 12 ,-1 , 0
  3451.3    .045       0  4614.4    .035       0  4967.5    .035       0
  4973.5    .035       0  5004.9     .07       0  6390.8    .035       0
  6584.1     .07       0  6584.9    .035       0  6711.2     .07       0
  6740.2    .035       0  6814.5     .07       0  7027.8    .035       0
Bank Sta=4967.5,4973.5
XS Rating Curve= 0 ,0
Exp/Cntr=0.3,0.1

Type RM Length L Ch R = 1 ,30638   ,493,493,493
BEGIN DESCRIPTION:
Alkali Creek Trib 02 30.5
END DESCRIPTION:
XS GIS Cut Line= 3
      1364943.62      6952461.25      1366255.82      6950772.66
      1366944.87      6949147.61
#Sta/Elev= 30
  2861.5 2028.12  3050.2 2026.87  3093.6 2024.14  3135.3 2026.06    3214 2025.79
  3257.5 2022.91  3392.3 2023.88  3442.1 2021.66  3485.5 2023.57  3527.1 2021.18
  3585.1 2022.86  3769.7 2020.44    3919 2022.38    4033 2020.63  4240.3 2022.25
  4375.1 2019.77  4532.6 2021.41  4834.6 2016.62  4983.8 2011.96  4984.3 2011.46
  4993.6 2011.96  5210.8 2020.69  5637.4 2021.73  5895.7 2023.13  6033.4 2020.34
  6047.8 2019.46  6062.5 2015.09  6091.6 2020.51  6162.4 2020.14  6765.1 2032.84
#Mann= 6 ,-1 , 0
  2861.5    .045       0  4834.6    .035       0  4983.8    .035       0
  4993.6    .035       0  5637.4     .07       0  6162.4    .035       0
Bank Sta=4983.8,4993.6
XS Rating Curve= 0 ,0
Exp/Cntr=0.3,0.1

Type RM Length L Ch R = 1 ,30145   ,461,461,461
BEGIN DESCRIPTION:
Alkali Creek Trib 02 30.0
END DESCRIPTION:
XS GIS Cut Line= 3
        1365055.        6952538.        1366655.        6950988.
      1367041.88      6949184.29
#Sta/Elev= 30
  2772.3 2028.27  2885.4 2025.77  2927.8 2027.07  2956.1 2024.99  2998.5 2026.15
    3041 2023.22  3076.5  2025.2  3118.9 2022.29  3154.2 2024.08  3210.8 2021.66
  3239.1 2023.27  3451.3 2019.86  3486.5 2021.33  3698.7 2018.41  4632.6 2017.17
    4703 2018.75  4763.5 2014.19    4908 2011.89  4978.9 2011.16  5046.2 2010.24
  5046.7 2009.74    5056 2010.24  5100.3 2010.92  5235.2 2018.27  5552.8 2019.88
  5705.7 2019.05  5746.6  2011.6  5797.7 2016.37  5889.8 2019.05  6844.7 2033.17
#Mann= 8 ,-1 , 0
  2772.3    .045       0  4632.6    .035       0  4763.5    .045       0
    4908    .035       0  4978.9     .07       0  5046.2     .07       0
    5056     .07       0  5100.3    .035       0
Bank Sta=5046.2,5056
XS Rating Curve= 0 ,0
Exp/Cntr=0.3,0.1