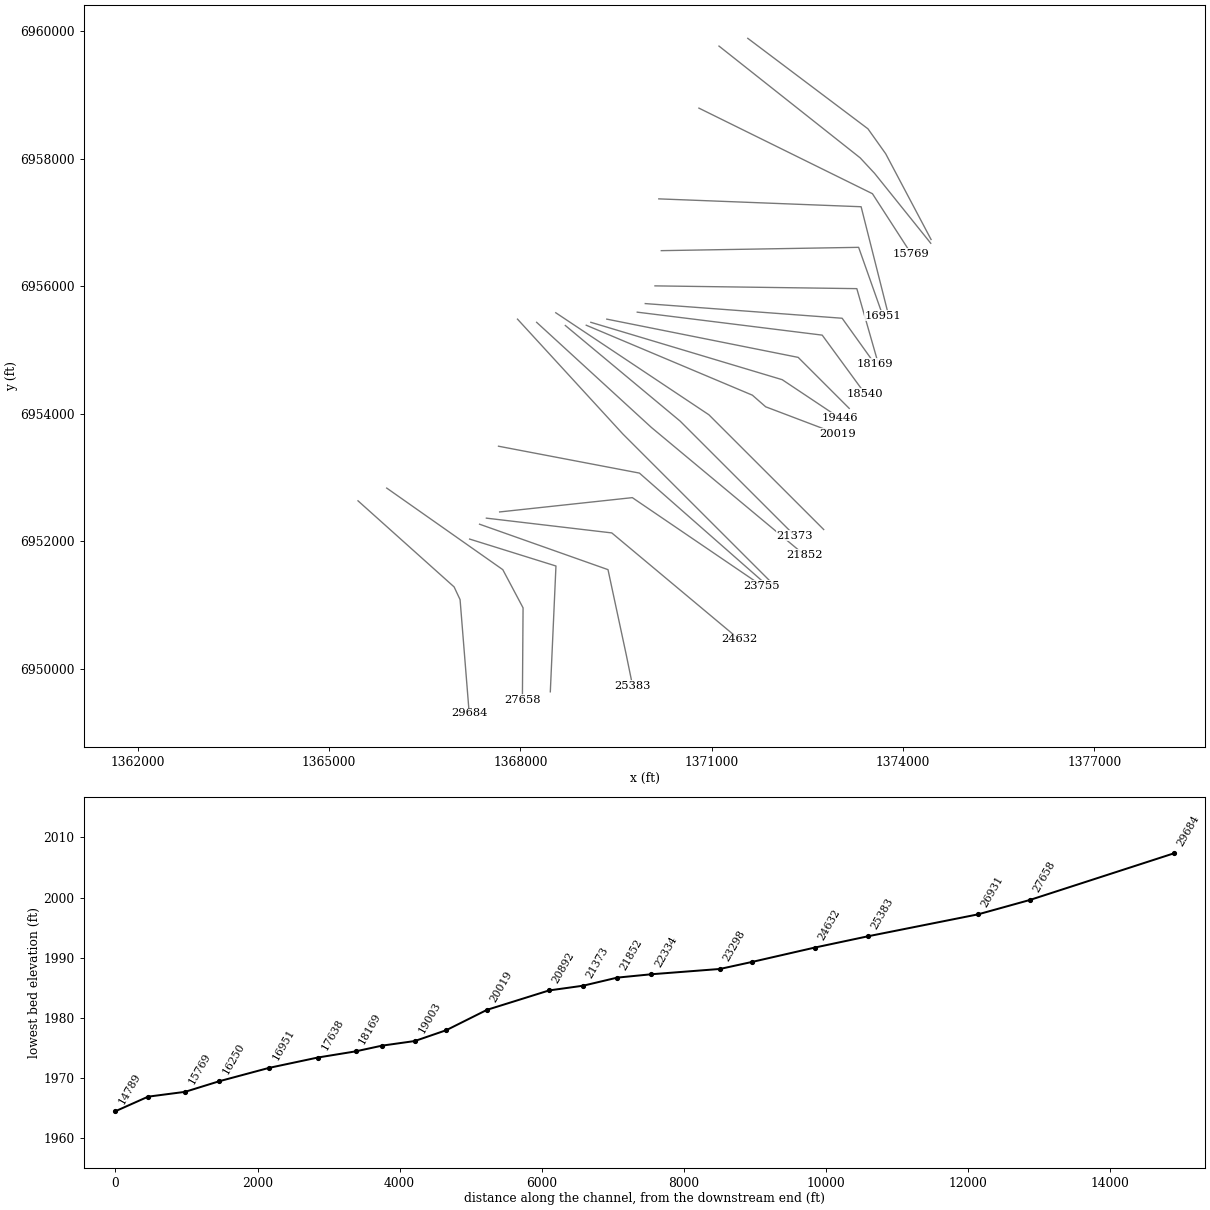
HEC-RAS study Alkali Creek Trib 02.prj: Alkali Creek Trib 02 Base Level Engineering

--- Alkali Creek Trib 02.g01 (geometry) --- (continued)

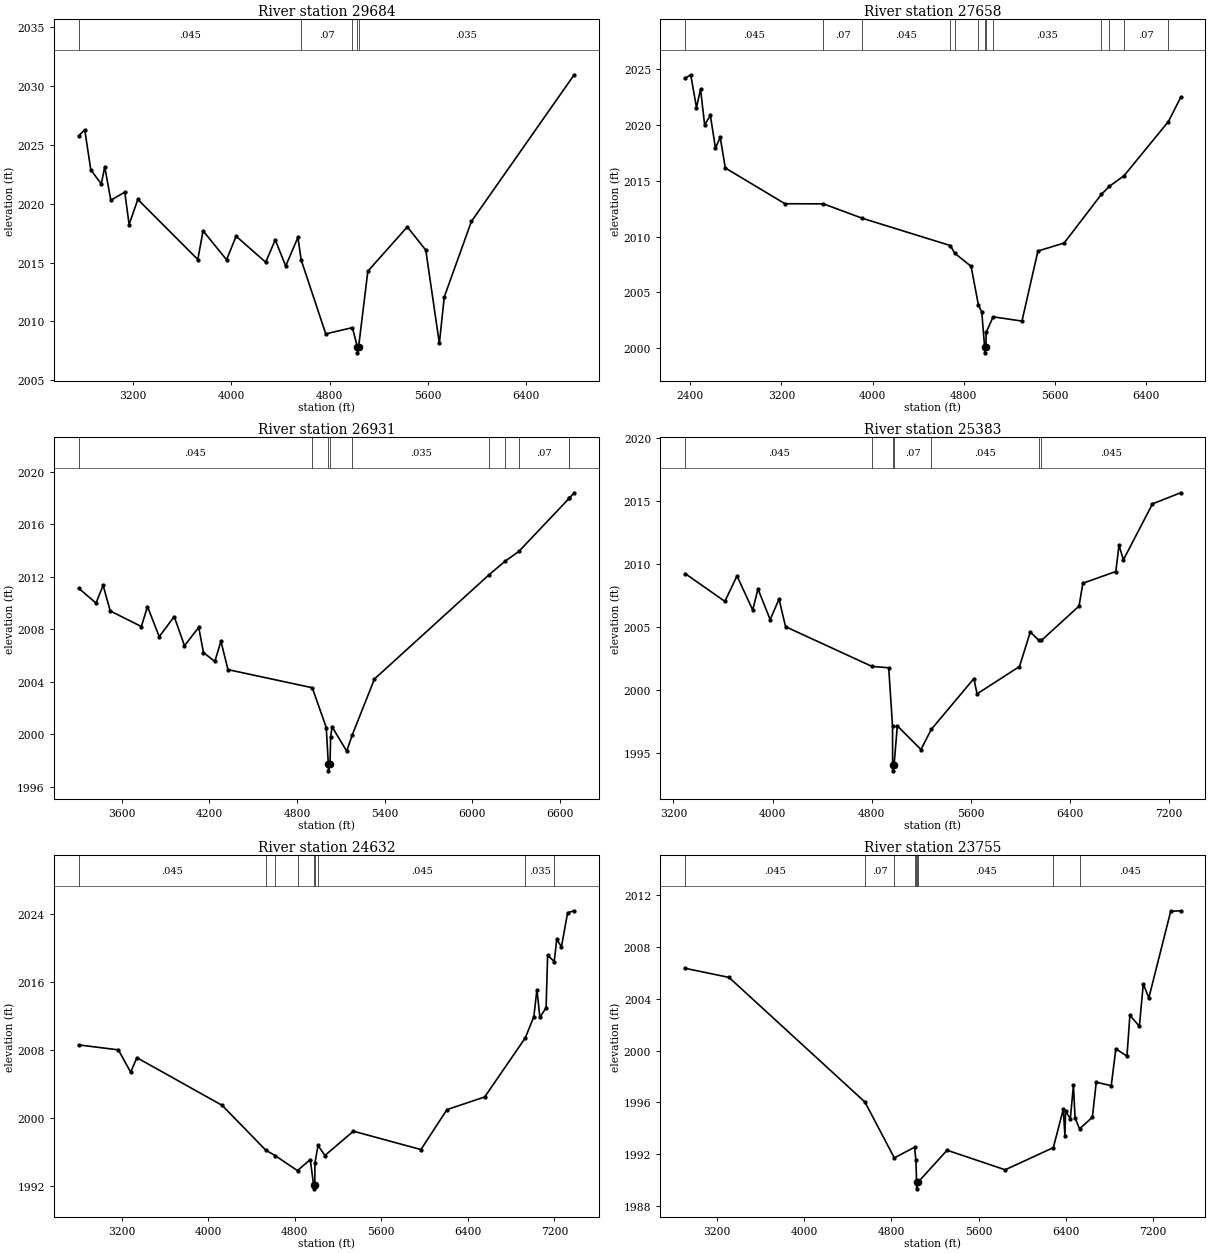
Type RM Length L Ch R = 1 ,29684   ,2026,2026,2026
BEGIN DESCRIPTION:
Alkali Creek Trib 02 29.0
END DESCRIPTION:
XS GIS Cut Line= 4
      1365454.98      6952638.02      1366961.67      6951287.41
        1367055.        6951088.      1367198.13      6949304.03
#Sta/Elev= 30
  2756.3 2025.75    2806 2026.28  2855.4 2022.87  2940.6 2021.68    2969 2023.12
  3018.4 2020.29    3132 2020.98  3167.1 2018.23  3238.2 2020.36  3726.3 2015.26
  3768.9  2017.7  3960.3 2015.24  4038.1 2017.24  4278.8 2015.03  4356.5 2016.93
  4441.8 2014.71  4541.2 2017.14  4567.7 2015.22  4767.7 2008.95  4984.6 2009.48
    5025 2007.84  5025.5 2007.34  5034.9 2007.84  5110.3 2014.27  5431.3 2018.03
  5581.8 2016.06  5692.4 2008.14  5732.2 2012.08    5953 2018.49  6789.6 2030.94
#Mann= 5 ,-1 , 0
  2756.3    .045       0  4567.7     .07       0  4984.6    .035       0
    5025    .035       0  5034.9    .035       0
Bank Sta=5025,5034.9
XS Rating Curve= 0 ,0
Exp/Cntr=0.3,0.1

Type RM Length L Ch R = 1 ,27658   ,727,727,727
BEGIN DESCRIPTION:
Alkali Creek Trib 02 28.0
END DESCRIPTION:
XS GIS Cut Line= 4
      1365904.96      6952838.03      1367724.69      6951558.24
       1368042.4      6950959.28      1368031.98      6949516.62
#Sta/Elev= 30
  2355.7 2024.15    2405 2024.46  2455.5 2021.53  2491.2 2023.17    2527 2019.99
  2577.5 2020.82  2621.9 2017.91  2663.7 2018.87  2708.1 2016.13  3231.7 2012.93
  3568.3 2012.92    3910 2011.63  4681.9 2009.19  4718.7 2008.52  4863.6 2007.33
  4927.3  2003.9  4957.2 2003.24  4982.5  2000.1    4983  1999.6  4993.8  2000.1
  4995.5 2001.42  5056.8 2002.82  5309.7 2002.44  5449.7  2008.7  5679.7 2009.42
  6006.4 2013.77  6076.5 2014.49  6204.5 2015.43  6593.8 2020.28  6701.1 2022.43
#Mann= 13 ,-1 , 0
  2355.7    .045       0  3568.3     .07       0    3910    .045       0
  4681.9     .07       0  4718.7    .045       0  4927.3     .07       0
  4982.5     .07       0  4993.8     .07       0  5056.8    .035       0
  6006.4     .07       0  6076.5    .035       0  6204.5     .07       0
  6593.8    .035       0
Bank Sta=4982.5,4993.8
XS Rating Curve= 0 ,0
Exp/Cntr=0.3,0.1

Type RM Length L Ch R = 1 ,26931   ,1548,1548,1548
BEGIN DESCRIPTION:
Alkali Creek Trib 02 27.0
END DESCRIPTION:
XS GIS Cut Line= 3
      1367204.99        6952038.      1368558.02      6951615.53
      1368469.51      6949642.27
#Sta/Elev= 30
  3305.5 2011.13  3424.5    2010  3473.1 2011.35  3521.9  2009.4    3735 2008.21
  3776.9 2009.73  3857.3 2007.44    3960 2008.97  4030.2 2006.75  4127.7 2008.15
  4160.2 2006.23  4237.9 2005.55  4279.8 2007.09  4327.9 2004.93  4905.1 2003.55
  5000.8 2000.52  5015.1 1997.72  5015.6 1997.22  5026.5 1997.72  5030.8  1999.8
  5040.8 2000.57  5140.9 1998.72  5178.7 1999.95  5331.1 2004.22  6115.9 2012.16
  6225.6 2013.19    6319 2013.93  6664.2 2017.98  6665.6    2018  6698.2  2018.4
#Mann= 10 ,-1 , 0
  3305.5    .045       0  4905.1     .07       0  5015.1     .07       0
  5026.5     .07       0  5178.7    .035       0  6115.9     .07       0
  6225.6    .035       0    6319     .07       0  6664.2    .035       0
  6665.6     .07       0
Bank Sta=5015.1,5026.5
XS Rating Curve= 0 ,0
Exp/Cntr=0.3,0.1

Type RM Length L Ch R = 1 ,25383   ,751,751,751
BEGIN DESCRIPTION:
Alkali Creek Trib 02 26.8
END DESCRIPTION:
XS GIS Cut Line= 4
      1367360.61      6952271.22      1369373.74       6951558.6
      1369658.79      6950228.38      1369759.75      6949735.47
#Sta/Elev= 30
  3294.1 2009.24    3615 2007.03    3713 2009.05  3839.8 2006.34  3882.2 2008.02
  3980.5 2005.58  4051.9 2007.21    4105 2005.02  4801.8 2001.87  4937.3 2001.76
  4968.2 1997.11  4968.9 1994.08  4969.4 1993.58  4980.8 1994.08  5006.7 1997.15
  5197.6 1995.27  5280.8 1996.87  5624.6  2000.9  5650.3 1999.69  5992.7 2001.86
  6079.8  2004.6    6150 2003.93  6169.6 2003.93  6473.4 2006.66  6504.1 2008.47
    6770  2009.4  6795.8 2011.48  6831.3 2010.33  7066.1 2014.77  7293.2 2015.65
#Mann= 7 ,-1 , 0
  3294.1    .045       0  4801.8     .07       0  4968.9     .07       0
  4980.8     .07       0  5280.8    .045       0    6150     .07       0
  6169.6    .045       0
Bank Sta=4968.9,4980.8
XS Rating Curve= 0 ,0
Exp/Cntr=0.3,0.1

Type RM Length L Ch R = 1 ,24632   ,877,877,877
BEGIN DESCRIPTION:
Alkali Creek Trib 02 26.4
END DESCRIPTION:
XS GIS Cut Line= 3
      1367467.52      6952366.23      1369433.13      6952134.64
       1371428.5      6950465.89
#Sta/Elev= 30
  2802.4 2008.63  3169.6 2008.05  3283.2 2005.42  3340.7 2007.13    4129 2001.52
  4530.7 1996.27    4620  1995.6  4825.5 1993.84  4943.5 1995.15  4973.6  1992.2
  4974.1  1991.7  4985.5  1992.2  4986.5 1994.72  5015.1  1996.8  5078.8 1995.62
  5341.7 1998.48  5966.3 1996.32  6207.1 2001.02  6555.8 2002.51  6931.7 2009.47
    7010 2011.96  7038.6 2015.14  7065.9 2011.87  7123.2    2013  7137.5 2019.19
  7198.2 2018.43  7222.1 2021.07    7265 2020.16  7322.3 2024.18  7382.8 2024.41
#Mann= 9 ,-1 , 0
  2802.4    .045       0  4530.7     .07       0    4620    .045       0
  4825.5     .07       0  4973.6     .07       0  4985.5     .07       0
  5015.1    .045       0  6931.7    .035       0  7198.2    .045       0
Bank Sta=4973.6,4985.5
XS Rating Curve= 0 ,0
Exp/Cntr=0.3,0.1

Type RM Length L Ch R = 1 ,23755   ,457,457,457
BEGIN DESCRIPTION:
Alkali Creek Trib 02 26.0
END DESCRIPTION:
XS GIS Cut Line= 3
      1367675.17      6952463.62        1369755.        6952688.
      1371780.97      6951308.93
#Sta/Elev= 30
  2908.1 2006.35  3310.3 2005.65  4556.6 1996.03  4825.9 1991.72  5011.7 1992.54
    5024 1991.53  5030.3 1989.83  5030.8 1989.33  5042.3 1989.83  5309.7 1992.31
  5842.4  1990.8  6283.7 1992.51  6375.1 1995.47  6390.1 1993.42  6396.1 1995.33
  6439.5 1994.74    6468 1997.32  6482.9 1994.81  6524.2 1993.96  6641.5 1994.85
  6677.4 1997.56  6814.5 1997.29    6857 2000.14  6958.7 1999.57  6985.7 2002.73
  7072.5 2001.87  7108.4 2005.14  7159.3 2004.07  7359.8 2010.75  7450.8 2010.79
#Mann= 9 ,-1 , 0
  2908.1    .045       0  4556.6     .07       0  4825.9    .045       0
  5011.7     .07       0    5024    .045       0  5030.3    .045       0
  5042.3    .045       0  6283.7    .035       0  6524.2    .045       0
Bank Sta=5030.3,5042.3
XS Rating Curve= 0 ,0
Exp/Cntr=0.3,0.1

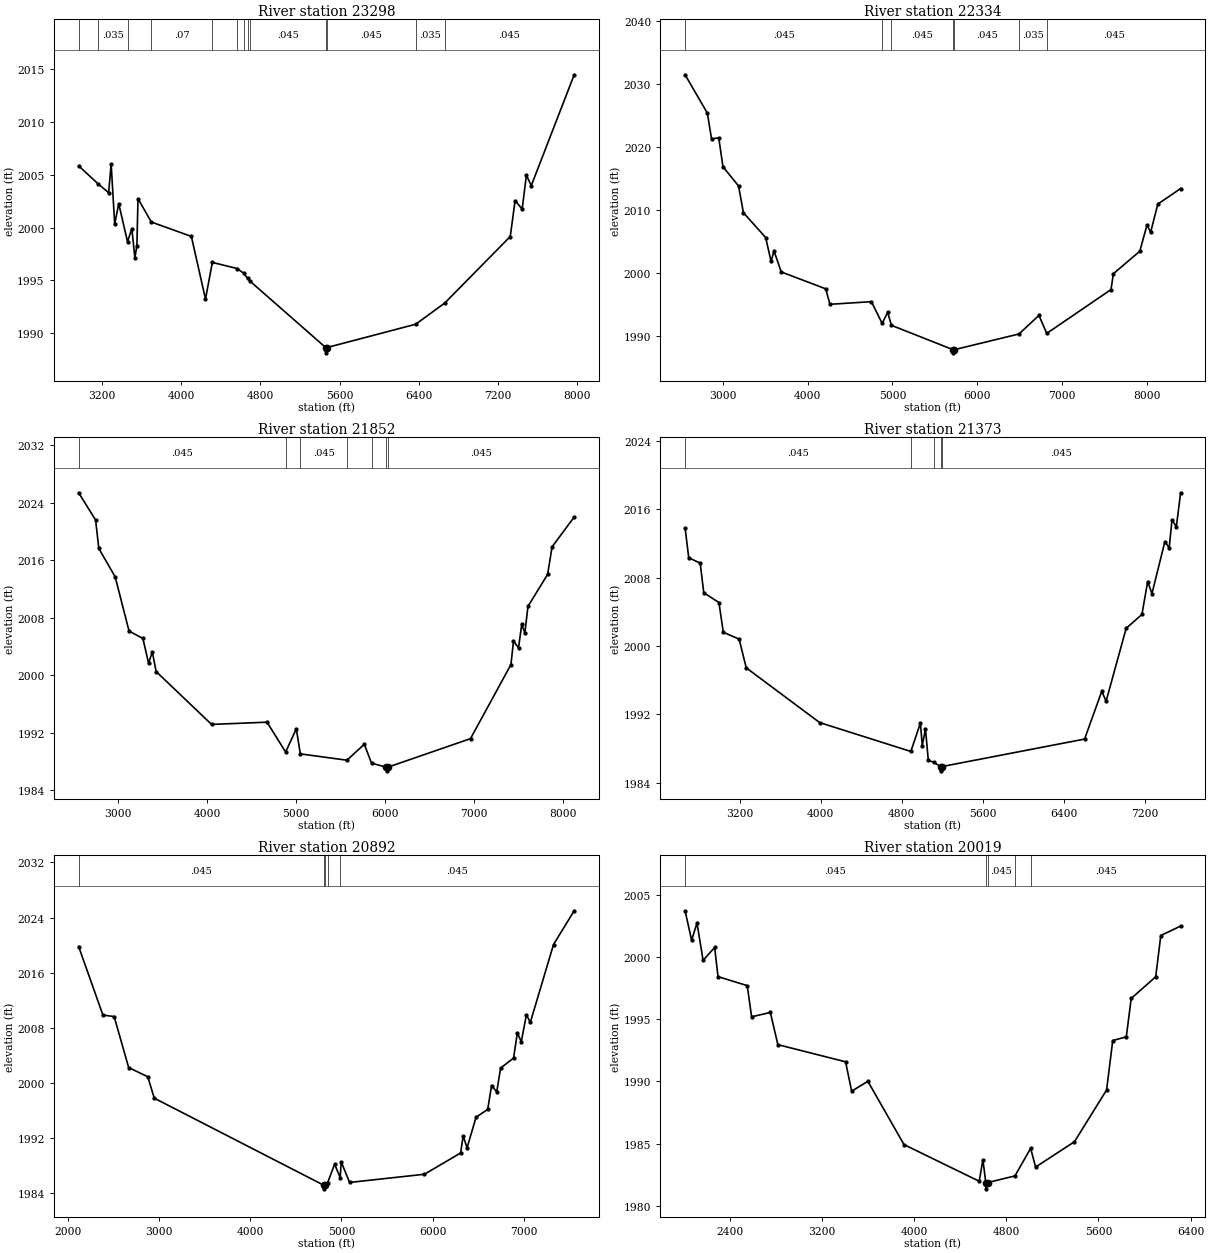
Type RM Length L Ch R = 1 ,23298   ,964,964,964
BEGIN DESCRIPTION:
Alkali Creek Trib 02 25.5
END DESCRIPTION:
XS GIS Cut Line= 3
      1367657.54      6953494.55      1369866.64      6953072.92
      1371933.25      6951255.72
#Sta/Elev= 30
  2966.5 2005.85  3164.8 2004.13  3269.3 2003.31  3294.8 2006.03  3330.4 2000.32
  3371.1 2002.28  3459.8 1998.66  3503.3  1999.9    3534 1997.17  3554.4 1998.26
  3565.6 2002.74  3700.6 2000.53  4104.1 1999.17  4246.7 1993.24    4316 1996.71
  4565.7 1996.13  4631.5 1995.69  4672.9  1995.2  4694.2 1994.95  5460.2 1988.65
  5460.7 1988.15  5472.3 1988.65  6368.4 1990.86  6660.9 1992.86  7322.1 1999.16
  7371.5 2002.56  7442.6 2001.76  7485.3 2004.96  7534.7 2003.98  7967.4 2014.47
#Mann= 13 ,-1 , 0
  2966.5    .045       0  3164.8    .035       0  3459.8    .045       0
  3700.6     .07       0    4316    .045       0  4565.7     .07       0
  4631.5    .045       0  4672.9     .07       0  4694.2    .045       0
  5460.2    .045       0  5472.3    .045       0  6368.4    .035       0
  6660.9    .045       0
Bank Sta=5460.2,5472.3
XS Rating Curve= 0 ,0
Exp/Cntr=0.3,0.1

Type RM Length L Ch R = 1 ,22334   ,482,482,482
BEGIN DESCRIPTION:
Alkali Creek Trib 02 25.0
END DESCRIPTION:
XS GIS Cut Line= 3
      1367954.99      6955488.01        1369605.        6953688.
      1372004.97      6951288.03
#Sta/Elev= 30
  2557.6 2031.44  2819.4 2025.36  2869.3 2021.25  2953.8 2021.43  3003.7 2016.83
  3187.5 2013.77  3244.2 2009.53  3506.3 2005.59  3569.8 2001.81  3604.9 2003.44
    3690 2000.12  4213.5 1997.44  4263.5 1994.98  4751.9  1995.4  4878.4 1991.95
    4943 1993.71  4987.5 1991.64  5713.9 1987.77  5714.4 1987.27  5727.5 1987.77
  6490.5 1990.27  6724.8 1993.22  6816.8 1990.36  7573.3 1997.32  7601.6 1999.84
  7912.7 2003.41  7997.6  2007.6    8040 2006.42  8124.8  2010.9  8393.5 2013.37
#Mann= 7 ,-1 , 0
  2557.6    .045       0  4878.4    .035       0  4987.5    .045       0
  5713.9    .045       0  5727.5    .045       0  6490.5    .035       0
  6816.8    .045       0
Bank Sta=5713.9,5727.5
XS Rating Curve= 0 ,0
Exp/Cntr=0.3,0.1

Type RM Length L Ch R = 1 ,21852   ,479,479,479
BEGIN DESCRIPTION:
Alkali Creek Trib 02 24.0
END DESCRIPTION:
XS GIS Cut Line= 3
      1368255.04      6955437.97        1370055.        6953788.
      1372455.02      6951787.98
#Sta/Elev= 30
  2557.6  2025.4  2748.4 2021.61  2784.2 2017.65  2967.9 2013.71  3123.9 2006.16
  3279.3 2005.13  3343.4 2001.69  3385.4 2003.26  3427.9 2000.53  4050.7 1993.17
  4673.8 1993.48  4882.3 1989.33  5002.6 1992.56  5047.7 1989.07  5570.8 1988.19
  5766.7 1990.41  5847.1 1987.78  6015.1 1987.21  6015.6 1986.71  6028.7 1987.21
  6959.1 1991.19  7413.4  2001.5    7442 2004.75  7498.7 2003.84  7534.5 2007.08
  7569.6  2005.9  7604.7  2009.6  7824.7 2014.03  7875.5 2017.88  8123.5 2022.02
#Mann= 7 ,-1 , 0
  2557.6    .045       0  4882.3    .035       0  5047.7    .045       0
  5570.8    .035       0  5847.1    .045       0  6015.1    .035       0
  6028.7    .045       0
Bank Sta=6015.1,6028.7
XS Rating Curve= 0 ,0
Exp/Cntr=0.3,0.1

Type RM Length L Ch R = 1 ,21373   ,481,481,481
BEGIN DESCRIPTION:
Alkali Creek Trib 02 23.0
END DESCRIPTION:
XS GIS Cut Line= 3
        1368705.        6955388.        1370505.        6953888.
      1372305.03      6952087.97
#Sta/Elev= 30
  2661.7 2013.83  2697.5 2010.32  2810.7 2009.69  2845.9 2006.22  2995.6 2005.08
  3038.5  2001.6  3194.8 2000.79    3265 1997.43  3989.4 1991.02  4888.6 1987.64
  4983.3 1990.96  5001.5 1988.33  5033.1 1990.26  5061.3 1986.59  5115.1 1986.37
  5181.8 1985.87  5182.3 1985.37  5195.4 1985.87  6602.8 1989.09  6772.5 1994.69
    6815 1993.52    7013 2002.06  7168.5 2003.68  7225.1 2007.53  7267.5 2006.12
  7394.8 2012.21  7437.2 2011.47  7465.5 2014.77  7507.9 2013.96  7550.4 2017.93
#Mann= 5 ,-1 , 0
  2661.7    .045       0  4888.6    .035       0  5115.1    .045       0
  5181.8    .035       0  5195.4    .045       0
Bank Sta=5181.8,5195.4
XS Rating Curve= 0 ,0
Exp/Cntr=0.3,0.1

Type RM Length L Ch R = 1 ,20892   ,873,873,873
BEGIN DESCRIPTION:
Alkali Creek Trib 02 22.0
END DESCRIPTION:
XS GIS Cut Line= 3
        1368555.        6955588.        1370955.        6953988.
      1372754.98      6952188.02
#Sta/Elev= 30
  2120.7 2019.79  2386.6 2009.83  2509.8 2009.61    2669  2002.2  2877.9 2000.87
    2950 1997.75  4810.5 1985.08    4811 1984.58  4824.1 1985.08  4849.4 1985.48
  4925.5 1988.16  4987.3 1986.21  4997.6  1988.5    5090 1985.51  5910.2  1986.7
  6306.2 1989.79  6334.5 1992.27  6376.9 1990.54  6475.9 1994.99  6603.2 1996.12
  6645.6 1999.59  6702.2 1998.66  6744.6 2002.13    6886 2003.57  6928.5 2007.25
  6970.9 2005.94  7027.5 2009.89  7069.9 2008.75  7324.4 2020.08  7550.7 2024.98
#Mann= 5 ,-1 , 0
  2120.7    .045       0  4810.5    .045       0  4824.1    .045       0
  4849.4    .035       0  4987.3    .045       0
Bank Sta=4810.5,4824.1
XS Rating Curve= 0 ,0
Exp/Cntr=0.3,0.1

Type RM Length L Ch R = 1 ,20019   ,573,573,573
BEGIN DESCRIPTION:
Alkali Creek Trib 02 21.5
END DESCRIPTION:
XS GIS Cut Line= 4
      1369032.96      6955392.32      1371637.02      6954295.22
      1371845.35      6954112.93      1372965.99      6953687.59
#Sta/Elev= 30
    2012 2003.73  2068.5 2001.36  2115.3 2002.74  2168.2 1999.74  2268.5 2000.78
  2297.7 1998.43  2551.2 1997.71  2589.3  1995.2  2751.9 1995.55  2817.2 1992.96
  3404.8 1991.58  3457.7 1989.22  3598.5 1990.01    3912 1984.92  4564.9 1981.97
  4596.8  1983.7  4621.9 1981.86  4622.4 1981.36  4636.8 1981.86  4874.8  1982.4
  5011.5 1984.62    5054 1983.11  5391.5 1985.15  5670.4 1989.31  5723.9 1993.29
  5841.5 1993.59  5884.3 1996.68  6096.8 1998.42    6141 2001.74  6313.2  2002.5
#Mann= 5 ,-1 , 0
    2012    .045       0  4621.9    .035       0  4636.8    .045       0
  4874.8    .035       0  5011.5    .045       0
Bank Sta=4621.9,4636.8
XS Rating Curve= 0 ,0
Exp/Cntr=0.3,0.1

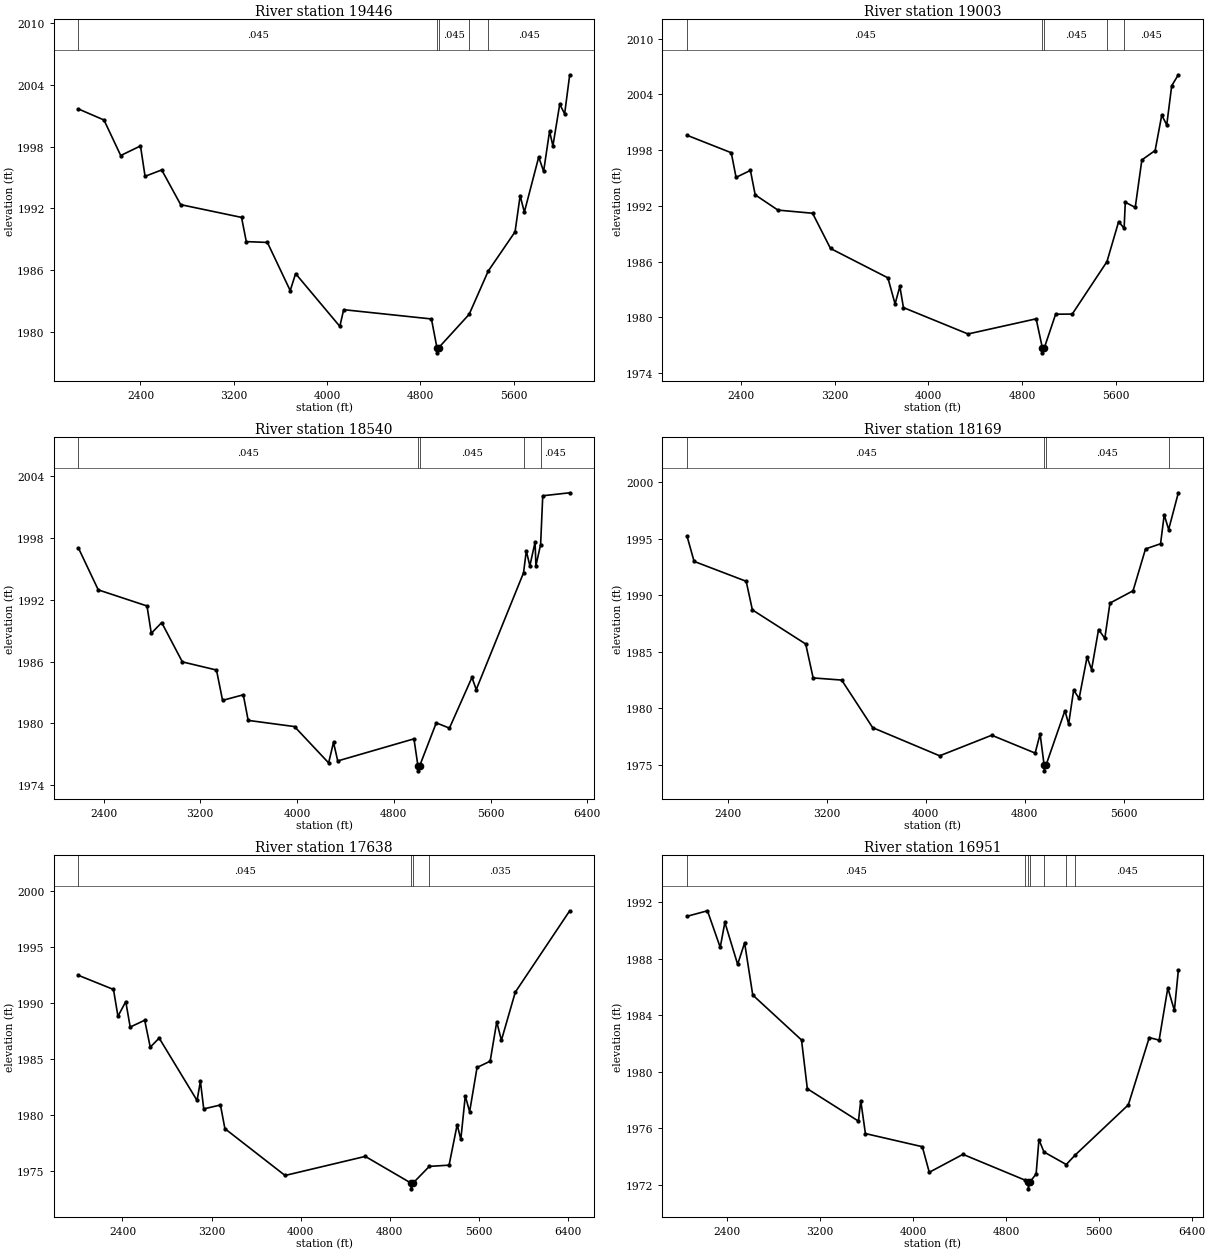
Type RM Length L Ch R = 1 ,19446   ,443,443,443
BEGIN DESCRIPTION:
Alkali Creek Trib 02 21.0
END DESCRIPTION:
XS GIS Cut Line= 3
      1369105.02      6955437.99        1372105.        6954538.
      1373004.97      6953938.02
#Sta/Elev= 30
  1867.7 2001.66  2086.9 2000.59  2230.5 1997.14  2400.1 1998.07  2439.3 1995.12
    2582 1995.74  2744.7 1992.37  3266.7 1991.13  3307.6 1988.78  3488.5  1988.7
  3684.3 1984.02  3730.4 1985.67  4109.7 1980.55  4142.8 1982.17  4895.4 1981.27
  4942.7 1978.48  4943.2 1977.98  4957.7 1978.48  5218.9 1981.72  5382.5 1985.92
  5612.7 1989.73  5656.3 1993.24  5692.3 1991.64  5815.5 1996.99  5857.6  1995.6
  5908.7 1999.51  5937.2 1998.07  5995.8 2002.12  6037.9 2001.19  6081.4 2004.98
#Mann= 5 ,-1 , 0
  1867.7    .045       0  4942.7    .045       0  4957.7    .045       0
  5218.9    .035       0  5382.5    .045       0
Bank Sta=4942.7,4957.7
XS Rating Curve= 0 ,0
Exp/Cntr=0.3,0.1

Type RM Length L Ch R = 1 ,19003   ,463,463,463
BEGIN DESCRIPTION:
Alkali Creek Trib 02 20.0
END DESCRIPTION:
XS GIS Cut Line= 3
      1369355.03      6955487.99        1372355.        6954888.
      1373154.97      6954088.03
#Sta/Elev= 30
  1940.6 1999.59  2317.9 1997.71  2358.7 1995.06  2481.1 1995.81  2521.9 1993.18
  2715.6 1991.54  3011.4  1991.2  3164.3 1987.41  3653.8 1984.25    3715 1981.44
  3755.8 1983.33  3786.4 1981.05  4337.1 1978.21  4918.4 1979.84  4972.1 1976.68
  4972.6 1976.18  4987.1 1976.68  5084.8 1980.34  5226.3 1980.35  5522.3 1985.99
  5622.2  1990.3  5668.8 1989.58  5678.8 1992.38  5763.7 1991.83  5820.2 1996.94
  5933.4 1997.95  5989.9 2001.76  6032.4  2000.7  6074.8 2004.92  6131.3  2006.1
#Mann= 5 ,-1 , 0
  1940.6    .045       0  4972.1    .045       0  4987.1    .045       0
  5522.3    .035       0  5668.8    .045       0
Bank Sta=4972.1,4987.1
XS Rating Curve= 0 ,0
Exp/Cntr=0.3,0.1

Type RM Length L Ch R = 1 ,18540   ,371,371,371
BEGIN DESCRIPTION:
Alkali Creek Trib 02 19.0
END DESCRIPTION:
XS GIS Cut Line= 3
      1369832.38       6955597.3      1372731.64      6955237.06
      1373404.38      6954316.92
#Sta/Elev= 30
  2192.4 1997.01  2356.3 1992.95  2759.3 1991.39  2794.8 1988.74  2880.7 1989.78
  3051.6 1985.97  3333.7 1985.18  3384.1 1982.24  3555.4 1982.78  3595.7  1980.3
  3978.7  1979.7  4260.8 1976.18  4301.1 1978.17  4336.1 1976.37  4966.2 1978.51
  4998.9 1975.91  4999.4 1975.41    5014 1975.91  5150.6 1980.06  5259.5 1979.55
  5445.6 1984.46  5481.1 1983.29    5872  1994.6    5895 1996.73  5924.3 1995.27
  5967.5 1997.58  5974.5  1995.3  6013.3 1997.34  6030.9 2002.07  6253.8 2002.36
#Mann= 5 ,-1 , 0
  2192.4    .045       0  4998.9    .045       0    5014    .045       0
    5872    .035       0  6013.3    .045       0
Bank Sta=4998.9,5014
XS Rating Curve= 0 ,0
Exp/Cntr=0.3,0.1

Type RM Length L Ch R = 1 ,18169   ,531,531,531
BEGIN DESCRIPTION:
Alkali Creek Trib 02 18.0
END DESCRIPTION:
XS GIS Cut Line= 3
      1369958.18      6955731.85      1373044.14      6955501.82
        1373555.      6954788.01
#Sta/Elev= 30
    2069 1995.22    2126 1992.99  2547.1 1991.23  2597.3  1988.7  3028.5 1985.68
  3088.6 1982.68  3319.3 1982.49    3570 1978.28  4111.5 1975.79  4532.6 1977.61
  4883.6 1976.03  4923.7 1977.72  4956.3 1974.96  4956.8 1974.46  4971.4 1974.96
  5124.3 1979.78  5154.4 1978.61  5194.9  1981.6  5239.1 1980.87  5303.5 1984.53
  5339.8 1983.42  5396.3 1986.96  5446.7 1986.18  5488.5  1989.3  5675.2 1990.39
  5775.9 1994.09  5897.6 1994.55  5927.1 1997.11    5963 1995.81  6041.3 1999.06
#Mann= 4 ,-1 , 0
    2069    .045       0  4956.3    .045       0  4971.4    .045       0
    5963    .035       0
Bank Sta=4956.3,4971.4
XS Rating Curve= 0 ,0
Exp/Cntr=0.3,0.1

Type RM Length L Ch R = 1 ,17638   ,687,687,687
BEGIN DESCRIPTION:
Alkali Creek Trib 02 17.0
END DESCRIPTION:
XS GIS Cut Line= 3
      1370110.14      6956009.63      1373274.17      6955966.23
      1373617.04      6954768.36
#Sta/Elev= 30
  2004.5 1992.46  2319.4  1991.2  2359.4 1988.81  2429.4 1990.12  2469.4 1987.85
  2599.4 1988.46  2649.4 1986.06  2729.4 1986.87  3069.5 1981.31  3099.5 1983.02
  3129.5 1980.56  3279.5 1980.91  3319.5  1978.8  3859.5 1974.63  4579.6 1976.33
  4992.1 1973.94  4992.6 1973.44  5007.2 1973.94  5154.5 1975.44  5331.8 1975.55
  5404.5 1979.15  5437.4 1977.85  5477.3 1981.72  5516.3 1980.31    5583 1984.25
  5700.7 1984.81  5759.9 1988.32  5801.5 1986.67  5926.3 1990.96  6414.8 1998.21
#Mann= 4 ,-1 , 0
  2004.5    .045       0  4992.1    .045       0  5007.2    .045       0
  5154.5    .035       0
Bank Sta=4992.1,5007.2
XS Rating Curve= 0 ,0
Exp/Cntr=0.3,0.1

Type RM Length L Ch R = 1 ,16951   ,701,701,701
BEGIN DESCRIPTION:
Alkali Creek Trib 02 16.7
END DESCRIPTION:
XS GIS Cut Line= 3
      1370209.22      6956562.09      1373302.58      6956614.08
      1373681.78      6955541.96
#Sta/Elev= 30
    2054    1991  2229.8 1991.39  2339.8  1988.8  2379.8 1990.57  2489.8  1987.6
  2549.8 1989.12  2619.9 1985.43  3039.9 1982.25  3089.9  1978.8    3530 1976.51
    3550 1977.96    3590 1975.63  4080.1  1974.7  4140.1 1972.89  4430.1 1974.16
  4960.7 1972.35  4992.6 1972.22  4993.1 1971.72  5007.8 1972.22  5060.2 1972.77
  5084.5  1975.2  5127.6 1974.33  5319.9 1973.44  5395.2  1974.1  5854.3 1977.66
  6034.5 1982.42  6119.5 1982.24  6194.4 1985.93  6250.9 1984.34    6285 1987.17
#Mann= 7 ,-1 , 0
    2054    .045       0  4960.7    .035       0  4992.6    .035       0
  5007.8    .035       0  5127.6    .045       0  5319.9    .035       0
  5395.2    .045       0
Bank Sta=4992.6,5007.8
XS Rating Curve= 0 ,0
Exp/Cntr=0.3,0.1

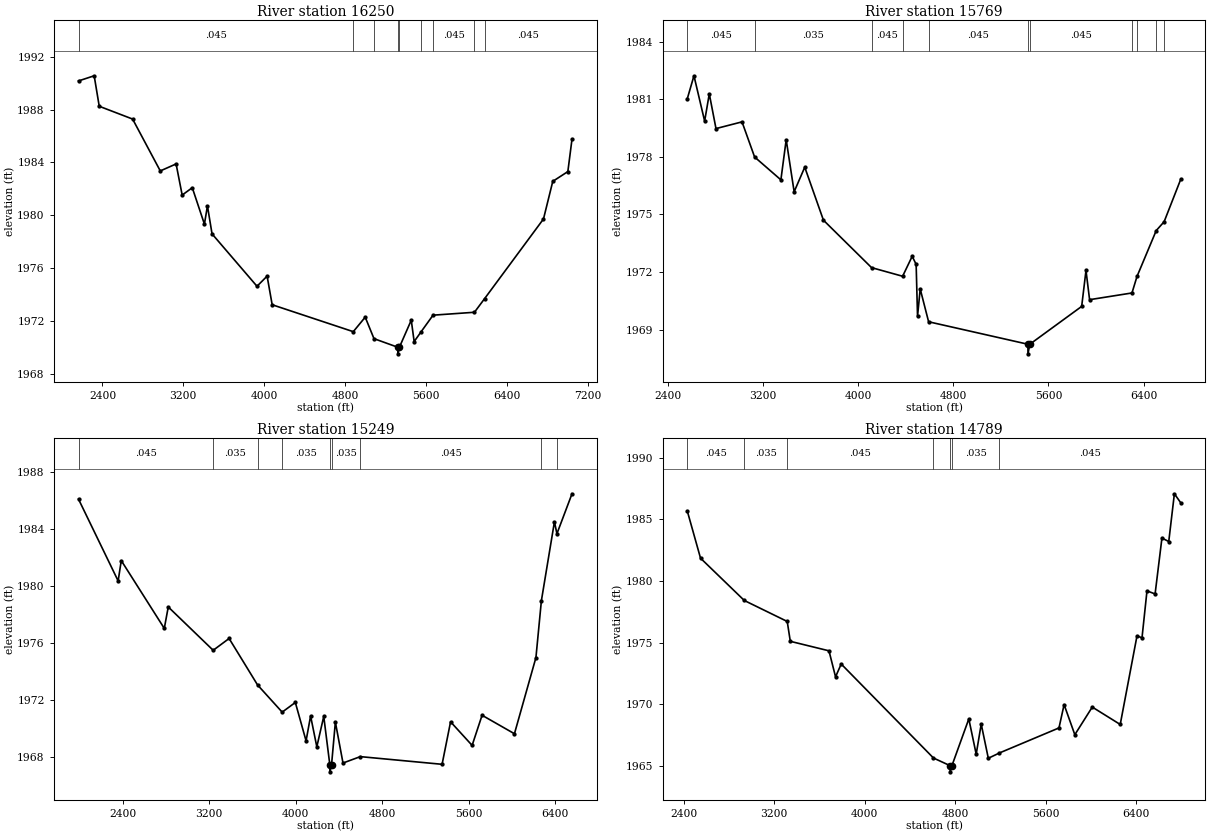
Type RM Length L Ch R = 1 ,16250   ,481,481,481
BEGIN DESCRIPTION:
Alkali Creek Trib 02 16.3
END DESCRIPTION:
XS GIS Cut Line= 3
      1370170.22      6957374.42      1373341.57      6957250.95
      1373760.14      6955593.54
#Sta/Elev= 30
  2163.3 1990.18  2318.2 1990.57  2368.2 1988.26  2698.5 1987.29  2972.3 1983.36
  3128.8 1983.89  3188.9 1981.53  3288.9 1982.09    3409 1979.33    3439 1980.71
  3484.5 1978.59  3929.4 1974.62  4029.5 1975.39  4079.5 1973.22  4882.2 1971.18
  5000.2 1972.28    5087 1970.65  5322.5    1970    5323  1969.5  5338.5    1970
  5455.9 1972.05  5484.5 1970.43    5554 1971.18  5671.4 1972.43  6081.1 1972.65
  6181.3 1973.68  6764.3 1979.72  6856.2 1982.57  7005.4 1983.31  7046.5 1985.77
#Mann= 9 ,-1 , 0
  2163.3    .045       0  4882.2    .035       0    5087    .045       0
  5322.5    .035       0  5338.5    .045       0    5554    .035       0
  5671.4    .045       0  6081.1    .035       0  6181.3    .045       0
Bank Sta=5322.5,5338.5
XS Rating Curve= 0 ,0
Exp/Cntr=0.3,0.1

Type RM Length L Ch R = 1 ,15769   ,520,520,520
BEGIN DESCRIPTION:
Alkali Creek Trib 02 16.5
END DESCRIPTION:
XS GIS Cut Line= 3
      1370798.95      6958797.65      1373518.82      6957455.54
      1374124.55      6956517.24
#Sta/Elev= 30
  2562.3 1981.02  2618.6 1982.22  2708.4 1979.86  2747.5 1981.28  2803.8 1979.47
  3022.7 1979.82  3128.6 1977.99  3349.6  1976.8  3394.2 1978.89  3461.1 1976.18
  3550.3 1977.46  3707.4  1974.7    4112 1972.23  4373.3 1971.78  4453.8 1972.82
    4487  1972.4  4498.7  1969.7  4521.2 1971.12  4591.8 1969.41  5426.9 1968.24
  5427.4 1967.74  5442.9 1968.24    5879 1970.21  5915.3 1972.08  5945.6 1970.56
    6302 1970.91  6344.3 1971.77    6506 1974.16  6572.4 1974.62  6712.1 1976.83
#Mann= 11 ,-1 , 0
  2562.3    .045       0  3128.6    .035       0    4112    .045       0
  4373.3    .035       0  4591.8    .045       0  5426.9    .045       0
  5442.9    .045       0    6302     .07       0  6344.3    .045       0
    6506     .07       0  6572.4    .035       0
Bank Sta=5426.9,5442.9
XS Rating Curve= 0 ,0
Exp/Cntr=0.3,0.1

Type RM Length L Ch R = 1 ,15249   ,460,460,460
BEGIN DESCRIPTION:
Alkali Creek Trib 02 16.0
END DESCRIPTION:
XS GIS Cut Line= 4
      1371113.56      6959770.93      1373327.12      6958017.44
      1373552.82      6957774.39      1374433.04      6956678.02
#Sta/Elev= 30
  1993.5 1986.12  2359.7 1980.37  2388.6  1981.8  2786.3 1977.03  2822.9 1978.54
  3238.2 1975.49  3385.4 1976.32  3648.6 1973.05  3876.1 1971.14  3997.6 1971.82
  4096.9 1969.12  4138.6 1970.87  4196.2  1968.7  4260.3 1970.84  4316.4 1967.44
  4316.9 1966.94  4332.4 1967.44  4367.7 1970.44  4438.2 1967.56  4598.2 1968.01
  5354.2 1967.47  5432.6 1970.46  5631.8  1968.8  5723.8 1970.92    6023 1969.62
  6221.7 1974.98  6272.1 1978.98  6392.7 1984.53  6415.7 1983.69  6555.1  1986.5
#Mann= 9 ,-1 , 0
  1993.5    .045       0  3238.2    .035       0  3648.6    .045       0
  3876.1    .035       0  4316.4    .045       0  4332.4    .035       0
  4598.2    .045       0  6272.1     .07       0  6415.7    .045       0
Bank Sta=4316.4,4332.4
XS Rating Curve= 0 ,0
Exp/Cntr=0.3,0.1

Type RM Length L Ch R = 1 ,14789   ,397,397,397
BEGIN DESCRIPTION:
Alkali Creek Trib 02 15.0
END DESCRIPTION:
XS GIS Cut Line= 4
        1371565.      6959892.42      1373448.65      6958473.17
      1373726.43      6958082.55      1374438.25      6956737.03
#Sta/Elev= 30
    2433 1985.67  2550.2 1981.84  2936.9 1978.41  3316.2 1976.71  3343.4  1975.1
  3685.1 1974.33  3743.1 1972.22  3793.1 1973.26  4608.3 1965.64  4755.2 1965.02
  4755.7 1964.52  4771.4 1965.02  4920.6 1968.81  4985.8 1965.95  5030.1 1968.39
  5092.8 1965.62    5191 1966.05  5717.2 1968.08  5762.4 1969.97  5857.2 1967.53
  6011.3 1969.77  6258.3 1968.36  6406.7 1975.55  6450.7 1975.38  6494.7 1979.19
  6566.4 1978.94  6626.8 1983.47  6687.1 1983.19  6736.8 1987.06    6793 1986.33
#Mann= 7 ,-1 , 0
    2433    .045       0  2936.9    .035       0  3316.2    .045       0
  4608.3    .035       0  4755.2    .035       0  4771.4    .035       0
    5191    .045       0
Bank Sta=4755.2,4771.4
XS Rating Curve= 0 ,0
Exp/Cntr=0.3,0.1