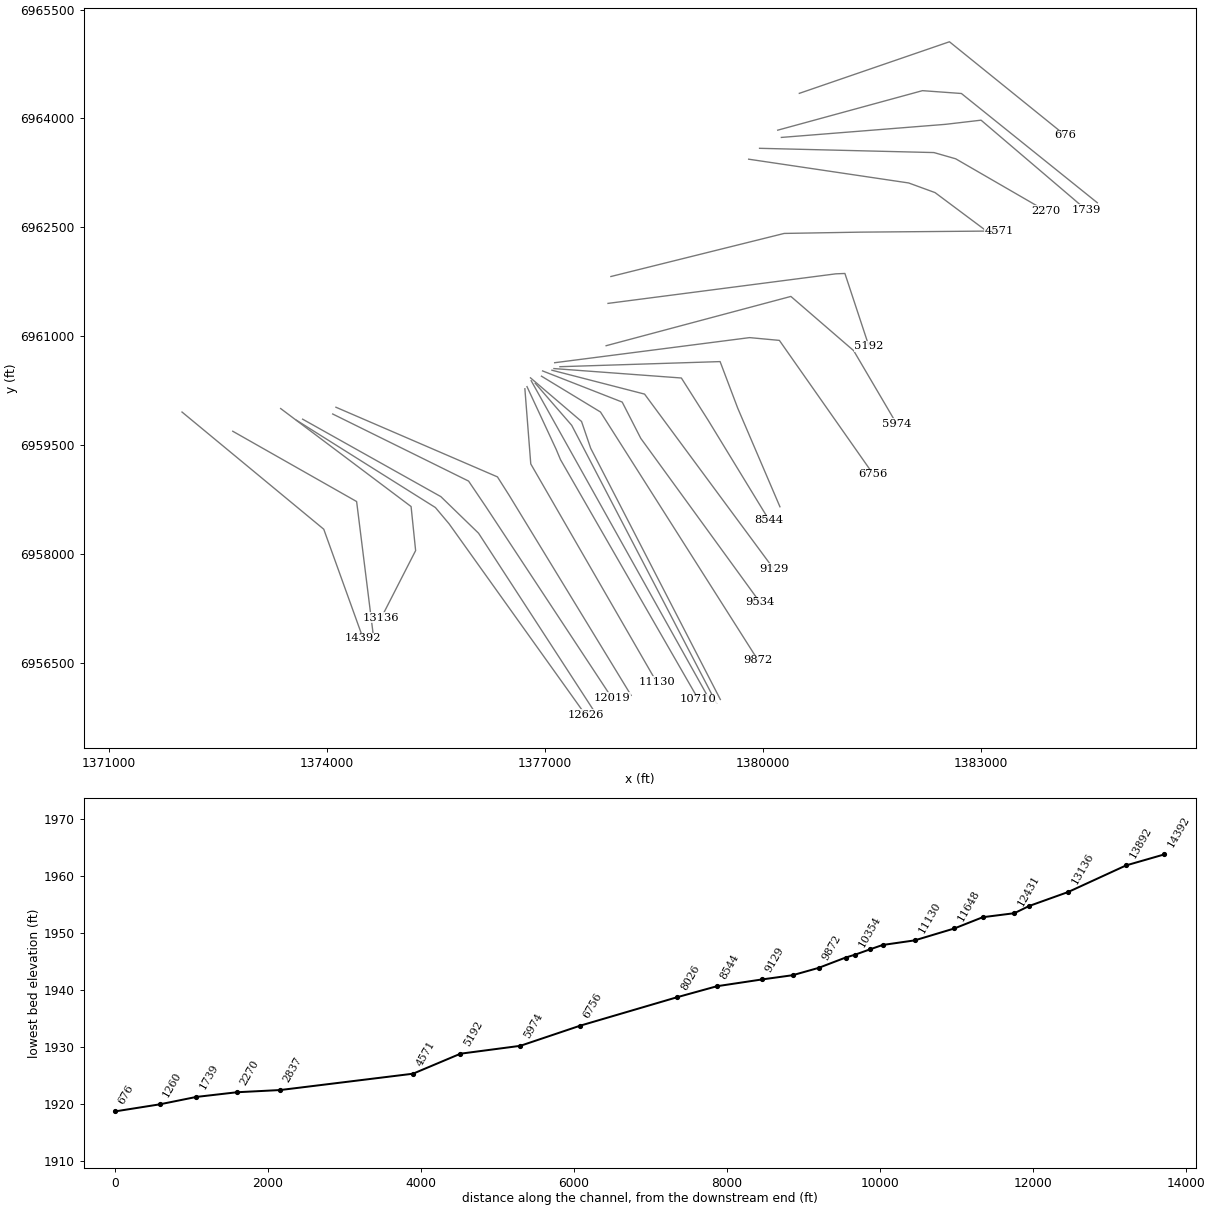
HEC-RAS study Alkali Creek Trib 02.prj: Alkali Creek Trib 02 Base Level Engineering

--- Alkali Creek Trib 02.g01 (geometry) --- (continued)

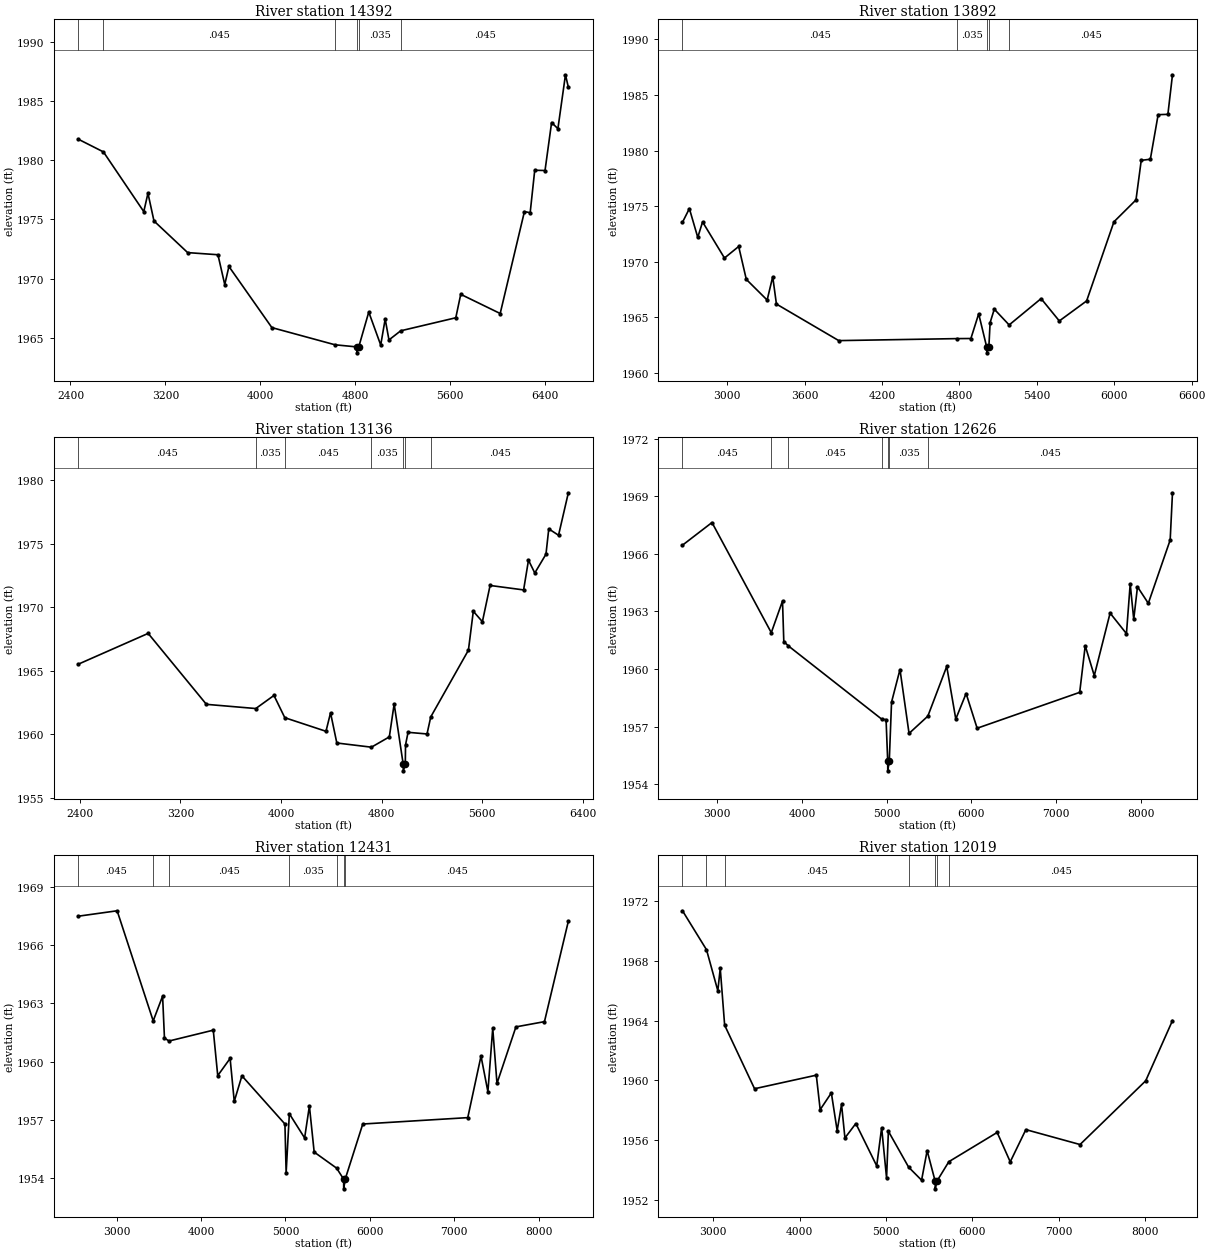
Type RM Length L Ch R = 1 ,14392   ,500,500,500
BEGIN DESCRIPTION:
Alkali Creek Trib 02 14.0
END DESCRIPTION:
XS GIS Cut Line= 3
      1372003.37      6959953.18        1373955.        6958338.
      1374495.52      6956835.15
#Sta/Elev= 30
  2466.7 1981.76  2678.1 1980.69  3018.2 1975.65  3053.4  1977.2  3104.2 1974.86
  3388.1 1972.19  3643.4 1972.01  3700.8 1969.49  3735.9 1971.02    4098 1965.86
  4630.1 1964.41  4814.1 1964.23  4814.6 1963.73  4830.3 1964.23  4914.7 1967.17
  5015.4 1964.39  5053.1 1966.58    5085 1964.82    5184 1965.59  5648.3 1966.69
  5689.9 1968.67  6022.5 1967.05  6226.8 1975.65  6275.3 1975.56  6313.7 1979.14
  6400.5 1979.12  6455.9 1983.17  6509.1 1982.65  6572.8  1987.2  6597.1 1986.15
#Mann= 6 ,-1 , 0
  2466.7    .035       0  2678.1    .045       0  4630.1    .035       0
  4814.1    .035       0  4830.3    .035       0    5184    .045       0
Bank Sta=4814.1,4830.3
XS Rating Curve= 0 ,0
Exp/Cntr=0.3,0.1

Type RM Length L Ch R = 1 ,13892   ,756,756,756
BEGIN DESCRIPTION:
Alkali Creek Trib 02 13.3
END DESCRIPTION:
XS GIS Cut Line= 3
      1372702.14      6959688.44      1374407.36      6958719.65
      1374634.41      6956897.65
#Sta/Elev= 30
  2654.2 1973.55  2707.5 1974.78  2772.5 1972.19  2809.8 1973.58  2979.5 1970.33
  3089.6 1971.37  3148.7 1968.41  3310.2 1966.55  3353.4 1968.65  3382.1 1966.19
  3865.2  1962.9  4782.2 1963.08  4889.2 1963.09  4949.6 1965.31  5012.1  1962.3
  5012.6  1961.8  5028.3  1962.3  5038.2 1964.52  5070.5 1965.73  5185.6 1964.31
  5433.3 1966.68  5574.4 1964.67    5786 1966.47  5997.7 1973.59  6168.6 1975.56
  6209.3 1979.12  6279.8 1979.22  6340.3 1983.23  6415.8 1983.26  6451.5 1986.82
#Mann= 5 ,-1 , 0
  2654.2    .045       0  4782.2    .035       0  5012.1    .035       0
  5028.3    .035       0  5185.6    .045       0
Bank Sta=5012.1,5028.3
XS Rating Curve= 0 ,0
Exp/Cntr=0.3,0.1

Type RM Length L Ch R = 1 ,13136   ,510,510,510
BEGIN DESCRIPTION:
Alkali Creek Trib 02 13.1
END DESCRIPTION:
XS GIS Cut Line= 4
      1373361.48      6960001.37      1375157.21      6958650.62
      1375219.69      6958043.78      1374747.05       6957118.5
#Sta/Elev= 30
  2388.1 1965.53  2943.1 1967.95  3406.2 1962.37  3798.9 1962.04  3943.5 1963.07
  4029.6 1961.32  4357.1 1960.25  4393.3  1961.7  4443.3 1959.33  4718.4    1959
  4860.8 1959.81  4899.2  1962.4  4971.4 1957.64  4971.9 1957.14  4987.8 1957.64
  4989.6 1959.18  5009.7 1960.17  5160.5 1960.04  5190.1 1961.38  5489.7 1966.63
  5528.5 1969.69  5600.8 1968.87  5661.9 1971.72  5928.5 1971.37  5967.3 1973.71
  6017.4  1972.7  6106.3 1974.18  6128.5 1976.17  6206.2 1975.67  6284.2 1979.01
#Mann= 7 ,-1 , 0
  2388.1    .045       0  3798.9    .035       0  4029.6    .045       0
  4718.4    .035       0  4971.4    .035       0  4987.8    .035       0
  5190.1    .045       0
Bank Sta=4971.4,4987.8
XS Rating Curve= 0 ,0
Exp/Cntr=0.3,0.1

Type RM Length L Ch R = 1 ,12626   ,195,195,195
BEGIN DESCRIPTION:
Alkali Creek Trib 02 13.2
END DESCRIPTION:
XS GIS Cut Line= 4
      1373578.78      6959840.46      1375491.89      6958637.06
        1375680.        6958413.      1377556.87      6955782.27
#Sta/Elev= 30
  2589.3 1966.45  2937.4 1967.63  3637.5 1961.89  3769.9 1963.54  3785.2 1961.43
  3839.2  1961.2  4942.1 1957.38  4992.4 1957.36  5011.9 1955.19  5012.4 1954.69
  5030.2 1955.19  5057.1 1958.27  5156.7 1959.97  5263.7 1956.64  5485.6 1957.54
  5708.6 1960.13  5815.5 1957.39  5937.2 1958.72  6067.5 1956.91  7278.2 1958.78
  7343.4 1961.21  7450.3 1959.65  7637.1 1962.91  7830.1 1961.84  7874.4 1964.43
  7916.1 1962.59  7960.4 1964.28  8088.2 1963.42  8346.3 1966.72  8373.6 1969.18
#Mann= 7 ,-1 , 0
  2589.3    .045       0  3637.5    .035       0  3839.2    .045       0
  4942.1    .035       0  5011.9    .035       0  5030.2    .035       0
  5485.6    .045       0
Bank Sta=5011.9,5030.2
XS Rating Curve= 0 ,0
Exp/Cntr=0.3,0.1

Type RM Length L Ch R = 1 ,12431   ,412,412,412
BEGIN DESCRIPTION:
Alkali Creek Trib 02 13.0
END DESCRIPTION:
XS GIS Cut Line= 4
      1373664.11      6959854.73       1375567.1      6958787.22
      1376086.08      6958283.23      1377665.93      6955848.35
#Sta/Elev= 30
  2545.8 1967.51  3005.5 1967.79  3432.9  1962.1  3544.4 1963.38  3566.4 1961.21
  3620.9 1961.06    4145 1961.62  4197.9 1959.27  4344.6 1960.16  4393.7 1957.94
  4484.6 1959.26  4994.4 1956.77  5008.6 1954.25  5046.8  1957.3  5227.7 1956.05
  5284.3  1957.7  5340.9 1955.32  5606.7 1954.49  5690.4 1953.92  5690.9 1953.42
  5708.7 1953.92    5917 1956.77  7161.5  1957.1  7318.5 1960.28  7400.2 1958.44
  7457.5 1961.72  7507.8 1958.87  7732.4 1961.79  8070.6 1962.06  8353.7 1967.25
#Mann= 7 ,-1 , 0
  2545.8    .045       0  3432.9    .035       0  3620.9    .045       0
  5046.8    .035       0  5606.7    .045       0  5690.4    .045       0
  5708.7    .045       0
Bank Sta=5690.4,5708.7
XS Rating Curve= 0 ,0
Exp/Cntr=0.3,0.1

Type RM Length L Ch R = 1 ,12019   ,371,371,371
BEGIN DESCRIPTION:
Alkali Creek Trib 02 12.0
END DESCRIPTION:
XS GIS Cut Line= 4
      1374078.05       6959926.1       1375948.7      6959001.63
      1376183.08      6958654.41        1377921.      6956014.81
#Sta/Elev= 30
  2646.8 1971.36  2924.3 1968.75  3055.3    1966  3083.3  1967.5  3134.2 1963.69
    3480 1959.43    4194 1960.34  4238.9 1958.03    4368 1959.15  4435.3 1956.62
  4485.8 1958.38  4525.1 1956.13  4651.2  1957.1  4892.6 1954.26  4949.6 1956.82
  5006.6 1953.44  5027.6 1956.58  5261.9 1954.17  5411.4  1953.3  5475.7 1955.28
    5569 1953.22  5569.5 1952.72  5587.3 1953.22  5726.6 1954.54  6285.5  1956.5
  6436.5 1954.53  6617.2 1956.69  7243.6 1955.69  8002.7 1959.96  8312.7    1964
#Mann= 7 ,-1 , 0
  2646.8    .045       0  2924.3    .035       0  3134.2    .045       0
  5261.9    .035       0    5569    .045       0  5587.3    .035       0
  5726.6    .045       0
Bank Sta=5569,5587.3
XS Rating Curve= 0 ,0
Exp/Cntr=0.3,0.1

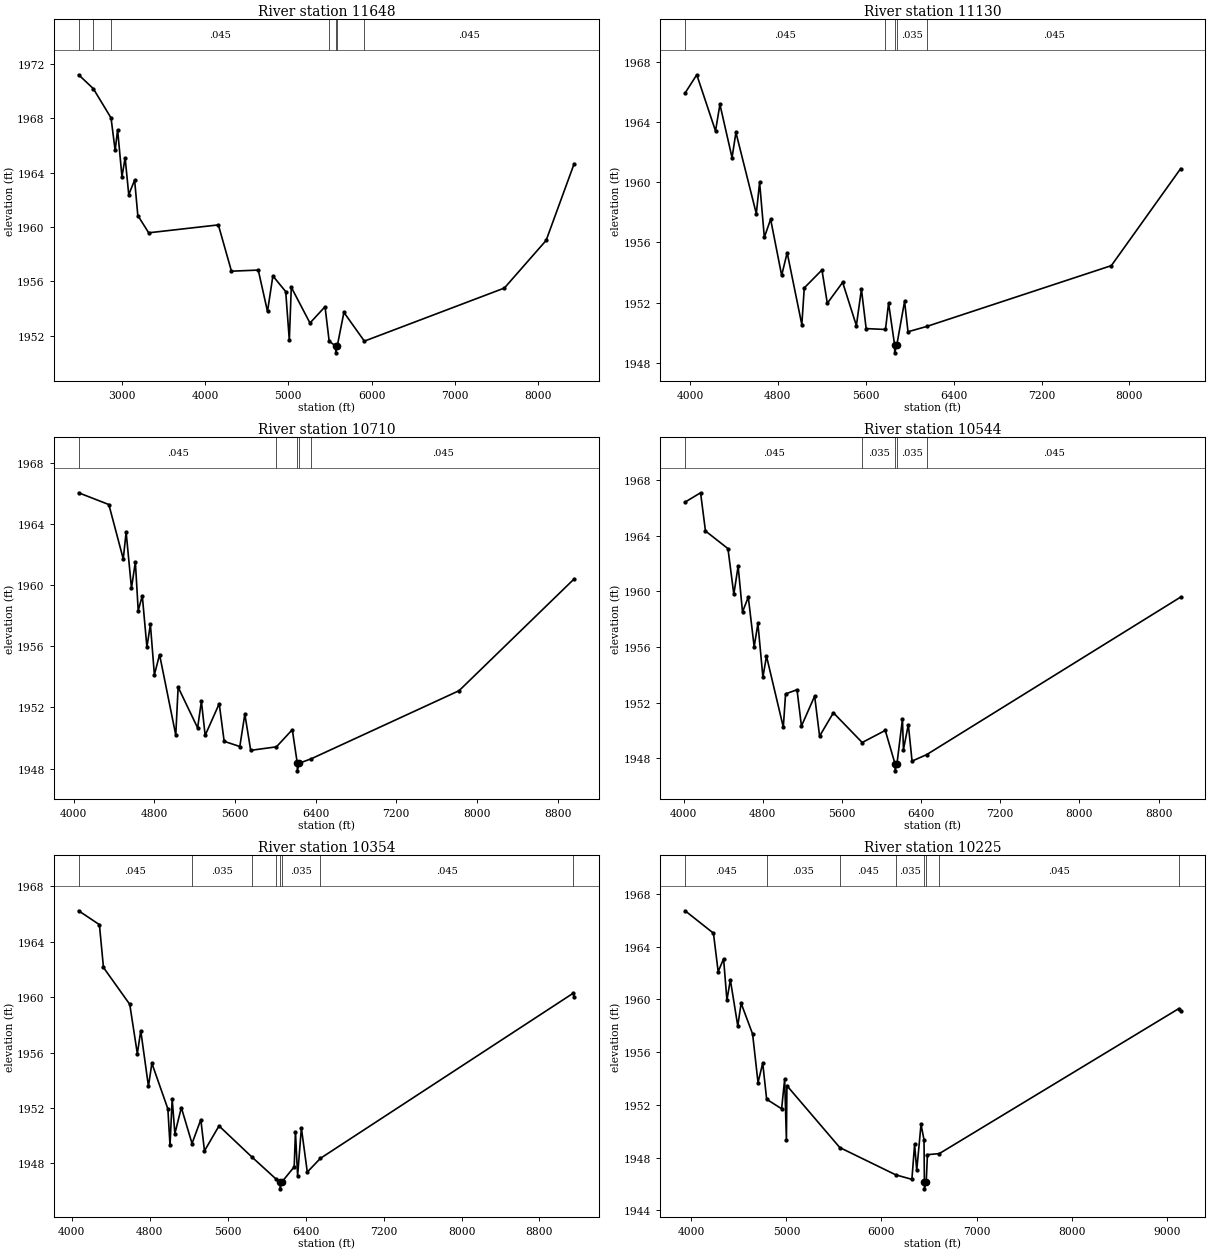
Type RM Length L Ch R = 1 ,11648   ,518,518,518
BEGIN DESCRIPTION:
Alkali Creek Trib 02 11.0
END DESCRIPTION:
XS GIS Cut Line= 4
      1374122.35      6960019.41      1376346.27      6959059.36
      1376505.99      6958807.62      1378186.76        6956048.
#Sta/Elev= 30
  2481.7 1971.18  2658.2 1970.16  2870.9 1968.01  2920.3 1965.62  2949.8 1967.14
  3002.2 1963.69  3040.1 1965.08  3083.6 1962.37  3154.2 1963.44  3192.6 1960.84
  3323.3 1959.57  4159.8 1960.15  4317.2 1956.75  4639.1 1956.83  4750.1 1953.79
  4814.6  1956.4  4968.8 1955.25  5012.2 1951.68  5035.8 1955.57  5260.2 1952.94
  5441.1 1954.14  5490.9  1951.6  5569.5 1951.25    5570 1950.75  5587.8 1951.25
  5667.7 1953.72  5913.6 1951.61  7594.9 1955.51  8096.5 1959.01  8433.3 1964.65
#Mann= 7 ,-1 , 0
  2481.7    .045       0  2658.2    .035       0  2870.9    .045       0
  5490.9    .035       0  5569.5    .045       0  5587.8    .035       0
  5913.6    .045       0
Bank Sta=5569.5,5587.8
XS Rating Curve= 0 ,0
Exp/Cntr=0.3,0.1

Type RM Length L Ch R = 1 ,11130   ,420,420,420
BEGIN DESCRIPTION:
Alkali Creek Trib 02 10.0
END DESCRIPTION:
XS GIS Cut Line= 3
      1376723.87      6960273.93        1376805.        6959238.
      1378537.57      6956231.61
#Sta/Elev= 30
  3956.5 1965.91  4062.8 1967.12  4233.3 1963.39  4273.4 1965.15  4383.7 1961.62
    4419 1963.29  4604.4  1957.9  4634.5 1959.97  4677.5 1956.33  4734.8 1957.53
  4835.1  1953.8  4885.3 1955.31  5018.7 1950.53  5040.8 1952.97  5201.7 1954.16
  5250.6 1951.95    5390 1953.34    5515 1950.47  5560.9 1952.88    5604 1950.27
  5779.9 1950.21    5808 1951.96  5863.2 1949.16  5863.7 1948.66  5882.4 1949.16
  5953.6 1952.08  5984.7 1950.06  6154.4 1950.41  7835.1 1954.45  8465.5 1960.89
#Mann= 5 ,-1 , 0
  3956.5    .045       0  5779.9    .035       0  5863.2    .045       0
  5882.4    .035       0  6154.4    .045       0
Bank Sta=5863.2,5882.4
XS Rating Curve= 0 ,0
Exp/Cntr=0.3,0.1

Type RM Length L Ch R = 1 ,10710   ,166,166,166
BEGIN DESCRIPTION:
Alkali Creek Trib 02 9.0
END DESCRIPTION:
XS GIS Cut Line= 4
      1376753.05      6960303.13        1377155.        6959438.
      1377214.36      6959296.66      1379110.63      6955996.98
#Sta/Elev= 30
  4050.6 1966.03  4350.2 1965.26  4493.1  1961.7  4521.5 1963.46  4574.5 1959.79
    4613 1961.51  4641.4 1958.32  4681.7  1959.3  4727.5 1955.94    4762 1957.42
  4801.7 1954.13    4853 1955.45  5013.7 1950.19  5037.1 1953.32  5230.3 1950.66
  5267.7  1952.4  5305.1 1950.17  5444.5 1952.24  5493.4 1949.78  5648.7 1949.44
  5698.4 1951.56  5756.5 1949.19  6011.6 1949.42  6169.1 1950.54  6218.4 1948.35
  6218.9 1947.85  6237.7 1948.35  6357.3 1948.64  7822.4 1953.09  8963.6  1960.4
#Mann= 5 ,-1 , 0
  4050.6    .045       0  6011.6    .035       0  6218.4    .045       0
  6237.7    .035       0  6357.3    .045       0
Bank Sta=6218.4,6237.7
XS Rating Curve= 0 ,0
Exp/Cntr=0.3,0.1

Type RM Length L Ch R = 1 ,10544   ,190,190,190
BEGIN DESCRIPTION:
Alkali Creek Trib 02 8.5
END DESCRIPTION:
XS GIS Cut Line= 2
      1376810.69      6960384.53      1379253.47      6956012.47
#Sta/Elev= 30
  4014.4 1966.43  4170.8  1967.1  4220.2 1964.35  4447.5 1963.08  4506.9 1959.79
  4550.3 1961.82  4594.6 1958.52  4653.1 1959.59  4712.5 1956.01  4750.2 1957.69
  4800.8 1953.82    4837 1955.34    5007 1950.22  5029.9 1952.62  5145.4 1952.92
  5190.3  1950.3  5323.6 1952.46  5373.6 1949.58  5513.2 1951.26  5804.2 1949.12
  6037.5 1949.99  6136.3 1947.58  6136.8 1947.08  6155.6 1947.58  6211.1  1950.8
  6221.2 1948.61  6270.5 1950.41  6308.2 1947.78  6456.5 1948.25  9022.6 1959.59
#Mann= 5 ,-1 , 0
  4014.4    .045       0  5804.2    .035       0  6136.3    .045       0
  6155.6    .035       0  6456.5    .045       0
Bank Sta=6136.3,6155.6
XS Rating Curve= 0 ,0
Exp/Cntr=0.3,0.1

Type RM Length L Ch R = 1 ,10354   ,129,129,129
BEGIN DESCRIPTION:
Alkali Creek Trib 02 8.6
END DESCRIPTION:
XS GIS Cut Line= 3
       1376866.6      6960349.56      1377368.37      6959770.58
        1379362.      6955939.41
#Sta/Elev= 30
  4071.1 1966.23  4284.2 1965.23  4325.9 1962.14  4595.7 1959.48  4673.5 1955.92
  4708.6 1957.58  4787.5 1953.57  4822.7 1955.23  4986.7 1951.94  5008.9 1949.31
    5031 1952.65  5058.7 1950.15    5125 1952.03  5234.7 1949.44  5324.9 1951.16
  5362.5 1948.91  5511.6 1950.71  5848.5 1948.47  6093.4  1946.9  6138.2 1946.67
  6138.7 1946.17  6157.5 1946.67  6283.1 1947.76  6296.1 1950.28  6318.2 1947.11
  6356.8 1950.56  6417.5 1947.38  6552.2 1948.37  9145.5 1960.28  9156.1 1960.04
#Mann= 8 ,-1 , 0
  4071.1    .045       0  5234.7    .035       0  5848.5    .045       0
  6093.4    .035       0  6138.2    .045       0  6157.5    .035       0
  6552.2    .045       0  9145.5    .035       0
Bank Sta=6138.2,6157.5
XS Rating Curve= 0 ,0
Exp/Cntr=0.3,0.1

Type RM Length L Ch R = 1 ,10225   ,353,353,353
BEGIN DESCRIPTION:
Alkali Creek Trib 02 8.0
END DESCRIPTION:
XS GIS Cut Line= 4
      1376800.81      6960424.62      1377503.94       6959823.1
      1377629.81      6959454.18      1379415.11      6955991.44
#Sta/Elev= 30
  3934.9 1966.72  4233.1 1965.02  4282.6  1962.1  4339.6 1963.08  4374.7 1959.95
  4410.9 1961.48  4488.9 1957.99    4524 1959.71  4644.7 1957.38  4701.8 1953.69
  4751.2 1955.17  4792.5 1952.43  4950.1 1951.71  4981.8 1953.95  5000.3 1949.36
  5005.6 1953.46  5561.6 1948.77  6150.4  1946.7  6319.9 1946.36  6348.3 1949.01
  6370.8 1947.04  6415.8 1950.53  6447.3 1949.36  6451.2 1946.14  6451.7 1945.64
  6470.5 1946.14  6483.3 1948.23  6607.8 1948.31    9128 1959.31  9145.9 1959.11
#Mann= 8 ,-1 , 0
  3934.9    .045       0  4792.5    .035       0  5561.6    .045       0
  6150.4    .035       0  6451.2    .035       0  6470.5    .035       0
  6607.8    .045       0    9128    .035       0
Bank Sta=6451.2,6470.5
XS Rating Curve= 0 ,0
Exp/Cntr=0.3,0.1

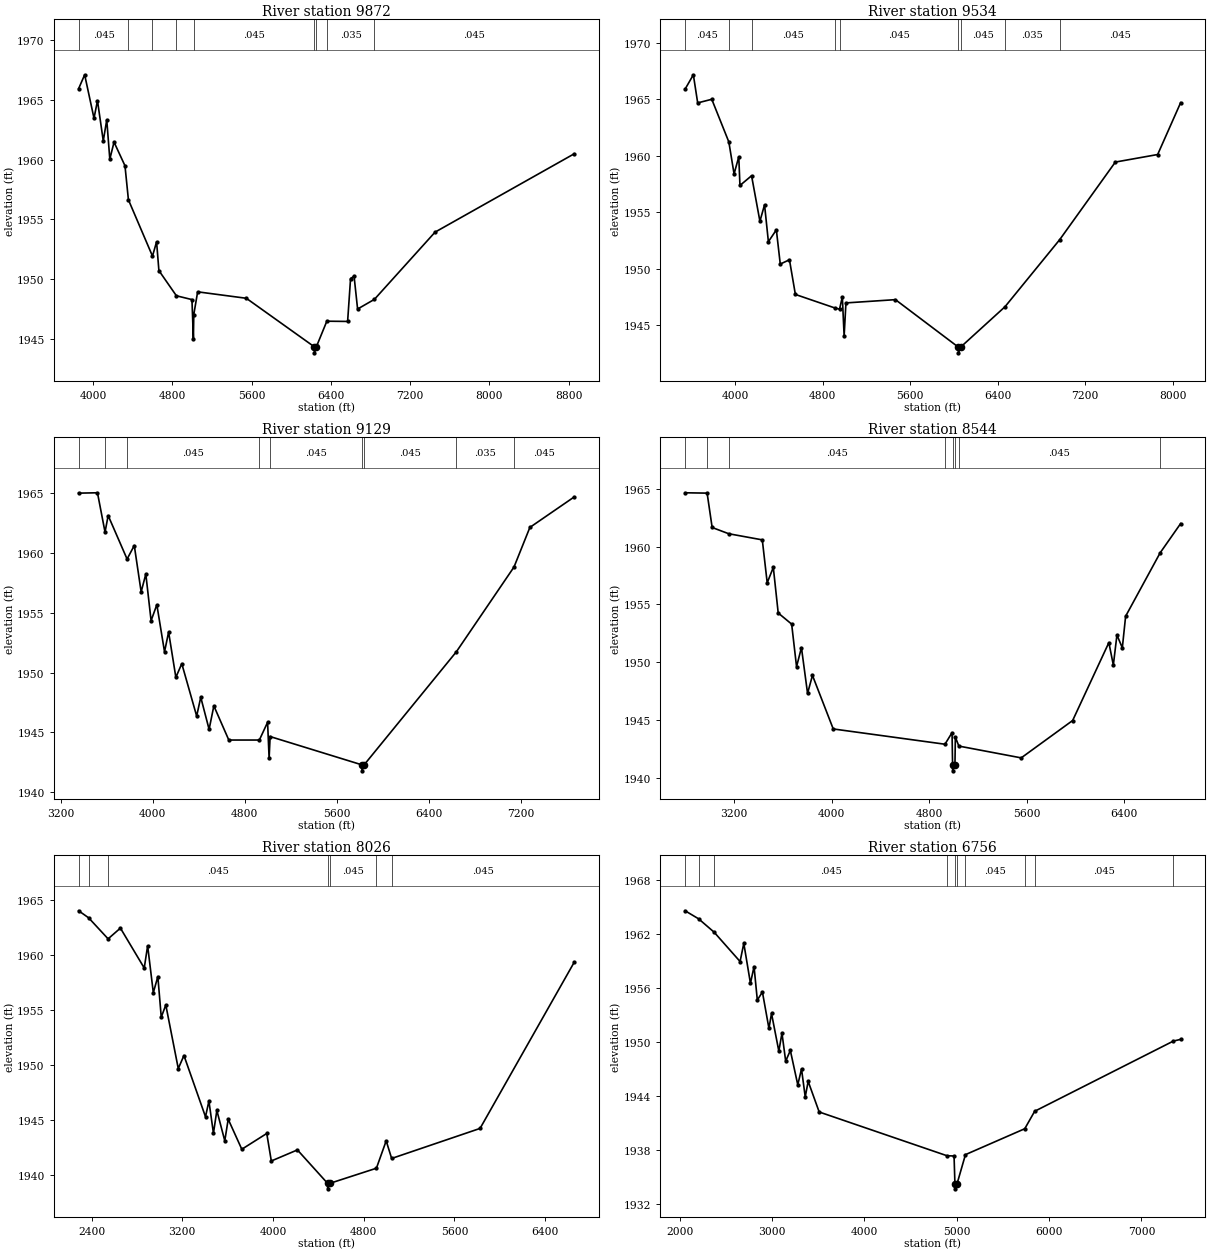
Type RM Length L Ch R = 1 ,9872    ,338,338,338
BEGIN DESCRIPTION:
Alkali Creek Trib 02 8.4
END DESCRIPTION:
XS GIS Cut Line= 3
      1376952.38      6960447.28      1377764.94      6959953.57
       1379934.9      6956531.34
#Sta/Elev= 30
  3853.3 1965.96  3914.2 1967.12  4008.5 1963.48  4043.6 1964.95  4102.1 1961.58
  4137.2 1963.35  4168.1 1960.05  4210.7 1961.48  4321.2  1959.5  4355.9 1956.65
    4599 1951.93  4640.3 1953.13  4663.7 1950.72  4840.3 1948.61  4997.3 1948.29
    5012    1945  5015.9 1947.04  5054.9 1948.94  5546.3  1948.4  6233.8 1944.33
  6234.3 1943.83  6253.1 1944.33  6359.2 1946.48    6569 1946.46  6598.7 1950.05
  6634.2 1950.25  6669.7  1947.5  6839.5 1948.31  7451.9 1953.94  8856.3  1960.5
#Mann= 9 ,-1 , 0
  3853.3    .045       0  4355.9    .035       0    4599    .045       0
  4840.3    .035       0  5015.9    .045       0  6233.8    .035       0
  6253.1    .045       0  6359.2    .035       0  6839.5    .045       0
Bank Sta=6233.8,6253.1
XS Rating Curve= 0 ,0
Exp/Cntr=0.3,0.1

Type RM Length L Ch R = 1 ,9534    ,405,405,405
BEGIN DESCRIPTION:
Alkali Creek Trib 02 7.8
END DESCRIPTION:
XS GIS Cut Line= 4
      1376967.82      6960519.78      1378063.83      6960090.42
      1378319.56      6959590.47      1379960.99      6957329.68
#Sta/Elev= 30
  3540.4  1965.9  3615.9 1967.17  3655.5 1964.68  3784.4    1965  3940.6 1961.22
  3988.4 1958.39  4031.4 1959.91  4042.1 1957.37  4148.4 1958.23  4224.7  1954.2
  4267.1 1955.66  4302.2 1952.39  4375.1 1953.44  4410.8 1950.41  4494.9 1950.79
  4549.1 1947.72  4914.5 1946.51    4953 1946.42  4978.6  1947.5    4995 1944.04
  5011.6 1946.97  5464.2 1947.26  6040.5 1943.05    6041 1942.55  6059.8 1943.05
  6466.2 1946.63  6966.6 1952.57  7475.6 1959.44  7862.8 1960.11  8072.9  1964.7
#Mann= 9 ,-1 , 0
  3540.4    .045       0  3940.6    .035       0  4148.4    .045       0
  4914.5    .035       0    4953    .045       0  6040.5    .045       0
  6059.8    .045       0  6466.2    .035       0  6966.6    .045       0
Bank Sta=6040.5,6059.8
XS Rating Curve= 0 ,0
Exp/Cntr=0.3,0.1

Type RM Length L Ch R = 1 ,9129    ,585,585,585
BEGIN DESCRIPTION:
Alkali Creek Trib 02 7.5
END DESCRIPTION:
XS GIS Cut Line= 3
      1377096.36      6960529.56      1378371.77      6960200.42
      1380148.52      6957792.85
#Sta/Elev= 30
  3356.9 1964.97  3520.7    1965  3586.5 1961.72  3613.7  1963.1  3778.3 1959.47
  3840.9  1960.6  3900.6 1956.73  3941.2 1958.22    3987 1954.33  4037.1 1955.66
  4103.9 1951.73  4139.4 1953.38  4202.4  1949.6    4254 1950.74  4383.4 1946.37
  4418.9 1947.94  4491.5 1945.26  4532.8 1947.22  4662.9 1944.37  4928.5 1944.37
  5000.2 1945.85  5013.4 1942.84  5022.2 1944.66  5820.3  1942.3  5820.8  1941.8
  5839.6  1942.3  6642.2 1951.74  7143.3 1958.81  7281.1 1962.11  7666.3 1964.65
#Mann= 9 ,-1 , 0
  3356.9    .045       0  3586.5    .035       0  3778.3    .045       0
  4928.5    .035       0  5022.2    .045       0  5820.3    .035       0
  5839.6    .045       0  6642.2    .035       0  7143.3    .045       0
Bank Sta=5820.3,5839.6
XS Rating Curve= 0 ,0
Exp/Cntr=0.3,0.1

Type RM Length L Ch R = 1 ,8544    ,518,518,518
BEGIN DESCRIPTION:
Alkali Creek Trib 02 7.3
END DESCRIPTION:
XS GIS Cut Line= 4
      1377123.78      6960552.27      1378878.44       6960422.3
      1379248.87      6959837.42      1380087.26      6958462.09
#Sta/Elev= 30
  2798.7 1964.65  2979.3 1964.62  3020.5 1961.65  3156.5 1961.11  3431.6 1960.58
  3471.8 1956.87  3521.9  1958.2    3562 1954.26  3672.3  1953.3  3712.4 1949.62
  3752.5 1951.27  3802.7 1947.31  3842.8 1948.87  4013.2 1944.24  4929.1 1942.92
  4987.2 1943.92  4991.6 1941.12  4992.1 1940.62  5010.9 1941.12  5014.3 1943.54
  5042.9 1942.76  5554.2 1941.74  5975.9 1944.97  6272.7  1951.7  6309.5 1949.76
    6339 1952.36  6383.1 1951.25  6410.2 1953.98  6693.2 1959.46  6861.2 1961.99
#Mann= 8 ,-1 , 0
  2798.7    .045       0  2979.3    .035       0  3156.5    .045       0
  4929.1    .035       0  4991.6    .035       0  5010.9    .035       0
  5042.9    .045       0  6693.2    .035       0
Bank Sta=4991.6,5010.9
XS Rating Curve= 0 ,0
Exp/Cntr=0.3,0.1

Type RM Length L Ch R = 1 ,8026    ,1270,1270,1270
BEGIN DESCRIPTION:
Alkali Creek Trib 02 7.1
END DESCRIPTION:
XS GIS Cut Line= 4
      1377206.71      6960578.02      1379411.71      6960648.39
       1379654.1      6960007.23       1380235.4      6958647.77
#Sta/Elev= 30
  2286.3 1964.06  2374.3 1963.42  2546.2  1961.5  2654.8 1962.48  2864.9 1958.84
  2894.9 1960.87  2944.9 1956.59  2984.9 1958.06    3015 1954.35    3055 1955.47
    3165 1949.67  3215.1 1950.86  3405.2 1945.27  3435.2 1946.71  3475.2 1943.77
  3505.2 1945.85  3575.2 1943.08  3605.3 1945.05  3725.3 1942.31  3945.4 1943.75
  3985.5 1941.24  4215.6 1942.25  4481.9  1939.2  4482.4  1938.7  4501.2  1939.2
  4912.4 1940.58  4998.6 1943.08  5046.7 1941.47  5826.4 1944.21  6656.4 1959.36
#Mann= 7 ,-1 , 0
  2286.3    .045       0  2374.3    .035       0  2546.2    .045       0
  4481.9    .035       0  4501.2    .045       0  4912.4    .035       0
  5046.7    .045       0
Bank Sta=4481.9,4501.2
XS Rating Curve= 0 ,0
Exp/Cntr=0.3,0.1

Type RM Length L Ch R = 1 ,6756    ,782,782,782
BEGIN DESCRIPTION:
Alkali Creek Trib 02 7.0
END DESCRIPTION:
XS GIS Cut Line= 4
      1377134.19      6960632.96        1379818.      6960978.92
      1380227.72      6960940.72      1381519.39      6959096.97
#Sta/Elev= 30
  2056.4  1964.6  2202.4 1963.71    2371 1962.22  2652.1 1958.96  2692.4 1960.98
  2764.4 1956.54  2803.3  1958.4  2838.8 1954.68  2894.1 1955.57  2964.7 1951.53
  2992.6 1953.19    3072    1949  3105.8    1951  3146.2 1947.89  3196.6 1949.08
  3277.2 1945.26  3317.6 1947.02  3357.9 1943.92  3389.8 1945.64  3509.1 1942.24
  4893.3 1937.38  4970.3 1937.35  4979.9  1934.2  4980.4  1933.7    5001  1934.2
  5093.7  1937.5  5736.4 1940.38  5843.7 1942.32  7346.2 1950.12  7425.1 1950.31
#Mann= 10 ,-1 , 0
  2056.4    .045       0  2202.4    .035       0    2371    .045       0
  4893.3     .07       0  4979.9     .07       0    5001     .07       0
  5093.7    .045       0  5736.4    .035       0  5843.7    .045       0
  7346.2    .035       0
Bank Sta=4979.9,5001
XS Rating Curve= 0 ,0
Exp/Cntr=0.3,0.1

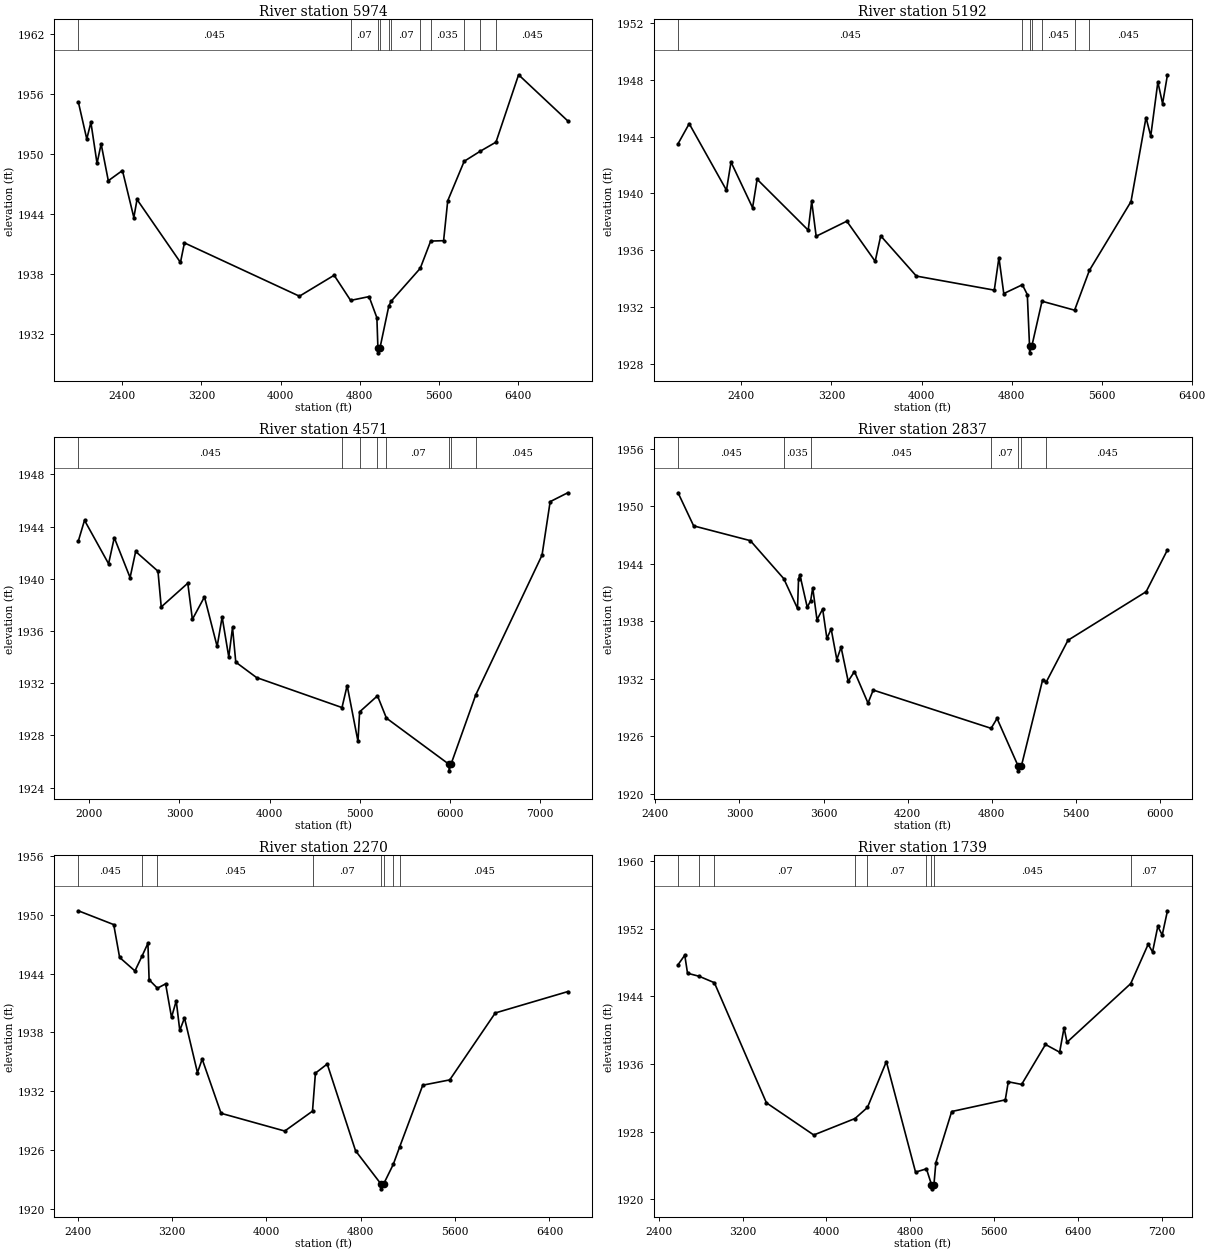
Type RM Length L Ch R = 1 ,5974    ,782,782,782
BEGIN DESCRIPTION:
Alkali Creek Trib 02 6.5
END DESCRIPTION:
XS GIS Cut Line= 4
      1377842.51      6960867.33      1380386.14      6961546.57
      1381250.46      6960799.22       1381840.6      6959794.03
#Sta/Elev= 30
    1958  1955.2  2043.4  1951.5  2084.8 1953.17  2146.9 1949.07  2188.3 1951.01
  2260.7 1947.34  2403.4 1948.36  2518.5 1943.67  2550.6 1945.47  2989.1 1939.19
  3029.2 1941.14  4190.2 1935.82  4540.6 1937.91  4706.9  1935.4  4893.3 1935.78
  4972.2 1933.67  4982.5 1930.67    4983 1930.17  5003.6 1930.67  5092.1 1934.82
  5116.3 1935.32  5409.9  1938.6  5515.3 1941.32  5645.7 1941.36  5687.4 1945.34
  5853.5 1949.28  6013.4 1950.27  6174.5 1951.19  6402.8 1957.91    6899 1953.31
#Mann= 11 ,-1 , 0
    1958    .045       0  4706.9     .07       0  4982.5     .07       0
  5003.6     .07       0  5092.1    .045       0  5116.3     .07       0
  5409.9    .045       0  5515.3    .035       0  5853.5    .045       0
  6013.4    .035       0  6174.5    .045       0
Bank Sta=4982.5,5003.6
XS Rating Curve= 0 ,0
Exp/Cntr=0.3,0.1

Type RM Length L Ch R = 1 ,5192    ,621,621,621
BEGIN DESCRIPTION:
Alkali Creek Trib 02 6.0
END DESCRIPTION:
XS GIS Cut Line= 4
      1377868.54      6961450.66        1381005.        6961858.
        1381130.        6961863.      1381461.99      6960856.97
#Sta/Elev= 30
  1837.2  1943.5  1936.3 1944.91  2267.2 1940.23  2307.6 1942.21  2499.2    1939
  2539.5    1941  2993.3 1937.42  3024.3 1939.45  3063.9 1936.99  3336.1 1938.05
  3588.2 1935.23  3637.4 1937.02    3954 1934.19  4646.3  1933.2  4687.4 1935.49
  4730.5 1932.96  4895.6 1933.58  4939.5 1932.89  4959.2 1929.29  4959.7 1928.79
  4980.4 1929.29  5070.1 1932.42  5359.6 1931.79    5491 1934.59  5860.6 1939.43
  5993.9 1945.34    6036 1944.04  6099.2 1947.84  6141.1 1946.32  6184.5 1948.35
#Mann= 7 ,-1 , 0
  1837.2    .045       0  4895.6    .035       0  4959.2    .035       0
  4980.4    .035       0  5070.1    .045       0  5359.6     .07       0
    5491    .045       0
Bank Sta=4959.2,4980.4
XS Rating Curve= 0 ,0
Exp/Cntr=0.3,0.1

Type RM Length L Ch R = 1 ,4571    ,1734,1734,1734
BEGIN DESCRIPTION:
Alkali Creek Trib 02 5.0
END DESCRIPTION:
XS GIS Cut Line= 4
      1377908.29      6961821.04      1380293.72       6962414.8
      1381342.62      6962432.61      1383259.89      6962448.65
#Sta/Elev= 30
  1879.7 1942.89  1948.4 1944.48  2215.1 1941.15  2278.2 1943.15  2453.4 1940.09
  2515.2 1942.09  2762.5 1940.58  2798.6 1937.84    3093 1939.66  3143.8 1936.89
  3277.8 1938.61  3418.3 1934.81  3473.6 1937.07  3547.4    1934  3588.7 1936.27
  3624.8 1933.61  3854.9 1932.43  4802.2 1930.13  4859.3 1931.82  4979.3 1927.54
  4997.6  1929.8  5195.6 1931.03  5294.6 1929.32  5988.6 1925.78  5989.1 1925.28
  6010.2 1925.78  6284.5  1931.1  7019.4 1941.81  7109.4 1945.91  7304.3 1946.59
#Mann= 8 ,-1 , 0
  1879.7    .045       0  4802.2    .035       0  4997.6     .07       0
  5195.6    .045       0  5294.6     .07       0  5988.6     .07       0
  6010.2     .07       0  6284.5    .045       0
Bank Sta=5988.6,6010.2
XS Rating Curve= 0 ,0
Exp/Cntr=0.3,0.1

Type RM Length L Ch R = 1 ,2837    ,567,567,567
BEGIN DESCRIPTION:
Alkali Creek Trib 02 4.0
END DESCRIPTION:
XS GIS Cut Line= 4
      1379805.02        6963438.      1382007.76       6963110.4
      1382371.06      6962977.61       1383073.2      6962452.92
#Sta/Elev= 30
  2562.5  1951.4  2673.7 1947.95  3078.1 1946.41  3316.4 1942.45  3414.5 1939.34
  3421.8 1942.43  3431.9 1942.81  3483.9 1939.47  3508.4 1940.16  3522.9  1941.5
  3553.3 1938.17  3593.7 1939.28    3624 1936.22  3654.4 1937.21  3694.8 1934.02
  3725.1 1935.31  3775.7 1931.76  3820.6 1932.77  3917.2 1929.48  3954.3 1930.84
  4795.2 1926.85  4837.3 1927.88  4987.9 1922.92  4988.4 1922.42    5011 1922.92
  5162.5  1931.9  5189.5 1931.71  5343.5 1936.03  5900.7 1941.09  6052.8 1945.45
#Mann= 7 ,-1 , 0
  2562.5    .045       0  3316.4    .035       0  3508.4    .045       0
  4795.2     .07       0  4987.9     .07       0    5011     .07       0
  5189.5    .045       0
Bank Sta=4987.9,5011
XS Rating Curve= 0 ,0
Exp/Cntr=0.3,0.1

Type RM Length L Ch R = 1 ,2270    ,531,531,531
BEGIN DESCRIPTION:
Alkali Creek Trib 02 3.0
END DESCRIPTION:
XS GIS Cut Line= 4
      1379954.98        6963588.      1382355.96      6963529.34
      1382654.94      6963443.58      1383898.95      6962723.34
#Sta/Elev= 30
  2404.6 1950.41  2704.7    1949  2754.7 1945.65  2884.8 1944.27  2945.4  1945.8
  2994.8 1947.09  3004.8 1943.37  3075.3 1942.51  3144.8 1942.95  3194.9 1939.53
  3234.9 1941.22  3264.9  1938.2  3304.9 1939.47  3414.9 1933.89  3454.9 1935.27
    3615 1929.74  4155.1 1927.93  4390.4 1929.96  4415.2 1933.84  4515.3 1934.77
  4755.3 1925.92  4970.6 1922.53  4971.1 1922.03  4993.7 1922.53  5075.4 1924.53
  5128.3 1926.27  5325.4 1932.61  5554.1 1933.15  5940.2 1939.98  6554.8 1942.16
#Mann= 8 ,-1 , 0
  2404.6    .045       0  2945.4    .035       0  3075.3    .045       0
  4390.4     .07       0  4970.6     .07       0  4993.7     .07       0
  5075.4     .16       0  5128.3    .045       0
Bank Sta=4970.6,4993.7
XS Rating Curve= 0 ,0
Exp/Cntr=0.3,0.1

Type RM Length L Ch R = 1 ,1739    ,479,479,479
BEGIN DESCRIPTION:
Alkali Creek Trib 02 2.0
END DESCRIPTION:
XS GIS Cut Line= 4
      1380255.02        6963738.      1382515.03      6963918.45
      1383004.61      6963975.74      1384455.03      6962737.97
#Sta/Elev= 30
  2585.2 1947.76  2649.2 1948.89  2675.5 1946.75  2786.5 1946.39  2931.5 1945.63
  3427.9  1931.4  3879.3 1927.59  4272.6 1929.54  4391.2 1930.85  4571.5 1936.28
  4849.9 1923.19  4953.8 1923.58  5001.9 1921.71  5002.4 1921.21  5025.1 1921.71
  5043.7 1924.32  5194.7 1930.37  5705.6 1931.75  5734.2 1933.89  5861.5 1933.58
  6088.8 1938.31  6223.8  1937.4  6266.1 1940.29  6294.1 1938.58  6901.6 1945.52
    7068 1950.18  7109.9 1949.28    7160  1952.3  7202.1 1951.28  7252.1 1954.15
#Mann= 9 ,-1 , 0
  2585.2    .045       0  2786.5    .035       0  2931.5     .07       0
  4272.6    .045       0  4391.2     .07       0  4953.8    .045       0
  5001.9    .045       0  5025.1    .045       0  6901.6     .07       0
Bank Sta=5001.9,5025.1
XS Rating Curve= 0 ,0
Exp/Cntr=0.3,0.1

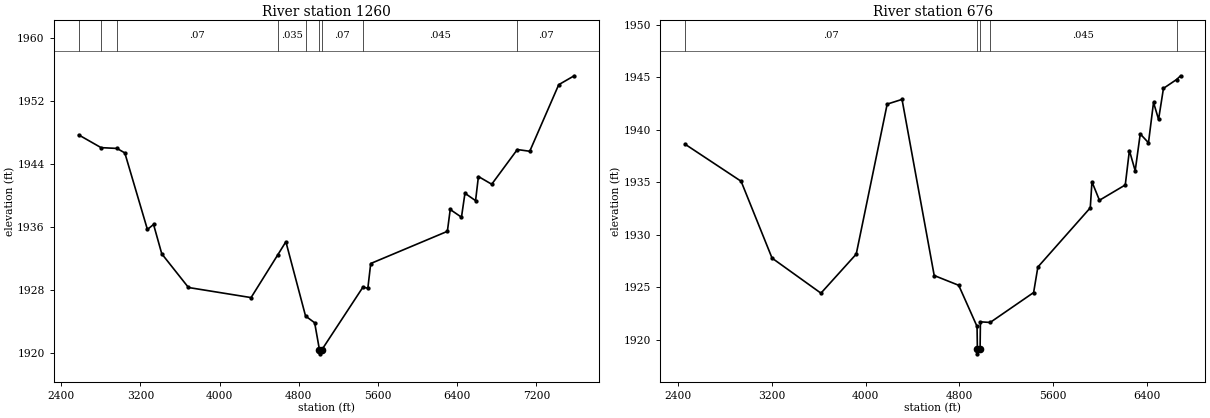
Type RM Length L Ch R = 1 ,1260    ,584,584,584
BEGIN DESCRIPTION:
Alkali Creek Trib 02 1.0
END DESCRIPTION:
XS GIS Cut Line= 4
      1380204.96      6963837.99      1382197.75      6964382.57
      1382733.78      6964343.51      1384605.02      6962837.98
#Sta/Elev= 30
  2576.3 1947.67  2803.1 1946.05  2964.1 1945.95  3042.8 1945.38  3270.9 1935.68
  3333.1 1936.31    3416 1932.59  3685.6 1928.32  4317.9 1927.04  4587.2 1932.45
  4669.5 1934.12  4868.3  1924.7  4960.2 1923.85  5008.8 1920.41  5009.3 1919.91
    5032 1920.41  5447.5 1928.36  5497.5 1928.23  5526.3 1931.36  6300.7 1935.44
  6329.4 1938.21    6443 1937.23  6478.2 1940.27  6585.4 1939.33  6614.2 1942.39
  6748.6 1941.41  7007.1 1945.81  7132.6 1945.59  7425.3 1954.03  7581.3 1955.16
#Mann= 9 ,-1 , 0
  2576.3    .045       0  2803.1    .035       0  2964.1     .07       0
  4587.2    .035       0  4868.3     .07       0  5008.8     .07       0
    5032     .07       0  5447.5    .045       0  7007.1     .07       0
Bank Sta=5008.8,5032
XS Rating Curve= 0 ,0
Exp/Cntr=0.3,0.1

Type RM Length L Ch R = 1 ,676     ,0,0,0
BEGIN DESCRIPTION:
Alkali Creek Trib 02 0.9
END DESCRIPTION:
XS GIS Cut Line= 3
      1380502.48      6964345.56      1382569.28       6965056.4
      1384161.53      6963768.55
#Sta/Elev= 30
  2457.4 1938.64  2935.9 1935.11  3200.3 1927.79    3618 1924.45  3919.4 1928.17
  4183.8 1942.46  4310.7 1942.91  4585.6 1926.13  4794.9  1925.2  4951.6 1921.28
  4954.4 1919.17  4954.9 1918.67  4977.6 1919.17  4980.4 1921.72  5063.8 1921.66
  5434.9 1924.51  5471.2 1926.94  5918.9 1932.58  5933.3 1935.06  5997.2  1933.3
  6217.9 1934.76  6253.1 1938.04  6302.6 1936.11  6345.8 1939.62  6416.2 1938.78
  6459.3 1942.62  6502.4    1941  6544.1 1943.96  6655.8  1944.8  6690.9 1945.16
#Mann= 5 ,-1 , 0
  2457.4     .07       0  4954.4     .07       0  4977.6     .07       0
  5063.8    .045       0  6655.8     .07       0
Bank Sta=4954.4,4977.6
XS Rating Curve= 0 ,0
Exp/Cntr=0.3,0.1

Chan Stop Cuts=-1
Use User Specified Reach Order=0
Composite Channel Slope=5