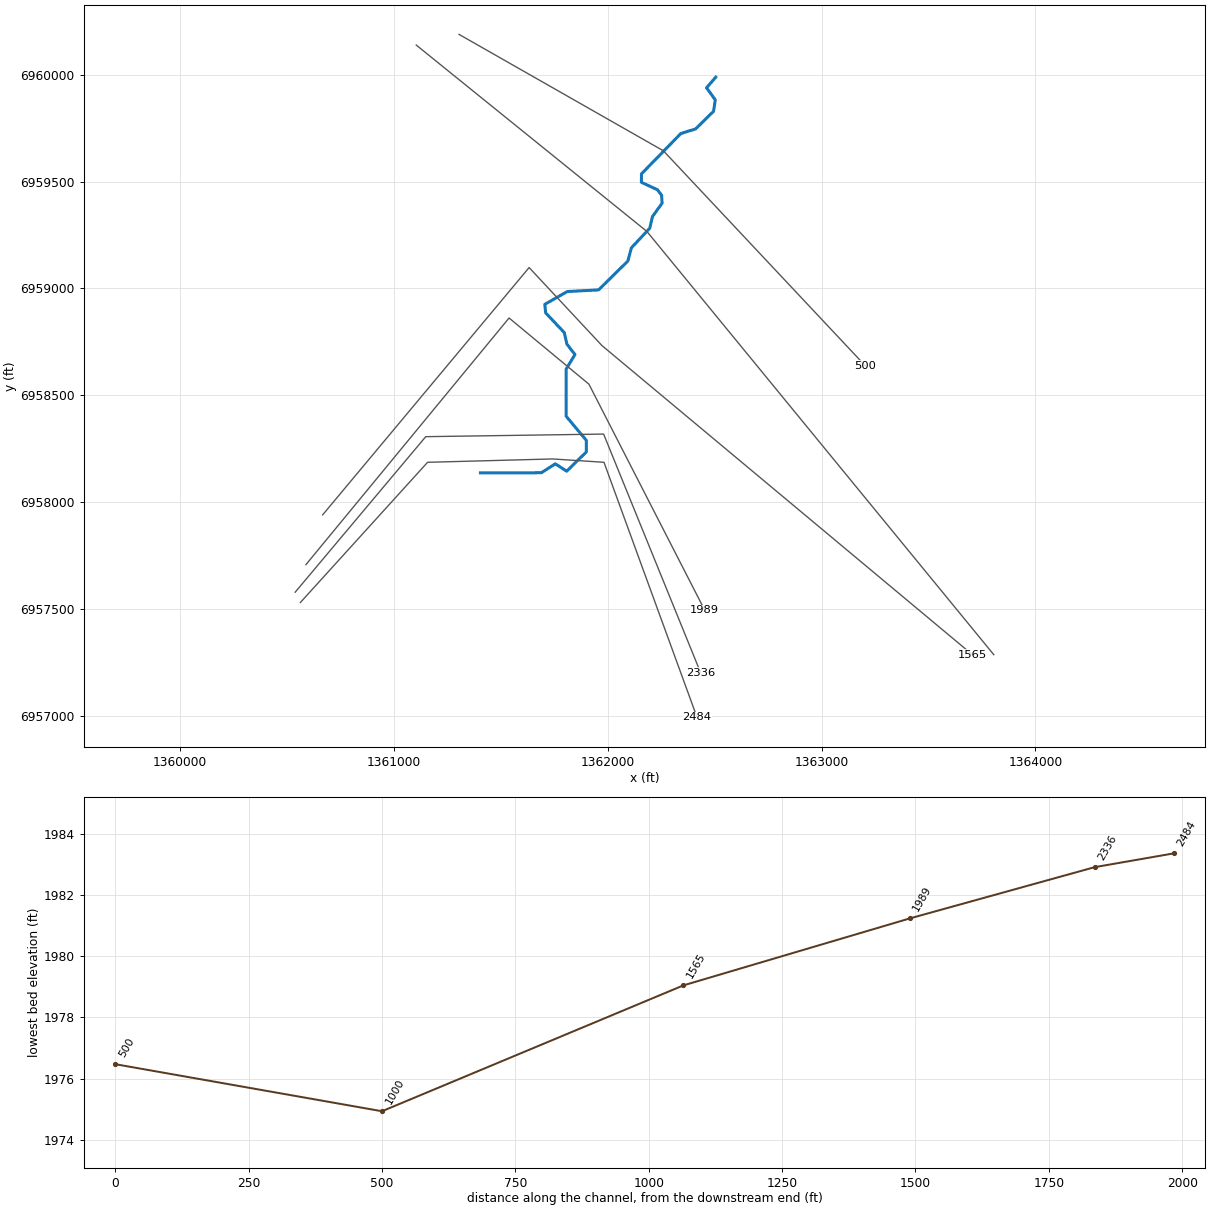
--- Alkali Creek Trib 04-01.prj (project) ---

Proj Title=Alkali Creek Trib 04-01 Base Level Engineering
Current Plan=p01
Default Exp/Contr=0.3,0.1
English Units
Geom File=g01
Flow File=f01
Plan File=p01
BEGIN DESCRIPTION:
Alkali Creek Trib 04-01
END DESCRIPTION:

--- Alkali Creek Trib 04-01.p01 (plan) ---

Plan Title=Multiple Run
Short Identifier=Multiple
Geom File=g01
Flow File=f01
Subcritical Flow
K Sum by GR= 0
Std Step Tol= 0.01
Critical Tol= 0.01
Num of Std Step Trials= 20
Max Error Tol= 0.3
Flow Tol Ratio= 0.001
Split Flow NTrial= 30
Split Flow Tol= 0.02
Split Flow Ratio= 0.02
Log Output Level= 0
Friction Slope Method= 1
Unsteady Friction Slope Method= 2
Unsteady Bridges Friction Slope Method= 1
Parabolic Critical Depth
Global Vel Dist=  1 , 1 , 1
Global Log Level= 0
CheckData=True
Encroach Param= -1, 0, 0, 0
BEGIN DESCRIPTION:
Multiple Run
END DESCRIPTION:

--- Alkali Creek Trib 04-01.f01 (steady flow) ---

Flow Title=Multiple
Number of Profiles=7
Profile Names=10-year,25-year,50-year,1pct_min,100-year,1pct_plu,500-year
River Rch & RM= Alkali Creek Tri,Reach-1,2484
     290     411     513     318     635    1268     988
Boundary for River Rch & Prof#=Alkali Creek Tri,Reach-1,1
Up Type=0
Dn Type=3
Dn Slope=0.005
Boundary for River Rch & Prof#=Alkali Creek Tri,Reach-1,2
Up Type=0
Dn Type=3
Dn Slope=0.005
Boundary for River Rch & Prof#=Alkali Creek Tri,Reach-1,3
Up Type=0
Dn Type=3
Dn Slope=0.005
Boundary for River Rch & Prof#=Alkali Creek Tri,Reach-1,4
Up Type=0
Dn Type=3
Dn Slope=0.005
Boundary for River Rch & Prof#=Alkali Creek Tri,Reach-1,5
Up Type=0
Dn Type=3
Dn Slope=0.005
Boundary for River Rch & Prof#=Alkali Creek Tri,Reach-1,6
Up Type=0
Dn Type=3
Dn Slope=0.005
Boundary for River Rch & Prof#=Alkali Creek Tri,Reach-1,7
Up Type=0
Dn Type=3
Dn Slope=0.005

--- Alkali Creek Trib 04-01.g01 (geometry) ---

Geom Title=Existing Conditions

River Reach=Alkali Creek Tri,Reach-1
Reach XY= 30
      1361405.00      6958138.00      1361689.84      6958138.65
      1361755.10      6958180.19      1361808.35      6958145.99
      1361899.94      6958235.68      1361899.92      6958290.28
      1361805.39      6958403.16      1361805.66      6958622.84
      1361846.96      6958691.32      1361809.45      6958739.65
      1361796.86      6958794.04      1361709.94      6958886.05
      1361706.12      6958925.99      1361810.90      6958985.76
      1361957.45      6958993.47      1362094.22      6959128.32
      1362110.87      6959190.28      1362196.85      6959281.95
      1362209.25      6959336.27      1362254.31      6959398.75
      1362251.93      6959436.57      1362232.30      6959461.79
      1362157.62      6959496.51      1362157.95      6959535.99
      1362341.79      6959724.37      1362411.07      6959746.15
      1362494.81      6959828.30      1362503.14      6959881.95
      1362461.95      6959938.12      1362505.00      6959988.00

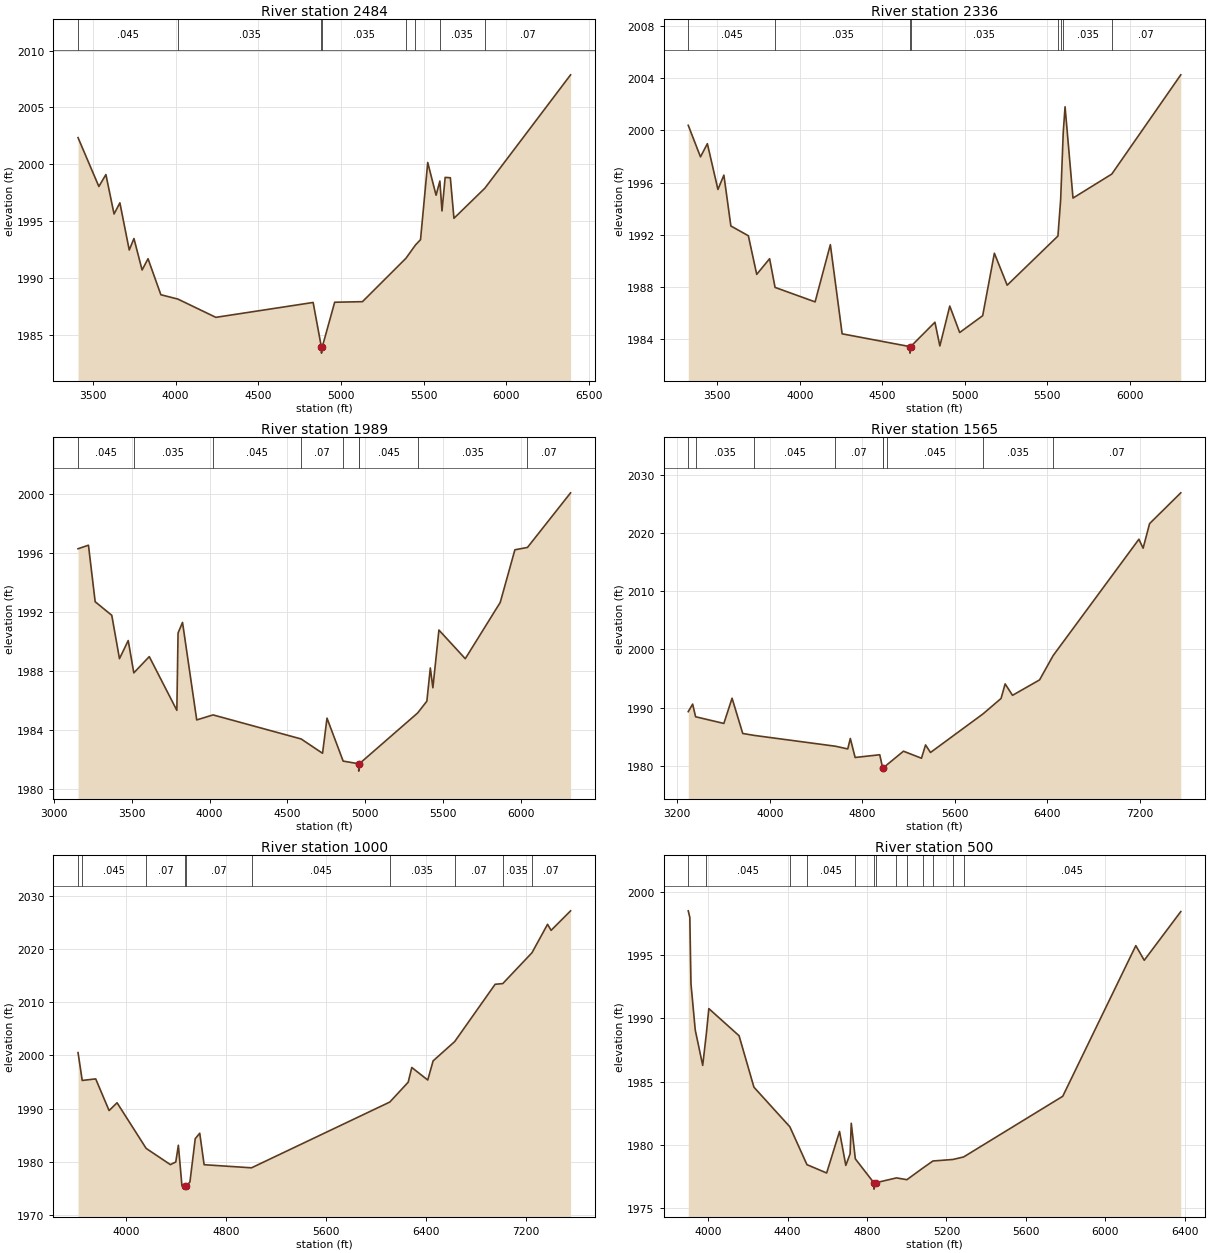
Type RM Length L Ch R = 1,2484,148,148,148
BEGIN DESCRIPTION:
Alkali Creek Trib 04-01 5.0
END DESCRIPTION:
XS GIS Cut Line= 5
      1360563.22      6957531.98      1361158.00      6958187.48
      1361743.07      6958203.10      1361982.65      6958187.48
      1362417.67      6956995.14
#Sta/Elev= 30
  3409.3 2002.34  3535.3 1998.04  3577.9 1999.09  3627.2 1995.62  3662.4 1996.60
  3719.1 1992.45  3747.5 1993.46  3796.8 1990.69  3832.7 1991.68  3910.4 1988.51
  4013.1 1988.13  4242.9 1986.52  4831.6 1987.83  4881.9 1983.87  4882.1 1983.37
  4886.0 1983.87  4961.8 1987.85  5129.9 1987.90  5393.0 1991.72  5450.7 1992.89
  5481.2 1993.36  5524.8 2000.15  5575.3 1997.27  5598.2 1998.52  5611.1 1995.89
  5630.2 1998.84  5661.6 1998.81  5683.4 1995.24  5870.5 1997.89  6389.0 2007.87
#Mann=8,-1,0
  3409.3   0.045       0  4013.1   0.035       0  4881.9   0.035       0
  4886.0   0.035       0  5393.0   0.045       0  5450.7    0.07       0
  5598.2   0.035       0  5870.5    0.07       0
Bank Sta=4881.9,4886
Exp/Cntr=0.3,0.1

Type RM Length L Ch R = 1,2336,347,347,347
BEGIN DESCRIPTION:
Alkali Creek Trib 04-01 4.5
END DESCRIPTION:
XS GIS Cut Line= 4
      1360538.91      6957580.13      1361149.32      6958307.27
      1361980.92      6958319.42      1362434.42      6957203.84
#Sta/Elev= 30
  3324.1 2000.39  3398.3 1997.97  3440.0 1998.98  3504.1 1995.47  3540.1 1996.57
  3582.4 1992.67  3688.5 1991.92  3739.1 1988.96  3817.2 1990.16  3850.3 1987.96
  4093.0 1986.85  4185.4 1991.24  4256.9 1984.40  4667.9 1983.42  4668.2 1982.92
  4672.1 1983.42  4819.2 1985.29  4849.2 1983.47  4909.2 1986.53  4969.2 1984.50
  5108.6 1985.79  5179.6 1990.58  5257.2 1988.13  5564.8 1991.90  5581.3 1994.69
  5596.9 1999.83  5608.0 2001.81  5656.1 1994.81  5891.2 1996.65  6309.4 2004.26
#Mann=8,-1,0
  3324.1   0.045       0  3850.3   0.035       0  4667.9   0.035       0
  4672.1   0.035       0  5564.8   0.045       0  5581.3    0.07       0
  5596.9   0.035       0  5891.2    0.07       0
Bank Sta=4667.9,4672.1
Exp/Cntr=0.3,0.1

Type RM Length L Ch R = 1,1989,424,424,424
BEGIN DESCRIPTION:
Alkali Creek Trib 04-01 4.0
END DESCRIPTION:
XS GIS Cut Line= 4
      1360589.22      6957709.02      1361538.92      6958862.08
      1361912.15      6958552.78      1362453.81      6957495.50
#Sta/Elev= 30
  3154.6 1996.31  3221.6 1996.55  3264.7 1992.72  3371.5 1991.80  3421.0 1988.86
  3477.2 1990.09  3513.1 1987.90  3612.6 1989.00  3789.8 1985.36  3797.6 1990.60
  3826.3 1991.32  3917.6 1984.71  4022.5 1985.05  4588.8 1983.42  4726.5 1982.45
  4755.2 1984.83  4859.0 1981.92  4958.9 1981.74  4959.2 1981.24  4963.1 1981.74
  5337.8 1985.18  5397.1 1985.98  5419.4 1988.23  5435.9 1986.89  5474.7 1990.80
  5644.1 1988.86  5868.7 1992.67  5963.1 1996.24  6044.0 1996.40  6321.1 2000.10
#Mann=9,-1,0
  3154.6   0.045       0  3513.1   0.035       0  4022.5   0.045       0
  4588.8    0.07       0  4859.0   0.045       0  4958.9   0.045       0
  4963.1   0.045       0  5337.8   0.035       0  6044.0    0.07       0
Bank Sta=4958.9,4963.1
Exp/Cntr=0.3,0.1

Type RM Length L Ch R = 1,1565,565,565,565
BEGIN DESCRIPTION:
Alkali Creek Trib 04-01 3.0
END DESCRIPTION:
XS GIS Cut Line= 4
      1360667.35      6957941.66      1361632.64      6959097.92
      1361972.92      6958733.34      1363704.97      6957288.03
#Sta/Elev= 30
  3295.0 1989.29  3333.1 1990.59  3358.6 1988.41  3602.9 1987.26  3674.1 1991.60
  3766.5 1985.53  3866.0 1985.20  4567.3 1983.34  4674.9 1982.87  4697.0 1984.67
  4738.7 1981.40  4951.6 1981.87  4977.4 1979.55  4977.7 1979.05  4981.7 1979.55
  5017.3 1980.20  5156.8 1982.48  5312.6 1981.27  5347.8 1983.56  5390.7 1982.26
  5845.3 1988.91  6001.1 1991.56  6036.3 1994.07  6100.1 1992.10  6334.3 1994.76
  6451.5 1998.94  7193.4 2018.97  7229.8 2017.43  7285.8 2021.66  7555.8 2026.96
#Mann=9,-1,0
  3295.0   0.045       0  3358.6   0.035       0  3866.0   0.045       0
  4567.3    0.07       0  4977.4    0.07       0  4981.7    0.07       0
  5017.3   0.045       0  5845.3   0.035       0  6451.5    0.07       0
Bank Sta=4977.4,4981.7
Exp/Cntr=0.3,0.1

Type RM Length L Ch R = 1,1000,500,500,500
BEGIN DESCRIPTION:
Alkali Creek Trib 04-01 2.0
END DESCRIPTION:
XS GIS Cut Line= 3
      1361105.00      6960138.00      1362183.64      6959266.35
      1363805.02      6957287.98
#Sta/Elev= 30
  3613.2 2000.54  3646.8 1995.32  3754.7 1995.61  3861.9 1989.67  3925.8 1991.13
  4158.8 1982.57  4352.7 1979.53  4395.9 1980.02  4416.7 1983.16  4445.5 1975.53
  4470.0 1975.43  4470.5 1974.93  4478.4 1975.43  4509.4 1976.29  4551.8 1984.39
  4587.8 1985.42  4623.0 1979.51  5002.7 1978.93  6110.2 1991.27  6257.4 1994.99
  6286.1 1997.75  6413.9 1995.40  6456.9 1998.99  6630.1 2002.62  6953.6 2013.36
  7014.8 2013.49  7248.8 2019.28  7373.4 2024.61  7402.1 2023.48  7557.9 2027.14
#Mann=10,-1,0
  3613.2   0.035       0  3646.8   0.045       0  4158.8    0.07       0
  4470.0    0.07       0  4478.4    0.07       0  5002.7   0.045       0
  6110.2   0.035       0  6630.1    0.07       0  7014.8   0.035       0
  7248.8    0.07       0
Bank Sta=4470,4478.4
Exp/Cntr=0.3,0.1

Type RM Length L Ch R = 1,500,0,0,0
BEGIN DESCRIPTION:
Alkali Creek Trib 04-01 1.0
END DESCRIPTION:
XS GIS Cut Line= 3
      1361304.96      6960188.02      1362260.57      6959643.63
      1363205.01      6958637.99
#Sta/Elev= 30
  3900.2 1998.53  3908.2 1998.00  3913.9 1992.75  3935.5 1989.08  3973.0 1986.28
  3991.8 1988.86  4003.8 1990.78  4156.0 1988.63  4230.9 1984.55  4411.8 1981.41
  4497.8 1978.41  4596.9 1977.75  4661.7 1981.04  4693.4 1978.35  4715.0 1979.27
  4720.8 1981.69  4741.3 1978.87  4834.7 1976.97  4835.2 1976.47  4843.1 1976.97
  4948.4 1977.36  5001.0 1977.22  5082.9 1978.16  5131.9 1978.70  5232.1 1978.82
  5286.4 1979.02  5785.4 1983.83  6153.2 1995.77  6195.7 1994.61  6379.6 1998.47
#Mann=13,-1,0
  3900.2   0.035       0  3991.8   0.045       0  4411.8    0.07       0
  4497.8   0.045       0  4741.3    0.07       0  4834.7   0.045       0
  4843.1    0.07       0  4948.4   0.045       0  5001.0    0.07       0
  5082.9   0.035       0  5131.9    0.07       0  5232.1   0.035       0
  5286.4   0.045       0
Bank Sta=4834.7,4843.1
Exp/Cntr=0.3,0.1

Chan Stop Cuts=-1