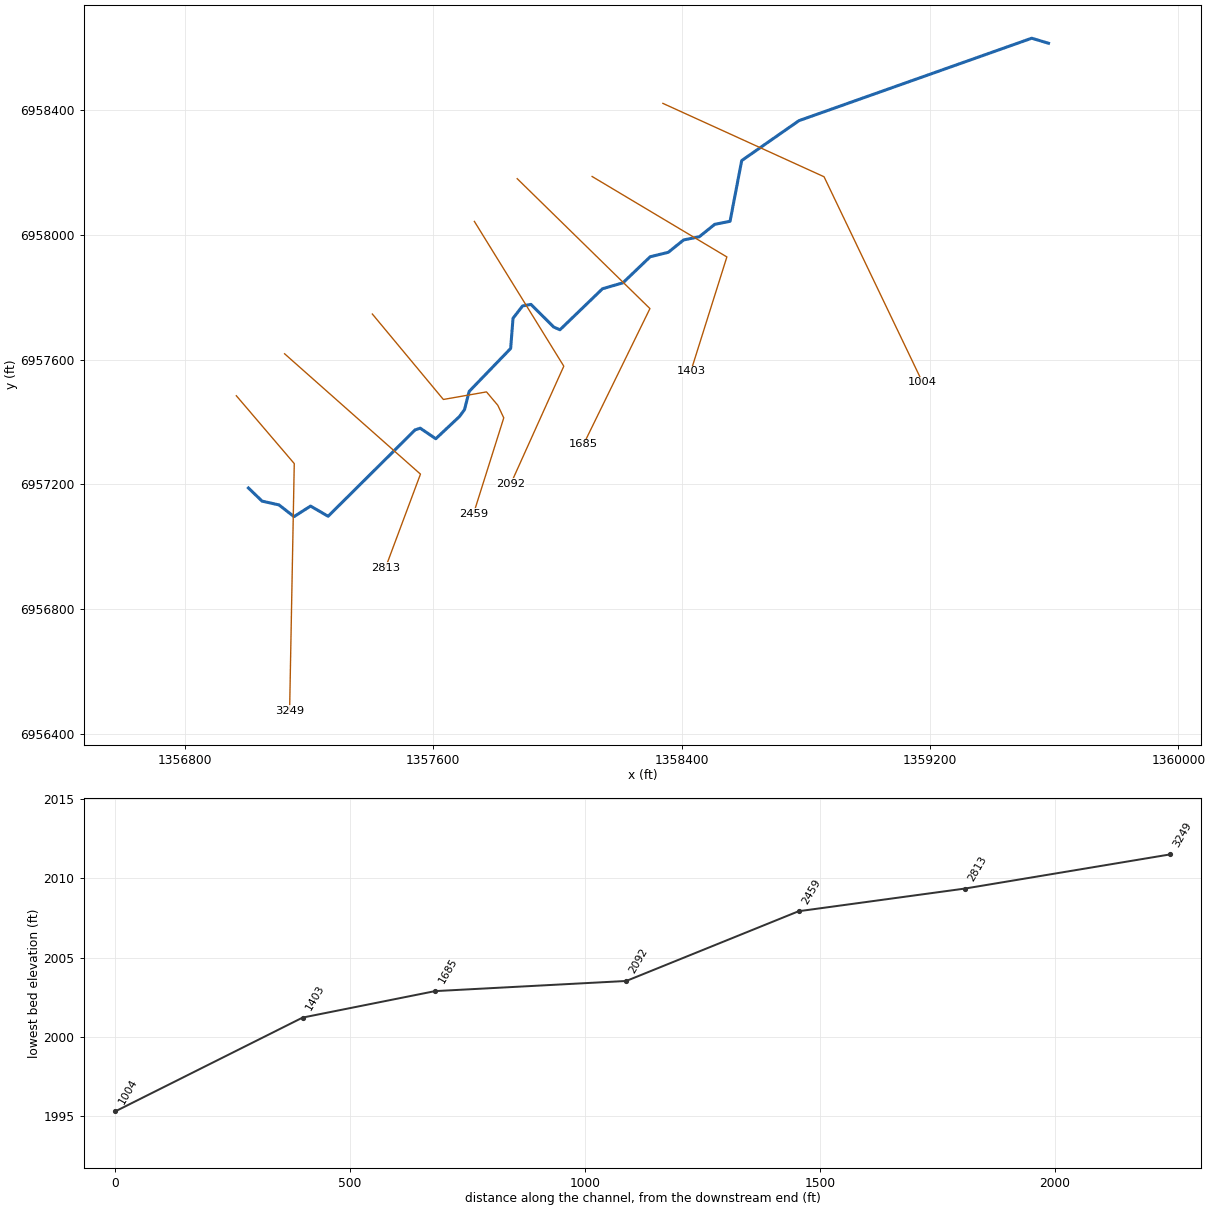
--- Alkali Creek Trib 04-02.prj (project) ---

Proj Title=Alkali Creek Trib 04-02 Base Level Engineering
Current Plan=p01
Default Exp/Contr=0.3,0.1
English Units
Geom File=g01
Flow File=f01
Plan File=p01
BEGIN DESCRIPTION:
Alkali Creek Trib 04-02
END DESCRIPTION:

--- Alkali Creek Trib 04-02.p01 (plan) ---

Plan Title=Multiple Run
Short Identifier=Multiple
Geom File=g01
Flow File=f01
Subcritical Flow
K Sum by GR= 0
Std Step Tol= 0.01
Critical Tol= 0.01
Num of Std Step Trials= 20
Max Error Tol= 0.3
Flow Tol Ratio= 0.001
Split Flow NTrial= 30
Split Flow Tol= 0.02
Split Flow Ratio= 0.02
Log Output Level= 0
Friction Slope Method= 1
Unsteady Friction Slope Method= 2
Unsteady Bridges Friction Slope Method= 1
Parabolic Critical Depth
Global Vel Dist=  1 , 1 , 1
Global Log Level= 0
CheckData=True
Encroach Param= -1, 0, 0, 0
BEGIN DESCRIPTION:
Multiple Run
END DESCRIPTION:

--- Alkali Creek Trib 04-02.f01 (steady flow) ---

Flow Title=Multiple
Number of Profiles=7
Profile Names=10-year,25-year,50-year,1pct_min,100-year,1pct_plu,500-year
River Rch & RM= Alkali Creek Tri,Reach-1,3249
     169     232     283     172     343     685     510
River Rch & RM= Alkali Creek Tri,Reach-1,1004
     179     246     300     183     365     727     544
Boundary for River Rch & Prof#=Alkali Creek Tri,Reach-1,1
Up Type=0
Dn Type=3
Dn Slope=0.005
Boundary for River Rch & Prof#=Alkali Creek Tri,Reach-1,2
Up Type=0
Dn Type=3
Dn Slope=0.005
Boundary for River Rch & Prof#=Alkali Creek Tri,Reach-1,3
Up Type=0
Dn Type=3
Dn Slope=0.005
Boundary for River Rch & Prof#=Alkali Creek Tri,Reach-1,4
Up Type=0
Dn Type=3
Dn Slope=0.005
Boundary for River Rch & Prof#=Alkali Creek Tri,Reach-1,5
Up Type=0
Dn Type=3
Dn Slope=0.005
Boundary for River Rch & Prof#=Alkali Creek Tri,Reach-1,6
Up Type=0
Dn Type=3
Dn Slope=0.005
Boundary for River Rch & Prof#=Alkali Creek Tri,Reach-1,7
Up Type=0
Dn Type=3
Dn Slope=0.005

--- Alkali Creek Trib 04-02.g01 (geometry) ---

Geom Title=Existing Conditions

River Reach=Alkali Creek Tri,Reach-1
Reach XY= 30
      1357005.00      6957188.00      1357048.86      6957145.88
      1357103.42      6957133.68      1357151.77      6957096.21
      1357205.00      6957129.96      1357261.67      6957097.29
      1357541.67      6957374.35      1357558.33      6957379.84
      1357608.35      6957346.00      1357685.21      6957417.83
      1357701.02      6957439.62      1357715.78      6957497.68
      1357849.48      6957635.58      1357857.15      6957732.52
      1357887.88      6957771.99      1357914.86      6957777.06
      1357988.33      6957704.26      1358008.33      6957695.61
      1358145.32      6957827.22      1358211.04      6957846.18
      1358298.95      6957929.84      1358357.19      6957944.10
      1358406.72      6957983.84      1358457.20      6957994.08
      1358506.72      6958033.84      1358556.12      6958043.60
      1358593.62      6958238.41      1358778.08      6958366.45
      1359527.60      6958630.93      1359581.79      6958614.79

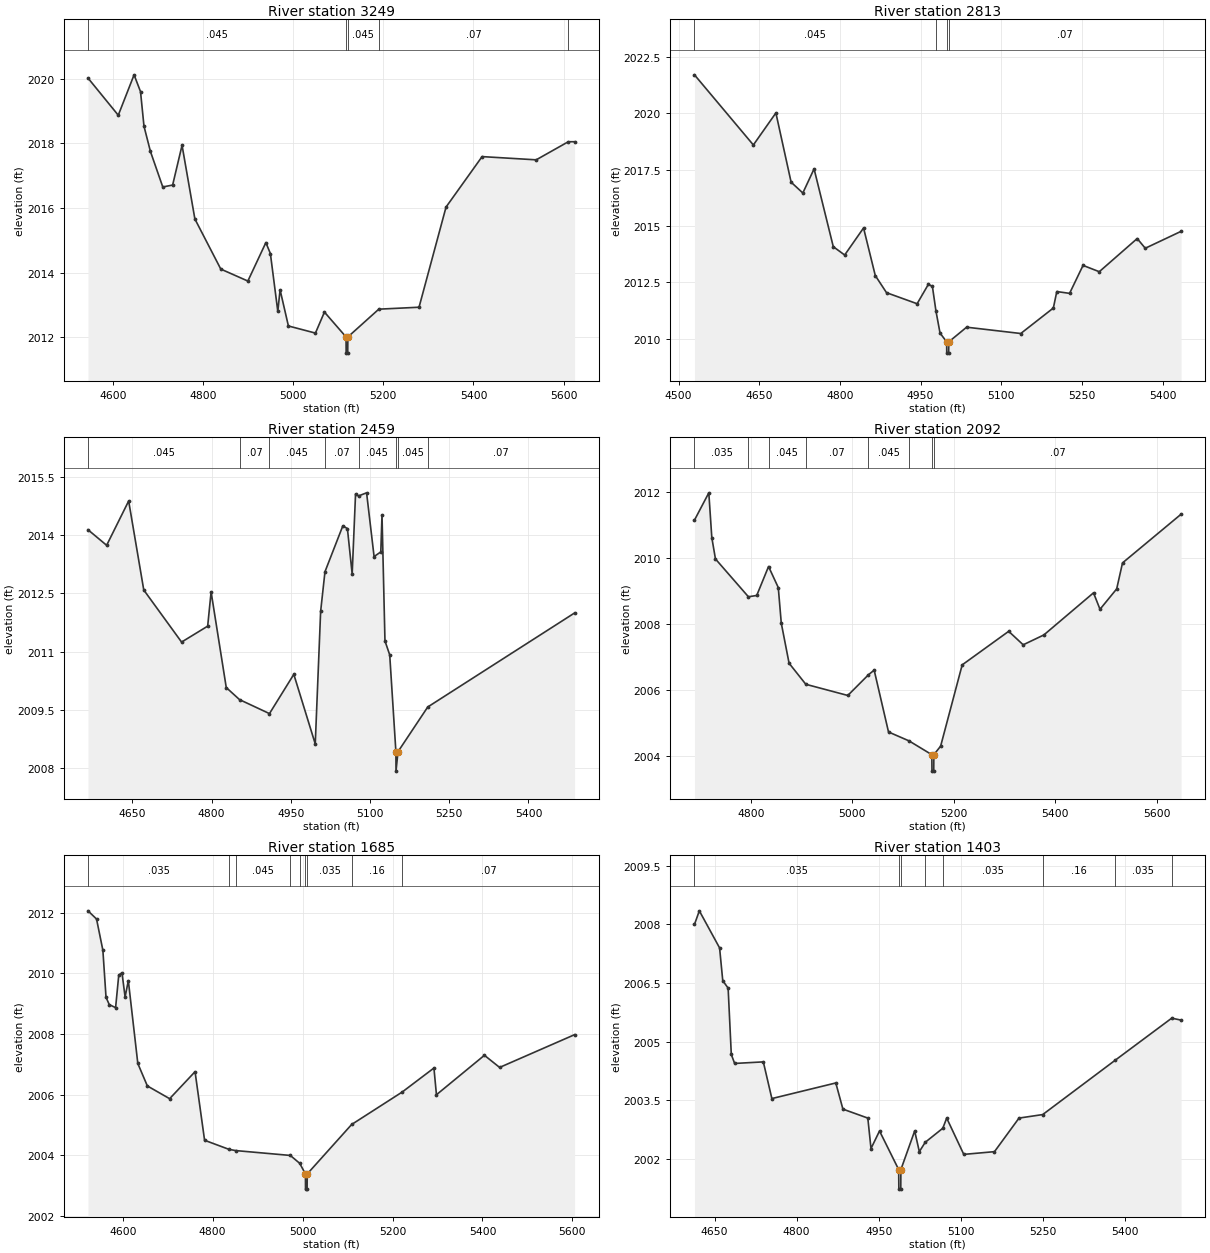
Type RM Length L Ch R = 1,3249,436,436,436
BEGIN DESCRIPTION:
Alkali Creek Trib 04-02  6.0
END DESCRIPTION:
XS GIS Cut Line= 3
      1356966.11      6957483.86      1357152.58      6957266.31
      1357137.57      6956472.68
#Sta/Elev= 30
  4544.3 2020.02  4611.5 2018.87  4646.6 2020.12  4660.9 2019.60  4668.6 2018.53
  4682.9 2017.75  4710.3 2016.65  4732.2 2016.71  4753.1 2017.94  4781.6 2015.66
  4839.1 2014.11  4899.2 2013.74  4939.2 2014.93  4949.2 2014.59  4965.7 2012.80
  4970.7 2013.47  4989.2 2012.35  5049.2 2012.13  5069.2 2012.78  5117.2 2012.01
  5117.4 2011.51  5120.9 2011.51  5121.2 2012.01  5189.9 2012.87  5279.2 2012.93
  5339.2 2016.03  5419.2 2017.59  5539.3 2017.49  5610.6 2018.05  5624.6 2018.05
#Mann=5,-1,0
  4544.3   0.045       0  5117.2   0.045       0  5121.2   0.045       0
  5189.9    0.07       0  5610.6   0.045       0
Bank Sta=5117.2,5121.2
Exp/Cntr=0.3,0.1

Type RM Length L Ch R = 1,2813,354,354,354
BEGIN DESCRIPTION:
Alkali Creek Trib 04-02  5.0
END DESCRIPTION:
XS GIS Cut Line= 3
      1357121.47      6957618.54      1357559.01      6957232.48
      1357446.22      6956931.64
#Sta/Elev= 30
  4529.6 2021.70  4639.1 2018.59  4681.0 2020.01  4709.3 2016.94  4731.1 2016.46
  4752.0 2017.53  4787.7 2014.08  4808.9 2013.71  4844.0 2014.91  4865.8 2012.80
  4886.7 2012.04  4943.6 2011.55  4964.5 2012.41  4972.0 2012.32  4978.6 2011.23
  4986.2 2010.25  4998.5 2009.86  4998.7 2009.36  5002.2 2009.36  5002.5 2009.86
  5035.6 2010.51  5136.3 2010.23  5196.9 2011.36  5203.3 2012.09  5227.1 2012.01
  5252.1 2013.25  5282.3 2012.97  5352.8 2014.44  5367.8 2014.01  5434.4 2014.76
#Mann=4,-1,0
  4529.6   0.045       0  4978.6    0.07       0  4998.5    0.07       0
  5002.5    0.07       0
Bank Sta=4998.5,5002.5
Exp/Cntr=0.3,0.1

Type RM Length L Ch R = 1,2459,367,367,367
BEGIN DESCRIPTION:
Alkali Creek Trib 04-02  4.0
END DESCRIPTION:
XS GIS Cut Line= 6
      1357404.04      6957746.10      1357632.79      6957471.99
      1357771.68      6957496.30      1357808.14      6957453.33
      1357827.31      6957412.91      1357730.01      6957105.66
#Sta/Elev= 30
  4566.0 2014.14  4601.3 2013.74  4643.0 2014.88  4671.6 2012.59  4743.2 2011.25
  4792.6 2011.66  4799.1 2012.54  4827.8 2010.08  4852.9 2009.77  4909.6 2009.41
  4955.7 2010.42  4996.3 2008.63  5006.5 2012.04  5014.7 2013.06  5048.5 2014.24
  5057.2 2014.17  5066.2 2013.00  5072.6 2015.06  5078.2 2015.01  5093.5 2015.09
  5107.7 2013.45  5120.4 2013.57  5122.7 2014.52  5128.3 2011.28  5137.3 2010.92
  5149.0 2008.43  5149.2 2007.93  5153.0 2008.43  5209.3 2009.58  5487.4 2012.00
#Mann=8,-1,0
  4566.0   0.045       0  4852.9    0.07       0  4909.6   0.045       0
  5014.7    0.07       0  5078.2   0.045       0  5149.0   0.045       0
  5153.0   0.045       0  5209.3    0.07       0
Bank Sta=5149,5153
Exp/Cntr=0.3,0.1

Type RM Length L Ch R = 1,2092,407,407,407
BEGIN DESCRIPTION:
Alkali Creek Trib 04-02 3.0
END DESCRIPTION:
XS GIS Cut Line= 3
      1357732.68      6958043.22      1358020.65      6957578.75
      1357850.31      6957202.28
#Sta/Elev= 30
  4688.5 2011.16  4716.8 2011.99  4722.7 2010.63  4729.9 2009.98  4794.9 2008.83
  4811.3 2008.87  4834.6 2009.75  4853.8 2009.11  4859.7 2008.03  4875.1 2006.81
  4908.1 2006.17  4990.9 2005.83  5031.7 2006.46  5042.9 2006.60  5071.2 2004.72
  5111.6 2004.45  5156.6 2004.03  5156.9 2003.53  5160.4 2003.53  5160.6 2004.03
  5174.0 2004.29  5216.5 2006.76  5308.2 2007.78  5336.8 2007.37  5377.6 2007.67
  5475.5 2008.95  5488.3 2008.45  5521.2 2009.07  5532.7 2009.86  5648.2 2011.34
#Mann=8,-1,0
  4688.5   0.035       0  4794.9    0.07       0  4834.6   0.045       0
  4908.1    0.07       0  5031.7   0.045       0  5111.6    0.07       0
  5156.6    0.07       0  5160.6    0.07       0
Bank Sta=5156.6,5160.6
Exp/Cntr=0.3,0.1

Type RM Length L Ch R = 1,1685,282,282,282
BEGIN DESCRIPTION:
Alkali Creek Trib 04-02 2.0
END DESCRIPTION:
XS GIS Cut Line= 3
      1357870.62      6958180.34      1358298.06      6957763.55
      1358084.19      6957327.92
#Sta/Elev= 30
  4522.7 2012.06  4541.7 2011.79  4555.8 2010.76  4562.8 2009.21  4570.0 2008.97
  4584.1 2008.87  4591.1 2009.94  4598.3 2010.02  4605.2 2009.22  4612.4 2009.76
  4633.5 2007.03  4654.7 2006.29  4704.3 2005.87  4760.8 2006.76  4782.0 2004.50
  4836.4 2004.20  4851.3 2004.16  4972.7 2004.00  4993.6 2003.74  5006.3 2003.39
  5006.5 2002.89  5010.0 2002.89  5010.3 2003.39  5109.1 2005.02  5221.6 2006.09
  5292.1 2006.88  5297.7 2006.00  5404.4 2007.30  5438.2 2006.90  5605.0 2007.98
#Mann=9,-1,0
  4522.7   0.035       0  4836.4    0.07       0  4851.3   0.045       0
  4972.7    0.16       0  4993.6   0.035       0  5006.3   0.035       0
  5010.3   0.035       0  5109.1    0.16       0  5221.6    0.07       0
Bank Sta=5006.3,5010.3
Exp/Cntr=0.3,0.1

Type RM Length L Ch R = 1,1403,399,399,399
BEGIN DESCRIPTION:
Alkali Creek Trib 04-02  1.0
END DESCRIPTION:
XS GIS Cut Line= 3
      1358111.92      6958187.29      1358545.84      6957929.28
      1358430.00      6957562.99
#Sta/Elev= 30
  4613.3 2008.00  4622.2 2008.35  4659.2 2007.40  4665.0 2006.56  4674.8 2006.37
  4680.6 2004.67  4686.7 2004.44  4739.1 2004.48  4754.7 2003.54  4871.5 2003.94
  4884.5 2003.27  4930.0 2003.04  4935.8 2002.26  4951.4 2002.71  4986.4 2001.72
  4986.7 2001.22  4990.2 2001.22  4990.4 2001.72  5015.6 2002.71  5024.1 2002.18
  5034.9 2002.42  5067.0 2002.78  5074.1 2003.04  5105.3 2002.11  5161.4 2002.18
  5206.2 2003.04  5249.5 2003.13  5381.7 2004.52  5485.2 2005.60  5502.3 2005.55
#Mann=8,-1,0
  4613.3   0.035       0  4986.4   0.035       0  4990.4   0.035       0
  5034.9    0.16       0  5067.0   0.035       0  5249.5    0.16       0
  5381.7   0.035       0  5485.2    0.07       0
Bank Sta=4986.4,4990.4
Exp/Cntr=0.3,0.1

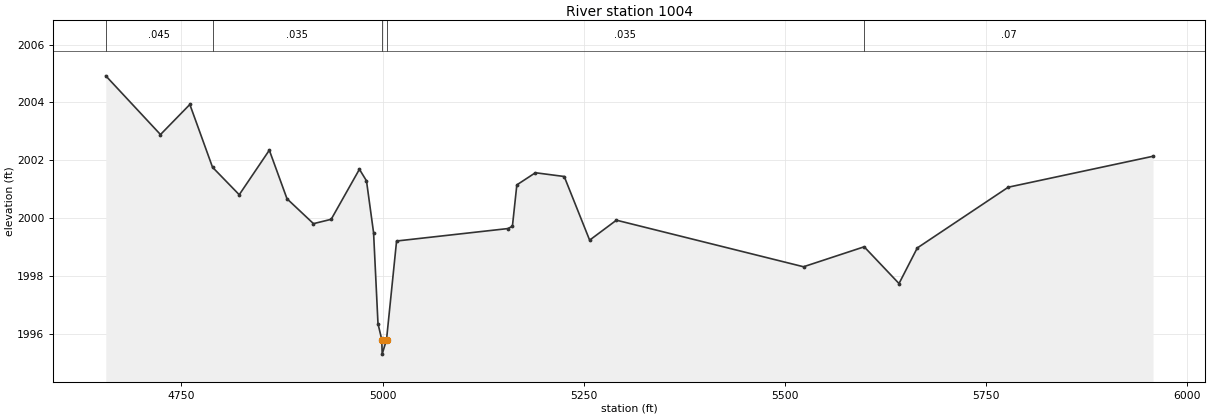
Type RM Length L Ch R = 1,1004,0,0,0
BEGIN DESCRIPTION:
Alkali Creek Trib 04-02 0.5
END DESCRIPTION:
XS GIS Cut Line= 3
      1358339.84      6958421.91      1358858.84      6958186.48
      1359176.07      6957526.80
#Sta/Elev= 30
  4655.9 2004.92  4723.9 2002.89  4760.4 2003.93  4788.6 2001.76  4821.8 2000.81
  4859.2 2002.35  4881.2 2000.67  4914.1 1999.81  4936.1 1999.96  4971.2 2001.69
  4980.0 2001.29  4988.8 1999.50  4994.3 1996.35  4999.0 1995.80  4999.5 1995.30
  5004.9 1995.80  5017.4 1999.21  5155.7 1999.64  5161.4 1999.72  5166.9 2001.15
  5190.0 2001.57  5225.8 2001.44  5257.4 1999.24  5290.7 1999.93  5523.3 1998.32
  5598.7 1999.01  5642.0 1997.74  5664.7 1998.97  5777.8 2001.07  5957.8 2002.14
#Mann=5,-1,0
  4655.9   0.045       0  4788.6   0.035       0  4999.0   0.035       0
  5004.9   0.035       0  5598.7    0.07       0
Bank Sta=4999,5004.9
Exp/Cntr=0.3,0.1

Chan Stop Cuts=-1