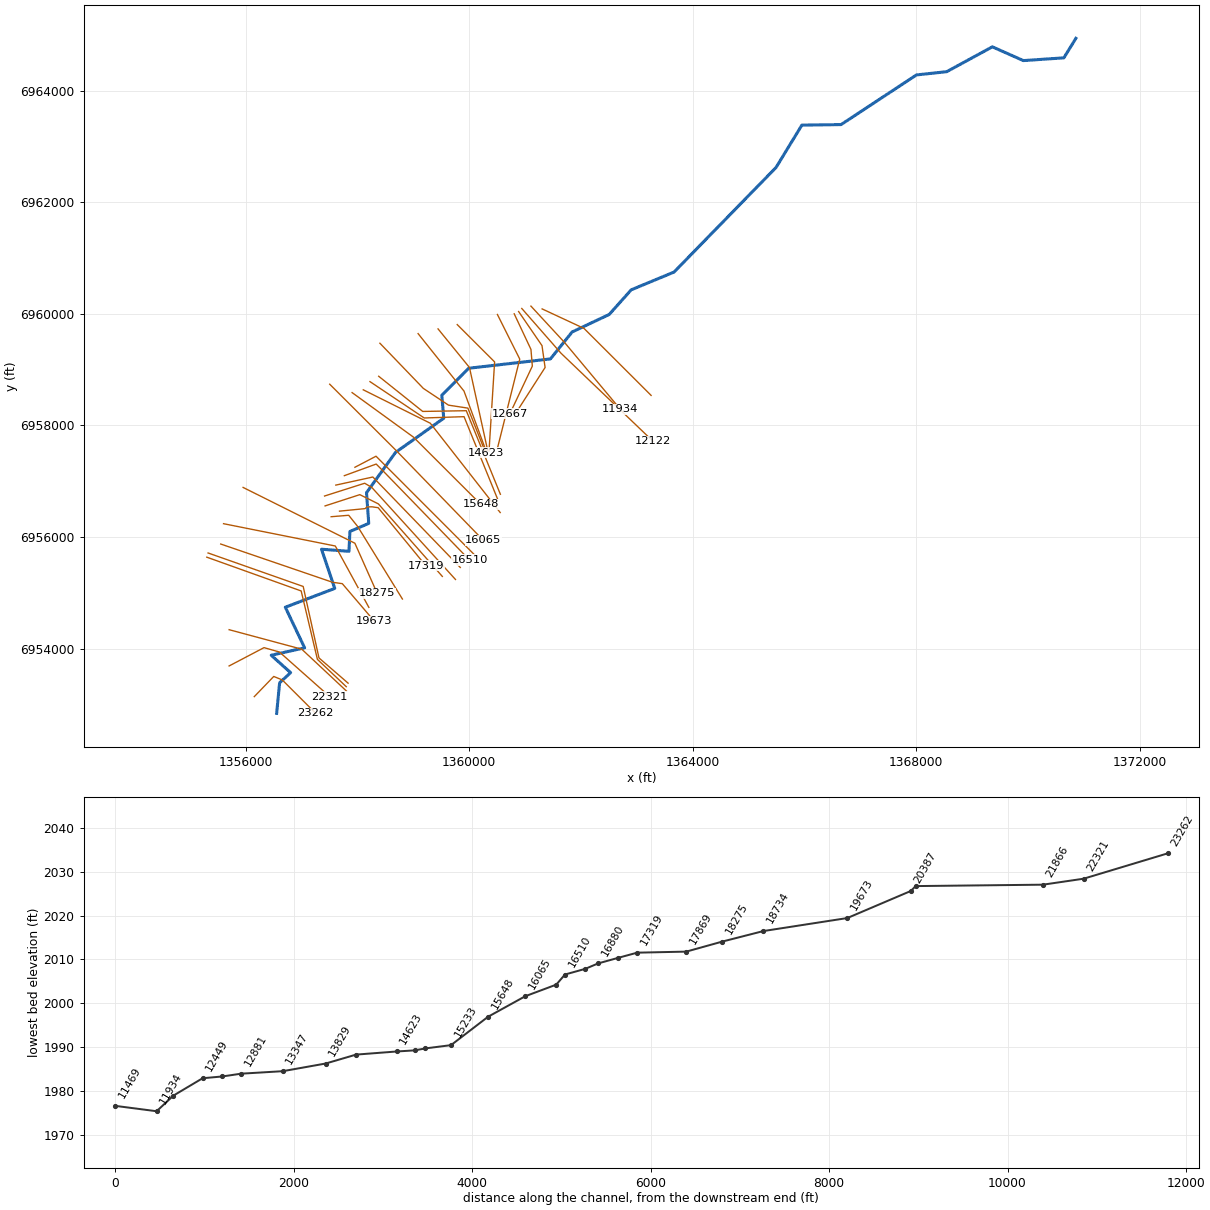
--- Alkali Creek Trib 04.prj (project) ---

Proj Title=Alkali Creek Trib 04 Base Level Engineering
Current Plan=p01
Default Exp/Contr=0.3,0.1
English Units
Geom File=g01
Flow File=f01
Plan File=p01
Y Axis Title=Elevation
X Axis Title(PF)=Main Channel Distance
X Axis Title(XS)=Station
BEGIN DESCRIPTION:
Alkali Creek Trib 04
END DESCRIPTION:
DSS Export Rating Curves= 0
DSS Export Rating Curve Sorted= 0
DSS Export Volume Flow Curves= 0
DXF OffsetX= 0
DXF OffsetY= 0
DXF ScaleX= 1
DXF ScaleY= 10

--- Alkali Creek Trib 04.p01 (plan) ---

Plan Title=Multiple Run
Short Identifier=Multiple
Geom File=g01
Flow File=f01
Subcritical Flow
K Sum by GR= 0
Std Step Tol= 0.01
Critical Tol= 0.01
Num of Std Step Trials= 20
Max Error Tol= 0.3
Flow Tol Ratio= 0.001
Split Flow NTrial= 30
Split Flow Tol= 0.02
Split Flow Ratio= 0.02
Log Output Level= 0
Friction Slope Method= 1
Unsteady Friction Slope Method= 2
Unsteady Bridges Friction Slope Method= 1
Parabolic Critical Depth
Global Vel Dist=  1 , 1 , 1
Global Log Level= 0
CheckData=True
Encroach Param= -1, 0, 0, 0
BEGIN DESCRIPTION:
Multiple Run
END DESCRIPTION:

--- Alkali Creek Trib 04.f01 (steady flow) ---

Flow Title=Multiple
Program Version=4.10
Number of Profiles= 7
Profile Names=10-year,25-year,50-year,1pct_min,100-year,1pct_plu,500-year
River Rch & RM=Alkali Creek Tri,Reach-1         ,23262
     347     495     619     385     767    1531    1196
River Rch & RM=Alkali Creek Tri,Reach-1         ,18275
     371     531     665     414     826    1649    1292
River Rch & RM=Alkali Creek Tri,Reach-1         ,16065
     409     587     738     461     919    1834    1445
River Rch & RM=Alkali Creek Tri,Reach-1         ,10575
     637     933    1190     752    1500    2993    2418
Boundary for River Rch & Prof#=Alkali Creek Tri,Reach-1         , 1
Up Type= 0
Dn Type= 3
Dn Slope=0.005
Boundary for River Rch & Prof#=Alkali Creek Tri,Reach-1         , 2
Up Type= 0
Dn Type= 3
Dn Slope=0.005
Boundary for River Rch & Prof#=Alkali Creek Tri,Reach-1         , 3
Up Type= 0
Dn Type= 3
Dn Slope=0.005
Boundary for River Rch & Prof#=Alkali Creek Tri,Reach-1         , 4
Up Type= 0
Dn Type= 3
Dn Slope=0.005
Boundary for River Rch & Prof#=Alkali Creek Tri,Reach-1         , 5
Up Type= 0
Dn Type= 3
Dn Slope=0.005
Boundary for River Rch & Prof#=Alkali Creek Tri,Reach-1         , 6
Up Type= 0
Dn Type= 3
Dn Slope=0.005
Boundary for River Rch & Prof#=Alkali Creek Tri,Reach-1         , 7
Up Type= 0
Dn Type= 3
Dn Slope=0.005
DSS Import GetInterval= 0
DSS Import GetPeak= 0
DSS Import FillOption= 0

--- Alkali Creek Trib 04.g01 (geometry) ---

Geom Title=Existing Conditions

River Reach=Alkali Creek Tri,Reach-1
Reach XY= 30
      1356555.00      6952838.00      1356608.53      6953386.55
      1356805.42      6953567.56      1356457.92      6953880.02
      1357055.54      6954012.87      1356710.27      6954740.62
      1357594.98      6955077.94      1357357.91      6955780.09
      1357849.53      6955743.11      1357865.96      6956098.38
      1358203.02      6956243.62      1358163.12      6956794.05
      1358681.48      6957515.01      1359544.54      6958128.18
      1359510.46      6958540.45      1359991.78      6959024.38
      1361453.54      6959191.54      1361841.76      6959674.39
      1362505.00      6959988.00      1362898.95      6960429.84
      1363665.12      6960748.34      1365491.37      6962624.79
      1365952.53      6963382.55      1366653.45      6963391.75
      1368002.71      6964282.16      1368543.05      6964339.92
      1369360.94      6964785.75      1369915.50      6964539.20
      1370639.66      6964587.95      1370855.00      6964938.00

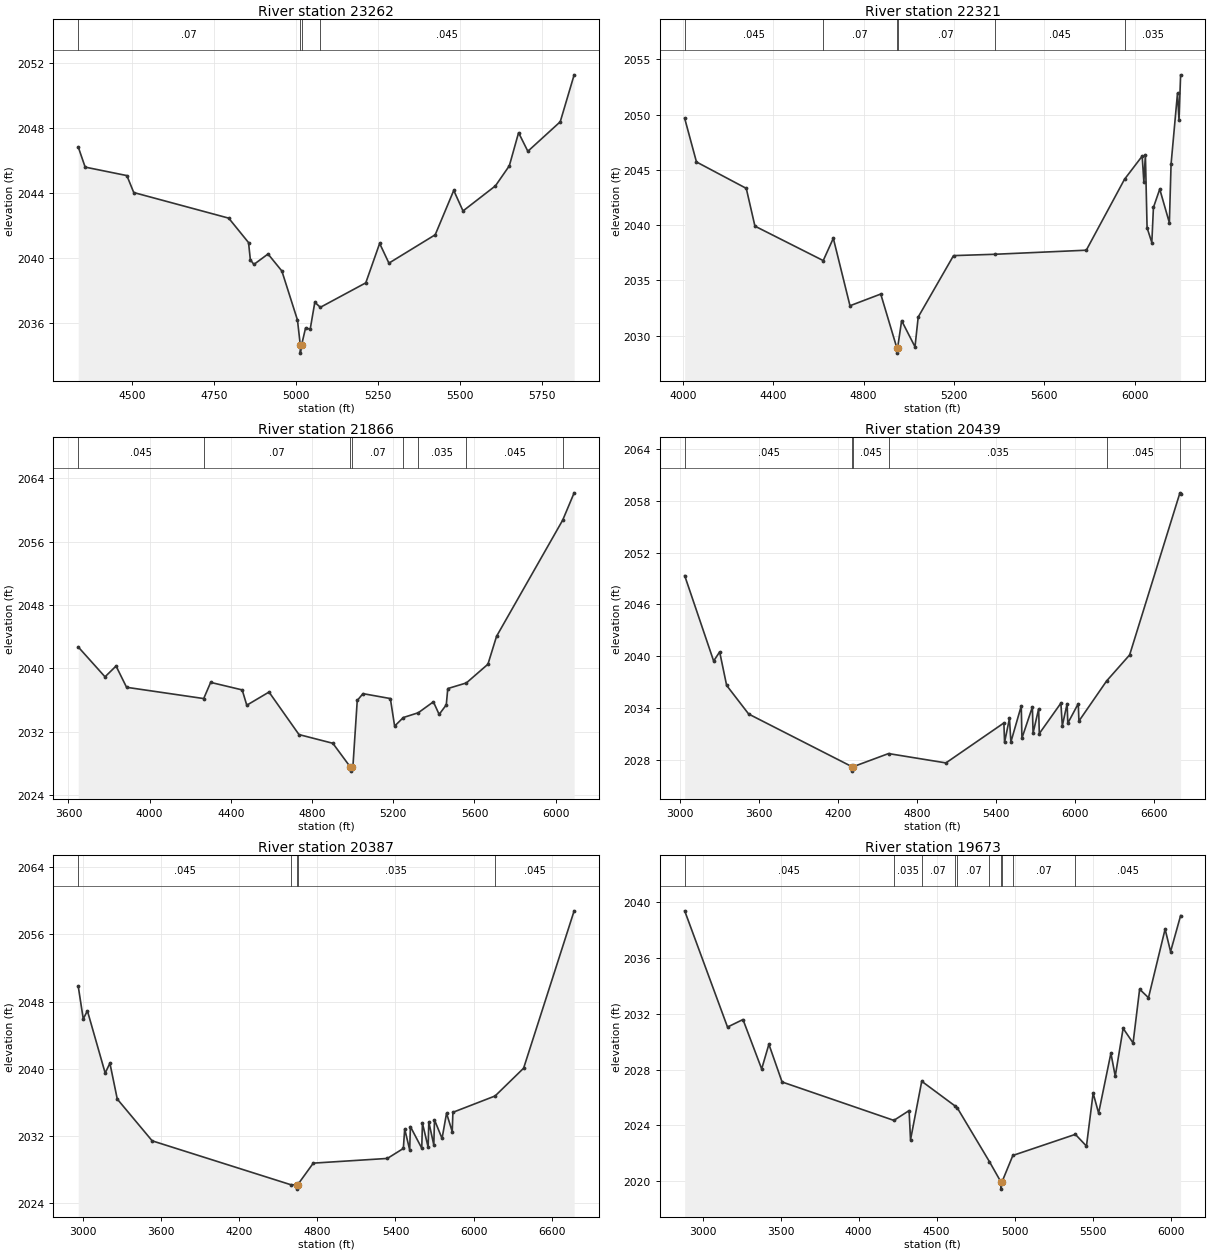
Type RM Length L Ch R = 1,23262,941,941,941
BEGIN DESCRIPTION:
Alkali Creek Trib 04 33.0
END DESCRIPTION:
XS GIS Cut Line= 5
      1356155.01      6953138.01      1356503.17      6953499.82
      1356655.00      6953438.00      1356760.85      6953332.15
      1357255.02      6952837.98
#Sta/Elev= 30
  4334.5 2046.83  4355.7 2045.59  4483.1 2045.07  4504.1 2044.03  4794.1 2042.46
  4854.7 2040.96  4860.2 2039.91  4871.0 2039.62  4914.2 2040.26  4956.4 2039.22
  5004.1 2036.21  5012.7 2034.68  5012.9 2034.18  5016.7 2034.68  5028.8 2035.72
  5043.0 2035.65  5057.1 2037.30  5074.0 2036.99  5212.7 2038.49  5255.1 2040.91
  5283.4 2039.70  5424.8 2041.44  5481.4 2044.16  5509.7 2042.90  5608.7 2044.44
  5651.1 2045.67  5679.4 2047.70  5707.7 2046.56  5806.6 2048.37  5849.1 2051.25
#Mann=4,-1,0
  4334.5    0.07       0  5012.7    0.07       0  5016.7    0.07       0
  5074.0   0.045       0
Bank Sta=5012.7,5016.7
Exp/Cntr=0.3,0.1

Type RM Length L Ch R = 1,22321,455,455,455
BEGIN DESCRIPTION:
Alkali Creek Trib 04 32.0
END DESCRIPTION:
XS GIS Cut Line= 4
      1355705.03      6953688.02      1356329.56      6954016.32
      1356605.00      6953938.00      1357505.02      6953137.99
#Sta/Elev= 30
  4008.1 2049.67  4060.3 2045.72  4280.8 2043.33  4319.2 2039.91  4621.6 2036.79
  4666.3 2038.81  4740.1 2032.70  4876.3 2033.76  4947.2 2028.91  4947.5 2028.41
  4951.2 2028.91  4968.8 2031.35  5028.0 2028.98  5042.2 2031.68  5198.6 2037.24
  5380.4 2037.36  5786.5 2037.73  5955.7 2044.15  6034.0 2046.25  6041.5 2043.90
  6048.2 2046.38  6055.7 2039.76  6076.7 2038.42  6083.8 2041.60  6111.8 2043.26
  6154.4 2040.21  6161.9 2045.52  6190.4 2051.95  6197.1 2049.52  6204.2 2053.61
#Mann=6,-1,0
  4008.1   0.045       0  4621.6    0.07       0  4947.2    0.07       0
  4951.2    0.07       0  5380.4   0.045       0  5955.7   0.035       0
Bank Sta=4947.2,4951.2
Exp/Cntr=0.3,0.1

Type RM Length L Ch R = 1,21866,1427,1427,1427
BEGIN DESCRIPTION:
Alkali Creek Trib 04 31.0
END DESCRIPTION:
XS GIS Cut Line= 3
      1355705.03      6954337.99      1357005.00      6953988.00
      1357804.97      6953238.03
#Sta/Elev= 30
  3648.2 2042.71  3780.2 2038.94  3834.6 2040.30  3886.4 2037.62  4266.3 2036.20
  4300.6 2038.24  4455.9 2037.29  4478.5 2035.36  4588.0 2037.02  4735.6 2031.66
  4902.4 2030.56  4989.1 2027.55  4989.6 2027.05  4994.6 2027.55  5001.5 2027.72
  5022.6 2035.96  5050.9 2036.82  5185.7 2036.20  5206.7 2032.73  5249.7 2033.81
  5323.2 2034.41  5397.7 2035.79  5426.0 2034.20  5461.2 2035.41  5468.5 2037.46
  5560.1 2038.17  5666.3 2040.53  5708.8 2044.05  6034.6 2058.70  6091.0 2062.14
#Mann=8,-1,0
  3648.2   0.045       0  4266.3    0.07       0  4989.1    0.07       0
  4994.6    0.07       0  5249.7   0.045       0  5323.2   0.035       0
  5560.1   0.045       0  6034.6   0.035       0
Bank Sta=4989.1,4994.6
Exp/Cntr=0.3,0.1

Type RM Length L Ch R = 1,20439,52,52,52
BEGIN DESCRIPTION:
Alkali Creek Trib 04 30.0
END DESCRIPTION:
XS GIS Cut Line= 4
      1355304.99      6955638.00      1356994.19      6955032.28
      1357284.41      6953806.36      1357800.73      6953316.42
#Sta/Elev= 30
  3034.8 2049.34  3254.8 2039.46  3300.4 2040.52  3353.5 2036.64  3520.9 2033.33
  4306.9 2027.23  4307.3 2026.73  4312.4 2027.23  4582.7 2028.76  5018.7 2027.68
  5458.8 2032.30  5464.0 2030.05  5501.1 2032.83  5512.0 2030.10  5590.8 2034.27
  5595.9 2030.54  5675.3 2034.15  5680.4 2031.13  5722.7 2033.92  5727.8 2031.07
  5891.7 2034.59  5902.5 2031.98  5939.1 2034.53  5944.2 2032.27  6023.6 2034.53
  6028.7 2032.52  6239.1 2037.16  6413.8 2040.17  6795.7 2058.91  6800.9 2058.81
#Mann=6,-1,0
  3034.8   0.045       0  4306.9   0.035       0  4312.4   0.045       0
  4582.7   0.035       0  6239.1   0.045       0  6795.7   0.035       0
Bank Sta=4306.9,4312.4
Exp/Cntr=0.3,0.1

Type RM Length L Ch R = 1,20387,714,714,714
BEGIN DESCRIPTION:
Alkali Creek Trib 04 29.5
END DESCRIPTION:
XS GIS Cut Line= 4
      1355328.50      6955713.15      1357030.00      6955113.00
      1357312.70      6953831.60      1357833.69      6953379.44
#Sta/Elev= 30
  2965.3 2049.84  3004.0 2045.93  3035.8 2046.90  3172.3 2039.47  3208.5 2040.65
  3265.1 2036.37  3532.9 2031.39  4596.0 2026.16  4643.0 2026.13  4643.5 2025.63
  4648.5 2026.13  4769.5 2028.73  5337.9 2029.29  5460.7 2030.48  5471.0 2032.81
  5509.5 2030.30  5514.7 2033.09  5602.0 2030.51  5607.2 2033.50  5650.9 2030.63
  5656.0 2033.65  5694.5 2030.89  5699.7 2033.89  5757.7 2031.67  5792.2 2034.68
  5835.9 2032.49  5841.0 2034.79  6164.9 2036.74  6383.7 2040.05  6771.6 2058.82
#Mann=5,-1,0
  2965.3   0.045       0  4596.0   0.035       0  4643.0   0.035       0
  4648.5   0.035       0  6164.9   0.045       0
Bank Sta=4643,4648.5
Exp/Cntr=0.3,0.1

Type RM Length L Ch R = 1,19673,939,939,939
BEGIN DESCRIPTION:
Alkali Creek Trib 04 29.0
END DESCRIPTION:
XS GIS Cut Line= 4
      1355554.56      6955873.41      1357555.00      6955188.00
      1357730.00      6955163.00      1358305.01      6954487.99
#Sta/Elev= 30
  2885.3 2039.36  3159.8 2031.04  3258.9 2031.58  3378.7 2028.04  3424.9 2029.81
  3509.4 2027.11  4225.8 2024.36  4323.4 2025.06  4332.6 2022.97  4404.4 2027.16
  4615.8 2025.41  4631.5 2025.27  4838.6 2021.40  4912.6 2019.94  4913.0 2019.44
  4918.1 2019.94  4988.3 2021.85  5388.9 2023.36  5460.0 2022.52  5502.8 2026.31
  5537.9 2024.88  5616.7 2029.17  5644.5 2027.52  5695.0 2030.95  5758.7 2029.90
  5800.7 2033.75  5857.5 2033.14  5964.0 2038.05  5999.1 2036.44  6063.4 2039.02
#Mann=10,-1,0
  2885.3   0.045       0  4225.8   0.035       0  4404.4    0.07       0
  4615.8    0.16       0  4631.5    0.07       0  4838.6   0.035       0
  4912.6    0.07       0  4918.1   0.035       0  4988.3    0.07       0
  5388.9   0.045       0
Bank Sta=4912.6,4918.1
Exp/Cntr=0.3,0.1

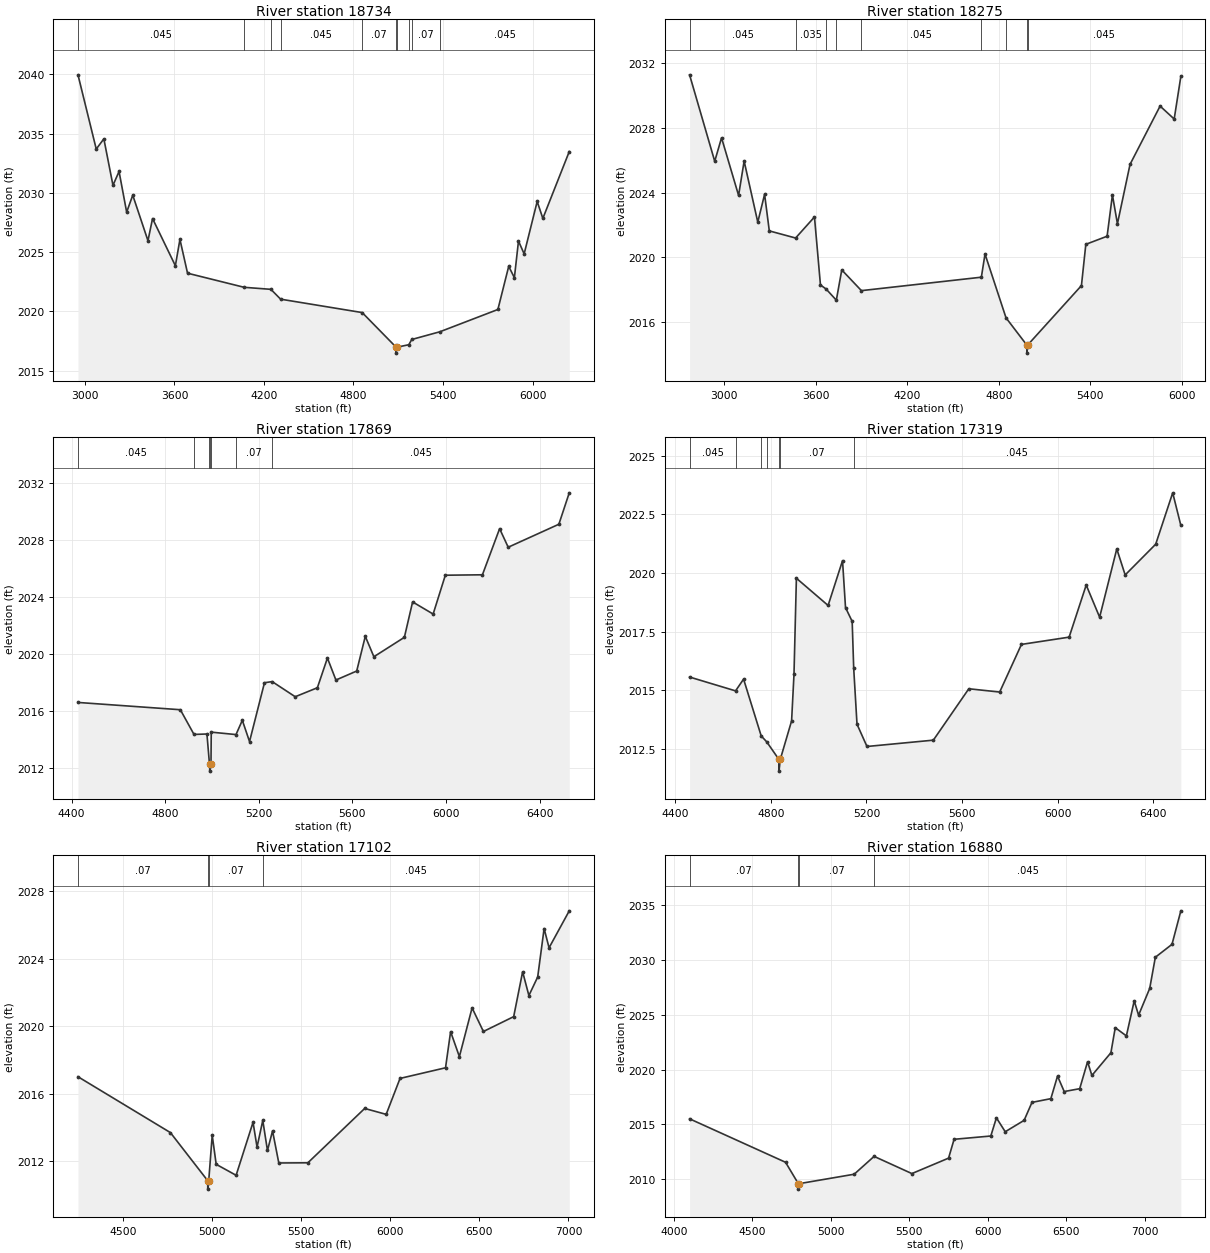
Type RM Length L Ch R = 1,18734,459,459,459
BEGIN DESCRIPTION:
Alkali Creek Trib 04 28.0
END DESCRIPTION:
XS GIS Cut Line= 3
      1355605.01      6956238.00      1357605.00      6955838.00
      1358205.00      6954738.00
#Sta/Elev= 30
  2953.5 2039.95  3075.9 2033.69  3126.9 2034.55  3188.0 2030.63  3228.8 2031.80
  3279.8 2028.37  3320.6 2029.80  3422.6 2025.96  3453.2 2027.83  3606.2 2023.85
  3636.8 2026.07  3687.8 2023.22  4067.4 2022.03  4246.4 2021.86  4311.6 2021.03
  4858.3 2019.90  5085.7 2016.98  5086.1 2016.48  5091.3 2016.98  5170.8 2017.19
  5190.5 2017.63  5378.6 2018.28  5767.7 2020.16  5840.3 2023.80  5878.3 2022.84
  5905.8 2025.93  5943.8 2024.85  6031.1 2029.27  6069.1 2027.84  6246.1 2033.48
#Mann=10,-1,0
  2953.5   0.045       0  4067.4   0.035       0  4246.4    0.07       0
  4311.6   0.045       0  4858.3    0.07       0  5085.7    0.07       0
  5091.3    0.07       0  5170.8   0.045       0  5190.5    0.07       0
  5378.6   0.045       0
Bank Sta=5085.7,5091.3
Exp/Cntr=0.3,0.1

Type RM Length L Ch R = 1,18275,406,406,406
BEGIN DESCRIPTION:
Alkali Creek Trib 04 27.0
END DESCRIPTION:
XS GIS Cut Line= 3
      1355955.02      6956887.99      1357955.00      6955888.00
      1358354.99      6954988.03
#Sta/Elev= 30
  2773.2 2031.28  2938.1 2025.94  2982.8 2027.39  3094.6 2023.83  3130.9 2025.95
  3220.4 2022.18  3265.1 2023.90  3295.9 2021.64  3468.3 2021.20  3592.1 2022.50
  3631.3 2018.30  3668.3 2018.05  3735.4 2017.36  3771.0 2019.23  3899.8 2017.95
  4686.2 2018.78  4710.2 2020.21  4847.9 2016.27  4984.0 2014.59  4984.5 2014.09
  4989.8 2014.59  5342.3 2018.26  5371.1 2020.81  5510.6 2021.31  5545.5 2023.86
  5578.3 2022.08  5661.0 2025.75  5858.0 2029.35  5950.4 2028.55  5994.1 2031.18
#Mann=9,-1,0
  2773.2   0.045       0  3468.3   0.035       0  3668.3   0.045       0
  3735.4    0.07       0  3899.8   0.045       0  4686.2    0.07       0
  4847.9   0.045       0  4984.0   0.045       0  4989.8   0.045       0
Bank Sta=4984,4989.8
Exp/Cntr=0.3,0.1

Type RM Length L Ch R = 1,17869,550,550,550
BEGIN DESCRIPTION:
Alkali Creek Trib 04 26.0
END DESCRIPTION:
XS GIS Cut Line= 4
      1357530.00      6956363.00      1357844.27      6956388.92
      1358005.00      6956188.00      1358805.02      6954887.97
#Sta/Elev= 30
  4427.5 2016.60  4864.9 2016.09  4923.2 2014.36  4978.5 2014.39  4988.8 2012.39
  4990.0 2012.29  4990.5 2011.79  4995.8 2012.29  4996.9 2014.52  5102.7 2014.35
  5129.7 2015.35  5160.5 2013.86  5224.3 2017.98  5257.2 2018.06  5355.7 2017.00
  5450.4 2017.63  5493.3 2019.71  5529.6 2018.17  5618.4 2018.80  5655.1 2021.23
  5691.8 2019.80  5822.1 2021.16  5857.3 2023.64  5945.0 2022.79  5997.1 2025.51
  6155.6 2025.54  6229.0 2028.77  6265.7 2027.47  6482.2 2029.08  6526.6 2031.28
#Mann=7,-1,0
  4427.5   0.045       0  4923.2    0.07       0  4988.8   0.045       0
  4990.0   0.045       0  4995.8   0.045       0  5102.7    0.07       0
  5257.2   0.045       0
Bank Sta=4990,4995.8
Exp/Cntr=0.3,0.1

Type RM Length L Ch R = 1,17319,217,217,217
BEGIN DESCRIPTION:
Alkali Creek Trib 04 25.0
END DESCRIPTION:
XS GIS Cut Line= 6
      1357680.00      6956463.00      1358139.14      6956508.40
      1358167.51      6956537.97      1358261.26      6956540.57
      1358371.50      6956524.95      1359226.82      6955481.60
#Sta/Elev= 30
  4459.7 2015.56  4652.2 2014.97  4685.8 2015.47  4759.6 2013.05  4782.5 2012.80
  4833.6 2012.05  4834.1 2011.55  4839.4 2012.05  4886.8 2013.69  4896.8 2015.67
  4906.9 2019.77  5039.6 2018.61  5100.0 2020.52  5112.5 2018.52  5140.4 2017.93
  5146.8 2015.93  5160.6 2013.55  5202.4 2012.60  5480.2 2012.87  5628.7 2015.06
  5757.9 2014.92  5849.0 2016.95  6048.6 2017.26  6120.1 2019.48  6176.3 2018.11
  6248.1 2021.02  6283.2 2019.91  6411.0 2021.22  6482.2 2023.41  6516.3 2022.02
#Mann=7,-1,0
  4459.7   0.045       0  4652.2    0.07       0  4759.6   0.045       0
  4782.5    0.07       0  4833.6    0.07       0  4839.4    0.07       0
  5146.8   0.045       0
Bank Sta=4833.6,4839.4
Exp/Cntr=0.3,0.1

Type RM Length L Ch R = 1,17102,222,222,222
BEGIN DESCRIPTION:
Alkali Creek Trib 04 24.5
END DESCRIPTION:
XS GIS Cut Line= 4
      1357421.91      6956556.73      1358043.44      6956758.73
      1358374.92      6956592.99      1359519.58      6955292.94
#Sta/Elev= 30
  4248.3 2017.01  4766.8 2013.70  4976.1 2010.85  4976.5 2010.35  4981.9 2010.85
  5001.4 2013.54  5023.7 2011.82  5135.5 2011.17  5230.5 2014.31  5252.9 2012.84
  5285.1 2014.42  5311.4 2012.64  5339.9 2013.80  5375.0 2011.90  5538.1 2011.91
  5856.9 2015.13  5977.4 2014.78  6055.2 2016.91  6310.4 2017.54  6338.9 2019.68
  6388.2 2018.20  6459.4 2021.09  6522.9 2019.69  6692.8 2020.57  6743.0 2023.23
  6778.1 2021.82  6827.5 2022.92  6863.5 2025.79  6891.3 2024.65  7004.6 2026.84
#Mann=4,-1,0
  4248.3    0.07       0  4976.1    0.07       0  4981.9    0.07       0
  5285.1   0.045       0
Bank Sta=4976.1,4981.9
Exp/Cntr=0.3,0.1

Type RM Length L Ch R = 1,16880,143,143,143
BEGIN DESCRIPTION:
Alkali Creek Trib 04 24.0
END DESCRIPTION:
XS GIS Cut Line= 4
      1357412.30      6956734.15      1358130.00      6956963.00
      1358256.27      6956889.31      1359754.98      6955238.02
#Sta/Elev= 30
  4100.5 2015.51  4712.1 2011.54  4793.2 2009.59  4793.6 2009.09  4799.0 2009.59
  5149.0 2010.45  5276.0 2012.08  5516.6 2010.51  5750.4 2011.92  5785.5 2013.64
  6019.4 2013.94  6055.1 2015.60  6111.3 2014.33  6231.6 2015.37  6281.6 2017.01
  6401.9 2017.35  6444.4 2019.41  6487.0 2018.00  6585.7 2018.26  6635.7 2020.72
  6663.4 2019.47  6784.4 2021.54  6812.1 2023.83  6883.0 2023.08  6932.9 2026.28
  6960.7 2024.97  7031.7 2027.42  7067.5 2030.26  7173.6 2031.44  7230.0 2034.50
#Mann=4,-1,0
  4100.5    0.07       0  4793.2    0.07       0  4799.0    0.07       0
  5276.0   0.045       0
Bank Sta=4793.2,4799
Exp/Cntr=0.3,0.1

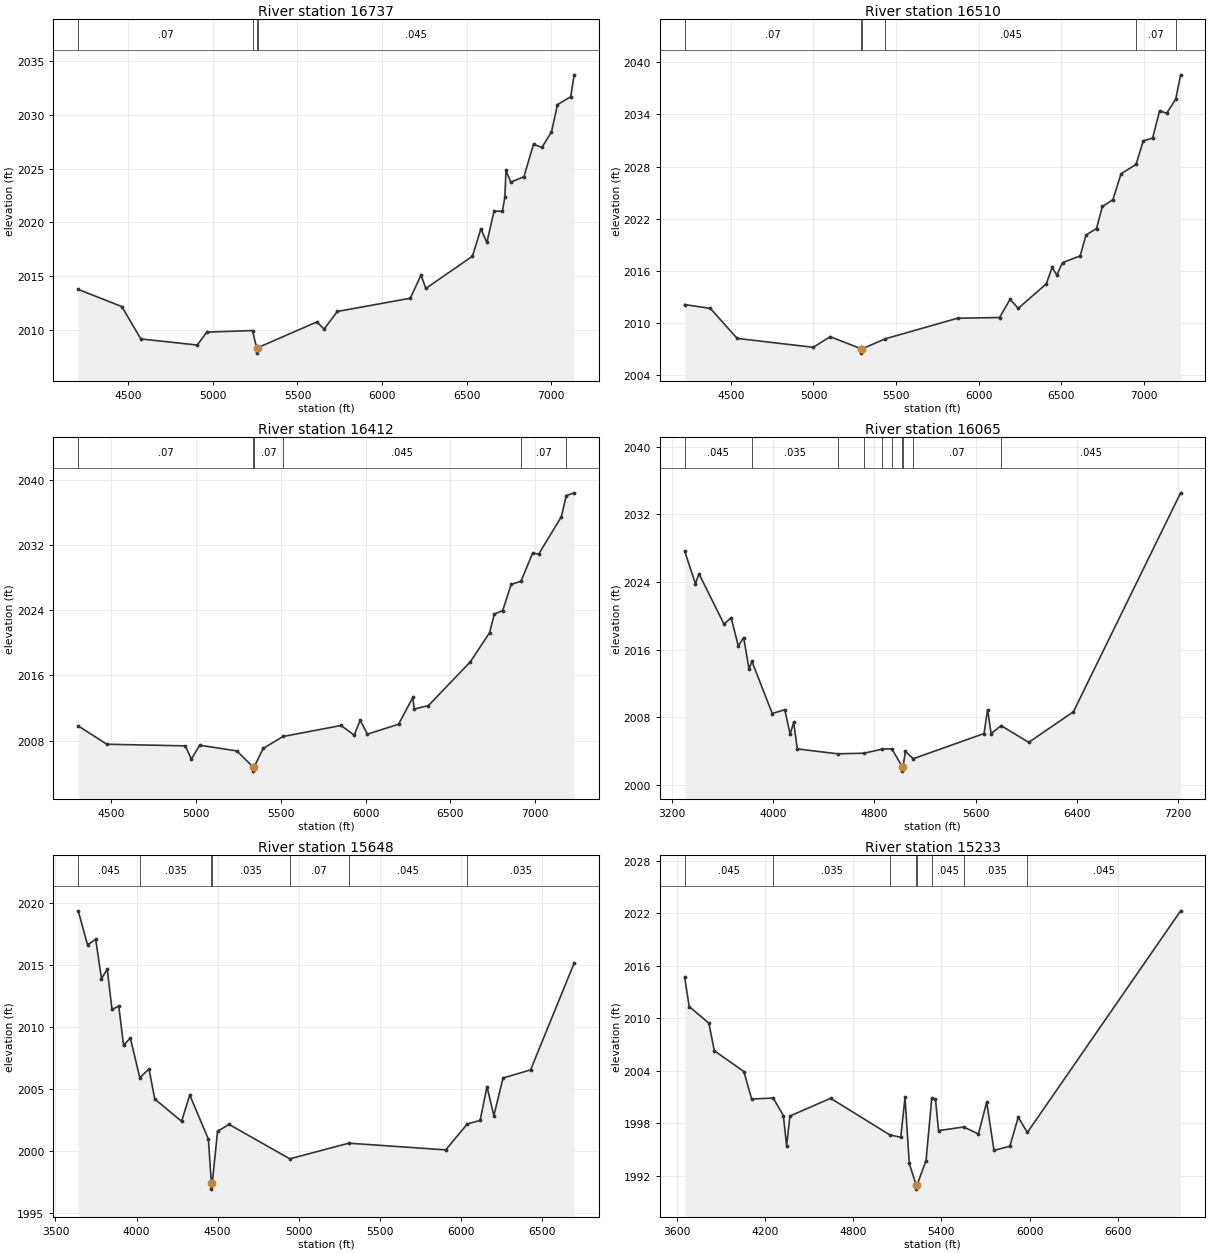
Type RM Length L Ch R = 1,16737,227,227,227
BEGIN DESCRIPTION:
Alkali Creek Trib 04 23.2
END DESCRIPTION:
XS GIS Cut Line= 3
      1357613.53      6956929.65      1358276.51      6957074.67
      1359840.35      6955453.87
#Sta/Elev= 30
  4204.3 2013.78  4461.7 2012.19  4574.3 2009.18  4907.7 2008.61  4964.3 2009.81
  5234.4 2009.96  5258.5 2008.36  5259.0 2007.86  5264.3 2008.36  5614.9 2010.76
  5657.4 2010.09  5735.3 2011.73  6166.7 2012.96  6230.3 2015.11  6258.6 2013.87
  6534.3 2016.87  6584.0 2019.41  6619.2 2018.14  6661.7 2021.05  6711.3 2021.05
  6725.5 2022.34  6732.4 2024.83  6760.7 2023.75  6838.4 2024.25  6895.0 2027.27
  6944.7 2026.97  7001.3 2028.42  7036.5 2030.95  7114.5 2031.68  7135.2 2033.72
#Mann=4,-1,0
  4204.3    0.07       0  5234.4   0.045       0  5258.5    0.07       0
  5264.3   0.045       0
Bank Sta=5258.5,5264.3
Exp/Cntr=0.3,0.1

Type RM Length L Ch R = 1,16510,98,98,98
BEGIN DESCRIPTION:
Alkali Creek Trib 04 23.0
END DESCRIPTION:
XS GIS Cut Line= 4
      1357766.46      6957098.73      1358335.93      6957307.07
      1358455.00      6957188.00      1360004.97      6955588.03
#Sta/Elev= 30
  4220.4 2012.15  4375.8 2011.71  4538.3 2008.26  4998.7 2007.24  5101.3 2008.46
  5289.3 2007.07  5289.7 2006.57  5295.1 2007.07  5435.3 2008.22  5872.2 2010.58
  6126.6 2010.66  6190.4 2012.75  6239.8 2011.72  6409.6 2014.53  6444.8 2016.41
  6473.1 2015.55  6508.6 2016.98  6614.6 2017.74  6650.1 2020.14  6713.6 2020.89
  6749.1 2023.42  6812.7 2024.20  6862.1 2027.17  6953.0 2028.26  6996.6 2030.95
  7053.2 2031.28  7095.6 2034.42  7138.1 2034.13  7193.4 2035.77  7222.8 2038.55
#Mann=6,-1,0
  4220.4    0.07       0  5289.3    0.07       0  5295.1    0.07       0
  5435.3   0.045       0  6953.0    0.07       0  7193.4   0.045       0
Bank Sta=5289.3,5295.1
Exp/Cntr=0.3,0.1

Type RM Length L Ch R = 1,16412,347,347,347
BEGIN DESCRIPTION:
Alkali Creek Trib 04 22.5
END DESCRIPTION:
XS GIS Cut Line= 3
      1357955.55      6957249.45      1358333.48      6957447.59
      1360099.63      6955676.26
#Sta/Elev= 30
  4303.5 2009.81  4472.2 2007.56  4936.1 2007.36  4971.4 2005.74  5020.9 2007.44
  5240.1 2006.74  5336.2 2004.76  5336.7 2004.26  5342.0 2004.76  5395.7 2007.05
  5512.8 2008.51  5855.3 2009.86  5933.1 2008.68  5968.4 2010.51  6010.9 2008.80
  6194.7 2010.01  6279.6 2013.32  6286.6 2011.87  6371.5 2012.31  6619.0 2017.68
  6732.1 2021.25  6760.4 2023.53  6809.9 2023.97  6859.4 2027.17  6918.0 2027.57
  6986.7 2031.04  7022.0 2030.88  7156.4 2035.49  7184.9 2038.07  7231.6 2038.41
#Mann=6,-1,0
  4303.5    0.07       0  5336.2    0.07       0  5342.0    0.07       0
  5512.8   0.045       0  6918.0    0.07       0  7184.9   0.045       0
Bank Sta=5336.2,5342
Exp/Cntr=0.3,0.1

Type RM Length L Ch R = 1,16065,417,417,417
BEGIN DESCRIPTION:
Alkali Creek Trib 04 22.0
END DESCRIPTION:
XS GIS Cut Line= 3
      1357504.99      6958738.01      1358705.00      6957538.00
      1360254.97      6955938.03
#Sta/Elev= 30
  3298.2 2027.66  3383.1 2023.81  3411.4 2024.97  3609.3 2019.03  3665.9 2019.79
  3722.5 2016.44  3764.9 2017.43  3807.3 2013.72  3830.5 2014.61  3991.2 2008.44
  4090.2 2008.89  4132.6 2005.99  4160.9 2007.40  4189.2 2004.25  4508.9 2003.67
  4717.0 2003.74  4862.0 2004.23  4937.6 2004.26  5020.6 2002.12  5021.0 2001.62
  5026.4 2002.12  5044.8 2003.95  5107.4 2003.09  5667.1 2006.07  5695.3 2008.90
  5723.6 2006.05  5801.6 2007.01  6020.7 2005.03  6374.2 2008.64  7222.9 2034.56
#Mann=10,-1,0
  3298.2   0.045       0  3830.5   0.035       0  4508.9    0.16       0
  4717.0   0.035       0  4862.0    0.07       0  4937.6   0.035       0
  5020.6   0.035       0  5026.4   0.035       0  5107.4    0.07       0
  5801.6   0.045       0
Bank Sta=5020.6,5026.4
Exp/Cntr=0.3,0.1

Type RM Length L Ch R = 1,15648,415,415,415
BEGIN DESCRIPTION:
Alkali Creek Trib 04 21.0
END DESCRIPTION:
XS GIS Cut Line= 3
      1357904.98      6958588.01      1359005.00      6957788.00
      1360204.98      6956588.02
#Sta/Elev= 30
  3640.3 2019.35  3697.9 2016.61  3748.1 2017.06  3783.7 2013.89  3819.2 2014.65
  3848.6 2011.41  3890.3 2011.68  3919.7 2008.54  3961.8 2009.10  4019.9 2005.91
  4076.6 2006.62  4112.1 2004.20  4277.5 2002.40  4327.7 2004.52  4442.9 2000.96
  4460.8 1997.44  4461.3 1996.94  4466.7 1997.44  4499.3 2001.60  4570.4 2002.15
  4944.6 1999.38  5308.3 2000.64  5905.6 2000.10  6039.0 2002.19  6117.7 2002.47
  6160.1 2005.19  6202.6 2002.86  6259.1 2005.89  6428.8 2006.54  6697.5 2015.14
#Mann=7,-1,0
  3640.3   0.045       0  4019.9   0.035       0  4460.8    0.07       0
  4466.7   0.035       0  4944.6    0.07       0  5308.3   0.045       0
  6039.0   0.035       0
Bank Sta=4460.8,4466.7
Exp/Cntr=0.3,0.1

Type RM Length L Ch R = 1,15233,292,292,292
BEGIN DESCRIPTION:
Alkali Creek Trib 04 20.0
END DESCRIPTION:
XS GIS Cut Line= 3
      1358105.03      6958637.98      1359305.00      6958038.00
      1360555.00      6956438.00
#Sta/Elev= 30
  3654.6 2014.69  3685.3 2011.35  3819.5 2009.45  3855.8 2006.30  4057.1 2003.92
  4110.2 2000.77  4256.4 2000.89  4325.4 1998.89  4347.7 1995.44  4370.1 1998.83
  4646.8 2000.86  5049.8 1996.67  5123.7 1996.40  5152.7 2000.97  5181.6 1993.41
  5227.6 1990.97  5228.1 1990.47  5235.1 1990.97  5295.6 1993.74  5334.4 2000.84
  5359.8 2000.77  5380.6 1997.16  5550.7 1997.58  5651.9 1996.78  5708.0 2000.43
  5757.7 1994.90  5865.3 1995.38  5922.6 1998.69  5984.6 1996.95  7026.6 2022.30
#Mann=8,-1,0
  3654.6   0.045       0  4256.4   0.035       0  5049.8    0.07       0
  5227.6   0.035       0  5235.1    0.07       0  5334.4   0.045       0
  5550.7   0.035       0  5984.6   0.045       0
Bank Sta=5227.6,5235.1
Exp/Cntr=0.3,0.1

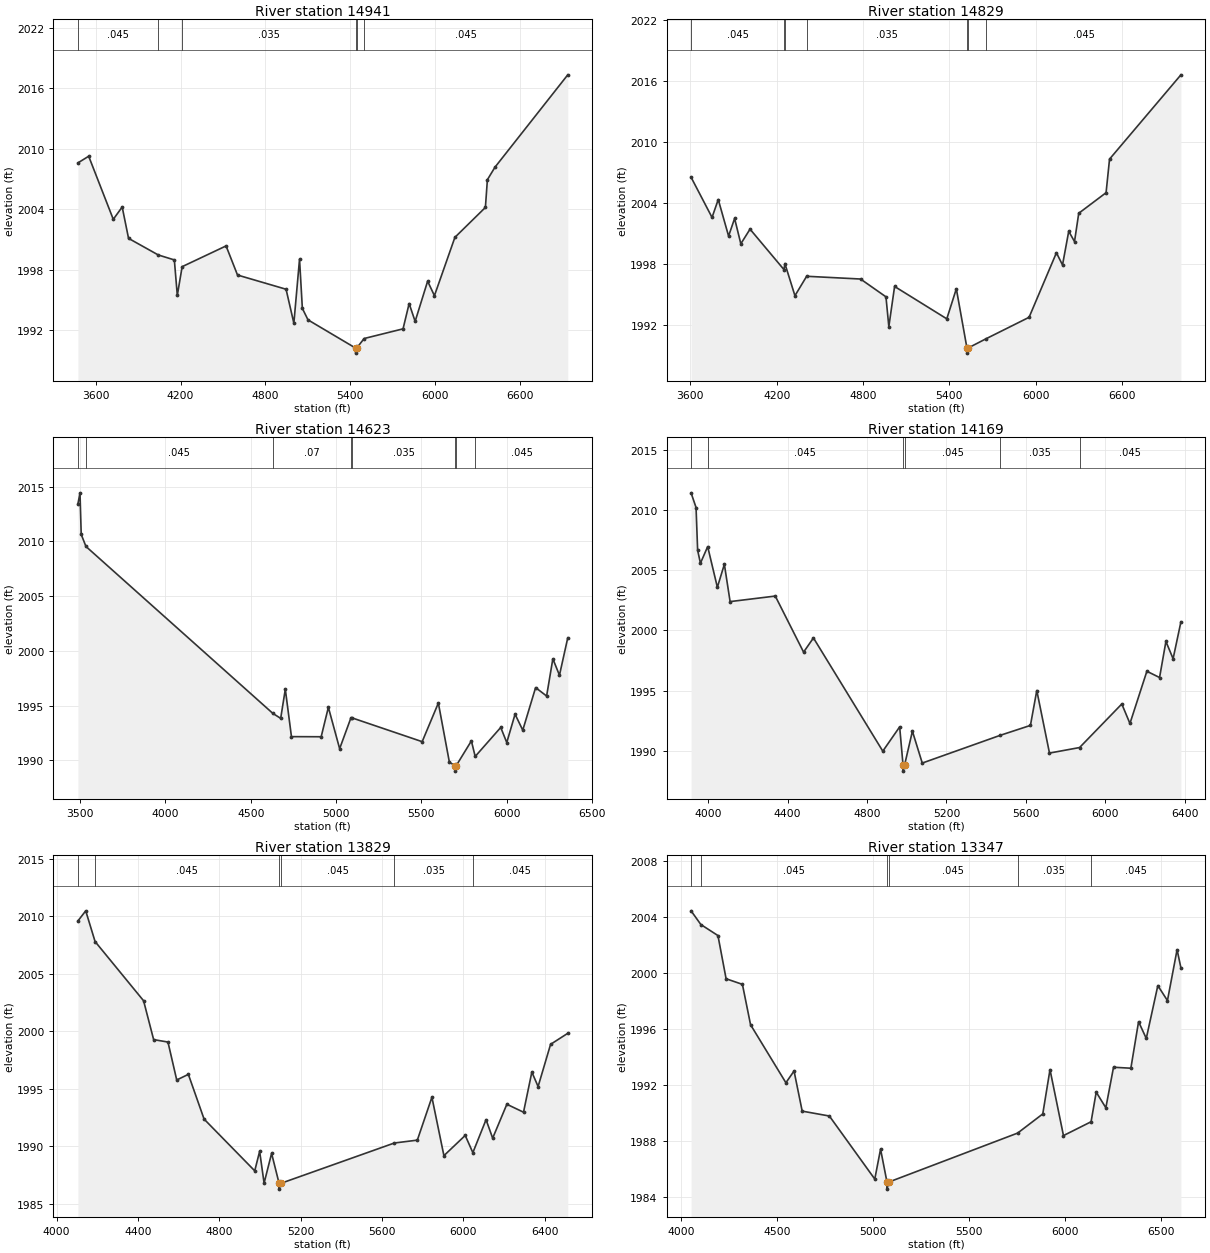
Type RM Length L Ch R = 1,14941,112,112,112
BEGIN DESCRIPTION:
Alkali Creek Trib 04 19.0
END DESCRIPTION:
XS GIS Cut Line= 4
      1358225.07      6958784.46      1359195.89      6958133.00
      1359908.13      6958156.44      1360505.01      6956687.97
#Sta/Elev= 30
  3473.4 2008.59  3549.7 2009.25  3723.7 2002.99  3786.8 2004.21  3831.8 2001.10
  4042.4 1999.45  4155.9 1998.96  4176.9 1995.44  4211.1 1998.29  4522.0 2000.35
  4603.0 1997.46  4946.6 1996.05  5001.8 1992.68  5041.9 1999.03  5061.9 1994.15
  5101.9 1993.01  5438.8 1990.21  5439.3 1989.71  5446.3 1990.21  5499.2 1991.16
  5774.5 1992.12  5817.6 1994.63  5860.1 1992.86  5948.5 1996.85  5996.6 1995.41
  6141.5 2001.20  6357.4 2004.17  6371.4 2006.92  6425.0 2008.16  6940.3 2017.33
#Mann=6,-1,0
  3473.4   0.045       0  4042.4    0.07       0  4211.1   0.035       0
  5438.8   0.035       0  5446.3   0.035       0  5499.2   0.045       0
Bank Sta=5438.8,5446.3
Exp/Cntr=0.3,0.1

Type RM Length L Ch R = 1,14829,206,206,206
BEGIN DESCRIPTION:
Alkali Creek Trib 04 18.5
END DESCRIPTION:
XS GIS Cut Line= 4
      1358381.38      6958880.32      1359168.55      6958250.19
      1359948.49      6958263.21      1360557.95      6956765.64
#Sta/Elev= 30
  3604.8 2006.56  3750.6 2002.61  3793.8 2004.37  3865.6 2000.78  3907.5 2002.51
  3950.7 2000.02  4014.7 2001.46  4250.9 1997.48  4257.0 1998.08  4326.9 1994.92
  4408.3 1996.83  4783.0 1996.56  4959.6 1994.81  4979.6 1991.88  5019.6 1995.83
  5382.5 1992.65  5448.8 1995.60  5522.6 1989.78  5523.1 1989.28  5530.1 1989.78
  5656.5 1990.70  5954.5 1992.80  6144.6 1999.14  6186.9 1997.94  6230.1 2001.25
  6270.3 2000.24  6299.7 2003.02  6489.7 2005.04  6513.8 2008.34  7010.0 2016.62
#Mann=7,-1,0
  3604.8   0.045       0  4250.9    0.07       0  4257.0   0.045       0
  4408.3   0.035       0  5522.6   0.035       0  5530.1   0.035       0
  5656.5   0.045       0
Bank Sta=5522.6,5530.1
Exp/Cntr=0.3,0.1

Type RM Length L Ch R = 1,14623,454,454,454
BEGIN DESCRIPTION:
Alkali Creek Trib 04 18.2
END DESCRIPTION:
XS GIS Cut Line= 5
      1358402.65      6959472.94      1359180.00      6958663.00
      1359630.00      6958363.00      1359977.03      6958309.54
      1360292.56      6957512.72
#Sta/Elev= 30
  3487.0 2013.42  3499.2 2014.44  3506.4 2010.64  3534.2 2009.54  4630.0 1994.29
  4675.7 1993.84  4702.8 1996.50  4738.8 1992.17  4913.1 1992.16  4955.2 1994.85
  5021.3 1991.07  5087.8 1993.90  5094.7 1993.88  5505.1 1991.71  5600.0 1995.24
  5664.6 1989.84  5697.2 1989.52  5697.7 1989.02  5704.7 1989.52  5793.6 1991.78
  5815.9 1990.36  5965.7 1993.01  6001.0 1991.63  6049.6 1994.22  6094.8 1992.76
  6170.1 1996.65  6234.6 1995.88  6271.2 1999.28  6309.9 1997.78  6358.6 2001.20
#Mann=8,-1,0
  3487.0   0.035       0  3534.2   0.045       0  4630.0    0.07       0
  5087.8   0.045       0  5094.7   0.035       0  5697.2    0.07       0
  5704.7   0.035       0  5815.9   0.045       0
Bank Sta=5697.2,5704.7
Exp/Cntr=0.3,0.1

Type RM Length L Ch R = 1,14169,340,340,340
BEGIN DESCRIPTION:
Alkali Creek Trib 04 18.1
END DESCRIPTION:
XS GIS Cut Line= 3
      1359086.20      6959644.93      1359907.48      6958614.50
      1360304.05      6957537.15
#Sta/Elev= 30
  3914.3 2011.44  3939.4 2010.22  3947.4 2006.66  3961.5 2005.59  3997.9 2006.97
  4046.7 2003.59  4081.9 2005.50  4110.8 2002.40  4338.2 2002.86  4480.7 1998.20
  4530.3 1999.38  4879.4 1989.97  4964.3 1991.99  4981.3 1988.81  4981.8 1988.31
  4988.9 1988.81  5028.4 1991.63  5078.0 1988.98  5471.2 1991.29  5622.5 1992.11
  5654.5 1995.01  5718.4 1989.81  5869.9 1990.27  6082.4 1993.89  6123.4 1992.27
  6208.6 1996.61  6272.5 1996.09  6304.5 1999.09  6340.6 1997.65  6380.0 2000.72
#Mann=6,-1,0
  3914.3   0.035       0  3997.9   0.045       0  4981.3   0.045       0
  4988.9   0.045       0  5471.2   0.035       0  5869.9   0.045       0
Bank Sta=4981.3,4988.9
Exp/Cntr=0.3,0.1

Type RM Length L Ch R = 1,13829,482,482,482
BEGIN DESCRIPTION:
Alkali Creek Trib 04 18.0
END DESCRIPTION:
XS GIS Cut Line= 3
      1359443.13      6959729.53      1360005.00      6959038.00
      1360329.72      6957555.47
#Sta/Elev= 30
  4104.6 2009.60  4143.0 2010.48  4189.0 2007.81  4427.5 2002.66  4477.0 1999.28
  4547.4 1999.07  4590.5 1995.77  4647.7 1996.26  4725.0 1992.37  4974.1 1987.87
  4998.2 1989.57  5020.1 1986.80  5057.0 1989.39  5093.9 1986.78  5094.4 1986.28
  5102.0 1986.78  5660.5 1990.29  5773.6 1990.54  5845.3 1994.27  5904.3 1989.19
  6009.1 1990.95  6046.6 1989.45  6111.5 1992.32  6144.0 1990.71  6213.8 1993.66
  6295.7 1992.97  6336.7 1996.46  6367.4 1995.20  6428.8 1998.87  6513.3 1999.83
#Mann=6,-1,0
  4104.6    0.07       0  4189.0   0.045       0  5093.9   0.045       0
  5102.0   0.045       0  5660.5   0.035       0  6046.6   0.045       0
Bank Sta=5093.9,5102
Exp/Cntr=0.3,0.1

Type RM Length L Ch R = 1,13347,466,466,466
BEGIN DESCRIPTION:
Alkali Creek Trib 04 17.0
END DESCRIPTION:
XS GIS Cut Line= 3
      1359786.07      6959806.93      1360455.00      6959138.00
      1360355.00      6957538.03
#Sta/Elev= 30
  4054.0 2004.44  4104.9 2003.46  4193.9 2002.67  4236.3 1999.58  4321.2 1999.18
  4363.6 1996.29  4547.5 1992.14  4589.9 1992.98  4632.3 1990.11  4773.7 1989.76
  5010.0 1985.25  5040.1 1987.39  5073.6 1985.03  5074.1 1984.53  5081.8 1985.03
  5753.5 1988.54  5884.2 1989.91  5921.8 1993.08  5991.9 1988.36  6135.6 1989.35
  6162.3 1991.47  6212.4 1990.35  6252.4 1993.25  6342.6 1993.18  6382.7 1996.51
  6422.8 1995.31  6482.9 1999.09  6533.0 1998.02  6583.1 2001.66  6603.1 2000.36
#Mann=6,-1,0
  4054.0   0.035       0  4104.9   0.045       0  5073.6   0.045       0
  5081.8   0.045       0  5753.5   0.035       0  6135.6   0.045       0
Bank Sta=5073.6,5081.8
Exp/Cntr=0.3,0.1

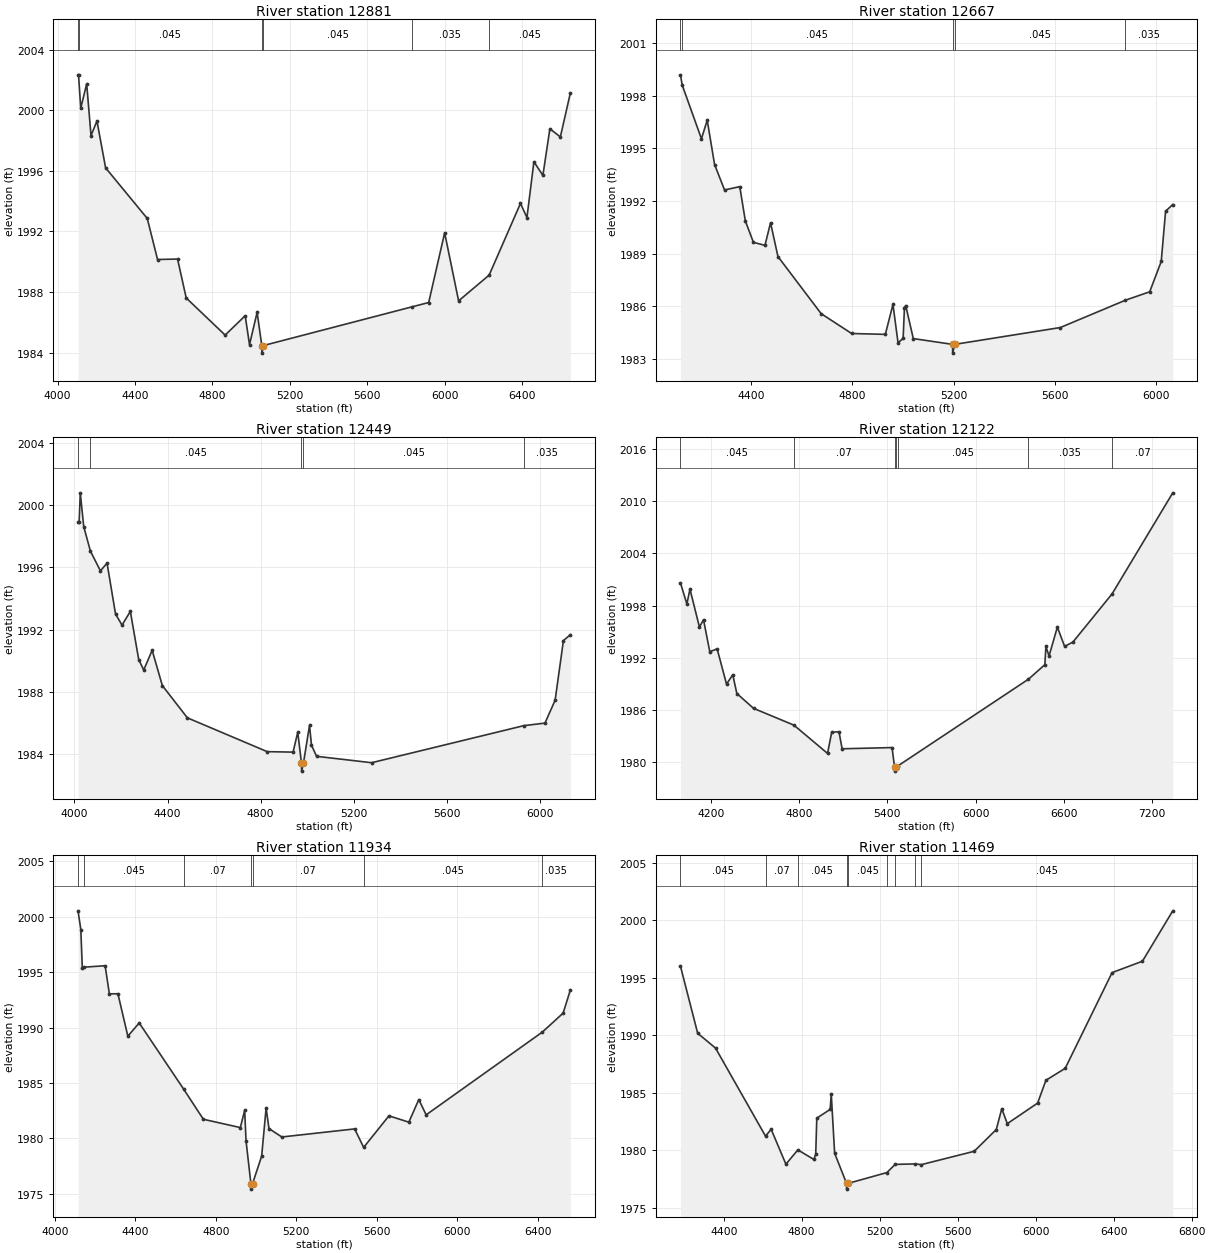
Type RM Length L Ch R = 1,12881,214,214,214
BEGIN DESCRIPTION:
Alkali Creek Trib 04 16.0
END DESCRIPTION:
XS GIS Cut Line= 3
      1360505.01      6959987.98      1360905.00      6959188.00
      1360505.01      6957588.05
#Sta/Elev= 30
  4105.6 2002.33  4108.2 2002.33  4119.6 2000.13  4150.3 2001.73  4172.7 1998.32
  4203.4 1999.28  4248.1 1996.19  4463.3 1992.85  4516.5 1990.14  4619.9 1990.17
  4664.6 1987.60  4865.8 1985.15  4969.3 1986.43  4991.6 1984.52  5030.9 1986.65
  5055.1 1984.46  5055.6 1983.96  5063.4 1984.46  5829.6 1987.01  5917.4 1987.30
  5999.9 1991.90  6072.0 1987.41  6229.8 1989.11  6391.6 1993.84  6425.1 1992.91
  6461.1 1996.59  6507.5 1995.69  6543.6 1998.77  6597.7 1998.23  6649.2 2001.12
#Mann=6,-1,0
  4105.6   0.035       0  4108.2   0.045       0  5055.1   0.045       0
  5063.4   0.045       0  5829.6   0.035       0  6229.8   0.045       0
Bank Sta=5055.1,5063.4
Exp/Cntr=0.3,0.1

Type RM Length L Ch R = 1,12667,218,218,218
BEGIN DESCRIPTION:
Alkali Creek Trib 04 15.2
END DESCRIPTION:
XS GIS Cut Line= 4
      1360805.78      6959999.97      1361104.99      6959362.38
      1361130.00      6959063.00      1360730.02      6958213.04
#Sta/Elev= 30
  4120.7 1999.20  4127.2 1998.63  4203.5 1995.55  4226.3 1996.61  4255.4 1994.08
  4294.7 1992.63  4354.8 1992.82  4376.9 1990.86  4408.8 1989.64  4454.3 1989.47
  4476.4 1990.76  4505.6 1988.83  4676.4 1985.57  4796.7 1984.44  4929.7 1984.39
  4959.8 1986.10  4979.9 1983.91  5000.0 1984.16  5005.2 1985.92  5010.2 1986.03
  5040.1 1984.15  5195.2 1983.82  5195.7 1983.32  5203.5 1983.82  5620.7 1984.78
  5877.9 1986.34  5973.7 1986.82  6019.2 1988.55  6036.5 1991.42  6064.8 1991.80
#Mann=5,-1,0
  4120.7   0.035       0  4127.2   0.045       0  5195.2   0.045       0
  5203.5   0.045       0  5877.9   0.035       0
Bank Sta=5195.2,5203.5
Exp/Cntr=0.3,0.1

Type RM Length L Ch R = 1,12449,327,327,327
BEGIN DESCRIPTION:
Alkali Creek Trib 04 15.5
END DESCRIPTION:
XS GIS Cut Line= 4
      1360884.56      6960040.91      1361302.79      6959430.02
      1361358.12      6959037.69      1360830.03      6958213.04
#Sta/Elev= 30
  4015.2 1998.91  4020.0 1998.91  4024.8 2000.78  4039.7 1998.61  4068.4 1997.04
  4111.5 1995.77  4139.9 1996.27  4176.3 1993.01  4204.2 1992.29  4240.1 1993.17
  4276.0 1990.08  4297.5 1989.41  4333.8 1990.67  4377.6 1988.41  4485.2 1986.34
  4828.3 1984.17  4939.4 1984.14  4959.6 1985.42  4975.6 1983.42  4976.1 1982.92
  4983.9 1983.42  5010.1 1985.86  5018.6 1984.59  5040.4 1983.87  5277.1 1983.46
  5931.6 1985.84  6022.0 1986.00  6065.7 1987.47  6101.4 1991.30  6131.0 1991.67
#Mann=5,-1,0
  4015.2   0.035       0  4068.4   0.045       0  4975.6   0.045       0
  4983.9   0.045       0  5931.6   0.035       0
Bank Sta=4975.6,4983.9
Exp/Cntr=0.3,0.1

Type RM Length L Ch R = 1,12122,188,188,188
BEGIN DESCRIPTION:
Alkali Creek Trib 04 15.0
END DESCRIPTION:
XS GIS Cut Line= 3
      1360941.12      6960095.63      1361641.11      6959295.64
      1363290.94      6957713.87
#Sta/Elev= 30
  3992.4 2000.60  4036.0 1998.19  4056.9 1999.90  4121.4 1995.53  4149.0 1996.39
  4191.7 1992.70  4241.7 1993.03  4305.6 1988.97  4348.0 1990.05  4375.8 1987.89
  4489.7 1986.18  4764.2 1984.25  4992.7 1981.00  5021.2 1983.44  5070.7 1983.49
  5091.8 1981.53  5431.4 1981.67  5448.3 1979.46  5448.8 1978.96  5456.7 1979.46
  5468.7 1979.53  6359.6 1989.54  6471.1 1991.21  6478.0 1993.31  6499.4 1992.21
  6556.0 1995.53  6605.4 1993.31  6662.0 1993.81  6928.5 1999.36  7341.0 2010.98
#Mann=7,-1,0
  3992.4   0.045       0  4764.2    0.07       0  5448.3    0.07       0
  5456.7    0.07       0  5468.7   0.045       0  6359.6   0.035       0
  6928.5    0.07       0
Bank Sta=5448.3,5456.7
Exp/Cntr=0.3,0.1

Type RM Length L Ch R = 1,11934,465,465,465
BEGIN DESCRIPTION:
Alkali Creek Trib 04 14.0
END DESCRIPTION:
XS GIS Cut Line= 3
      1361104.99      6960138.01      1361705.00      6959488.00
      1362704.97      6958288.04
#Sta/Elev= 30
  4115.4 2000.54  4129.3 1998.85  4136.7 1995.35  4145.0 1995.45  4250.1 1995.58
  4271.1 1993.04  4313.6 1993.05  4362.9 1989.22  4419.6 1990.41  4640.8 1984.42
  4738.3 1981.71  4922.0 1980.96  4943.6 1982.51  4950.4 1979.76  4974.5 1975.90
  4975.0 1975.40  4982.9 1975.90  5028.0 1978.38  5050.1 1982.72  5064.4 1980.87
  5128.2 1980.11  5490.1 1980.84  5534.9 1979.17  5660.6 1982.02  5759.5 1981.45
  5809.0 1983.49  5845.5 1982.11  6423.2 1989.59  6526.3 1991.30  6562.0 1993.38
#Mann=7,-1,0
  4115.4   0.035       0  4145.0   0.045       0  4640.8    0.07       0
  4974.5    0.07       0  4982.9    0.07       0  5534.9   0.045       0
  6423.2   0.035       0
Bank Sta=4974.5,4982.9
Exp/Cntr=0.3,0.1

Type RM Length L Ch R = 1,11469,442,442,442
BEGIN DESCRIPTION:
Alkali Creek Trib 04 13.0
END DESCRIPTION:
XS GIS Cut Line= 3
      1361305.04      6960087.98      1362055.00      6959738.00
      1363255.03      6958537.97
#Sta/Elev= 30
  4178.4 1996.00  4266.6 1990.18  4358.1 1988.89  4614.5 1981.24  4643.4 1981.83
  4719.1 1978.80  4780.4 1980.04  4862.5 1979.21  4872.0 1979.67  4877.5 1982.80
  4946.1 1983.56  4951.6 1984.91  4969.0 1979.75  5030.1 1977.13  5030.6 1976.63
  5038.5 1977.13  5237.2 1978.07  5279.4 1978.78  5381.4 1978.82  5414.1 1978.76
  5684.8 1979.92  5798.0 1981.81  5826.2 1983.62  5854.5 1982.32  6010.1 1984.11
  6052.5 1986.09  6151.5 1987.13  6391.9 1995.45  6547.5 1996.44  6703.1 2000.82
#Mann=9,-1,0
  4178.4   0.045       0  4614.5    0.07       0  4780.4   0.045       0
  5030.1   0.045       0  5038.5   0.045       0  5237.2    0.07       0
  5279.4   0.035       0  5381.4    0.07       0  5414.1   0.045       0
Bank Sta=5030.1,5038.5
Exp/Cntr=0.3,0.1