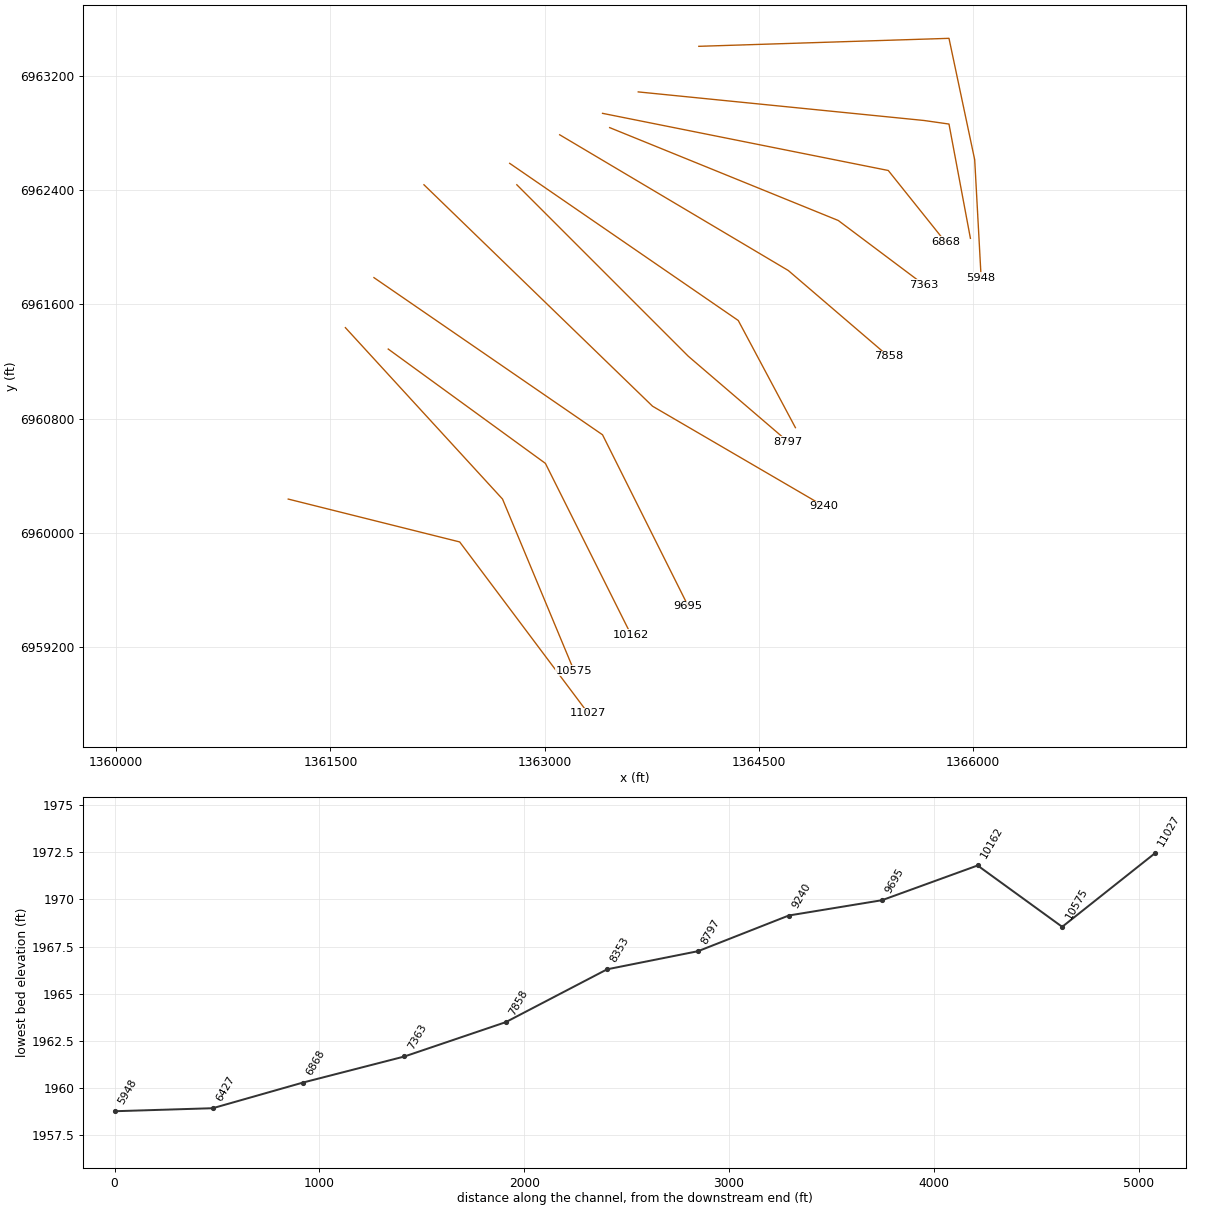
HEC-RAS study Alkali Creek Trib 04.prj: Alkali Creek Trib 04 Base Level Engineering

--- Alkali Creek Trib 04.g01 (geometry) --- (continued)

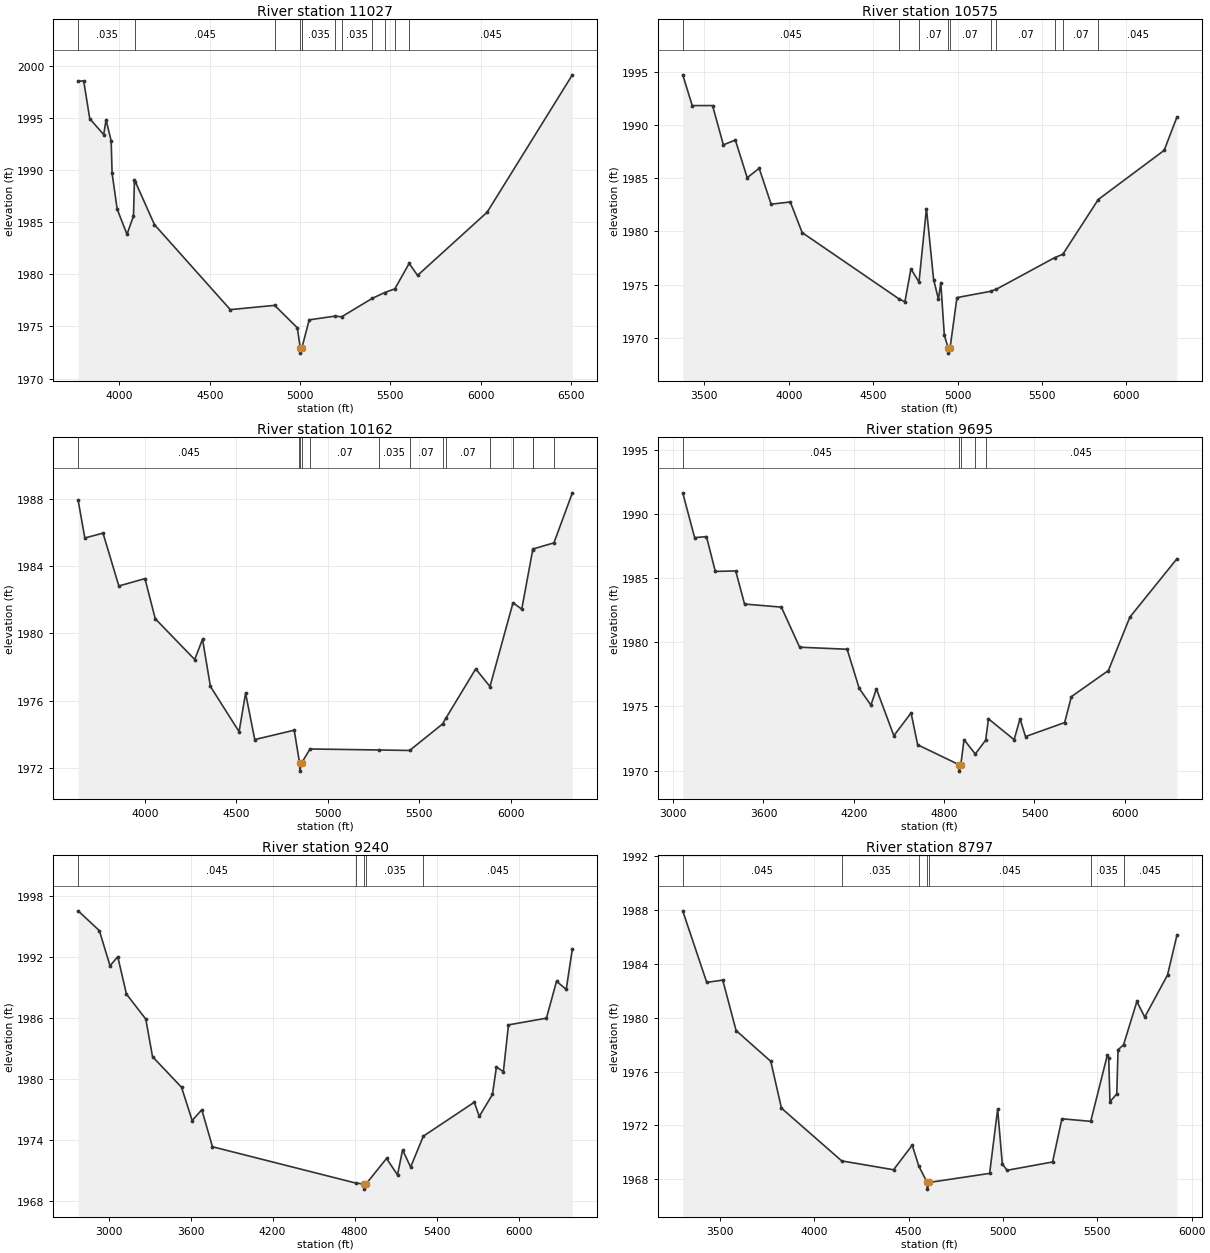
Type RM Length L Ch R = 1,11027,452,452,452
BEGIN DESCRIPTION:
Alkali Creek Trib 04 12.0
END DESCRIPTION:
XS GIS Cut Line= 3
      1361205.03      6960237.99      1362405.00      6959938.00
      1363305.00      6958738.00
#Sta/Elev= 30
  3771.0 1998.52  3801.9 1998.53  3835.4 1994.91  3912.7 1993.39  3925.6 1994.80
  3953.9 1992.80  3959.1 1989.68  3987.4 1986.23  4041.6 1983.83  4077.6 1985.58
  4082.8 1989.03  4087.5 1988.88  4193.6 1984.76  4613.6 1976.61  4859.3 1977.02
  4984.7 1974.87  5001.1 1972.94  5001.6 1972.44  5009.5 1972.94  5010.0 1972.94
  5050.6 1975.63  5194.2 1975.99  5230.0 1975.92  5398.7 1977.68  5469.0 1978.25
  5524.8 1978.60  5604.1 1981.04  5650.6 1979.89  6036.0 1985.95  6507.9 1999.12
#Mann=12,-1,0
  3771.0   0.035       0  4087.5   0.045       0  4859.3    0.07       0
  5001.1    0.07       0  5009.5    0.07       0  5010.0   0.035       0
  5194.2    0.07       0  5230.0   0.035       0  5398.7    0.07       0
  5469.0   0.035       0  5524.8    0.07       0  5604.1   0.045       0
Bank Sta=5001.1,5009.5
Exp/Cntr=0.3,0.1

Type RM Length L Ch R = 1,10575,413,413,413
BEGIN DESCRIPTION:
Alkali Creek Trib 04 11.0
END DESCRIPTION:
XS GIS Cut Line= 3
      1361604.98      6961438.02      1362705.00      6960238.00
      1363205.00      6959038.01
#Sta/Elev= 30
  3371.9 1994.71  3428.3 1991.82  3548.6 1991.82  3612.7 1988.13  3683.6 1988.58
  3753.9 1985.04  3824.8 1985.92  3895.7 1982.55  4009.2 1982.76  4079.5 1979.88
  4654.7 1973.63  4688.1 1973.38  4723.9 1976.47  4771.6 1975.23  4815.7 1982.14
  4858.3 1975.46  4886.7 1973.63  4900.8 1975.13  4921.8 1970.21  4944.5 1969.05
  4945.0 1968.55  4955.8 1969.05  4996.4 1973.77  5195.3 1974.36  5230.3 1974.56
  5574.7 1977.52  5624.0 1977.85  5833.6 1982.99  6224.0 1987.61  6299.8 1990.75
#Mann=10,-1,0
  3371.9   0.045       0  4654.7   0.035       0  4771.6    0.07       0
  4944.5    0.07       0  4955.8    0.07       0  5195.3   0.035       0
  5230.3    0.07       0  5574.7   0.045       0  5624.0    0.07       0
  5833.6   0.045       0
Bank Sta=4944.5,4955.8
Exp/Cntr=0.3,0.1

Type RM Length L Ch R = 1,10162,467,467,467
BEGIN DESCRIPTION:
Alkali Creek Trib 04 10.0
END DESCRIPTION:
XS GIS Cut Line= 3
      1361904.99      6961288.01      1363005.00      6960488.00
      1363605.00      6959288.00
#Sta/Elev= 30
  3635.3 1987.94  3672.0 1985.69  3771.3 1985.98  3857.9 1982.83  4000.5 1983.27
  4056.9 1980.88  4272.5 1978.45  4315.4 1979.66  4358.3 1976.85  4515.2 1974.15
  4550.7 1976.44  4600.9 1973.68  4816.6 1974.24  4844.4 1972.38  4846.4 1972.30
  4846.9 1971.80  4857.8 1972.30  4903.1 1973.12  5280.2 1973.06  5447.5 1973.03
  5627.4 1974.61  5645.5 1974.95  5808.8 1977.89  5886.7 1976.84  6012.6 1981.83
  6060.4 1981.45  6120.5 1984.99  6123.7 1985.04  6236.4 1985.40  6337.1 1988.38
#Mann=14,-1,0
  3635.3   0.045       0  4844.4   0.035       0  4846.4    0.07       0
  4857.8   0.035       0  4903.1    0.07       0  5280.2   0.035       0
  5447.5    0.07       0  5627.4   0.035       0  5645.5    0.07       0
  5886.7   0.045       0  6012.6    0.07       0  6120.5   0.045       0
  6123.7    0.07       0  6236.4   0.045       0
Bank Sta=4846.4,4857.8
Exp/Cntr=0.3,0.1

Type RM Length L Ch R = 1,9695,455,455,455
BEGIN DESCRIPTION:
Alkali Creek Trib 04 9.0
END DESCRIPTION:
XS GIS Cut Line= 3
      1361804.96      6961788.02      1363405.00      6960688.00
      1364004.99      6959488.03
#Sta/Elev= 30
  3063.5 1991.63  3142.7 1988.14  3221.3 1988.22  3280.0 1985.51  3415.5 1985.55
  3474.2 1982.97  3718.8 1982.73  3840.2 1979.61  4155.7 1979.45  4236.0 1976.40
  4313.8 1975.10  4349.9 1976.37  4466.0 1972.72  4580.5 1974.49  4624.3 1972.01
  4899.2 1970.46  4899.7 1969.96  4910.9 1970.46  4932.4 1972.41  5007.0 1971.29
  5075.9 1972.37  5094.6 1974.03  5265.1 1972.41  5304.3 1974.04  5340.6 1972.65
  5600.5 1973.74  5645.3 1975.76  5891.2 1977.79  6033.8 1981.95  6346.8 1986.50
#Mann=5,-1,0
  3063.5   0.045       0  4899.2   0.045       0  4910.9   0.045       0
  5007.0   0.035       0  5075.9   0.045       0
Bank Sta=4899.2,4910.9
Exp/Cntr=0.3,0.1

Type RM Length L Ch R = 1,9240,443,443,443
BEGIN DESCRIPTION:
Alkali Creek Trib 04 8.0
END DESCRIPTION:
XS GIS Cut Line= 3
      1362154.99      6962438.01      1363755.00      6960888.00
      1364954.98      6960188.01
#Sta/Elev= 30
  2777.3 1996.53  2932.8 1994.58  3010.7 1991.12  3067.3 1992.02  3130.9 1988.34
  3272.4 1985.88  3321.8 1982.18  3534.0 1979.17  3611.9 1975.90  3682.4 1976.96
  3760.3 1973.32  4808.3 1969.75  4871.9 1969.65  4872.4 1969.15  4883.7 1969.65
  5034.3 1972.17  5114.5 1970.55  5151.8 1973.01  5210.5 1971.32  5303.5 1974.36
  5676.4 1977.70  5713.2 1976.31  5809.2 1978.46  5838.5 1981.16  5889.4 1980.71
  5926.6 1985.31  6204.4 1985.97  6278.4 1989.60  6349.2 1988.80  6394.2 1992.80
#Mann=5,-1,0
  2777.3   0.045       0  4808.3   0.035       0  4871.9   0.035       0
  4883.7   0.035       0  5303.5   0.045       0
Bank Sta=4871.9,4883.7
Exp/Cntr=0.3,0.1

Type RM Length L Ch R = 1,8797,444,444,444
BEGIN DESCRIPTION:
Alkali Creek Trib 04 7.0
END DESCRIPTION:
XS GIS Cut Line= 3
      1362805.03      6962437.97      1364005.00      6961238.00
      1364705.03      6960637.98
#Sta/Elev= 30
  3303.2 1987.95  3430.4 1982.63  3515.3 1982.80  3586.0 1979.05  3769.8 1976.76
  3826.4 1973.28  4145.5 1969.36  4420.4 1968.70  4519.4 1970.53  4554.0 1968.98
  4598.3 1967.76  4598.8 1967.26  4610.1 1967.76  4929.5 1968.43  4971.9 1973.20
  4996.7 1969.14  5021.6 1968.66  5263.1 1969.28  5312.5 1972.49  5465.2 1972.30
  5553.4 1977.23  5560.5 1977.02  5567.1 1973.76  5603.3 1974.34  5609.9 1977.62
  5639.2 1977.99  5709.8 1981.21  5751.5 1980.05  5872.2 1983.18  5922.2 1986.15
#Mann=7,-1,0
  3303.2   0.045       0  4145.5   0.035       0  4554.0   0.045       0
  4598.3   0.045       0  4610.1   0.045       0  5465.2   0.035       0
  5639.2   0.045       0
Bank Sta=4598.3,4610.1
Exp/Cntr=0.3,0.1

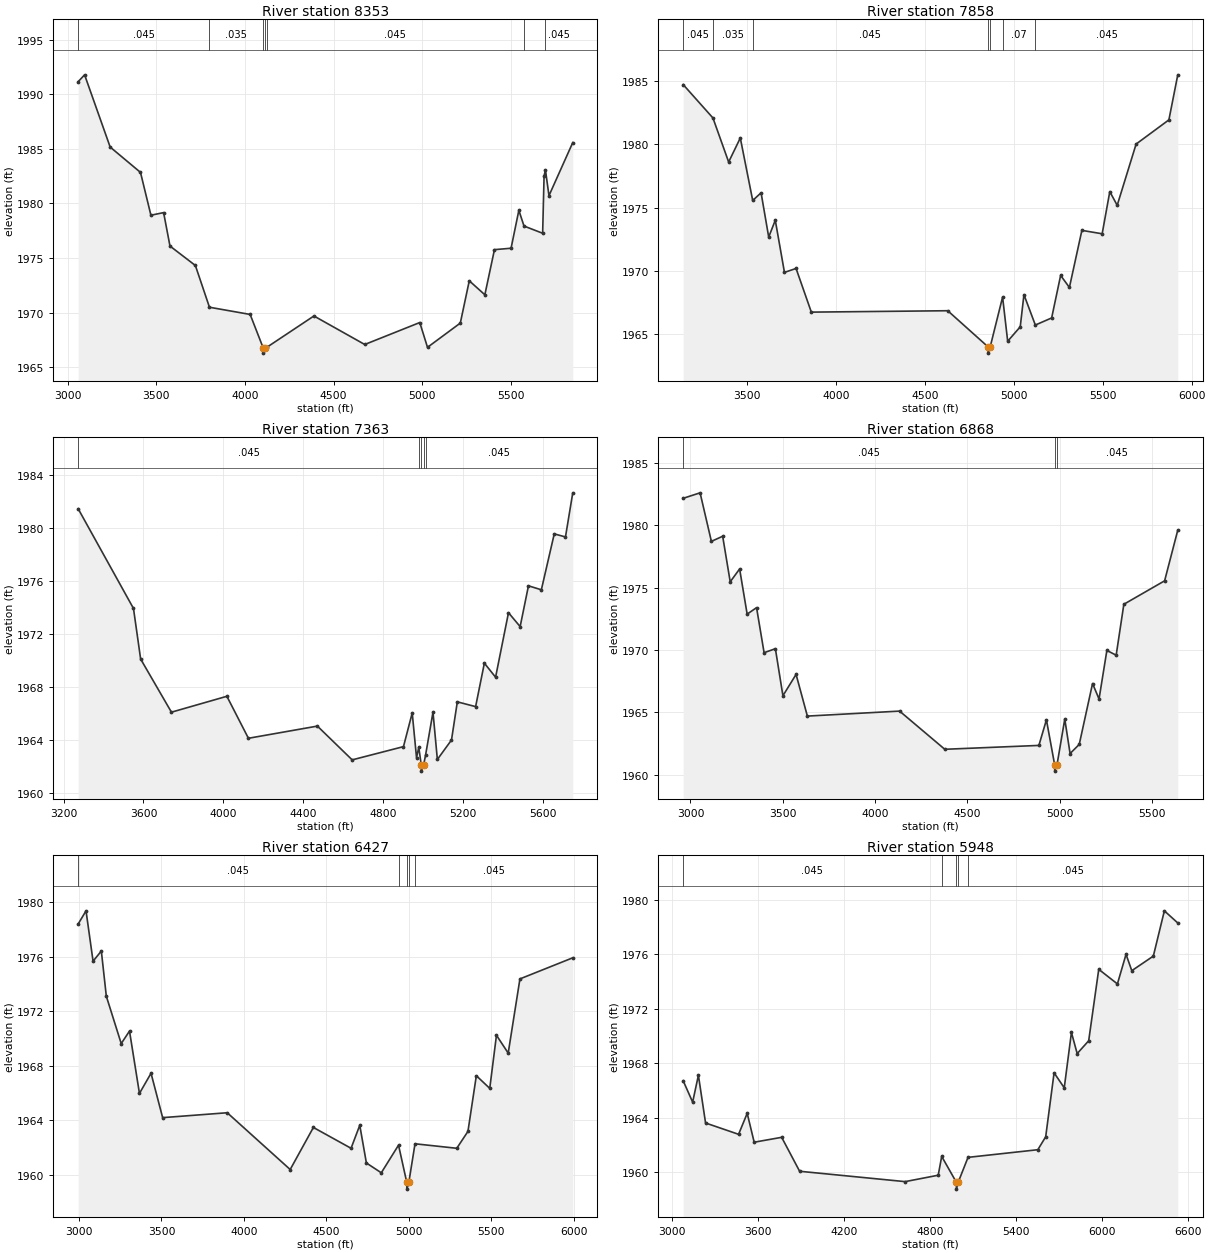
Type RM Length L Ch R = 1,8353,495,495,495
BEGIN DESCRIPTION:
Alkali Creek Trib 04 6.0
END DESCRIPTION:
XS GIS Cut Line= 3
      1362754.98      6962588.01      1364355.00      6961488.00
      1364755.02      6960737.97
#Sta/Elev= 30
  3058.3 1991.14  3094.7 1991.77  3239.0 1985.16  3410.2 1982.84  3469.0 1978.92
  3540.7 1979.16  3576.6 1976.10  3720.0 1974.32  3799.4 1970.50  4029.1 1969.84
  4102.1 1966.80  4102.6 1966.30  4114.5 1966.80  4123.0 1966.83  4389.1 1969.70
  4675.9 1967.09  4986.5 1969.10  5030.1 1966.83  5215.3 1969.05  5265.9 1972.92
  5353.8 1971.64  5408.0 1975.77  5501.8 1975.90  5545.7 1979.37  5574.8 1977.93
  5680.0 1977.27  5688.1 1982.52  5695.9 1983.05  5715.7 1980.71  5850.0 1985.57
#Mann=7,-1,0
  3058.3   0.045       0  3799.4   0.035       0  4102.1   0.045       0
  4114.5   0.035       0  4123.0   0.045       0  5574.8   0.035       0
  5695.9   0.045       0
Bank Sta=4102.1,4114.5
Exp/Cntr=0.3,0.1

Type RM Length L Ch R = 1,7858,495,495,495
BEGIN DESCRIPTION:
Alkali Creek Trib 04 5.0
END DESCRIPTION:
XS GIS Cut Line= 3
      1363104.98      6962788.01      1364705.00      6961838.00
      1365405.04      6961237.97
#Sta/Elev= 30
  3139.2 1984.72  3306.8 1982.08  3395.1 1978.60  3460.7 1980.50  3530.5 1975.56
  3577.6 1976.17  3620.5 1972.67  3657.5 1974.00  3709.1 1969.88  3774.4 1970.19
  3860.3 1966.74  4627.8 1966.85  4854.2 1964.00  4854.7 1963.50  4866.7 1964.00
  4936.4 1967.93  4965.0 1964.44  5035.7 1965.58  5056.5 1968.12  5120.6 1965.72
  5212.4 1966.28  5262.9 1969.64  5312.3 1968.69  5382.5 1973.20  5496.6 1972.93
  5539.5 1976.26  5581.2 1975.18  5687.6 1980.02  5872.0 1981.93  5922.0 1985.49
#Mann=7,-1,0
  3139.2   0.045       0  3306.8   0.035       0  3530.5   0.045       0
  4854.2    0.07       0  4866.7   0.045       0  4936.4    0.07       0
  5120.6   0.045       0
Bank Sta=4854.2,4866.7
Exp/Cntr=0.3,0.1

Type RM Length L Ch R = 1,7363,495,495,495
BEGIN DESCRIPTION:
Alkali Creek Trib 04 4.0
END DESCRIPTION:
XS GIS Cut Line= 3
      1363454.99      6962838.00      1365055.00      6962188.00
      1365655.00      6961738.00
#Sta/Elev= 30
  3273.0 1981.49  3550.1 1973.96  3586.0 1970.14  3740.2 1966.13  4017.8 1967.33
  4125.7 1964.16  4471.1 1965.08  4645.3 1962.53  4902.2 1963.53  4946.0 1966.07
  4967.6 1962.69  4978.8 1963.48  4991.0 1962.18  4991.5 1961.68  5003.5 1962.18
  5013.0 1962.90  5050.0 1966.13  5071.9 1962.56  5142.7 1964.03  5171.9 1966.91
  5263.5 1966.55  5307.3 1969.83  5363.5 1968.77  5428.1 1973.64  5486.5 1972.59
  5528.1 1975.67  5592.7 1975.37  5657.3 1979.59  5713.5 1979.36  5750.0 1982.69
#Mann=5,-1,0
  3273.0   0.045       0  4978.8    0.07       0  4991.0    0.07       0
  5003.5    0.07       0  5013.0   0.045       0
Bank Sta=4991,5003.5
Exp/Cntr=0.3,0.1

Type RM Length L Ch R = 1,6868,441,441,441
BEGIN DESCRIPTION:
Alkali Creek Trib 04 3.0
END DESCRIPTION:
XS GIS Cut Line= 3
      1363405.04      6962937.99      1365405.00      6962538.00
      1365805.01      6962037.98
#Sta/Elev= 30
  2960.4 1982.16  3052.1 1982.60  3113.3 1978.71  3174.5 1979.12  3215.3 1975.47
  3266.3 1976.50  3307.1 1972.88  3358.1 1973.40  3398.9 1969.79  3460.1 1970.11
  3500.9 1966.34  3572.2 1968.05  3633.4 1964.71  4133.1 1965.11  4377.9 1962.05
  4887.8 1962.36  4928.6 1964.41  4973.3 1960.80  4973.8 1960.30  4985.9 1960.80
  5028.0 1964.47  5056.8 1961.71  5106.4 1962.44  5178.5 1967.32  5213.7 1966.08
  5256.1 1969.97  5306.5 1969.59  5348.1 1973.67  5569.0 1975.55  5640.3 1979.61
#Mann=3,-1,0
  2960.4   0.045       0  4973.3   0.045       0  4985.9   0.045       0
Bank Sta=4973.3,4985.9
Exp/Cntr=0.3,0.1

Type RM Length L Ch R = 1,6427,479,479,479
BEGIN DESCRIPTION:
Alkali Creek Trib 04 2.0
END DESCRIPTION:
XS GIS Cut Line= 5
      1363654.98      6963088.00      1365655.00      6962888.00
      1365800.91      6962867.16      1365830.00      6962863.00
      1365980.00      6962063.01
#Sta/Elev= 30
  2994.8 1978.41  3042.6 1979.38  3085.3 1975.68  3135.5 1976.43  3165.7 1973.11
  3256.1 1969.63  3306.4 1970.55  3366.7 1965.97  3437.0 1967.45  3507.4 1964.19
  3899.3 1964.55  4281.2 1960.38  4421.9 1963.47  4650.5 1961.94  4703.3 1963.63
  4743.5 1960.86  4833.9 1960.14  4938.5 1962.17  4988.4 1959.44  4988.9 1958.94
  5001.0 1959.44  5038.5 1962.27  5291.8 1961.94  5359.6 1963.18  5410.5 1967.27
  5491.9 1966.34  5532.6 1970.24  5603.8 1968.93  5675.0 1974.38  5995.5 1975.93
#Mann=5,-1,0
  2994.8   0.045       0  4938.5    0.07       0  4988.4    0.07       0
  5001.0    0.07       0  5038.5   0.045       0
Bank Sta=4988.4,5001
Exp/Cntr=0.3,0.1

Type RM Length L Ch R = 1,5948,0,0,0
BEGIN DESCRIPTION:
Alkali Creek Trib 04 1.0
END DESCRIPTION:
XS GIS Cut Line= 4
      1364078.90      6963407.09      1365830.00      6963463.00
      1366010.00      6962613.00      1366055.00      6961787.97
#Sta/Elev= 30
  3078.2 1966.73  3144.3 1965.16  3184.4 1967.13  3234.4 1963.63  3464.5 1962.80
  3524.5 1964.34  3573.1 1962.22  3764.7 1962.58  3889.9 1960.09  4625.1 1959.33
  4855.8 1959.80  4880.0 1961.18  4982.3 1959.28  4982.8 1958.78  4994.9 1959.28
  5063.5 1961.11  5550.0 1961.67  5604.8 1962.62  5663.3 1967.31  5734.1 1966.21
  5784.2 1970.27  5824.2 1968.72  5904.4 1969.66  5974.5 1974.90  6104.6 1973.83
  6164.7 1976.00  6204.8 1974.80  6355.0 1975.87  6431.8 1979.19  6525.3 1978.30
#Mann=5,-1,0
  3078.2   0.045       0  4880.0    0.07       0  4982.3    0.07       0
  4994.9    0.07       0  5063.5   0.045       0
Bank Sta=4982.3,4994.9
Exp/Cntr=0.3,0.1

Chan Stop Cuts=-1