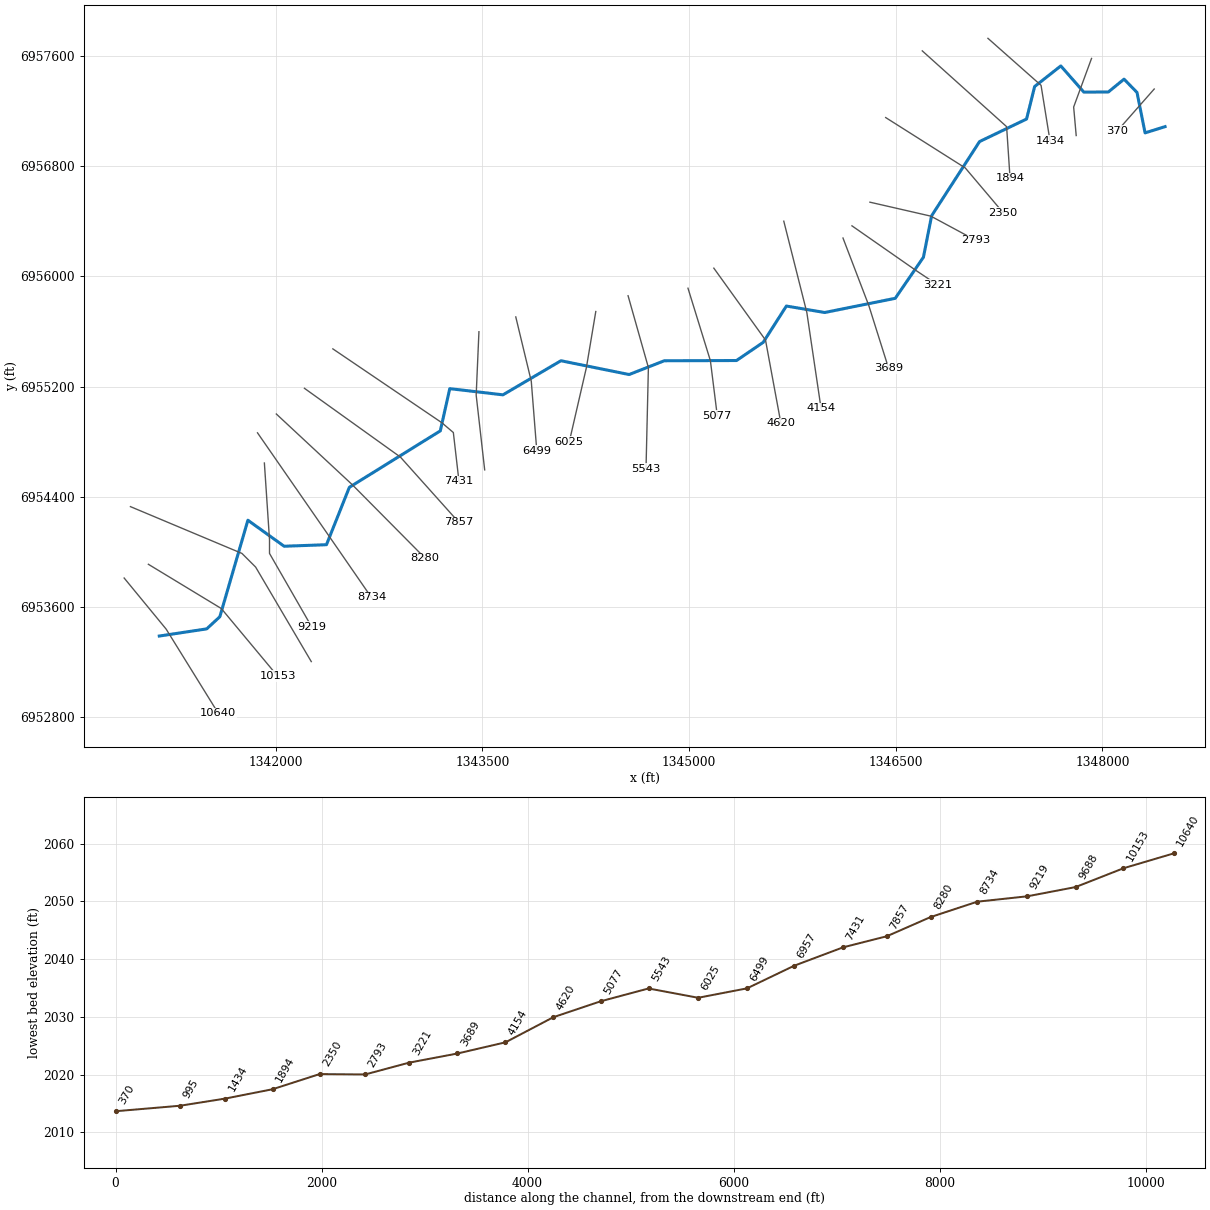
--- Alkali Creek Trib 06.prj (project) ---

Proj Title=Alkali Creek Trib 06 Base Level Engineering
Current Plan=p01
Default Exp/Contr=0.3,0.1
English Units
Geom File=g01
Flow File=f01
Plan File=p01
BEGIN DESCRIPTION:
Alkali Creek Trib 06
END DESCRIPTION:

--- Alkali Creek Trib 06.p01 (plan) ---

Plan Title=Multiple Run
Short Identifier=Multiple
Geom File=g01
Flow File=f01
Subcritical Flow
K Sum by GR= 0
Std Step Tol= 0.01
Critical Tol= 0.01
Num of Std Step Trials= 20
Max Error Tol= 0.3
Flow Tol Ratio= 0.001
Split Flow NTrial= 30
Split Flow Tol= 0.02
Split Flow Ratio= 0.02
Log Output Level= 0
Friction Slope Method= 1
Unsteady Friction Slope Method= 2
Unsteady Bridges Friction Slope Method= 1
Parabolic Critical Depth
Global Vel Dist=  1 , 1 , 1
Global Log Level= 0
CheckData=True
Encroach Param= -1, 0, 0, 0
BEGIN DESCRIPTION:
Multiple Run
END DESCRIPTION:

--- Alkali Creek Trib 06.f01 (steady flow) ---

Flow Title=Multiple
Number of Profiles=7
Profile Names=10-year,25-year,50-year,1pct_min,100-year,1pct_plu,500-year
River Rch & RM= Alkali Creek Tri,Reach-1,10640
     508     754     970     620    1238    2470    2044
River Rch & RM= Alkali Creek Tri,Reach-1,5077
     618     921    1188     761    1519    3030    2517
Boundary for River Rch & Prof#=Alkali Creek Tri,Reach-1,1
Up Type=0
Dn Type=3
Dn Slope=0.005
Boundary for River Rch & Prof#=Alkali Creek Tri,Reach-1,2
Up Type=0
Dn Type=3
Dn Slope=0.005
Boundary for River Rch & Prof#=Alkali Creek Tri,Reach-1,3
Up Type=0
Dn Type=3
Dn Slope=0.005
Boundary for River Rch & Prof#=Alkali Creek Tri,Reach-1,4
Up Type=0
Dn Type=3
Dn Slope=0.005
Boundary for River Rch & Prof#=Alkali Creek Tri,Reach-1,5
Up Type=0
Dn Type=3
Dn Slope=0.005
Boundary for River Rch & Prof#=Alkali Creek Tri,Reach-1,6
Up Type=0
Dn Type=3
Dn Slope=0.005
Boundary for River Rch & Prof#=Alkali Creek Tri,Reach-1,7
Up Type=0
Dn Type=3
Dn Slope=0.005

--- Alkali Creek Trib 06.g01 (geometry) ---

Geom Title=Existing Conditions

River Reach=Alkali Creek Tri,Reach-1
Reach XY= 30
      1341155.00      6953388.00      1341499.16      6953440.05
      1341594.49      6953528.19      1341798.00      6954229.18
      1342060.93      6954040.24      1342368.35      6954051.36
      1342534.48      6954468.28      1343194.52      6954878.20
      1343263.28      6955184.95      1343649.32      6955140.01
      1344070.16      6955387.63      1344565.17      6955287.50
      1344820.22      6955387.48      1345344.50      6955389.20
      1345538.36      6955521.29      1345706.42      6955784.96
      1345984.97      6955738.07      1346496.70      6955841.08
      1346701.24      6956139.56      1346760.54      6956440.42
      1347108.50      6956979.54      1347449.82      6957143.41
      1347508.51      6957379.52      1347698.34      6957529.05
      1347865.28      6957338.98      1348043.17      6957339.64
      1348157.28      6957432.95      1348251.39      6957336.52
      1348310.01      6957042.91      1348455.00      6957088.00

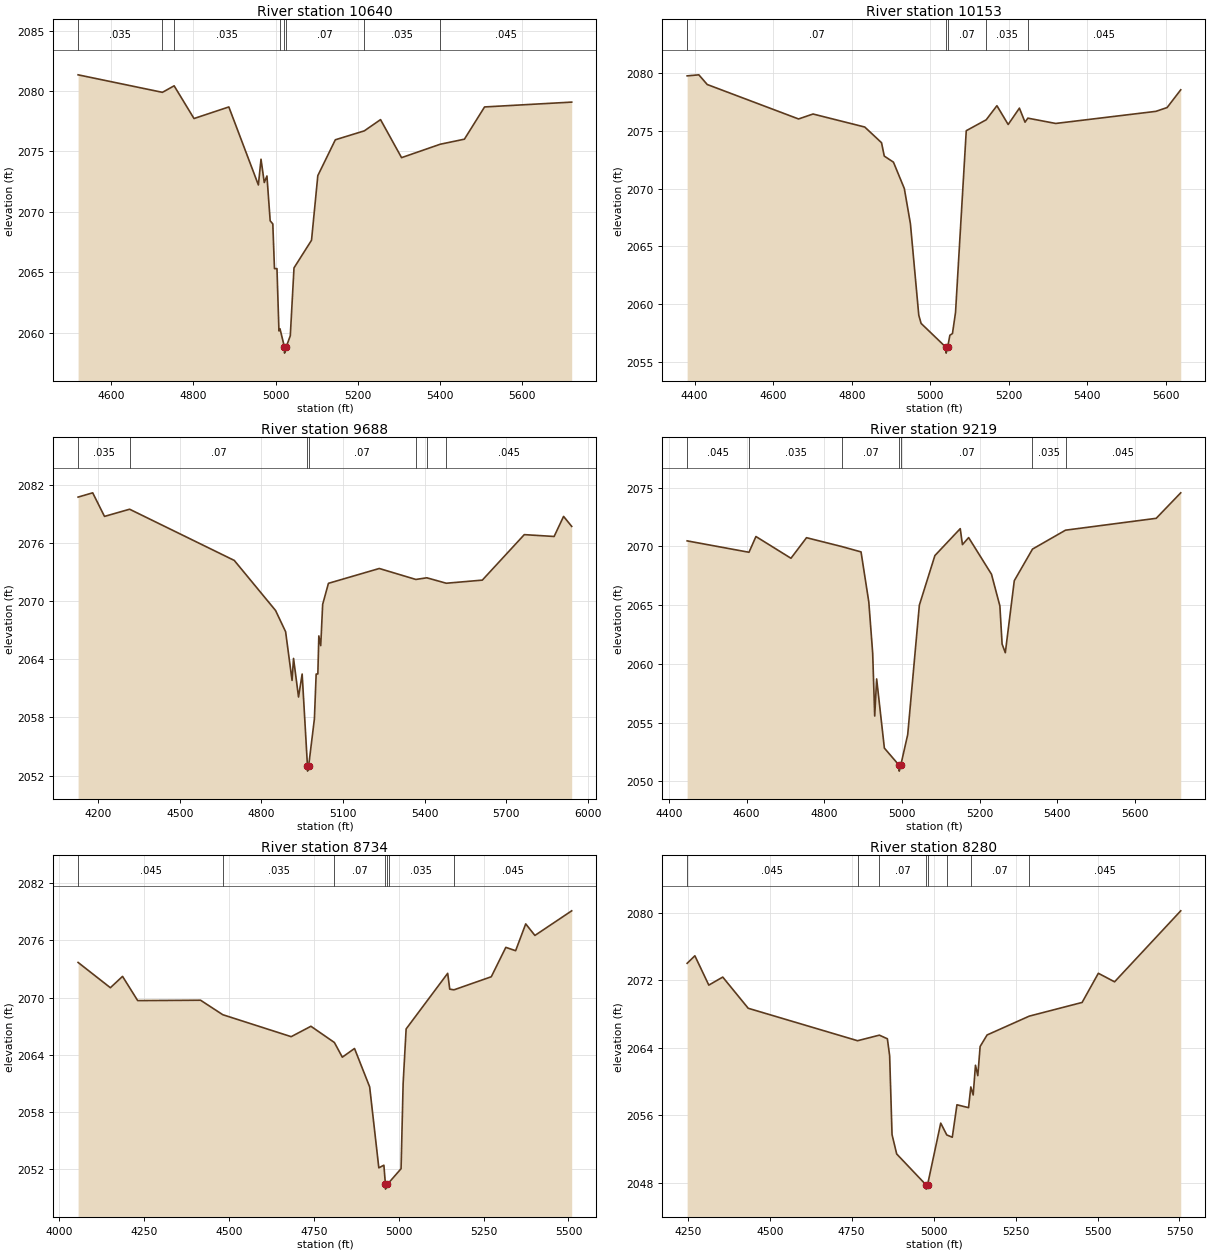
Type RM Length L Ch R = 1,10640,487,487,487
BEGIN DESCRIPTION:
Alkali Creek Trib 06 21.0
END DESCRIPTION:
XS GIS Cut Line= 3
      1340899.94      6953809.38      1341205.00      6953438.00
      1341583.56      6952826.27
#Sta/Elev= 30
  4519.9 2081.35  4724.9 2079.90  4753.4 2080.44  4801.7 2077.73  4886.4 2078.69
  4958.2 2072.23  4964.6 2074.36  4972.5 2072.43  4979.0 2072.97  4986.9 2069.26
  4993.3 2069.00  4997.3 2065.30  5003.4 2065.30  5008.2 2060.14  5010.7 2060.32
  5021.6 2058.80  5021.8 2058.30  5025.6 2058.80  5035.8 2059.74  5044.8 2065.36
  5087.4 2067.65  5102.7 2073.00  5145.3 2075.97  5215.8 2076.71  5255.2 2077.64
  5306.3 2074.49  5400.2 2075.60  5459.1 2076.02  5508.1 2078.69  5719.9 2079.09
#Mann=8,-1,0
  4519.9   0.035       0  4724.9    0.07       0  4753.4   0.035       0
  5010.7    0.07       0  5021.6   0.035       0  5025.6    0.07       0
  5215.8   0.035       0  5400.2   0.045       0
Bank Sta=5021.6,5025.6
Exp/Cntr=0.3,0.1

Type RM Length L Ch R = 1,10153,465,465,465
BEGIN DESCRIPTION:
Alkali Creek Trib 06 20.0
END DESCRIPTION:
XS GIS Cut Line= 3
      1341075.72      6953909.20      1341605.00      6953588.00
      1342013.21      6953097.59
#Sta/Elev= 30
  4380.8 2079.79  4410.6 2079.88  4432.0 2079.04  4664.6 2076.05  4701.4 2076.48
  4833.2 2075.35  4875.9 2073.99  4882.9 2072.83  4906.3 2072.30  4934.0 2070.01
  4949.5 2066.96  4970.8 2059.02  4976.7 2058.31  5040.2 2056.23  5040.5 2055.73
  5044.2 2056.23  5050.0 2057.28  5056.6 2057.43  5064.4 2059.26  5091.7 2075.03
  5142.6 2075.98  5169.8 2077.20  5198.5 2075.57  5227.1 2076.99  5241.4 2075.77
  5248.6 2076.12  5319.5 2075.66  5574.7 2076.71  5603.3 2077.04  5638.0 2078.58
#Mann=5,-1,0
  4380.8    0.07       0  5040.2    0.07       0  5044.2    0.07       0
  5142.6   0.035       0  5248.6   0.045       0
Bank Sta=5040.2,5044.2
Exp/Cntr=0.3,0.1

Type RM Length L Ch R = 1,9688,469,469,469
BEGIN DESCRIPTION:
Alkali Creek Trib 06 19.0
END DESCRIPTION:
XS GIS Cut Line= 4
      1340945.52      6954328.03      1341755.00      6953988.00
      1341854.19      6953889.03      1342258.11      6953202.33
#Sta/Elev= 30
  4126.1 2080.72  4179.8 2081.16  4223.2 2078.73  4315.5 2079.47  4700.4 2074.19
  4852.2 2069.03  4889.1 2066.84  4912.8 2061.82  4918.2 2064.09  4936.6 2060.11
  4949.9 2062.48  4969.5 2052.97  4969.8 2052.47  4973.6 2052.97  4994.9 2057.85
  5001.4 2062.48  5007.6 2062.48  5011.2 2066.41  5018.2 2065.41  5025.3 2069.66
  5046.5 2071.83  5233.5 2073.36  5367.9 2072.23  5408.3 2072.40  5479.7 2071.84
  5612.3 2072.16  5766.6 2076.85  5876.3 2076.66  5911.1 2078.73  5940.9 2077.70
#Mann=7,-1,0
  4126.1   0.035       0  4315.5    0.07       0  4969.5    0.07       0
  4973.6    0.07       0  5367.9   0.035       0  5408.3    0.07       0
  5479.7   0.045       0
Bank Sta=4969.5,4973.6
Exp/Cntr=0.3,0.1

Type RM Length L Ch R = 1,9219,485,485,485
BEGIN DESCRIPTION:
Alkali Creek Trib 06 18.0
END DESCRIPTION:
XS GIS Cut Line= 4
      1341917.75      6954644.85      1341955.00      6954088.00
      1341955.00      6953988.00      1342260.31      6953456.20
#Sta/Elev= 30
  4446.8 2070.47  4606.1 2069.50  4624.0 2070.84  4714.2 2068.99  4754.3 2070.74
  4845.7 2069.98  4894.7 2069.53  4914.7 2065.27  4924.7 2060.91  4929.9 2055.56
  4934.9 2058.72  4954.8 2052.83  4992.7 2051.37  4993.0 2050.87  4997.0 2051.37
  5014.9 2053.98  5044.9 2065.00  5084.9 2069.22  5150.2 2071.51  5155.9 2070.15
  5171.8 2070.75  5230.7 2067.63  5252.3 2064.93  5258.0 2061.69  5266.3 2060.95
  5289.4 2067.08  5336.3 2069.77  5421.3 2071.38  5654.9 2072.39  5718.1 2074.56
#Mann=7,-1,0
  4446.8   0.045       0  4606.1   0.035       0  4845.7    0.07       0
  4992.7    0.07       0  4997.0    0.07       0  5336.3   0.035       0
  5421.3   0.045       0
Bank Sta=4992.7,4997
Exp/Cntr=0.3,0.1

Type RM Length L Ch R = 1,8734,454,454,454
BEGIN DESCRIPTION:
Alkali Creek Trib 06 17.0
END DESCRIPTION:
XS GIS Cut Line= 3
      1341867.85      6954864.04      1342405.00      6954088.00
      1342694.63      6953668.35
#Sta/Elev= 30
  4055.7 2073.70  4150.8 2071.05  4186.6 2072.24  4231.2 2069.70  4416.4 2069.74
  4481.9 2068.22  4683.3 2065.92  4741.4 2067.01  4810.5 2065.31  4833.9 2063.77
  4869.8 2064.68  4914.4 2060.66  4941.4 2052.17  4956.3 2052.45  4960.8 2050.44
  4961.1 2049.94  4965.3 2050.44  4970.0 2050.58  5006.9 2052.08  5013.0 2061.03
  5021.8 2066.73  5144.2 2072.56  5150.3 2070.90  5162.7 2070.83  5272.6 2072.20
  5315.4 2075.28  5344.3 2074.93  5374.0 2077.74  5401.1 2076.53  5509.4 2079.11
#Mann=7,-1,0
  4055.7   0.045       0  4481.9   0.035       0  4810.5    0.07       0
  4960.8   0.035       0  4965.3    0.07       0  4970.0   0.035       0
  5162.7   0.045       0
Bank Sta=4960.8,4965.3
Exp/Cntr=0.3,0.1

Type RM Length L Ch R = 1,8280,423,423,423
BEGIN DESCRIPTION:
Alkali Creek Trib 06 16.0
END DESCRIPTION:
XS GIS Cut Line= 3
      1342004.55      6955000.78      1342555.00      6954488.00
      1343085.11      6953952.77
#Sta/Elev= 30
  4248.2 2073.99  4271.8 2074.88  4314.3 2071.41  4356.8 2072.36  4434.5 2068.67
  4768.1 2064.83  4834.6 2065.49  4859.0 2065.06  4865.9 2063.05  4873.2 2053.72
  4887.4 2051.43  4977.0 2047.77  4977.3 2047.27  4981.5 2047.77  5021.7 2055.08
  5040.2 2053.68  5057.0 2053.41  5071.2 2057.25  5106.6 2056.91  5113.5 2059.36
  5120.7 2058.41  5127.7 2061.93  5134.8 2060.70  5141.9 2064.15  5163.1 2065.51
  5291.8 2067.74  5453.0 2069.36  5502.5 2072.81  5552.0 2071.80  5753.8 2080.20
#Mann=8,-1,0
  4248.2   0.045       0  4768.1   0.035       0  4834.6    0.07       0
  4977.0    0.07       0  4981.5    0.07       0  5040.2   0.035       0
  5113.5    0.07       0  5291.8   0.045       0
Bank Sta=4977,4981.5
Exp/Cntr=0.3,0.1

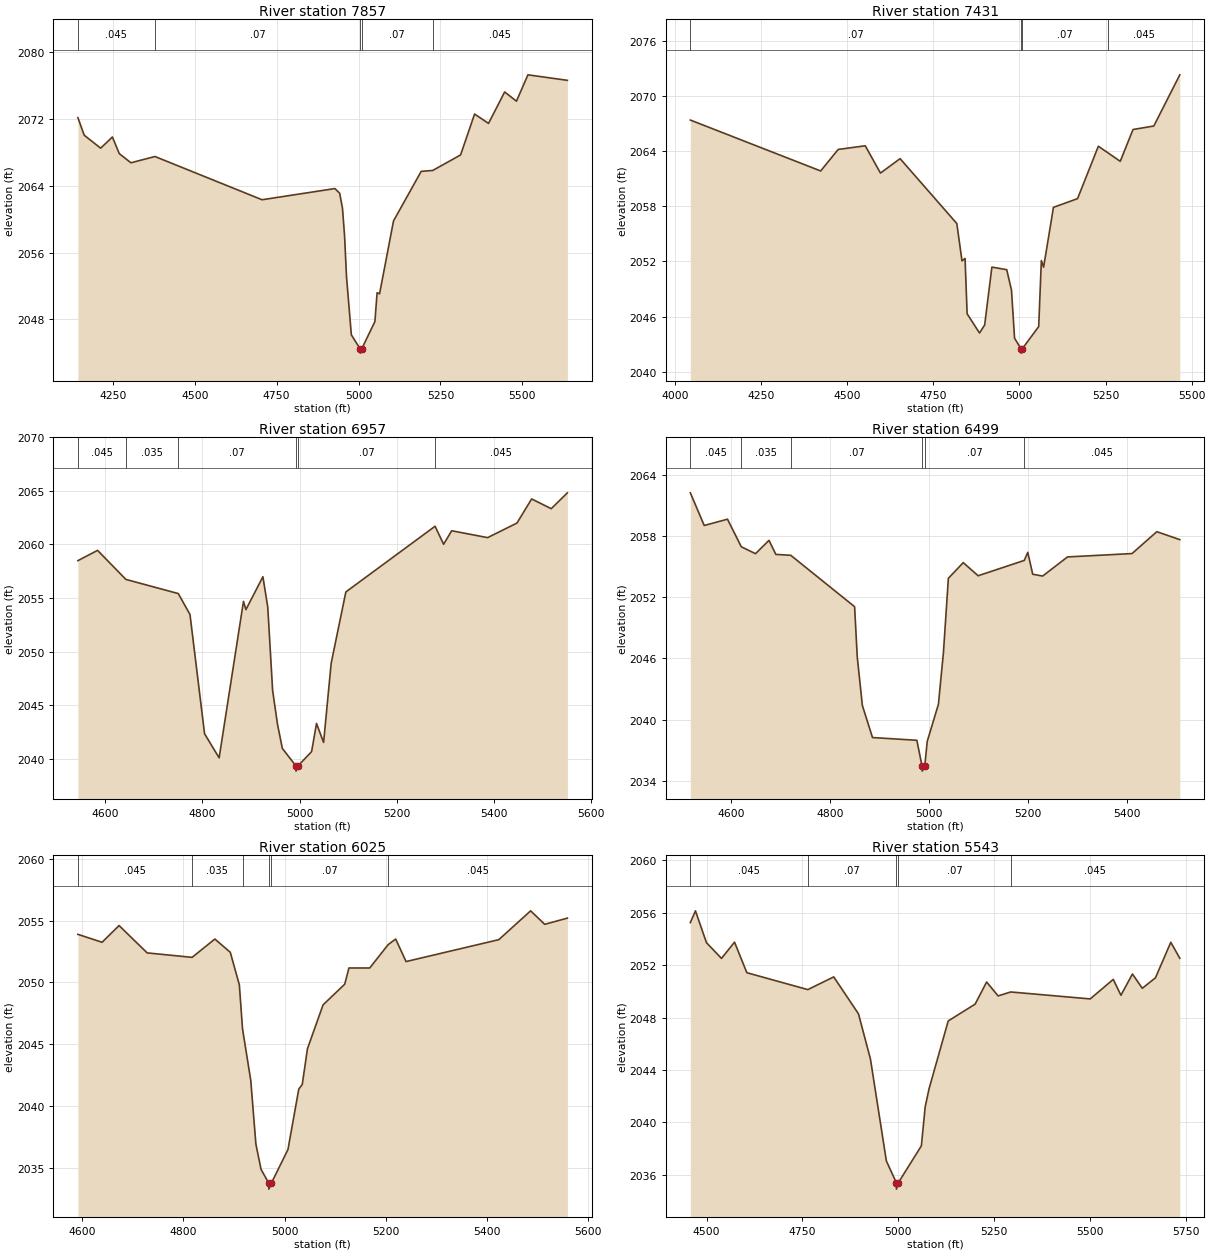
Type RM Length L Ch R = 1,7857,426,426,426
BEGIN DESCRIPTION:
Alkali Creek Trib 06 15.0
END DESCRIPTION:
XS GIS Cut Line= 3
      1342208.51      6955187.43      1342905.00      6954688.00
      1343329.99      6954213.02
#Sta/Elev= 30
  4143.2 2072.18  4162.6 2070.07  4212.7 2068.52  4248.6 2069.86  4269.5 2067.87
  4305.1 2066.77  4378.5 2067.52  4705.5 2062.34  4927.8 2063.68  4942.5 2063.12
  4951.0 2061.32  4957.3 2058.08  4963.4 2053.07  4978.1 2046.15  5005.1 2044.46
  5005.4 2043.96  5009.6 2044.46  5050.0 2047.74  5056.7 2051.20  5064.2 2051.06
  5106.8 2059.80  5191.3 2065.74  5226.6 2065.85  5311.6 2067.71  5354.3 2072.61
  5396.9 2071.49  5446.2 2075.26  5482.1 2074.15  5517.2 2077.31  5637.6 2076.65
#Mann=5,-1,0
  4143.2   0.045       0  4378.5    0.07       0  5005.1    0.07       0
  5009.6    0.07       0  5226.6   0.045       0
Bank Sta=5005.1,5009.6
Exp/Cntr=0.3,0.1

Type RM Length L Ch R = 1,7431,474,474,474
BEGIN DESCRIPTION:
Alkali Creek Trib 06 14.0
END DESCRIPTION:
XS GIS Cut Line= 4
      1342414.69      6955473.88      1343205.00      6954938.00
      1343289.28      6954866.22      1343330.00      6954513.02
#Sta/Elev= 30
  4044.6 2067.39  4423.0 2061.85  4473.8 2064.19  4552.4 2064.59  4596.6 2061.62
  4653.6 2063.19  4818.3 2056.13  4833.3 2052.07  4842.2 2052.33  4848.2 2046.31
  4884.2 2044.22  4899.1 2045.09  4920.1 2051.39  4963.2 2051.11  4977.0 2048.88
  4985.9 2043.65  5004.3 2042.53  5004.6 2042.03  5008.9 2042.53  5056.0 2044.92
  5063.7 2052.10  5070.3 2051.38  5098.8 2057.89  5168.8 2058.84  5229.2 2064.54
  5256.7 2063.83  5292.8 2062.90  5329.8 2066.36  5390.2 2066.74  5465.7 2072.31
#Mann=4,-1,0
  4044.6    0.07       0  5004.3    0.07       0  5008.9    0.07       0
  5256.7   0.045       0
Bank Sta=5004.3,5008.9
Exp/Cntr=0.3,0.1

Type RM Length L Ch R = 1,6957,458,458,458
BEGIN DESCRIPTION:
Alkali Creek Trib 06 13.0
END DESCRIPTION:
XS GIS Cut Line= 3
      1343475.04      6955598.44      1343455.00      6955138.00
      1343516.71      6954594.97
#Sta/Elev= 30
  4543.6 2058.49  4584.1 2059.45  4642.4 2056.74  4750.2 2055.42  4774.3 2053.47
  4804.3 2042.34  4834.3 2040.09  4884.4 2054.69  4889.4 2053.92  4924.4 2056.99
  4934.4 2054.15  4944.4 2046.37  4954.4 2043.23  4964.4 2040.97  4992.1 2039.35
  4992.5 2038.85  4996.8 2039.35  5024.6 2040.67  5034.7 2043.30  5049.3 2041.53
  5064.9 2048.92  5095.1 2055.57  5278.7 2061.70  5296.3 2060.02  5312.9 2061.28
  5386.9 2060.64  5447.3 2062.00  5477.5 2064.25  5517.8 2063.34  5551.0 2064.82
#Mann=6,-1,0
  4543.6   0.045       0  4642.4   0.035       0  4750.2    0.07       0
  4992.1    0.07       0  4996.8    0.07       0  5278.7   0.045       0
Bank Sta=4992.1,4996.8
Exp/Cntr=0.3,0.1

Type RM Length L Ch R = 1,6499,474,474,474
BEGIN DESCRIPTION:
Alkali Creek Trib 06 12.0
END DESCRIPTION:
XS GIS Cut Line= 3
      1343742.41      6955706.02      1343855.00      6955238.00
      1343895.08      6954731.66
#Sta/Elev= 30
  4518.2 2062.28  4546.3 2059.07  4593.3 2059.69  4621.2 2056.98  4649.9 2056.30
  4677.2 2057.61  4691.0 2056.23  4721.2 2056.14  4850.2 2051.09  4855.6 2046.13
  4865.9 2041.38  4886.4 2038.23  4976.0 2037.96  4986.5 2035.43  4986.9 2034.93
  4992.0 2035.43  4997.0 2037.85  5019.6 2041.50  5029.7 2046.56  5039.7 2053.88
  5069.8 2055.42  5099.9 2054.13  5193.2 2055.64  5200.2 2056.43  5210.2 2054.28
  5230.3 2054.10  5280.5 2055.98  5410.9 2056.31  5461.0 2058.46  5507.5 2057.68
#Mann=6,-1,0
  4518.2   0.045       0  4621.2   0.035       0  4721.2    0.07       0
  4986.5    0.07       0  4992.0    0.07       0  5193.2   0.045       0
Bank Sta=4986.5,4992
Exp/Cntr=0.3,0.1

Type RM Length L Ch R = 1,6025,482,482,482
BEGIN DESCRIPTION:
Alkali Creek Trib 06 11.0
END DESCRIPTION:
XS GIS Cut Line= 3
      1344323.13      6955745.12      1344255.00      6955338.00
      1344130.43      6954797.24
#Sta/Elev= 30
  4591.5 2053.89  4639.3 2053.25  4672.9 2054.60  4728.5 2052.39  4817.3 2052.03
  4862.3 2053.51  4892.8 2052.44  4910.7 2049.81  4917.0 2046.25  4933.3 2042.08
  4943.4 2036.94  4953.6 2034.90  4968.6 2033.80  4969.0 2033.30  4974.2 2033.80
  5006.8 2036.50  5028.2 2041.38  5035.1 2041.76  5045.3 2044.64  5076.2 2048.19
  5119.0 2049.86  5127.4 2051.17  5168.5 2051.17  5204.9 2053.06  5219.8 2053.51
  5240.3 2051.69  5423.7 2053.46  5486.6 2055.79  5514.4 2054.70  5559.2 2055.20
#Mann=6,-1,0
  4591.5   0.045       0  4817.3   0.035       0  4917.0    0.07       0
  4968.6    0.07       0  4974.2    0.07       0  5204.9   0.045       0
Bank Sta=4968.6,4974.2
Exp/Cntr=0.3,0.1

Type RM Length L Ch R = 1,5543,466,466,466
BEGIN DESCRIPTION:
Alkali Creek Trib 06 10.0
END DESCRIPTION:
XS GIS Cut Line= 3
      1344557.50      6955859.75      1344705.00      6955338.00
      1344687.72      6954604.50
#Sta/Elev= 30
  4457.8 2055.24  4471.1 2056.14  4499.9 2053.71  4539.0 2052.51  4573.0 2053.75
  4605.1 2051.42  4764.0 2050.13  4831.6 2051.10  4896.1 2048.28  4927.3 2044.83
  4968.8 2037.06  4994.6 2035.41  4995.1 2034.91  5000.2 2035.41  5060.0 2038.21
  5070.0 2041.19  5080.0 2042.56  5130.0 2047.74  5200.1 2049.02  5230.1 2050.71
  5260.1 2049.65  5293.0 2049.95  5500.1 2049.42  5560.2 2050.91  5580.2 2049.70
  5610.2 2051.32  5636.0 2050.23  5670.2 2051.03  5710.2 2053.74  5733.7 2052.52
#Mann=5,-1,0
  4457.8   0.045       0  4764.0    0.07       0  4994.6    0.07       0
  5000.2    0.07       0  5293.0   0.045       0
Bank Sta=4994.6,5000.2
Exp/Cntr=0.3,0.1

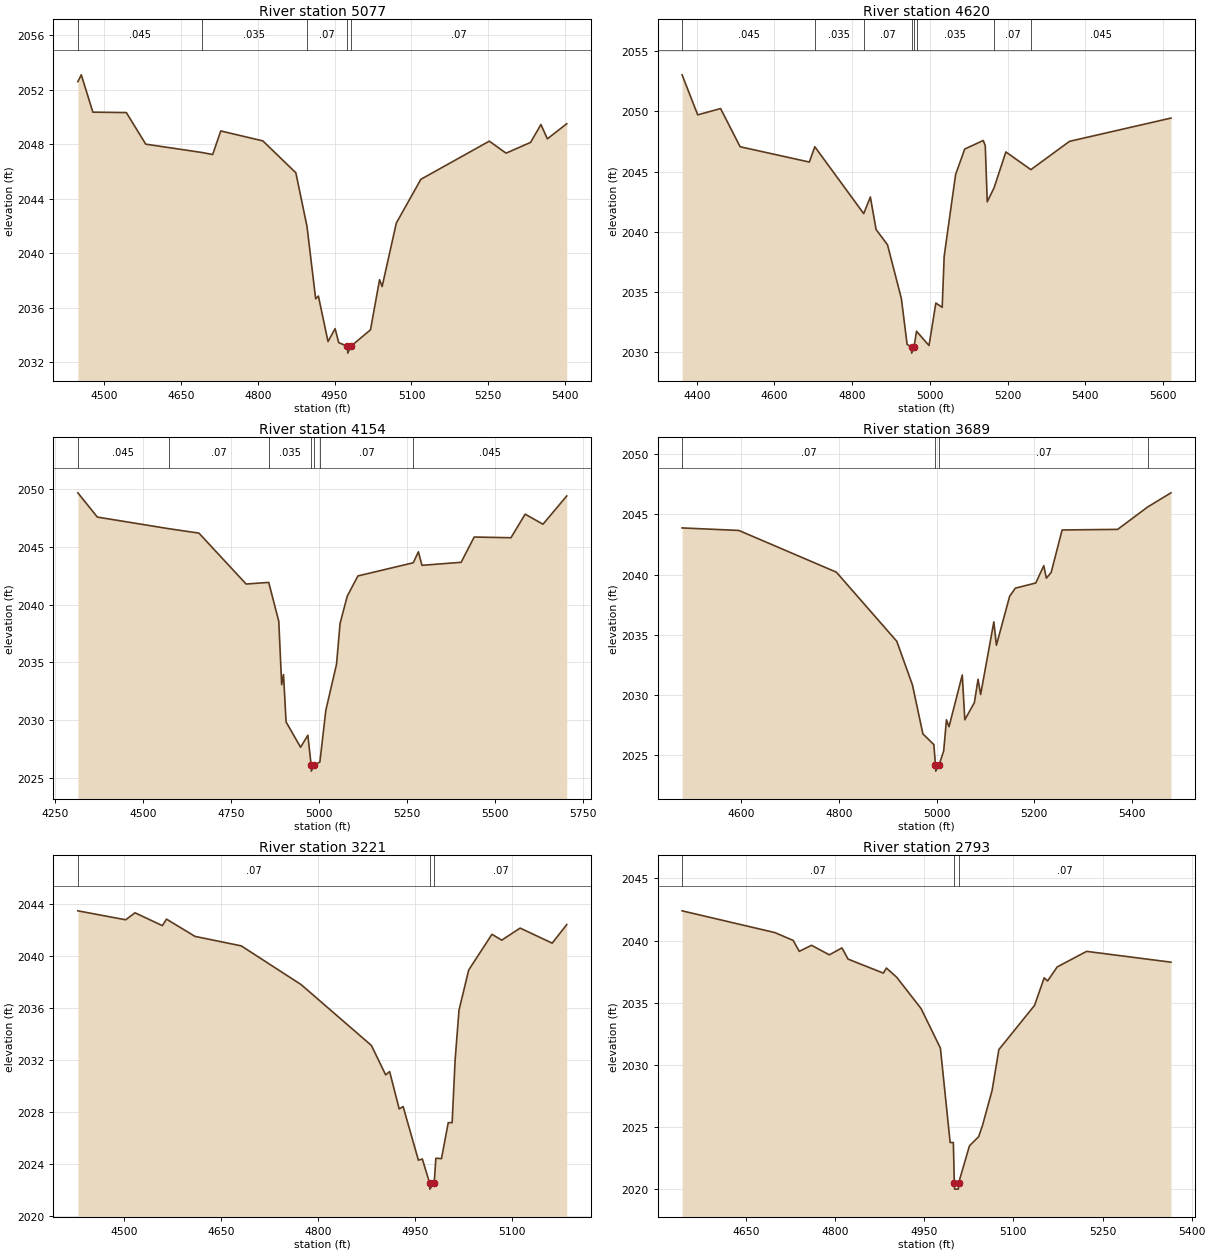
Type RM Length L Ch R = 1,5077,457,457,457
BEGIN DESCRIPTION:
Alkali Creek Trib 06 9.0
END DESCRIPTION:
XS GIS Cut Line= 3
      1344992.39      6955914.44      1345155.00      6955388.00
      1345205.00      6954987.99
#Sta/Elev= 30
  4449.0 2052.61  4455.7 2053.11  4478.3 2050.37  4543.6 2050.34  4581.5 2048.02
  4690.9 2047.41  4712.1 2047.26  4727.9 2048.99  4810.0 2048.26  4874.4 2045.92
  4896.2 2041.98  4913.1 2036.67  4918.4 2036.87  4937.2 2033.53  4951.0 2034.48
  4958.1 2033.45  4975.2 2033.18  4975.7 2032.68  4981.6 2033.18  5020.1 2034.39
  5037.8 2038.07  5042.8 2037.57  5070.5 2042.23  5118.4 2045.44  5251.9 2048.24
  5284.7 2047.36  5332.5 2048.15  5352.7 2049.46  5365.3 2048.41  5403.1 2049.52
#Mann=5,-1,0
  4449.0   0.045       0  4690.9   0.035       0  4896.2    0.07       0
  4975.2    0.07       0  4981.6    0.07       0
Bank Sta=4975.2,4981.6
Exp/Cntr=0.3,0.1

Type RM Length L Ch R = 1,4620,466,466,466
BEGIN DESCRIPTION:
Alkali Creek Trib 06 8.0
END DESCRIPTION:
XS GIS Cut Line= 3
      1345179.89      6956060.25      1345555.00      6955538.00
      1345666.84      6954932.85
#Sta/Elev= 30
  4362.3 2053.04  4402.5 2049.72  4461.4 2050.24  4511.7 2047.07  4689.8 2045.80
  4703.9 2047.07  4829.8 2041.52  4846.9 2042.90  4861.7 2040.20  4891.1 2038.93
  4926.7 2034.48  4941.5 2030.67  4952.8 2030.44  4953.3 2029.94  4959.3 2030.44
  4965.7 2031.76  4997.9 2030.57  5015.5 2034.10  5031.8 2033.74  5036.9 2037.98
  5066.3 2044.76  5089.8 2046.88  5137.5 2047.59  5142.7 2047.15  5147.8 2042.50
  5165.4 2043.67  5195.7 2046.64  5260.1 2045.17  5359.6 2047.52  5620.7 2049.45
#Mann=8,-1,0
  4362.3   0.045       0  4703.9   0.035       0  4829.8    0.07       0
  4952.8   0.035       0  4959.3    0.07       0  4965.7   0.035       0
  5165.4    0.07       0  5260.1   0.045       0
Bank Sta=4952.8,4959.3
Exp/Cntr=0.3,0.1

Type RM Length L Ch R = 1,4154,465,465,465
BEGIN DESCRIPTION:
Alkali Creek Trib 06 7.0
END DESCRIPTION:
XS GIS Cut Line= 3
      1345687.70      6956401.42      1345855.00      6955738.00
      1345958.28      6955041.20
#Sta/Elev= 30
  4315.4 2049.69  4370.7 2047.59  4574.3 2046.58  4659.3 2046.20  4793.3 2041.79
  4857.5 2041.93  4886.1 2038.56  4894.3 2033.07  4899.5 2033.95  4906.8 2029.84
  4948.0 2027.65  4968.7 2028.69  4978.1 2026.08  4978.6 2025.58  4985.2 2026.08
  5002.8 2026.37  5019.8 2030.86  5050.1 2034.84  5060.2 2038.38  5080.5 2040.73
  5110.8 2042.49  5268.0 2043.63  5282.6 2044.58  5292.8 2043.41  5404.0 2043.67
  5441.1 2045.86  5545.5 2045.80  5585.9 2047.84  5636.5 2046.97  5704.0 2049.42
#Mann=7,-1,0
  4315.4   0.045       0  4574.3    0.07       0  4857.5   0.035       0
  4978.1   0.035       0  4985.2   0.035       0  5002.8    0.07       0
  5268.0   0.045       0
Bank Sta=4978.1,4985.2
Exp/Cntr=0.3,0.1

Type RM Length L Ch R = 1,3689,468,468,468
BEGIN DESCRIPTION:
Alkali Creek Trib 06 6.0
END DESCRIPTION:
XS GIS Cut Line= 3
      1346117.40      6956278.98      1346305.00      6955788.00
      1346448.12      6955333.71
#Sta/Elev= 30
  4478.5 2043.88  4594.9 2043.67  4794.7 2040.20  4918.5 2034.45  4950.6 2030.82
  4972.0 2026.75  4994.4 2025.86  4997.8 2024.15  4998.3 2023.65  5005.0 2024.15
  5014.6 2025.33  5020.3 2027.92  5025.5 2027.34  5052.7 2031.65  5057.9 2027.92
  5077.5 2029.35  5085.0 2031.29  5090.3 2030.02  5117.4 2036.07  5122.6 2034.12
  5149.8 2038.20  5161.4 2038.87  5203.3 2039.30  5219.7 2040.74  5225.0 2039.70
  5234.8 2040.17  5257.3 2043.71  5371.1 2043.76  5432.9 2045.63  5480.4 2046.80
#Mann=4,-1,0
  4478.5    0.07       0  4997.8    0.07       0  5005.0    0.07       0
  5432.9   0.045       0
Bank Sta=4997.8,5005
Exp/Cntr=0.3,0.1

Type RM Length L Ch R = 1,3221,428,428,428
BEGIN DESCRIPTION:
Alkali Creek Trib 06 5.0
END DESCRIPTION:
XS GIS Cut Line= 3
      1346182.51      6956367.52      1346655.00      6956038.00
      1346804.98      6955938.01
#Sta/Elev= 30
  4428.4 2043.51  4502.4 2042.82  4516.8 2043.36  4559.1 2042.37  4565.5 2042.87
  4609.7 2041.54  4681.2 2040.81  4773.7 2037.83  4882.5 2033.14  4904.6 2030.87
  4910.7 2031.13  4925.5 2028.25  4931.6 2028.43  4955.2 2024.30  4961.3 2024.39
  4972.4 2022.57  4972.9 2022.07  4979.7 2022.57  4982.2 2024.45  4990.9 2024.42
  5001.4 2027.19  5007.4 2027.19  5012.0 2032.00  5018.0 2035.85  5033.0 2038.95
  5069.0 2041.70  5084.1 2041.25  5112.6 2042.18  5162.2 2041.02  5184.7 2042.45
#Mann=3,-1,0
  4428.4    0.07       0  4972.4    0.07       0  4979.7    0.07       0
Bank Sta=4972.4,4979.7
Exp/Cntr=0.3,0.1

Type RM Length L Ch R = 1,2793,443,443,443
BEGIN DESCRIPTION:
Alkali Creek Trib 06 4.0
END DESCRIPTION:
XS GIS Cut Line= 3
      1346312.74      6956539.39      1346755.00      6956438.00
      1347080.04      6956262.98
#Sta/Elev= 30
  4542.3 2042.40  4698.5 2040.65  4729.3 2040.02  4739.5 2039.14  4760.1 2039.63
  4790.2 2038.86  4811.4 2039.42  4821.6 2038.52  4881.1 2037.39  4886.2 2037.80
  4903.7 2037.05  4944.7 2034.53  4977.1 2031.36  4993.5 2023.77  4998.9 2023.77
  5000.5 2020.52  5001.0 2020.02  5007.3 2020.02  5007.8 2020.52  5026.0 2023.50
  5041.5 2024.24  5048.0 2025.15  5064.2 2027.98  5075.5 2031.24  5135.6 2034.80
  5151.8 2037.01  5157.5 2036.76  5173.7 2037.89  5223.2 2039.14  5365.2 2038.27
#Mann=3,-1,0
  4542.3    0.07       0  5000.5    0.07       0  5007.8    0.07       0
Bank Sta=5000.5,5007.8
Exp/Cntr=0.3,0.1

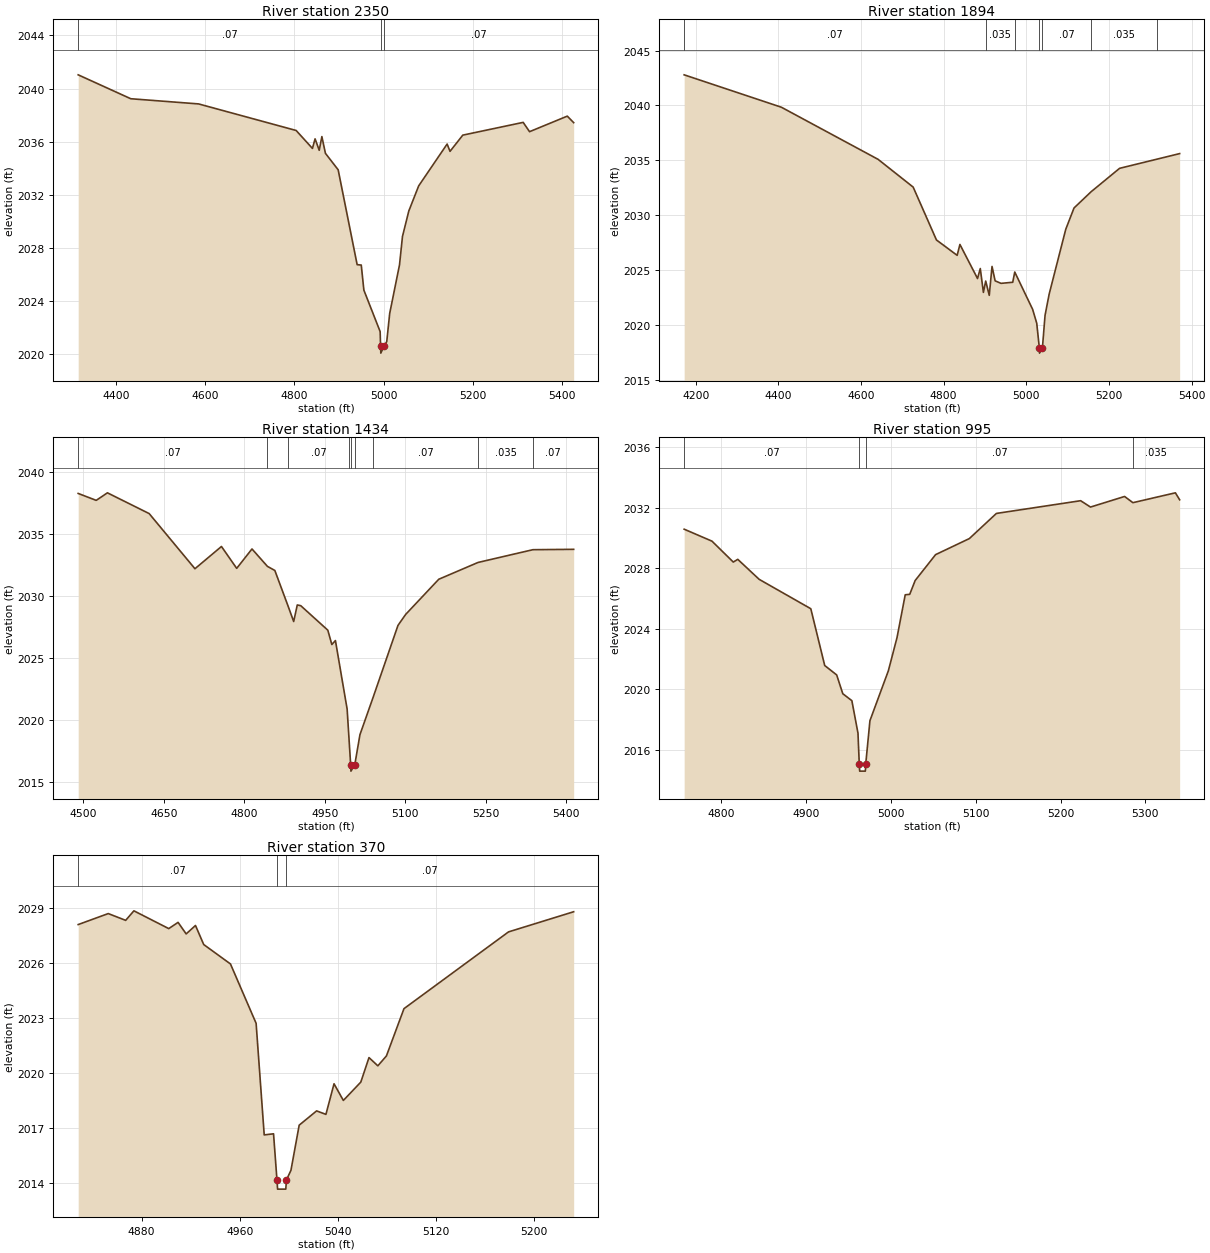
Type RM Length L Ch R = 1,2350,456,456,456
BEGIN DESCRIPTION:
Alkali Creek Trib 06 3.0
END DESCRIPTION:
XS GIS Cut Line= 3
      1346427.30      6957153.99      1347005.00      6956788.00
      1347279.99      6956463.01
#Sta/Elev= 30
  4315.9 2041.03  4433.7 2039.23  4585.5 2038.84  4804.0 2036.84  4840.5 2035.49
  4846.4 2036.21  4855.7 2035.35  4861.6 2036.38  4869.6 2035.12  4898.1 2033.88
  4940.6 2026.74  4949.8 2026.71  4955.7 2024.82  4992.1 2021.70  4993.1 2020.58
  4993.6 2020.08  5000.5 2020.58  5006.9 2020.95  5013.5 2023.07  5035.5 2026.73
  5042.1 2028.86  5056.3 2030.78  5078.4 2032.67  5142.1 2035.82  5148.6 2035.27
  5177.2 2036.49  5312.4 2037.45  5326.7 2036.75  5411.2 2037.92  5425.5 2037.43
#Mann=3,-1,0
  4315.9    0.07       0  4993.1    0.07       0  5000.5    0.07       0
Bank Sta=4993.1,5000.5
Exp/Cntr=0.3,0.1

Type RM Length L Ch R = 1,1894,460,460,460
BEGIN DESCRIPTION:
Alkali Creek Trib 06 2.0
END DESCRIPTION:
XS GIS Cut Line= 3
      1346692.91      6957638.37      1347305.00      6957088.00
      1347330.00      6956712.97
#Sta/Elev= 30
  4172.0 2042.79  4407.3 2039.84  4641.2 2035.10  4726.2 2032.57  4782.5 2027.76
  4832.6 2026.36  4839.3 2027.35  4881.9 2024.25  4888.6 2025.16  4896.1 2022.99
  4901.7 2024.02  4910.3 2022.72  4917.0 2025.35  4924.5 2024.04  4938.7 2023.81
  4967.1 2023.91  4972.0 2024.84  5015.2 2021.45  5025.2 2020.18  5031.4 2017.96
  5031.9 2017.46  5039.0 2017.96  5045.3 2020.90  5055.3 2022.84  5095.4 2028.73
  5115.4 2030.67  5156.8 2032.15  5225.7 2034.28  5316.8 2035.12  5371.0 2035.62
#Mann=7,-1,0
  4172.0    0.07       0  4901.7   0.035       0  4972.0    0.07       0
  5031.4    0.07       0  5039.0    0.07       0  5156.8   0.035       0
  5316.8    0.07       0
Bank Sta=5031.4,5039
Exp/Cntr=0.3,0.1

Type RM Length L Ch R = 1,1434,439,439,439
BEGIN DESCRIPTION:
Alkali Creek Trib 06 1.0
END DESCRIPTION:
XS GIS Cut Line= 3
      1347169.52      6957729.48      1347555.00      6957388.00
      1347620.00      6956984.78
#Sta/Elev= 30
  4490.3 2038.30  4523.9 2037.74  4544.8 2038.35  4622.6 2036.67  4707.9 2032.21
  4757.3 2034.01  4785.7 2032.24  4814.2 2033.81  4843.0 2032.40  4856.8 2032.07
  4881.2 2029.22  4891.9 2027.94  4898.6 2029.28  4905.1 2029.22  4955.5 2027.24
  4963.0 2026.08  4969.7 2026.40  4991.5 2020.86  4994.9 2018.53  4998.1 2016.34
  4998.6 2015.84  5005.7 2016.34  5015.4 2018.79  5039.7 2021.78  5086.3 2027.63
  5100.5 2028.51  5162.3 2031.36  5235.6 2032.72  5337.7 2033.75  5413.7 2033.78
#Mann=9,-1,0
  4490.3    0.07       0  4843.0   0.035       0  4881.2    0.07       0
  4994.9   0.035       0  4998.1   0.035       0  5005.7   0.035       0
  5039.7    0.07       0  5235.6   0.035       0  5337.7    0.07       0
Bank Sta=4998.1,5005.7
Exp/Cntr=0.3,0.1

Type RM Length L Ch R = 1,995,625,625,625
BEGIN DESCRIPTION:
Alkali Creek Trib 06 0.9
END DESCRIPTION:
XS GIS Cut Line= 3
      1347921.39      6957583.53      1347791.61      6957230.55
      1347810.03      6957023.35
#Sta/Elev= 30
  4756.3 2030.57  4789.1 2029.78  4814.2 2028.40  4819.5 2028.58  4844.7 2027.26
  4905.6 2025.32  4922.0 2021.57  4936.1 2020.95  4943.3 2019.71  4954.0 2019.25
  4961.2 2017.11  4962.7 2015.10  4963.2 2014.60  4969.9 2014.60  4970.4 2015.10
  4975.3 2017.93  4997.0 2021.22  5007.2 2023.41  5016.9 2026.24  5022.2 2026.27
  5028.6 2027.18  5052.7 2028.89  5092.5 2029.95  5124.4 2031.61  5223.7 2032.45
  5235.3 2032.03  5275.5 2032.73  5285.3 2032.32  5335.4 2032.97  5340.4 2032.51
#Mann=4,-1,0
  4756.3    0.07       0  4962.7    0.07       0  4970.4    0.07       0
  5285.3   0.035       0
Bank Sta=4962.7,4970.4
Exp/Cntr=0.3,0.1

Type RM Length L Ch R = 1,370,0,0,0
BEGIN DESCRIPTION:
Alkali Creek Trib 06 0.8
END DESCRIPTION:
XS GIS Cut Line= 2
      1348376.23      6957361.30      1348109.47      6957058.16
#Sta/Elev= 30
  4828.4 2028.09  4852.9 2028.69  4867.1 2028.32  4873.8 2028.84  4902.2 2027.87
  4909.8 2028.21  4916.4 2027.58  4924.0 2028.04  4930.7 2027.00  4952.5 2025.94
  4973.4 2022.70  4980.0 2016.61  4987.6 2016.67  4990.4 2014.15  4990.9 2013.65
  4997.6 2013.65  4998.1 2014.15  5001.8 2014.68  5008.5 2017.14  5022.7 2017.92
  5030.3 2017.73  5036.9 2019.40  5044.5 2018.49  5058.7 2019.49  5065.4 2020.83
  5072.6 2020.38  5079.6 2020.92  5093.9 2023.50  5179.1 2027.69  5232.2 2028.79
#Mann=3,-1,0
  4828.4    0.07       0  4990.4    0.07       0  4998.1    0.07       0
Bank Sta=4990.4,4998.1
Exp/Cntr=0.3,0.1

Chan Stop Cuts=-1