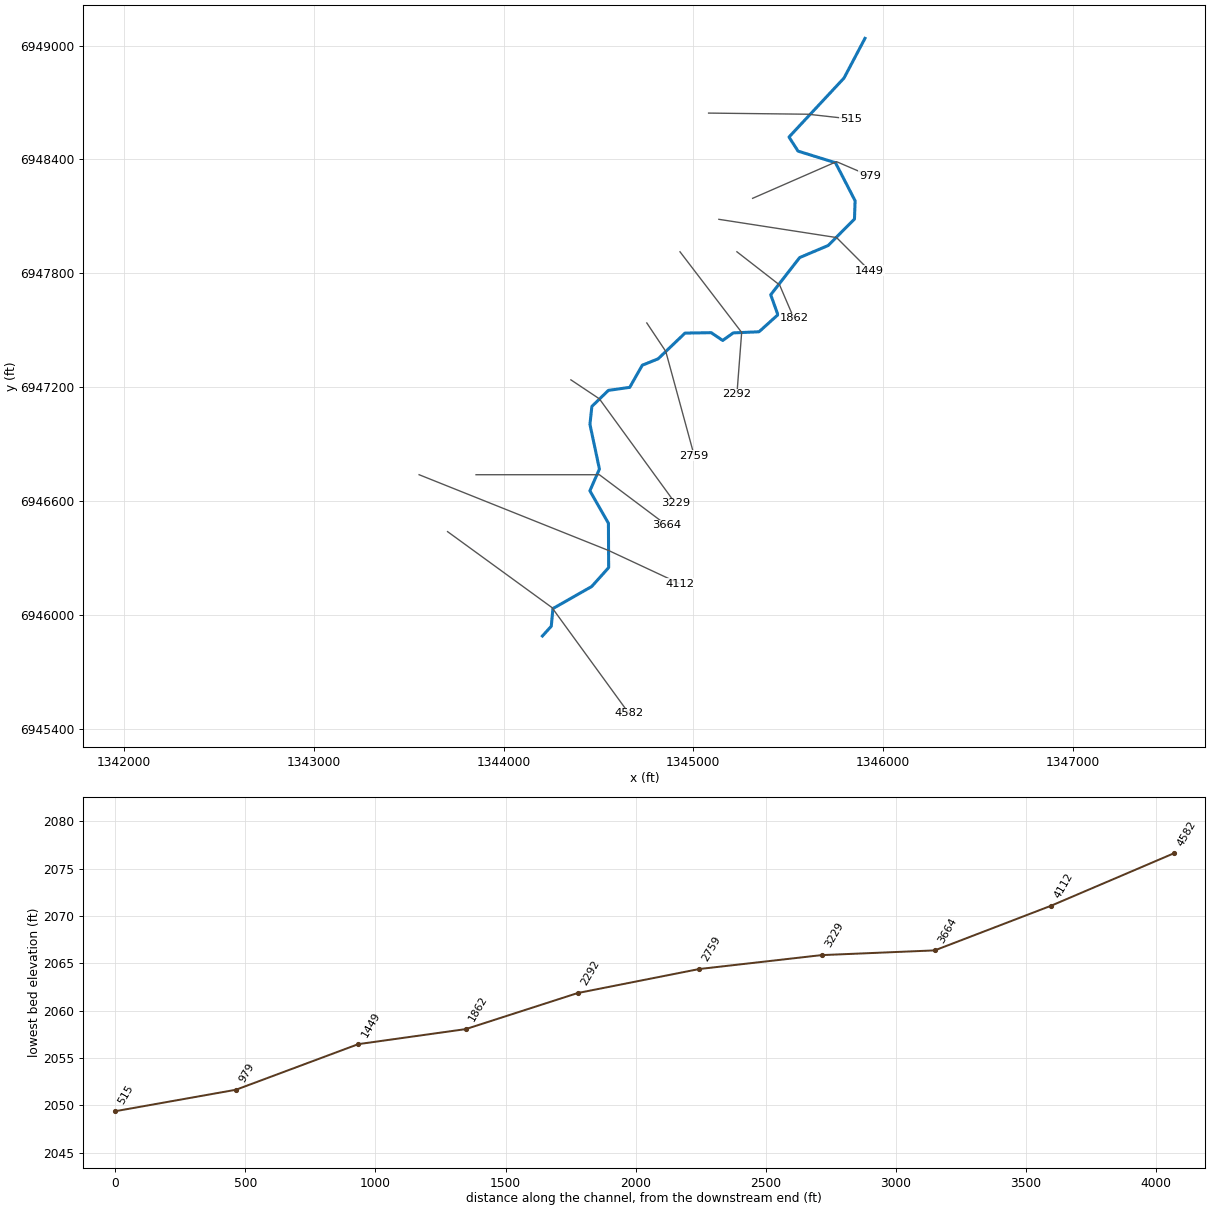
--- Alkali Creek Trib 07.prj (project) ---

Proj Title=Alkali Creek Trib 07 Base Level Engineering
Current Plan=p01
Default Exp/Contr=0.3,0.1
English Units
Geom File=g01
Flow File=f01
Plan File=p01
BEGIN DESCRIPTION:
Alkali Creek Trib 07
END DESCRIPTION:

--- Alkali Creek Trib 07.p01 (plan) ---

Plan Title=Multiple Run
Short Identifier=Multiple
Geom File=g01
Flow File=f01
Subcritical Flow
K Sum by GR= 0
Std Step Tol= 0.01
Critical Tol= 0.01
Num of Std Step Trials= 20
Max Error Tol= 0.3
Flow Tol Ratio= 0.001
Split Flow NTrial= 30
Split Flow Tol= 0.02
Split Flow Ratio= 0.02
Log Output Level= 0
Friction Slope Method= 1
Unsteady Friction Slope Method= 2
Unsteady Bridges Friction Slope Method= 1
Parabolic Critical Depth
Global Vel Dist=  1 , 1 , 1
Global Log Level= 0
CheckData=True
Encroach Param= -1, 0, 0, 0
BEGIN DESCRIPTION:
Multiple Run
END DESCRIPTION:

--- Alkali Creek Trib 07.f01 (steady flow) ---

Flow Title=Multiple
Number of Profiles=7
Profile Names=10-year,25-year,50-year,1pct_min,100-year,1pct_plu,500-year
River Rch & RM= Alkali Creek Tri,Reach-1,4582
     385     561     714     452     902    1800    1459
River Rch & RM= Alkali Creek Tri,Reach-1,1449
     522     773     994     635    1268    2530    2090
Boundary for River Rch & Prof#=Alkali Creek Tri,Reach-1,1
Up Type=0
Dn Type=3
Dn Slope=0.005
Boundary for River Rch & Prof#=Alkali Creek Tri,Reach-1,2
Up Type=0
Dn Type=3
Dn Slope=0.005
Boundary for River Rch & Prof#=Alkali Creek Tri,Reach-1,3
Up Type=0
Dn Type=3
Dn Slope=0.005
Boundary for River Rch & Prof#=Alkali Creek Tri,Reach-1,4
Up Type=0
Dn Type=3
Dn Slope=0.005
Boundary for River Rch & Prof#=Alkali Creek Tri,Reach-1,5
Up Type=0
Dn Type=3
Dn Slope=0.005
Boundary for River Rch & Prof#=Alkali Creek Tri,Reach-1,6
Up Type=0
Dn Type=3
Dn Slope=0.005
Boundary for River Rch & Prof#=Alkali Creek Tri,Reach-1,7
Up Type=0
Dn Type=3
Dn Slope=0.005

--- Alkali Creek Trib 07.g01 (geometry) ---

Geom Title=Existing Conditions

River Reach=Alkali Creek Tri,Reach-1
Reach XY= 30
      1344205.00      6945888.00      1344251.57      6945939.50
      1344260.22      6946032.55      1344464.70      6946148.77
      1344553.96      6946248.43      1344552.76      6946482.07
      1344455.08      6946653.39      1344505.35      6946767.85
      1344455.38      6947003.28      1344465.42      6947097.81
      1344552.56      6947182.48      1344665.10      6947198.39
      1344731.17      6947315.13      1344814.66      6947348.79
      1344956.47      6947484.47      1345094.56      6947486.63
      1345155.00      6947445.56      1345210.87      6947485.53
      1345346.56      6947491.41      1345445.93      6947581.00
      1345408.16      6947686.35      1345560.61      6947882.41
      1345711.05      6947946.14      1345849.60      6948085.57
      1345852.86      6948182.03      1345749.42      6948382.42
      1345552.25      6948443.42      1345504.49      6948517.76
      1345794.24      6948828.32      1345905.00      6949038.00

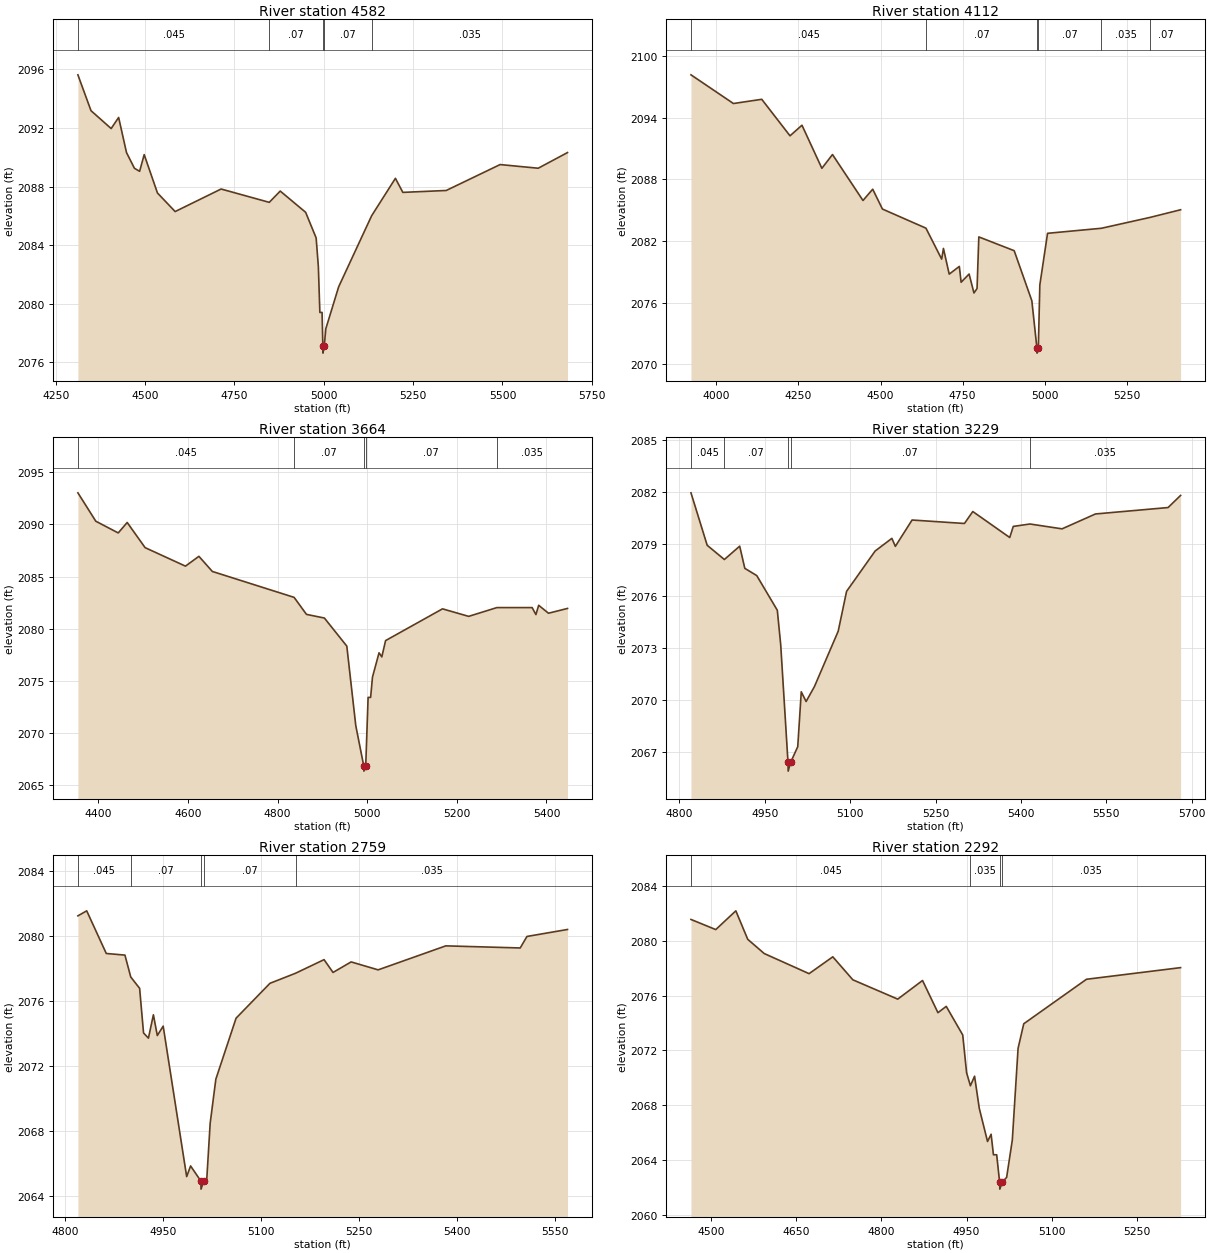
Type RM Length L Ch R = 1,4582,470,470,470
BEGIN DESCRIPTION:
Alkali Creek Trib 07 10.0
END DESCRIPTION:
XS GIS Cut Line= 3
      1343704.98      6946438.01      1344255.00      6946038.00
      1344660.72      6945480.13
#Sta/Elev= 30
  4312.1 2095.63  4348.8 2093.18  4405.2 2091.96  4426.1 2092.72  4448.1 2090.32
  4470.2 2089.25  4484.8 2089.04  4497.6 2090.18  4534.7 2087.56  4584.2 2086.29
  4712.8 2087.83  4847.5 2086.92  4878.2 2087.69  4949.3 2086.24  4978.7 2084.49
  4984.9 2082.53  4989.1 2079.40  4995.3 2079.40  4997.5 2077.12  4997.8 2076.62
  5001.5 2077.12  5005.7 2078.28  5041.7 2081.15  5133.9 2086.00  5200.5 2088.56
  5221.3 2087.60  5342.7 2087.73  5493.4 2089.50  5600.0 2089.25  5682.0 2090.32
#Mann=5,-1,0
  4312.1   0.045       0  4847.5    0.07       0  4997.5    0.07       0
  5001.5    0.07       0  5133.9   0.035       0
Bank Sta=4997.5,5001.5
Exp/Cntr=0.3,0.1

Type RM Length L Ch R = 1,4112,448,448,448
BEGIN DESCRIPTION:
Alkali Creek Trib 07 9.0
END DESCRIPTION:
XS GIS Cut Line= 3
      1343554.96      6946738.02      1344555.00      6946338.00
      1344930.00      6946163.00
#Sta/Elev= 30
  3922.8 2098.16  4052.1 2095.37  4138.3 2095.78  4224.4 2092.23  4260.8 2093.26
  4321.4 2089.07  4353.7 2090.41  4446.6 2085.94  4476.2 2087.04  4505.8 2085.11
  4638.3 2083.25  4686.2 2080.24  4691.6 2081.28  4709.1 2078.78  4740.0 2079.53
  4745.4 2077.99  4769.7 2078.79  4784.5 2076.95  4793.9 2077.38  4799.3 2082.40
  4907.0 2081.06  4960.8 2076.19  4976.2 2071.60  4976.5 2071.10  4980.5 2071.60
  4985.1 2077.73  5008.6 2082.75  5172.6 2083.24  5321.1 2084.30  5413.7 2085.04
#Mann=6,-1,0
  3922.8   0.045       0  4638.3    0.07       0  4976.2    0.07       0
  4980.5    0.07       0  5172.6   0.035       0  5321.1    0.07       0
Bank Sta=4976.2,4980.5
Exp/Cntr=0.3,0.1

Type RM Length L Ch R = 1,3664,435,435,435
BEGIN DESCRIPTION:
Alkali Creek Trib 07 8.0
END DESCRIPTION:
XS GIS Cut Line= 3
      1343855.00      6946738.00      1344505.00      6946738.00
      1344858.92      6946472.56
#Sta/Elev= 30
  4354.6 2093.02  4394.6 2090.30  4444.6 2089.18  4464.6 2090.18  4504.6 2087.77
  4594.6 2086.00  4624.6 2086.94  4654.6 2085.49  4837.0 2083.01  4864.6 2081.38
  4904.6 2081.03  4954.6 2078.34  4974.6 2070.73  4992.4 2066.87  4992.7 2066.37
  4996.8 2066.87  5002.1 2073.43  5007.7 2073.43  5011.9 2075.38  5026.5 2077.70
  5032.7 2077.31  5041.1 2078.87  5168.1 2081.91  5226.5 2081.19  5289.4 2082.03
  5368.1 2082.03  5376.5 2081.36  5382.7 2082.25  5404.6 2081.49  5447.0 2081.95
#Mann=5,-1,0
  4354.6   0.045       0  4837.0    0.07       0  4992.4    0.07       0
  4996.8    0.07       0  5289.4   0.035       0
Bank Sta=4992.4,4996.8
Exp/Cntr=0.3,0.1

Type RM Length L Ch R = 1,3229,470,470,470
BEGIN DESCRIPTION:
Alkali Creek Trib 07 7.0
END DESCRIPTION:
XS GIS Cut Line= 3
      1344355.04      6947237.98      1344505.00      6947138.00
      1344905.00      6946588.01
#Sta/Elev= 30
  4820.3 2081.94  4848.8 2078.91  4879.0 2078.09  4905.9 2078.86  4914.9 2077.58
  4935.9 2077.16  4972.0 2075.16  4978.0 2073.16  4990.8 2066.37  4991.1 2065.87
  4995.3 2066.37  5007.9 2067.28  5014.1 2070.45  5022.6 2069.89  5037.2 2070.75
  5079.0 2073.95  5093.7 2076.25  5143.9 2078.58  5173.3 2079.31  5179.4 2078.85
  5208.8 2080.37  5300.8 2080.17  5315.5 2080.86  5380.4 2079.36  5386.6 2080.00
  5416.0 2080.14  5472.3 2079.86  5531.1 2080.72  5658.6 2081.09  5680.6 2081.79
#Mann=5,-1,0
  4820.3   0.045       0  4879.0    0.07       0  4990.8    0.07       0
  4995.3    0.07       0  5416.0   0.035       0
Bank Sta=4990.8,4995.3
Exp/Cntr=0.3,0.1

Type RM Length L Ch R = 1,2759,467,467,467
BEGIN DESCRIPTION:
Alkali Creek Trib 07 6.0
END DESCRIPTION:
XS GIS Cut Line= 3
      1344755.01      6947537.98      1344855.00      6947388.00
      1345004.99      6946838.04
#Sta/Elev= 30
  4819.5 2081.25  4833.0 2081.56  4863.0 2078.93  4891.6 2078.83  4900.5 2077.48
  4914.1 2076.78  4920.1 2074.03  4927.6 2073.71  4935.2 2075.15  4941.2 2073.87
  4950.2 2074.45  4986.2 2065.17  4992.2 2065.83  5007.9 2064.90  5008.2 2064.40
  5012.4 2064.90  5017.0 2065.02  5022.2 2068.46  5030.9 2071.18  5061.9 2074.94
  5113.8 2077.09  5153.0 2077.71  5196.7 2078.55  5210.5 2077.76  5238.2 2078.41
  5279.6 2077.92  5383.3 2079.40  5497.3 2079.27  5507.7 2079.98  5569.8 2080.41
#Mann=5,-1,0
  4819.5   0.045       0  4900.5    0.07       0  5007.9    0.07       0
  5012.4    0.07       0  5153.0   0.035       0
Bank Sta=5007.9,5012.4
Exp/Cntr=0.3,0.1

Type RM Length L Ch R = 1,2292,430,430,430
BEGIN DESCRIPTION:
Alkali Creek Trib 07 5.0
END DESCRIPTION:
XS GIS Cut Line= 3
      1344929.98      6947913.02      1345255.00      6947488.00
      1345230.00      6947163.01
#Sta/Elev= 30
  4465.3 2081.56  4508.9 2080.82  4544.2 2082.19  4565.1 2080.11  4594.1 2079.07
  4673.0 2077.60  4714.7 2078.83  4750.0 2077.15  4828.9 2075.74  4872.5 2077.10
  4899.6 2074.75  4914.2 2075.21  4943.2 2073.12  4950.0 2070.36  4956.7 2069.41
  4964.0 2070.11  4972.3 2067.76  4986.8 2065.34  4993.1 2065.87  4997.2 2064.37
  5002.9 2064.37  5008.1 2062.36  5008.4 2061.86  5012.6 2062.36  5020.4 2062.72
  5030.4 2065.45  5040.5 2072.14  5050.5 2073.94  5160.8 2077.19  5326.3 2078.04
#Mann=4,-1,0
  4465.3   0.045       0  4956.7   0.035       0  5008.1   0.035       0
  5012.6   0.035       0
Bank Sta=5008.1,5012.6
Exp/Cntr=0.3,0.1

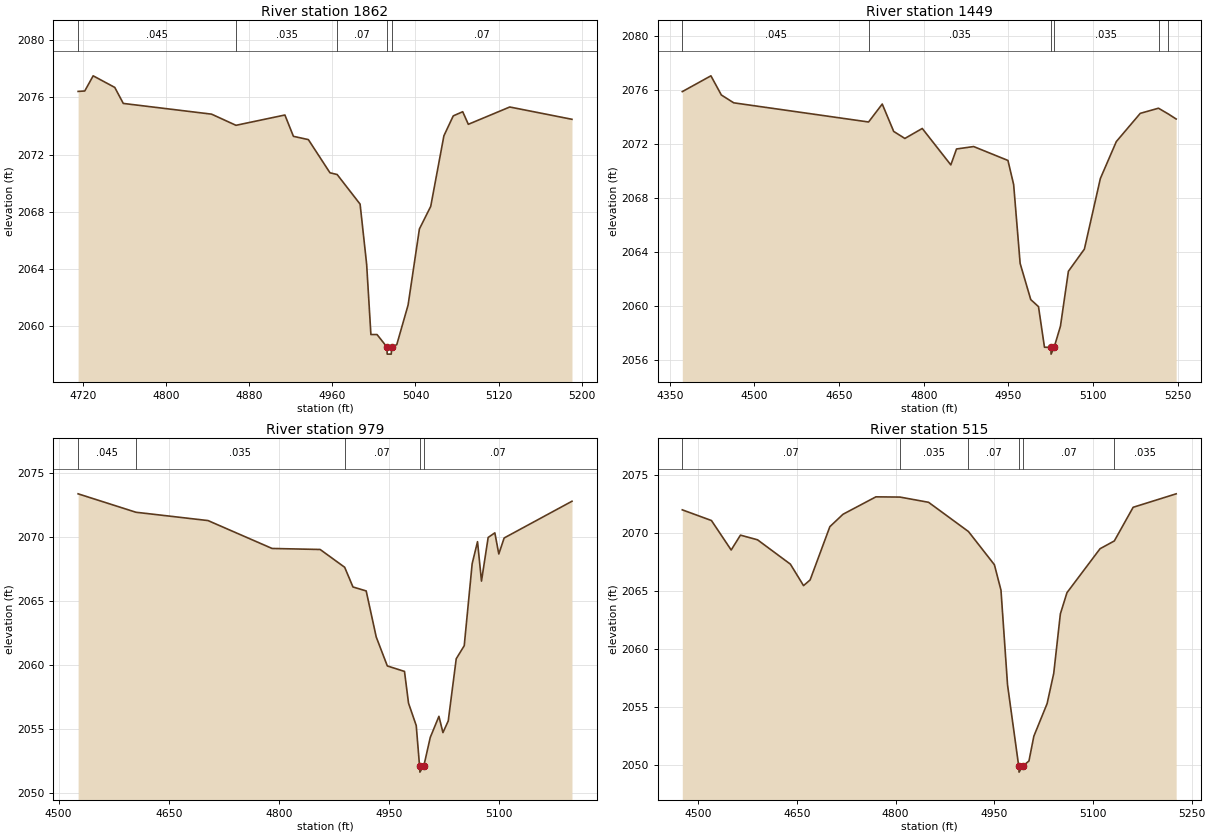
Type RM Length L Ch R = 1,1862,413,413,413
BEGIN DESCRIPTION:
Alkali Creek Trib 07 4.0
END DESCRIPTION:
XS GIS Cut Line= 3
      1345229.98      6947913.02      1345455.00      6947738.00
      1345530.01      6947562.97
#Sta/Elev= 30
  4715.2 2076.42  4721.6 2076.45  4729.7 2077.51  4750.5 2076.70  4758.7 2075.58
  4843.7 2074.83  4867.2 2074.05  4914.3 2074.77  4922.5 2073.28  4936.9 2073.05
  4957.7 2070.73  4964.6 2070.61  4986.7 2068.54  4993.0 2064.34  4997.1 2059.42
  5003.0 2059.42  5012.5 2058.55  5012.8 2058.05  5016.7 2058.05  5017.1 2058.55
  5022.0 2058.71  5032.9 2061.48  5043.8 2066.80  5054.7 2068.38  5067.4 2073.32
  5076.4 2074.71  5085.5 2075.00  5090.9 2074.12  5130.8 2075.33  5190.7 2074.47
#Mann=5,-1,0
  4715.2   0.045       0  4867.2   0.035       0  4964.6    0.07       0
  5012.5    0.07       0  5017.1    0.07       0
Bank Sta=5012.5,5017.1
Exp/Cntr=0.3,0.1

Type RM Length L Ch R = 1,1449,470,470,470
BEGIN DESCRIPTION:
Alkali Creek Trib 07 3.0
END DESCRIPTION:
XS GIS Cut Line= 3
      1345134.94      6948084.10      1345755.00      6947988.00
      1345929.97      6947813.03
#Sta/Elev= 30
  4372.3 2075.91  4423.0 2077.08  4441.5 2075.66  4463.4 2075.08  4702.3 2073.66
  4726.5 2074.99  4746.8 2072.96  4766.6 2072.44  4797.4 2073.18  4848.0 2070.48
  4858.1 2071.66  4888.4 2071.84  4949.2 2070.81  4959.3 2069.02  4970.8 2063.18
  4989.6 2060.50  5003.3 2059.98  5013.9 2056.97  5025.1 2056.96  5025.6 2056.46
  5031.0 2056.96  5042.2 2058.53  5056.3 2062.60  5084.6 2064.24  5112.9 2069.47
  5141.2 2072.21  5183.6 2074.30  5215.9 2074.68  5233.4 2074.25  5247.2 2073.88
#Mann=6,-1,0
  4372.3   0.045       0  4702.3   0.035       0  5025.1   0.035       0
  5031.0   0.035       0  5215.9    0.07       0  5233.4   0.035       0
Bank Sta=5025.1,5031
Exp/Cntr=0.3,0.1

Type RM Length L Ch R = 1,979,464,464,464
BEGIN DESCRIPTION:
Alkali Creek Trib 07 2.0
END DESCRIPTION:
XS GIS Cut Line= 3
      1345312.83      6948194.77      1345755.00      6948388.00
      1345929.96      6948313.02
#Sta/Elev= 30
  4526.5 2073.39  4605.3 2071.95  4703.5 2071.30  4790.8 2069.12  4856.3 2069.04
  4889.7 2067.65  4901.0 2066.11  4919.0 2065.80  4932.7 2062.20  4947.8 2059.94
  4971.2 2059.51  4976.7 2057.03  4987.2 2055.28  4991.7 2052.14  4992.2 2051.64
  4997.6 2052.14  5006.3 2054.35  5018.1 2056.00  5023.6 2054.73  5030.8 2055.64
  5041.7 2060.50  5052.6 2061.52  5063.4 2067.93  5070.7 2069.65  5076.1 2066.57
  5085.2 2069.98  5094.3 2070.34  5099.7 2068.69  5107.0 2069.94  5199.4 2072.81
#Mann=5,-1,0
  4526.5   0.045       0  4605.3   0.035       0  4889.7    0.07       0
  4991.7    0.07       0  4997.6    0.07       0
Bank Sta=4991.7,4997.6
Exp/Cntr=0.3,0.1

Type RM Length L Ch R = 1,515,0,0,0
BEGIN DESCRIPTION:
Alkali Creek Trib 07 1.0
END DESCRIPTION:
XS GIS Cut Line= 3
      1345080.68      6948644.00      1345605.00      6948638.00
      1345829.96      6948613.00
#Sta/Elev= 30
  4475.7 2071.97  4520.0 2071.05  4550.0 2068.51  4564.1 2069.79  4590.0 2069.39
  4640.0 2067.29  4660.0 2065.44  4670.0 2065.93  4700.0 2070.52  4720.0 2071.59
  4770.0 2073.09  4806.6 2073.07  4850.0 2072.62  4910.7 2070.10  4950.1 2067.24
  4960.1 2065.05  4970.1 2056.88  4987.1 2049.87  4987.6 2049.37  4993.0 2049.87
  5002.6 2050.33  5010.1 2052.47  5030.2 2055.27  5040.3 2057.88  5050.4 2063.01
  5060.4 2064.83  5110.7 2068.62  5132.4 2069.29  5161.0 2072.19  5226.4 2073.35
#Mann=6,-1,0
  4475.7    0.07       0  4806.6   0.035       0  4910.7    0.07       0
  4987.1    0.07       0  4993.0    0.07       0  5132.4   0.035       0
Bank Sta=4987.1,4993
Exp/Cntr=0.3,0.1

Chan Stop Cuts=-1