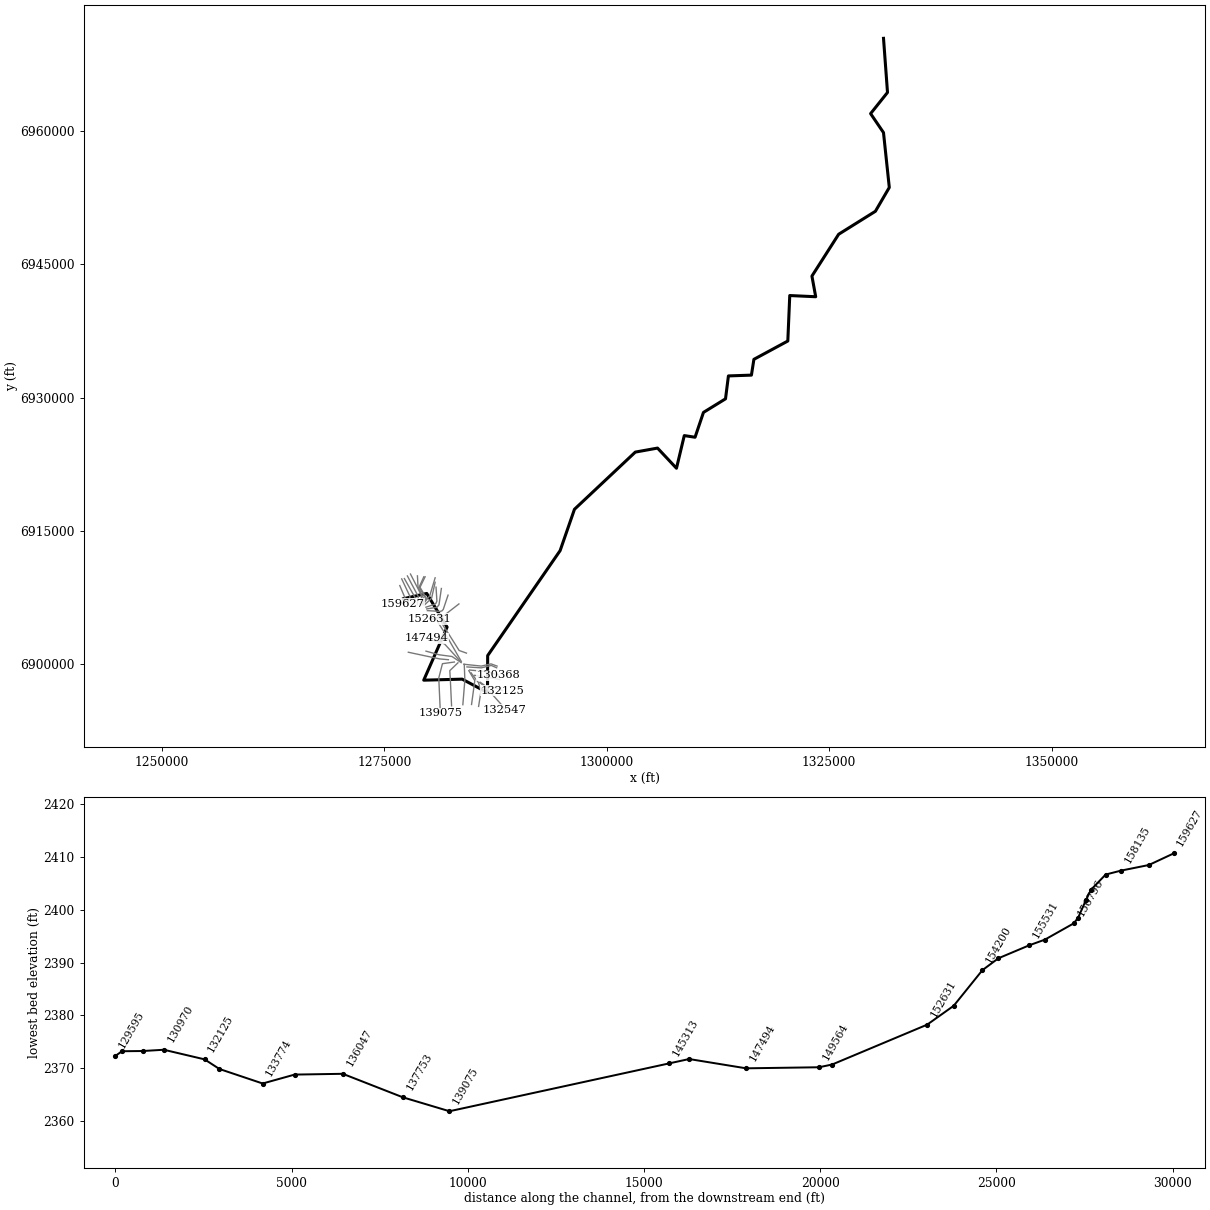
--- Buffalo Creek.prj (project) ---

Proj Title=Buffalo Creek Base Level Engineering
Current Plan=p01
Default Exp/Contr=0.3,0.1
English Units
Geom File=g01
Flow File=f01
Plan File=p01
BEGIN DESCRIPTION:
Buffalo Creek
END DESCRIPTION:

--- Buffalo Creek.p01 (plan) ---

Plan Title=Multiple Run
Short Identifier=Multiple
Geom File=g01
Flow File=f01
Subcritical Flow
K Sum by GR= 0
Std Step Tol= 0.01
Critical Tol= 0.01
Num of Std Step Trials= 20
Max Error Tol= 0.3
Flow Tol Ratio= 0.001
Split Flow NTrial= 30
Split Flow Tol= 0.02
Split Flow Ratio= 0.02
Log Output Level= 0
Friction Slope Method= 1
Unsteady Friction Slope Method= 2
Unsteady Bridges Friction Slope Method= 1
Parabolic Critical Depth
Global Vel Dist=  1 , 1 , 1
Global Log Level= 0
CheckData=True
Encroach Param= -1, 0, 0, 0
BEGIN DESCRIPTION:
Multiple Run
END DESCRIPTION:

--- Buffalo Creek.f01 (steady flow) ---

Flow Title=Multiple
Number of Profiles=7
Profile Names=10-year,25-year,50-year,1pct_min,100-year,1pct_plu,500-year
River Rch & RM= Buffalo Creek,Reach-1,159627
     162     216     257     152     303     605     428
River Rch & RM= Buffalo Creek,Reach-1,155970
     230     312     376     226     450     898     653
River Rch & RM= Buffalo Creek,Reach-1,154653
     320     444     544     331     660    1316     984
River Rch & RM= Buffalo Creek,Reach-1,149934
     386     540     666     407     812    1621    1225
River Rch & RM= Buffalo Creek,Reach-1,147494
     443     622     771     472     943    1881    1430
River Rch & RM= Buffalo Creek,Reach-1,139075
     798    1143    1434     889    1773    3538    2750
River Rch & RM= Buffalo Creek,Reach-1,132547
     895    1283    1611     998    1992    3974    3089
River Rch & RM= Buffalo Creek,Reach-1,126446
     940    1352    1699    1055    2104    4198    3273
River Rch & RM= Buffalo Creek,Reach-1,123120
     943    1354    1702    1056    2107    4204    3276
River Rch & RM= Buffalo Creek,Reach-1,122185
    1035    1493    1882    1171    2336    4662    3651
River Rch & RM= Buffalo Creek,Reach-1,120889
    1074    1551    1957    1219    2432    4852    3807
River Rch & RM= Buffalo Creek,Reach-1,120244
    1186    1727    2191    1373    2739    5464    4337
River Rch & RM= Buffalo Creek,Reach-1,116553
    1268    1856    2362    1484    2962    5910    4722
River Rch & RM= Buffalo Creek,Reach-1,113248
    1334    1960    2502    1577    3146    6276    5042
River Rch & RM= Buffalo Creek,Reach-1,108849
    1464    2159    2762    1745    3481    6946    5605
River Rch & RM= Buffalo Creek,Reach-1,108428
    1512    2233    2860    1808    3607    7198    5820
River Rch & RM= Buffalo Creek,Reach-1,105136
    1605    2381    3059    1940    3871    7724    6286
River Rch & RM= Buffalo Creek,Reach-1,98472
    1662    2472    3182    2022    4034    8049    6574
River Rch & RM= Buffalo Creek,Reach-1,95787
    2321    3492    4532    2902    5790   11552    9579
River Rch & RM= Buffalo Creek,Reach-1,90892
    2321    3492    4530    2900    5787   11546    9569
River Rch & RM= Buffalo Creek,Reach-1,86537
    2559    3862    5021    3222    6428   12826   10674
River Rch & RM= Buffalo Creek,Reach-1,80183
    2594    3917    5095    3270    6525   13019   10843
River Rch & RM= Buffalo Creek,Reach-1,73205
    2760    4174    5435    3492    6968   13902   11603
River Rch & RM= Buffalo Creek,Reach-1,66437
    2879    4360    5682    3654    7290   14545   12158
River Rch & RM= Buffalo Creek,Reach-1,65019
    2958    4483    5845    3760    7503   14970   12524
River Rch & RM= Buffalo Creek,Reach-1,63102
    2997    4540    5918    3806    7594   15152   12668
River Rch & RM= Buffalo Creek,Reach-1,55756
    3026    4585    5978    3845    7672   15307   12801
River Rch & RM= Buffalo Creek,Reach-1,52513
    3076    4667    6092    3922    7826   15614   13085
River Rch & RM= Buffalo Creek,Reach-1,50935
    3137    4761    6215    4002    7984   15931   13352
River Rch & RM= Buffalo Creek,Reach-1,41797
    3150    4777    6234    4013    8006   15975   13379
River Rch & RM= Buffalo Creek,Reach-1,36205
    3145    4767    6218    4001    7983   15928   13329
River Rch & RM= Buffalo Creek,Reach-1,32754
    3609    5488    7174    4625    9229   18414   15469
River Rch & RM= Buffalo Creek,Reach-1,21026
    3644    5541    7245    4672    9321   18598   15627
River Rch & RM= Buffalo Creek,Reach-1,20078
    3653    5555    7262    4682    9342   18640   15658
River Rch & RM= Buffalo Creek,Reach-1,14834
    3672    5583    7298    4705    9388   18731   15731
River Rch & RM= Buffalo Creek,Reach-1,11343
    3754    5709    7465    4814    9605   19164   16102
Boundary for River Rch & Prof#=Buffalo Creek,Reach-1,1
Up Type=0
Dn Type=3
Dn Slope=0.003
Boundary for River Rch & Prof#=Buffalo Creek,Reach-1,2
Up Type=0
Dn Type=3
Dn Slope=0.003
Boundary for River Rch & Prof#=Buffalo Creek,Reach-1,3
Up Type=0
Dn Type=3
Dn Slope=0.003
Boundary for River Rch & Prof#=Buffalo Creek,Reach-1,4
Up Type=0
Dn Type=3
Dn Slope=0.003
Boundary for River Rch & Prof#=Buffalo Creek,Reach-1,5
Up Type=0
Dn Type=3
Dn Slope=0.003
Boundary for River Rch & Prof#=Buffalo Creek,Reach-1,6
Up Type=0
Dn Type=3
Dn Slope=0.003
Boundary for River Rch & Prof#=Buffalo Creek,Reach-1,7
Up Type=0
Dn Type=3
Dn Slope=0.003

--- Buffalo Creek.g01 (geometry) ---

Geom Title=Existing Conditions

River Reach=Buffalo Creek,Reach-1
Reach XY= 30
      1277155.00      6907388.00      1279761.16      6907980.23
      1282047.24      6904191.05      1279421.20      6898220.43
      1283744.50      6898336.78      1286591.38      6896824.78
      1286608.75      6900986.45      1294752.02      6912795.60
      1296365.32      6917448.18      1303206.58      6923884.33
      1305703.52      6924334.39      1307831.82      6922064.29
      1308710.34      6925740.74      1309922.23      6925554.23
      1310865.04      6928348.11      1313344.68      6929877.82
      1313671.64      6932454.68      1316257.55      6932543.73
      1316534.95      6934318.81      1320347.53      6936381.93
      1320565.78      6941497.68      1323481.88      6941364.16
      1323058.53      6943686.53      1326062.80      6948394.21
      1330193.92      6950977.95      1331755.47      6953658.16
      1331102.94      6959832.15      1329654.43      6961967.58
      1331554.13      6964348.29      1331105.00      6970438.00

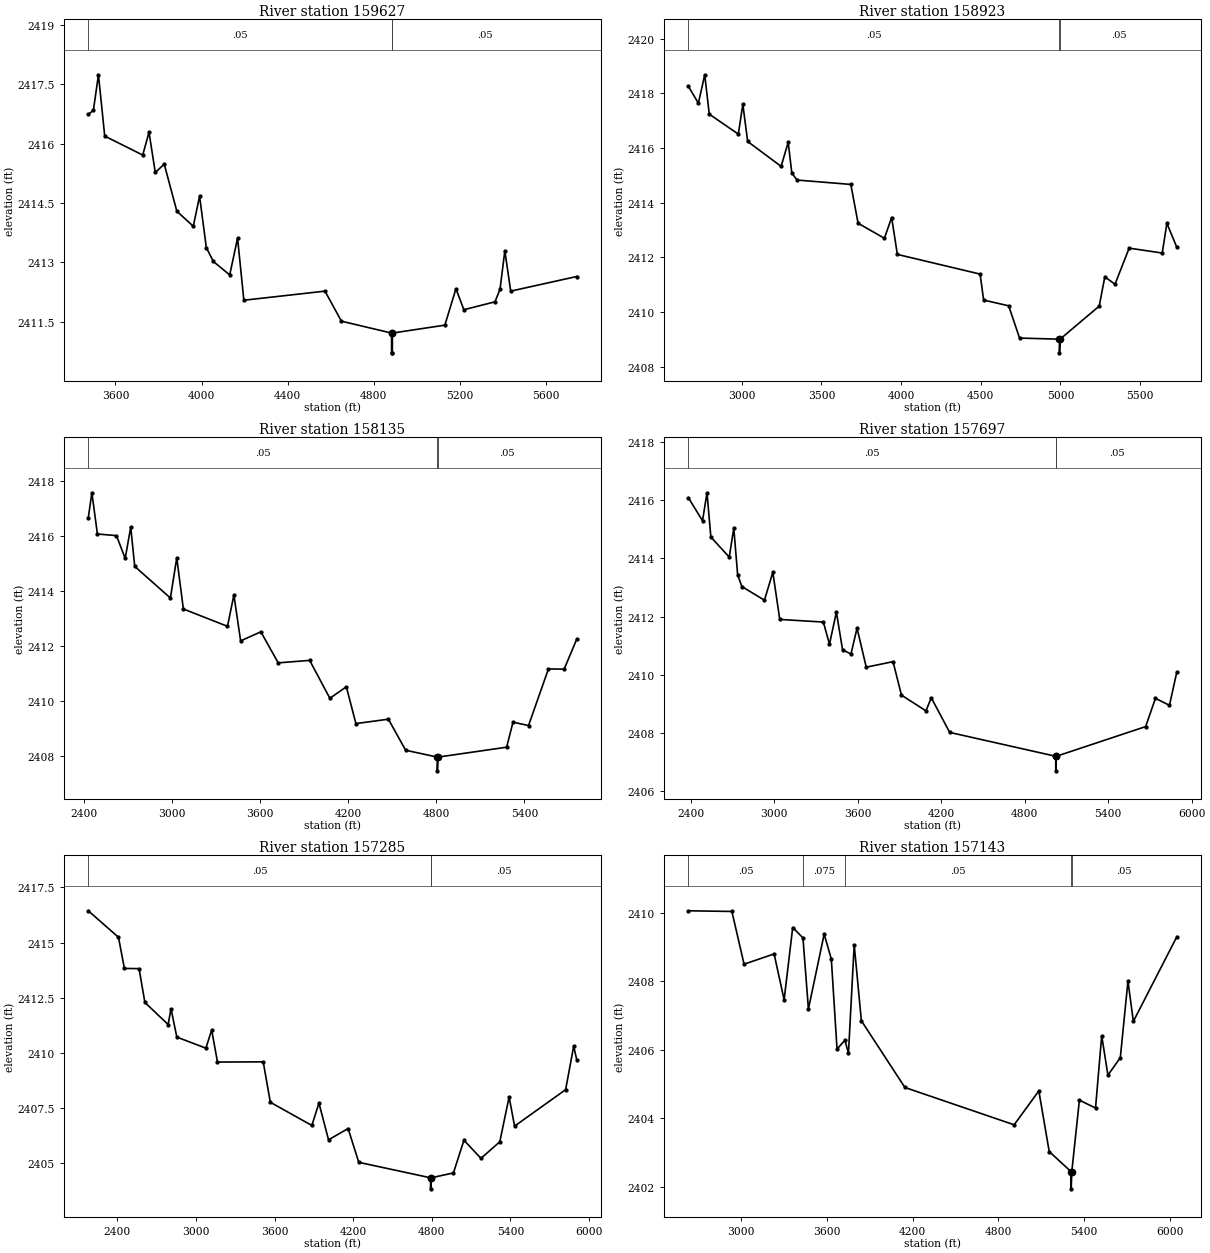
Type RM Length L Ch R = 1,159627,704,704,704
BEGIN DESCRIPTION:
Buffalo Creek 195
END DESCRIPTION:
XS GIS Cut Line= 5
      1276730.01      6908862.98      1277279.53      6907566.07
      1277325.48      6907457.63      1277386.11      6907320.57
      1277080.00      6906813.00
#Sta/Elev= 30
  3473.7 2416.74  3497.4 2416.84  3521.0 2417.74  3550.1 2416.19  3726.7 2415.71
  3755.8 2416.29  3784.9 2415.27  3826.6 2415.48  3885.1 2414.29  3961.5 2413.91
  3990.7 2414.67  4022.1 2413.37  4054.7 2413.02  4130.7 2412.68  4167.2 2413.61
  4196.4 2412.04  4573.2 2412.27  4649.7 2411.51  4882.5 2411.21  4882.7 2410.71
  4886.2 2410.71  4886.5 2411.21  5130.1 2411.41  5181.6 2412.33  5218.4 2411.80
  5363.1 2412.00  5386.4 2412.32  5408.7 2413.29  5435.9 2412.27  5742.6 2412.64
#Mann=3,-1,0
  3473.7    0.05       0  4882.5   0.035       0  4886.5    0.05       0
Bank Sta=4882.5,4886.5
Exp/Cntr=0.3,0.1

Type RM Length L Ch R = 1,158923,788,788,788
BEGIN DESCRIPTION:
Buffalo Creek 194
END DESCRIPTION:
XS GIS Cut Line= 4
      1276945.64      6909614.74      1277858.33      6907674.74
      1277855.89      6907476.19      1277565.84      6906814.18
#Sta/Elev= 30
  2664.8 2418.26  2727.5 2417.64  2767.6 2418.68  2795.9 2417.24  2978.3 2416.51
  3006.6 2417.60  3036.9 2416.24  3246.9 2415.33  3291.2 2416.21  3314.0 2415.09
  3346.4 2414.83  3684.3 2414.67  3729.9 2413.25  3895.0 2412.70  3940.6 2413.46
  3976.3 2412.11  4495.7 2411.39  4517.8 2410.44  4674.9 2410.23  4743.3 2409.05
  4993.5 2409.01  4993.8 2408.51  4997.5 2409.01  5243.2 2410.22  5278.3 2411.29
  5342.2 2411.02  5431.1 2412.34  5638.6 2412.16  5667.9 2413.25  5730.1 2412.37
#Mann=3,-1,0
  2664.8    0.05       0  4993.5   0.035       0  4997.5    0.05       0
Bank Sta=4993.5,4997.5
Exp/Cntr=0.3,0.1

Type RM Length L Ch R = 1,158135,438,438,438
BEGIN DESCRIPTION:
Buffalo Creek 193.0
END DESCRIPTION:
XS GIS Cut Line= 5
      1277247.03      6909652.72      1278417.36      6907570.57
      1278455.00      6907388.00      1278479.86      6907244.18
      1278106.47      6906766.34
#Sta/Elev= 30
  2429.1 2416.66  2453.6 2417.57  2491.3 2416.07  2621.3 2416.01  2680.6 2415.18
  2718.2 2416.32  2745.6 2414.89  2988.5 2413.74  3031.9 2415.20  3076.9 2413.34
  3377.4 2412.71  3421.1 2413.85  3466.9 2412.18  3604.6 2412.51  3723.0 2411.38
  3937.3 2411.47  4074.9 2410.09  4187.1 2410.51  4252.1 2409.17  4473.4 2409.33
  4591.1 2408.20  4806.8 2407.95  4807.2 2407.45  4811.4 2407.95  5279.0 2408.31
  5322.4 2409.22  5428.3 2409.10  5563.9 2411.16  5670.6 2411.15  5756.4 2412.24
#Mann=3,-1,0
  2429.1    0.05       0  4806.8   0.035       0  4811.4    0.05       0
Bank Sta=4806.8,4811.4
Exp/Cntr=0.3,0.1

Type RM Length L Ch R = 1,157697,412,412,412
BEGIN DESCRIPTION:
Buffalo Creek 192.0
END DESCRIPTION:
XS GIS Cut Line= 3
      1277585.58      6909947.84      1278805.00      6907638.00
      1278705.83      6906745.46
#Sta/Elev= 30
  2383.5 2416.08  2485.1 2415.29  2517.4 2416.25  2545.1 2414.73  2677.3 2414.04
  2709.9 2415.04  2737.6 2413.43  2767.8 2413.03  2930.1 2412.56  2990.5 2413.52
  3040.2 2411.90  3353.5 2411.81  3397.5 2411.05  3447.2 2412.15  3491.5 2410.86
  3551.7 2410.71  3595.7 2411.60  3661.8 2410.26  3854.3 2410.45  3914.7 2409.30
  4090.8 2408.76  4129.2 2409.21  4261.3 2408.02  5023.3 2407.20  5023.8 2406.70
  5028.0 2407.20  5669.6 2408.22  5740.0 2409.19  5840.6 2408.95  5893.5 2410.09
#Mann=3,-1,0
  2383.5    0.05       0  5023.3   0.035       0  5028.0    0.05       0
Bank Sta=5023.3,5028
Exp/Cntr=0.3,0.1

Type RM Length L Ch R = 1,157285,142,142,142
BEGIN DESCRIPTION:
Buffalo Creek 191.0
END DESCRIPTION:
XS GIS Cut Line= 5
      1277930.00      6910163.01      1279124.65      6907844.87
      1279155.00      6907638.00      1279167.36      6907452.51
      1279006.68      6906745.49
#Sta/Elev= 30
  2178.1 2416.44  2408.7 2415.24  2453.7 2413.83  2565.8 2413.82  2610.1 2412.29
  2787.5 2411.29  2809.6 2412.00  2854.0 2410.72  3075.6 2410.22  3119.9 2411.04
  3164.3 2409.59  3513.3 2409.60  3567.5 2407.77  3884.4 2406.72  3938.7 2407.73
  4011.8 2406.07  4161.3 2406.58  4242.5 2405.05  4790.6 2404.35  4791.1 2403.85
  4795.3 2404.35  4965.2 2404.57  5045.2 2406.05  5175.4 2405.23  5318.9 2405.98
  5390.1 2408.01  5431.7 2406.69  5821.4 2408.34  5882.9 2410.31  5906.0 2409.70
#Mann=3,-1,0
  2178.1    0.05       0  4790.6   0.035       0  4795.3    0.05       0
Bank Sta=4790.6,4795.3
Exp/Cntr=0.3,0.1

Type RM Length L Ch R = 1,157143,225,225,225
BEGIN DESCRIPTION:
Buffalo Creek 190.7
END DESCRIPTION:
XS GIS Cut Line= 4
      1278713.88      6909957.56      1278781.84      6908675.99
      1279412.90      6907423.57      1279053.73      6906782.88
#Sta/Elev= 30
  2629.2 2410.06  2933.9 2410.04  3019.3 2408.50  3229.6 2408.80  3299.7 2407.46
  3359.8 2409.57  3431.6 2409.27  3469.9 2407.19  3580.1 2409.38  3630.2 2408.65
  3670.2 2406.02  3725.2 2406.28  3750.3 2405.90  3790.4 2409.07  3840.5 2406.85
  4145.5 2404.90  4910.5 2403.81  5083.4 2404.80  5155.9 2403.03  5309.4 2402.44
  5309.9 2401.94  5314.1 2402.44  5367.4 2404.53  5480.3 2404.30  5523.7 2406.41
  5567.1 2405.26  5653.9 2405.77  5707.5 2408.01  5745.1 2406.83  6049.5 2409.30
#Mann=5,-1,0
  2629.2    0.05       0  3431.6   0.075       0  3725.2    0.05       0
  5309.4   0.035       0  5314.1    0.05       0
Bank Sta=5309.4,5314.1
Exp/Cntr=0.3,0.1

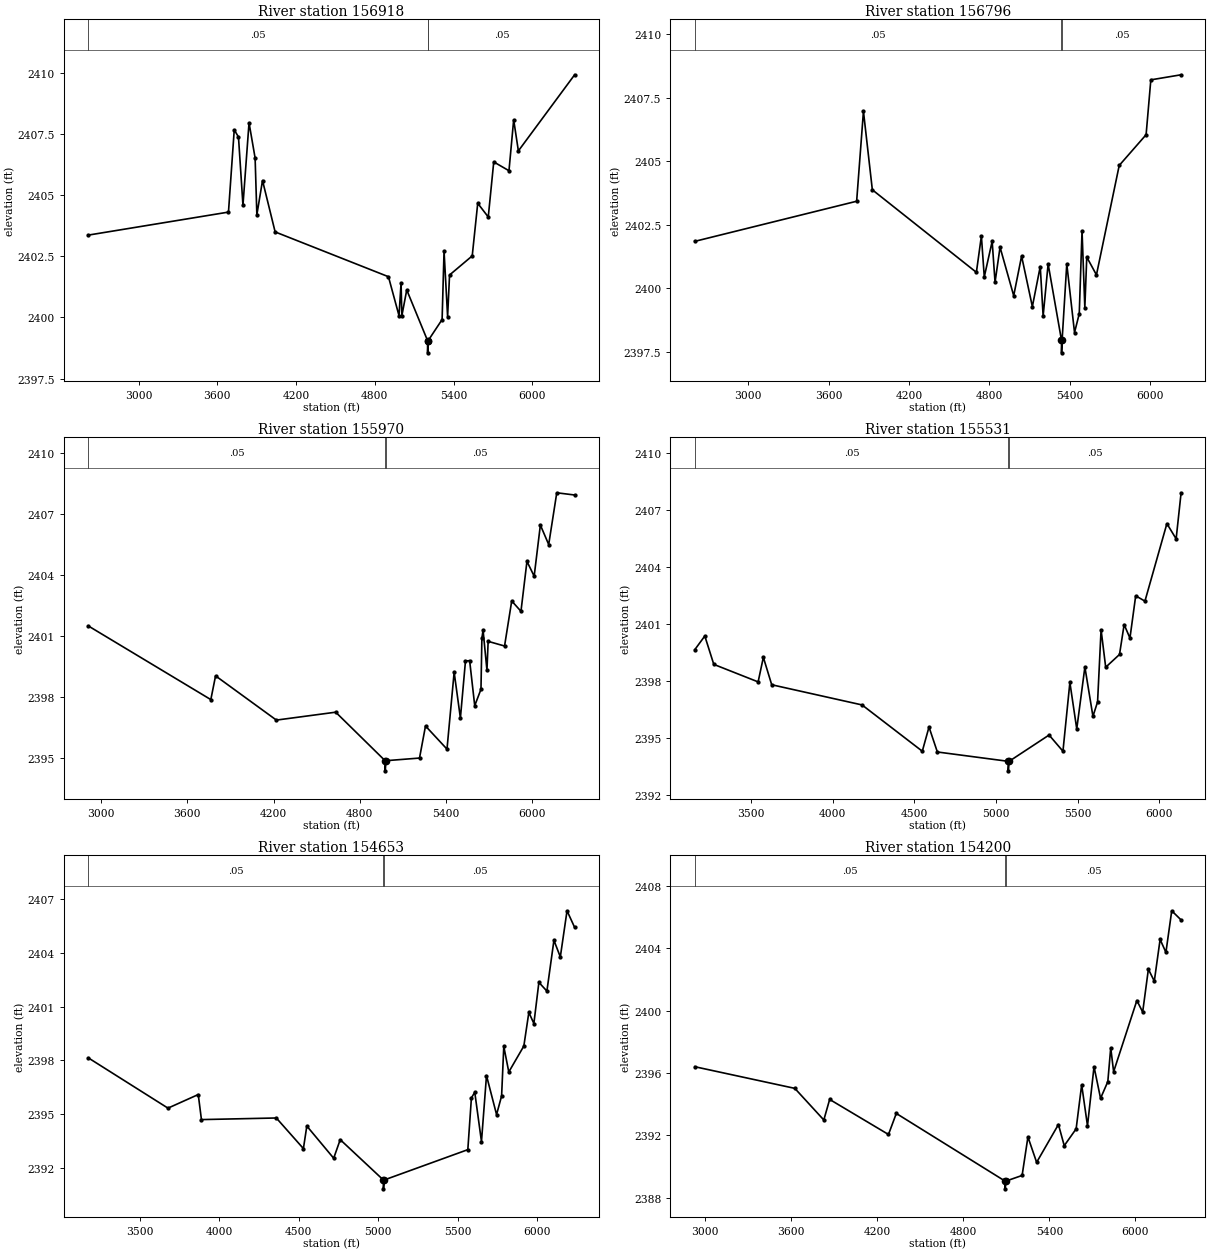
Type RM Length L Ch R = 1,156918,122,122,122
BEGIN DESCRIPTION:
Buffalo Creek 190.6
END DESCRIPTION:
XS GIS Cut Line= 4
      1279431.30      6909851.70      1278906.52      6908685.22
      1279599.15      6907485.22      1279003.63      6906633.01
#Sta/Elev= 30
  2617.6 2403.36  3685.3 2404.30  3729.2 2407.66  3761.5 2407.37  3795.6 2404.58
  3841.9 2407.95  3888.2 2406.51  3901.5 2404.19  3944.6 2405.59  4040.7 2403.49
  4903.8 2401.66  4984.2 2400.07  5000.0 2401.41  5005.8 2400.06  5043.1 2401.12
  5201.6 2399.05  5202.1 2398.55  5206.3 2399.05  5312.5 2399.91  5327.3 2402.71
  5354.4 2400.03  5369.2 2401.73  5541.9 2402.51  5583.8 2404.66  5664.0 2404.10
  5705.8 2406.35  5821.8 2405.99  5857.6 2408.07  5893.4 2406.80  6321.9 2409.91
#Mann=3,-1,0
  2617.6    0.05       0  5201.6   0.033       0  5206.3    0.05       0
Bank Sta=5201.6,5206.3
Exp/Cntr=0.3,0.1

Type RM Length L Ch R = 1,156796,826,826,826
BEGIN DESCRIPTION:
Buffalo Creek 190.5
END DESCRIPTION:
XS GIS Cut Line= 4
      1279577.71      6909856.03      1279005.48      6908674.81
      1279725.87      6907433.72      1279180.34      6906745.44
#Sta/Elev= 30
  2602.9 2401.85  3809.8 2403.43  3860.5 2406.97  3926.8 2403.88  4702.5 2400.63
  4739.8 2402.06  4761.3 2400.45  4820.1 2401.85  4841.6 2400.24  4878.9 2401.62
  4980.7 2399.71  5039.5 2401.27  5119.8 2399.28  5178.6 2400.86  5200.1 2398.91
  5237.4 2400.96  5336.9 2397.96  5337.4 2397.46  5341.6 2397.96  5376.4 2400.96
  5434.2 2398.26  5469.4 2399.00  5490.2 2402.26  5511.0 2399.24  5525.4 2401.23
  5597.6 2400.53  5767.4 2404.84  5967.8 2406.05  6003.0 2408.21  6228.7 2408.41
#Mann=3,-1,0
  2602.9    0.05       0  5336.9    0.05       0  5341.6    0.05       0
Bank Sta=5336.9,5341.6
Exp/Cntr=0.3,0.1

Type RM Length L Ch R = 1,155970,439,439,439
BEGIN DESCRIPTION:
Buffalo Creek 190.0
END DESCRIPTION:
XS GIS Cut Line= 3
      1280705.00      6909738.00      1280105.00      6907738.00
      1279313.42      6906715.57
#Sta/Elev= 30
  2912.2 2401.49  3764.0 2397.86  3797.0 2399.03  4219.8 2396.85  4632.2 2397.24
  4975.6 2394.85  4976.5 2394.35  4981.5 2394.85  5214.9 2394.98  5256.5 2396.56
  5405.9 2395.42  5455.7 2399.21  5499.1 2396.95  5534.4 2399.76  5563.4 2399.78
  5598.7 2397.56  5642.2 2398.37  5648.5 2400.88  5656.7 2401.28  5683.8 2399.30
  5692.0 2400.73  5806.1 2400.50  5855.9 2402.72  5920.2 2402.21  5961.8 2404.67
  6012.0 2403.94  6055.1 2406.46  6113.0 2405.50  6169.1 2408.05  6293.3 2407.94
#Mann=3,-1,0
  2912.2    0.05       0  4975.6   0.035       0  4981.5    0.05       0
Bank Sta=4975.6,4981.5
Exp/Cntr=0.3,0.1

Type RM Length L Ch R = 1,155531,878,878,878
BEGIN DESCRIPTION:
Buffalo Creek 189.0
END DESCRIPTION:
XS GIS Cut Line= 3
      1280705.00      6909238.01      1280305.00      6907438.00
      1279479.92      6906660.22
#Sta/Elev= 30
  3156.1 2399.65  3217.6 2400.37  3272.6 2398.88  3544.1 2397.96  3576.1 2399.25
  3627.3 2397.81  4180.5 2396.75  4549.3 2394.32  4590.3 2395.59  4641.5 2394.28
  5074.9 2393.79  5075.9 2393.29  5080.8 2393.79  5325.5 2395.17  5410.5 2394.32
  5452.9 2397.93  5495.0 2395.49  5544.8 2398.74  5594.1 2396.15  5622.5 2396.91
  5643.9 2400.70  5672.2 2398.73  5756.8 2399.40  5785.1 2400.97  5820.7 2400.26
  5855.9 2402.48  5912.5 2402.20  6046.9 2406.27  6103.5 2405.47  6133.9 2407.89
#Mann=3,-1,0
  3156.1    0.05       0  5074.9   0.035       0  5080.8    0.05       0
Bank Sta=5074.9,5080.8
Exp/Cntr=0.3,0.1

Type RM Length L Ch R = 1,154653,453,453,453
BEGIN DESCRIPTION:
Buffalo Creek 188.0
END DESCRIPTION:
XS GIS Cut Line= 5
      1280805.00      6908688.02      1280902.43      6907120.05
      1280805.00      6906888.00      1280650.69      6906759.81
      1279669.65      6906430.56
#Sta/Elev= 30
  3177.7 2398.14  3678.7 2395.33  3869.1 2396.09  3889.1 2394.69  4360.0 2394.78
  4530.3 2393.07  4551.8 2394.33  4720.7 2392.53  4761.8 2393.57  5032.5 2391.32
  5033.6 2390.82  5039.8 2391.32  5564.2 2393.01  5586.7 2395.90  5607.8 2396.22
  5650.0 2393.46  5681.6 2397.15  5744.9 2394.97  5776.6 2396.01  5790.3 2398.78
  5821.8 2397.35  5916.4 2398.80  5947.9 2400.68  5979.5 2400.06  6011.0 2402.36
  6061.4 2401.87  6105.6 2404.71  6145.8 2403.78  6188.0 2406.36  6235.8 2405.43
#Mann=3,-1,0
  3177.7    0.05       0  5032.5   0.035       0  5039.8    0.05       0
Bank Sta=5032.5,5039.8
Exp/Cntr=0.3,0.1

Type RM Length L Ch R = 1,154200,815,815,815
BEGIN DESCRIPTION:
Buffalo Creek 187.0
END DESCRIPTION:
XS GIS Cut Line= 5
      1281405.01      6908538.04      1281136.80      6906699.04
      1281005.00      6906538.00      1280906.77      6906421.26
      1279750.52      6906237.98
#Sta/Elev= 30
  2928.4 2396.41  3625.7 2395.02  3827.9 2392.99  3868.6 2394.31  4278.6 2392.06
  4333.1 2393.41  5090.7 2389.07  5091.9 2388.57  5098.1 2389.07  5210.1 2389.43
  5250.6 2391.90  5311.3 2390.27  5463.2 2392.70  5503.7 2391.34  5586.6 2392.42
  5625.2 2395.25  5665.7 2392.62  5711.3 2396.41  5756.8 2394.38  5807.4 2395.45
  5827.7 2397.62  5847.9 2396.09  6009.9 2400.66  6050.4 2399.92  6090.2 2402.67
  6131.4 2401.90  6171.9 2404.58  6212.4 2403.75  6252.9 2406.42  6318.2 2405.83
#Mann=3,-1,0
  2928.4    0.05       0  5090.7   0.035       0  5098.1    0.05       0
Bank Sta=5090.7,5098.1
Exp/Cntr=0.3,0.1

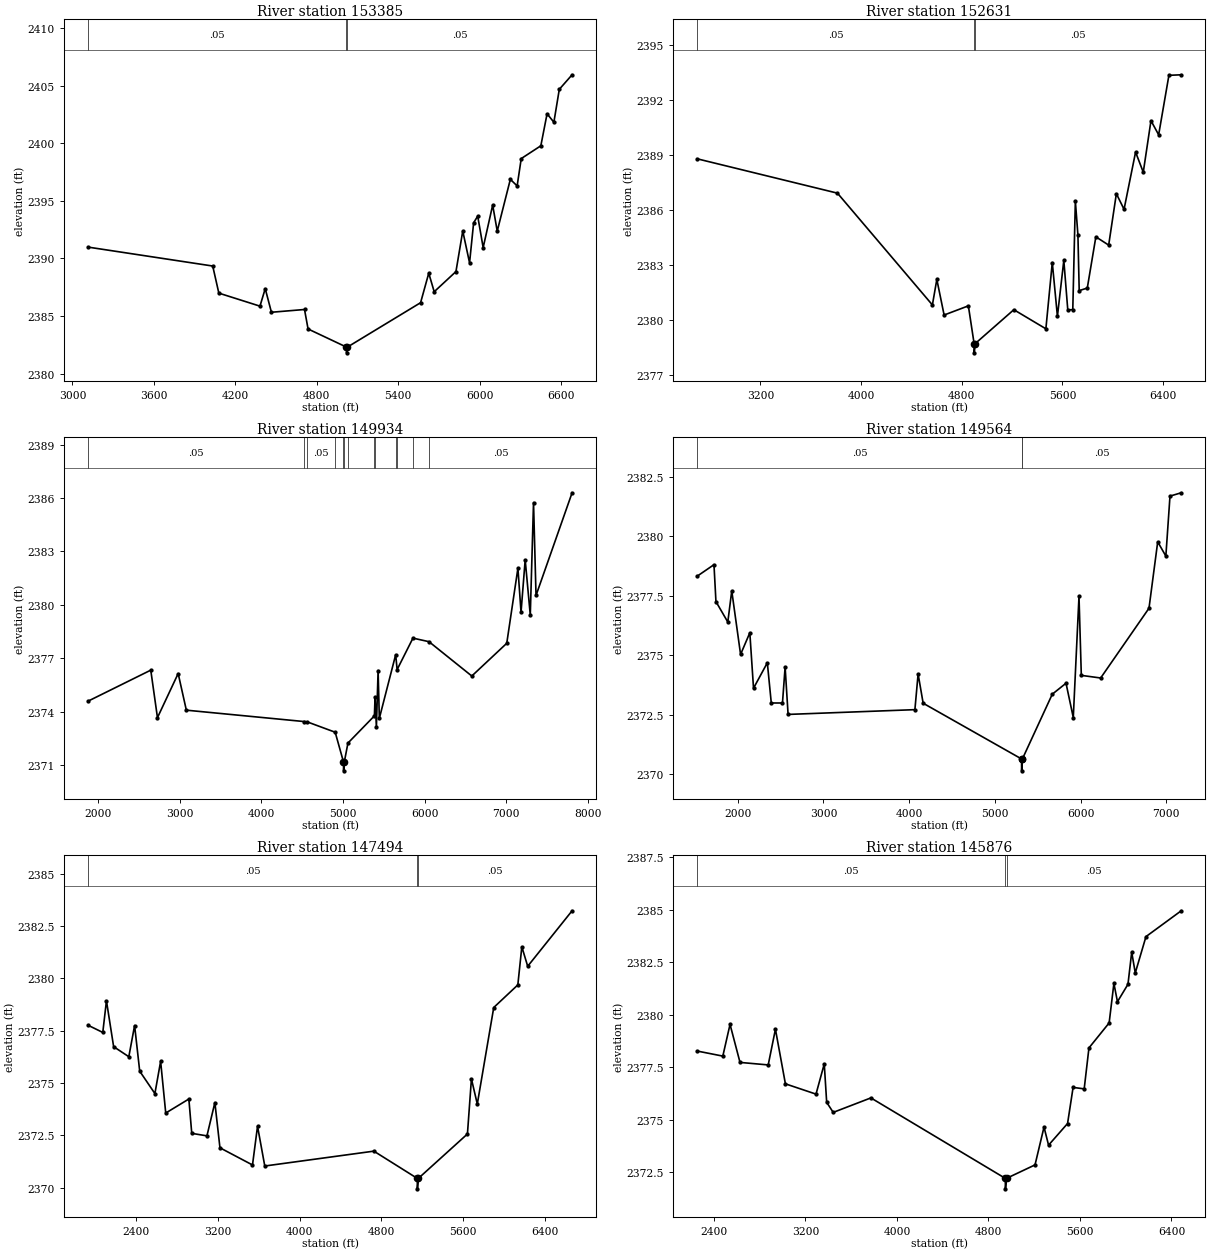
Type RM Length L Ch R = 1,153385,754,754,754
BEGIN DESCRIPTION:
Buffalo Creek 186.0
END DESCRIPTION:
XS GIS Cut Line= 5
      1282155.01      6907788.04      1281618.57      6906186.89
      1281488.37      6906030.64      1281284.37      6905956.85
      1279831.03      6906047.37
#Sta/Elev= 30
  3115.8 2390.98  4033.4 2389.34  4078.4 2386.99  4381.4 2385.86  4420.2 2387.38
  4465.8 2385.33  4709.6 2385.57  4735.8 2383.88  5018.3 2382.31  5019.5 2381.81
  5025.7 2382.31  5564.8 2386.16  5624.9 2388.72  5665.0 2387.11  5825.3 2388.86
  5875.4 2392.38  5925.5 2389.62  5955.5 2393.09  5985.6 2393.67  6025.7 2390.94
  6095.8 2394.63  6129.4 2392.37  6226.0 2396.86  6276.1 2396.29  6306.2 2398.66
  6450.6 2399.77  6496.6 2402.55  6546.7 2401.81  6586.7 2404.67  6680.9 2405.93
#Mann=3,-1,0
  3115.8    0.05       0  5018.3   0.035       0  5025.7    0.05       0
Bank Sta=5018.3,5025.7
Exp/Cntr=0.3,0.1

Type RM Length L Ch R = 1,152631,2697,2697,2697
BEGIN DESCRIPTION:
Buffalo Creek 185.0
END DESCRIPTION:
XS GIS Cut Line= 3
      1283376.69      6906799.28      1281576.70      6905399.28
      1280038.90      6905099.96
#Sta/Elev= 30
  2697.6 2388.80  3811.8 2386.93  4566.5 2380.84  4601.8 2382.23  4659.7 2380.29
  4852.5 2380.79  4898.2 2378.73  4899.4 2378.23  4906.2 2378.73  5214.0 2380.58
  5468.7 2379.54  5519.6 2383.15  5560.4 2380.22  5611.3 2383.27  5642.9 2380.56
  5682.6 2380.59  5703.0 2386.50  5723.4 2384.65  5733.6 2381.62  5797.9 2381.76
  5866.0 2384.55  5967.9 2384.10  6029.0 2386.90  6090.1 2386.05  6181.8 2389.17
  6242.9 2388.07  6304.1 2390.88  6365.2 2390.11  6446.7 2393.35  6544.6 2393.38
#Mann=3,-1,0
  2697.6    0.05       0  4898.2   0.035       0  4906.2    0.05       0
Bank Sta=4898.2,4906.2
Exp/Cntr=0.3,0.1

Type RM Length L Ch R = 1,149934,370,370,370
BEGIN DESCRIPTION:
Mapping XS 34a78e2c
END DESCRIPTION:
XS GIS Cut Line= 6
      1284224.66      6901266.58      1283402.67      6901559.56
      1282141.28      6903561.51      1281652.78      6904293.95
      1281145.85      6905245.55      1280432.27      6905099.59
#Sta/Elev= 30
  1881.3 2374.59  2647.8 2376.33  2729.7 2373.66  2983.3 2376.14  3083.4 2374.08
  4527.3 2373.44  4564.9 2373.42  4906.1 2372.84  5007.7 2371.17  5009.1 2370.67
  5017.8 2371.17  5062.2 2372.23  5386.2 2373.76  5394.5 2374.83  5410.6 2373.12
  5431.6 2376.31  5446.7 2373.62  5646.9 2377.20  5664.4 2376.36  5858.3 2378.13
  6054.8 2377.93  6579.0 2376.00  7007.0 2377.84  7143.7 2382.06  7181.7 2379.58
  7232.7 2382.53  7295.1 2379.43  7334.8 2385.75  7365.4 2380.53  7807.1 2386.30
#Mann=13,-1,0
  1881.3    0.05       0  4527.3   0.075       0  4564.9    0.05       0
  4906.1   0.075       0  5007.7    0.07       0  5017.8   0.075       0
  5062.2    0.05       0  5386.2   0.075       0  5394.5    0.05       0
  5646.9   0.075       0  5664.4    0.05       0  5858.3   0.075       0
  6054.8    0.05       0
Bank Sta=5007.7,5017.8
Exp/Cntr=0.3,0.1

Type RM Length L Ch R = 1,149564,2070,2070,2070
BEGIN DESCRIPTION:
Mapping XS dfa5fabc
END DESCRIPTION:
XS GIS Cut Line= 3
      1283644.12      6900329.33      1281929.69      6903313.30
      1280736.13      6905168.74
#Sta/Elev= 30
  1527.3 2378.33  1721.9 2378.81  1744.9 2377.26  1883.3 2376.40  1929.4 2377.71
  2032.4 2375.04  2140.3 2375.95  2183.4 2373.62  2344.6 2374.69  2390.7 2373.00
  2521.3 2373.00  2552.2 2374.51  2586.8 2372.52  4066.8 2372.72  4104.2 2374.22
  4163.1 2372.99  5311.2 2370.65  5312.6 2370.15  5321.4 2370.65  5670.2 2373.37
  5830.4 2373.83  5915.2 2372.39  5981.9 2377.48  6009.0 2374.16  6234.7 2374.05
  6798.8 2376.98  6900.5 2379.77  6995.6 2379.17  7043.8 2381.69  7174.9 2381.83
#Mann=3,-1,0
  1527.3    0.05       0  5311.2   0.033       0  5321.4    0.05       0
Bank Sta=5311.2,5321.4
Exp/Cntr=0.3,0.1

Type RM Length L Ch R = 1,147494,1618,1618,1618
BEGIN DESCRIPTION:
Mapping XS 3df1f60b
END DESCRIPTION:
XS GIS Cut Line= 3
      1283503.02      6900383.64      1281756.08      6902304.19
      1279716.17      6902955.23
#Sta/Elev= 30
  1930.5 2377.76  2073.5 2377.42  2109.4 2378.93  2179.7 2376.74  2328.4 2376.26
  2385.0 2377.75  2435.0 2375.57  2583.7 2374.50  2639.8 2376.04  2689.8 2373.57
  2916.2 2374.24  2944.5 2372.60  3093.2 2372.48  3170.9 2374.07  3220.6 2371.91
  3539.2 2371.09  3588.5 2372.94  3659.4 2371.04  4727.3 2371.75  5152.1 2370.45
  5153.6 2369.95  5163.2 2370.45  5643.4 2372.57  5682.5 2375.20  5740.0 2374.00
  5900.9 2378.61  6136.8 2379.69  6175.9 2381.51  6233.4 2380.58  6668.0 2383.23
#Mann=3,-1,0
  1930.5    0.05       0  5152.1    0.05       0  5163.2    0.05       0
Bank Sta=5152.1,5163.2
Exp/Cntr=0.3,0.1

Type RM Length L Ch R = 1,145876,563,563,563
BEGIN DESCRIPTION:
Buffalo Creek 180.9
END DESCRIPTION:
XS GIS Cut Line= 4
      1283632.64      6900197.43      1282597.90      6900884.94
      1281124.08      6901082.40      1279678.21      6901487.68
#Sta/Elev= 30
  2254.6 2378.27  2477.7 2378.03  2540.8 2379.54  2628.0 2377.73  2874.6 2377.61
  2937.7 2379.31  3024.9 2376.71  3292.5 2376.22  3364.6 2377.66  3385.7 2375.83
  3442.8 2375.35  3772.3 2376.04  4947.2 2372.21  4948.7 2371.71  4958.3 2372.21
  5207.3 2372.85  5285.9 2374.65  5325.7 2373.79  5491.8 2374.82  5540.2 2376.54
  5637.2 2376.47  5678.8 2378.42  5855.3 2379.61  5896.9 2381.49  5928.0 2380.62
  6019.9 2381.45  6052.6 2382.98  6083.8 2381.99  6177.3 2383.72  6485.5 2384.95
#Mann=3,-1,0
  2254.6    0.05       0  4947.2   0.033       0  4958.3    0.05       0
Bank Sta=4947.2,4958.3
Exp/Cntr=0.3,0.1

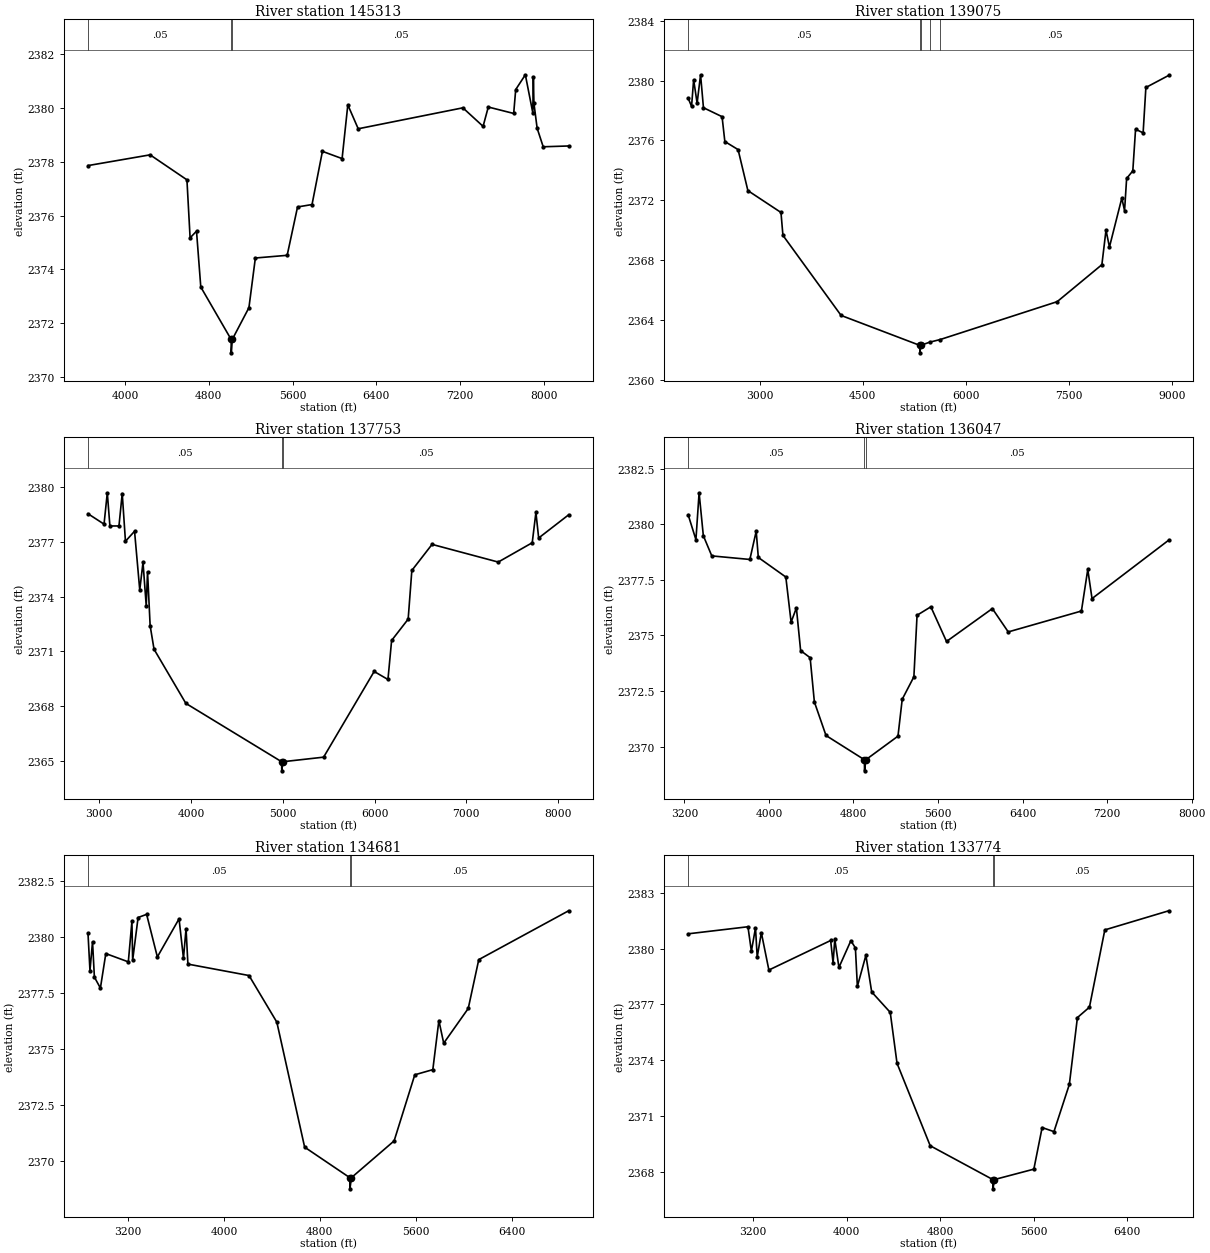
Type RM Length L Ch R = 1,145313,6238,6238,6238
BEGIN DESCRIPTION:
Buffalo Creek 180.8
END DESCRIPTION:
XS GIS Cut Line= 4
      1282195.13      6900523.83      1281230.00      6900613.00
      1280855.00      6900688.00      1277691.32      6901363.24
#Sta/Elev= 30
  3647.9 2377.86  4240.5 2378.26  4592.0 2377.33  4622.2 2375.17  4683.4 2375.42
  4724.2 2373.34  5013.7 2371.39  5015.2 2370.89  5024.8 2371.39  5183.6 2372.57
  5245.0 2374.42  5548.6 2374.52  5647.6 2376.32  5785.9 2376.41  5885.0 2378.39
  6072.8 2378.12  6127.4 2380.12  6226.6 2379.23  7225.4 2380.01  7418.4 2379.32
  7467.9 2380.04  7710.4 2379.80  7729.7 2380.69  7821.7 2381.24  7893.1 2379.82
  7898.2 2381.16  7903.5 2380.18  7934.2 2379.25  7992.1 2378.56  8234.5 2378.59
#Mann=3,-1,0
  3647.9    0.05       0  5013.7   0.035       0  5024.8    0.05       0
Bank Sta=5013.7,5024.8
Exp/Cntr=0.3,0.1

Type RM Length L Ch R = 1,139075,1322,1322,1322
BEGIN DESCRIPTION:
Buffalo Creek 178.5
END DESCRIPTION:
XS GIS Cut Line= 4
      1282864.00      6900263.42      1281525.59      6900075.71
      1281113.11      6898472.24      1281292.79      6894485.16
#Sta/Elev= 30
  1958.6 2378.82  2008.1 2378.28  2038.5 2380.06  2088.9 2378.49  2139.3 2380.39
  2181.2 2378.19  2452.4 2377.59  2492.8 2375.93  2685.6 2375.39  2828.3 2372.65
  3310.1 2371.19  3338.7 2369.66  4185.4 2364.31  5331.2 2362.31  5332.7 2361.81
  5345.2 2362.31  5474.0 2362.52  5629.7 2362.70  7332.4 2365.23  7983.1 2367.70
  8043.1 2370.01  8093.2 2368.88  8273.4 2372.15  8313.4 2371.31  8343.4 2373.46
  8433.5 2373.97  8473.6 2376.75  8583.7 2376.51  8623.7 2379.54  8956.9 2380.35
#Mann=5,-1,0
  1958.6    0.05       0  5331.2   0.035       0  5345.2    0.05       0
  5474.0   0.075       0  5629.7    0.05       0
Bank Sta=5331.2,5345.2
Exp/Cntr=0.3,0.1

Type RM Length L Ch R = 1,137753,1706,1706,1706
BEGIN DESCRIPTION:
Buffalo Creek 177.0
END DESCRIPTION:
XS GIS Cut Line= 4
      1283267.63      6900172.29      1282352.22      6899292.99
      1282405.00      6898438.00      1282551.44      6895332.28
#Sta/Elev= 30
  2878.8 2378.55  3053.4 2377.98  3088.9 2379.70  3117.2 2377.88  3216.0 2377.88
  3251.5 2379.66  3286.7 2377.04  3385.8 2377.59  3442.4 2374.37  3477.9 2375.88
  3513.1 2373.50  3527.3 2375.37  3555.6 2372.41  3598.0 2371.12  3944.6 2368.15
  4987.7 2364.95  4989.2 2364.45  5001.7 2364.95  5445.2 2365.20  5995.8 2369.90
  6146.0 2369.46  6186.0 2371.60  6366.2 2372.77  6406.3 2375.44  6626.5 2376.87
  7347.3 2375.90  7717.7 2376.96  7757.8 2378.62  7787.8 2377.22  8113.9 2378.49
#Mann=3,-1,0
  2878.8    0.05       0  4987.7   0.035       0  5001.7    0.05       0
Bank Sta=4987.7,5001.7
Exp/Cntr=0.3,0.1

Type RM Length L Ch R = 1,136047,1366,1366,1366
BEGIN DESCRIPTION:
Buffalo Creek 175.9
END DESCRIPTION:
XS GIS Cut Line= 3
      1283978.32      6900001.41      1284045.80      6898238.20
      1283818.40      6895464.30
#Sta/Elev= 30
  3235.5 2380.43  3309.0 2379.31  3339.0 2381.42  3379.0 2379.49  3459.1 2378.58
  3819.3 2378.42  3879.4 2379.69  3899.4 2378.51  4159.6 2377.63  4209.6 2375.60
  4259.7 2376.24  4299.7 2374.32  4389.7 2374.00  4429.8 2372.01  4539.9 2370.50
  4903.1 2369.41  4904.6 2368.91  4917.1 2369.41  5220.9 2370.47  5261.1 2372.13
  5371.4 2373.14  5401.5 2375.91  5532.0 2376.29  5680.2 2374.73  6113.9 2376.21
  6264.4 2375.16  6956.7 2376.10  7016.9 2377.97  7057.1 2376.66  7783.2 2379.29
#Mann=3,-1,0
  3235.5    0.05       0  4903.1   0.035       0  4917.1    0.05       0
Bank Sta=4903.1,4917.1
Exp/Cntr=0.3,0.1

Type RM Length L Ch R = 1,134681,907,907,907
BEGIN DESCRIPTION:
Buffalo Creek 175.6
END DESCRIPTION:
XS GIS Cut Line= 3
      1284491.58      6899286.82      1285159.96      6898167.06
      1284797.57      6895485.20
#Sta/Elev= 30
  2865.4 2380.16  2881.7 2378.50  2903.1 2379.79  2918.6 2378.21  2968.8 2377.72
  3014.0 2379.26  3201.8 2378.89  3231.9 2380.70  3237.8 2378.96  3283.3 2380.87
  3354.5 2381.01  3444.1 2379.11  3625.0 2380.81  3662.0 2379.05  3683.4 2380.37
  3699.0 2378.79  4208.9 2378.28  4441.0 2376.20  4673.1 2370.62  5049.5 2369.26
  5051.0 2368.76  5063.5 2369.26  5419.8 2370.90  5592.2 2373.85  5742.7 2374.08
  5793.2 2376.27  5833.5 2375.26  6038.2 2376.81  6126.1 2378.99  6875.7 2381.17
#Mann=3,-1,0
  2865.4    0.05       0  5049.5   0.035       0  5063.5    0.05       0
Bank Sta=5049.5,5063.5
Exp/Cntr=0.3,0.1

Type RM Length L Ch R = 1,133774,1227,1227,1227
BEGIN DESCRIPTION:
Buffalo Creek 175.4
END DESCRIPTION:
XS GIS Cut Line= 5
      1284743.32      6899043.76      1285576.63      6897941.36
      1285839.91      6897035.55      1285832.95      6896823.23
      1285589.83      6895267.46
#Sta/Elev= 30
  2643.7 2380.80  3155.4 2381.18  3184.6 2379.86  3219.9 2381.12  3234.5 2379.55
  3269.9 2380.86  3334.4 2378.85  3863.0 2380.44  3883.8 2379.23  3898.4 2380.51
  3933.8 2378.99  4036.0 2380.43  4074.7 2380.04  4091.6 2377.97  4164.5 2379.64
  4214.1 2377.67  4372.8 2376.57  4430.9 2373.83  4714.8 2369.39  5250.5 2367.57
  5252.0 2367.07  5264.5 2367.57  5601.6 2368.13  5672.5 2370.37  5773.7 2370.15
  5905.3 2372.69  5974.4 2376.29  6077.3 2376.85  6208.9 2381.01  6756.0 2382.04
#Mann=3,-1,0
  2643.7    0.05       0  5250.5   0.033       0  5264.5    0.05       0
Bank Sta=5250.5,5264.5
Exp/Cntr=0.3,0.1

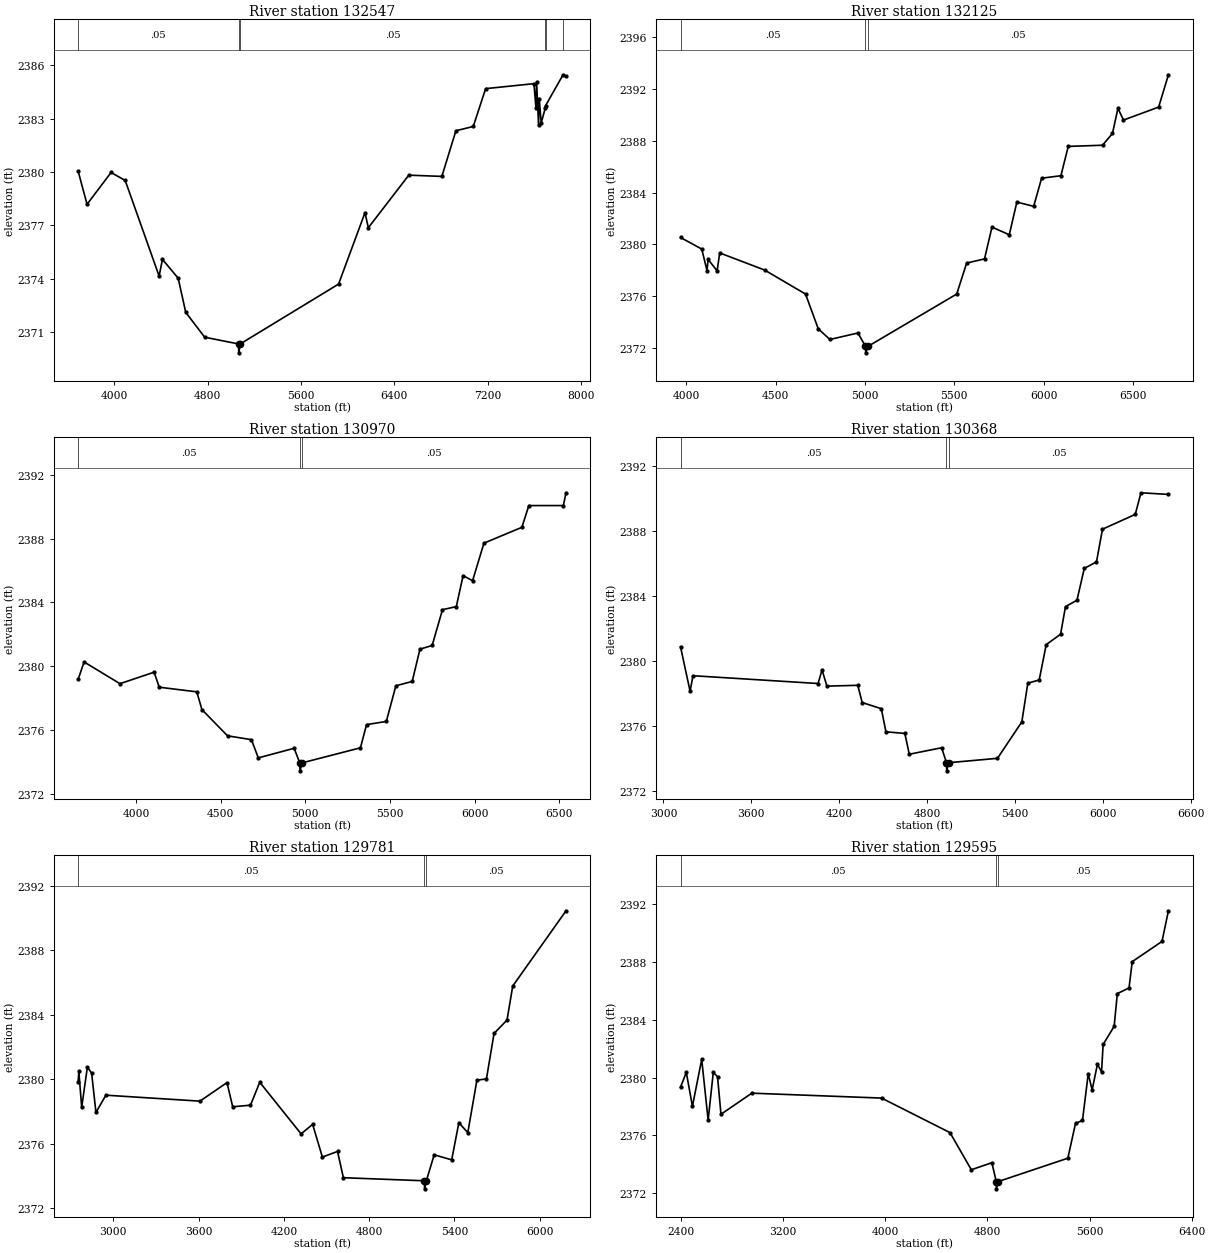
Type RM Length L Ch R = 1,132547,422,422,422
BEGIN DESCRIPTION:
Buffalo Creek 175.32
END DESCRIPTION:
XS GIS Cut Line= 4
      1285722.66      6897952.91      1286518.24      6897298.51
      1288305.37      6895301.07      1288510.07      6894876.50
#Sta/Elev= 30
  3689.2 2380.05  3765.6 2378.18  3971.5 2379.97  4092.7 2379.52  4383.3 2374.14
  4412.0 2375.08  4546.8 2374.02  4611.4 2372.10  4773.7 2370.70  5064.3 2370.32
  5065.8 2369.82  5078.3 2370.32  5921.4 2373.69  6147.9 2377.71  6176.3 2376.86
  6523.2 2379.82  6806.6 2379.75  6927.0 2382.32  7075.7 2382.56  7181.9 2384.69
  7595.8 2384.97  7612.9 2383.62  7618.5 2385.07  7635.5 2382.65  7641.1 2384.13
  7658.1 2382.76  7693.9 2383.62  7695.1 2383.73  7845.5 2385.47  7870.9 2385.40
#Mann=6,-1,0
  3689.2    0.05       0  5064.3   0.033       0  5078.3    0.05       0
  7693.9   0.075       0  7695.1    0.05       0  7845.5   0.075       0
Bank Sta=5064.3,5078.3
Exp/Cntr=0.3,0.1

Type RM Length L Ch R = 1,132125,1155,1155,1155
BEGIN DESCRIPTION:
Buffalo Creek 174.0
END DESCRIPTION:
XS GIS Cut Line= 4
      1285782.53      6897981.57      1286473.60      6897485.96
      1287019.96      6897513.74      1288271.11      6897054.07
#Sta/Elev= 30
  3968.0 2380.54  4086.8 2379.65  4116.3 2377.99  4122.4 2378.85  4172.8 2377.97
  4187.5 2379.35  4438.7 2378.03  4667.7 2376.18  4738.9 2373.50  4804.0 2372.68
  4961.0 2373.18  5003.1 2372.15  5004.6 2371.65  5017.1 2372.15  5513.6 2376.18
  5569.3 2378.57  5669.2 2378.89  5711.0 2381.34  5807.8 2380.75  5850.3 2383.27
  5944.2 2382.94  5988.8 2385.11  6096.6 2385.30  6137.9 2387.56  6329.8 2387.65
  6385.4 2388.56  6415.9 2390.50  6446.9 2389.59  6643.7 2390.59  6698.4 2393.08
#Mann=3,-1,0
  3968.0    0.05       0  5003.1   0.035       0  5017.1    0.05       0
Bank Sta=5003.1,5017.1
Exp/Cntr=0.3,0.1

Type RM Length L Ch R = 1,130970,602,602,602
BEGIN DESCRIPTION:
Buffalo Creek 172.0
END DESCRIPTION:
XS GIS Cut Line= 3
      1285129.99      6898763.00      1286455.00      6898588.00
      1287970.58      6898284.42
#Sta/Elev= 30
  3658.3 2379.19  3693.6 2380.28  3905.4 2378.92  4107.2 2379.64  4137.4 2378.70
  4359.3 2378.41  4389.6 2377.30  4540.9 2375.66  4682.1 2375.42  4722.5 2374.28
  4934.3 2374.88  4967.6 2373.97  4969.1 2373.47  4981.6 2373.97  5326.0 2374.91
  5362.0 2376.36  5478.9 2376.56  5535.3 2378.79  5631.7 2379.06  5677.6 2381.08
  5749.5 2381.31  5810.7 2383.55  5892.3 2383.74  5932.4 2385.68  5988.4 2385.36
  6055.5 2387.71  6279.8 2388.70  6320.6 2390.06  6524.6 2390.06  6540.5 2390.86
#Mann=3,-1,0
  3658.3    0.05       0  4967.6   0.035       0  4981.6    0.05       0
Bank Sta=4967.6,4981.6
Exp/Cntr=0.3,0.1

Type RM Length L Ch R = 1,130368,587,587,587
BEGIN DESCRIPTION:
Buffalo Creek 171.0
END DESCRIPTION:
XS GIS Cut Line= 3
      1284579.97      6899363.00      1286455.00      6899188.00
      1287847.35      6898790.72
#Sta/Elev= 30
  3116.9 2380.86  3182.2 2378.13  3202.3 2379.08  4056.0 2378.60  4083.3 2379.44
  4116.3 2378.44  4327.2 2378.49  4357.3 2377.43  4487.9 2377.05  4519.4 2375.63
  4648.6 2375.53  4678.7 2374.25  4899.6 2374.65  4932.8 2373.73  4934.3 2373.23
  4946.8 2373.73  5280.9 2374.00  5447.2 2376.24  5487.9 2378.62  5565.9 2378.82
  5613.6 2380.99  5711.6 2381.63  5745.4 2383.33  5823.5 2383.72  5873.6 2385.68
  5956.8 2386.08  5997.8 2388.09  6221.5 2389.00  6260.5 2390.33  6448.0 2390.23
#Mann=3,-1,0
  3116.9    0.05       0  4932.8   0.035       0  4946.8    0.05       0
Bank Sta=4932.8,4946.8
Exp/Cntr=0.3,0.1

Type RM Length L Ch R = 1,129781,186,186,186
BEGIN DESCRIPTION:
Buffalo Creek 170.0
END DESCRIPTION:
XS GIS Cut Line= 4
      1284279.97      6899713.00      1285886.56      6899606.77
      1287011.56      6899883.68      1287617.32      6899612.67
#Sta/Elev= 30
  2753.0 2379.84  2758.0 2380.47  2778.1 2378.25  2818.2 2380.75  2848.2 2380.36
  2878.3 2377.93  2948.5 2379.00  3609.9 2378.63  3800.3 2379.78  3840.4 2378.28
  3965.6 2378.38  4030.8 2379.80  4321.5 2376.60  4402.7 2377.19  4471.2 2375.16
  4577.8 2375.51  4619.0 2373.88  5188.7 2373.69  5190.2 2373.19  5202.7 2373.69
  5257.5 2375.30  5381.0 2374.99  5431.3 2377.29  5494.3 2376.68  5558.3 2379.93
  5625.4 2380.01  5678.8 2382.83  5770.1 2383.66  5810.3 2385.77  6185.3 2390.44
#Mann=3,-1,0
  2753.0    0.05       0  5188.7   0.035       0  5202.7    0.05       0
Bank Sta=5188.7,5202.7
Exp/Cntr=0.3,0.1

Type RM Length L Ch R = 1,129595,925,925,925
BEGIN DESCRIPTION:
Buffalo Creek 169.0
END DESCRIPTION:
XS GIS Cut Line= 4
      1283929.98      6900013.00      1285893.51      6899807.29
      1286990.73      6900053.82      1287666.24      6899805.37
#Sta/Elev= 30
  2399.0 2379.33  2444.3 2380.36  2492.3 2378.01  2564.9 2381.26  2615.2 2377.05
  2655.4 2380.35  2688.8 2380.06  2715.7 2377.46  2957.1 2378.92  3972.6 2378.58
  4508.0 2376.19  4675.1 2373.62  4836.0 2374.11  4870.0 2372.80  4871.5 2372.30
  4884.0 2372.80  5430.5 2374.42  5490.5 2376.83  5545.0 2377.03  5590.1 2380.27
  5620.5 2379.14  5662.2 2380.93  5694.2 2380.39  5706.6 2382.29  5792.7 2383.54
  5817.8 2385.81  5909.2 2386.20  5934.3 2388.02  6167.4 2389.42  6217.6 2391.54
#Mann=3,-1,0
  2399.0    0.05       0  4870.0   0.035       0  4884.0    0.05       0
Bank Sta=4870,4884
Exp/Cntr=0.3,0.1