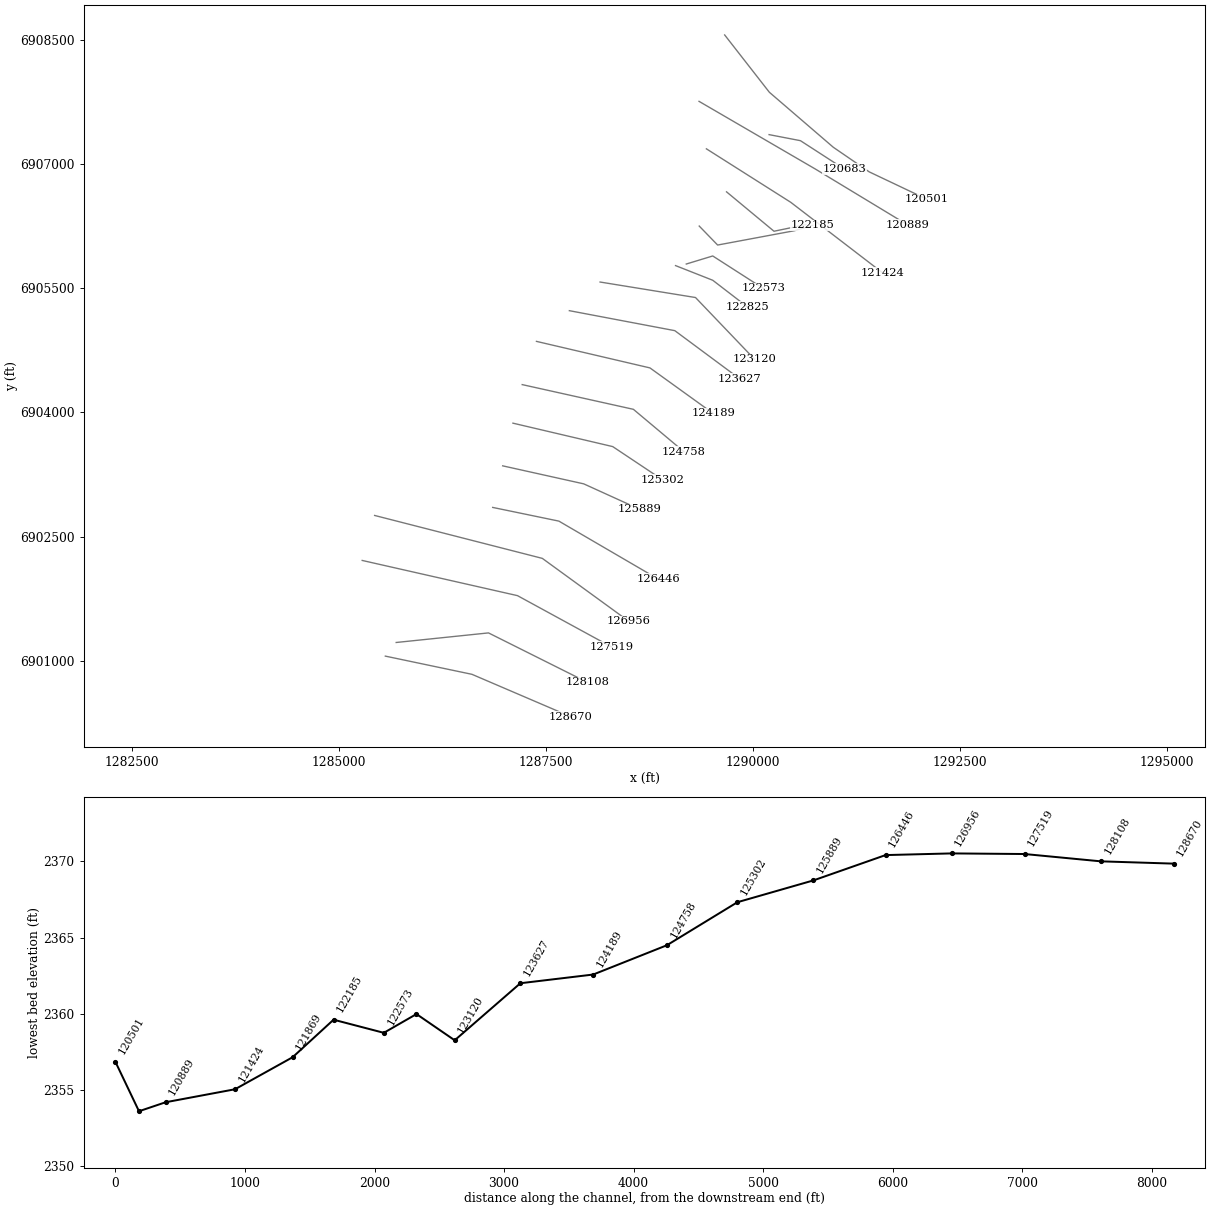
HEC-RAS study Buffalo Creek.prj: Buffalo Creek Base Level Engineering

--- Buffalo Creek.g01 (geometry) --- (continued)

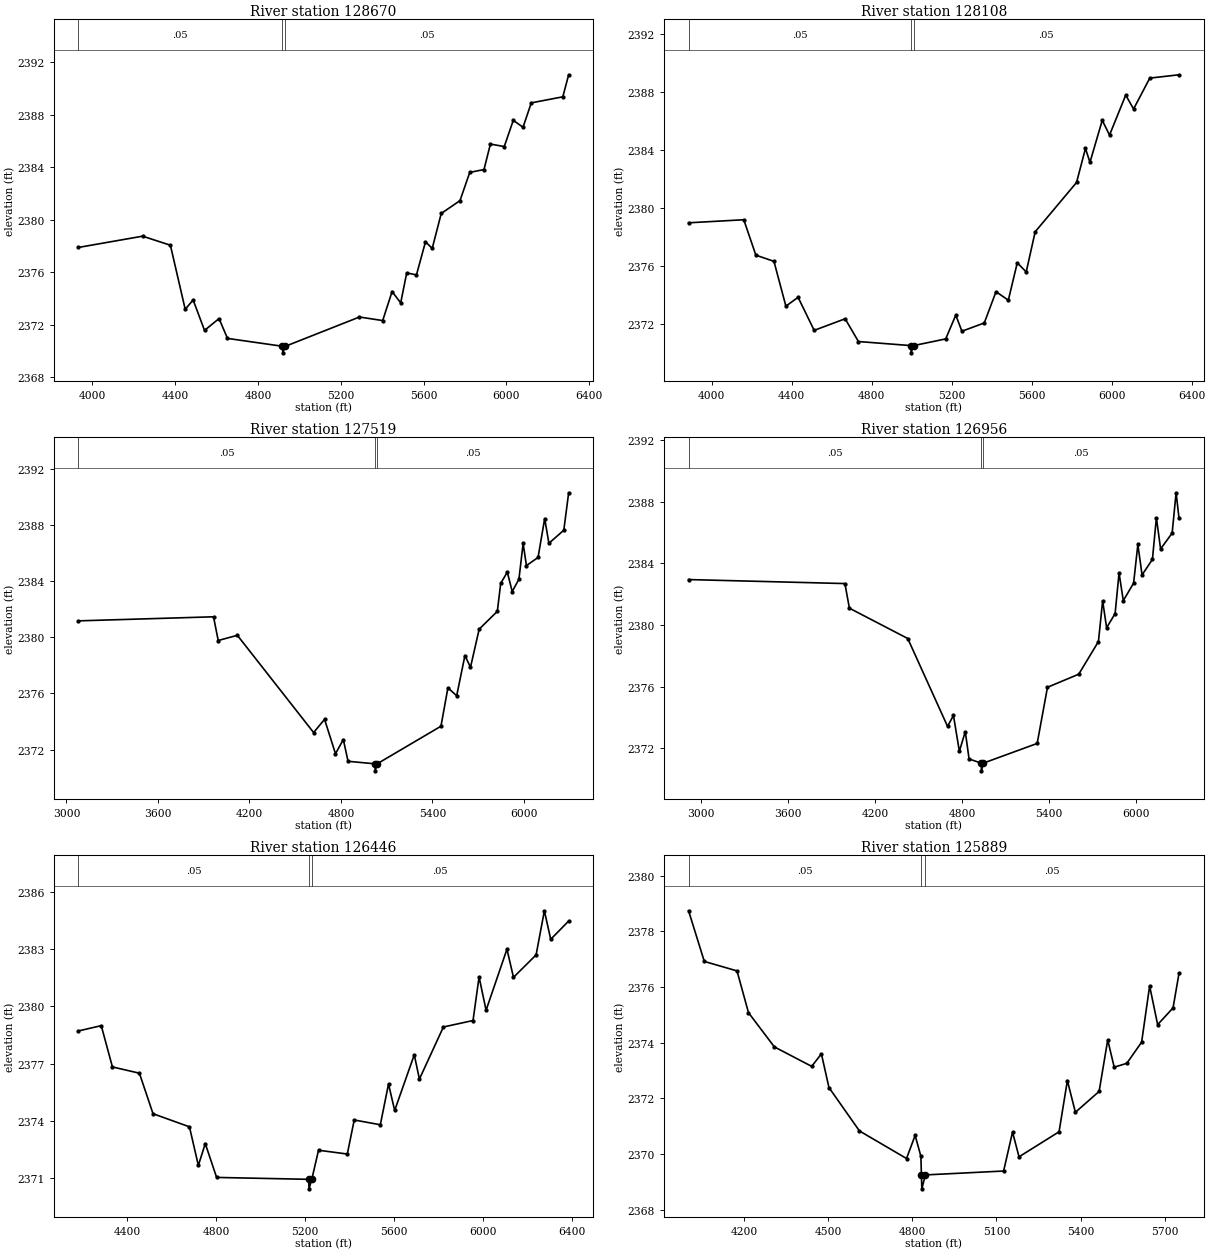
Type RM Length L Ch R = 1,128670,562,562,562
BEGIN DESCRIPTION:
Buffalo Creek 168.0
END DESCRIPTION:
XS GIS Cut Line= 3
      1285559.23      6901057.69      1286605.00      6900838.00
      1287801.00      6900325.43
#Sta/Elev= 30
  3931.4 2377.88  4242.4 2378.74  4376.7 2378.05  4448.2 2373.17  4486.6 2373.88
  4541.6 2371.56  4611.7 2372.46  4652.6 2370.95  4918.2 2370.35  4919.7 2369.85
  4932.2 2370.35  5290.1 2372.58  5402.5 2372.31  5447.9 2374.52  5489.6 2373.66
  5518.6 2375.94  5565.7 2375.79  5609.3 2378.31  5641.9 2377.81  5685.4 2380.47
  5776.1 2381.45  5823.2 2383.60  5892.1 2383.82  5923.0 2385.76  5990.0 2385.57
  6033.6 2387.57  6080.7 2387.04  6120.6 2388.90  6272.9 2389.36  6301.2 2391.04
#Mann=3,-1,0
  3931.4    0.05       0  4918.2   0.035       0  4932.2    0.05       0
Bank Sta=4918.2,4932.2
Exp/Cntr=0.3,0.1

Type RM Length L Ch R = 1,128108,589,589,589
BEGIN DESCRIPTION:
Buffalo Creek 167.0
END DESCRIPTION:
XS GIS Cut Line= 3
      1285690.45      6901222.33      1286805.00      6901338.00
      1287995.63      6900742.68
#Sta/Elev= 30
  3884.8 2378.97  4160.8 2379.18  4221.1 2376.74  4311.6 2376.31  4371.3 2373.22
  4432.3 2373.83  4512.7 2371.55  4667.4 2372.35  4733.9 2370.78  4995.8 2370.50
  4997.3 2370.00  5009.8 2370.50  5170.2 2370.96  5220.6 2372.60  5251.3 2371.49
  5363.1 2372.06  5421.8 2374.22  5483.3 2373.63  5528.0 2376.21  5572.7 2375.58
  5617.5 2378.35  5824.3 2381.75  5869.0 2384.10  5891.4 2383.14  5952.9 2386.04
  5989.2 2385.02  6070.3 2387.78  6109.4 2386.82  6190.5 2388.95  6336.5 2389.18
#Mann=3,-1,0
  3884.8    0.05       0  4995.8   0.035       0  5009.8    0.05       0
Bank Sta=4995.8,5009.8
Exp/Cntr=0.3,0.1

Type RM Length L Ch R = 1,127519,563,563,563
BEGIN DESCRIPTION:
Buffalo Creek 166.0
END DESCRIPTION:
XS GIS Cut Line= 3
      1285280.00      6902213.00      1287155.00      6901788.00
      1288290.06      6901168.87
#Sta/Elev= 30
  3077.4 2381.17  3964.3 2381.46  3995.1 2379.77  4120.6 2380.14  4620.6 2373.21
  4692.4 2374.15  4764.1 2371.70  4815.4 2372.71  4846.5 2371.16  5022.9 2370.98
  5024.4 2370.48  5036.9 2370.98  5455.6 2373.66  5501.2 2376.40  5558.6 2375.83
  5612.7 2378.70  5649.2 2377.86  5706.2 2380.58  5825.3 2381.85  5847.2 2383.84
  5890.8 2384.65  5922.6 2383.26  5966.8 2384.14  5994.3 2386.69  6016.1 2385.11
  6092.1 2385.69  6135.7 2388.46  6163.3 2386.70  6261.0 2387.63  6292.9 2390.30
#Mann=3,-1,0
  3077.4    0.05       0  5022.9   0.035       0  5036.9    0.05       0
Bank Sta=5022.9,5036.9
Exp/Cntr=0.3,0.1

Type RM Length L Ch R = 1,126956,510,510,510
BEGIN DESCRIPTION:
Buffalo Creek 165.0
END DESCRIPTION:
XS GIS Cut Line= 3
      1285430.04      6902756.33      1287455.00      6902238.00
      1288501.06      6901477.23
#Sta/Elev= 30
  2914.1 2382.95  3992.8 2382.69  4023.7 2381.09  4426.3 2379.12  4700.9 2373.41
  4741.7 2374.12  4782.5 2371.79  4823.3 2373.07  4849.5 2371.29  4933.6 2371.02
  4935.1 2370.52  4947.6 2371.02  5319.3 2372.30  5390.4 2375.95  5606.0 2376.80
  5742.0 2378.92  5771.0 2381.57  5798.4 2379.82  5857.1 2380.74  5884.2 2383.38
  5913.6 2381.58  5984.7 2382.72  6014.0 2385.23  6043.0 2383.25  6114.5 2384.26
  6141.9 2386.97  6170.9 2384.94  6250.5 2385.97  6277.9 2388.59  6297.8 2386.95
#Mann=3,-1,0
  2914.1    0.05       0  4933.6   0.035       0  4947.6    0.05       0
Bank Sta=4933.6,4947.6
Exp/Cntr=0.3,0.1

Type RM Length L Ch R = 1,126446,557,557,557
BEGIN DESCRIPTION:
Buffalo Creek 164.0
END DESCRIPTION:
XS GIS Cut Line= 3
      1286855.79      6902853.33      1287655.00      6902688.00
      1288854.67      6901988.19
#Sta/Elev= 30
  4179.5 2378.71  4282.9 2378.99  4333.1 2376.82  4454.4 2376.49  4515.7 2374.36
  4679.5 2373.67  4719.5 2371.64  4750.6 2372.79  4801.6 2371.01  5215.6 2370.91
  5217.1 2370.41  5229.6 2370.91  5259.8 2372.44  5389.3 2372.24  5420.3 2374.03
  5537.7 2373.78  5574.5 2375.92  5602.2 2374.53  5690.3 2377.46  5713.4 2376.18
  5821.3 2378.92  5954.5 2379.26  5981.7 2381.55  6013.2 2379.80  6107.0 2383.01
  6136.4 2381.53  6238.1 2382.71  6275.3 2385.03  6303.8 2383.53  6384.5 2384.49
#Mann=3,-1,0
  4179.5    0.05       0  5215.6   0.035       0  5229.6    0.05       0
Bank Sta=5215.6,5229.6
Exp/Cntr=0.3,0.1

Type RM Length L Ch R = 1,125889,587,587,587
BEGIN DESCRIPTION:
Buffalo Creek 163.0
END DESCRIPTION:
XS GIS Cut Line= 3
      1286976.45      6903355.46      1287955.00      6903138.00
      1288634.29      6902829.23
#Sta/Elev= 30
  4002.2 2378.74  4058.3 2376.92  4174.9 2376.58  4215.8 2375.08  4308.0 2373.85
  4441.2 2373.15  4475.8 2373.60  4502.7 2372.39  4611.5 2370.83  4779.3 2369.84
  4810.0 2370.67  4830.5 2369.92  4832.4 2369.25  4833.9 2368.75  4846.4 2369.25
  5125.5 2369.39  5157.3 2370.79  5180.4 2369.90  5323.2 2370.80  5352.8 2372.64
  5381.4 2371.50  5466.0 2372.25  5496.7 2374.10  5519.8 2373.12  5564.8 2373.26
  5617.6 2374.02  5646.1 2376.04  5674.7 2374.65  5729.6 2375.25  5750.8 2376.49
#Mann=3,-1,0
  4002.2    0.05       0  4832.4   0.035       0  4846.4    0.05       0
Bank Sta=4832.4,4846.4
Exp/Cntr=0.3,0.1

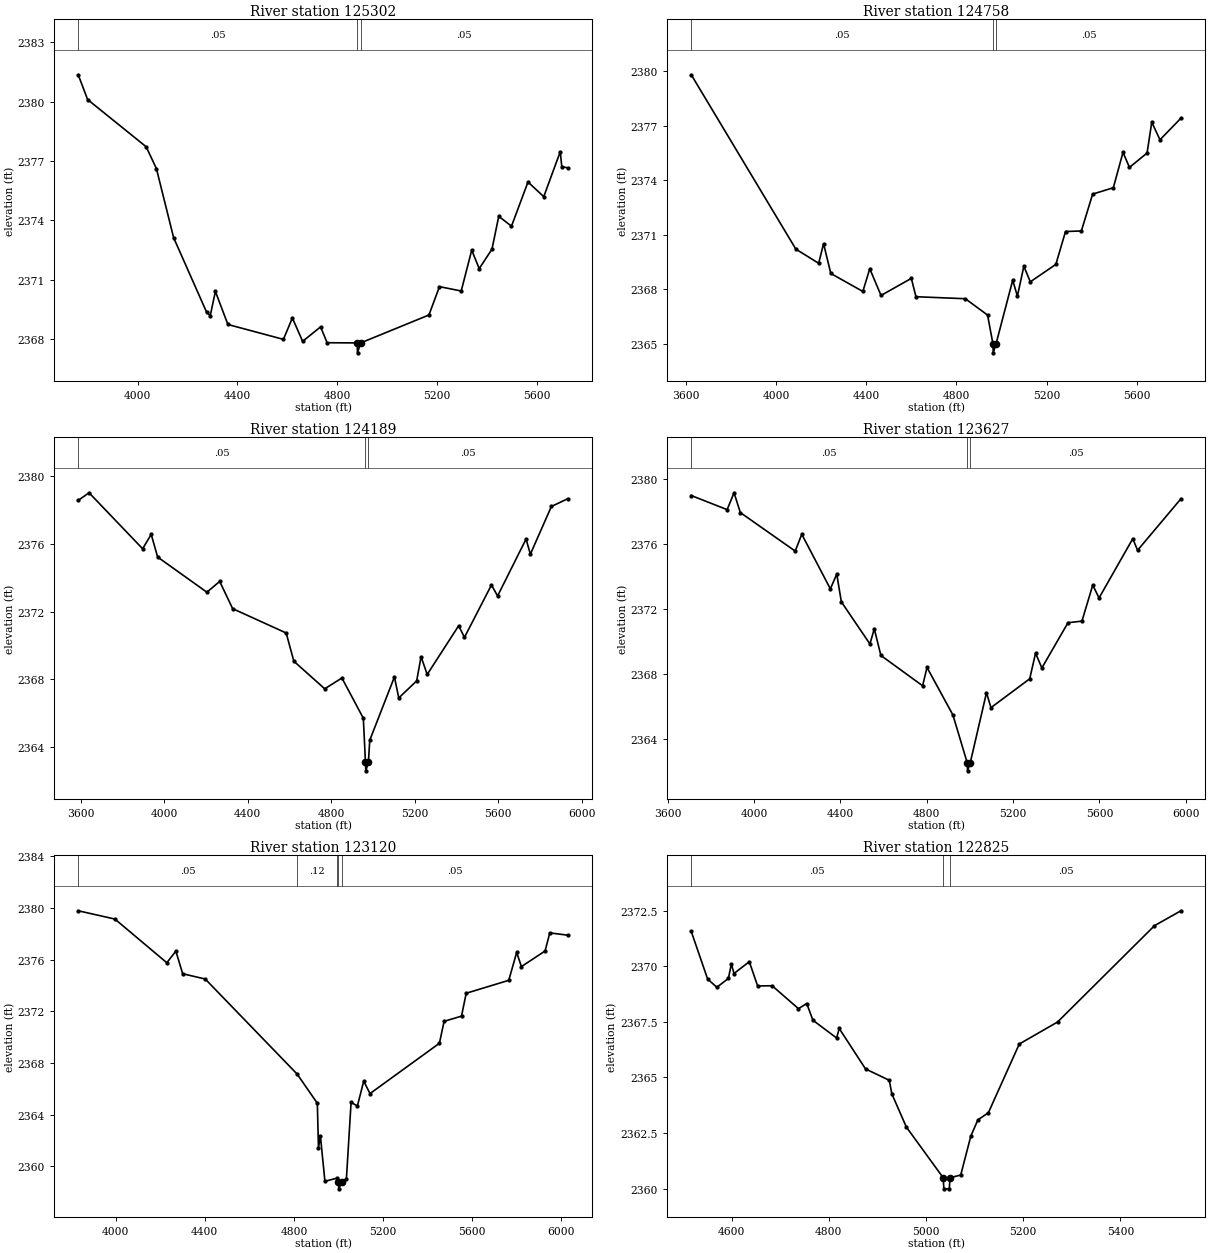
Type RM Length L Ch R = 1,125302,544,544,544
BEGIN DESCRIPTION:
Buffalo Creek 162.0
END DESCRIPTION:
XS GIS Cut Line= 3
      1287100.29      6903870.84      1288305.00      6903588.00
      1288906.60      6903186.93
#Sta/Elev= 30
  3762.5 2381.35  3800.1 2380.10  4034.4 2377.72  4075.5 2376.62  4144.5 2373.13
  4276.9 2369.36  4291.2 2369.20  4311.7 2370.42  4361.8 2368.75  4584.1 2368.00
  4619.9 2369.08  4661.0 2367.90  4732.9 2368.63  4759.0 2367.83  4879.2 2367.82
  4880.7 2367.32  4893.2 2367.82  5166.7 2369.23  5208.8 2370.66  5295.9 2370.44
  5338.0 2372.50  5368.0 2371.57  5419.1 2372.55  5446.2 2374.21  5497.2 2373.71
  5563.3 2375.94  5626.4 2375.20  5692.5 2377.47  5698.5 2376.72  5723.0 2376.65
#Mann=3,-1,0
  3762.5    0.05       0  4879.2   0.035       0  4893.2    0.05       0
Bank Sta=4879.2,4893.2
Exp/Cntr=0.3,0.1

Type RM Length L Ch R = 1,124758,569,569,569
BEGIN DESCRIPTION:
Buffalo Creek 161.0
END DESCRIPTION:
XS GIS Cut Line= 3
      1287212.13      6904336.42      1288555.00      6904038.00
      1289165.02      6903526.37
#Sta/Elev= 30
  3624.1 2379.81  4088.0 2370.21  4189.2 2369.43  4210.9 2370.51  4243.0 2368.87
  4385.1 2367.88  4415.8 2369.13  4465.8 2367.66  4600.2 2368.60  4620.7 2367.59
  4839.7 2367.48  4938.3 2366.58  4962.0 2365.00  4963.5 2364.50  4976.0 2365.00
  5049.8 2368.50  5070.6 2367.62  5099.2 2369.27  5127.9 2368.41  5241.1 2369.37
  5284.0 2371.18  5354.3 2371.21  5404.3 2373.24  5496.1 2373.59  5539.0 2375.54
  5567.6 2374.71  5645.7 2375.50  5666.5 2377.20  5702.9 2376.23  5795.9 2377.42
#Mann=3,-1,0
  3624.1    0.05       0  4962.0    0.05       0  4976.0    0.05       0
Bank Sta=4962,4976
Exp/Cntr=0.3,0.1

Type RM Length L Ch R = 1,124189,562,562,562
BEGIN DESCRIPTION:
Buffalo Creek 160.0
END DESCRIPTION:
XS GIS Cut Line= 3
      1287384.30      6904858.49      1288755.00      6904538.00
      1289517.34      6903989.02
#Sta/Elev= 30
  3587.6 2378.57  3639.7 2379.02  3896.4 2375.71  3937.5 2376.56  3968.3 2375.22
  4204.5 2373.14  4265.8 2373.78  4327.7 2372.17  4584.5 2370.73  4621.2 2369.06
  4769.3 2367.43  4851.5 2368.07  4954.2 2365.69  4964.5 2363.08  4966.0 2362.58
  4978.5 2363.08  4985.0 2364.39  5103.3 2368.13  5124.1 2366.89  5210.0 2367.90
  5230.9 2369.33  5260.4 2368.28  5411.3 2371.16  5438.9 2370.47  5568.4 2373.57
  5597.8 2372.92  5734.1 2376.28  5755.0 2375.39  5855.6 2378.21  5934.7 2378.67
#Mann=3,-1,0
  3587.6    0.05       0  4964.5    0.05       0  4978.5    0.05       0
Bank Sta=4964.5,4978.5
Exp/Cntr=0.3,0.1

Type RM Length L Ch R = 1,123627,507,507,507
BEGIN DESCRIPTION:
Buffalo Creek 159.0
END DESCRIPTION:
XS GIS Cut Line= 3
      1287781.69      6905229.24      1289055.00      6904988.00
      1289836.45      6904408.22
#Sta/Elev= 30
  3708.7 2379.00  3874.9 2378.13  3907.0 2379.17  3936.0 2377.95  4190.4 2375.57
  4220.8 2376.61  4353.3 2373.24  4382.8 2374.15  4404.2 2372.44  4536.5 2369.84
  4556.8 2370.77  4587.4 2369.13  4780.7 2367.26  4801.1 2368.39  4921.1 2365.46
  4987.4 2362.51  4988.9 2362.01  5001.5 2362.51  5076.7 2366.83  5097.5 2365.91
  5277.0 2367.69  5304.0 2369.27  5333.3 2368.36  5454.3 2371.15  5519.0 2371.25
  5569.0 2373.47  5598.3 2372.68  5754.7 2376.34  5776.7 2375.62  5977.7 2378.80
#Mann=3,-1,0
  3708.7    0.05       0  4987.4    0.05       0  5001.5    0.05       0
Bank Sta=4987.4,5001.5
Exp/Cntr=0.3,0.1

Type RM Length L Ch R = 1,123120,295,295,295
BEGIN DESCRIPTION:
Buffalo Creek 158.0
END DESCRIPTION:
XS GIS Cut Line= 3
      1288152.60      6905575.18      1289305.00      6905388.00
      1290016.26      6904644.40
#Sta/Elev= 30
  3832.5 2379.78  3997.0 2379.14  4230.0 2375.76  4270.6 2376.66  4301.0 2374.91
  4402.3 2374.50  4814.4 2367.15  4905.1 2364.89  4910.2 2361.44  4919.0 2362.34
  4939.2 2358.85  4991.2 2359.09  5000.0 2358.77  5001.5 2358.27  5014.1 2358.77
  5035.4 2359.01  5056.5 2364.96  5084.8 2364.68  5113.1 2366.60  5141.4 2365.64
  5452.7 2369.53  5473.8 2371.23  5551.8 2371.63  5572.9 2373.40  5763.8 2374.40
  5799.3 2376.56  5820.4 2375.46  5926.7 2376.67  5947.8 2378.07  6029.0 2377.89
#Mann=5,-1,0
  3832.5    0.05       0  4814.4    0.12       0  4991.2    0.05       0
  5000.0    0.05       0  5014.1    0.05       0
Bank Sta=5000,5014.1
Exp/Cntr=0.3,0.1

Type RM Length L Ch R = 1,122825,252,252,252
BEGIN DESCRIPTION:
Buffalo Creek 157.0
END DESCRIPTION:
XS GIS Cut Line= 3
      1289063.93      6905773.53      1289513.38      6905596.37
      1289929.11      6905276.74
#Sta/Elev= 30
  4516.9 2371.56  4550.6 2369.42  4569.6 2369.05  4593.3 2369.45  4599.4 2370.10
  4604.8 2369.67  4636.3 2370.20  4653.5 2369.11  4683.3 2369.12  4737.4 2368.09
  4754.5 2368.32  4767.2 2367.57  4816.0 2366.77  4821.3 2367.20  4875.5 2365.38
  4924.3 2364.87  4929.6 2364.26  4959.4 2362.77  5035.2 2360.49  5036.7 2359.99
  5047.8 2359.99  5049.3 2360.49  5071.3 2360.61  5092.1 2362.36  5106.6 2363.09
  5128.2 2363.41  5191.8 2366.50  5270.6 2367.49  5470.0 2371.82  5524.4 2372.49
#Mann=3,-1,0
  4516.9    0.05       0  5035.2    0.05       0  5049.3    0.05       0
Bank Sta=5035.2,5049.3
Exp/Cntr=0.3,0.1

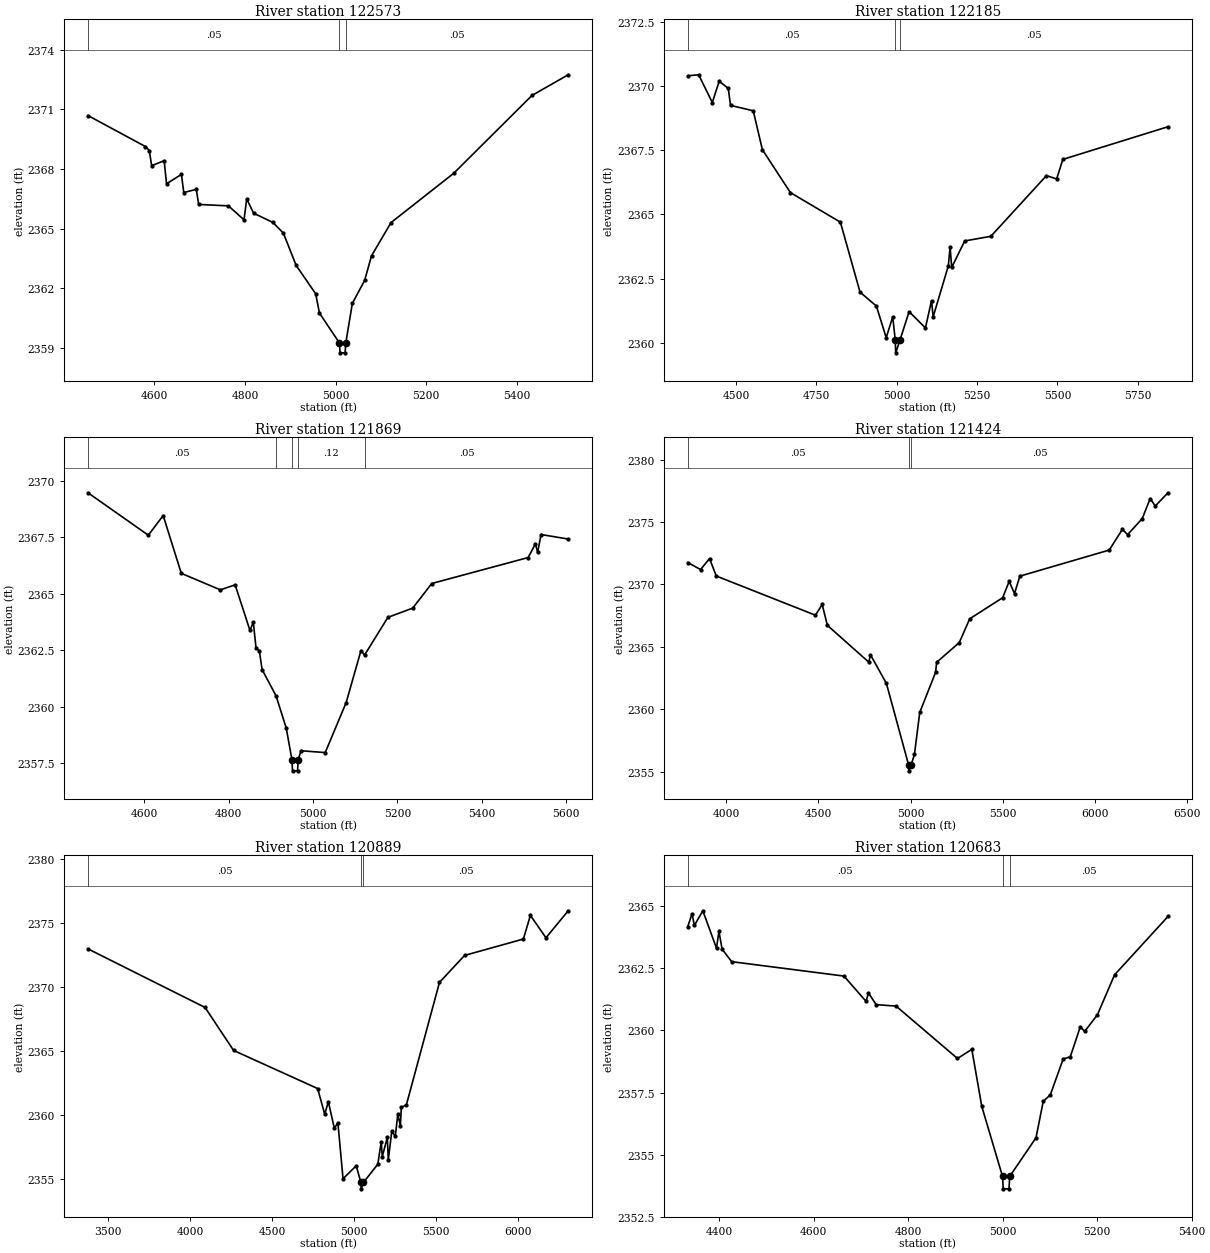
Type RM Length L Ch R = 1,122573,388,388,388
BEGIN DESCRIPTION:
Mapping XS d12b80e9
END DESCRIPTION:
XS GIS Cut Line= 3
      1289193.59      6905792.67      1289513.04      6905889.90
      1290124.12      6905497.56
#Sta/Elev= 30
  4453.4 2370.69  4580.3 2369.13  4588.7 2368.93  4593.9 2368.17  4621.6 2368.42
  4626.8 2367.26  4659.6 2367.73  4664.9 2366.82  4692.5 2366.98  4697.7 2366.22
  4763.4 2366.15  4797.8 2365.45  4803.8 2366.50  4819.0 2365.78  4861.3 2365.32
  4884.7 2364.78  4912.8 2363.16  4956.0 2361.73  4964.3 2360.76  5008.4 2359.26
  5009.9 2358.76  5021.0 2358.76  5022.5 2359.26  5037.0 2361.25  5064.1 2362.40
  5079.3 2363.64  5122.4 2365.31  5260.9 2367.79  5433.4 2371.70  5513.5 2372.74
#Mann=3,-1,0
  4453.4    0.05       0  5008.4    0.05       0  5022.5    0.05       0
Bank Sta=5008.4,5022.5
Exp/Cntr=0.3,0.1

Type RM Length L Ch R = 1,122185,316,316,316
BEGIN DESCRIPTION:
Mapping XS d27f5a74
END DESCRIPTION:
XS GIS Cut Line= 4
      1289349.82      6906251.05      1289572.07      6906021.84
      1290502.63      6906195.46      1290720.65      6906261.21
#Sta/Elev= 30
  4350.2 2370.39  4384.2 2370.43  4426.7 2369.35  4448.0 2370.18  4476.3 2369.90
  4483.3 2369.24  4554.0 2369.03  4582.3 2367.52  4669.5 2365.85  4825.0 2364.70
  4886.1 2361.98  4936.9 2361.44  4967.5 2360.21  4987.8 2361.02  4995.6 2360.12
  4997.1 2359.62  5010.4 2360.12  5038.7 2361.22  5089.5 2360.59  5108.4 2361.65
  5113.5 2361.02  5160.7 2363.00  5166.2 2363.74  5171.2 2362.94  5211.6 2363.97
  5293.0 2364.15  5465.9 2366.51  5497.6 2366.38  5516.8 2367.14  5843.8 2368.41
#Mann=3,-1,0
  4350.2    0.05       0  4995.6   0.033       0  5010.4    0.05       0
Bank Sta=4995.6,5010.4
Exp/Cntr=0.3,0.1

Type RM Length L Ch R = 1,121869,445,445,445
BEGIN DESCRIPTION:
Mapping XS 6788db7d
END DESCRIPTION:
XS GIS Cut Line= 3
      1289679.73      6906664.19      1290252.63      6906188.51
      1290638.00      6906268.36
#Sta/Elev= 30
  4466.5 2369.48  4609.5 2367.60  4644.7 2368.47  4687.7 2365.91  4780.1 2365.18
  4815.3 2365.40  4850.4 2363.38  4858.3 2363.75  4864.8 2362.60  4872.6 2362.48
  4879.1 2361.65  4912.3 2360.48  4936.4 2359.05  4949.8 2357.66  4951.3 2357.16
  4963.2 2357.16  4964.7 2357.66  4971.5 2358.05  5028.8 2357.97  5078.3 2360.18
  5113.5 2362.49  5122.0 2362.29  5177.3 2363.96  5236.2 2364.37  5281.2 2365.46
  5509.7 2366.61  5527.0 2367.22  5532.1 2366.84  5540.4 2367.63  5604.7 2367.43
#Mann=5,-1,0
  4466.5    0.05       0  4912.3    0.12       0  4949.8    0.07       0
  4964.7    0.12       0  5122.0    0.05       0
Bank Sta=4949.8,4964.7
Exp/Cntr=0.3,0.1

Type RM Length L Ch R = 1,121424,535,535,535
BEGIN DESCRIPTION:
Buffalo Creek 155.0
END DESCRIPTION:
XS GIS Cut Line= 3
      1289436.33      6907183.84      1290455.00      6906538.00
      1291561.35      6905688.70
#Sta/Elev= 30
  3793.4 2371.75  3862.9 2371.19  3911.6 2372.07  3948.0 2370.67  4485.2 2367.53
  4521.7 2368.39  4549.6 2366.72  4774.6 2363.76  4782.6 2364.37  4869.3 2362.07
  4989.1 2355.56  4990.6 2355.06  5004.0 2355.56  5021.3 2356.38  5050.0 2359.74
  5135.5 2362.94  5141.8 2363.76  5264.3 2365.34  5320.4 2367.24  5499.0 2368.93
  5534.3 2370.24  5563.3 2369.26  5592.1 2370.66  6076.3 2372.75  6147.0 2374.40
  6176.0 2373.99  6254.9 2375.27  6298.0 2376.88  6325.6 2376.28  6394.3 2377.34
#Mann=3,-1,0
  3793.4    0.05       0  4989.1    0.05       0  5004.0    0.05       0
Bank Sta=4989.1,5004
Exp/Cntr=0.3,0.1

Type RM Length L Ch R = 1,120889,206,206,206
BEGIN DESCRIPTION:
Buffalo Creek 154.0
END DESCRIPTION:
XS GIS Cut Line= 3
      1289347.52      6907757.04      1290755.00      6906938.00
      1291868.33      6906263.99
#Sta/Elev= 30
  3375.9 2372.97  4090.3 2368.39  4264.2 2365.03  4777.2 2362.05  4820.2 2360.04
  4842.4 2361.02  4879.0 2358.94  4900.5 2359.39  4931.9 2355.00  5012.1 2356.01
  5041.3 2354.71  5042.8 2354.21  5056.5 2354.71  5144.0 2356.13  5165.3 2357.91
  5171.2 2356.72  5202.2 2358.24  5208.0 2356.46  5229.3 2358.70  5250.7 2358.32
  5266.2 2360.04  5281.7 2359.15  5287.5 2360.57  5318.5 2360.78  5520.3 2370.35
  5673.5 2372.46  6032.3 2373.74  6075.0 2375.59  6170.0 2373.84  6305.8 2375.95
#Mann=3,-1,0
  3375.9    0.05       0  5041.3   0.033       0  5056.5    0.05       0
Bank Sta=5041.3,5056.5
Exp/Cntr=0.3,0.1

Type RM Length L Ch R = 1,120683,182,182,182
BEGIN DESCRIPTION:
Mapping XS bec42f6b
END DESCRIPTION:
XS GIS Cut Line= 3
      1290193.56      6907355.19      1290572.07      6907282.26
      1291101.69      6906939.56
#Sta/Elev= 30
  4333.4 2364.18  4342.5 2364.70  4347.5 2364.23  4365.4 2364.82  4394.3 2363.31
  4399.4 2363.99  4406.2 2363.27  4426.5 2362.77  4664.0 2362.19  4710.8 2361.17
  4715.9 2361.51  4732.1 2361.04  4774.3 2360.98  4904.3 2358.87  4934.6 2359.24
  4955.7 2356.94  4999.6 2354.12  5001.1 2353.62  5013.3 2353.62  5014.8 2354.12
  5070.5 2355.68  5085.7 2357.14  5100.8 2357.41  5127.9 2358.85  5143.0 2358.94
  5164.2 2360.15  5173.4 2359.96  5200.4 2360.63  5236.7 2362.24  5349.7 2364.59
#Mann=3,-1,0
  4333.4    0.05       0  4999.6    0.05       0  5014.8    0.05       0
Bank Sta=4999.6,5014.8
Exp/Cntr=0.3,0.1

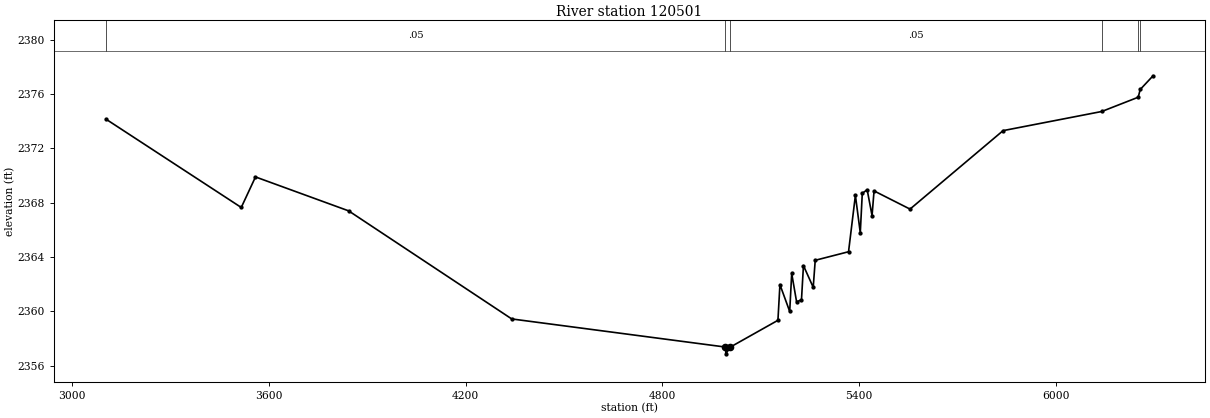
Type RM Length L Ch R = 1,120501,257,257,257
BEGIN DESCRIPTION:
Buffalo Creek 153.5
END DESCRIPTION:
XS GIS Cut Line= 5
      1289657.16      6908558.86      1290196.61      6907866.98
      1290969.33      6907202.33      1291402.03      6906905.78
      1292098.95      6906574.92
#Sta/Elev= 30
  3104.0 2374.14  3516.2 2367.64  3559.6 2369.89  3843.7 2367.39  4341.0 2359.43
  4992.5 2357.36  4994.0 2356.86  5007.7 2357.36  5152.7 2359.33  5158.8 2361.96
  5188.6 2359.98  5194.7 2362.78  5209.6 2360.69  5224.5 2360.84  5230.5 2363.36
  5260.3 2361.76  5266.4 2363.75  5368.0 2364.38  5388.9 2368.53  5403.8 2365.78
  5409.9 2368.68  5424.8 2368.95  5439.7 2367.04  5445.8 2368.86  5555.5 2367.52
  5839.3 2373.30  6140.2 2374.71  6251.3 2375.76  6257.4 2376.33  6296.6 2377.34
#Mann=6,-1,0
  3104.0    0.05       0  4992.5    0.05       0  5007.7    0.05       0
  6140.2   0.075       0  6251.3    0.05       0  6257.4   0.075       0
Bank Sta=4992.5,5007.7
Exp/Cntr=0.3,0.1