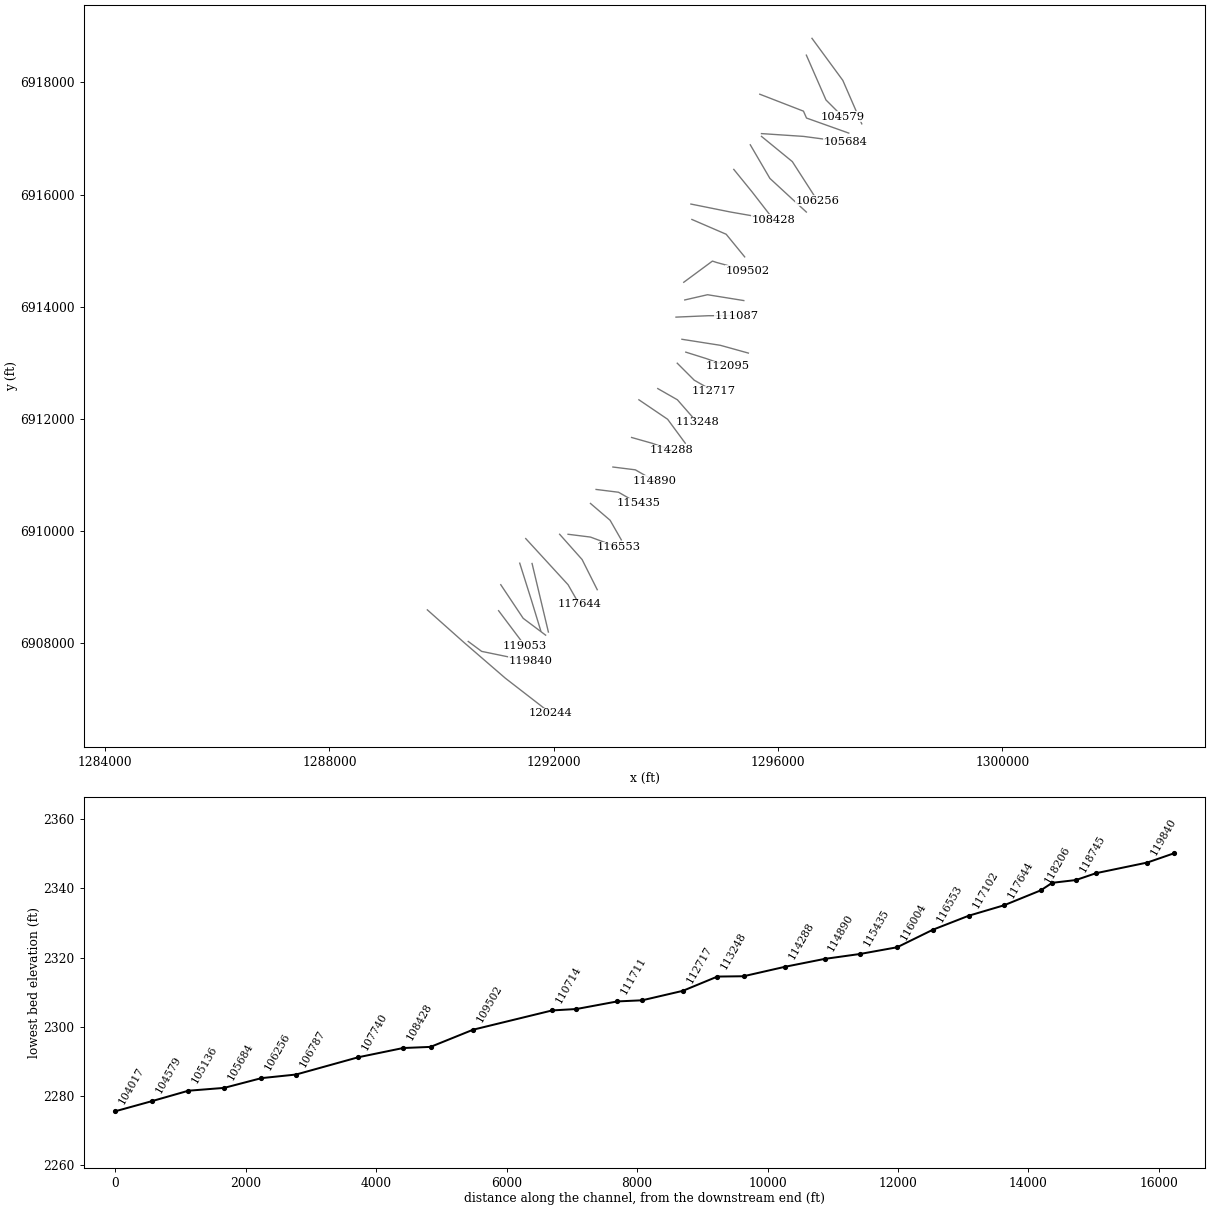
HEC-RAS study Buffalo Creek.prj: Buffalo Creek Base Level Engineering

--- Buffalo Creek.g01 (geometry) --- (continued)

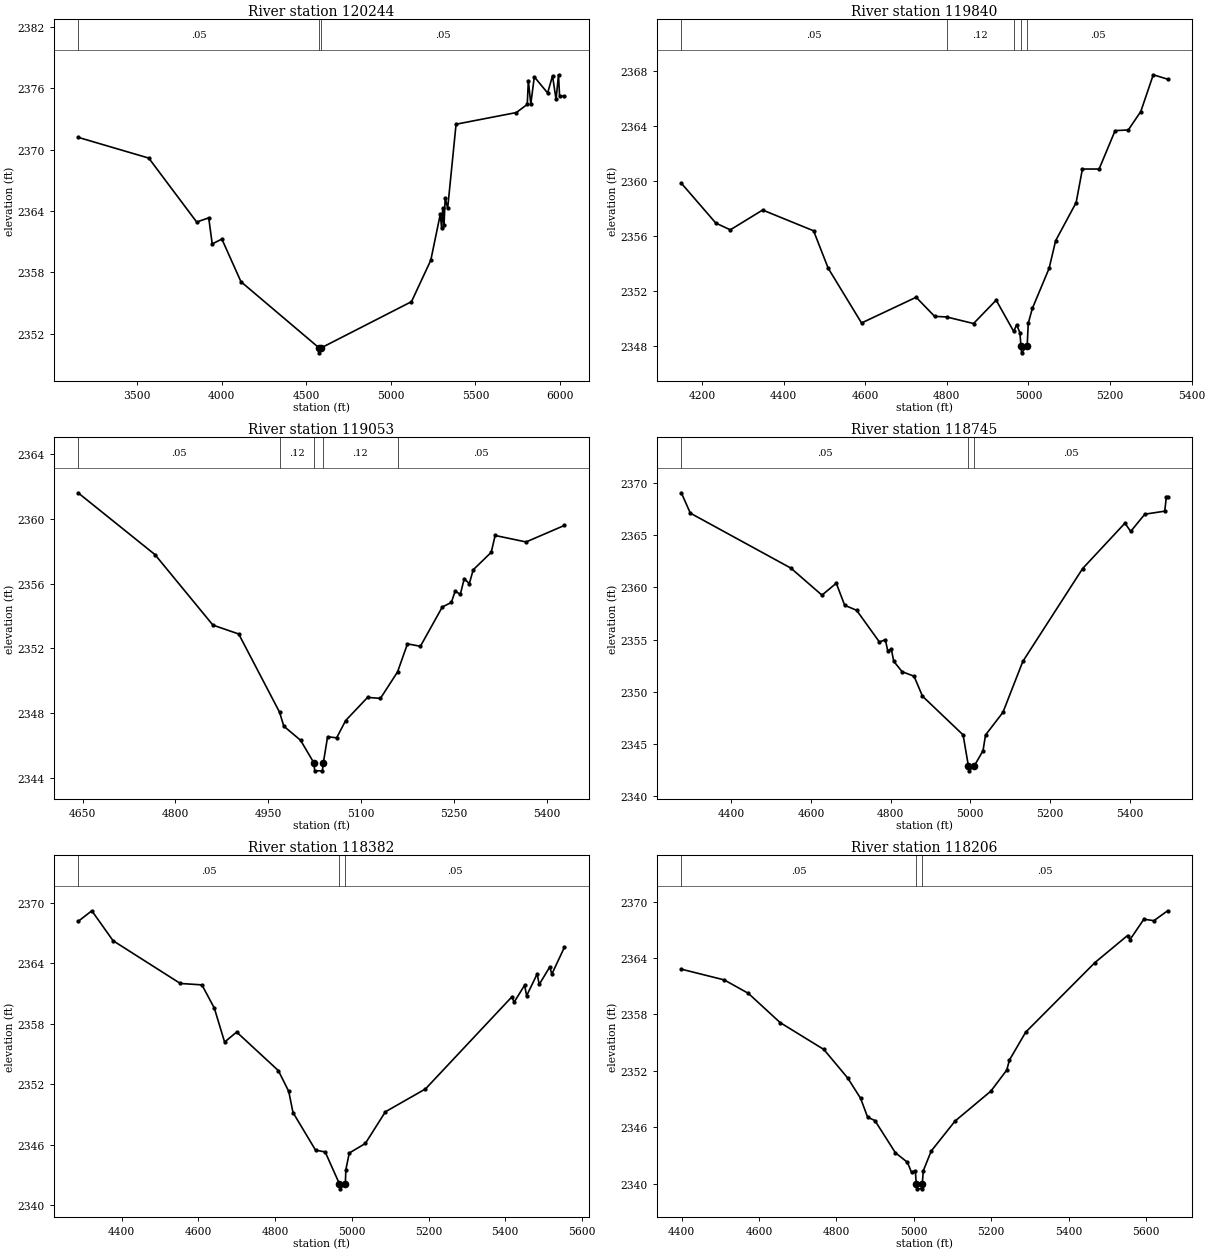
Type RM Length L Ch R = 1,120244,404,404,404
BEGIN DESCRIPTION:
Buffalo Creek 153.0
END DESCRIPTION:
XS GIS Cut Line= 4
      1289745.66      6908589.05      1290398.43      6908007.60
      1291136.65      6907369.65      1291947.51      6906741.93
#Sta/Elev= 30
  3150.4 2371.20  3568.4 2369.17  3851.8 2362.92  3922.9 2363.33  3943.8 2360.78
  4000.7 2361.26  4113.6 2357.09  4574.3 2350.64  4575.8 2350.14  4589.6 2350.64
  5121.9 2355.14  5236.0 2359.19  5292.1 2363.68  5300.3 2362.29  5306.6 2364.29
  5314.3 2362.64  5321.1 2365.30  5335.6 2364.25  5385.4 2372.48  5742.1 2373.62
  5806.4 2374.42  5812.7 2376.75  5827.2 2374.44  5848.0 2377.11  5926.8 2375.53
  5955.8 2377.21  5976.6 2374.90  5991.1 2377.31  5997.4 2375.24  6025.7 2375.21
#Mann=3,-1,0
  3150.4    0.05       0  4574.3    0.05       0  4589.6    0.05       0
Bank Sta=4574.3,4589.6
Exp/Cntr=0.3,0.1

Type RM Length L Ch R = 1,119840,787,787,787
BEGIN DESCRIPTION:
Mapping XS caff2ccb
END DESCRIPTION:
XS GIS Cut Line= 3
      1290474.83      6908025.33      1290714.43      6907848.23
      1291589.44      6907667.68
#Sta/Elev= 30
  4149.6 2359.83  4234.1 2356.93  4269.6 2356.44  4348.8 2357.88  4473.6 2356.37
  4509.4 2353.65  4591.1 2349.67  4724.9 2351.54  4770.1 2350.15  4799.3 2350.11
  4865.5 2349.63  4920.9 2351.33  4963.8 2349.06  4971.1 2349.54  4979.1 2348.96
  4981.6 2348.00  4983.1 2347.50  4996.9 2348.00  4999.5 2349.65  5009.7 2350.74
  5050.6 2353.64  5066.6 2355.65  5116.8 2358.42  5132.2 2360.86  5173.1 2360.86
  5212.3 2363.65  5244.6 2363.70  5275.2 2365.04  5305.8 2367.71  5341.0 2367.39
#Mann=5,-1,0
  4149.6    0.05       0  4799.3    0.12       0  4963.8    0.05       0
  4981.6    0.05       0  4996.9    0.05       0
Bank Sta=4981.6,4996.9
Exp/Cntr=0.3,0.1

Type RM Length L Ch R = 1,119053,308,308,308
BEGIN DESCRIPTION:
Mapping XS 54e9c5d2
END DESCRIPTION:
XS GIS Cut Line= 2
      1291016.50      6908573.95      1291488.71      6907945.49
#Sta/Elev= 30
  4642.7 2361.61  4767.0 2357.79  4860.7 2353.43  4902.4 2352.88  4968.5 2348.04
  4975.3 2347.18  5002.4 2346.31  5023.8 2344.92  5025.3 2344.42  5037.7 2344.42
  5039.2 2344.92  5046.1 2346.53  5060.7 2346.46  5075.3 2347.53  5110.7 2348.96
  5131.5 2348.90  5159.1 2350.53  5175.2 2352.27  5196.1 2352.12  5231.5 2354.55
  5246.1 2354.83  5252.3 2355.53  5260.6 2355.33  5266.9 2356.29  5275.2 2356.00
  5281.5 2356.85  5310.6 2357.93  5316.9 2358.97  5366.9 2358.57  5428.8 2359.59
#Mann=5,-1,0
  4642.7    0.05       0  4968.5    0.12       0  5023.8    0.07       0
  5039.2    0.12       0  5159.1    0.05       0
Bank Sta=5023.8,5039.2
Exp/Cntr=0.3,0.1

Type RM Length L Ch R = 1,118745,363,363,363
BEGIN DESCRIPTION:
Buffalo Creek 150.0
END DESCRIPTION:
XS GIS Cut Line= 3
      1291054.98      6909038.04      1291455.00      6908438.00
      1291855.04      6908137.97
#Sta/Elev= 30
  4274.3 2369.06  4296.9 2367.11  4549.3 2361.85  4627.4 2359.26  4663.4 2360.40
  4684.5 2358.29  4714.5 2357.81  4771.6 2354.78  4786.6 2354.99  4792.6 2353.94
  4801.7 2354.07  4807.7 2352.93  4828.7 2351.93  4858.7 2351.50  4879.8 2349.59
  4981.9 2345.88  4995.0 2342.94  4996.5 2342.44  5010.4 2342.94  5031.9 2344.37
  5038.2 2345.87  5081.9 2348.04  5131.9 2352.92  5281.9 2361.80  5388.2 2366.15
  5402.7 2365.36  5438.2 2367.01  5488.2 2367.30  5492.3 2368.69  5495.5 2368.69
#Mann=3,-1,0
  4274.3    0.05       0  4995.0    0.05       0  5010.4    0.05       0
Bank Sta=4995,5010.4
Exp/Cntr=0.3,0.1

Type RM Length L Ch R = 1,118382,176,176,176
BEGIN DESCRIPTION:
Buffalo Creek 149.0
END DESCRIPTION:
XS GIS Cut Line= 3
      1291393.23      6909422.27      1291602.31      6908760.05
      1291769.58      6908211.74
#Sta/Elev= 30
  4286.3 2368.16  4322.2 2369.22  4377.6 2366.25  4552.9 2362.01  4609.2 2361.87
  4641.5 2359.57  4668.3 2356.20  4699.8 2357.19  4808.4 2353.37  4835.5 2351.31
  4846.6 2349.21  4905.4 2345.48  4930.5 2345.30  4967.6 2342.14  4969.1 2341.64
  4983.1 2342.14  4984.4 2343.54  4993.3 2345.19  5035.2 2346.14  5087.4 2349.28
  5192.0 2351.55  5417.6 2360.70  5422.8 2360.14  5450.4 2361.84  5455.6 2360.79
  5483.2 2362.96  5488.4 2361.91  5516.0 2363.65  5521.3 2362.93  5554.0 2365.59
#Mann=3,-1,0
  4286.3    0.05       0  4967.6    0.05       0  4983.1    0.05       0
Bank Sta=4967.6,4983.1
Exp/Cntr=0.3,0.1

Type RM Length L Ch R = 1,118206,562,562,562
BEGIN DESCRIPTION:
Buffalo Creek 149.5
END DESCRIPTION:
XS GIS Cut Line= 2
      1291613.35      6909416.49      1291904.32      6908193.42
#Sta/Elev= 30
  4398.9 2362.82  4509.7 2361.68  4572.1 2360.25  4654.3 2357.14  4767.4 2354.28
  4829.1 2351.24  4862.4 2349.08  4880.5 2347.08  4899.4 2346.72  4952.4 2343.29
  4983.3 2342.29  4994.0 2341.21  5003.8 2341.40  5006.3 2339.96  5007.8 2339.46
  5020.3 2339.46  5021.8 2339.96  5024.4 2341.38  5044.9 2343.48  5106.6 2346.67
  5199.1 2349.85  5240.2 2352.09  5247.0 2353.15  5289.1 2356.12  5468.1 2363.52
  5552.4 2366.40  5558.9 2365.97  5594.6 2368.13  5620.6 2367.98  5656.1 2369.03
#Mann=3,-1,0
  4398.9    0.05       0  5006.3   0.033       0  5021.8    0.05       0
Bank Sta=5006.3,5021.8
Exp/Cntr=0.3,0.1

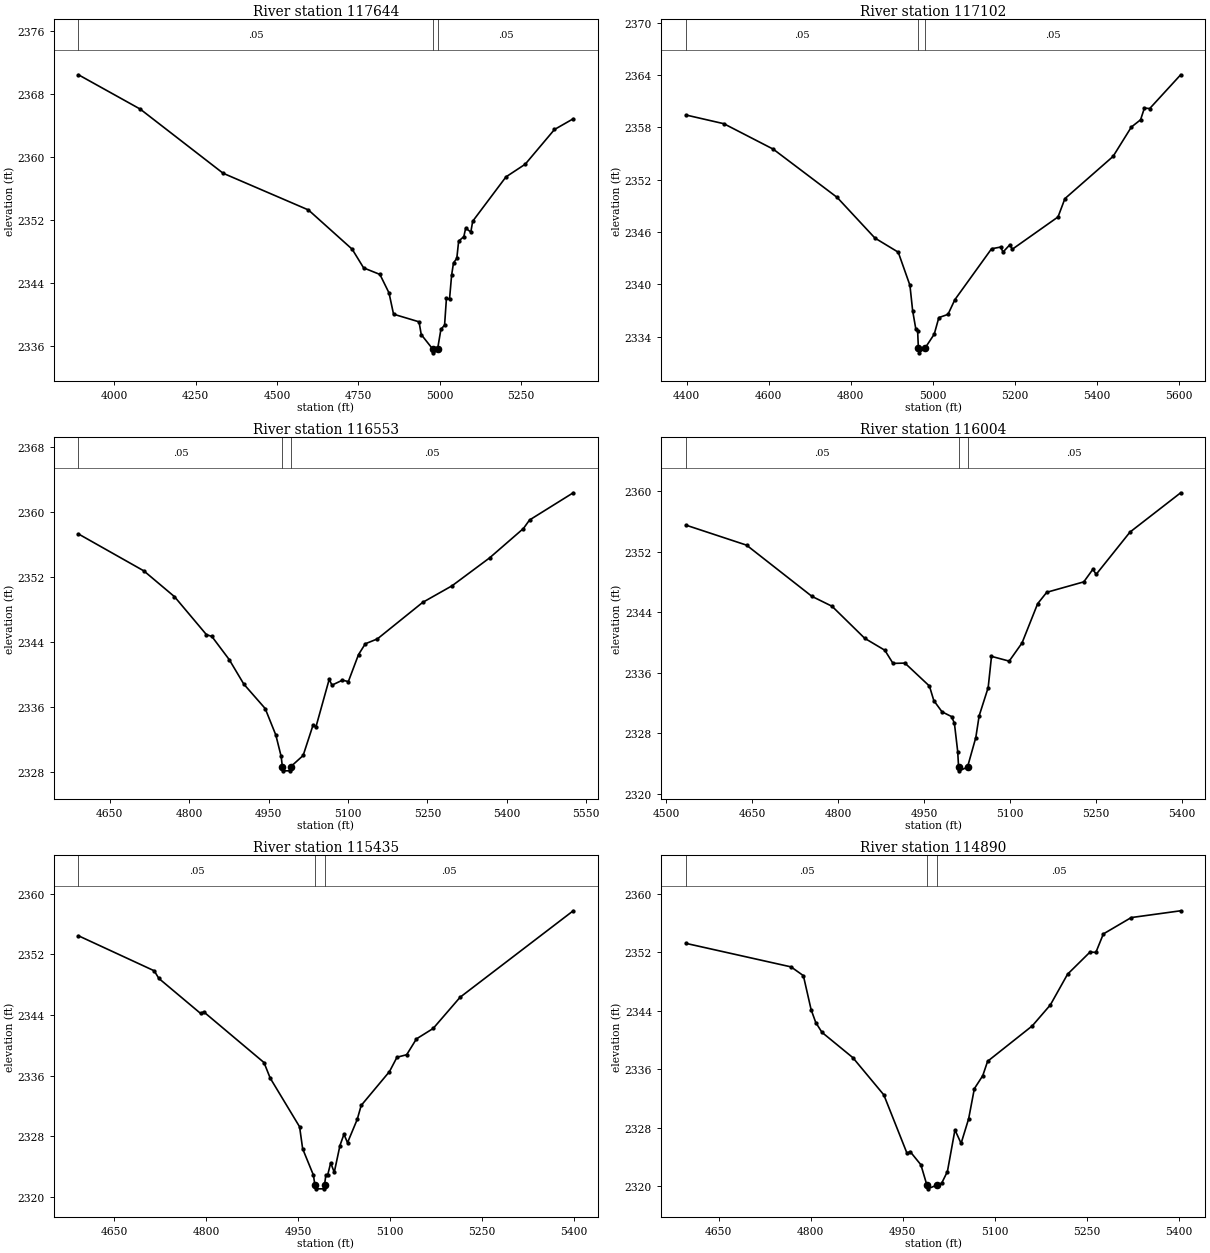
Type RM Length L Ch R = 1,117644,542,542,542
BEGIN DESCRIPTION:
Buffalo Creek 148.0
END DESCRIPTION:
XS GIS Cut Line= 3
      1291500.29      6909861.20      1292255.00      6909038.00
      1292454.99      6908688.02
#Sta/Elev= 30
  3890.4 2370.47  4080.1 2366.11  4334.8 2357.96  4596.8 2353.30  4731.3 2348.31
  4766.4 2345.94  4816.4 2345.11  4844.4 2342.76  4858.3 2340.06  4936.6 2339.09
  4943.4 2337.47  4978.2 2335.65  4979.7 2335.15  4993.7 2335.65  5003.8 2338.13
  5015.1 2338.68  5020.9 2342.14  5030.2 2341.93  5036.7 2345.02  5042.5 2346.58
  5052.6 2347.14  5058.3 2349.34  5074.2 2349.91  5079.9 2350.99  5095.7 2350.49
  5101.5 2351.87  5203.7 2357.50  5262.8 2359.11  5352.7 2363.52  5410.3 2364.88
#Mann=3,-1,0
  3890.4    0.05       0  4978.2    0.05       0  4993.7    0.05       0
Bank Sta=4978.2,4993.7
Exp/Cntr=0.3,0.1

Type RM Length L Ch R = 1,117102,549,549,549
BEGIN DESCRIPTION:
Buffalo Creek 147.0
END DESCRIPTION:
XS GIS Cut Line= 3
      1292104.99      6909938.02      1292505.00      6909488.00
      1292775.50      6908948.96
#Sta/Elev= 30
  4398.4 2359.40  4490.8 2358.40  4611.2 2355.48  4766.8 2349.95  4858.8 2345.29
  4915.6 2343.67  4944.1 2339.87  4950.7 2336.96  4958.3 2334.90  4962.9 2334.60
  4964.7 2332.63  4966.2 2332.13  4980.3 2332.63  5003.3 2334.27  5014.5 2336.17
  5036.8 2336.54  5053.5 2338.22  5142.9 2344.06  5165.2 2344.26  5170.8 2343.68
  5187.6 2344.53  5193.2 2344.00  5304.8 2347.71  5321.6 2349.81  5438.9 2354.65
  5483.5 2358.02  5505.9 2358.85  5515.2 2360.19  5528.2 2360.14  5603.6 2364.01
#Mann=3,-1,0
  4398.4    0.05       0  4964.7    0.05       0  4980.3    0.05       0
Bank Sta=4964.7,4980.3
Exp/Cntr=0.3,0.1

Type RM Length L Ch R = 1,116553,549,549,549
BEGIN DESCRIPTION:
Buffalo Creek 146.0
END DESCRIPTION:
XS GIS Cut Line= 3
      1292255.05      6909937.99      1292655.00      6909888.00
      1293153.19      6909702.71
#Sta/Elev= 30
  4591.0 2357.25  4714.4 2352.71  4772.4 2349.53  4832.8 2344.85  4842.9 2344.64
  4875.7 2341.79  4903.4 2338.76  4943.7 2335.76  4963.8 2332.50  4973.9 2329.86
  4976.2 2328.59  4977.7 2328.09  4990.3 2328.09  4991.8 2328.59  5015.4 2329.98
  5034.3 2333.76  5039.6 2333.50  5064.6 2339.35  5069.9 2338.64  5089.6 2339.25
  5100.8 2339.08  5120.0 2342.40  5132.8 2343.73  5155.6 2344.33  5241.3 2348.83
  5296.7 2350.87  5367.5 2354.30  5431.5 2357.92  5443.1 2358.97  5525.6 2362.32
#Mann=3,-1,0
  4591.0    0.05       0  4976.2    0.05       0  4991.8    0.05       0
Bank Sta=4976.2,4991.8
Exp/Cntr=0.3,0.1

Type RM Length L Ch R = 1,116004,569,569,569
BEGIN DESCRIPTION:
Buffalo Creek 145.0
END DESCRIPTION:
XS GIS Cut Line= 3
      1292654.99      6910488.01      1293005.00      6910188.00
      1293205.00      6909838.00
#Sta/Elev= 30
  4534.3 2355.53  4640.2 2352.88  4754.4 2346.10  4789.5 2344.79  4846.6 2340.55
  4881.7 2338.97  4896.0 2337.23  4916.8 2337.27  4959.6 2334.23  4967.3 2332.30
  4981.6 2330.82  4998.2 2330.19  5003.2 2329.32  5009.0 2325.55  5010.5 2323.51
  5012.0 2323.01  5026.1 2323.51  5040.6 2327.42  5046.4 2330.28  5062.2 2334.03
  5068.0 2338.16  5098.9 2337.53  5121.3 2339.93  5148.6 2345.13  5164.5 2346.64
  5229.2 2348.02  5245.1 2349.69  5250.8 2349.01  5309.9 2354.61  5398.4 2359.81
#Mann=3,-1,0
  4534.3    0.05       0  5010.5   0.033       0  5026.1    0.05       0
Bank Sta=5010.5,5026.1
Exp/Cntr=0.3,0.1

Type RM Length L Ch R = 1,115435,545,545,545
BEGIN DESCRIPTION:
Buffalo Creek 144.0
END DESCRIPTION:
XS GIS Cut Line= 3
      1292755.02      6910738.00      1293155.00      6910688.00
      1293505.00      6910488.00
#Sta/Elev= 30
  4592.3 2354.47  4715.7 2349.85  4723.3 2348.84  4791.3 2344.22  4796.4 2344.43
  4894.6 2337.74  4904.7 2335.69  4952.6 2329.26  4957.6 2326.36  4975.2 2322.87
  4977.5 2321.57  4979.0 2321.07  4991.7 2321.07  4993.2 2321.57  4995.4 2322.87
  4998.3 2322.87  5003.3 2324.50  5009.1 2323.25  5018.4 2326.79  5024.9 2328.27
  5030.7 2327.16  5046.5 2330.23  5053.0 2332.08  5099.1 2336.55  5111.3 2338.44
  5127.1 2338.77  5143.0 2340.86  5170.3 2342.24  5214.2 2346.36  5398.5 2357.77
#Mann=3,-1,0
  4592.3    0.05       0  4977.5   0.033       0  4993.2    0.05       0
Bank Sta=4977.5,4993.2
Exp/Cntr=0.3,0.1

Type RM Length L Ch R = 1,114890,602,602,602
BEGIN DESCRIPTION:
Buffalo Creek 143.0
END DESCRIPTION:
XS GIS Cut Line= 3
      1293055.03      6911138.00      1293455.00      6911088.00
      1293805.01      6910888.00
#Sta/Elev= 30
  4596.7 2353.24  4768.0 2350.02  4788.1 2348.82  4800.7 2344.17  4808.3 2342.40
  4818.4 2341.06  4868.8 2337.59  4919.2 2332.50  4957.0 2324.50  4962.0 2324.75
  4979.6 2322.93  4989.4 2320.14  4990.9 2319.64  5005.1 2320.14  5013.5 2320.42
  5022.8 2322.01  5035.1 2327.71  5045.1 2325.86  5057.4 2329.23  5066.7 2333.35
  5080.4 2335.13  5088.3 2337.10  5161.0 2341.94  5190.5 2344.81  5218.6 2349.02
  5255.3 2352.06  5264.7 2352.00  5276.9 2354.53  5322.3 2356.77  5402.9 2357.70
#Mann=3,-1,0
  4596.7    0.05       0  4989.4   0.033       0  5005.1    0.05       0
Bank Sta=4989.4,5005.1
Exp/Cntr=0.3,0.1

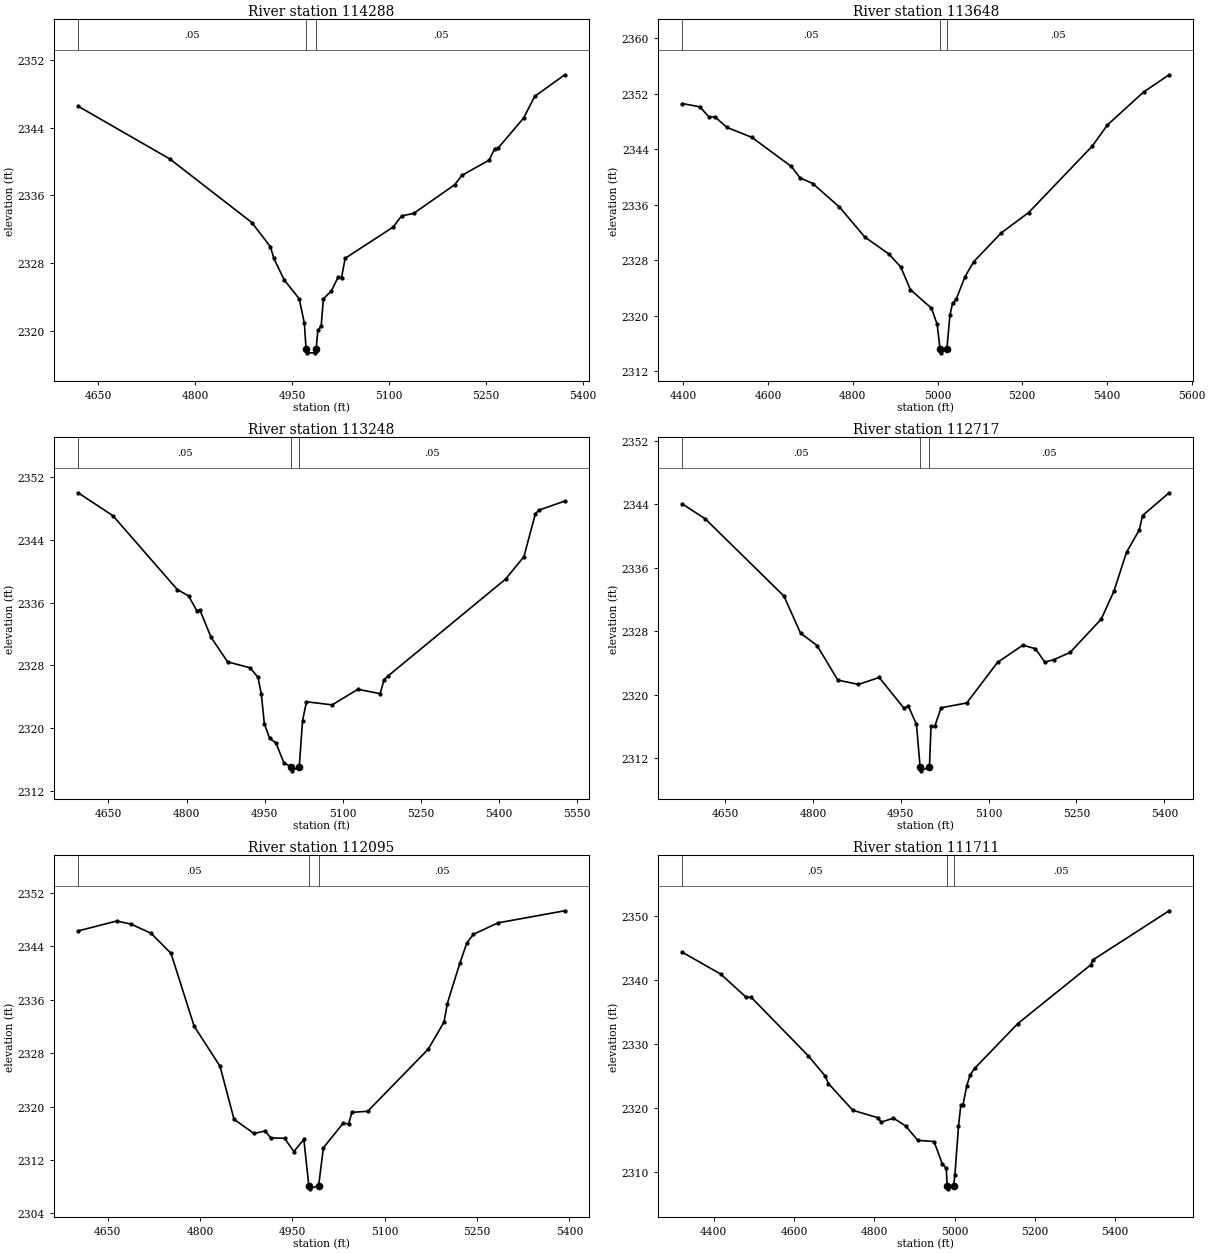
Type RM Length L Ch R = 1,114288,640,640,640
BEGIN DESCRIPTION:
Buffalo Creek 142.0
END DESCRIPTION:
XS GIS Cut Line= 3
      1293388.42      6911665.28      1293756.45      6911561.11
      1294104.96      6911438.01
#Sta/Elev= 30
  4619.3 2346.52  4761.2 2340.28  4887.9 2332.77  4916.7 2329.90  4921.9 2328.54
  4937.9 2325.99  4961.0 2323.78  4969.1 2320.86  4971.6 2317.88  4973.1 2317.38
  4985.9 2317.38  4987.4 2317.88  4989.8 2320.02  4995.0 2320.54  4998.4 2323.76
  5010.9 2324.70  5021.2 2326.33  5026.5 2326.28  5032.1 2328.55  5106.3 2332.24
  5119.2 2333.55  5138.1 2333.86  5201.4 2337.24  5212.4 2338.34  5254.8 2340.16
  5263.2 2341.52  5268.5 2341.57  5307.8 2345.11  5325.1 2347.68  5371.4 2350.23
#Mann=3,-1,0
  4619.3    0.05       0  4971.6    0.05       0  4987.4    0.05       0
Bank Sta=4971.6,4987.4
Exp/Cntr=0.3,0.1

Type RM Length L Ch R = 1,113648,400,400,400
BEGIN DESCRIPTION:
Buffalo Creek 141.0
END DESCRIPTION:
XS GIS Cut Line= 3
      1293518.55      6912337.84      1294030.41      6911990.59
      1294344.94      6911563.55
#Sta/Elev= 30
  4397.9 2350.55  4439.0 2350.08  4460.0 2348.65  4475.0 2348.63  4502.4 2347.13
  4561.8 2345.68  4654.7 2341.49  4675.6 2339.85  4705.5 2339.03  4768.5 2335.64
  4828.3 2331.32  4885.2 2328.87  4913.2 2327.01  4936.1 2323.73  4985.7 2321.06
  4999.1 2318.75  5006.1 2315.13  5007.6 2314.63  5022.0 2315.13  5029.2 2320.02
  5035.4 2321.75  5043.9 2322.32  5064.7 2325.58  5085.6 2327.77  5150.3 2331.91
  5215.1 2334.84  5365.5 2344.43  5401.0 2347.46  5486.6 2352.22  5546.8 2354.70
#Mann=3,-1,0
  4397.9    0.05       0  5006.1    0.05       0  5022.0    0.05       0
Bank Sta=5006.1,5022
Exp/Cntr=0.3,0.1

Type RM Length L Ch R = 1,113248,531,531,531
BEGIN DESCRIPTION:
Buffalo Creek 140.0
END DESCRIPTION:
XS GIS Cut Line= 3
      1293855.04      6912537.98      1294205.00      6912338.00
      1294555.01      6911937.98
#Sta/Elev= 30
  4591.7 2350.00  4658.6 2347.08  4782.4 2337.65  4804.0 2336.85  4819.8 2334.95
  4825.6 2335.06  4847.2 2331.56  4878.9 2328.44  4922.1 2327.68  4937.2 2326.47
  4943.7 2324.31  4949.4 2320.57  4959.5 2318.69  4971.7 2318.10  4986.9 2315.58
  5000.6 2315.04  5002.1 2314.54  5016.5 2315.04  5022.8 2320.92  5030.4 2323.35
  5079.7 2322.95  5129.1 2324.94  5171.8 2324.38  5179.4 2326.17  5186.0 2326.58
  5412.9 2339.00  5448.0 2341.86  5469.8 2347.28  5476.4 2347.78  5526.3 2348.94
#Mann=3,-1,0
  4591.7    0.05       0  5000.6   0.033       0  5016.5    0.05       0
Bank Sta=5000.6,5016.5
Exp/Cntr=0.3,0.1

Type RM Length L Ch R = 1,112717,622,622,622
BEGIN DESCRIPTION:
Buffalo Creek 139.0
END DESCRIPTION:
XS GIS Cut Line= 3
      1294202.60      6912990.60      1294505.00      6912688.00
      1294854.99      6912488.01
#Sta/Elev= 30
  4577.3 2344.05  4616.2 2342.18  4750.5 2332.45  4778.8 2327.78  4807.1 2326.21
  4842.5 2321.85  4877.8 2321.31  4913.2 2322.18  4955.6 2318.29  4962.7 2318.62
  4976.8 2316.26  4983.0 2310.91  4984.5 2310.41  4999.0 2310.91  5001.6 2316.01
  5008.0 2316.01  5018.8 2318.36  5062.7 2318.97  5115.2 2324.09  5158.4 2326.25
  5180.0 2325.81  5195.9 2324.12  5211.7 2324.44  5239.1 2325.34  5292.3 2329.54
  5313.9 2333.05  5335.5 2337.98  5357.1 2340.76  5362.9 2342.60  5408.2 2345.47
#Mann=3,-1,0
  4577.3    0.05       0  4983.0   0.033       0  4999.0    0.05       0
Bank Sta=4983,4999
Exp/Cntr=0.3,0.1

Type RM Length L Ch R = 1,112095,384,384,384
BEGIN DESCRIPTION:
Buffalo Creek 138.0
END DESCRIPTION:
XS GIS Cut Line= 3
      1294355.04      6913187.99      1294717.91      6913073.93
      1295104.97      6912938.01
#Sta/Elev= 30
  4601.9 2346.30  4664.8 2347.79  4688.1 2347.32  4720.5 2345.95  4752.9 2342.94
  4790.5 2332.04  4832.5 2326.04  4855.3 2318.09  4887.7 2315.97  4905.8 2316.35
  4914.9 2315.31  4937.3 2315.25  4952.5 2313.27  4968.7 2315.08  4976.8 2308.18
  4978.3 2307.68  4992.8 2308.18  5000.4 2313.82  5032.2 2317.47  5041.5 2317.42
  5046.8 2319.14  5072.4 2319.29  5170.7 2328.59  5196.4 2332.65  5201.8 2335.43
  5222.1 2341.46  5233.6 2344.52  5244.2 2345.79  5284.1 2347.51  5392.5 2349.32
#Mann=3,-1,0
  4601.9    0.05       0  4976.8    0.05       0  4992.8    0.05       0
Bank Sta=4976.8,4992.8
Exp/Cntr=0.3,0.1

Type RM Length L Ch R = 1,111711,624,624,624
BEGIN DESCRIPTION:
Buffalo Creek 137.0
END DESCRIPTION:
XS GIS Cut Line= 3
      1294285.95      6913417.69      1294971.38      6913310.04
      1295470.65      6913171.35
#Sta/Elev= 30
  4322.5 2344.34  4417.4 2340.95  4480.0 2337.38  4493.6 2337.31  4635.3 2328.19
  4677.9 2325.00  4685.9 2323.82  4746.7 2319.64  4808.2 2318.49  4817.5 2317.79
  4847.9 2318.40  4878.3 2317.19  4908.6 2314.93  4949.1 2314.75  4969.4 2311.26
  4979.5 2310.57  4981.6 2307.85  4983.1 2307.35  4997.6 2307.85  5001.0 2309.55
  5009.9 2317.12  5015.6 2320.39  5020.8 2320.39  5030.5 2323.46  5039.1 2325.22
  5051.2 2326.26  5157.5 2333.19  5339.1 2342.37  5344.3 2343.14  5534.5 2350.84
#Mann=3,-1,0
  4322.5    0.05       0  4981.6    0.05       0  4997.6    0.05       0
Bank Sta=4981.6,4997.6
Exp/Cntr=0.3,0.1

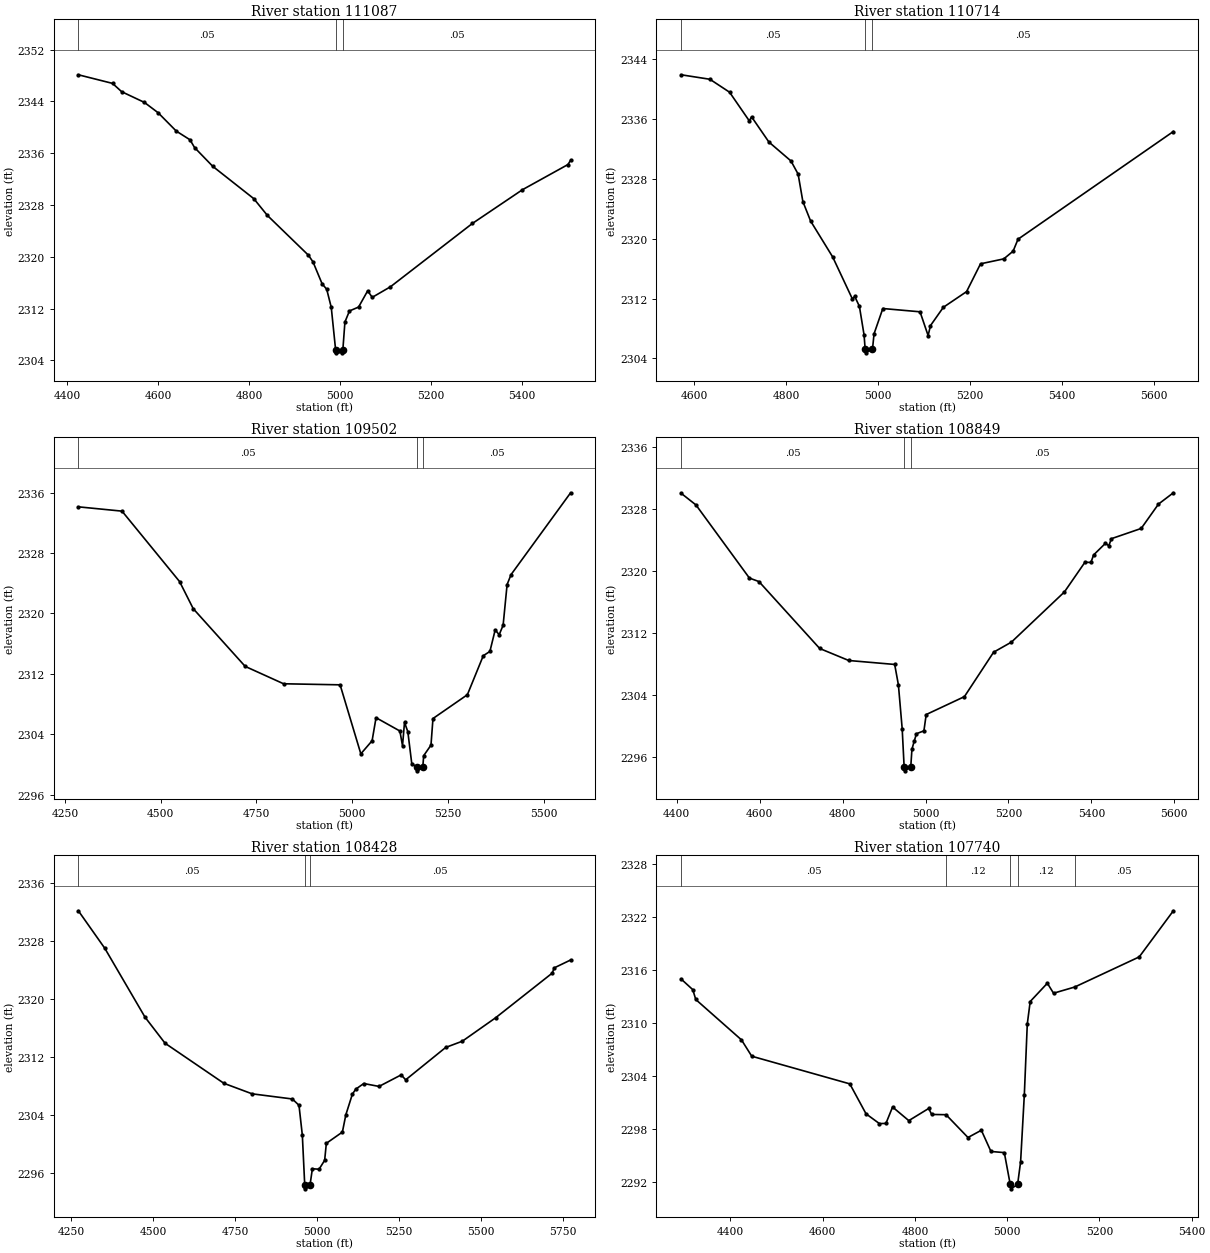
Type RM Length L Ch R = 1,111087,373,373,373
BEGIN DESCRIPTION:
Buffalo Creek 136.0
END DESCRIPTION:
XS GIS Cut Line= 3
      1294179.96      6913813.00      1294755.00      6913838.00
      1295260.81      6913841.30
#Sta/Elev= 30
  4424.8 2348.10  4499.9 2346.77  4519.9 2345.49  4570.0 2343.83  4600.0 2342.24
  4640.0 2339.40  4670.1 2338.06  4680.1 2336.86  4720.1 2333.96  4810.2 2328.97
  4840.2 2326.37  4930.3 2320.23  4940.3 2319.20  4960.3 2315.82  4970.4 2314.98
  4980.4 2312.18  4989.9 2305.66  4991.4 2305.16  5004.4 2305.16  5005.9 2305.66
  5010.4 2309.92  5020.4 2311.63  5040.4 2312.23  5060.4 2314.74  5070.4 2313.73
  5110.4 2315.36  5290.4 2325.14  5400.4 2330.35  5500.4 2334.24  5506.2 2334.90
#Mann=3,-1,0
  4424.8    0.05       0  4989.9    0.05       0  5005.9    0.05       0
Bank Sta=4989.9,5005.9
Exp/Cntr=0.3,0.1

Type RM Length L Ch R = 1,110714,1212,1212,1212
BEGIN DESCRIPTION:
Buffalo Creek 135.5
END DESCRIPTION:
XS GIS Cut Line= 3
      1294336.68      6914119.49      1294742.42      6914212.70
      1295389.48      6914108.51
#Sta/Elev= 30
  4571.0 2341.95  4633.7 2341.35  4676.5 2339.62  4719.4 2335.79  4724.5 2336.32
  4762.2 2332.95  4810.2 2330.42  4825.8 2328.66  4836.1 2324.99  4853.0 2322.38
  4901.0 2317.58  4943.9 2311.96  4949.0 2312.30  4959.2 2310.97  4969.4 2307.13
  4971.7 2305.25  4973.2 2304.75  4987.7 2305.25  4991.1 2307.30  5010.2 2310.68
  5091.2 2310.24  5108.8 2307.06  5113.9 2308.39  5141.9 2310.84  5192.5 2312.94
  5222.9 2316.66  5273.5 2317.32  5293.8 2318.35  5304.5 2319.95  5642.7 2334.36
#Mann=3,-1,0
  4571.0    0.05       0  4971.7    0.05       0  4987.7    0.05       0
Bank Sta=4971.7,4987.7
Exp/Cntr=0.3,0.1

Type RM Length L Ch R = 1,109502,653,653,653
BEGIN DESCRIPTION:
Buffalo Creek 135.0
END DESCRIPTION:
XS GIS Cut Line= 4
      1294318.62      6914435.06      1294830.00      6914813.00
      1294905.00      6914788.00      1295454.97      6914638.01
#Sta/Elev= 30
  4285.0 2334.11  4399.0 2333.54  4549.3 2324.22  4584.8 2320.64  4720.5 2313.00
  4820.7 2310.70  4968.3 2310.56  5022.4 2301.43  5051.8 2303.16  5062.1 2306.21
  5124.3 2304.45  5131.2 2302.50  5136.4 2305.59  5145.1 2304.35  5155.4 2300.11
  5168.1 2299.68  5169.6 2299.18  5184.1 2299.68  5186.5 2301.19  5205.5 2302.58
  5210.7 2306.10  5300.5 2309.25  5342.0 2314.41  5359.3 2314.98  5373.1 2317.83
  5383.5 2317.19  5393.8 2318.44  5404.2 2323.83  5414.6 2325.15  5570.0 2335.97
#Mann=3,-1,0
  4285.0    0.05       0  5168.1    0.05       0  5184.1    0.05       0
Bank Sta=5168.1,5184.1
Exp/Cntr=0.3,0.1

Type RM Length L Ch R = 1,108849,421,421,421
BEGIN DESCRIPTION:
Buffalo Creek 134.0
END DESCRIPTION:
XS GIS Cut Line= 3
      1294463.73      6915555.81      1295074.91      6915291.95
      1295405.02      6914887.98
#Sta/Elev= 30
  4410.4 2330.01  4446.3 2328.50  4575.2 2319.07  4598.2 2318.62  4744.7 2309.99
  4814.8 2308.44  4925.6 2307.93  4934.6 2305.29  4943.7 2299.64  4948.4 2294.71
  4949.9 2294.21  4964.4 2294.71  4967.2 2296.99  4972.6 2298.02  4978.2 2299.00
  4996.1 2299.37  5001.6 2301.47  5093.8 2303.78  5164.2 2309.51  5207.2 2310.81
  5335.0 2317.28  5384.6 2321.12  5398.9 2321.08  5405.4 2322.05  5434.1 2323.56
  5442.0 2323.23  5448.4 2324.15  5520.2 2325.47  5561.9 2328.61  5597.8 2330.07
#Mann=3,-1,0
  4410.4    0.05       0  4948.4    0.05       0  4964.4    0.05       0
Bank Sta=4948.4,4964.4
Exp/Cntr=0.3,0.1

Type RM Length L Ch R = 1,108428,688,688,688
BEGIN DESCRIPTION:
Buffalo Creek 133.0
END DESCRIPTION:
XS GIS Cut Line= 3
      1294446.02      6915830.54      1295155.00      6915688.00
      1295919.97      6915554.50
#Sta/Elev= 30
  4272.9 2332.19  4353.5 2327.02  4475.9 2317.54  4537.1 2313.94  4716.3 2308.42
  4802.3 2306.97  4924.9 2306.26  4945.1 2305.39  4955.3 2301.27  4962.6 2294.38
  4964.1 2293.88  4978.6 2294.38  4985.9 2296.65  5006.2 2296.58  5023.3 2297.81
  5028.4 2300.15  5077.3 2301.70  5087.9 2304.09  5107.7 2306.92  5117.9 2307.61
  5142.4 2308.39  5188.9 2307.99  5256.4 2309.58  5270.1 2308.90  5392.0 2313.36
  5442.7 2314.22  5543.9 2317.44  5716.8 2323.61  5722.5 2324.32  5772.6 2325.41
#Mann=3,-1,0
  4272.9    0.05       0  4962.6    0.05       0  4978.6    0.05       0
Bank Sta=4962.6,4978.6
Exp/Cntr=0.3,0.1

Type RM Length L Ch R = 1,107740,953,953,953
BEGIN DESCRIPTION:
Mapping XS 453d3822
END DESCRIPTION:
XS GIS Cut Line= 3
      1295210.96      6916448.93      1295540.82      6916042.68
      1295873.84      6915612.53
#Sta/Elev= 30
  4292.9 2314.96  4318.3 2313.75  4324.7 2312.64  4423.8 2308.07  4446.1 2306.22
  4658.7 2303.09  4693.9 2299.70  4722.7 2298.60  4737.0 2298.61  4751.4 2300.47
  4786.6 2298.93  4829.8 2300.31  4836.1 2299.63  4867.3 2299.60  4914.9 2297.02
  4943.9 2297.84  4964.7 2295.44  4993.7 2295.31  5006.5 2291.71  5008.0 2291.21
  5022.5 2291.71  5029.0 2294.27  5037.1 2301.88  5043.5 2309.87  5049.8 2312.41
  5087.0 2314.48  5100.4 2313.35  5146.3 2314.05  5286.2 2317.46  5360.2 2322.68
#Mann=5,-1,0
  4292.9    0.05       0  4867.3    0.12       0  5006.5    0.07       0
  5022.5    0.12       0  5146.3    0.05       0
Bank Sta=5006.5,5022.5
Exp/Cntr=0.3,0.1

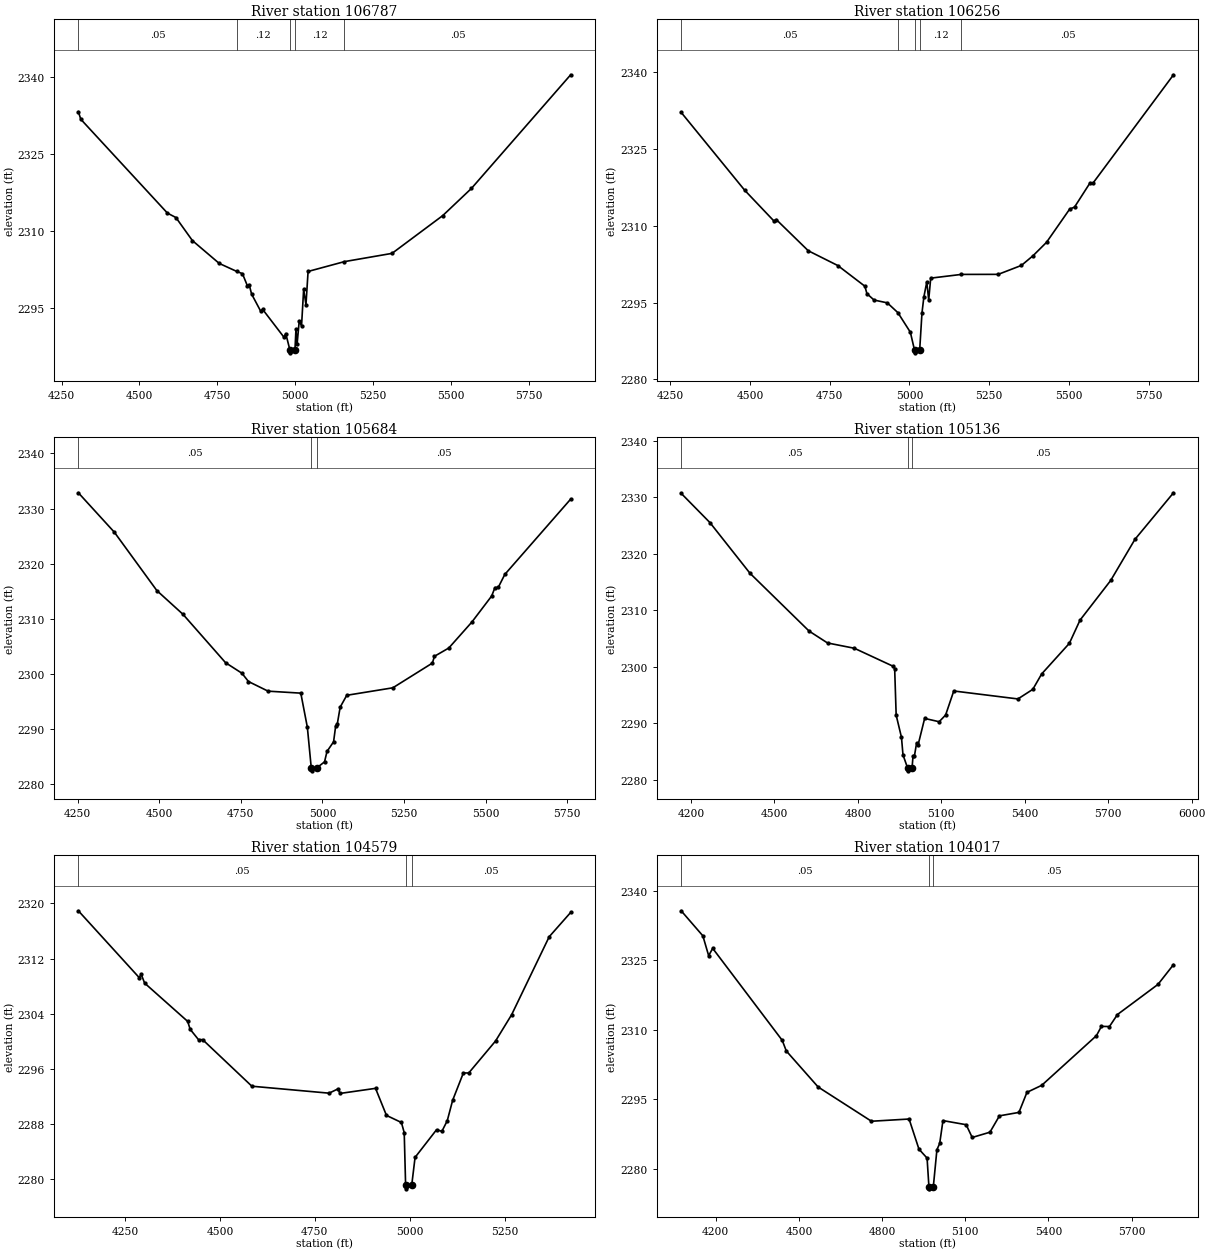
Type RM Length L Ch R = 1,106787,531,531,531
BEGIN DESCRIPTION:
Buffalo Creek 131.0
END DESCRIPTION:
XS GIS Cut Line= 3
      1295504.99      6916888.01      1295855.00      6916288.00
      1296504.98      6915688.02
#Sta/Elev= 30
  4303.9 2333.27  4311.8 2331.80  4589.6 2313.49  4616.9 2312.62  4669.8 2308.12
  4755.8 2303.67  4812.2 2302.10  4830.3 2301.67  4846.0 2299.32  4851.8 2299.54
  4859.6 2297.69  4889.0 2294.32  4894.8 2294.72  4963.4 2289.27  4969.2 2289.98
  4982.7 2286.72  4984.2 2286.22  4998.7 2286.72  5001.9 2290.84  5005.6 2287.93
  5012.4 2292.45  5019.8 2291.47  5026.6 2298.63  5034.0 2295.61  5040.8 2302.10
  5157.4 2304.02  5310.1 2305.63  5472.9 2313.01  5564.7 2318.30  5883.1 2340.48
#Mann=5,-1,0
  4303.9    0.05       0  4812.2    0.12       0  4982.7    0.07       0
  4998.7    0.12       0  5157.4    0.05       0
Bank Sta=4982.7,4998.7
Exp/Cntr=0.3,0.1

Type RM Length L Ch R = 1,106256,572,572,572
BEGIN DESCRIPTION:
Buffalo Creek 130.0
END DESCRIPTION:
XS GIS Cut Line= 3
      1295705.00      6917038.00      1296255.00      6916588.00
      1296705.00      6915888.00
#Sta/Elev= 30
  4284.6 2332.18  4483.4 2316.98  4576.0 2310.90  4582.5 2311.24  4683.0 2305.13
  4775.6 2302.24  4860.3 2298.20  4866.7 2296.75  4889.0 2295.50  4930.6 2294.95
  4963.8 2293.03  5002.8 2289.21  5016.0 2285.68  5017.5 2285.18  5032.0 2285.68
  5039.2 2292.96  5045.1 2296.08  5054.3 2299.04  5060.3 2295.52  5066.6 2299.78
  5162.8 2300.51  5278.2 2300.52  5350.9 2302.27  5387.2 2304.16  5429.5 2306.78
  5502.1 2313.28  5517.3 2313.67  5565.9 2318.40  5574.8 2318.33  5827.4 2339.53
#Mann=5,-1,0
  4284.6    0.05       0  4963.8    0.12       0  5016.0    0.07       0
  5032.0    0.12       0  5162.8    0.05       0
Bank Sta=5016,5032
Exp/Cntr=0.3,0.1

Type RM Length L Ch R = 1,105684,548,548,548
BEGIN DESCRIPTION:
Buffalo Creek 129.0
END DESCRIPTION:
XS GIS Cut Line= 3
      1295704.99      6917088.00      1296455.00      6917038.00
      1297204.98      6916938.00
#Sta/Elev= 30
  4252.2 2332.86  4362.5 2325.70  4492.7 2315.10  4572.9 2310.78  4703.2 2302.00
  4753.3 2300.09  4773.4 2298.58  4833.5 2296.83  4933.7 2296.47  4953.8 2290.27
  4965.8 2282.86  4967.3 2282.36  4981.8 2282.86  5006.4 2283.99  5014.0 2285.89
  5034.1 2287.63  5040.4 2290.44  5045.5 2290.87  5054.3 2293.92  5074.5 2296.08
  5215.7 2297.44  5336.8 2301.93  5343.1 2303.16  5387.2 2304.67  5457.9 2309.39
  5518.4 2314.11  5528.5 2315.64  5538.6 2315.67  5558.7 2318.03  5760.5 2331.71
#Mann=3,-1,0
  4252.2    0.05       0  4965.8    0.05       0  4981.8    0.05       0
Bank Sta=4965.8,4981.8
Exp/Cntr=0.3,0.1

Type RM Length L Ch R = 1,105136,557,557,557
BEGIN DESCRIPTION:
Buffalo Creek 128.0
END DESCRIPTION:
XS GIS Cut Line= 4
      1295674.46      6917790.75      1296453.49      6917488.50
      1296507.77      6917365.41      1297261.52      6917096.83
#Sta/Elev= 30
  4164.4 2330.71  4267.8 2325.53  4412.0 2316.54  4624.5 2306.30  4690.6 2304.20
  4787.1 2303.26  4926.5 2300.07  4932.1 2299.67  4937.5 2291.41  4956.6 2287.47
  4962.0 2284.38  4978.6 2282.04  4980.1 2281.54  4994.6 2282.04  4998.1 2284.12
  5003.0 2284.12  5011.1 2286.52  5016.5 2286.16  5039.9 2290.83  5092.0 2290.24
  5115.3 2291.43  5144.6 2295.69  5375.3 2294.28  5428.8 2295.98  5460.7 2298.71
  5560.2 2304.13  5598.7 2308.25  5709.0 2315.28  5796.1 2322.56  5934.7 2330.81
#Mann=3,-1,0
  4164.4    0.05       0  4978.6    0.05       0  4994.6    0.05       0
Bank Sta=4978.6,4994.6
Exp/Cntr=0.3,0.1

Type RM Length L Ch R = 1,104579,562,562,562
BEGIN DESCRIPTION:
Buffalo Creek 127.0
END DESCRIPTION:
XS GIS Cut Line= 3
      1296504.99      6918488.02      1296855.00      6917688.00
      1297155.00      6917388.00
#Sta/Elev= 30
  4126.8 2318.94  4287.0 2309.24  4292.5 2309.70  4301.5 2308.43  4414.9 2302.87
  4421.5 2301.72  4443.7 2300.20  4454.3 2300.22  4584.1 2293.45  4787.6 2292.44
  4811.0 2293.06  4816.4 2292.40  4910.0 2293.14  4938.8 2289.21  4978.2 2288.18
  4985.6 2286.71  4989.3 2279.04  4990.8 2278.54  5005.3 2279.04  5014.2 2283.11
  5070.7 2287.12  5084.9 2286.90  5099.0 2288.43  5113.2 2291.40  5141.5 2295.38
  5155.6 2295.37  5226.3 2300.02  5268.7 2303.84  5367.7 2315.17  5424.3 2318.70
#Mann=3,-1,0
  4126.8    0.05       0  4989.3    0.05       0  5005.3    0.05       0
Bank Sta=4989.3,5005.3
Exp/Cntr=0.3,0.1

Type RM Length L Ch R = 1,104017,553,553,553
BEGIN DESCRIPTION:
Buffalo Creek 126.0
END DESCRIPTION:
XS GIS Cut Line= 3
      1296605.03      6918787.96      1297155.00      6918038.00
      1297492.64      6917262.09
#Sta/Elev= 30
  4075.3 2335.75  4153.6 2330.33  4174.5 2326.04  4189.1 2327.62  4440.0 2307.72
  4454.6 2305.43  4569.6 2297.63  4761.8 2290.23  4897.6 2290.71  4933.2 2284.19
  4962.5 2282.26  4969.1 2276.11  4970.6 2275.61  4985.1 2276.11  4998.0 2284.08
  5008.0 2285.42  5019.8 2290.37  5103.5 2289.48  5125.3 2286.72  5189.3 2287.86
  5223.6 2291.40  5293.9 2292.14  5322.8 2296.48  5376.1 2298.00  5573.5 2308.74
  5591.5 2310.75  5620.4 2310.71  5649.3 2313.31  5795.4 2319.82  5851.5 2324.10
#Mann=3,-1,0
  4075.3    0.05       0  4969.1    0.05       0  4985.1    0.05       0
Bank Sta=4969.1,4985.1
Exp/Cntr=0.3,0.1