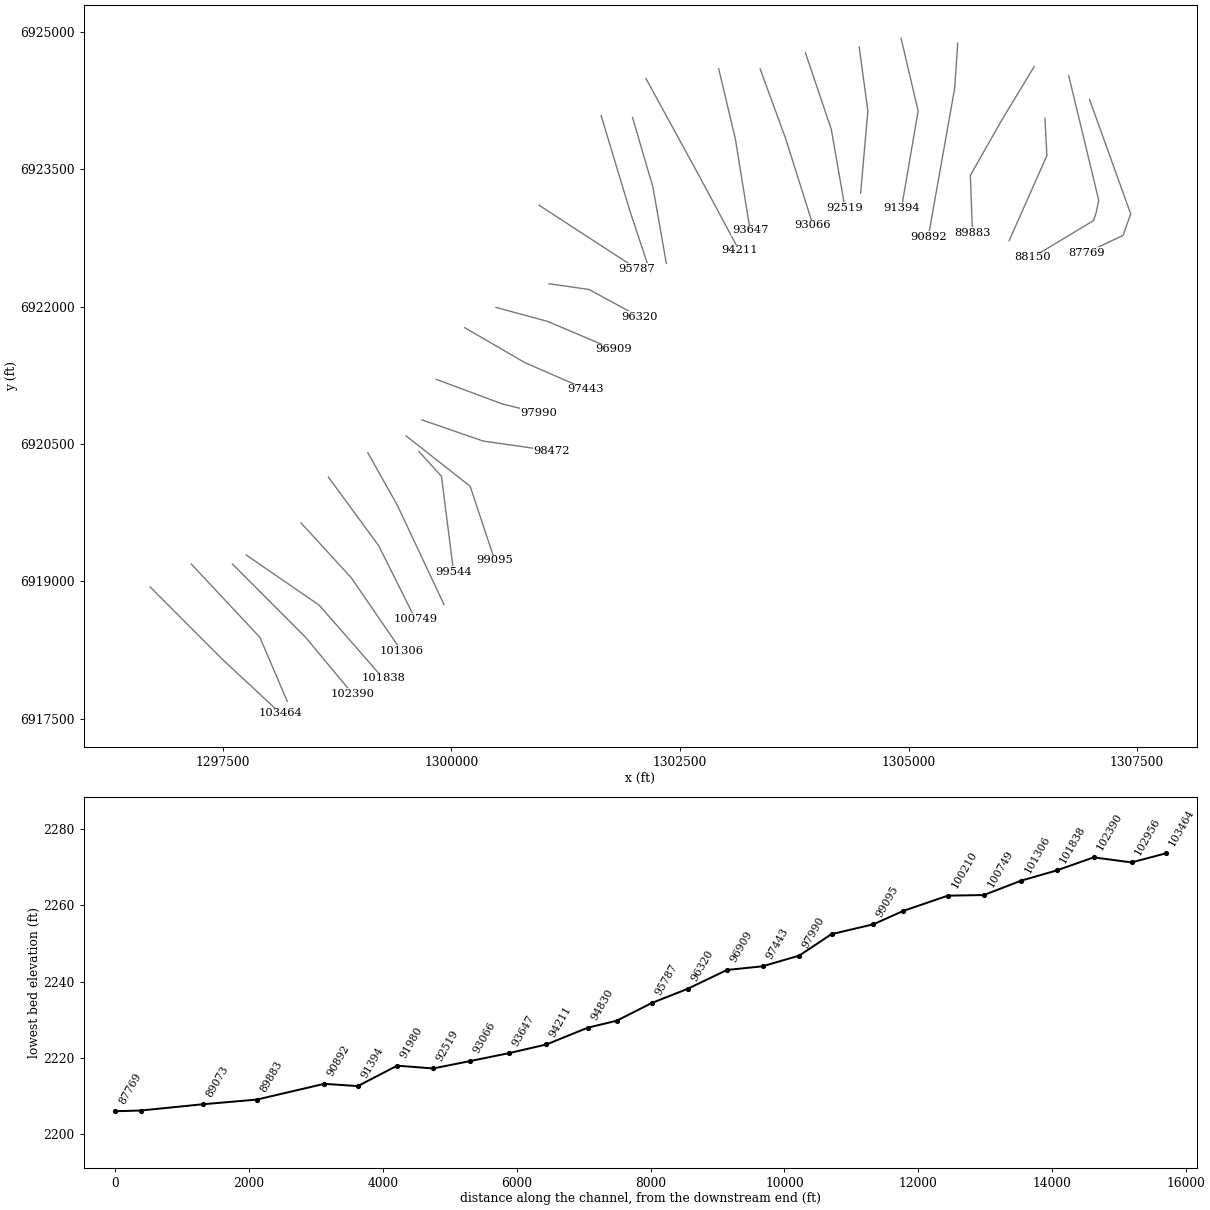
HEC-RAS study Buffalo Creek.prj: Buffalo Creek Base Level Engineering

--- Buffalo Creek.g01 (geometry) --- (continued)

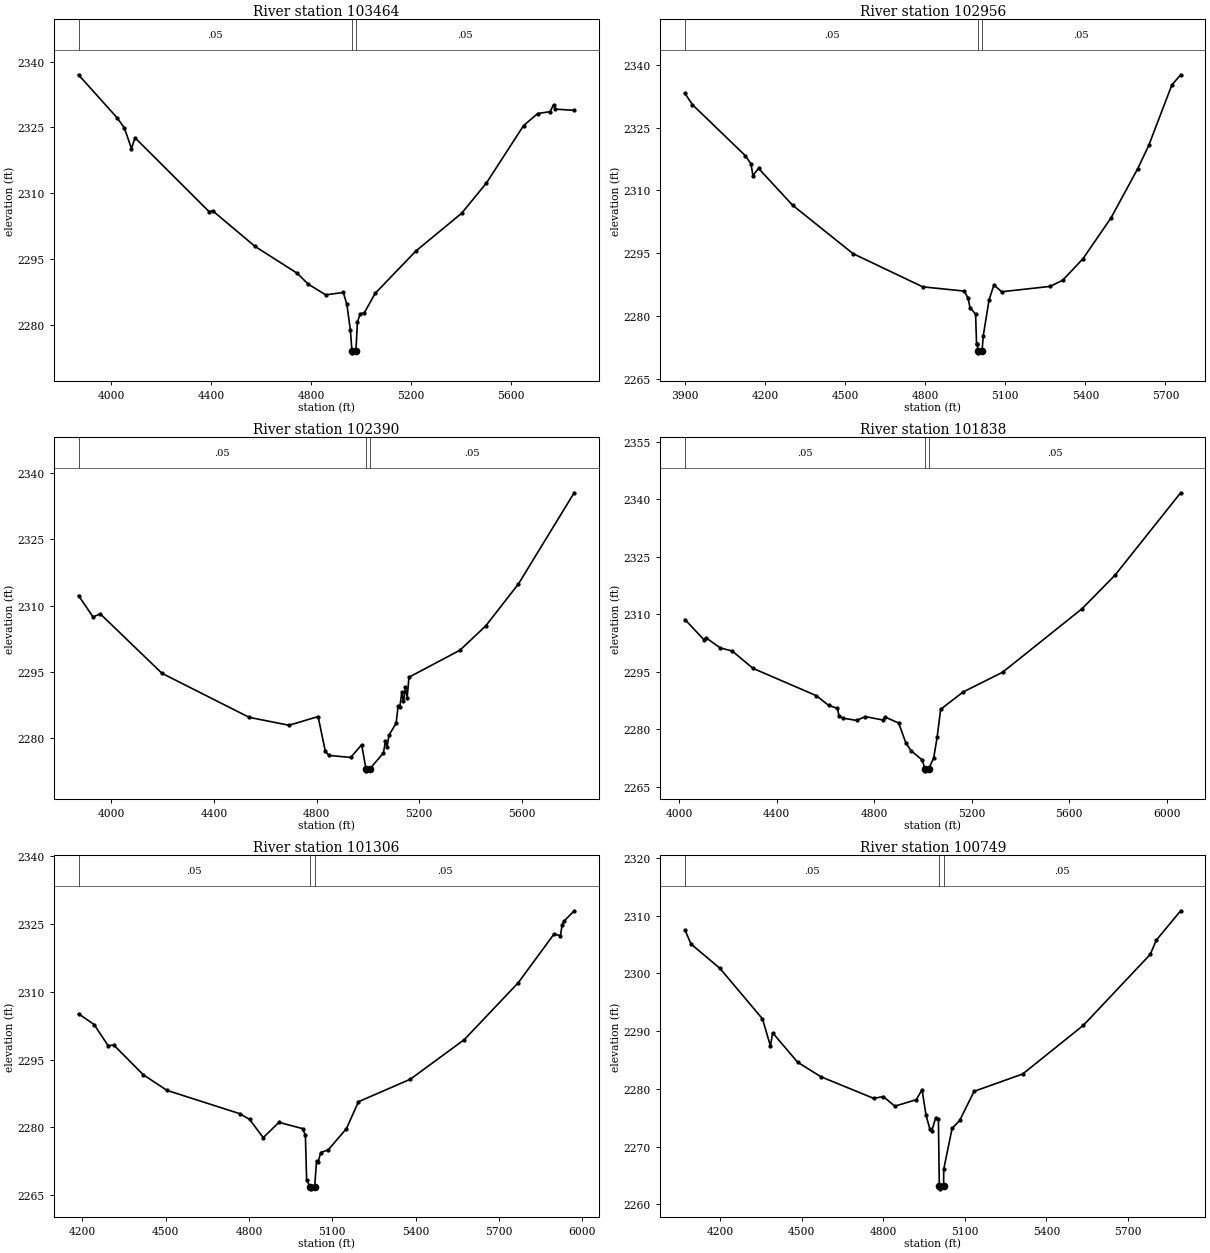
Type RM Length L Ch R = 1,103464,508,508,508
BEGIN DESCRIPTION:
Buffalo Creek 125.0
END DESCRIPTION:
XS GIS Cut Line= 3
      1296705.01      6918937.99      1297505.00      6918138.00
      1298130.54      6917556.84
#Sta/Elev= 30
  3869.1 2337.01  4024.7 2327.14  4052.9 2324.86  4081.2 2320.18  4095.4 2322.64
  4392.3 2305.78  4406.5 2305.98  4576.2 2297.86  4745.9 2291.70  4788.3 2289.29
  4859.0 2286.81  4929.8 2287.35  4943.9 2284.61  4958.0 2278.79  4964.2 2274.08
  4965.7 2273.58  4980.2 2274.08  4986.3 2280.61  4996.9 2282.43  5014.4 2282.77
  5056.9 2287.12  5219.6 2296.77  5403.8 2305.43  5503.0 2312.33  5651.5 2325.40
  5708.2 2328.17  5757.6 2328.60  5771.7 2330.15  5778.6 2329.17  5854.3 2328.90
#Mann=3,-1,0
  3869.1    0.05       0  4964.2    0.05       0  4980.2    0.05       0
Bank Sta=4964.2,4980.2
Exp/Cntr=0.3,0.1

Type RM Length L Ch R = 1,102956,566,566,566
BEGIN DESCRIPTION:
Buffalo Creek 124.0
END DESCRIPTION:
XS GIS Cut Line= 3
      1297154.99      6919188.01      1297905.00      6918388.00
      1298205.01      6917687.98
#Sta/Elev= 30
  3898.9 2333.18  3927.0 2330.49  4125.3 2318.31  4146.3 2316.35  4153.6 2313.57
  4174.7 2315.28  4302.1 2306.50  4528.8 2294.92  4790.1 2286.99  4945.9 2285.97
  4960.1 2284.29  4967.4 2282.05  4988.4 2280.45  4992.1 2273.23  4995.5 2273.23
  4996.6 2271.72  4998.1 2271.22  5012.6 2271.72  5017.3 2275.36  5039.0 2283.90
  5057.2 2287.43  5086.2 2285.81  5267.5 2287.09  5314.6 2288.55  5390.8 2293.68
  5496.0 2303.45  5595.7 2315.14  5637.4 2320.75  5724.4 2335.23  5757.1 2337.64
#Mann=3,-1,0
  3898.9    0.05       0  4996.6    0.05       0  5012.6    0.05       0
Bank Sta=4996.6,5012.6
Exp/Cntr=0.3,0.1

Type RM Length L Ch R = 1,102390,552,552,552
BEGIN DESCRIPTION:
Buffalo Creek 123.0
END DESCRIPTION:
XS GIS Cut Line= 3
      1297605.00      6919188.00      1298405.00      6918388.00
      1298916.65      6917773.36
#Sta/Elev= 30
  3872.3 2312.27  3928.9 2307.42  3957.1 2308.11  4197.6 2294.64  4537.0 2284.67
  4692.5 2282.87  4805.7 2284.84  4834.0 2276.95  4848.1 2276.03  4933.0 2275.58
  4975.4 2278.45  4992.1 2273.04  4993.6 2272.54  5008.1 2273.04  5060.3 2276.60
  5068.1 2279.24  5074.6 2277.97  5081.7 2280.59  5109.8 2283.35  5117.6 2287.22
  5124.1 2287.01  5131.9 2290.30  5138.4 2288.26  5146.2 2291.44  5152.7 2289.09
  5159.8 2293.76  5358.4 2299.88  5458.7 2305.38  5586.2 2314.89  5803.4 2335.56
#Mann=3,-1,0
  3872.3    0.05       0  4992.1   0.033       0  5008.1    0.05       0
Bank Sta=4992.1,5008.1
Exp/Cntr=0.3,0.1

Type RM Length L Ch R = 1,101838,532,532,532
BEGIN DESCRIPTION:
Buffalo Creek 122.0
END DESCRIPTION:
XS GIS Cut Line= 3
      1297755.03      6919287.98      1298555.00      6918738.00
      1299255.00      6917938.00
#Sta/Elev= 30
  4024.0 2308.64  4103.1 2303.28  4109.2 2303.91  4168.8 2301.23  4218.1 2300.41
  4303.3 2295.88  4563.2 2288.75  4613.9 2286.20  4649.8 2285.44  4655.8 2283.51
  4670.7 2282.89  4727.8 2282.30  4764.2 2283.28  4837.0 2282.39  4843.9 2283.20
  4900.7 2281.61  4930.5 2276.41  4951.5 2274.39  4998.1 2271.92  5008.1 2269.62
  5009.6 2269.12  5024.1 2269.62  5044.6 2272.51  5058.8 2277.95  5073.1 2285.19
  5165.1 2289.71  5327.4 2294.88  5653.9 2311.50  5788.7 2320.24  6057.8 2341.75
#Mann=3,-1,0
  4024.0    0.05       0  5008.1   0.033       0  5024.1    0.05       0
Bank Sta=5008.1,5024.1
Exp/Cntr=0.3,0.1

Type RM Length L Ch R = 1,101306,557,557,557
BEGIN DESCRIPTION:
Buffalo Creek 121.0
END DESCRIPTION:
XS GIS Cut Line= 3
      1298355.02      6919637.98      1298905.00      6919038.00
      1299454.98      6918238.03
#Sta/Elev= 30
  4186.2 2305.10  4242.6 2302.72  4292.5 2298.08  4313.5 2298.18  4419.6 2291.63
  4504.7 2288.19  4766.7 2283.04  4801.9 2281.79  4851.2 2277.74  4907.9 2281.13
  4993.0 2279.74  5003.1 2278.30  5007.6 2268.32  5020.5 2266.94  5022.0 2266.44
  5036.5 2266.94  5043.4 2272.65  5049.5 2272.44  5058.3 2274.46  5085.3 2275.04
  5151.0 2279.75  5194.3 2285.68  5381.0 2290.65  5575.2 2299.39  5769.3 2311.94
  5898.1 2322.69  5921.6 2322.36  5927.6 2324.78  5934.5 2325.56  5970.9 2327.85
#Mann=3,-1,0
  4186.2    0.05       0  5020.5    0.05       0  5036.5    0.05       0
Bank Sta=5020.5,5036.5
Exp/Cntr=0.3,0.1

Type RM Length L Ch R = 1,100749,539,539,539
BEGIN DESCRIPTION:
Buffalo Creek 120.0
END DESCRIPTION:
XS GIS Cut Line= 3
      1298654.98      6920138.03      1299205.00      6919388.00
      1299604.99      6918588.02
#Sta/Elev= 30
  4069.9 2307.51  4091.9 2305.08  4198.5 2300.86  4355.2 2292.11  4384.5 2287.40
  4392.4 2289.70  4484.8 2284.59  4570.5 2282.08  4764.4 2278.34  4800.5 2278.65
  4842.2 2276.98  4921.6 2278.12  4942.5 2279.86  4957.2 2275.41  4971.8 2272.96
  4978.0 2272.65  4992.7 2274.97  5002.8 2274.73  5006.0 2263.17  5007.5 2262.67
  5022.0 2263.17  5022.4 2266.07  5053.1 2273.13  5081.0 2274.51  5134.2 2279.56
  5313.0 2282.56  5536.6 2291.00  5782.6 2303.28  5805.0 2305.75  5894.4 2310.83
#Mann=3,-1,0
  4069.9    0.05       0  5006.0    0.05       0  5022.0    0.05       0
Bank Sta=5006,5022
Exp/Cntr=0.3,0.1

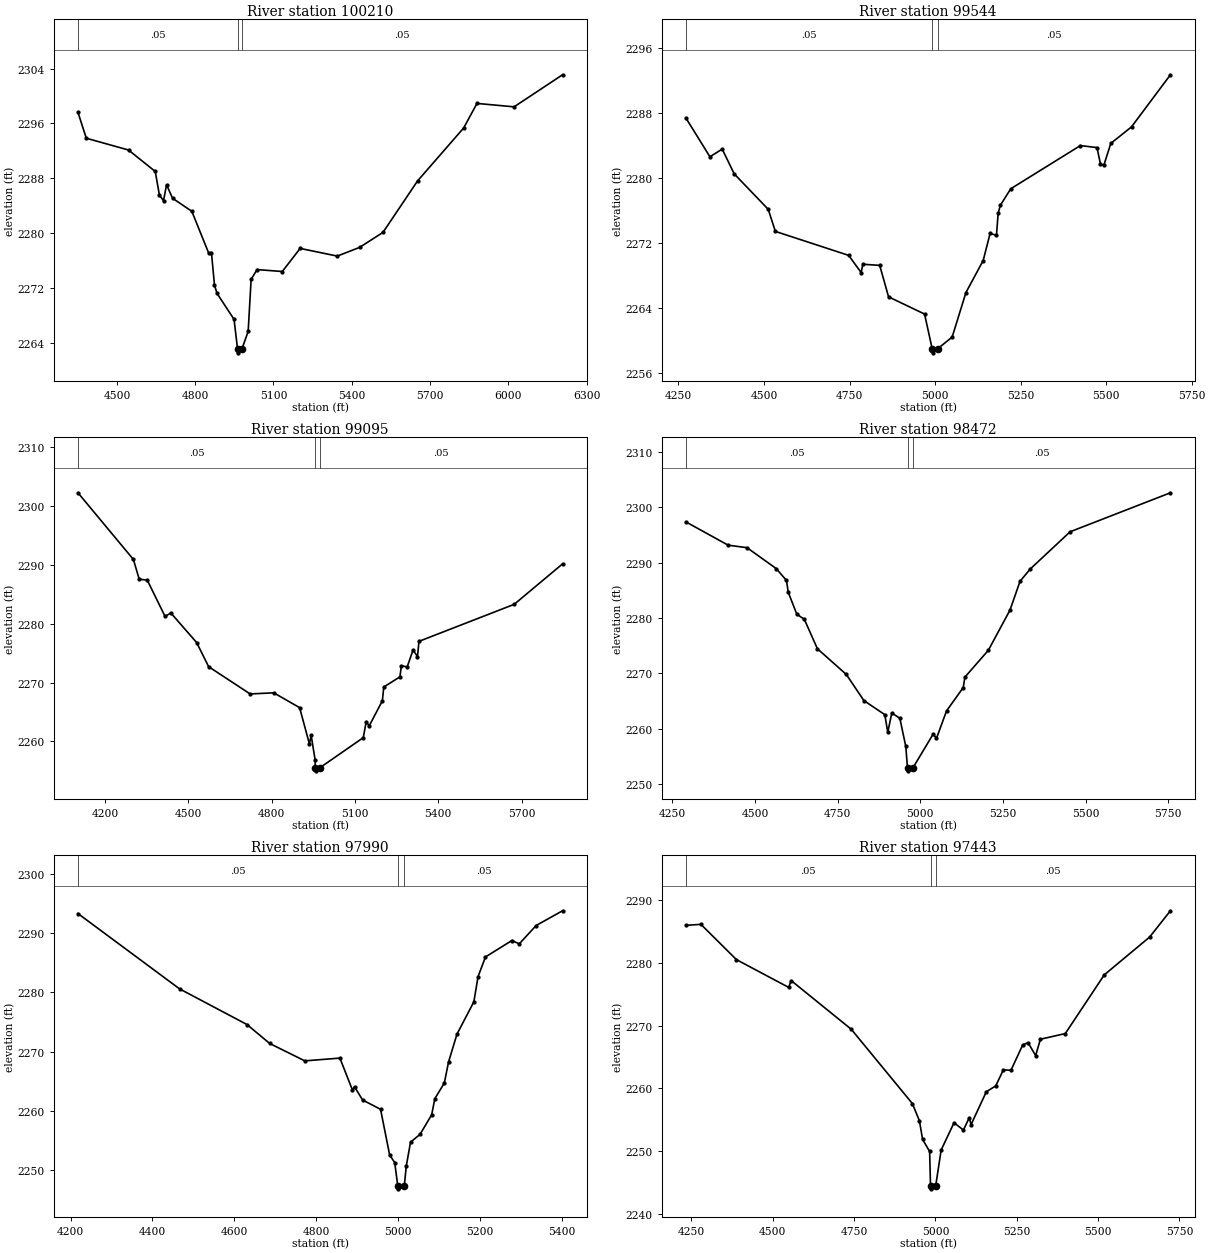
Type RM Length L Ch R = 1,100210,666,666,666
BEGIN DESCRIPTION:
Buffalo Creek 119.0
END DESCRIPTION:
XS GIS Cut Line= 3
      1299085.90      6920403.59      1299405.00      6919838.00
      1299919.25      6918745.58
#Sta/Elev= 30
  4350.8 2297.61  4382.7 2293.83  4544.5 2292.11  4647.0 2288.98  4662.9 2285.53
  4678.7 2284.71  4690.3 2287.05  4713.2 2285.07  4787.1 2283.17  4852.1 2277.03
  4862.3 2277.14  4873.9 2272.42  4883.9 2271.17  4948.9 2267.40  4962.6 2263.01
  4964.1 2262.51  4978.6 2263.01  5003.0 2265.64  5014.4 2273.23  5037.1 2274.66
  5133.8 2274.38  5202.2 2277.75  5344.5 2276.63  5430.1 2277.90  5519.7 2280.09
  5652.3 2287.61  5828.7 2295.32  5879.8 2298.91  6022.0 2298.41  6207.6 2303.09
#Mann=3,-1,0
  4350.8    0.05       0  4962.6    0.05       0  4978.6    0.05       0
Bank Sta=4962.6,4978.6
Exp/Cntr=0.3,0.1

Type RM Length L Ch R = 1,99544,449,449,449
BEGIN DESCRIPTION:
Buffalo Creek 118.0
END DESCRIPTION:
XS GIS Cut Line= 3
      1299645.00      6920417.67      1299891.52      6920146.84
      1300023.46      6919105.18
#Sta/Elev= 30
  4271.7 2287.41  4342.1 2282.63  4377.9 2283.58  4413.0 2280.53  4512.4 2276.17
  4533.3 2273.45  4747.6 2270.50  4784.0 2268.39  4789.0 2269.41  4838.3 2269.27
  4864.1 2265.40  4969.4 2263.28  4991.6 2259.01  4993.1 2258.51  5007.6 2259.01
  5050.0 2260.45  5090.3 2265.93  5140.7 2269.87  5160.9 2273.20  5179.5 2272.97
  5184.5 2275.72  5191.1 2276.68  5221.4 2278.70  5424.8 2284.01  5473.4 2283.76
  5483.5 2281.71  5493.5 2281.61  5513.7 2284.28  5574.2 2286.31  5687.9 2292.72
#Mann=3,-1,0
  4271.7    0.05       0  4991.6    0.05       0  5007.6    0.05       0
Bank Sta=4991.6,5007.6
Exp/Cntr=0.3,0.1

Type RM Length L Ch R = 1,99095,623,623,623
BEGIN DESCRIPTION:
Buffalo Creek 117.0
END DESCRIPTION:
XS GIS Cut Line= 3
      1299505.03      6920587.98      1300205.00      6920038.00
      1300474.78      6919227.40
#Sta/Elev= 30
  4103.0 2302.25  4302.7 2290.91  4323.5 2287.56  4352.4 2287.41  4416.6 2281.24
  4437.4 2281.82  4530.4 2276.79  4573.5 2272.69  4722.9 2268.06  4807.9 2268.25
  4901.0 2265.73  4936.2 2259.58  4942.6 2261.00  4957.1 2256.78  4957.2 2255.49
  4958.7 2254.99  4973.2 2255.49  5130.2 2260.63  5140.8 2263.36  5151.3 2262.61
  5198.9 2266.90  5204.1 2269.24  5262.1 2270.96  5267.4 2272.86  5288.3 2272.65
  5309.4 2275.53  5325.4 2274.41  5330.7 2277.00  5673.5 2283.29  5847.5 2290.16
#Mann=3,-1,0
  4103.0    0.05       0  4957.2   0.033       0  4973.2    0.05       0
Bank Sta=4957.2,4973.2
Exp/Cntr=0.3,0.1

Type RM Length L Ch R = 1,98472,482,482,482
BEGIN DESCRIPTION:
Buffalo Creek 116.0
END DESCRIPTION:
XS GIS Cut Line= 3
      1299676.20      6920763.84      1300346.46      6920532.07
      1301095.49      6920425.30
#Sta/Elev= 30
  4290.8 2297.37  4418.8 2293.16  4475.8 2292.71  4564.1 2288.94  4595.2 2286.80
  4600.5 2284.67  4626.4 2280.71  4649.3 2279.77  4688.7 2274.47  4776.3 2269.82
  4829.2 2265.12  4892.6 2262.57  4901.6 2259.39  4913.8 2262.87  4938.1 2261.92
  4956.1 2256.83  4961.3 2252.93  4962.8 2252.43  4977.3 2252.93  5038.9 2259.06
  5049.0 2258.30  5079.3 2263.24  5129.8 2267.46  5135.0 2269.35  5205.8 2274.19
  5271.3 2281.44  5301.6 2286.63  5331.9 2288.82  5453.1 2295.58  5756.6 2302.62
#Mann=3,-1,0
  4290.8    0.05       0  4961.3    0.05       0  4977.3    0.05       0
Bank Sta=4961.3,4977.3
Exp/Cntr=0.3,0.1

Type RM Length L Ch R = 1,97990,547,547,547
BEGIN DESCRIPTION:
Buffalo Creek 115.0
END DESCRIPTION:
XS GIS Cut Line= 3
      1299832.40      6921206.56      1300555.00      6920938.00
      1300955.00      6920838.00
#Sta/Elev= 30
  4218.0 2293.34  4466.1 2280.61  4630.8 2274.58  4686.2 2271.38  4771.9 2268.44
  4857.6 2268.91  4888.0 2263.55  4893.3 2264.07  4913.0 2261.83  4956.9 2260.25
  4979.1 2252.53  4991.5 2251.25  4998.9 2247.31  5000.4 2246.81  5014.9 2247.31
  5019.8 2250.72  5030.1 2254.70  5053.3 2256.02  5081.7 2259.33  5089.4 2262.05
  5112.6 2264.70  5122.9 2268.25  5143.5 2272.96  5184.7 2278.42  5195.0 2282.69
  5213.1 2286.01  5277.5 2288.78  5295.6 2288.22  5336.8 2291.32  5401.2 2293.81
#Mann=3,-1,0
  4218.0    0.05       0  4998.9    0.05       0  5014.9    0.05       0
Bank Sta=4998.9,5014.9
Exp/Cntr=0.3,0.1

Type RM Length L Ch R = 1,97443,534,534,534
BEGIN DESCRIPTION:
Buffalo Creek 114.0
END DESCRIPTION:
XS GIS Cut Line= 3
      1300144.95      6921770.78      1300805.00      6921388.00
      1301471.52      6921098.71
#Sta/Elev= 30
  4232.7 2285.96  4279.0 2286.12  4388.3 2280.50  4548.9 2276.08  4556.4 2277.17
  4741.1 2269.42  4929.0 2257.59  4950.6 2254.86  4960.5 2251.88  4982.1 2249.96
  4984.8 2244.51  4986.3 2244.01  5000.8 2244.51  5017.5 2250.19  5057.1 2254.53
  5086.0 2253.37  5104.0 2255.34  5109.5 2254.24  5156.4 2259.47  5185.3 2260.40
  5208.7 2262.95  5232.2 2262.89  5268.2 2266.92  5284.6 2267.29  5308.0 2265.23
  5322.7 2267.83  5399.1 2268.73  5519.0 2278.08  5658.3 2284.09  5722.3 2288.28
#Mann=3,-1,0
  4232.7    0.05       0  4984.8   0.033       0  5000.8    0.05       0
Bank Sta=4984.8,5000.8
Exp/Cntr=0.3,0.1

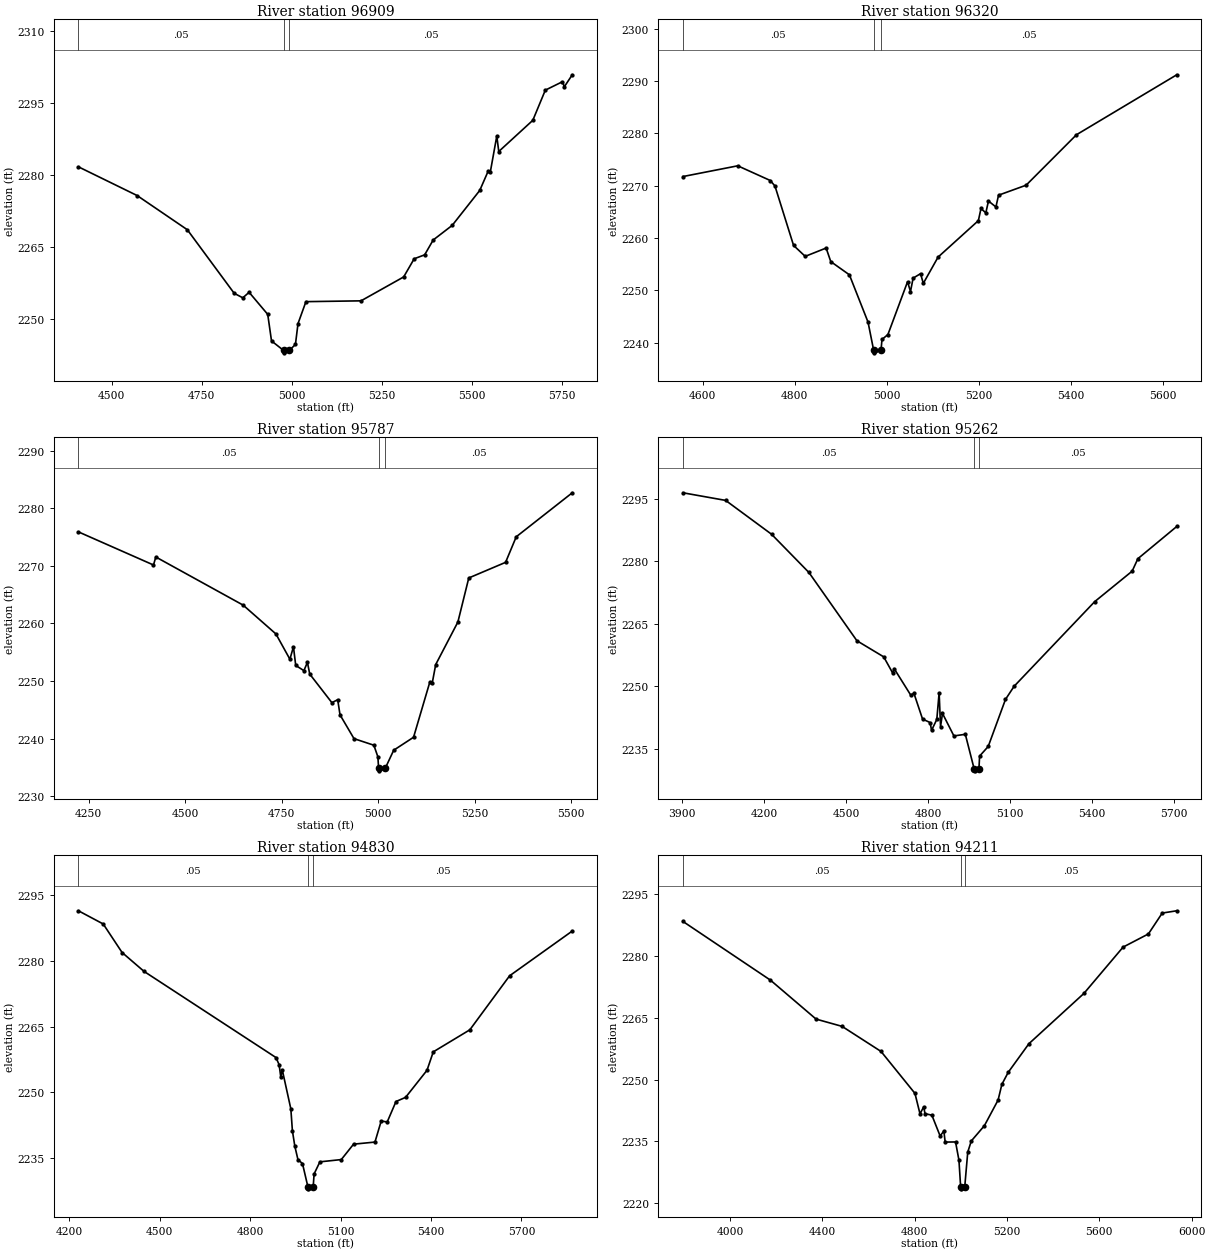
Type RM Length L Ch R = 1,96909,589,589,589
BEGIN DESCRIPTION:
Buffalo Creek 113.0
END DESCRIPTION:
XS GIS Cut Line= 3
      1300487.85      6921992.13      1301055.00      6921838.00
      1301775.82      6921532.52
#Sta/Elev= 30
  4408.0 2281.78  4570.9 2275.80  4710.2 2268.68  4840.3 2255.44  4864.2 2254.50
  4881.7 2255.65  4933.4 2251.05  4943.9 2245.52  4977.4 2243.54  4978.9 2243.04
  4993.4 2243.54  5010.3 2244.80  5017.4 2249.12  5039.4 2253.70  5192.3 2253.87
  5310.7 2258.85  5339.8 2262.63  5368.9 2263.45  5392.6 2266.54  5445.3 2269.58
  5521.8 2276.86  5545.5 2280.94  5550.9 2280.60  5569.1 2288.19  5574.6 2284.97
  5669.1 2291.47  5703.8 2297.75  5751.2 2299.50  5756.6 2298.46  5778.6 2300.95
#Mann=3,-1,0
  4408.0    0.05       0  4977.4   0.033       0  4993.4    0.05       0
Bank Sta=4977.4,4993.4
Exp/Cntr=0.3,0.1

Type RM Length L Ch R = 1,96320,533,533,533
BEGIN DESCRIPTION:
Buffalo Creek 112.0
END DESCRIPTION:
XS GIS Cut Line= 4
      1301067.09      6922250.56      1301330.00      6922213.00
      1301505.00      6922188.00      1302059.01      6921887.96
#Sta/Elev= 30
  4557.4 2271.74  4676.5 2273.79  4747.2 2270.98  4757.3 2269.93  4797.7 2258.59
  4823.0 2256.50  4868.4 2258.09  4878.5 2255.50  4918.9 2252.98  4959.4 2243.95
  4971.6 2238.58  4973.1 2238.08  4987.6 2238.58  4989.7 2240.63  5002.6 2241.58
  5045.2 2251.65  5051.6 2249.79  5057.3 2252.34  5073.5 2253.20  5079.4 2251.34
  5111.5 2256.36  5199.0 2263.32  5204.7 2265.64  5215.2 2264.80  5220.9 2267.07
  5237.1 2265.93  5242.8 2268.18  5302.7 2270.09  5412.0 2279.72  5629.8 2291.17
#Mann=3,-1,0
  4557.4    0.05       0  4971.6    0.05       0  4987.6    0.05       0
Bank Sta=4971.6,4987.6
Exp/Cntr=0.3,0.1

Type RM Length L Ch R = 1,95787,525,525,525
BEGIN DESCRIPTION:
Buffalo Creek 111.0
END DESCRIPTION:
XS GIS Cut Line= 3
      1300957.45      6923109.32      1301605.00      6922688.00
      1302030.03      6922412.98
#Sta/Elev= 30
  4223.8 2275.89  4418.2 2270.14  4424.2 2271.53  4650.4 2263.17  4735.2 2258.17
  4771.4 2253.78  4780.6 2255.94  4786.5 2252.70  4807.6 2251.80  4816.8 2253.23
  4822.8 2251.20  4880.1 2246.24  4895.2 2246.75  4901.2 2244.12  4937.4 2239.99
  4988.8 2238.85  4999.3 2236.82  5001.0 2234.90  5002.5 2234.40  5018.7 2234.90
  5040.2 2237.98  5091.6 2240.23  5133.9 2249.85  5139.8 2249.58  5149.0 2252.86
  5206.4 2260.24  5234.6 2267.89  5329.9 2270.60  5357.5 2275.04  5502.6 2282.68
#Mann=3,-1,0
  4223.8    0.05       0  5001.0    0.05       0  5018.7    0.05       0
Bank Sta=5001,5018.7
Exp/Cntr=0.3,0.1

Type RM Length L Ch R = 1,95262,432,432,432
BEGIN DESCRIPTION:
Buffalo Creek 110.0
END DESCRIPTION:
XS GIS Cut Line= 3
      1301637.29      6924087.79      1301955.00      6923038.00
      1302179.99      6922363.03
#Sta/Elev= 30
  3902.7 2296.49  4059.2 2294.66  4227.2 2286.54  4364.1 2277.36  4539.8 2260.97
  4638.0 2257.10  4671.0 2253.20  4676.2 2254.28  4736.8 2247.93  4748.8 2248.32
  4780.2 2242.17  4807.9 2241.33  4813.2 2239.46  4832.4 2242.09  4840.9 2248.48
  4846.1 2240.38  4853.2 2243.52  4895.0 2238.12  4936.8 2238.51  4969.0 2230.24
  4970.5 2229.74  4986.7 2230.24  4989.1 2233.28  5020.6 2235.59  5083.8 2246.88
  5115.5 2250.04  5410.6 2270.36  5547.6 2277.67  5568.7 2280.67  5711.0 2288.40
#Mann=3,-1,0
  3902.7    0.05       0  4969.0    0.05       0  4986.7    0.05       0
Bank Sta=4969,4986.7
Exp/Cntr=0.3,0.1

Type RM Length L Ch R = 1,94830,619,619,619
BEGIN DESCRIPTION:
Buffalo Creek 109.0
END DESCRIPTION:
XS GIS Cut Line= 3
      1301981.02      6924067.01      1302204.02      6923306.57
      1302350.82      6922473.27
#Sta/Elev= 30
  4230.1 2291.48  4312.4 2288.46  4375.0 2281.94  4447.9 2277.62  4885.6 2257.93
  4896.0 2256.30  4901.5 2253.51  4906.7 2255.05  4934.9 2246.20  4940.1 2241.18
  4948.1 2237.68  4958.5 2234.60  4973.5 2233.70  4991.4 2228.42  4992.9 2227.92
  5009.1 2228.42  5012.1 2231.33  5031.3 2234.09  5102.3 2234.61  5143.0 2238.13
  5214.0 2238.61  5234.7 2243.42  5254.7 2243.21  5283.8 2247.88  5315.6 2248.83
  5386.7 2255.02  5407.5 2259.23  5528.8 2264.27  5660.8 2276.62  5868.7 2286.85
#Mann=3,-1,0
  4230.1    0.05       0  4991.4    0.05       0  5009.1    0.05       0
Bank Sta=4991.4,5009.1
Exp/Cntr=0.3,0.1

Type RM Length L Ch R = 1,94211,564,564,564
BEGIN DESCRIPTION:
Buffalo Creek 108.0
END DESCRIPTION:
XS GIS Cut Line= 3
      1302126.85      6924494.09      1302705.00      6923438.00
      1303147.70      6922613.86
#Sta/Elev= 30
  3796.0 2288.37  4175.4 2274.12  4373.0 2264.68  4485.5 2262.92  4654.3 2256.84
  4801.3 2246.67  4823.1 2241.71  4839.2 2243.40  4844.9 2241.75  4874.6 2241.38
  4910.4 2236.33  4926.5 2237.55  4932.2 2234.86  4977.2 2234.89  4991.9 2230.46
  4999.2 2224.02  5000.7 2223.52  5017.0 2224.02  5030.0 2232.42  5045.4 2235.13
  5102.1 2238.83  5161.5 2245.05  5177.8 2248.85  5205.4 2251.78  5295.1 2258.72
  5533.3 2270.91  5703.0 2282.14  5812.6 2285.33  5872.7 2290.40  5935.5 2290.95
#Mann=3,-1,0
  3796.0    0.05       0  4999.2    0.05       0  5017.0    0.05       0
Bank Sta=4999.2,5017
Exp/Cntr=0.3,0.1

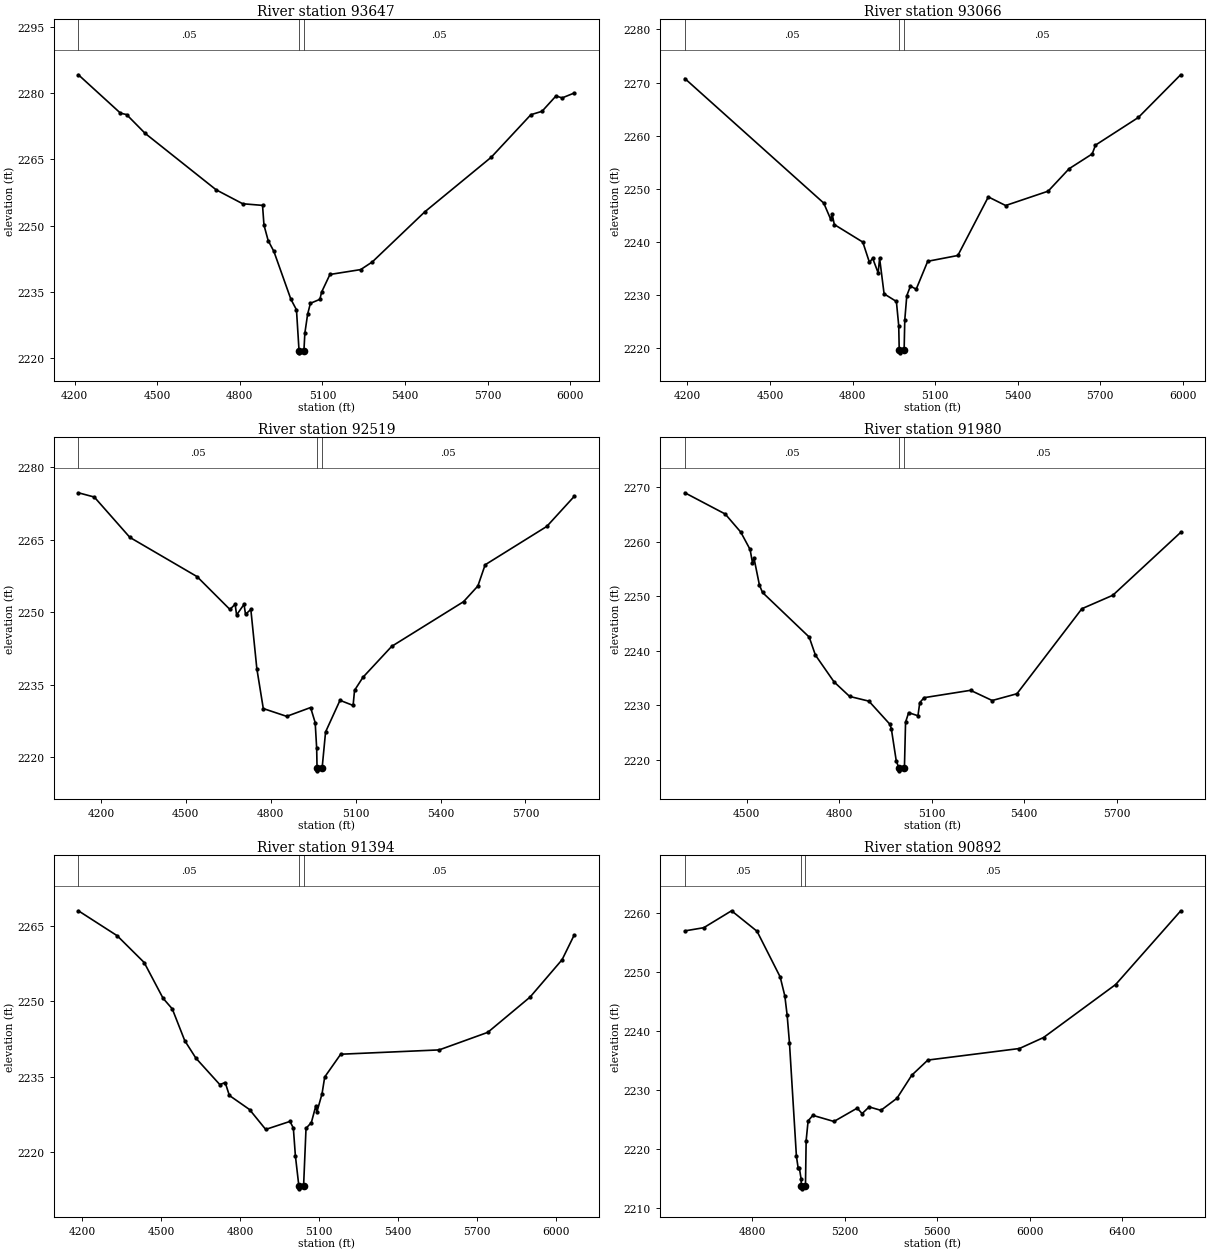
Type RM Length L Ch R = 1,93647,581,581,581
BEGIN DESCRIPTION:
Buffalo Creek 107.0
END DESCRIPTION:
XS GIS Cut Line= 3
      1302923.74      6924598.25      1303105.00      6923838.00
      1303267.46      6922832.80
#Sta/Elev= 30
  4214.0 2284.10  4366.8 2275.42  4389.0 2275.10  4456.2 2270.86  4714.1 2258.09
  4810.5 2254.94  4882.5 2254.57  4887.7 2250.12  4903.0 2246.60  4923.6 2244.18
  4985.3 2233.37  5005.7 2230.96  5015.0 2221.73  5016.5 2221.23  5032.8 2221.73
  5036.1 2225.66  5046.2 2229.97  5056.3 2232.43  5090.7 2233.33  5096.9 2234.96
  5127.2 2238.95  5238.7 2240.05  5280.9 2241.78  5471.7 2253.12  5713.0 2265.47
  5856.6 2275.07  5897.1 2275.84  5947.8 2279.31  5970.1 2278.87  6013.8 2279.97
#Mann=3,-1,0
  4214.0    0.05       0  5015.0    0.05       0  5032.8    0.05       0
Bank Sta=5015,5032.8
Exp/Cntr=0.3,0.1

Type RM Length L Ch R = 1,93066,547,547,547
BEGIN DESCRIPTION:
Buffalo Creek 106.0
END DESCRIPTION:
XS GIS Cut Line= 3
      1303376.87      6924598.21      1303655.00      6923838.00
      1303954.50      6922891.44
#Sta/Elev= 30
  4190.5 2270.75  4695.4 2247.33  4720.6 2244.29  4726.0 2245.25  4733.8 2243.29
  4837.4 2239.99  4861.6 2236.16  4873.3 2236.95  4893.2 2234.19  4898.5 2236.94
  4914.8 2230.26  4959.5 2228.82  4968.0 2224.26  4969.8 2219.66  4971.3 2219.16
  4987.6 2219.66  4990.0 2225.35  4997.3 2229.91  5010.5 2231.71  5031.5 2231.13
  5073.4 2236.38  5182.9 2237.47  5293.7 2248.49  5356.6 2246.87  5511.2 2249.57
  5587.4 2253.79  5671.3 2256.57  5683.3 2258.23  5839.1 2263.43  5992.8 2271.46
#Mann=3,-1,0
  4190.5    0.05       0  4969.8    0.05       0  4987.6    0.05       0
Bank Sta=4969.8,4987.6
Exp/Cntr=0.3,0.1

Type RM Length L Ch R = 1,92519,539,539,539
BEGIN DESCRIPTION:
Buffalo Creek 105.0
END DESCRIPTION:
XS GIS Cut Line= 3
      1303871.67      6924775.28      1304155.00      6923938.00
      1304303.92      6923082.79
#Sta/Elev= 30
  4120.2 2274.65  4176.4 2273.77  4302.1 2265.44  4539.6 2257.34  4655.7 2250.56
  4674.1 2251.64  4679.3 2249.42  4705.5 2251.62  4710.8 2249.56  4729.6 2250.57
  4750.8 2238.34  4773.6 2230.10  4856.3 2228.49  4940.8 2230.31  4957.0 2227.19
  4962.3 2221.87  4963.6 2217.74  4965.1 2217.24  4981.4 2217.74  4993.7 2225.27
  5044.7 2231.80  5091.0 2230.74  5096.1 2233.86  5125.9 2236.56  5227.4 2242.94
  5481.2 2252.16  5531.9 2255.40  5557.6 2259.78  5775.6 2267.71  5872.2 2273.89
#Mann=3,-1,0
  4120.2    0.05       0  4963.6    0.05       0  4981.4    0.05       0
Bank Sta=4963.6,4981.4
Exp/Cntr=0.3,0.1

Type RM Length L Ch R = 1,91980,586,586,586
BEGIN DESCRIPTION:
Buffalo Creek 104.0
END DESCRIPTION:
XS GIS Cut Line= 3
      1304460.21      6924837.77      1304555.00      6924138.00
      1304475.83      6923238.84
#Sta/Elev= 30
  4298.8 2269.01  4429.8 2265.11  4480.2 2261.79  4510.5 2258.60  4518.1 2256.19
  4523.2 2256.99  4540.8 2252.06  4550.8 2250.71  4702.2 2242.53  4722.4 2239.22
  4782.9 2234.30  4833.4 2231.63  4896.1 2230.76  4963.6 2226.55  4968.7 2225.74
  4984.8 2219.80  4993.5 2218.47  4995.0 2217.97  5011.3 2218.47  5015.0 2226.90
  5025.0 2228.65  5055.2 2228.08  5061.1 2230.50  5075.2 2231.40  5225.8 2232.75
  5296.1 2230.88  5376.4 2232.12  5587.2 2247.73  5687.6 2250.20  5907.6 2261.73
#Mann=3,-1,0
  4298.8    0.05       0  4993.5    0.05       0  5011.3    0.05       0
Bank Sta=4993.5,5011.3
Exp/Cntr=0.3,0.1

Type RM Length L Ch R = 1,91394,502,502,502
BEGIN DESCRIPTION:
Buffalo Creek 103.0
END DESCRIPTION:
XS GIS Cut Line= 3
      1304918.53      6924931.60      1305105.00      6924138.00
      1304923.77      6923082.76
#Sta/Elev= 30
  4184.7 2268.04  4332.2 2263.07  4434.9 2257.73  4506.8 2250.60  4541.8 2248.49
  4589.4 2242.14  4631.8 2238.66  4722.6 2233.40  4743.1 2233.81  4759.0 2231.23
  4835.6 2228.43  4897.2 2224.46  4989.6 2226.06  5002.4 2224.74  5010.1 2219.22
  5023.5 2213.12  5025.0 2212.62  5041.3 2213.12  5050.6 2224.68  5070.9 2225.83
  5087.3 2229.05  5092.4 2228.02  5111.5 2231.56  5121.7 2234.91  5182.5 2239.45
  5557.0 2240.31  5742.0 2243.81  5902.9 2250.84  6024.7 2258.29  6070.6 2263.19
#Mann=3,-1,0
  4184.7    0.05       0  5023.5    0.05       0  5041.3    0.05       0
Bank Sta=5023.5,5041.3
Exp/Cntr=0.3,0.1

Type RM Length L Ch R = 1,90892,1009,1009,1009
BEGIN DESCRIPTION:
Buffalo Creek 102.0
END DESCRIPTION:
XS GIS Cut Line= 3
      1305538.33      6924879.49      1305505.00      6924388.00
      1305215.71      6922761.34
#Sta/Elev= 30
  4508.2 2256.94  4589.9 2257.48  4710.2 2260.35  4820.4 2256.88  4920.6 2249.13
  4940.7 2245.91  4950.7 2242.65  4960.7 2237.98  4990.8 2218.74  4998.3 2216.76
  5003.4 2216.76  5011.0 2214.93  5012.2 2213.71  5013.7 2213.21  5030.0 2213.71
  5032.9 2221.39  5041.4 2224.73  5061.8 2225.67  5153.2 2224.63  5253.7 2226.89
  5275.1 2225.97  5305.5 2227.10  5356.3 2226.52  5425.7 2228.56  5489.8 2232.47
  5559.4 2235.04  5955.6 2237.00  6059.8 2238.86  6372.0 2247.85  6653.0 2260.32
#Mann=3,-1,0
  4508.2    0.05       0  5012.2    0.05       0  5030.0    0.05       0
Bank Sta=5012.2,5030
Exp/Cntr=0.3,0.1

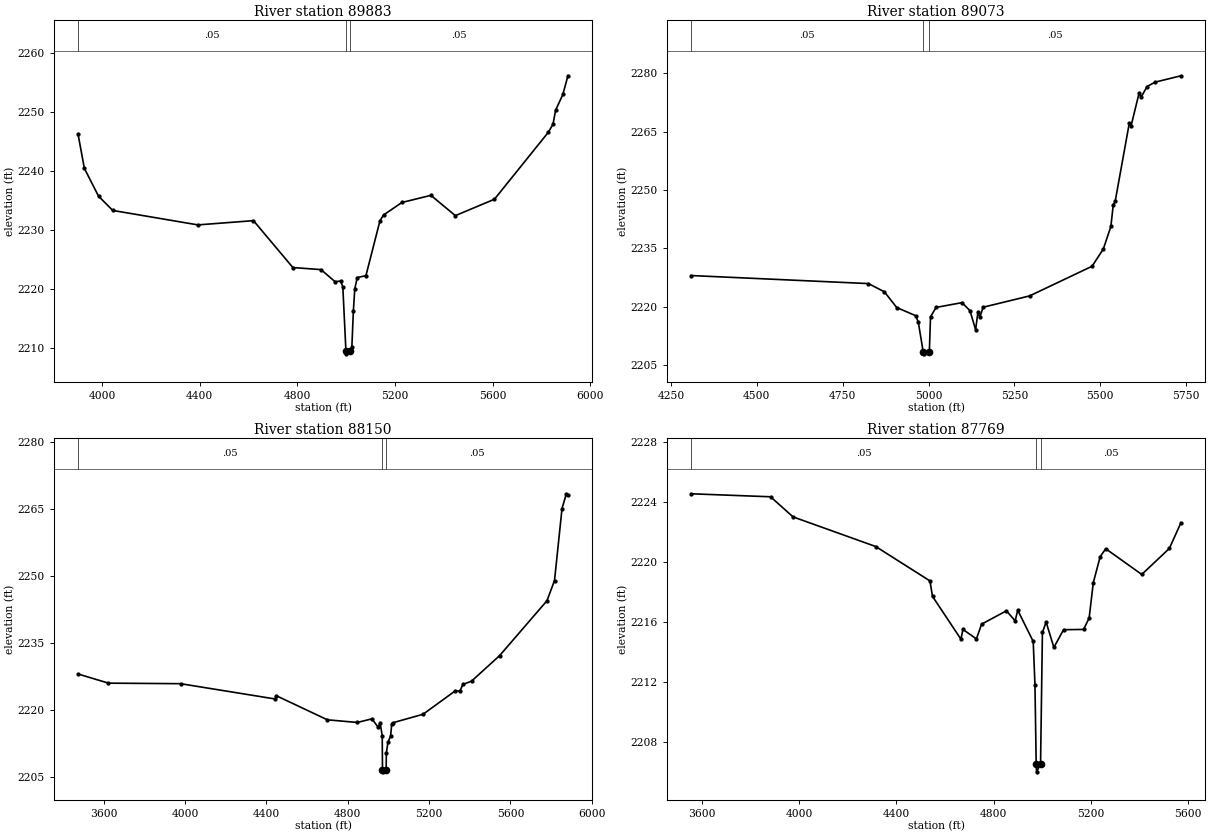
Type RM Length L Ch R = 1,89883,810,810,810
BEGIN DESCRIPTION:
Buffalo Creek 101.5
END DESCRIPTION:
XS GIS Cut Line= 4
      1306374.34      6924623.10      1306024.49      6924046.52
      1305675.91      6923434.57      1305699.15      6922807.18
#Sta/Elev= 30
  3901.9 2246.29  3927.5 2240.53  3985.6 2235.81  4043.8 2233.39  4392.7 2230.94
  4620.3 2231.66  4781.7 2223.71  4896.9 2223.36  4954.6 2221.31  4977.4 2221.42
  4986.3 2220.44  4999.0 2209.58  5000.5 2209.08  5016.9 2209.58  5023.4 2210.29
  5029.5 2216.33  5035.3 2220.11  5045.4 2222.01  5081.0 2222.34  5138.5 2231.65
  5153.4 2232.63  5228.4 2234.74  5347.2 2235.95  5447.3 2232.51  5607.4 2235.29
  5827.5 2246.61  5847.5 2248.02  5857.5 2250.34  5887.6 2253.05  5908.4 2256.22
#Mann=3,-1,0
  3901.9    0.05       0  4999.0    0.05       0  5016.9    0.05       0
Bank Sta=4999,5016.9
Exp/Cntr=0.3,0.1

Type RM Length L Ch R = 1,89073,923,923,923
BEGIN DESCRIPTION:
Mapping XS 5ac6d1be
END DESCRIPTION:
XS GIS Cut Line= 3
      1306492.21      6924060.01      1306513.04      6923650.32
      1306100.66      6922721.58
#Sta/Elev= 30
  4308.6 2227.99  4825.1 2225.92  4871.6 2223.80  4907.4 2219.76  4962.1 2217.68
  4970.1 2216.07  4984.5 2208.35  4986.0 2207.85  5002.4 2208.35  5005.8 2217.39
  5022.1 2219.79  5097.4 2221.02  5120.7 2218.96  5137.1 2214.04  5143.9 2218.61
  5149.4 2217.27  5159.0 2219.84  5294.4 2222.75  5476.3 2230.38  5509.1 2234.83
  5531.0 2240.61  5538.0 2246.22  5543.5 2247.05  5584.5 2267.10  5590.0 2266.54
  5613.3 2274.96  5618.7 2273.81  5636.5 2276.61  5659.8 2277.73  5735.0 2279.37
#Mann=3,-1,0
  4308.6    0.05       0  4984.5    0.05       0  5002.4    0.05       0
Bank Sta=4984.5,5002.4
Exp/Cntr=0.3,0.1

Type RM Length L Ch R = 1,88150,381,381,381
BEGIN DESCRIPTION:
Buffalo Creek 100.0
END DESCRIPTION:
XS GIS Cut Line= 5
      1306751.97      6924523.27      1307080.00      6923163.00
      1307055.00      6923038.00      1307024.37      6922941.48
      1306354.98      6922537.99
#Sta/Elev= 30
  3473.3 2228.07  3622.7 2226.03  3977.2 2225.91  4443.3 2222.49  4448.4 2223.22
  4699.8 2217.84  4846.9 2217.25  4918.5 2218.05  4949.1 2216.22  4959.3 2217.06
  4969.4 2214.30  4970.7 2206.72  4972.2 2206.22  4988.6 2206.72  4989.8 2210.45
  4997.5 2212.82  5010.5 2214.21  5016.2 2216.90  5021.4 2217.18  5170.3 2219.08
  5329.5 2224.34  5350.9 2224.22  5366.4 2225.73  5409.1 2226.49  5547.0 2232.19
  5780.0 2244.45  5816.9 2248.95  5853.8 2265.02  5875.1 2268.33  5882.9 2268.08
#Mann=3,-1,0
  3473.3    0.05       0  4970.7    0.05       0  4988.6    0.05       0
Bank Sta=4970.7,4988.6
Exp/Cntr=0.3,0.1

Type RM Length L Ch R = 1,87769,514,514,514
BEGIN DESCRIPTION:
Buffalo Creek 99.5
END DESCRIPTION:
XS GIS Cut Line= 4
      1306980.00      6924263.00      1307430.00      6923013.00
      1307345.63      6922778.23      1306949.15      6922591.64
#Sta/Elev= 30
  3554.9 2224.54  3882.0 2224.34  3974.7 2223.00  4314.8 2221.03  4538.0 2218.74
  4548.6 2217.71  4665.6 2214.86  4673.8 2215.51  4729.3 2214.88  4750.6 2215.86
  4852.7 2216.75  4888.8 2216.08  4899.4 2216.79  4963.1 2214.71  4970.3 2211.83
  4975.4 2206.53  4976.9 2206.03  4993.3 2206.53  5001.0 2215.31  5016.3 2216.00
  5048.1 2214.31  5087.9 2215.49  5170.5 2215.51  5193.3 2216.27  5210.5 2218.63
  5238.9 2220.36  5261.7 2220.88  5409.9 2219.17  5523.4 2220.90  5571.1 2222.61
#Mann=3,-1,0
  3554.9    0.05       0  4975.4    0.05       0  4993.3    0.05       0
Bank Sta=4975.4,4993.3
Exp/Cntr=0.3,0.1