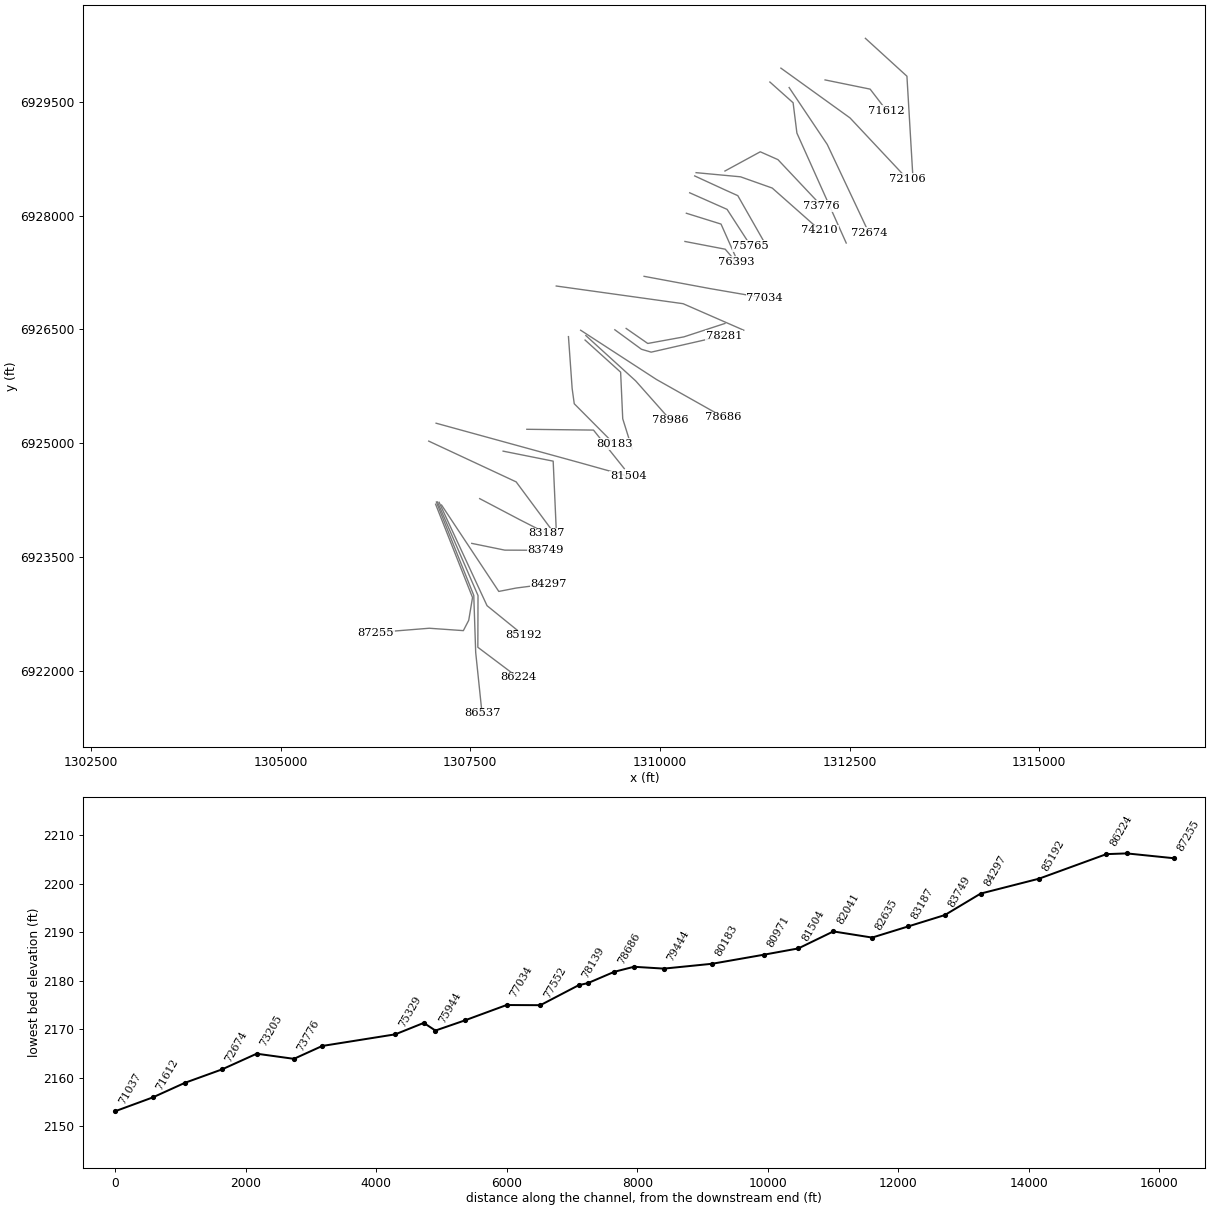
HEC-RAS study Buffalo Creek.prj: Buffalo Creek Base Level Engineering

--- Buffalo Creek.g01 (geometry) --- (continued)

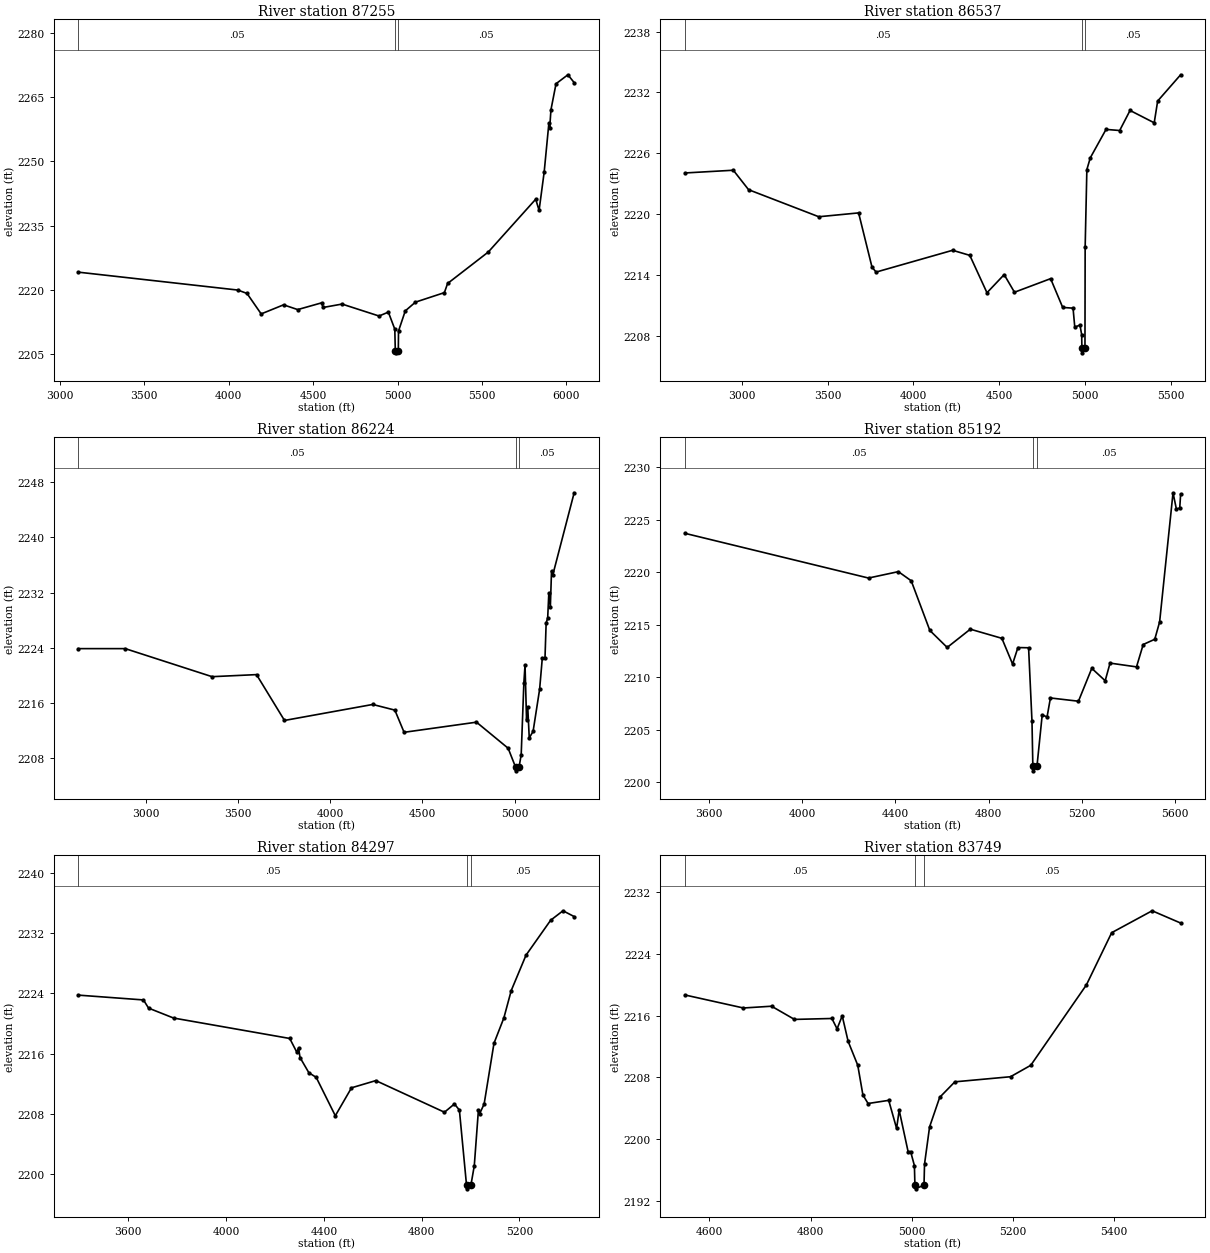
Type RM Length L Ch R = 1,87255,718,718,718
BEGIN DESCRIPTION:
Buffalo Creek 99.4
END DESCRIPTION:
XS GIS Cut Line= 6
      1307043.49      6924193.27      1307530.00      6922963.00
      1307480.00      6922663.00      1307409.17      6922526.31
      1306959.36      6922557.82      1306258.01      6922501.17
#Sta/Elev= 30
  3110.0 2224.14  4054.4 2219.96  4108.5 2219.17  4192.3 2214.39  4324.8 2216.51
  4408.6 2215.40  4549.6 2216.97  4559.7 2215.90  4671.2 2216.69  4890.2 2213.90
  4945.4 2214.81  4983.6 2210.82  4986.5 2205.80  4988.0 2205.30  5004.4 2205.80
  5005.5 2210.39  5045.6 2215.10  5105.8 2217.14  5277.1 2219.36  5296.2 2221.50
  5537.0 2228.84  5817.9 2241.18  5837.9 2238.58  5868.0 2247.50  5895.9 2258.93
  5900.9 2257.91  5908.2 2262.08  5938.3 2268.15  6008.5 2270.24  6045.6 2268.41
#Mann=3,-1,0
  3110.0    0.05       0  4986.5    0.05       0  5004.4    0.05       0
Bank Sta=4986.5,5004.4
Exp/Cntr=0.3,0.1

Type RM Length L Ch R = 1,86537,313,313,313
BEGIN DESCRIPTION:
Buffalo Creek 99.2
END DESCRIPTION:
XS GIS Cut Line= 4
      1307053.93      6924221.87      1307546.37      6922991.66
      1307571.71      6922238.59      1307655.40      6921435.05
#Sta/Elev= 30
  2668.9 2224.04  2951.0 2224.31  3039.9 2222.39  3448.6 2219.72  3680.5 2220.10
  3758.6 2214.74  3782.5 2214.26  4227.8 2216.41  4327.9 2215.91  4427.9 2212.22
  4528.0 2214.01  4588.0 2212.27  4798.4 2213.61  4868.8 2210.77  4929.1 2210.70
  4939.1 2208.83  4969.3 2209.03  4979.4 2208.07  4980.4 2206.79  4981.9 2206.29
  4998.4 2206.79  4999.5 2216.69  5009.5 2224.38  5029.6 2225.54  5121.1 2228.34
  5200.5 2228.23  5260.9 2230.21  5401.6 2228.99  5421.7 2231.14  5555.4 2233.73
#Mann=3,-1,0
  2668.9    0.05       0  4980.4    0.05       0  4998.4    0.05       0
Bank Sta=4980.4,4998.4
Exp/Cntr=0.3,0.1

Type RM Length L Ch R = 1,86224,1032,1032,1032
BEGIN DESCRIPTION:
Buffalo Creek 99.1
END DESCRIPTION:
XS GIS Cut Line= 4
      1307067.69      6924223.04      1307602.36      6922989.06
      1307600.11      6922306.73      1308128.17      6921909.27
#Sta/Elev= 30
  2634.5 2223.87  2888.5 2223.87  3359.3 2219.80  3600.3 2220.10  3752.0 2213.45
  4230.4 2215.77  4350.4 2214.95  4400.4 2211.73  4793.0 2213.20  4964.6 2209.42
  5005.5 2206.64  5007.0 2206.14  5023.5 2206.64  5035.4 2208.48  5049.9 2218.91
  5056.2 2221.48  5064.5 2213.50  5070.8 2215.45  5079.1 2210.92  5099.9 2211.86
  5135.3 2217.97  5149.9 2222.51  5164.5 2222.54  5170.7 2227.59  5179.0 2228.30
  5185.3 2231.95  5193.5 2229.93  5199.9 2235.17  5206.1 2234.50  5322.6 2246.48
#Mann=3,-1,0
  2634.5    0.05       0  5005.5    0.05       0  5023.5    0.05       0
Bank Sta=5005.5,5023.5
Exp/Cntr=0.3,0.1

Type RM Length L Ch R = 1,85192,895,895,895
BEGIN DESCRIPTION:
Buffalo Creek 99.0
END DESCRIPTION:
XS GIS Cut Line= 3
      1307089.38      6924218.72      1307721.26      6922855.22
      1308205.15      6922462.33
#Sta/Elev= 30
  3497.2 2223.69  4284.8 2219.43  4412.8 2220.04  4467.9 2219.17  4547.8 2214.44
  4622.2 2212.82  4721.4 2214.56  4856.7 2213.69  4902.6 2211.24  4925.5 2212.81
  4971.3 2212.79  4985.9 2205.77  4989.5 2201.57  4991.0 2201.07  5007.5 2201.57
  5029.7 2206.40  5050.5 2206.20  5064.9 2208.01  5185.1 2207.70  5242.3 2210.83
  5299.8 2209.65  5320.6 2211.33  5434.1 2210.97  5462.8 2213.10  5512.4 2213.60
  5533.2 2215.25  5590.7 2227.55  5605.1 2226.00  5619.5 2226.10  5623.3 2227.41
#Mann=3,-1,0
  3497.2    0.05       0  4989.5    0.05       0  5007.5    0.05       0
Bank Sta=4989.5,5007.5
Exp/Cntr=0.3,0.1

Type RM Length L Ch R = 1,84297,548,548,548
BEGIN DESCRIPTION:
Buffalo Creek 98.0
END DESCRIPTION:
XS GIS Cut Line= 4
      1307121.63      6924182.81      1307876.10      6923043.27
      1308105.00      6923088.00      1308530.37      6923142.95
#Sta/Elev= 30
  3395.6 2223.78  3661.8 2223.14  3682.8 2222.05  3785.1 2220.73  4260.5 2218.01
  4288.9 2216.21  4296.6 2216.74  4302.6 2215.47  4338.7 2213.45  4368.8 2212.83
  4447.0 2207.72  4513.2 2211.44  4612.7 2212.40  4893.6 2208.19  4934.4 2209.29
  4954.7 2208.48  4983.9 2198.49  4985.4 2197.99  5001.9 2198.49  5015.7 2201.07
  5032.7 2208.52  5037.7 2208.00  5056.0 2209.28  5096.3 2217.37  5136.7 2220.74
  5166.9 2224.39  5227.4 2229.10  5328.2 2233.75  5378.7 2235.01  5424.4 2234.24
#Mann=3,-1,0
  3395.6    0.05       0  4983.9    0.05       0  5001.9    0.05       0
Bank Sta=4983.9,5001.9
Exp/Cntr=0.3,0.1

Type RM Length L Ch R = 1,83749,562,562,562
BEGIN DESCRIPTION:
Buffalo Creek 97.0
END DESCRIPTION:
XS GIS Cut Line= 3
      1307520.17      6923676.95      1307955.00      6923588.00
      1308491.26      6923585.81
#Sta/Elev= 30
  4551.5 2218.69  4667.3 2217.00  4722.9 2217.23  4768.2 2215.52  4842.2 2215.64
  4852.4 2214.30  4862.6 2215.98  4874.3 2212.67  4893.3 2209.58  4903.5 2205.72
  4913.7 2204.62  4954.5 2205.03  4970.1 2201.39  4975.2 2203.75  4992.8 2198.39
  4997.8 2198.39  5005.3 2196.57  5006.3 2194.06  5007.8 2193.56  5024.3 2194.06
  5025.3 2196.76  5035.3 2201.59  5055.3 2205.42  5085.3 2207.43  5195.3 2208.09
  5235.3 2209.57  5345.3 2219.99  5395.3 2226.76  5475.3 2229.60  5531.6 2228.01
#Mann=3,-1,0
  4551.5    0.05       0  5006.3    0.05       0  5024.3    0.05       0
Bank Sta=5006.3,5024.3
Exp/Cntr=0.3,0.1

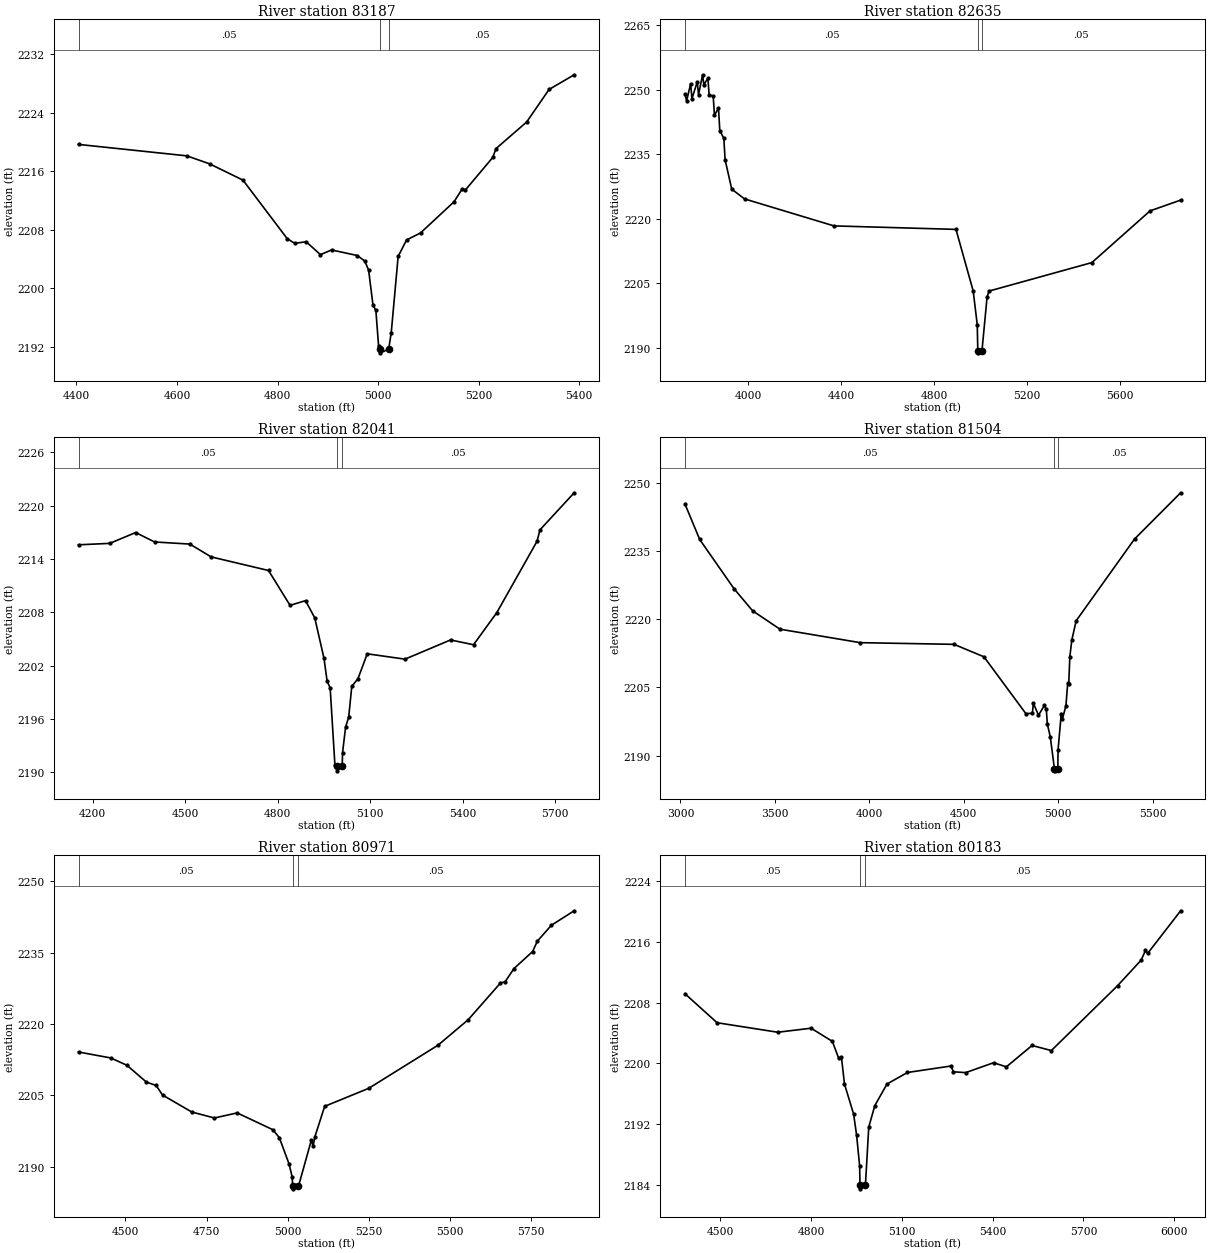
Type RM Length L Ch R = 1,83187,552,552,552
BEGIN DESCRIPTION:
Buffalo Creek 96.0
END DESCRIPTION:
XS GIS Cut Line= 3
      1307624.39      6924267.21      1308155.00      6923988.00
      1308499.05      6923812.54
#Sta/Elev= 30
  4404.2 2219.67  4619.6 2218.11  4664.8 2217.02  4731.2 2214.80  4819.3 2206.80
  4834.3 2206.16  4856.9 2206.38  4885.4 2204.62  4907.5 2205.26  4958.6 2204.50
  4973.6 2203.74  4981.2 2202.50  4989.9 2197.72  4995.6 2197.01  5001.0 2192.16
  5003.1 2191.71  5004.6 2191.21  5021.1 2191.71  5026.2 2193.98  5039.9 2204.37
  5056.6 2206.62  5084.4 2207.58  5151.1 2211.84  5167.7 2213.64  5173.3 2213.42
  5228.3 2217.91  5234.4 2219.09  5295.5 2222.73  5340.0 2227.17  5390.0 2229.18
#Mann=3,-1,0
  4404.2    0.05       0  5003.1    0.05       0  5021.1    0.05       0
Bank Sta=5003.1,5021.1
Exp/Cntr=0.3,0.1

Type RM Length L Ch R = 1,82635,594,594,594
BEGIN DESCRIPTION:
Buffalo Creek 95.0
END DESCRIPTION:
XS GIS Cut Line= 3
      1306952.81      6925025.64      1308105.00      6924488.00
      1308617.22      6923796.14
#Sta/Elev= 30
  3728.6 2248.86  3735.7 2247.37  3753.0 2251.37  3758.5 2247.88  3781.4 2251.76
  3786.9 2248.82  3804.3 2253.42  3809.8 2251.13  3827.1 2252.59  3832.6 2248.75
  3850.0 2248.47  3855.5 2244.02  3872.8 2245.69  3878.4 2240.46  3895.7 2238.68
  3901.2 2233.72  3929.7 2226.89  3984.8 2224.62  4369.5 2218.36  4894.4 2217.55
  4968.5 2203.26  4985.9 2195.46  4988.3 2189.41  4989.8 2188.91  5006.3 2189.41
  5028.2 2201.84  5036.6 2203.24  5479.1 2209.85  5729.5 2221.85  5860.9 2224.34
#Mann=3,-1,0
  3728.6    0.05       0  4988.3    0.05       0  5006.3    0.05       0
Bank Sta=4988.3,5006.3
Exp/Cntr=0.3,0.1

Type RM Length L Ch R = 1,82041,537,537,537
BEGIN DESCRIPTION:
Mapping XS 9f56ad51
END DESCRIPTION:
XS GIS Cut Line= 3
      1307933.20      6924893.37      1308592.91      6924761.43
      1308634.57      6923827.42
#Sta/Elev= 30
  4153.7 2215.60  4255.0 2215.76  4339.1 2216.98  4400.3 2215.92  4515.0 2215.68
  4583.9 2214.24  4770.0 2212.71  4839.9 2208.79  4890.0 2209.32  4920.0 2207.38
  4950.0 2202.82  4960.0 2200.29  4970.0 2199.49  4985.4 2190.82  4991.1 2190.68
  4992.6 2190.18  5009.1 2190.68  5010.1 2192.22  5020.1 2195.11  5030.1 2196.23
  5040.1 2199.68  5060.1 2200.54  5090.2 2203.34  5212.7 2202.74  5360.4 2204.90
  5435.0 2204.36  5510.6 2207.98  5640.7 2215.98  5650.7 2217.29  5761.4 2221.45
#Mann=3,-1,0
  4153.7    0.05       0  4991.1    0.05       0  5009.1    0.05       0
Bank Sta=4991.1,5009.1
Exp/Cntr=0.3,0.1

Type RM Length L Ch R = 1,81504,533,533,533
BEGIN DESCRIPTION:
Buffalo Creek 94.0
END DESCRIPTION:
XS GIS Cut Line= 3
      1307050.02      6925261.76      1308955.00      6924738.00
      1309579.99      6924563.00
#Sta/Elev= 30
  3023.8 2245.30  3101.6 2237.53  3283.1 2226.72  3381.6 2221.85  3526.8 2217.80
  3952.0 2214.84  4448.6 2214.47  4607.0 2211.73  4829.0 2199.24  4863.5 2199.32
  4868.6 2201.54  4895.8 2198.88  4926.9 2201.05  4937.2 2200.18  4942.7 2196.92
  4958.0 2194.21  4980.1 2187.17  4981.6 2186.67  4998.1 2187.17  4999.5 2191.33
  5016.5 2199.27  5021.7 2197.96  5041.0 2200.94  5050.7 2206.00  5055.8 2205.66
  5061.8 2211.75  5072.2 2215.39  5095.2 2219.65  5404.5 2237.62  5648.5 2247.78
#Mann=3,-1,0
  3023.8    0.05       0  4980.1    0.05       0  4998.1    0.05       0
Bank Sta=4980.1,4998.1
Exp/Cntr=0.3,0.1

Type RM Length L Ch R = 1,80971,788,788,788
BEGIN DESCRIPTION:
Buffalo Creek 93.0
END DESCRIPTION:
XS GIS Cut Line= 3
      1308245.73      6925181.57      1309124.16      6925171.15
      1309529.99      6924663.01
#Sta/Elev= 30
  4355.2 2214.12  4454.5 2212.87  4504.5 2211.33  4564.5 2207.80  4594.5 2207.09
  4614.5 2205.07  4704.5 2201.51  4774.5 2200.25  4844.5 2201.32  4954.5 2197.79
  4974.5 2196.13  5004.5 2190.61  5014.5 2187.79  5015.5 2185.86  5017.0 2185.36
  5033.5 2185.86  5073.6 2195.66  5078.6 2194.29  5084.5 2196.36  5114.5 2202.70
  5250.5 2206.49  5464.5 2215.57  5557.4 2220.92  5656.7 2228.62  5671.1 2228.89
  5698.4 2231.66  5755.9 2235.24  5770.3 2237.40  5813.6 2240.75  5884.0 2243.80
#Mann=3,-1,0
  4355.2    0.05       0  5015.5    0.05       0  5033.5    0.05       0
Bank Sta=5015.5,5033.5
Exp/Cntr=0.3,0.1

Type RM Length L Ch R = 1,80183,739,739,739
BEGIN DESCRIPTION:
Mapping XS 7a902f3b
END DESCRIPTION:
XS GIS Cut Line= 4
      1308794.29      6926403.79      1308842.91      6925719.76
      1308870.68      6925518.37      1309398.46      6924987.12
#Sta/Elev= 30
  4383.3 2209.15  4489.4 2205.34  4689.9 2204.09  4800.1 2204.62  4870.3 2202.89
  4891.2 2200.67  4900.4 2200.80  4910.4 2197.27  4940.5 2193.34  4950.5 2190.53
  4960.5 2186.50  4961.6 2184.00  4963.1 2183.50  4979.6 2184.00  4990.6 2191.62
  5010.7 2194.45  5050.8 2197.28  5118.6 2198.80  5262.5 2199.65  5270.0 2198.89
  5311.0 2198.78  5402.9 2200.08  5445.4 2199.54  5530.2 2202.35  5593.9 2201.68
  5813.1 2210.22  5890.9 2213.58  5905.0 2214.85  5912.1 2214.45  6021.2 2220.06
#Mann=3,-1,0
  4383.3    0.05       0  4961.6    0.05       0  4979.6    0.05       0
Bank Sta=4961.6,4979.6
Exp/Cntr=0.3,0.1

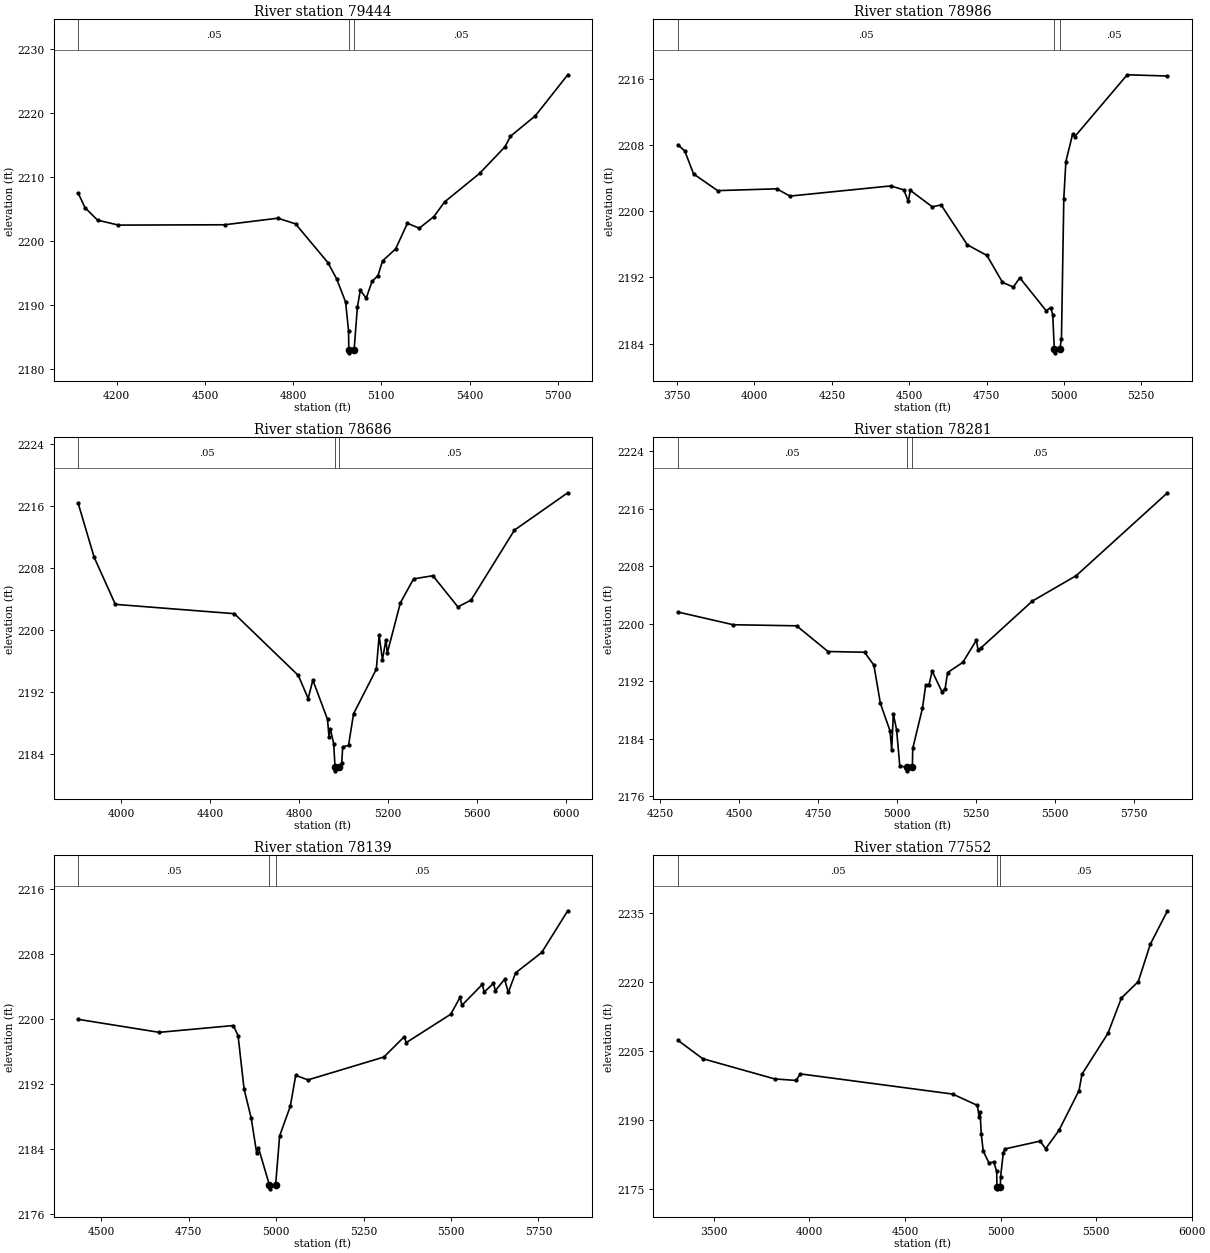
Type RM Length L Ch R = 1,79444,458,458,458
BEGIN DESCRIPTION:
Mapping XS 3ea0bba3
END DESCRIPTION:
XS GIS Cut Line= 4
      1309013.02      6926358.67      1309481.79      6925935.04
      1309509.57      6925320.46      1309634.29      6924922.06
#Sta/Elev= 30
  4069.3 2207.47  4092.4 2205.19  4135.0 2203.25  4206.0 2202.47  4566.9 2202.52
  4748.2 2203.55  4808.3 2202.66  4918.4 2196.60  4948.4 2194.03  4978.5 2190.44
  4988.5 2185.95  4989.5 2183.00  4991.0 2182.50  5007.5 2183.00  5018.5 2189.63
  5028.5 2192.27  5048.5 2191.05  5068.5 2193.66  5088.6 2194.59  5104.0 2196.86
  5148.6 2198.75  5188.7 2202.76  5228.7 2201.98  5278.8 2203.80  5315.1 2206.10
  5434.2 2210.55  5520.9 2214.74  5539.0 2216.36  5623.5 2219.55  5733.8 2225.97
#Mann=3,-1,0
  4069.3    0.05       0  4989.5    0.05       0  5007.5    0.05       0
Bank Sta=4989.5,5007.5
Exp/Cntr=0.3,0.1

Type RM Length L Ch R = 1,78986,300,300,300
BEGIN DESCRIPTION:
Mapping XS 36fe38c7
END DESCRIPTION:
XS GIS Cut Line= 3
      1309023.43      6926417.70      1309679.71      6925820.46
      1310140.76      6925300.48
#Sta/Elev= 30
  3752.6 2208.06  3774.7 2207.31  3803.1 2204.53  3880.8 2202.51  4072.0 2202.73
  4114.6 2201.85  4440.3 2203.08  4482.8 2202.60  4497.0 2201.22  4503.8 2202.54
  4574.7 2200.55  4603.1 2200.78  4687.8 2195.96  4751.4 2194.66  4801.6 2191.41
  4836.7 2190.84  4857.6 2191.96  4942.9 2187.97  4957.1 2188.36  4964.0 2187.50
  4969.0 2183.38  4970.5 2182.88  4987.0 2183.38  4992.2 2184.56  4999.8 2201.55
  5006.5 2206.03  5028.2 2209.33  5034.9 2209.03  5204.7 2216.53  5334.9 2216.38
#Mann=3,-1,0
  3752.6    0.05       0  4969.0    0.05       0  4987.0    0.05       0
Bank Sta=4969,4987
Exp/Cntr=0.3,0.1

Type RM Length L Ch R = 1,78686,405,405,405
BEGIN DESCRIPTION:
Buffalo Creek 89.0
END DESCRIPTION:
XS GIS Cut Line= 3
      1308954.98      6926488.02      1309955.00      6925838.00
      1310833.79      6925342.44
#Sta/Elev= 30
  3807.3 2216.30  3878.9 2209.36  3974.3 2203.29  4509.4 2202.09  4797.3 2194.13
  4841.5 2191.16  4862.6 2193.53  4928.5 2188.48  4935.1 2186.24  4941.1 2187.29
  4956.2 2185.36  4962.3 2182.35  4963.8 2181.85  4980.3 2182.35  4992.4 2182.90
  4997.0 2184.93  5023.0 2185.13  5045.6 2189.20  5148.1 2194.94  5160.7 2199.28
  5175.5 2196.16  5191.4 2198.75  5197.2 2197.01  5256.4 2203.50  5315.6 2206.57
  5402.3 2206.98  5515.0 2202.96  5574.0 2203.84  5769.2 2212.85  6008.9 2217.66
#Mann=3,-1,0
  3807.3    0.05       0  4962.3   0.033       0  4980.3    0.05       0
Bank Sta=4962.3,4980.3
Exp/Cntr=0.3,0.1

Type RM Length L Ch R = 1,78281,142,142,142
BEGIN DESCRIPTION:
Mapping XS a9b69f2b
END DESCRIPTION:
XS GIS Cut Line= 4
      1309405.44      6926494.04      1309756.10      6926237.12
      1309884.57      6926198.93      1310841.43      6926417.34
#Sta/Elev= 30
  4306.6 2201.63  4481.7 2199.86  4682.4 2199.71  4781.9 2196.13  4897.5 2196.03
  4927.1 2194.23  4947.6 2188.92  4978.3 2185.06  4983.5 2182.41  4988.6 2187.43
  4998.9 2185.25  5009.1 2180.20  5030.9 2180.01  5032.4 2179.51  5048.9 2180.01
  5050.1 2182.63  5080.9 2188.24  5091.2 2191.45  5101.4 2191.49  5111.7 2193.39
  5142.5 2190.53  5152.7 2190.96  5160.5 2193.20  5208.7 2194.62  5251.6 2197.69
  5256.8 2196.41  5265.5 2196.61  5428.7 2203.15  5567.9 2206.70  5856.8 2218.24
#Mann=3,-1,0
  4306.6    0.05       0  5030.9    0.05       0  5048.9    0.05       0
Bank Sta=5030.9,5048.9
Exp/Cntr=0.3,0.1

Type RM Length L Ch R = 1,78139,587,587,587
BEGIN DESCRIPTION:
Mapping XS b0f58db0
END DESCRIPTION:
XS GIS Cut Line= 4
      1309554.69      6926511.44      1309839.43      6926313.51
      1310315.13      6926400.32      1310856.79      6926577.40
#Sta/Elev= 30
  4433.8 2199.94  4665.6 2198.34  4877.7 2199.18  4891.1 2197.91  4908.2 2191.37
  4928.6 2187.79  4944.3 2183.47  4949.4 2184.12  4980.5 2179.58  4982.0 2179.08
  4998.5 2179.58  5009.9 2185.59  5040.4 2189.24  5055.9 2193.04  5091.2 2192.49
  5308.1 2195.30  5366.6 2197.81  5371.9 2197.07  5499.4 2200.57  5526.0 2202.65
  5531.2 2201.67  5589.7 2204.23  5595.0 2203.30  5621.6 2204.36  5626.9 2203.47
  5653.3 2204.87  5664.0 2203.26  5684.8 2205.66  5759.6 2208.17  5834.0 2213.30
#Mann=3,-1,0
  4433.8    0.05       0  4980.5    0.05       0  4998.5    0.05       0
Bank Sta=4980.5,4998.5
Exp/Cntr=0.3,0.1

Type RM Length L Ch R = 1,77552,518,518,518
BEGIN DESCRIPTION:
Buffalo Creek 87.0
END DESCRIPTION:
XS GIS Cut Line= 3
      1308633.34      6927071.08      1310305.00      6926838.00
      1311104.96      6926488.02
#Sta/Elev= 30
  3312.5 2207.31  3441.9 2203.31  3819.0 2198.90  3930.1 2198.57  3952.8 2200.00
  4749.9 2195.60  4879.2 2193.13  4888.0 2190.60  4893.0 2191.74  4899.4 2186.84
  4909.5 2183.17  4939.7 2180.59  4964.6 2180.81  4980.1 2178.73  4981.2 2175.45
  4982.7 2174.95  4999.2 2175.45  5000.3 2177.55  5014.7 2182.84  5022.2 2183.64
  5207.3 2185.35  5236.2 2183.70  5306.0 2187.71  5410.8 2196.37  5426.0 2199.92
  5562.1 2208.84  5632.2 2216.51  5720.7 2220.11  5783.5 2228.24  5873.5 2235.54
#Mann=3,-1,0
  3312.5    0.05       0  4981.2    0.05       0  4999.2    0.05       0
Bank Sta=4981.2,4999.2
Exp/Cntr=0.3,0.1

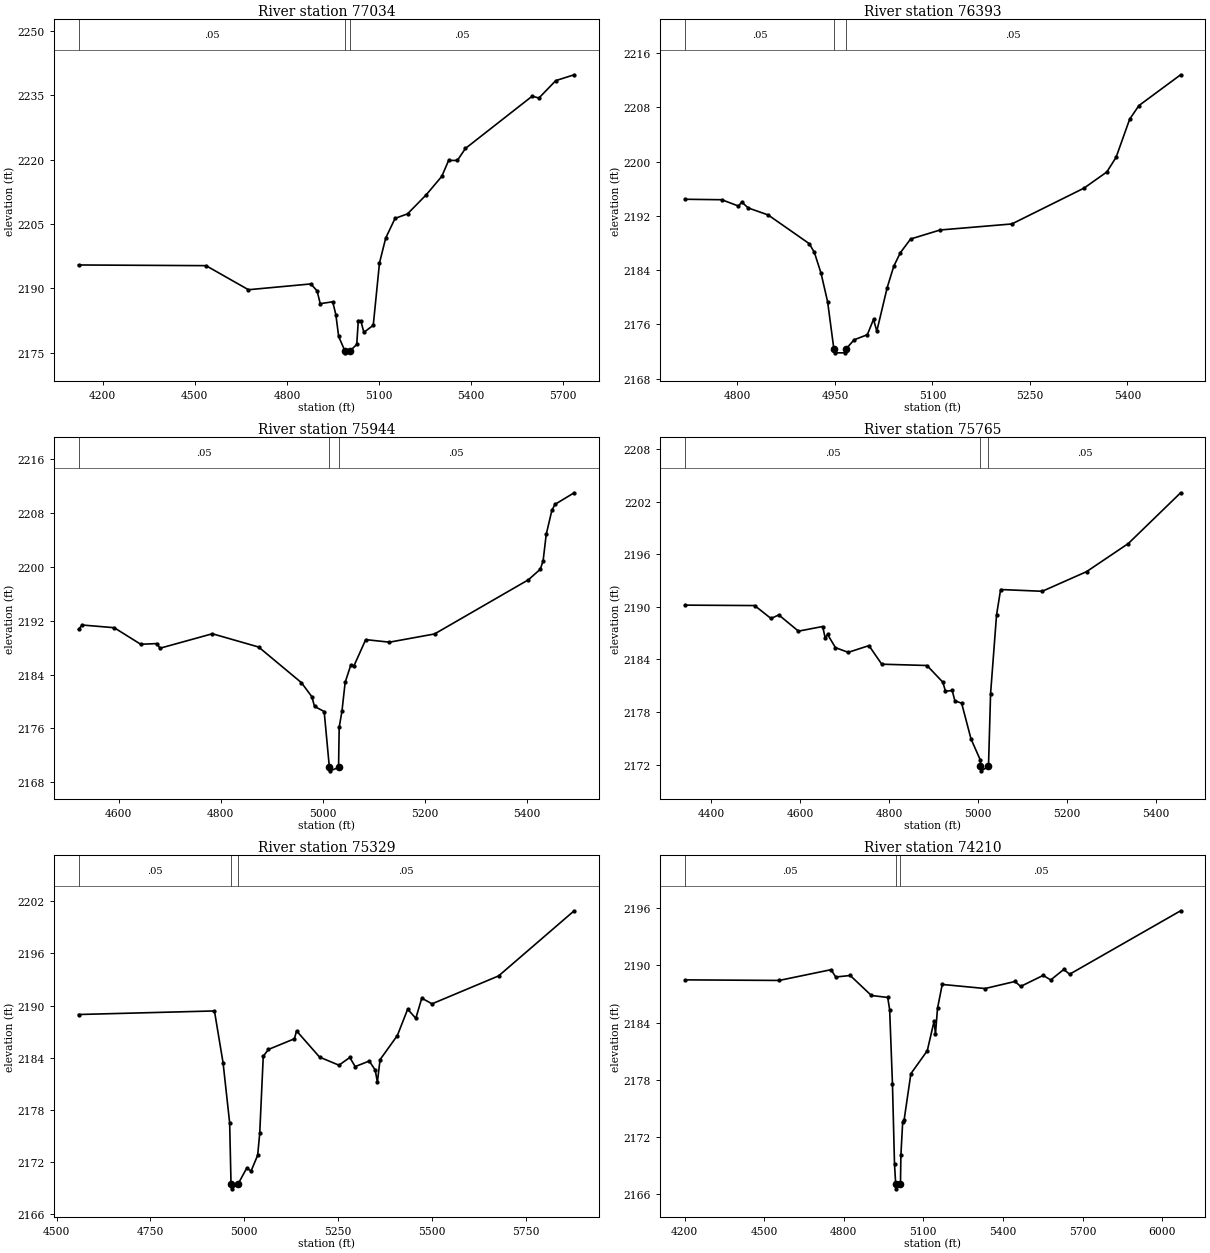
Type RM Length L Ch R = 1,77034,641,641,641
BEGIN DESCRIPTION:
Buffalo Creek 86.0
END DESCRIPTION:
XS GIS Cut Line= 3
      1309790.86      6927198.92      1310655.00      6927038.00
      1311380.01      6926913.00
#Sta/Elev= 30
  4121.0 2195.46  4536.4 2195.30  4674.5 2189.69  4877.9 2191.04  4898.3 2189.41
  4908.4 2186.44  4949.1 2186.88  4959.3 2183.89  4968.5 2178.79  4988.5 2175.48
  4990.0 2174.98  5006.5 2175.48  5027.4 2176.96  5032.5 2182.51  5040.6 2182.44
  5050.7 2179.76  5081.2 2181.40  5101.5 2195.94  5121.8 2201.74  5152.2 2206.32
  5192.8 2207.37  5253.7 2211.81  5304.4 2216.11  5326.7 2219.82  5355.2 2219.83
  5381.5 2222.62  5598.7 2234.79  5621.0 2234.38  5675.8 2238.43  5735.7 2239.79
#Mann=3,-1,0
  4121.0    0.05       0  4988.5    0.05       0  5006.5    0.05       0
Bank Sta=4988.5,5006.5
Exp/Cntr=0.3,0.1

Type RM Length L Ch R = 1,76393,449,449,449
BEGIN DESCRIPTION:
Buffalo Creek 85.0
END DESCRIPTION:
XS GIS Cut Line= 3
      1310329.43      6927658.58      1310860.27      6927556.57
      1311004.98      6927388.02
#Sta/Elev= 30
  4719.3 2194.44  4775.9 2194.37  4801.6 2193.44  4806.7 2194.03  4816.6 2193.16
  4847.2 2192.13  4910.6 2187.89  4918.4 2186.60  4928.6 2183.56  4938.8 2179.32
  4948.5 2172.30  4950.0 2171.80  4965.0 2171.80  4966.5 2172.30  4979.5 2173.72
  4999.9 2174.47  5009.4 2176.73  5014.5 2175.00  5030.5 2181.43  5040.6 2184.57
  5050.8 2186.57  5066.5 2188.58  5111.9 2189.91  5222.3 2190.80  5333.3 2196.08
  5368.4 2198.46  5382.7 2200.63  5403.6 2206.25  5417.8 2208.25  5482.0 2212.79
#Mann=3,-1,0
  4719.3    0.05       0  4948.5    0.05       0  4966.5    0.05       0
Bank Sta=4948.5,4966.5
Exp/Cntr=0.3,0.1

Type RM Length L Ch R = 1,75944,179,179,179
BEGIN DESCRIPTION:
Buffalo Creek 84.0
END DESCRIPTION:
XS GIS Cut Line= 3
      1310348.28      6928030.72      1310805.00      6927888.00
      1311004.98      6927438.04
#Sta/Elev= 30
  4521.5 2190.71  4528.5 2191.37  4591.4 2190.97  4643.3 2188.51  4675.2 2188.61
  4681.0 2187.92  4783.7 2190.07  4874.3 2188.10  4958.1 2182.81  4978.5 2180.73
  4983.8 2179.28  5002.7 2178.52  5012.9 2170.21  5014.4 2169.71  5030.9 2170.21
  5032.1 2176.15  5037.6 2178.61  5043.8 2182.84  5054.7 2185.39  5060.9 2185.28
  5084.1 2189.20  5130.6 2188.82  5218.9 2190.04  5402.8 2198.09  5426.1 2199.66
  5431.6 2200.93  5437.7 2204.85  5448.7 2208.39  5454.8 2209.29  5492.4 2211.01
#Mann=3,-1,0
  4521.5    0.05       0  5012.9    0.05       0  5030.9    0.05       0
Bank Sta=5012.9,5030.9
Exp/Cntr=0.3,0.1

Type RM Length L Ch R = 1,75765,436,436,436
BEGIN DESCRIPTION:
Mapping XS 4c8648b4
END DESCRIPTION:
XS GIS Cut Line= 3
      1310391.85      6928300.70      1310884.93      6928081.95
      1311197.43      6927599.31
#Sta/Elev= 30
  4341.5 2190.20  4498.1 2190.15  4534.8 2188.68  4552.5 2189.08  4596.6 2187.23
  4651.1 2187.76  4656.6 2186.48  4662.2 2186.85  4679.8 2185.35  4708.6 2184.81
  4755.1 2185.58  4783.9 2183.46  4885.6 2183.31  4921.2 2181.41  4927.2 2180.37
  4942.3 2180.46  4948.3 2179.28  4963.5 2179.01  4984.6 2174.93  5005.7 2172.50
  5005.9 2171.79  5007.4 2171.29  5023.9 2171.79  5028.6 2180.10  5042.0 2189.08
  5051.2 2191.98  5144.8 2191.78  5244.4 2194.02  5338.3 2197.23  5455.9 2203.02
#Mann=3,-1,0
  4341.5    0.05       0  5005.9    0.05       0  5023.9    0.05       0
Bank Sta=5005.9,5023.9
Exp/Cntr=0.3,0.1

Type RM Length L Ch R = 1,75329,1119,1119,1119
BEGIN DESCRIPTION:
Buffalo Creek 83.0
END DESCRIPTION:
XS GIS Cut Line= 4
      1310457.88      6928522.90      1310855.00      6928340.08
      1311026.11      6928262.83      1311369.85      6927658.69
#Sta/Elev= 30
  4558.6 2188.98  4920.6 2189.39  4943.6 2183.42  4961.1 2176.52  4964.8 2169.43
  4966.3 2168.93  4982.8 2169.43  5006.7 2171.32  5018.1 2170.97  5035.7 2172.79
  5041.2 2175.32  5050.6 2184.18  5064.3 2184.96  5133.7 2186.19  5139.2 2187.10
  5200.6 2184.08  5252.2 2183.15  5281.1 2184.04  5295.4 2182.99  5332.9 2183.63
  5348.8 2182.59  5354.5 2181.20  5361.7 2183.79  5407.7 2186.56  5435.2 2189.59
  5456.9 2188.54  5472.7 2190.86  5500.1 2190.21  5677.4 2193.42  5878.6 2200.91
#Mann=3,-1,0
  4558.6    0.05       0  4964.8    0.05       0  4982.8    0.05       0
Bank Sta=4964.8,4982.8
Exp/Cntr=0.3,0.1

Type RM Length L Ch R = 1,74210,434,434,434
BEGIN DESCRIPTION:
Buffalo Creek 82.0
END DESCRIPTION:
XS GIS Cut Line= 4
      1310476.73      6928565.99      1311061.66      6928511.43
      1311480.00      6928363.00      1312106.59      6927808.45
#Sta/Elev= 30
  4201.6 2188.49  4556.6 2188.43  4752.2 2189.56  4769.7 2188.79  4824.4 2188.95
  4904.0 2186.85  4965.7 2186.64  4973.0 2185.37  4983.6 2177.53  4991.3 2169.12
  4995.8 2167.03  4997.3 2166.53  5013.8 2167.03  5015.4 2170.09  5022.2 2173.60
  5027.5 2173.76  5053.0 2178.63  5114.8 2181.04  5140.3 2184.13  5145.7 2182.81
  5153.4 2185.50  5171.2 2188.01  5332.5 2187.58  5445.4 2188.32  5466.7 2187.80
  5551.6 2188.96  5580.1 2188.48  5629.4 2189.59  5651.2 2189.08  6069.7 2195.75
#Mann=3,-1,0
  4201.6    0.05       0  4995.8    0.05       0  5013.8    0.05       0
Bank Sta=4995.8,5013.8
Exp/Cntr=0.3,0.1

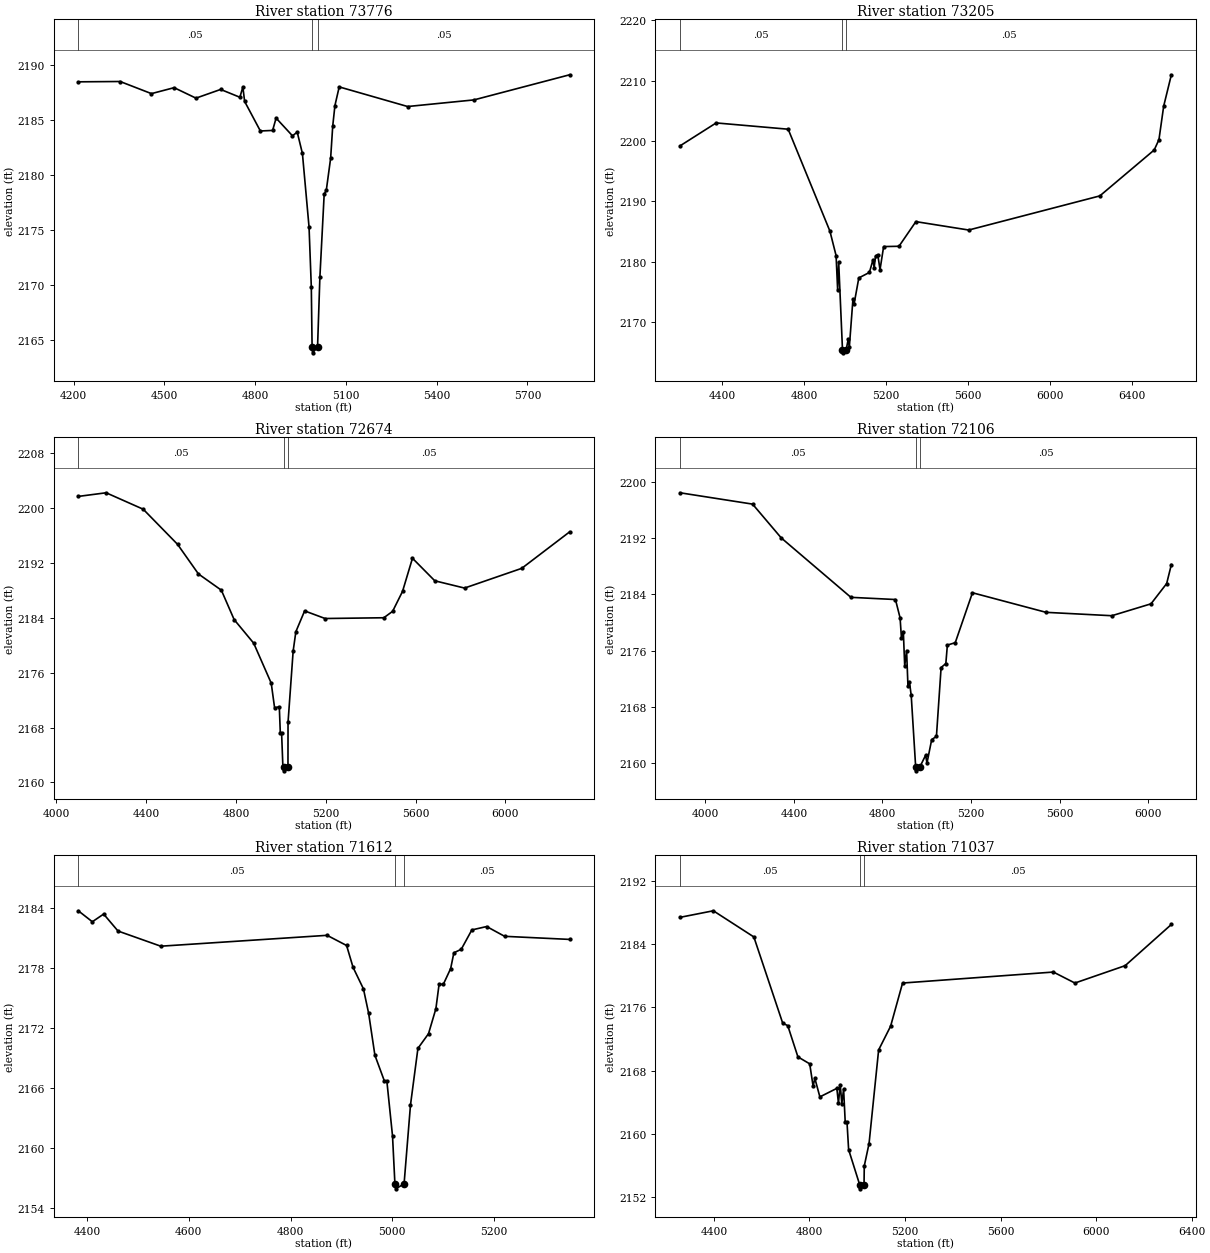
Type RM Length L Ch R = 1,73776,571,571,571
BEGIN DESCRIPTION:
Buffalo Creek 81.0
END DESCRIPTION:
XS GIS Cut Line= 4
      1310856.79      6928587.81      1311322.07      6928841.29
      1311555.00      6928738.00      1312130.53      6928126.62
#Sta/Elev= 30
  4215.1 2188.46  4353.4 2188.49  4456.9 2187.39  4531.9 2187.93  4604.1 2186.98
  4685.7 2187.77  4749.3 2187.06  4759.1 2187.99  4765.0 2186.68  4817.0 2184.00
  4857.5 2184.05  4869.0 2185.17  4923.2 2183.56  4938.8 2183.90  4956.0 2181.96
  4977.9 2175.29  4985.4 2169.86  4988.0 2164.37  4989.5 2163.87  5006.0 2164.37
  5013.7 2170.71  5027.9 2178.24  5035.2 2178.67  5049.3 2181.53  5056.2 2184.45
  5063.5 2186.31  5077.6 2188.00  5303.8 2186.22  5523.1 2186.82  5839.4 2189.10
#Mann=3,-1,0
  4215.1    0.05       0  4988.0    0.05       0  5006.0    0.05       0
Bank Sta=4988,5006
Exp/Cntr=0.3,0.1

Type RM Length L Ch R = 1,73205,531,531,531
BEGIN DESCRIPTION:
Buffalo Creek 80.0
END DESCRIPTION:
XS GIS Cut Line= 4
      1311448.91      6929761.36      1311755.00      6929488.00
      1311805.00      6929088.00      1312454.99      6927638.02
#Sta/Elev= 30
  4192.3 2199.19  4369.0 2202.99  4721.1 2201.95  4925.2 2185.08  4955.4 2181.03
  4963.0 2175.39  4968.0 2180.00  4986.7 2165.43  4988.2 2164.93  5004.7 2165.43
  5014.6 2167.15  5020.1 2165.84  5037.8 2173.80  5043.3 2173.00  5066.5 2177.33
  5118.3 2178.24  5136.0 2180.35  5141.5 2179.00  5148.3 2180.94  5159.2 2181.18
  5170.2 2178.70  5187.9 2182.52  5262.9 2182.57  5345.5 2186.65  5603.9 2185.26
  6245.0 2190.91  6510.9 2198.51  6534.1 2200.22  6557.3 2205.78  6594.8 2210.96
#Mann=3,-1,0
  4192.3    0.05       0  4986.7    0.05       0  5004.7    0.05       0
Bank Sta=4986.7,5004.7
Exp/Cntr=0.3,0.1

Type RM Length L Ch R = 1,72674,568,568,568
BEGIN DESCRIPTION:
Buffalo Creek 79.0
END DESCRIPTION:
XS GIS Cut Line= 3
      1311702.61      6929688.44      1312205.00      6928938.00
      1312752.93      6927774.44
#Sta/Elev= 30
  4097.4 2201.72  4221.4 2202.25  4386.7 2199.85  4539.6 2194.73  4632.7 2190.41
  4734.8 2188.04  4791.8 2183.75  4878.9 2180.31  4957.0 2174.48  4972.0 2170.88
  4993.0 2171.04  4997.5 2167.21  5003.2 2167.21  5009.1 2162.21  5013.6 2162.19
  5015.1 2161.69  5031.6 2162.19  5031.9 2168.76  5054.7 2179.16  5066.8 2181.99
  5105.8 2185.02  5197.0 2183.91  5458.7 2184.02  5497.9 2184.96  5542.1 2187.87
  5586.3 2192.70  5685.8 2189.41  5818.4 2188.35  6073.3 2191.23  6286.6 2196.55
#Mann=3,-1,0
  4097.4    0.05       0  5013.6    0.05       0  5031.6    0.05       0
Bank Sta=5013.6,5031.6
Exp/Cntr=0.3,0.1

Type RM Length L Ch R = 1,72106,494,494,494
BEGIN DESCRIPTION:
Buffalo Creek 78.0
END DESCRIPTION:
XS GIS Cut Line= 3
      1311594.11      6929944.53      1312505.00      6929288.00
      1313254.99      6928488.01
#Sta/Elev= 30
  3885.9 2198.41  4213.6 2196.80  4343.1 2192.00  4657.8 2183.56  4859.0 2183.25
  4879.9 2180.65  4886.0 2177.82  4894.6 2178.70  4900.8 2173.81  4909.3 2176.01
  4915.5 2170.94  4922.4 2171.49  4930.2 2169.63  4950.4 2159.42  4951.9 2158.92
  4968.4 2159.42  4995.2 2161.13  5001.4 2160.03  5022.7 2163.36  5044.1 2163.81
  5065.2 2173.59  5086.6 2174.16  5093.5 2176.78  5129.1 2177.12  5206.8 2184.21
  5539.4 2181.43  5836.4 2180.95  6013.3 2182.64  6084.1 2185.52  6105.3 2188.22
#Mann=3,-1,0
  3885.9    0.05       0  4950.4    0.05       0  4968.4    0.05       0
Bank Sta=4950.4,4968.4
Exp/Cntr=0.3,0.1

Type RM Length L Ch R = 1,71612,575,575,575
BEGIN DESCRIPTION:
Buffalo Creek 77.0
END DESCRIPTION:
XS GIS Cut Line= 3
      1312176.25      6929789.20      1312769.99      6929667.68
      1312988.74      6929382.96
#Sta/Elev= 30
  4383.1 2183.77  4410.7 2182.67  4432.9 2183.44  4461.1 2181.74  4545.1 2180.22
  4871.8 2181.31  4910.1 2180.29  4922.8 2178.10  4943.2 2175.94  4953.4 2173.49
  4965.7 2169.29  4984.1 2166.74  4989.1 2166.74  5000.3 2161.20  5005.0 2156.40
  5006.5 2155.90  5023.0 2156.40  5035.6 2164.31  5050.2 2169.98  5071.0 2171.45
  5085.5 2173.96  5091.8 2176.42  5100.0 2176.39  5114.5 2177.98  5120.8 2179.56
  5135.3 2179.91  5156.1 2181.85  5185.2 2182.19  5220.5 2181.21  5348.2 2180.90
#Mann=3,-1,0
  4383.1    0.05       0  5005.0    0.05       0  5023.0    0.05       0
Bank Sta=5005,5023
Exp/Cntr=0.3,0.1

Type RM Length L Ch R = 1,71037,683,683,683
BEGIN DESCRIPTION:
Buffalo Creek 76.0
END DESCRIPTION:
XS GIS Cut Line= 3
      1312707.66      6930337.57      1313255.00      6929838.00
      1313332.67      6928525.04
#Sta/Elev= 30
  4258.5 2187.39  4397.9 2188.22  4567.5 2184.91  4688.2 2174.01  4709.4 2173.69
  4751.9 2169.74  4801.3 2168.86  4815.4 2166.04  4822.9 2167.01  4843.8 2164.68
  4914.8 2165.76  4921.5 2163.88  4928.9 2166.24  4935.7 2163.83  4943.1 2165.66
  4949.9 2161.45  4957.3 2161.49  4964.1 2158.01  5010.6 2153.55  5012.1 2153.05
  5028.6 2153.55  5029.6 2155.94  5049.6 2158.78  5089.7 2170.62  5139.8 2173.62
  5189.9 2179.08  5821.0 2180.47  5911.1 2179.08  6121.5 2181.28  6314.8 2186.49
#Mann=3,-1,0
  4258.5    0.05       0  5010.6   0.033       0  5028.6    0.05       0
Bank Sta=5010.6,5028.6
Exp/Cntr=0.3,0.1