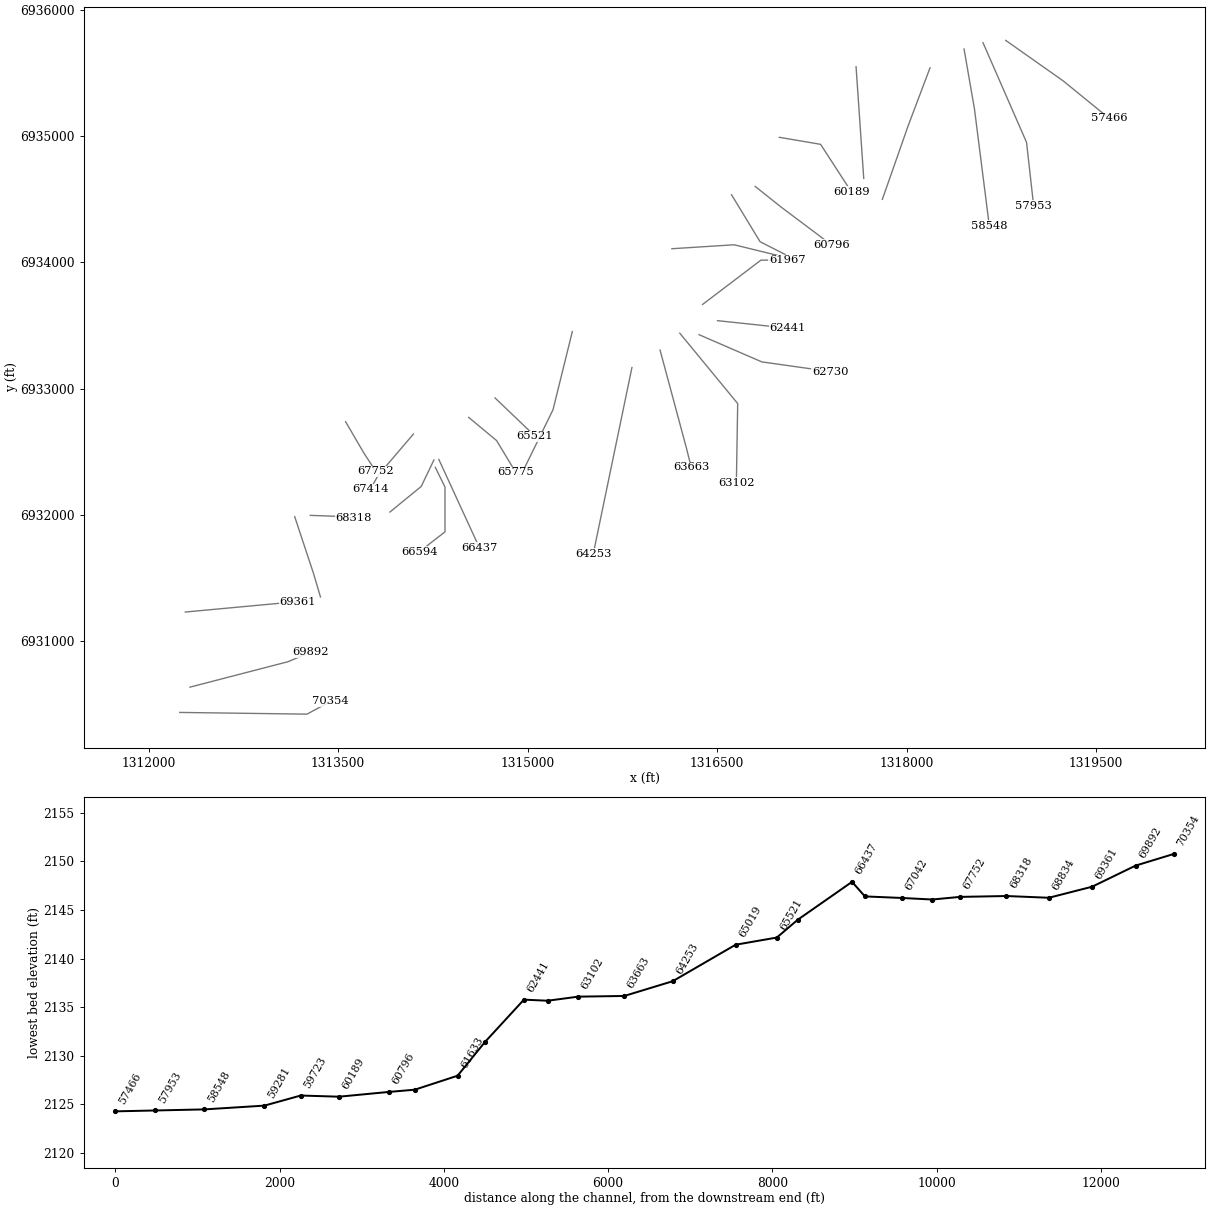
HEC-RAS study Buffalo Creek.prj: Buffalo Creek Base Level Engineering

--- Buffalo Creek.g01 (geometry) --- (continued)

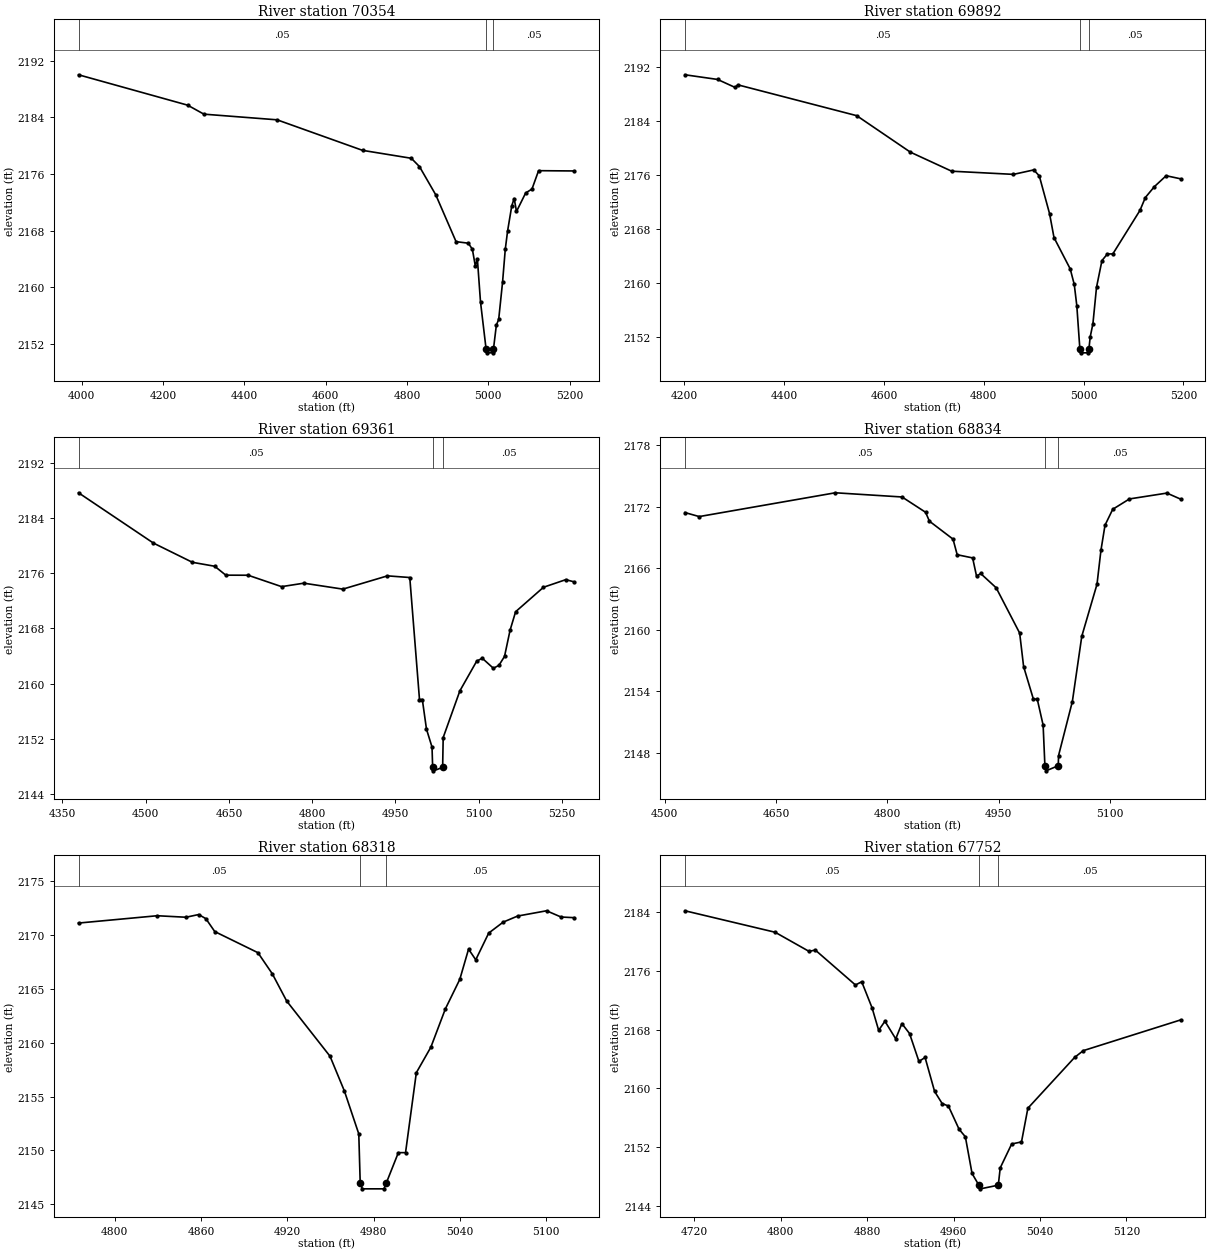
Type RM Length L Ch R = 1,70354,462,462,462
BEGIN DESCRIPTION:
Buffalo Creek 75.0
END DESCRIPTION:
XS GIS Cut Line= 3
      1312246.74      6930436.17      1313254.04      6930422.60
      1313439.96      6930523.01
#Sta/Elev= 30
  3992.6 2190.03  4260.9 2185.74  4300.9 2184.47  4480.9 2183.67  4690.9 2179.36
  4810.9 2178.24  4830.9 2177.07  4870.9 2173.09  4920.9 2166.47  4951.0 2166.25
  4961.0 2165.40  4968.3 2163.02  4973.3 2164.05  4981.0 2157.96  4994.8 2151.27
  4996.3 2150.77  5011.3 2150.77  5012.8 2151.27  5020.0 2154.69  5025.7 2155.48
  5035.2 2160.73  5041.9 2165.38  5047.6 2167.97  5057.9 2171.54  5063.8 2172.56
  5069.5 2170.73  5092.0 2173.34  5107.6 2173.90  5123.8 2176.49  5211.3 2176.45
#Mann=3,-1,0
  3992.6    0.05       0  4994.8    0.05       0  5012.8    0.05       0
Bank Sta=4994.8,5012.8
Exp/Cntr=0.3,0.1

Type RM Length L Ch R = 1,69892,531,531,531
BEGIN DESCRIPTION:
Buffalo Creek 74.0
END DESCRIPTION:
XS GIS Cut Line= 3
      1312327.67      6930636.38      1313105.00      6930838.00
      1313279.96      6930912.98
#Sta/Elev= 30
  4201.2 2190.79  4266.5 2190.10  4301.8 2188.91  4307.1 2189.30  4545.4 2184.73
  4653.0 2179.32  4735.7 2176.50  4859.6 2176.03  4900.2 2176.69  4911.3 2175.81
  4931.9 2170.21  4940.8 2166.66  4973.3 2162.02  4981.4 2159.72  4986.5 2156.58
  4992.7 2150.08  4994.2 2149.58  5009.2 2149.58  5010.7 2150.08  5013.3 2151.92
  5018.8 2153.89  5026.0 2159.29  5036.9 2163.25  5047.8 2164.24  5058.7 2164.24
  5113.1 2170.69  5123.9 2172.60  5142.1 2174.22  5165.6 2175.83  5194.6 2175.37
#Mann=3,-1,0
  4201.2    0.05       0  4992.7    0.05       0  5010.7    0.05       0
Bank Sta=4992.7,5010.7
Exp/Cntr=0.3,0.1

Type RM Length L Ch R = 1,69361,527,527,527
BEGIN DESCRIPTION:
Buffalo Creek 73.0
END DESCRIPTION:
XS GIS Cut Line= 3
      1312290.70      6931230.98      1312905.00      6931288.00
      1313180.03      6931313.00
#Sta/Elev= 30
  4379.0 2187.63  4514.0 2180.35  4584.2 2177.57  4624.4 2177.00  4644.4 2175.71
  4684.6 2175.70  4744.9 2174.05  4785.0 2174.55  4855.3 2173.69  4935.7 2175.61
  4975.9 2175.37  4993.4 2157.72  4998.5 2157.72  5006.0 2153.43  5016.0 2150.83
  5017.1 2147.90  5018.6 2147.40  5035.1 2147.90  5036.1 2152.22  5066.2 2158.98
  5096.4 2163.26  5106.4 2163.70  5126.5 2162.24  5136.5 2162.66  5146.6 2163.95
  5156.6 2167.74  5166.6 2170.42  5216.8 2173.96  5257.0 2175.06  5272.1 2174.74
#Mann=3,-1,0
  4379.0    0.05       0  5017.1    0.05       0  5035.1    0.05       0
Bank Sta=5017.1,5035.1
Exp/Cntr=0.3,0.1

Type RM Length L Ch R = 1,68834,516,516,516
BEGIN DESCRIPTION:
Buffalo Creek 72.0
END DESCRIPTION:
XS GIS Cut Line= 3
      1313156.62      6931986.21      1313305.00      6931538.00
      1313360.63      6931350.31
#Sta/Elev= 30
  4527.3 2171.44  4546.5 2171.05  4729.9 2173.37  4819.8 2172.96  4851.5 2171.47
  4856.7 2170.60  4888.5 2168.85  4894.1 2167.33  4914.9 2167.02  4920.2 2165.24
  4925.7 2165.50  4946.6 2164.11  4978.3 2159.69  4983.6 2156.43  4996.8 2153.25
  5002.0 2153.25  5009.9 2150.72  5012.3 2146.76  5013.8 2146.26  5030.3 2146.76
  5030.7 2147.75  5049.3 2153.02  5062.0 2159.38  5082.5 2164.45  5087.8 2167.75
  5093.3 2170.21  5103.7 2171.76  5126.2 2172.77  5176.7 2173.34  5195.2 2172.75
#Mann=3,-1,0
  4527.3    0.05       0  5012.3    0.05       0  5030.3    0.05       0
Bank Sta=5012.3,5030.3
Exp/Cntr=0.3,0.1

Type RM Length L Ch R = 1,68318,566,566,566
BEGIN DESCRIPTION:
Buffalo Creek 71.0
END DESCRIPTION:
XS GIS Cut Line= 3
      1313280.37      6931996.18      1313505.00      6931988.00
      1313624.05      6931975.35
#Sta/Elev= 30
  4774.9 2171.11  4829.6 2171.79  4849.6 2171.65  4858.4 2171.90  4863.4 2171.52
  4869.6 2170.32  4899.6 2168.36  4909.6 2166.40  4919.6 2163.87  4949.7 2158.75
  4959.7 2155.52  4969.7 2151.54  4970.7 2146.94  4972.2 2146.44  4987.2 2146.44
  4988.7 2146.94  4997.2 2149.80  5002.2 2149.80  5009.7 2157.22  5019.8 2159.59
  5029.9 2163.15  5039.9 2165.88  5046.0 2168.69  5051.0 2167.70  5060.0 2170.18
  5070.1 2171.20  5080.1 2171.76  5100.2 2172.25  5110.3 2171.67  5119.4 2171.61
#Mann=3,-1,0
  4774.9    0.05       0  4970.7    0.05       0  4988.7    0.05       0
Bank Sta=4970.7,4988.7
Exp/Cntr=0.3,0.1

Type RM Length L Ch R = 1,67752,338,338,338
BEGIN DESCRIPTION:
Buffalo Creek 70.0
END DESCRIPTION:
XS GIS Cut Line= 3
      1313559.55      6932737.78      1313705.00      6932488.00
      1313798.56      6932346.00
#Sta/Elev= 30
  4711.2 2184.16  4794.7 2181.24  4826.1 2178.64  4831.9 2178.82  4869.1 2174.07
  4874.9 2174.51  4884.5 2170.96  4890.6 2167.91  4896.4 2169.14  4906.4 2166.75
  4912.1 2168.82  4919.2 2167.47  4927.9 2163.68  4933.6 2164.21  4942.4 2159.60
  4949.4 2157.95  4955.2 2157.61  4965.1 2154.45  4970.9 2153.43  4977.1 2148.44
  4983.4 2146.85  4984.9 2146.35  5001.4 2146.85  5003.2 2149.20  5013.8 2152.45
  5022.9 2152.73  5028.8 2157.31  5072.1 2164.22  5080.1 2165.14  5170.3 2169.32
#Mann=3,-1,0
  4711.2    0.05       0  4983.4    0.05       0  5001.4    0.05       0
Bank Sta=4983.4,5001.4
Exp/Cntr=0.3,0.1

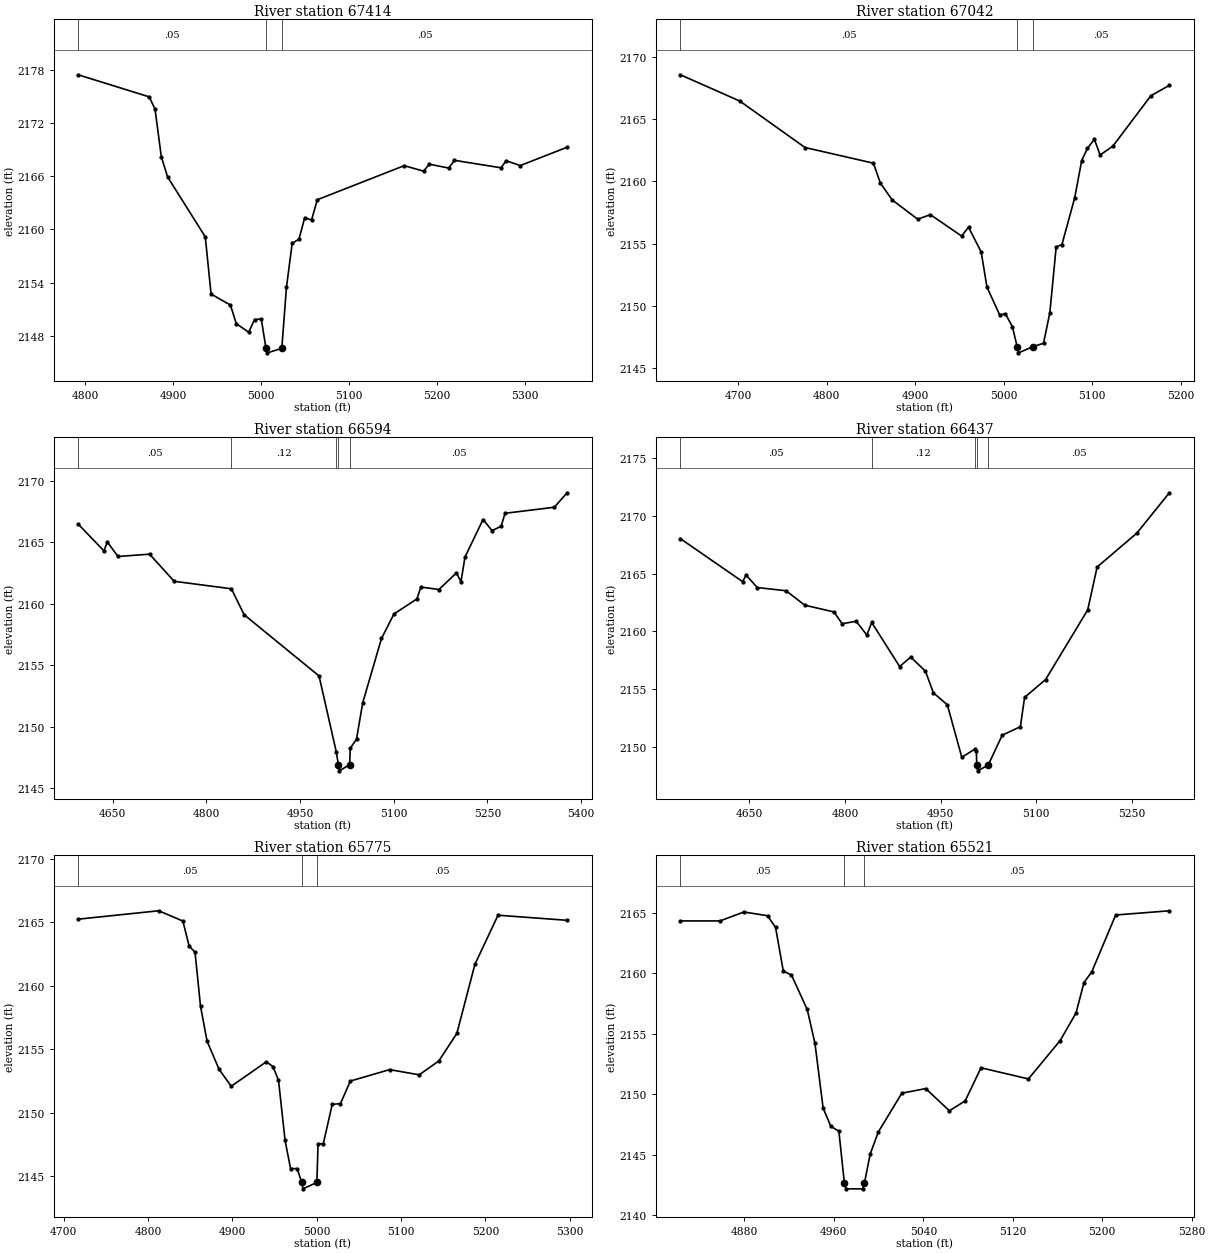
Type RM Length L Ch R = 1,67414,372,372,372
BEGIN DESCRIPTION:
Mapping XS f65db8f9
END DESCRIPTION:
XS GIS Cut Line= 3
      1314096.39      6932639.91      1313815.13      6932310.04
      1313756.27      6932202.72
#Sta/Elev= 30
  4792.3 2177.44  4873.1 2174.95  4879.7 2173.55  4886.8 2168.21  4894.0 2165.91
  4936.8 2159.16  4943.4 2152.71  4965.4 2151.47  4972.0 2149.38  4986.2 2148.40
  4992.8 2149.84  5000.5 2149.90  5005.8 2146.58  5007.3 2146.08  5023.8 2146.58
  5029.1 2153.47  5035.6 2158.43  5043.3 2158.90  5049.9 2161.34  5057.6 2161.06
  5064.2 2163.35  5163.0 2167.19  5185.0 2166.57  5191.5 2167.36  5213.5 2166.92
  5220.1 2167.79  5273.1 2166.95  5278.8 2167.75  5294.9 2167.20  5348.2 2169.27
#Mann=3,-1,0
  4792.3    0.05       0  5005.8    0.05       0  5023.8    0.05       0
Bank Sta=5005.8,5023.8
Exp/Cntr=0.3,0.1

Type RM Length L Ch R = 1,67042,448,448,448
BEGIN DESCRIPTION:
Buffalo Creek 69.5
END DESCRIPTION:
XS GIS Cut Line= 3
      1314258.47      6932434.65      1314158.17      6932225.18
      1313910.54      6932022.57
#Sta/Elev= 30
  4634.9 2168.57  4702.0 2166.46  4775.6 2162.73  4852.9 2161.47  4860.7 2159.87
  4874.1 2158.52  4902.9 2156.97  4917.2 2157.34  4952.4 2155.62  4960.3 2156.33
  4974.6 2154.34  4981.1 2151.52  4995.5 2149.28  5001.9 2149.38  5009.8 2148.35
  5015.2 2146.74  5016.7 2146.24  5033.2 2146.74  5045.0 2147.01  5052.1 2149.45
  5059.3 2154.75  5065.8 2154.94  5080.2 2158.69  5088.1 2161.68  5094.5 2162.65
  5102.4 2163.39  5108.9 2162.13  5123.2 2162.83  5166.3 2166.89  5187.1 2167.72
#Mann=3,-1,0
  4634.9    0.05       0  5015.2    0.05       0  5033.2    0.05       0
Bank Sta=5015.2,5033.2
Exp/Cntr=0.3,0.1

Type RM Length L Ch R = 1,66594,157,157,157
BEGIN DESCRIPTION:
Mapping XS 4d7350b4
END DESCRIPTION:
XS GIS Cut Line= 4
      1314269.97      6932376.04      1314346.38      6932219.76
      1314346.38      6931865.59      1314145.00      6931709.36
#Sta/Elev= 30
  4594.8 2166.50  4636.0 2164.32  4641.6 2165.04  4658.5 2163.86  4709.1 2164.05
  4748.5 2161.84  4840.2 2161.23  4860.5 2159.12  4980.5 2154.13  5008.0 2147.97
  5011.5 2146.90  5013.0 2146.40  5029.5 2146.90  5030.5 2148.24  5040.5 2148.98
  5050.5 2151.95  5080.5 2157.18  5100.5 2159.18  5137.2 2160.40  5143.6 2161.37
  5172.5 2161.17  5200.6 2162.53  5207.8 2161.80  5214.2 2163.81  5243.1 2166.87
  5257.6 2165.97  5272.1 2166.32  5278.4 2167.38  5357.2 2167.87  5377.8 2169.05
#Mann=5,-1,0
  4594.8    0.05       0  4840.2    0.12       0  5008.0    0.05       0
  5011.5    0.07       0  5029.5    0.05       0
Bank Sta=5011.5,5029.5
Exp/Cntr=0.3,0.1

Type RM Length L Ch R = 1,66437,662,662,662
BEGIN DESCRIPTION:
Buffalo Creek 69.0
END DESCRIPTION:
XS GIS Cut Line= 2
      1314297.76      6932438.53      1314618.07      6931741.62
#Sta/Elev= 30
  4541.7 2168.04  4639.3 2164.31  4644.8 2164.88  4662.3 2163.80  4707.4 2163.52
  4736.8 2162.27  4782.7 2161.68  4795.4 2160.66  4817.4 2160.87  4834.2 2159.68
  4841.8 2160.77  4885.6 2156.95  4903.1 2157.77  4926.1 2156.54  4938.5 2154.67
  4960.5 2153.62  4983.1 2149.08  5003.3 2149.77  5006.0 2149.62  5006.5 2148.40
  5008.0 2147.90  5024.5 2148.40  5046.5 2150.99  5075.0 2151.73  5081.6 2154.27
  5114.6 2155.82  5180.6 2161.86  5195.4 2165.58  5257.7 2168.52  5308.7 2172.02
#Mann=5,-1,0
  4541.7    0.05       0  4841.8    0.12       0  5003.3    0.05       0
  5006.5    0.07       0  5024.5    0.05       0
Bank Sta=5006.5,5024.5
Exp/Cntr=0.3,0.1

Type RM Length L Ch R = 1,65775,254,254,254
BEGIN DESCRIPTION:
Buffalo Creek 68.0
END DESCRIPTION:
XS GIS Cut Line= 3
      1314533.89      6932771.83      1314755.00      6932588.00
      1314905.43      6932337.78
#Sta/Elev= 30
  4717.3 2165.23  4812.8 2165.89  4841.4 2165.08  4848.8 2163.11  4855.8 2162.62
  4862.3 2158.37  4870.1 2155.61  4884.4 2153.39  4898.7 2152.07  4940.4 2154.00
  4948.2 2153.61  4954.7 2152.56  4962.5 2147.81  4969.0 2145.59  4976.9 2145.58
  4982.2 2144.49  4983.7 2143.99  5000.2 2144.49  5001.6 2147.54  5007.8 2147.54
  5018.4 2150.64  5028.2 2150.71  5039.9 2152.48  5086.4 2153.38  5121.5 2152.97
  5144.7 2154.06  5166.1 2156.23  5187.5 2161.67  5214.9 2165.54  5296.8 2165.14
#Mann=3,-1,0
  4717.3    0.05       0  4982.2    0.05       0  5000.2    0.05       0
Bank Sta=4982.2,5000.2
Exp/Cntr=0.3,0.1

Type RM Length L Ch R = 1,65521,502,502,502
BEGIN DESCRIPTION:
Mapping XS d12216ef
END DESCRIPTION:
XS GIS Cut Line= 2
      1314742.55      6932925.71      1315058.56      6932623.59
#Sta/Elev= 30
  4822.8 2164.34  4858.2 2164.34  4879.6 2165.08  4900.7 2164.77  4907.9 2163.80
  4914.8 2160.19  4922.1 2159.86  4936.2 2157.01  4943.1 2154.22  4950.4 2148.85
  4957.3 2147.33  4964.5 2146.93  4969.4 2142.66  4970.9 2142.16  4985.9 2142.16
  4987.4 2142.66  4992.5 2145.04  4999.8 2146.87  5020.8 2150.08  5042.2 2150.46
  5063.3 2148.62  5077.4 2149.44  5091.6 2152.18  5134.0 2151.26  5162.4 2154.44
  5176.5 2156.71  5183.7 2159.24  5190.7 2160.14  5212.0 2164.83  5260.0 2165.18
#Mann=3,-1,0
  4822.8    0.05       0  4969.4    0.05       0  4987.4    0.05       0
Bank Sta=4969.4,4987.4
Exp/Cntr=0.3,0.1

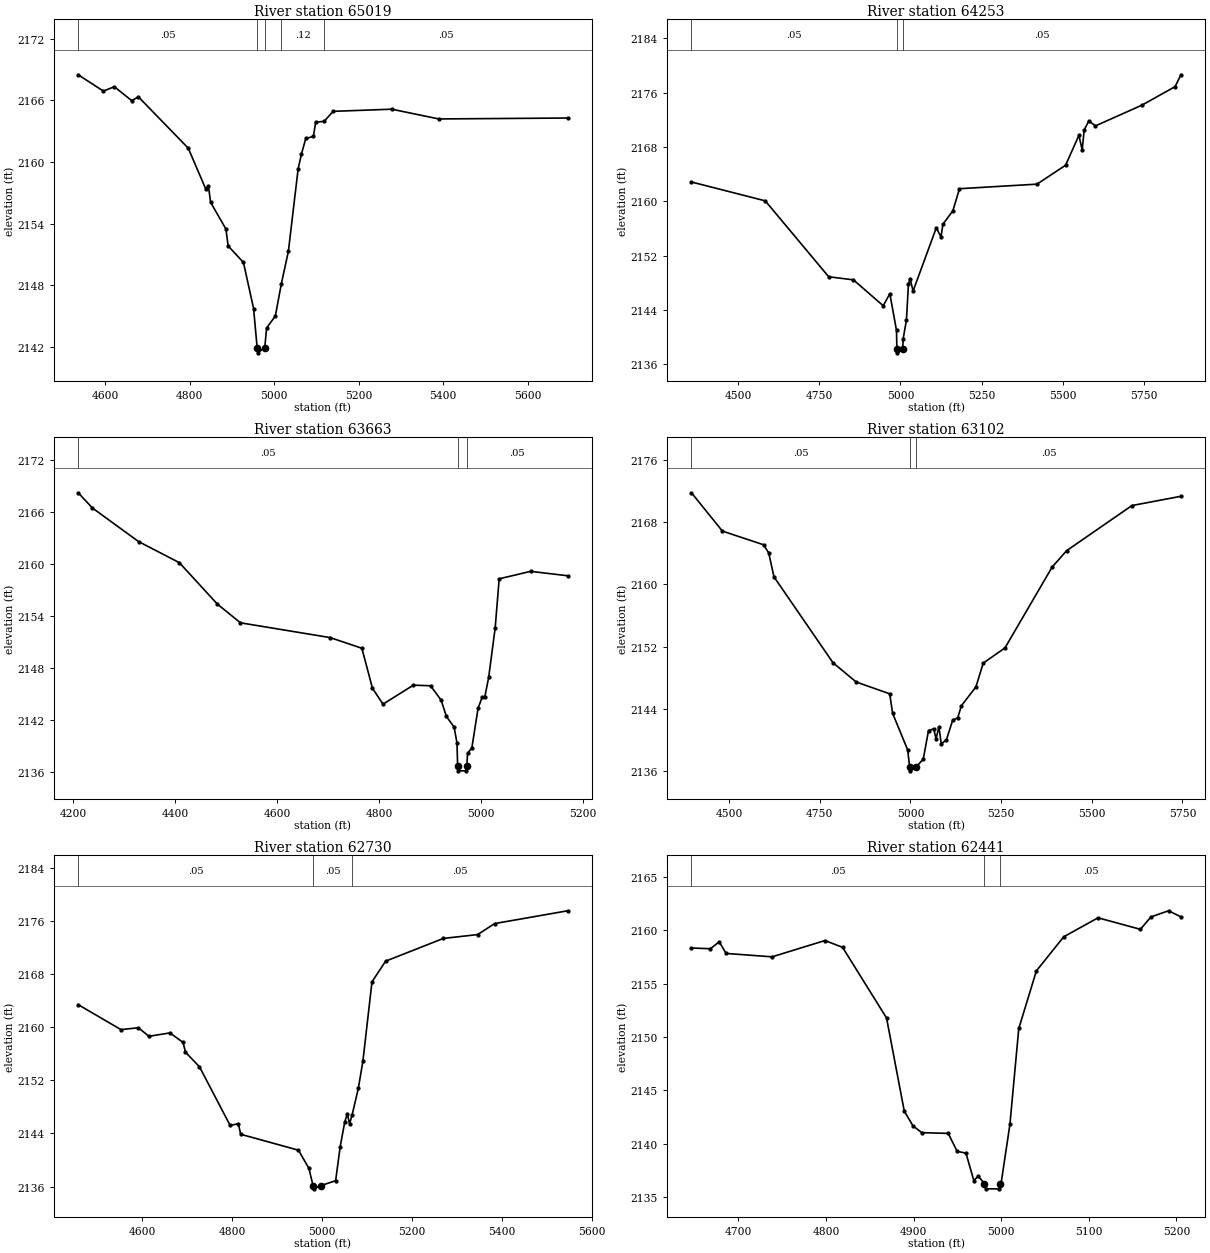
Type RM Length L Ch R = 1,65019,766,766,766
BEGIN DESCRIPTION:
Buffalo Creek 67.0
END DESCRIPTION:
XS GIS Cut Line= 3
      1315354.30      6933451.03      1315201.41      6932832.61
      1314972.25      6932363.87
#Sta/Elev= 30
  4535.9 2168.49  4595.6 2166.90  4621.4 2167.33  4662.6 2165.97  4678.4 2166.34
  4796.5 2161.34  4837.7 2157.38  4844.2 2157.66  4849.3 2156.08  4885.6 2153.47
  4890.8 2151.83  4927.1 2150.22  4951.1 2145.73  4959.5 2141.92  4961.0 2141.42
  4977.5 2141.92  4982.0 2143.85  5002.6 2145.00  5016.7 2148.12  5033.5 2151.31
  5056.5 2159.31  5064.4 2160.78  5074.7 2162.29  5092.8 2162.49  5098.0 2163.87
  5118.2 2163.96  5139.4 2164.93  5278.2 2165.14  5389.6 2164.19  5694.7 2164.28
#Mann=5,-1,0
  4535.9    0.05       0  4959.5    0.05       0  4977.5    0.05       0
  5016.7    0.12       0  5118.2    0.05       0
Bank Sta=4959.5,4977.5
Exp/Cntr=0.3,0.1

Type RM Length L Ch R = 1,64253,590,590,590
BEGIN DESCRIPTION:
Buffalo Creek 66.0
END DESCRIPTION:
XS GIS Cut Line= 2
      1315826.06      6933166.28      1315519.62      6931690.26
#Sta/Elev= 30
  4356.4 2162.84  4583.7 2160.06  4779.1 2148.87  4855.1 2148.42  4947.0 2144.60
  4967.4 2146.38  4987.9 2140.96  4989.1 2138.16  4990.6 2137.66  5007.1 2138.16
  5008.3 2139.71  5018.5 2142.49  5024.7 2147.79  5029.8 2148.59  5038.9 2146.76
  5110.4 2156.08  5124.9 2154.75  5130.8 2156.61  5161.5 2158.60  5181.9 2161.85
  5420.6 2162.52  5508.7 2165.31  5549.6 2169.71  5559.8 2167.58  5565.9 2170.50
  5580.2 2171.85  5600.7 2171.11  5743.6 2174.16  5845.8 2176.89  5863.9 2178.64
#Mann=3,-1,0
  4356.4    0.05       0  4989.1    0.05       0  5007.1    0.05       0
Bank Sta=4989.1,5007.1
Exp/Cntr=0.3,0.1

Type RM Length L Ch R = 1,63663,561,561,561
BEGIN DESCRIPTION:
Buffalo Creek 65.0
END DESCRIPTION:
XS GIS Cut Line= 3
      1316048.62      6933304.87      1316255.00      6932538.00
      1316295.17      6932377.71
#Sta/Elev= 30
  4210.0 2168.17  4237.8 2166.42  4328.3 2162.55  4408.2 2160.12  4482.9 2155.34
  4528.1 2153.19  4703.8 2151.49  4766.0 2150.26  4786.7 2145.66  4807.4 2143.82
  4866.9 2146.01  4900.6 2145.94  4921.3 2144.29  4931.7 2142.40  4946.8 2141.17
  4952.4 2139.36  4953.7 2136.64  4955.2 2136.14  4970.2 2136.14  4971.7 2136.64
  4973.1 2138.15  4981.6 2138.80  4993.8 2143.37  5001.6 2144.59  5006.7 2144.59
  5014.5 2146.90  5027.3 2152.62  5035.1 2158.26  5096.9 2159.12  5169.4 2158.61
#Mann=3,-1,0
  4210.0    0.05       0  4953.7   0.045       0  4971.7    0.05       0
Bank Sta=4953.7,4971.7
Exp/Cntr=0.3,0.1

Type RM Length L Ch R = 1,63102,372,372,372
BEGIN DESCRIPTION:
Buffalo Creek 64.0
END DESCRIPTION:
XS GIS Cut Line= 3
      1316204.98      6933438.03      1316663.22      6932881.22
      1316652.80      6932252.83
#Sta/Elev= 30
  4396.2 2171.75  4481.6 2166.83  4595.0 2165.08  4609.3 2164.03  4623.6 2160.97
  4786.5 2149.94  4850.4 2147.47  4942.9 2145.95  4950.8 2143.45  4992.4 2138.75
  4997.8 2136.57  4999.3 2136.07  5015.8 2136.57  5035.4 2137.58  5049.8 2141.24
  5064.1 2141.46  5070.6 2140.20  5078.5 2141.70  5085.0 2139.52  5099.3 2140.06
  5116.2 2142.54  5130.5 2142.90  5140.5 2144.42  5180.6 2146.85  5200.6 2149.89
  5260.6 2151.84  5390.6 2162.21  5430.6 2164.32  5610.6 2170.11  5745.8 2171.30
#Mann=3,-1,0
  4396.2    0.05       0  4997.8    0.05       0  5015.8    0.05       0
Bank Sta=4997.8,5015.8
Exp/Cntr=0.3,0.1

Type RM Length L Ch R = 1,62730,289,289,289
BEGIN DESCRIPTION:
Mapping XS f189dba6
END DESCRIPTION:
XS GIS Cut Line= 3
      1316357.67      6933426.36      1316854.19      6933211.08
      1317395.85      6933134.69
#Sta/Elev= 30
  4457.8 2163.43  4553.0 2159.66  4591.5 2159.95  4615.0 2158.66  4661.9 2159.17
  4690.9 2157.73  4696.3 2156.26  4727.4 2154.06  4795.6 2145.21  4813.7 2145.48
  4819.1 2143.88  4947.4 2141.48  4970.8 2138.73  4979.8 2136.15  4981.3 2135.65
  4997.8 2136.15  5030.1 2136.88  5040.2 2142.00  5050.3 2145.71  5056.1 2146.98
  5061.1 2145.45  5066.9 2146.84  5080.6 2150.82  5090.7 2154.89  5110.9 2166.87
  5141.2 2169.99  5269.6 2173.42  5345.8 2174.00  5383.6 2175.66  5546.0 2177.59
#Mann=3,-1,0
  4457.8    0.05       0  4979.8    0.05       0  5066.9    0.05       0
Bank Sta=4979.8,4997.8
Exp/Cntr=0.3,0.1

Type RM Length L Ch R = 1,62441,474,474,474
BEGIN DESCRIPTION:
Mapping XS c139a181
END DESCRIPTION:
XS GIS Cut Line= 2
      1316503.50      6933537.47      1317059.07      6933478.44
#Sta/Elev= 30
  4646.5 2158.35  4668.1 2158.28  4678.2 2158.93  4686.0 2157.84  4738.5 2157.52
  4798.9 2159.05  4819.0 2158.41  4869.2 2151.78  4889.4 2143.05  4899.4 2141.66
  4909.5 2141.03  4939.6 2140.96  4949.7 2139.28  4959.8 2139.11  4968.8 2136.54
  4973.8 2136.95  4980.9 2136.26  4982.4 2135.76  4997.4 2135.76  4998.9 2136.26
  5000.0 2136.32  5010.0 2141.81  5020.1 2150.80  5040.2 2156.20  5071.4 2159.40
  5110.6 2161.18  5158.9 2160.10  5170.9 2161.26  5191.0 2161.84  5205.2 2161.27
#Mann=3,-1,0
  4646.5    0.05       0  4980.9    0.05       0  4998.9    0.05       0
Bank Sta=4980.9,4998.9
Exp/Cntr=0.3,0.1

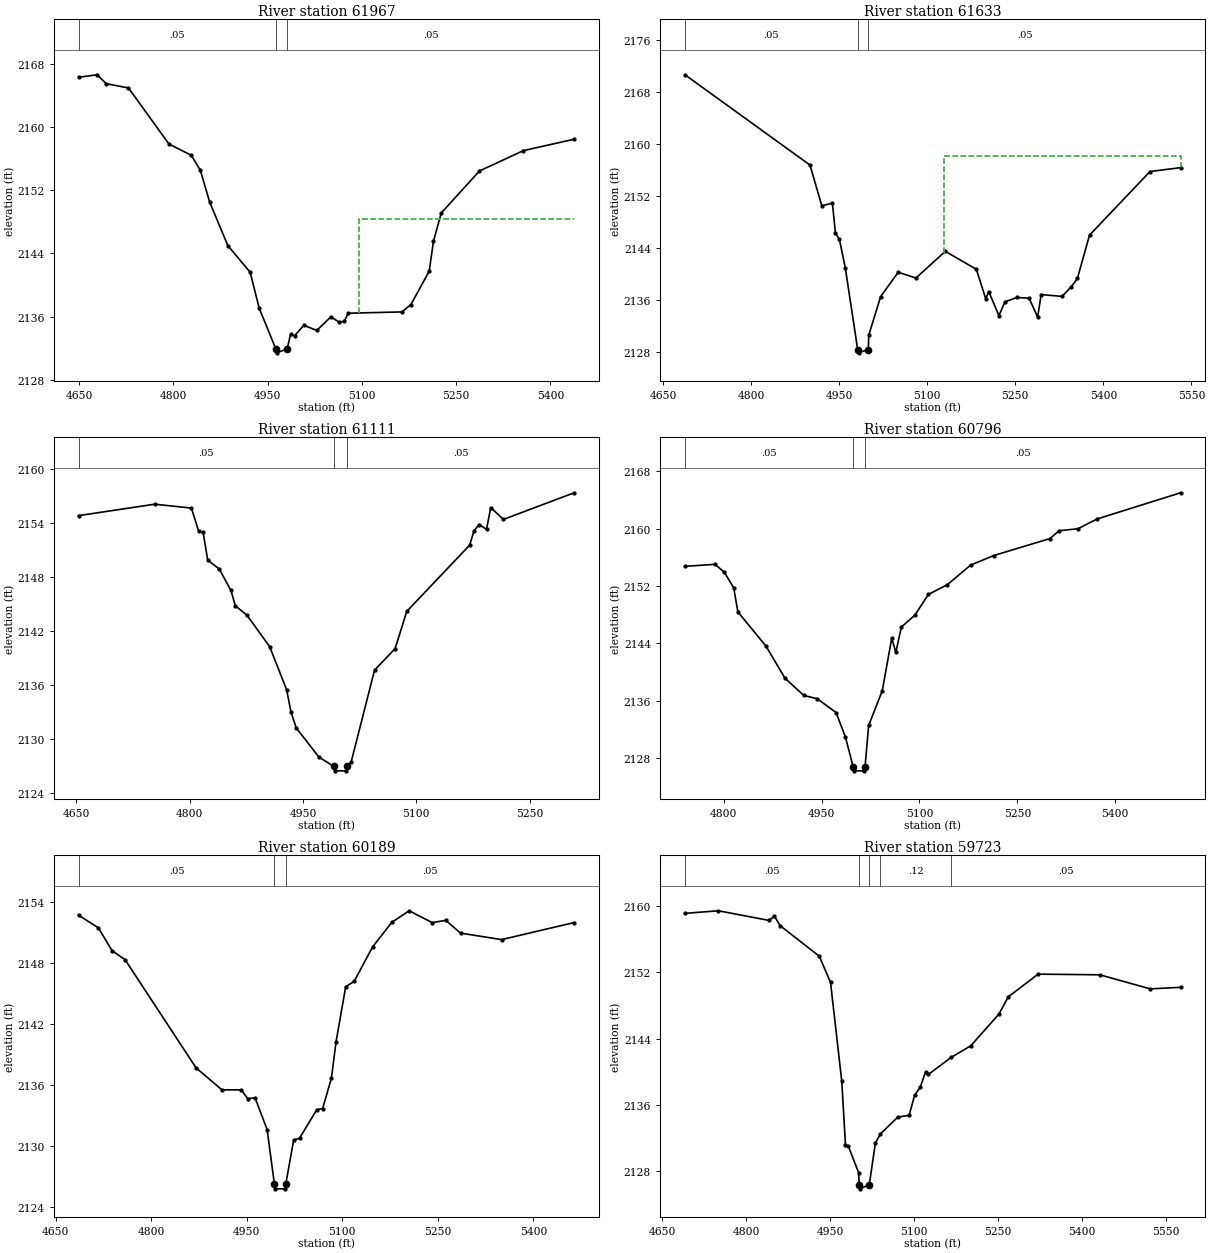
Type RM Length L Ch R = 1,61967,334,334,334
BEGIN DESCRIPTION:
Mapping XS 4ff49a69
END DESCRIPTION:
XS GIS Cut Line= 3
      1316385.40      6933665.91      1316847.25      6934016.64
      1317055.63      6934016.64
#Sta/Elev= 30
  4649.4 2166.29  4679.0 2166.61  4693.5 2165.48  4728.9 2164.94  4793.3 2157.84
  4828.7 2156.42  4843.3 2154.50  4857.8 2150.53  4886.9 2144.97  4922.3 2141.62
  4936.8 2137.05  4963.2 2131.90  4964.7 2131.40  4981.2 2131.90  4986.7 2133.75
  4993.0 2133.54  5007.6 2134.89  5028.4 2134.24  5050.7 2135.95  5063.8 2135.30
  5072.0 2135.38  5078.3 2136.42  5163.7 2136.58  5178.1 2137.52  5207.2 2141.75
  5213.9 2145.52  5226.3 2149.11  5287.1 2154.43  5357.1 2157.01  5437.7 2158.45
#Mann=3,-1,0
  4649.4    0.05       0  4963.2    0.05       0  4981.2    0.05       0
#XS Ineff=2,0
       0                 5095.20    0.00 2148.35
Permanent Ineff=
       F       F
Bank Sta=4963.2,4981.2
Exp/Cntr=0.3,0.1

Type RM Length L Ch R = 1,61633,522,522,522
BEGIN DESCRIPTION:
Mapping XS d26c76f6
END DESCRIPTION:
XS GIS Cut Line= 3
      1316142.38      6934106.91      1316635.44      6934138.16
      1316975.74      6934054.83
#Sta/Elev= 30
  4687.3 2170.63  4900.3 2156.76  4920.4 2150.51  4938.5 2150.92  4943.5 2146.36
  4950.4 2145.33  4960.5 2140.94  4981.5 2128.42  4983.0 2127.92  4999.5 2128.42
  5000.5 2130.66  5020.6 2136.56  5050.6 2140.30  5080.7 2139.41  5130.8 2143.51
  5183.7 2140.75  5199.7 2136.22  5204.8 2137.34  5222.1 2133.63  5232.4 2135.75
  5253.0 2136.43  5273.6 2136.30  5288.1 2133.40  5294.1 2136.87  5329.7 2136.59
  5345.6 2138.09  5355.9 2139.37  5376.5 2146.00  5479.5 2155.77  5531.7 2156.37
#Mann=3,-1,0
  4687.3    0.05       0  4981.5    0.05       0  4999.5    0.05       0
#XS Ineff=2,0
    0.00 4871.60 2158.22 5128.40    0.00 2158.22
Permanent Ineff=
       F       F
Bank Sta=4981.5,4999.5
Exp/Cntr=0.3,0.1

Type RM Length L Ch R = 1,61111,315,315,315
BEGIN DESCRIPTION:
Mapping XS 2f6fa850
END DESCRIPTION:
XS GIS Cut Line= 3
      1316614.59      6934534.03      1316840.30      6934162.47
      1317037.05      6934062.37
#Sta/Elev= 30
  4653.2 2154.84  4753.9 2156.11  4802.5 2155.68  4812.1 2153.10  4818.0 2152.98
  4824.1 2149.89  4839.3 2148.91  4854.8 2146.53  4860.6 2144.83  4876.1 2143.76
  4906.0 2140.28  4928.4 2135.50  4934.3 2132.98  4941.1 2131.26  4971.1 2128.01
  4990.6 2126.98  4992.1 2126.48  5007.1 2126.48  5008.6 2126.98  5013.7 2127.44
  5044.7 2137.67  5071.9 2140.06  5087.3 2144.20  5170.6 2151.57  5176.2 2153.15
  5183.0 2153.85  5192.8 2153.32  5198.4 2155.74  5215.1 2154.42  5308.7 2157.38
#Mann=3,-1,0
  4653.2    0.05       0  4990.6    0.05       0  5008.6    0.05       0
Bank Sta=4990.6,5008.6
Exp/Cntr=0.3,0.1

Type RM Length L Ch R = 1,60796,607,607,607
BEGIN DESCRIPTION:
Buffalo Creek 61.0
END DESCRIPTION:
XS GIS Cut Line= 3
      1316802.11      6934599.97      1317005.00      6934438.00
      1317404.99      6934138.00
#Sta/Elev= 30
  4740.6 2154.74  4786.5 2155.02  4800.9 2153.93  4815.3 2151.74  4821.7 2148.39
  4864.9 2143.61  4893.7 2139.17  4922.6 2136.76  4943.4 2136.29  4972.2 2134.37
  4986.6 2130.93  4998.5 2126.75  5000.0 2126.25  5015.0 2126.25  5016.5 2126.75
  5022.1 2132.58  5042.9 2137.39  5057.5 2144.74  5063.7 2142.74  5072.1 2146.27
  5092.9 2147.94  5113.7 2150.83  5142.9 2152.20  5178.3 2154.91  5213.7 2156.24
  5300.2 2158.62  5313.7 2159.70  5342.9 2159.98  5372.1 2161.34  5500.2 2164.99
#Mann=3,-1,0
  4740.6    0.05       0  4998.5   0.033       0  5016.5    0.05       0
Bank Sta=4998.5,5016.5
Exp/Cntr=0.3,0.1

Type RM Length L Ch R = 1,60189,466,466,466
BEGIN DESCRIPTION:
Buffalo Creek 60.0
END DESCRIPTION:
XS GIS Cut Line= 3
      1316993.08      6934988.86      1317319.47      6934933.30
      1317562.55      6934558.27
#Sta/Elev= 30
  4685.9 2152.72  4717.0 2151.47  4738.6 2149.22  4758.9 2148.34  4870.4 2137.68
  4911.0 2135.51  4941.4 2135.51  4951.6 2134.64  4963.0 2134.73  4982.0 2131.59
  4993.3 2126.26  4994.8 2125.76  5009.8 2125.76  5011.3 2126.26  5023.6 2130.56
  5032.8 2130.74  5059.9 2133.56  5069.1 2133.67  5082.9 2136.67  5090.2 2140.26
  5105.3 2145.67  5118.6 2146.20  5147.5 2149.59  5177.8 2152.02  5204.9 2153.15
  5241.2 2151.98  5262.3 2152.21  5285.5 2150.95  5350.0 2150.31  5463.9 2151.99
#Mann=3,-1,0
  4685.9    0.05       0  4993.3    0.05       0  5011.3    0.05       0
Bank Sta=4993.3,5011.3
Exp/Cntr=0.3,0.1

Type RM Length L Ch R = 1,59723,442,442,442
BEGIN DESCRIPTION:
Mapping XS 5c06f82c
END DESCRIPTION:
XS GIS Cut Line= 2
      1317600.21      6935547.52      1317660.98      6934663.90
#Sta/Elev= 30
  4690.2 2159.14  4749.9 2159.45  4840.1 2158.29  4850.1 2158.79  4860.1 2157.66
  4930.3 2153.96  4950.3 2150.80  4970.4 2138.85  4977.0 2131.17  4982.0 2131.05
  5000.4 2127.85  5001.5 2126.38  5003.0 2125.88  5019.5 2126.38  5030.5 2131.41
  5039.4 2132.51  5070.6 2134.55  5090.7 2134.76  5100.7 2137.20  5110.7 2138.16
  5120.0 2139.99  5125.1 2139.69  5166.0 2141.75  5200.9 2143.15  5251.0 2146.96
  5268.1 2149.07  5321.2 2151.80  5431.5 2151.72  5521.7 2150.02  5575.9 2150.21
#Mann=5,-1,0
  4690.2    0.05       0  5001.5    0.05       0  5019.5    0.05       0
  5039.4    0.12       0  5166.0    0.05       0
Bank Sta=5001.5,5019.5
Exp/Cntr=0.3,0.1

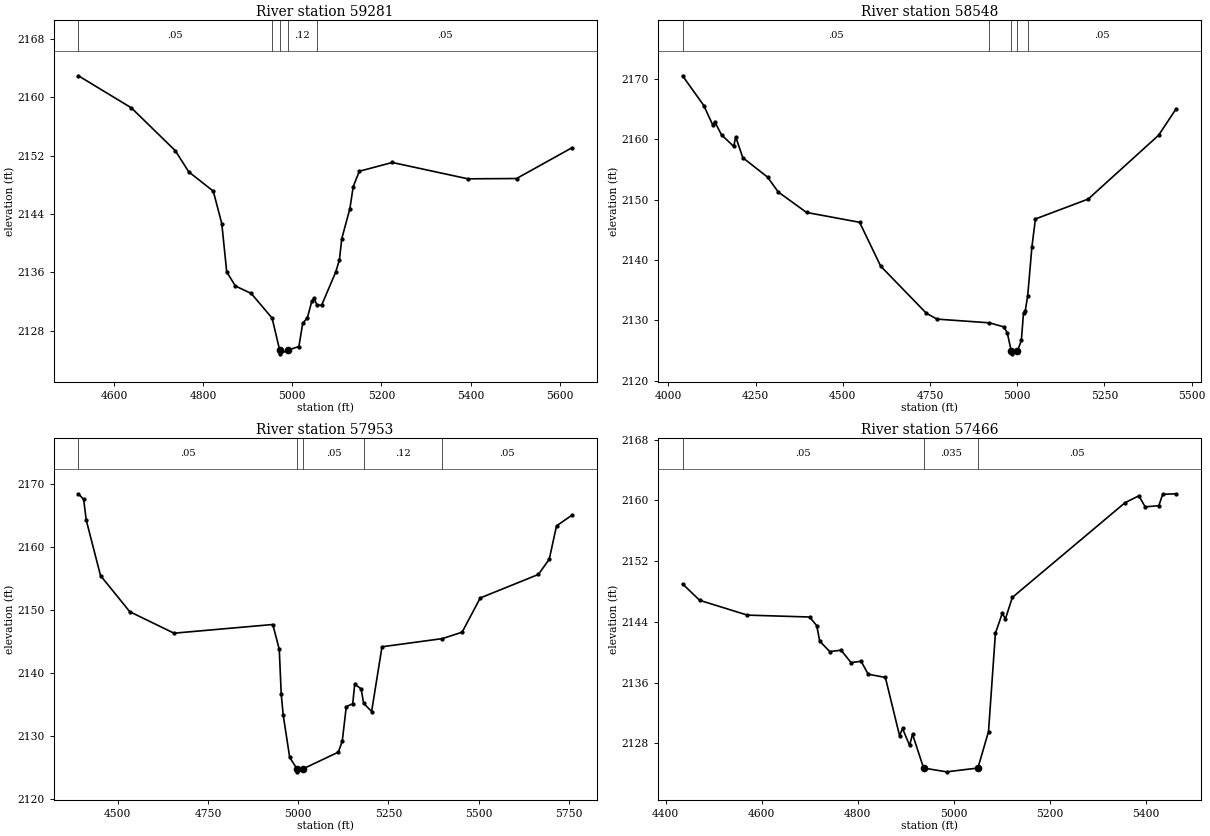
Type RM Length L Ch R = 1,59281,733,733,733
BEGIN DESCRIPTION:
Buffalo Creek 59.0
END DESCRIPTION:
XS GIS Cut Line= 3
      1318185.79      6935539.21      1318012.18      6935079.14
      1317808.17      6934497.51
#Sta/Elev= 30
  4519.7 2162.97  4638.6 2158.57  4737.2 2152.70  4767.4 2149.80  4822.5 2147.15
  4841.6 2142.70  4852.7 2136.07  4872.2 2134.14  4907.7 2133.12  4954.6 2129.74
  4971.6 2125.34  4973.1 2124.84  4989.6 2125.34  5014.7 2125.84  5023.3 2129.02
  5033.8 2129.78  5043.7 2132.06  5049.0 2132.50  5054.9 2131.56  5065.6 2131.49
  5097.4 2136.05  5105.7 2137.73  5111.0 2140.63  5129.2 2144.75  5136.7 2147.78
  5150.4 2149.88  5224.4 2151.08  5394.1 2148.84  5503.4 2148.88  5627.8 2153.10
#Mann=5,-1,0
  4519.7    0.05       0  4954.6    0.12       0  4971.6    0.07       0
  4989.6    0.12       0  5054.9    0.05       0
Bank Sta=4971.6,4989.6
Exp/Cntr=0.3,0.1

Type RM Length L Ch R = 1,58548,595,595,595
BEGIN DESCRIPTION:
Buffalo Creek 58.0
END DESCRIPTION:
XS GIS Cut Line= 3
      1318455.00      6935688.02      1318537.35      6935213.68
      1318655.00      6934287.96
#Sta/Elev= 30
  4040.9 2170.55  4101.8 2165.62  4127.9 2162.32  4133.0 2162.95  4152.6 2160.75
  4187.6 2158.84  4193.2 2160.43  4213.5 2156.97  4284.5 2153.75  4315.0 2151.29
  4396.2 2147.89  4548.3 2146.26  4608.7 2138.99  4739.8 2131.17  4770.0 2130.21
  4920.6 2129.59  4961.5 2128.92  4971.6 2127.93  4982.8 2124.95  4984.3 2124.45
  5000.8 2124.95  5011.9 2126.67  5018.1 2131.24  5023.1 2131.57  5030.1 2134.08
  5042.2 2142.20  5052.2 2146.81  5203.5 2150.11  5405.1 2160.68  5455.5 2165.07
#Mann=5,-1,0
  4040.9    0.05       0  4920.6    0.12       0  4982.8    0.07       0
  5000.8    0.12       0  5030.1    0.05       0
Bank Sta=4982.8,5000.8
Exp/Cntr=0.3,0.1

Type RM Length L Ch R = 1,57953,487,487,487
BEGIN DESCRIPTION:
Buffalo Creek 57.0
END DESCRIPTION:
XS GIS Cut Line= 3
      1318604.98      6935738.04      1318949.68      6934948.93
      1319006.10      6934445.49
#Sta/Elev= 30
  4390.8 2168.52  4405.3 2167.63  4412.7 2164.29  4452.1 2155.52  4533.2 2149.78
  4655.7 2146.37  4929.5 2147.75  4947.4 2143.80  4952.9 2136.64  4958.3 2133.37
  4976.3 2126.63  4996.2 2124.84  4997.7 2124.34  5014.2 2124.84  5111.1 2127.47
  5122.0 2129.23  5133.1 2134.70  5151.0 2135.16  5156.5 2138.28  5174.4 2137.51
  5181.1 2135.24  5203.3 2133.92  5232.1 2144.21  5399.5 2145.51  5454.1 2146.53
  5504.4 2151.97  5665.4 2155.70  5695.6 2158.13  5715.7 2163.42  5758.5 2165.12
#Mann=5,-1,0
  4390.8    0.05       0  4996.2    0.05       0  5014.2    0.05       0
  5181.1    0.12       0  5399.5    0.05       0
Bank Sta=4996.2,5014.2
Exp/Cntr=0.3,0.1

Type RM Length L Ch R = 1,57466,846,846,846
BEGIN DESCRIPTION:
Buffalo Creek 56.0
END DESCRIPTION:
XS GIS Cut Line= 3
      1318784.75      6935756.21      1319240.48      6935435.04
      1319605.04      6935137.97
#Sta/Elev= 30
  4435.2 2149.00  4470.8 2146.84  4570.1 2144.89  4699.8 2144.64  4714.6 2143.50
  4720.8 2141.46  4741.7 2140.09  4765.2 2140.27  4786.1 2138.64  4807.0 2138.81
  4821.8 2137.11  4857.5 2136.68  4887.1 2129.01  4893.2 2129.96  4908.0 2127.73
  4914.1 2129.20  4937.1 2124.75  4984.9 2124.25  5050.2 2124.75  5072.3 2129.55
  5086.7 2142.51  5101.0 2145.13  5107.5 2144.39  5121.9 2147.22  5356.7 2159.70
  5385.4 2160.60  5398.5 2159.15  5427.0 2159.30  5435.0 2160.80  5463.0 2160.87
#Mann=3,-1,0
  4435.2    0.05       0  4937.1   0.035       0  5050.2    0.05       0
Bank Sta=4937.1,5050.2
Exp/Cntr=0.3,0.1