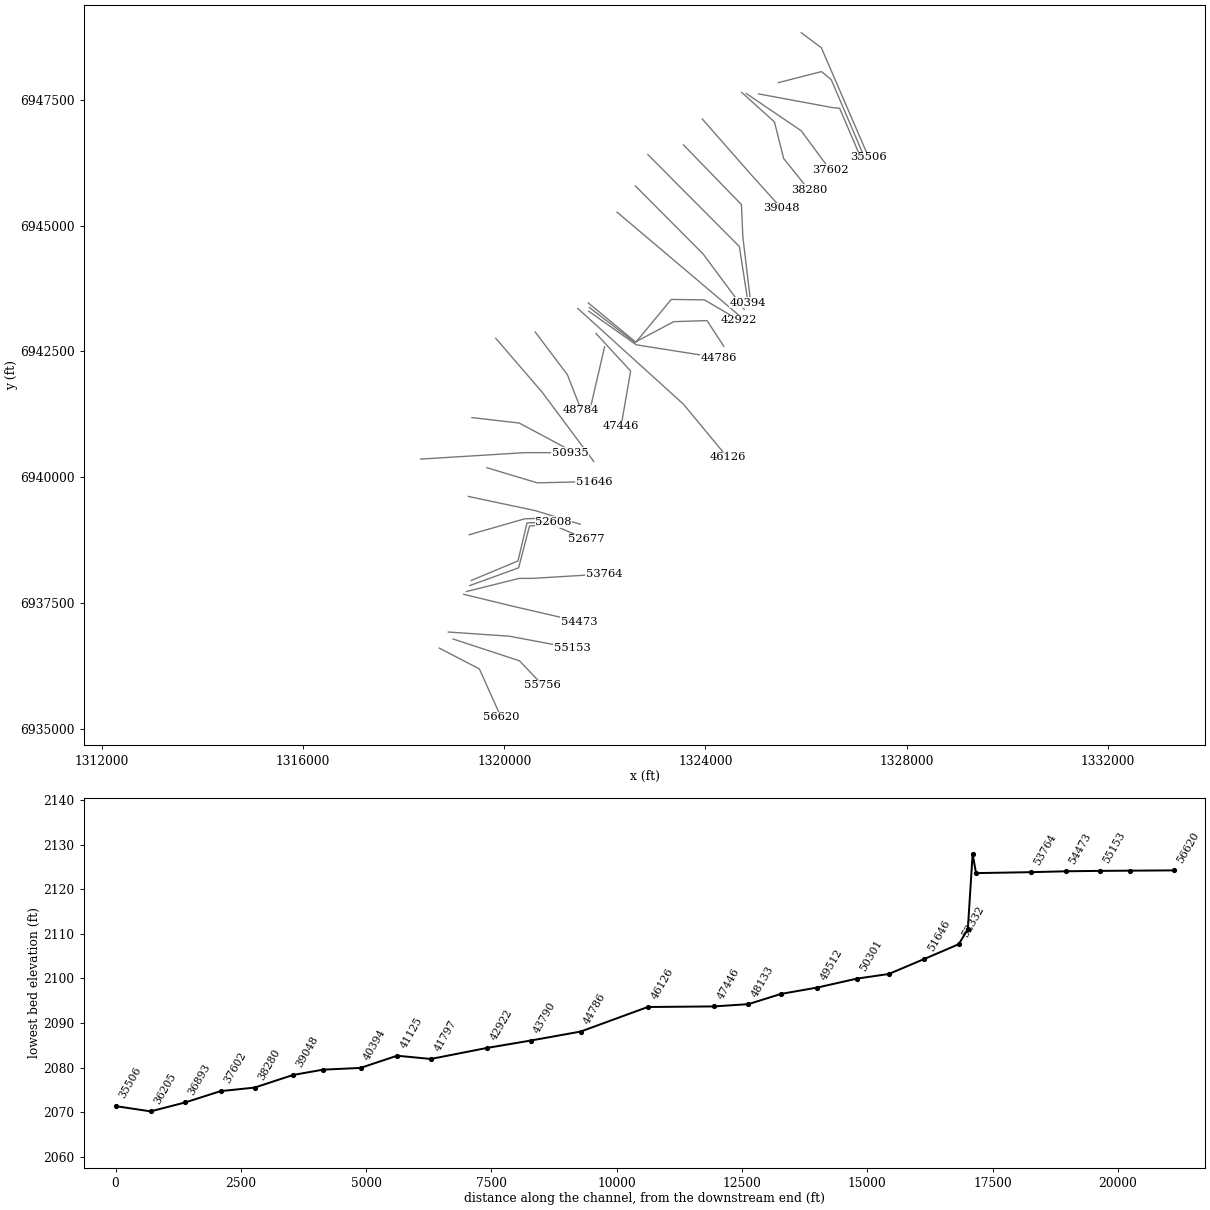
HEC-RAS study Buffalo Creek.prj: Buffalo Creek Base Level Engineering

--- Buffalo Creek.g01 (geometry) --- (continued)

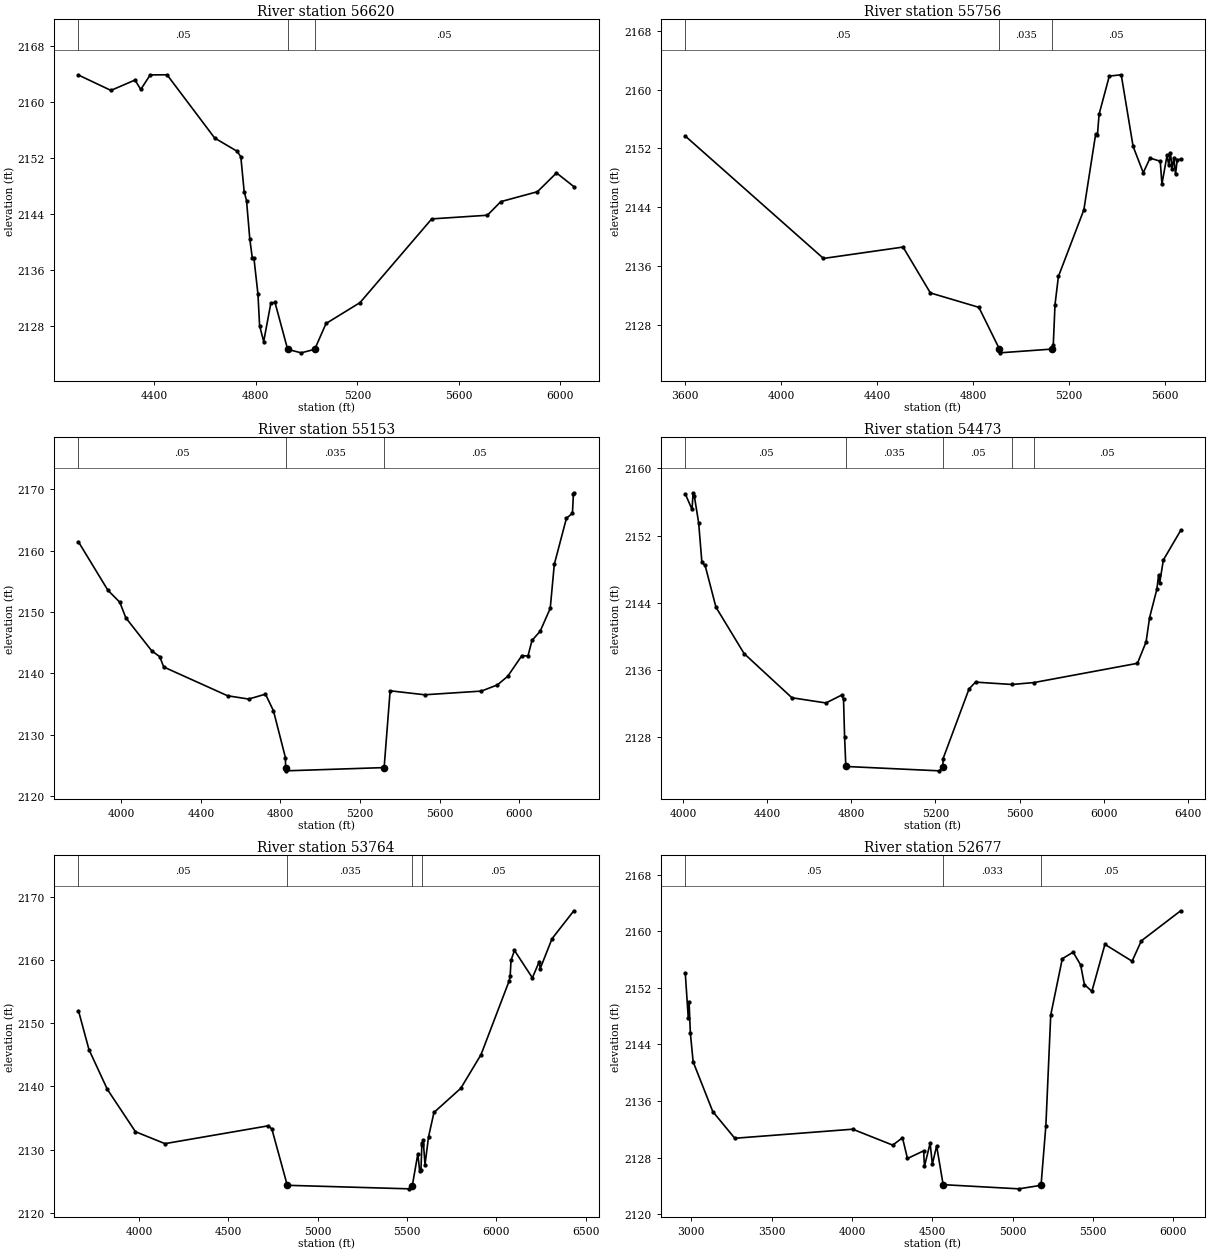
Type RM Length L Ch R = 1,56620,864,864,864
BEGIN DESCRIPTION:
Buffalo Creek 55.0
END DESCRIPTION:
XS GIS Cut Line= 3
      1318707.30      6936602.23      1319505.00      6936188.00
      1319936.49      6935227.18
#Sta/Elev= 30
  4101.2 2163.85  4229.0 2161.66  4324.0 2163.14  4346.5 2161.79  4383.8 2163.87
  4450.1 2163.89  4637.9 2154.86  4726.4 2152.97  4740.9 2152.18  4754.1 2147.21
  4763.4 2145.93  4776.3 2140.44  4785.9 2137.80  4792.7 2137.68  4808.5 2132.55
  4814.9 2128.09  4831.0 2125.81  4859.1 2131.27  4875.6 2131.39  4925.4 2124.70
  4978.7 2124.20  5032.0 2124.70  5076.8 2128.39  5210.7 2131.37  5493.3 2143.32
  5712.6 2143.84  5765.4 2145.78  5909.9 2147.20  5984.9 2149.88  6053.3 2147.93
#Mann=3,-1,0
  4101.2    0.05       0  4925.4   0.035       0  5032.0    0.05       0
Bank Sta=4925.4,5032
Exp/Cntr=0.3,0.1

Type RM Length L Ch R = 1,55756,603,603,603
BEGIN DESCRIPTION:
Buffalo Creek 55.5
END DESCRIPTION:
XS GIS Cut Line= 3
      1318983.25      6936782.55      1320302.95      6936349.14
      1320767.66      6935860.61
#Sta/Elev= 30
  3601.1 2153.67  4176.6 2137.00  4508.1 2138.55  4621.9 2132.30  4823.9 2130.34
  4909.8 2124.64  4911.3 2124.14  5126.9 2124.65  5133.8 2125.20  5141.1 2130.72
  5155.2 2134.54  5261.2 2143.62  5310.6 2153.98  5317.8 2153.84  5324.7 2156.65
  5367.2 2161.84  5416.9 2162.02  5466.3 2152.27  5508.7 2148.68  5537.0 2150.67
  5579.5 2150.24  5586.4 2147.12  5607.8 2151.05  5614.7 2149.71  5622.0 2151.39
  5628.9 2149.16  5636.1 2150.74  5643.0 2148.45  5650.3 2150.46  5664.4 2150.50
#Mann=3,-1,0
  3601.1    0.05       0  4909.8   0.035       0  5126.9    0.05       0
Bank Sta=4909.8,5126.9
Exp/Cntr=0.3,0.1

Type RM Length L Ch R = 1,55153,680,680,680
BEGIN DESCRIPTION:
Buffalo Creek 54.0
END DESCRIPTION:
XS GIS Cut Line= 3
      1318887.85      6936921.67      1320105.00      6936838.00
      1321351.53      6936602.53
#Sta/Elev= 30
  3785.2 2161.41  3932.7 2153.54  3992.8 2151.57  4022.9 2149.04  4153.2 2143.65
  4193.3 2142.70  4213.4 2141.02  4534.1 2136.33  4640.0 2135.79  4724.6 2136.59
  4764.7 2133.88  4824.8 2126.24  4825.8 2124.59  4827.3 2124.09  5320.7 2124.62
  5350.8 2137.14  5524.2 2136.49  5809.2 2137.09  5889.8 2138.10  5941.5 2139.50
  6012.7 2142.87  6043.3 2142.81  6063.6 2145.35  6104.3 2146.83  6155.2 2150.58
  6175.6 2157.75  6236.6 2165.27  6266.7 2166.07  6271.7 2169.25  6273.8 2169.42
#Mann=3,-1,0
  3785.2    0.05       0  4825.8   0.035       0  5320.7    0.05       0
Bank Sta=4825.8,5320.7
Exp/Cntr=0.3,0.1

Type RM Length L Ch R = 1,54473,709,709,709
BEGIN DESCRIPTION:
Buffalo Creek 53.0
END DESCRIPTION:
XS GIS Cut Line= 3
      1319193.43      6937671.66      1320155.00      6937438.00
      1321485.05      6937130.01
#Sta/Elev= 30
  4010.7 2156.96  4042.7 2155.12  4047.9 2157.10  4053.5 2156.73  4074.1 2153.54
  4089.6 2148.82  4104.9 2148.45  4156.4 2143.48  4290.2 2137.96  4517.5 2132.70
  4679.4 2132.08  4753.3 2133.01  4762.9 2132.52  4768.0 2128.01  4773.9 2124.52
  5218.6 2124.00  5235.1 2124.50  5236.3 2125.46  5359.5 2133.75  5390.3 2134.56
  5563.9 2134.28  5668.3 2134.51  6160.2 2136.80  6201.2 2139.35  6217.9 2142.25
  6252.5 2145.62  6260.6 2147.30  6265.8 2146.36  6283.3 2149.10  6365.5 2152.61
#Mann=5,-1,0
  4010.7    0.05       0  4773.9   0.035       0  5235.1    0.05       0
  5563.9    0.12       0  5668.3    0.05       0
Bank Sta=4773.9,5235.1
Exp/Cntr=0.3,0.1

Type RM Length L Ch R = 1,53764,1087,1087,1087
BEGIN DESCRIPTION:
Buffalo Creek 52.0
END DESCRIPTION:
XS GIS Cut Line= 4
      1319248.11      6937726.66      1320298.45      6937988.00
      1320555.00      6937988.00      1321986.78      6938074.44
#Sta/Elev= 30
  3661.4 2151.97  3720.0 2145.83  3823.1 2139.53  3980.2 2132.84  4145.4 2130.95
  4723.9 2133.77  4743.8 2133.29  4830.3 2124.36  5513.8 2123.80  5530.3 2124.30
  5561.3 2129.33  5571.3 2126.66  5578.7 2126.76  5583.7 2130.66  5586.9 2131.00
  5591.4 2131.49  5601.4 2127.64  5621.4 2132.05  5651.5 2135.88  5801.8 2139.71
  5915.0 2145.03  6072.3 2156.68  6078.1 2157.42  6083.1 2159.96  6102.3 2161.52
  6202.5 2157.18  6241.2 2159.75  6246.2 2158.63  6312.7 2163.38  6434.7 2167.79
#Mann=4,-1,0
  3661.4    0.05       0  4830.3   0.035       0  5530.3    0.05       0
  5586.9    0.05       0
Bank Sta=4830.3,5530.3
Exp/Cntr=0.3,0.1

Type RM Length L Ch R = 1,52677,69,69,69
BEGIN DESCRIPTION:
Buffalo Creek 51.0
END DESCRIPTION:
XS GIS Cut Line= 5
      1319315.52      6937845.85      1320285.61      6938198.06
      1320501.76      6939028.79      1320934.05      6939067.85
      1321630.01      6938762.99
#Sta/Elev= 30
  2962.5 2154.04  2980.7 2147.81  2986.0 2150.06  2993.9 2145.65  3011.3 2141.55
  3133.7 2134.51  3270.5 2130.74  4004.8 2132.02  4254.1 2129.77  4314.8 2130.81
  4345.8 2127.88  4446.4 2128.96  4451.6 2126.76  4486.9 2130.04  4500.8 2127.08
  4527.4 2129.66  4568.0 2124.18  5039.5 2123.59  5177.5 2124.09  5207.6 2132.52
  5237.9 2148.16  5309.9 2156.12  5377.3 2157.05  5424.1 2155.24  5447.5 2152.46
  5494.2 2151.52  5575.3 2158.15  5744.4 2155.77  5802.1 2158.65  6046.8 2162.90
#Mann=3,-1,0
  2962.5    0.05       0  4568.0   0.033       0  5177.5    0.05       0
Bank Sta=4568,5177.5
Exp/Cntr=0.3,0.1

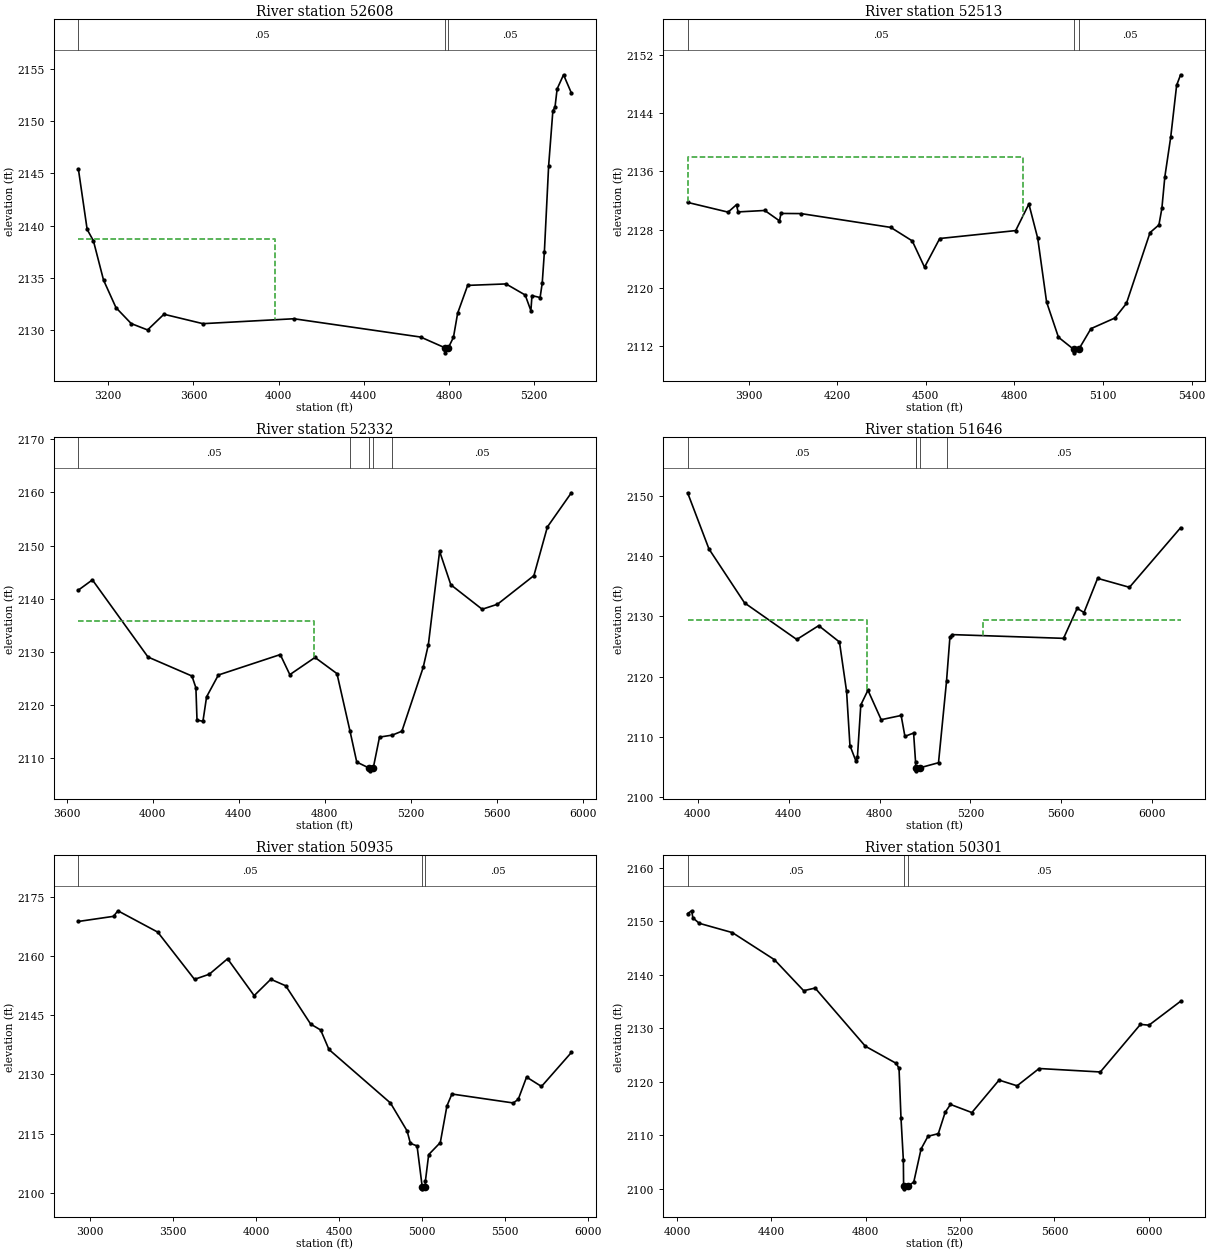
Type RM Length L Ch R = 1,52608,95,95,95
BEGIN DESCRIPTION:
Buffalo Creek 50.2
END DESCRIPTION:
XS GIS Cut Line= 4
      1319343.29      6937946.54      1320273.22      6938334.74
      1320452.28      6939091.29      1320981.72      6939109.46
#Sta/Elev= 30
  3059.9 2145.42  3101.1 2139.64  3130.4 2138.56  3178.0 2134.80  3236.5 2132.16
  3307.9 2130.64  3384.8 2130.03  3461.7 2131.53  3644.6 2130.63  4071.8 2131.10
  4667.0 2129.35  4779.4 2128.34  4780.9 2127.84  4797.4 2128.34  4821.1 2129.32
  4840.8 2131.63  4887.8 2134.29  5067.9 2134.43  5158.0 2133.37  5184.8 2131.87
  5189.8 2133.31  5228.0 2133.13  5238.0 2134.51  5248.0 2137.45  5268.0 2145.70
  5288.0 2150.99  5298.0 2151.34  5308.0 2153.08  5338.1 2154.43  5374.8 2152.69
#Mann=3,-1,0
  3059.9    0.05       0  4779.4   0.033       0  4797.4    0.05       0
#XS Ineff=2,0
    0.00 3981.90 2138.75               0
Permanent Ineff=
       F       F
Bank Sta=4779.4,4797.4
Exp/Cntr=0.3,0.1

Type RM Length L Ch R = 1,52513,181,181,181
BEGIN DESCRIPTION:
Buffalo Creek 50.1
END DESCRIPTION:
XS GIS Cut Line= 3
      1319303.82      6938856.49      1320404.55      6939171.96
      1320928.34      6939191.36
#Sta/Elev= 30
  3693.3 2131.74  3830.4 2130.40  3858.9 2131.43  3864.1 2130.43  3954.6 2130.63
  4004.4 2129.20  4009.6 2130.22  4077.1 2130.20  4381.1 2128.30  4453.9 2126.44
  4495.5 2122.82  4547.0 2126.77  4804.1 2127.86  4848.8 2131.52  4878.8 2126.79
  4908.8 2118.02  4948.9 2113.18  4999.9 2111.53  5001.4 2111.03  5017.9 2111.53
  5059.0 2114.36  5140.3 2115.83  5179.0 2117.83  5259.1 2127.59  5289.1 2128.64
  5299.1 2130.91  5309.1 2135.25  5329.1 2140.74  5349.1 2147.87  5362.5 2149.31
#Mann=3,-1,0
  3693.3    0.05       0  4999.9    0.05       0  5017.9    0.05       0
#XS Ineff=2,0
    0.00 4827.20 2138.05               0
Permanent Ineff=
       F       F
Bank Sta=4999.9,5017.9
Exp/Cntr=0.3,0.1

Type RM Length L Ch R = 1,52332,686,686,686
BEGIN DESCRIPTION:
Buffalo Creek 50.0
END DESCRIPTION:
XS GIS Cut Line= 3
      1319288.17      6939616.91      1320605.00      6939338.00
      1321511.84      6939064.60
#Sta/Elev= 30
  3654.3 2141.62  3719.5 2143.54  3978.2 2129.04  4182.6 2125.47  4201.0 2123.25
  4206.1 2117.19  4233.7 2116.96  4250.7 2121.56  4305.5 2125.66  4593.4 2129.50
  4637.9 2125.73  4755.0 2128.96  4857.2 2125.92  4917.7 2115.14  4949.2 2109.30
  5007.8 2108.15  5009.3 2107.65  5025.8 2108.15  5055.1 2113.99  5115.0 2114.37
  5159.2 2115.10  5258.2 2127.08  5282.4 2131.39  5334.6 2148.91  5386.8 2142.62
  5532.6 2138.02  5603.8 2138.96  5773.2 2144.34  5835.9 2153.48  5947.5 2159.91
#Mann=5,-1,0
  3654.3    0.05       0  4917.7    0.12       0  5007.8    0.05       0
  5025.8    0.12       0  5115.0    0.05       0
#XS Ineff=2,0
    0.00 4749.50 2135.74               0
Permanent Ineff=
       F       F
Bank Sta=5007.8,5025.8
Exp/Cntr=0.3,0.1

Type RM Length L Ch R = 1,51646,711,711,711
BEGIN DESCRIPTION:
Buffalo Creek 49.0
END DESCRIPTION:
XS GIS Cut Line= 3
      1319655.00      6940188.00      1320655.00      6939888.00
      1321779.99      6939913.00
#Sta/Elev= 30
  3955.4 2150.56  4049.4 2141.22  4206.0 2132.26  4435.7 2126.18  4532.2 2128.48
  4623.6 2125.76  4654.9 2117.56  4669.7 2108.56  4696.7 2105.91  4702.8 2106.72
  4717.5 2115.30  4748.9 2117.75  4807.2 2112.85  4895.0 2113.55  4911.6 2110.08
  4949.8 2110.63  4958.5 2105.79  4959.1 2104.85  4960.6 2104.35  4977.1 2104.85
  5059.4 2105.70  5094.7 2119.25  5109.5 2126.51  5119.5 2126.99  5609.6 2126.37
  5669.6 2131.36  5699.6 2130.66  5759.6 2136.34  5899.7 2134.85  6124.7 2144.75
#Mann=5,-1,0
  3955.4    0.05       0  4958.5    0.12       0  4959.1    0.05       0
  4977.1    0.12       0  5094.7    0.05       0
#XS Ineff=2,0
    0.00 4745.10 2129.36 5254.90    0.00 2129.36
Permanent Ineff=
       F       F
Bank Sta=4959.1,4977.1
Exp/Cntr=0.3,0.1

Type RM Length L Ch R = 1,50935,634,634,634
BEGIN DESCRIPTION:
Buffalo Creek 48.0
END DESCRIPTION:
XS GIS Cut Line= 3
      1318337.38      6940359.99      1320405.00      6940488.00
      1321305.02      6940488.00
#Sta/Elev= 30
  2928.5 2168.82  3140.3 2170.12  3166.6 2171.53  3407.0 2166.11  3628.5 2154.13
  3717.6 2155.43  3827.8 2159.35  3988.1 2150.00  4088.3 2154.15  4178.5 2152.49
  4328.8 2142.77  4388.9 2141.28  4439.0 2136.33  4809.7 2122.75  4909.9 2115.67
  4929.9 2112.51  4970.0 2111.86  5001.1 2101.47  5002.6 2100.97  5019.1 2101.47
  5020.1 2102.89  5040.1 2109.66  5110.1 2112.71  5150.1 2122.02  5180.1 2125.03
  5550.1 2122.76  5580.1 2123.70  5630.1 2129.33  5720.1 2126.95  5900.1 2135.57
#Mann=3,-1,0
  2928.5    0.05       0  5001.1    0.05       0  5019.1    0.05       0
Bank Sta=5001.1,5019.1
Exp/Cntr=0.3,0.1

Type RM Length L Ch R = 1,50301,789,789,789
BEGIN DESCRIPTION:
Buffalo Creek 47.0
END DESCRIPTION:
XS GIS Cut Line= 3
      1319356.35      6941185.36      1320298.60      6941076.64
      1321305.02      6940537.99
#Sta/Elev= 30
  4044.6 2151.49  4061.8 2152.00  4066.8 2150.69  4093.6 2149.66  4234.5 2147.91
  4412.4 2142.85  4536.5 2137.04  4585.2 2137.53  4798.2 2126.64  4929.1 2123.43
  4940.9 2122.49  4949.2 2113.24  4959.3 2105.28  4960.3 2100.44  4961.8 2099.94
  4978.3 2100.44  5003.4 2101.21  5034.4 2107.41  5063.6 2109.78  5107.4 2110.27
  5136.5 2114.27  5159.1 2115.74  5249.7 2114.22  5365.0 2120.30  5441.4 2119.23
  5534.9 2122.47  5794.3 2121.82  5964.4 2130.73  6000.5 2130.58  6134.6 2135.06
#Mann=3,-1,0
  4044.6    0.05       0  4960.3    0.05       0  4978.3    0.05       0
Bank Sta=4960.3,4978.3
Exp/Cntr=0.3,0.1

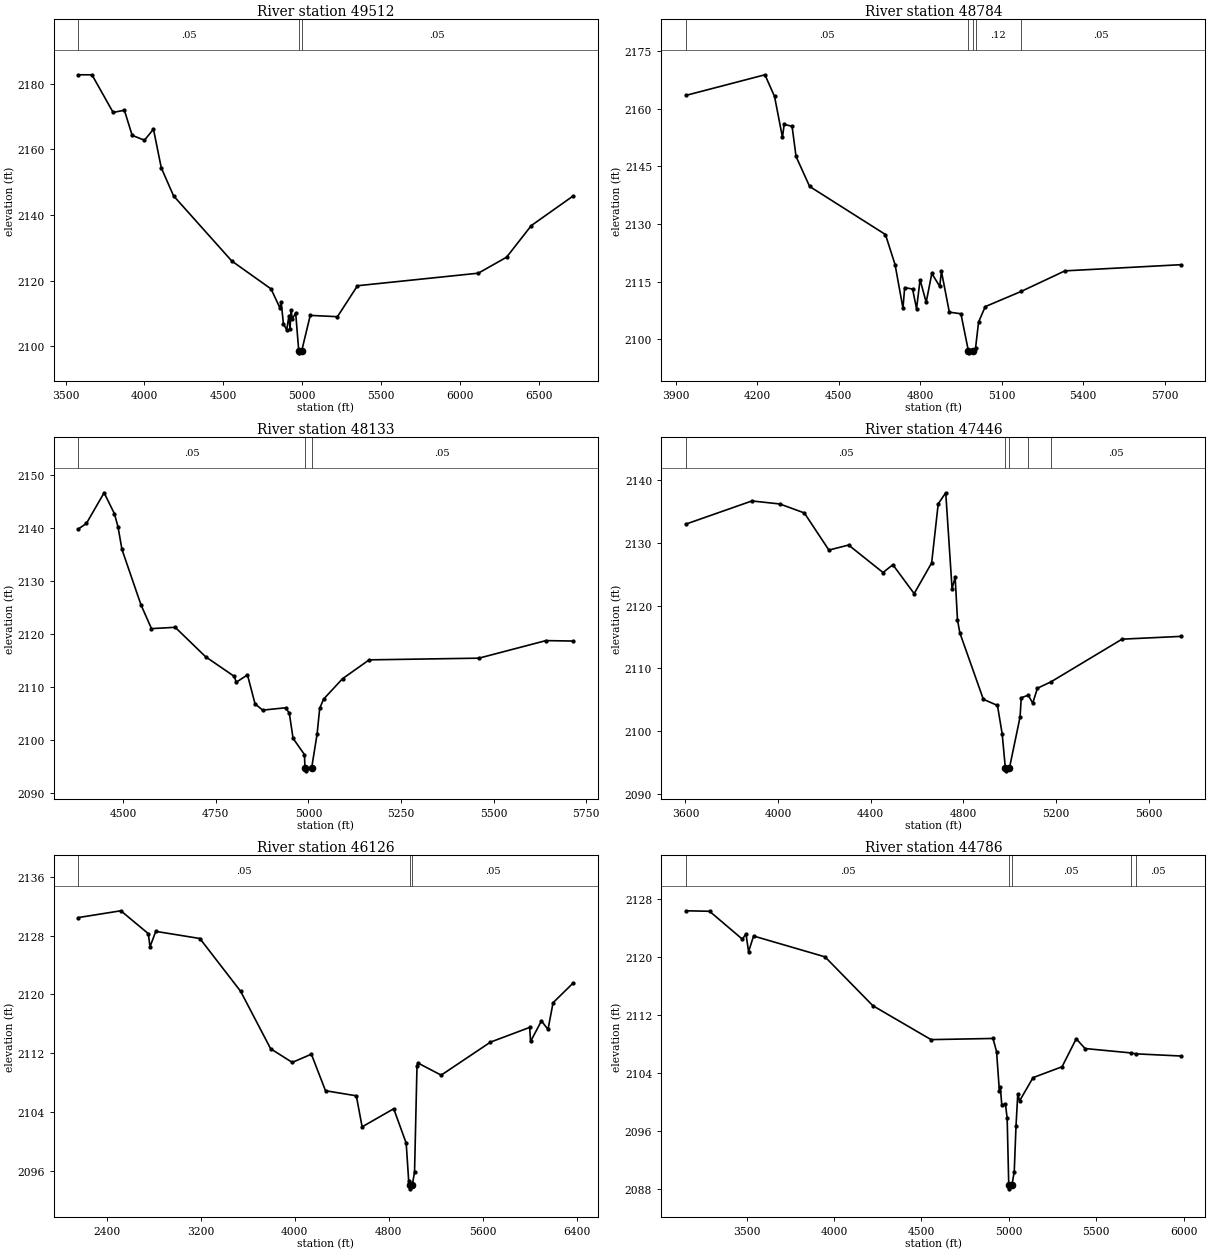
Type RM Length L Ch R = 1,49512,728,728,728
BEGIN DESCRIPTION:
Buffalo Creek 46.0
END DESCRIPTION:
XS GIS Cut Line= 3
      1319830.00      6942763.00      1320755.00      6941688.00
      1321780.00      6940313.00
#Sta/Elev= 30
  3582.1 2182.80  3667.7 2182.79  3801.6 2171.31  3872.9 2171.98  3922.3 2164.31
  4000.2 2162.83  4057.2 2166.21  4106.6 2154.41  4184.5 2145.85  4553.2 2125.97
  4802.2 2117.44  4858.2 2111.63  4865.9 2113.53  4880.1 2106.88  4901.0 2104.93
  4915.3 2109.21  4921.8 2105.15  4929.5 2110.99  4936.1 2108.27  4958.0 2110.09
  4977.6 2098.44  4979.1 2097.94  4995.6 2098.44  5050.2 2109.37  5222.4 2108.97
  5349.5 2118.42  6114.8 2122.25  6294.1 2127.14  6450.5 2136.78  6715.3 2145.81
#Mann=3,-1,0
  3582.1    0.05       0  4977.6    0.05       0  4995.6    0.05       0
Bank Sta=4977.6,4995.6
Exp/Cntr=0.3,0.1

Type RM Length L Ch R = 1,48784,651,651,651
BEGIN DESCRIPTION:
Buffalo Creek 45.0
END DESCRIPTION:
XS GIS Cut Line= 3
      1320616.05      6942886.01      1321255.00      6942038.00
      1321531.33      6941331.39
#Sta/Elev= 30
  3938.5 2163.43  4228.9 2168.78  4264.3 2163.14  4293.4 2152.53  4299.7 2155.88
  4328.8 2155.39  4343.4 2147.54  4393.4 2139.75  4672.4 2127.26  4707.8 2119.45
  4736.9 2108.11  4743.2 2113.46  4772.3 2113.08  4786.9 2107.98  4799.9 2115.50
  4822.3 2109.64  4843.1 2117.14  4872.2 2113.78  4878.5 2117.66  4907.6 2107.07
  4950.2 2106.66  4977.7 2097.00  4979.2 2096.50  4995.7 2097.00  5004.0 2097.70
  5015.2 2104.50  5039.7 2108.51  5171.5 2112.45  5333.1 2117.81  5759.0 2119.41
#Mann=5,-1,0
  3938.5    0.05       0  4977.7    0.05       0  4995.7    0.05       0
  5004.0    0.12       0  5171.5    0.05       0
Bank Sta=4977.7,4995.7
Exp/Cntr=0.3,0.1

Type RM Length L Ch R = 1,48133,687,687,687
BEGIN DESCRIPTION:
Mapping XS e63be25c
END DESCRIPTION:
XS GIS Cut Line= 2
      1321995.17      6942592.35      1321693.39      6941291.60
#Sta/Elev= 30
  4379.2 2139.84  4400.6 2140.86  4448.4 2146.65  4476.1 2142.73  4485.9 2140.25
  4496.6 2135.97  4547.9 2125.53  4576.3 2121.03  4640.3 2121.28  4722.4 2115.73
  4799.9 2112.02  4805.0 2110.91  4835.4 2112.31  4855.9 2106.84  4876.4 2105.66
  4938.1 2106.10  4948.3 2105.13  4958.5 2100.34  4989.3 2097.27  4990.6 2094.71
  4992.1 2094.21  5008.6 2094.71  5023.4 2101.15  5030.4 2105.98  5040.7 2107.72
  5092.0 2111.58  5163.9 2115.14  5460.2 2115.46  5641.1 2118.77  5714.5 2118.69
#Mann=3,-1,0
  4379.2    0.05       0  4990.6    0.05       0  5008.6    0.05       0
Bank Sta=4990.6,5008.6
Exp/Cntr=0.3,0.1

Type RM Length L Ch R = 1,47446,1320,1320,1320
BEGIN DESCRIPTION:
Buffalo Creek 44.0
END DESCRIPTION:
XS GIS Cut Line= 3
      1321823.29      6942857.99      1322512.83      6942111.11
      1322321.85      6941008.64
#Sta/Elev= 30
  3602.5 2132.98  3887.0 2136.66  4007.2 2136.18  4113.2 2134.75  4219.3 2128.84
  4304.3 2129.64  4452.9 2125.27  4495.4 2126.51  4587.3 2121.91  4662.8 2126.79
  4691.2 2136.20  4723.7 2137.96  4750.9 2122.71  4764.3 2124.50  4774.4 2117.73
  4784.6 2115.66  4886.0 2105.09  4946.9 2104.11  4967.2 2099.62  4980.9 2094.20
  4982.4 2093.70  4998.9 2094.20  5044.5 2102.26  5049.6 2105.33  5079.7 2105.74
  5099.2 2104.48  5119.5 2106.85  5178.2 2107.87  5484.8 2114.66  5737.9 2115.10
#Mann=5,-1,0
  3602.5    0.05       0  4980.9    0.05       0  4998.9    0.05       0
  5079.7    0.12       0  5178.2    0.05       0
Bank Sta=4980.9,4998.9
Exp/Cntr=0.3,0.1

Type RM Length L Ch R = 1,46126,1340,1340,1340
BEGIN DESCRIPTION:
Buffalo Creek 43.0
END DESCRIPTION:
XS GIS Cut Line= 3
      1321462.39      6943354.78      1323563.17      6941451.39
      1324439.68      6940392.65
#Sta/Elev= 30
  2161.1 2130.46  2521.7 2131.38  2755.6 2128.27  2769.8 2126.48  2819.1 2128.58
  3194.2 2127.61  3541.0 2120.43  3796.4 2112.62  3980.2 2110.76  4143.1 2111.88
  4263.3 2106.91  4525.6 2106.22  4574.9 2102.00  4843.9 2104.46  4950.0 2099.77
  4971.4 2094.57  4983.6 2094.07  4985.1 2093.57  5001.6 2094.07  5021.0 2095.85
  5041.9 2110.31  5049.7 2110.68  5247.7 2109.03  5667.1 2113.52  6000.5 2115.52
  6008.3 2113.61  6100.8 2116.40  6156.8 2115.25  6199.8 2118.88  6370.4 2121.55
#Mann=3,-1,0
  2161.1    0.05       0  4983.6    0.05       0  5001.6    0.05       0
Bank Sta=4983.6,5001.6
Exp/Cntr=0.3,0.1

Type RM Length L Ch R = 1,44786,996,996,996
BEGIN DESCRIPTION:
Mapping XS f93fbc87
END DESCRIPTION:
XS GIS Cut Line= 3
      1321679.46      6943300.38      1322625.67      6942631.95
      1324274.94      6942371.54
#Sta/Elev= 30
  3154.2 2126.39  3288.9 2126.32  3476.1 2122.48  3497.0 2123.20  3511.8 2120.75
  3540.5 2122.91  3948.8 2120.04  4222.1 2113.31  4555.0 2108.63  4909.3 2108.79
  4929.6 2106.99  4945.9 2101.53  4951.0 2102.10  4959.9 2099.55  4980.2 2099.79
  4990.3 2097.80  4999.4 2088.56  5000.9 2088.06  5017.4 2088.56  5030.8 2090.44
  5040.9 2096.74  5051.1 2101.17  5061.2 2100.18  5138.3 2103.39  5304.2 2104.89
  5385.1 2108.74  5435.8 2107.40  5696.7 2106.80  5726.9 2106.67  5982.4 2106.37
#Mann=5,-1,0
  3154.2    0.05       0  4999.4    0.05       0  5017.4    0.05       0
  5696.7    0.12       0  5726.9    0.05       0
Bank Sta=4999.4,5017.4
Exp/Cntr=0.3,0.1

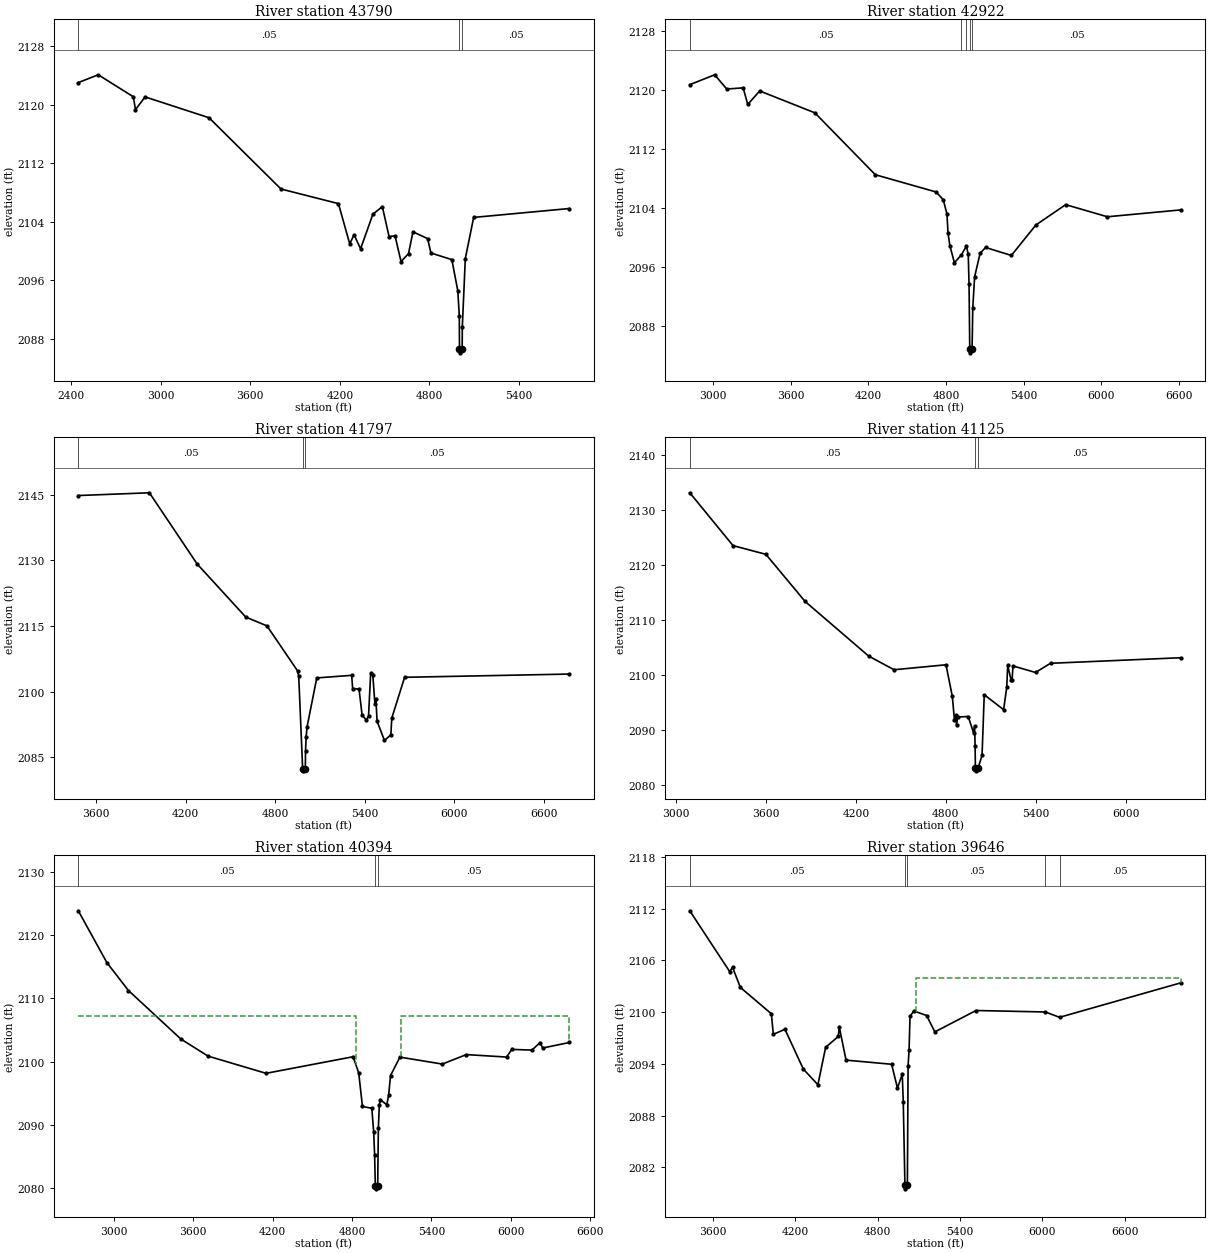
Type RM Length L Ch R = 1,43790,868,868,868
BEGIN DESCRIPTION:
Mapping XS 0ec48eba
END DESCRIPTION:
XS GIS Cut Line= 5
      1321693.08      6943373.62      1322594.13      6942680.91
      1323370.17      6943092.36      1324031.65      6943113.98
      1324364.60      6942603.17
#Sta/Elev= 30
  2449.7 2123.05  2583.3 2124.12  2818.0 2121.11  2832.5 2119.34  2896.8 2121.09
  3324.5 2118.24  3806.1 2108.48  4190.6 2106.48  4266.4 2100.97  4294.9 2102.21
  4338.9 2100.30  4421.2 2105.02  4484.3 2106.08  4529.5 2101.97  4569.5 2102.07
  4609.5 2098.55  4659.6 2099.63  4689.6 2102.62  4787.4 2101.69  4809.6 2099.72
  4949.7 2098.81  4989.7 2094.52  4999.7 2091.04  5000.7 2086.55  5002.2 2086.05
  5018.7 2086.55  5019.7 2089.60  5039.8 2098.96  5095.6 2104.59  5736.2 2105.81
#Mann=3,-1,0
  2449.7    0.05       0  5000.7    0.05       0  5018.7    0.05       0
Bank Sta=5000.7,5018.7
Exp/Cntr=0.3,0.1

Type RM Length L Ch R = 1,42922,1125,1125,1125
BEGIN DESCRIPTION:
Mapping XS 441552e7
END DESCRIPTION:
XS GIS Cut Line= 5
      1321670.83      6943465.27      1322616.99      6942684.03
      1323320.12      6943534.73      1323979.84      6943526.05
      1324674.31      6943118.05
#Sta/Elev= 30
  2820.2 2120.72  3012.9 2122.06  3105.5 2120.13  3233.1 2120.29  3268.3 2118.04
  3360.8 2119.87  3786.8 2116.91  4254.7 2108.52  4723.7 2106.19  4779.7 2105.14
  4808.3 2103.18  4816.2 2100.64  4830.5 2098.93  4865.7 2096.60  4920.4 2097.68
  4957.9 2098.85  4972.5 2097.79  4979.0 2093.66  4984.3 2084.90  4985.8 2084.40
  5002.3 2084.90  5007.7 2090.49  5022.0 2094.69  5064.3 2097.88  5106.7 2098.67
  5305.8 2097.59  5495.8 2101.72  5725.8 2104.47  6048.2 2102.83  6616.1 2103.76
#Mann=5,-1,0
  2820.2    0.05       0  4920.4    0.12       0  4957.9    0.05       0
  4984.3   0.033       0  5002.3    0.05       0
Bank Sta=4984.3,5002.3
Exp/Cntr=0.3,0.1

Type RM Length L Ch R = 1,41797,672,672,672
BEGIN DESCRIPTION:
Buffalo Creek 41.0
END DESCRIPTION:
XS GIS Cut Line= 3
      1322243.63      6945268.85      1323405.00      6944288.00
      1324757.21      6943142.71
#Sta/Elev= 30
  3480.1 2144.79  3956.9 2145.42  4276.7 2129.17  4603.0 2117.03  4744.8 2115.03
  4950.2 2104.75  4958.0 2103.53  4984.1 2082.42  4985.6 2081.92  5002.1 2082.42
  5003.5 2086.45  5007.4 2089.61  5013.9 2091.98  5078.8 2103.14  5312.8 2103.73
  5319.4 2100.72  5362.2 2100.58  5383.1 2094.56  5411.7 2093.55  5425.9 2094.43
  5440.2 2104.18  5454.5 2103.80  5468.8 2097.14  5475.4 2098.25  5483.1 2093.25
  5532.5 2088.86  5575.4 2090.14  5581.9 2093.98  5667.7 2103.28  6772.3 2104.02
#Mann=3,-1,0
  3480.1    0.05       0  4984.1    0.05       0  5002.1    0.05       0
Bank Sta=4984.1,5002.1
Exp/Cntr=0.3,0.1

Type RM Length L Ch R = 1,41125,731,731,731
BEGIN DESCRIPTION:
Buffalo Creek 40.0
END DESCRIPTION:
XS GIS Cut Line= 3
      1322608.25      6945789.65      1323955.00      6944438.00
      1324770.77      6943337.80
#Sta/Elev= 30
  3091.3 2133.07  3380.1 2123.49  3599.3 2121.91  3860.9 2113.37  4285.2 2103.46
  4454.9 2100.98  4801.4 2101.88  4843.8 2096.14  4857.9 2091.85  4865.0 2092.70
  4872.1 2090.94  4879.1 2092.41  4949.9 2092.50  4985.2 2089.53  4992.3 2090.69
  4995.8 2087.09  4997.7 2083.15  4999.2 2082.65  5015.7 2083.15  5042.1 2085.46
  5056.7 2096.45  5186.1 2093.74  5207.0 2097.85  5213.2 2101.76  5235.9 2099.10
  5242.5 2099.19  5248.7 2101.67  5398.9 2100.49  5499.1 2102.15  6369.0 2103.16
#Mann=3,-1,0
  3091.3    0.05       0  4997.7    0.05       0  5015.7    0.05       0
Bank Sta=4997.7,5015.7
Exp/Cntr=0.3,0.1

Type RM Length L Ch R = 1,40394,748,748,748
BEGIN DESCRIPTION:
Buffalo Creek 39.0
END DESCRIPTION:
XS GIS Cut Line= 3
      1322855.62      6946414.68      1324674.29      6944586.81
      1324847.90      6943468.71
#Sta/Elev= 30
  2732.6 2123.84  2949.0 2115.64  3111.6 2111.24  3507.6 2103.58  3712.7 2100.88
  4151.1 2098.16  4808.7 2100.78  4851.1 2098.23  4879.4 2092.92  4950.1 2092.64
  4964.3 2088.87  4971.3 2085.26  4976.5 2080.41  4978.0 2079.91  4994.5 2080.41
  4999.6 2089.47  5006.7 2093.08  5013.8 2094.01  5063.3 2093.18  5077.4 2094.75
  5091.6 2097.81  5162.3 2100.72  5482.8 2099.62  5664.1 2101.12  5967.7 2100.73
  6008.2 2101.94  6160.0 2101.83  6220.7 2103.02  6240.9 2102.16  6442.6 2103.03
#Mann=3,-1,0
  2732.6    0.05       0  4976.5    0.05       0  4994.5    0.05       0
#XS Ineff=2,0
    0.00 4830.30 2107.20 5169.70    0.00 2107.20
Permanent Ineff=
       F       F
Bank Sta=4976.5,4994.5
Exp/Cntr=0.3,0.1

Type RM Length L Ch R = 1,39646,598,598,598
BEGIN DESCRIPTION:
Mapping XS e1f5c627
END DESCRIPTION:
XS GIS Cut Line= 4
      1323563.16      6946607.65      1324715.95      6945420.14
      1324743.73      6944781.25      1324896.51      6943503.47
#Sta/Elev= 30
  3429.3 2111.75  3720.4 2104.70  3741.5 2105.19  3798.1 2102.87  4024.4 2099.81
  4038.6 2097.43  4123.5 2098.01  4257.8 2093.39  4363.8 2091.59  4420.3 2095.93
  4512.4 2097.18  4519.4 2098.29  4569.0 2094.44  4901.3 2093.96  4943.8 2091.20
  4979.0 2092.81  4986.2 2089.63  4998.3 2080.02  4999.8 2079.52  5016.3 2080.02
  5021.5 2093.81  5028.7 2095.63  5035.6 2099.53  5063.9 2100.14  5156.5 2099.61
  5216.6 2097.71  5516.9 2100.19  6022.9 2100.02  6125.8 2099.40  7010.7 2103.40
#Mann=5,-1,0
  3429.3    0.05       0  4998.3    0.05       0  5016.3    0.05       0
  6022.9    0.12       0  6125.8    0.05       0
#XS Ineff=2,0
       0                 5078.00    0.00 2103.96
Permanent Ineff=
       F       F
Bank Sta=4998.3,5016.3
Exp/Cntr=0.3,0.1

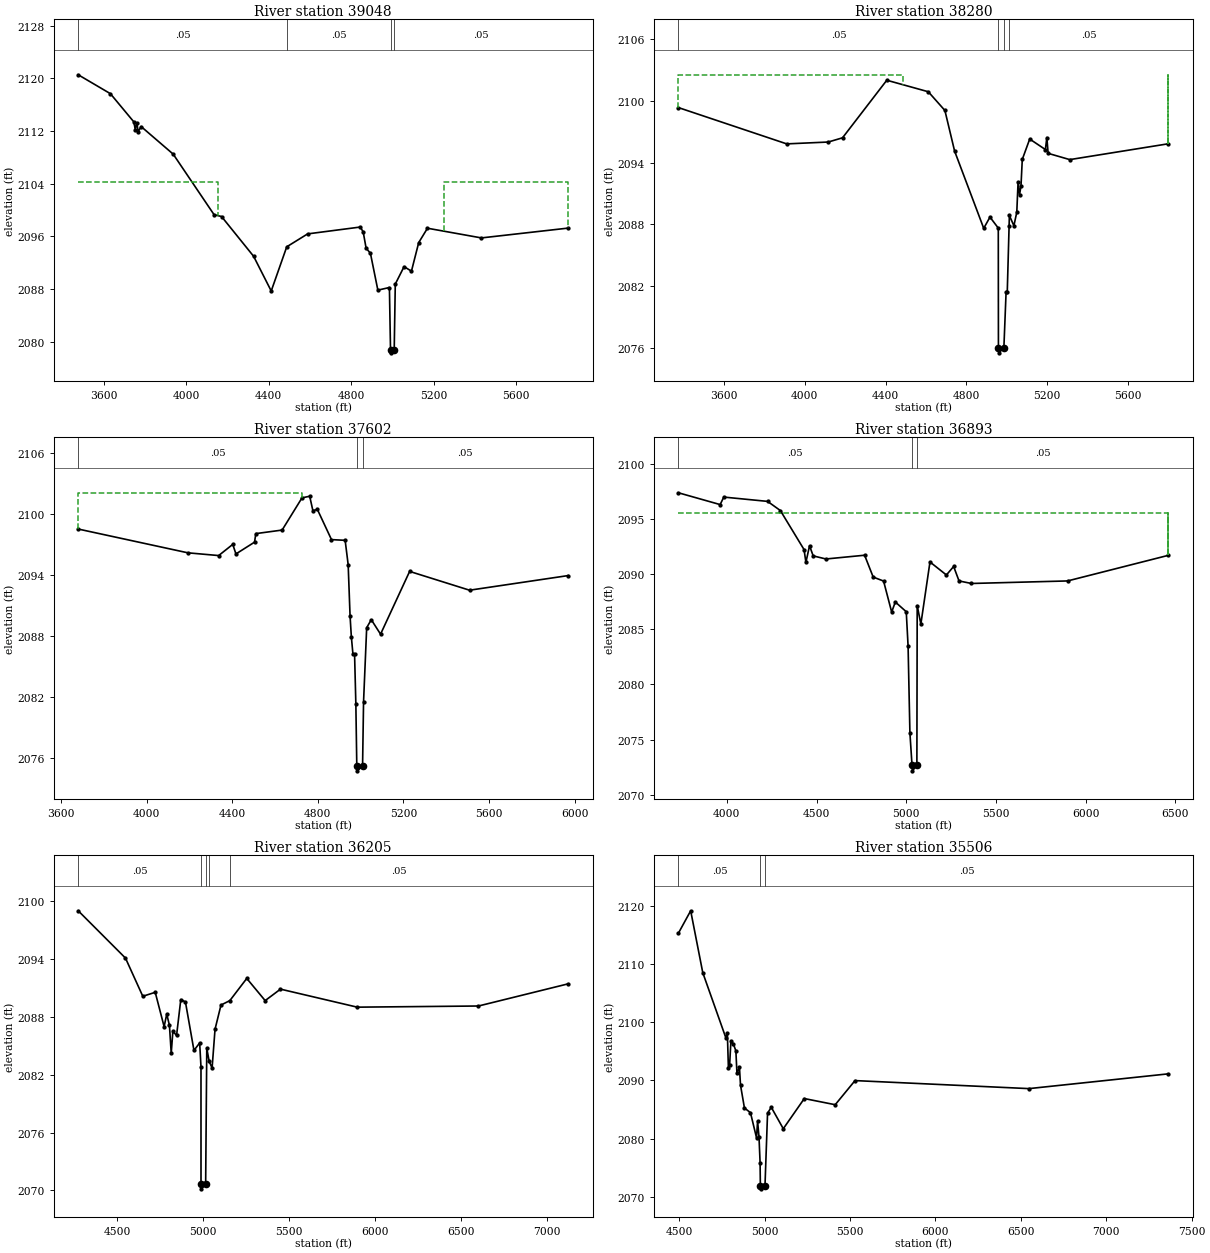
Type RM Length L Ch R = 1,39048,768,768,768
BEGIN DESCRIPTION:
Buffalo Creek 38.0
END DESCRIPTION:
XS GIS Cut Line= 3
      1323938.17      6947121.53      1324938.17      6945982.64
      1325514.58      6945343.74
#Sta/Elev= 30
  3476.8 2120.55  3632.8 2117.68  3746.7 2113.39  3753.3 2112.23  3760.9 2113.27
  3767.6 2111.90  3781.8 2112.69  3937.4 2108.50  4135.8 2099.30  4171.8 2099.03
  4327.4 2092.99  4412.8 2087.72  4488.1 2094.43  4589.3 2096.39  4844.6 2097.43
  4858.8 2096.70  4873.0 2094.22  4893.9 2093.45  4930.0 2087.85  4986.0 2088.25
  4991.3 2078.83  4992.8 2078.33  5009.3 2078.83  5014.5 2088.77  5057.1 2091.42
  5092.9 2090.73  5128.1 2095.07  5170.6 2097.25  5432.2 2095.78  5852.9 2097.27
#Mann=4,-1,0
  3476.8    0.05       0  4488.1    0.05       0  4991.3    0.05       0
  5009.3    0.05       0
#XS Ineff=2,0
    0.00 4153.90 2104.24 5250.00    0.00 2104.24
Permanent Ineff=
       F       F
Bank Sta=4991.3,5009.3
Exp/Cntr=0.3,0.1

Type RM Length L Ch R = 1,38280,678,678,678
BEGIN DESCRIPTION:
Buffalo Creek 37.0
END DESCRIPTION:
XS GIS Cut Line= 4
      1324720.27      6947651.43      1325372.32      6947064.67
      1325555.00      6946338.00      1326055.76      6945712.40
#Sta/Elev= 30
  3373.3 2099.35  3910.1 2095.82  4115.6 2096.00  4186.6 2096.41  4406.0 2102.01
  4611.6 2100.89  4693.9 2099.07  4742.0 2095.12  4886.3 2087.61  4917.3 2088.70
  4958.5 2087.63  4959.2 2076.00  4961.5 2075.50  4986.2 2076.00  4997.2 2081.44
  5003.0 2081.44  5012.0 2087.80  5013.4 2088.86  5035.8 2087.86  5050.2 2089.18
  5056.6 2092.14  5063.8 2090.87  5071.0 2091.74  5077.4 2094.31  5114.2 2096.29
  5191.9 2095.27  5199.1 2096.44  5205.5 2094.90  5312.7 2094.29  5801.1 2095.83
#Mann=4,-1,0
  3373.3    0.05       0  4959.2    0.07       0  4986.2    0.05       0
  5012.0    0.05       0
#XS Ineff=2,0
    0.00 4486.70 2102.54 5800.00    0.00 2102.54
Permanent Ineff=
       F       F
Bank Sta=4959.2,4986.2
Exp/Cntr=0.3,0.1

Type RM Length L Ch R = 1,37602,709,709,709
BEGIN DESCRIPTION:
Buffalo Creek 36.0
END DESCRIPTION:
XS GIS Cut Line= 3
      1324813.16      6947628.49      1325905.00      6946888.00
      1326479.85      6946107.63
#Sta/Elev= 30
  3680.8 2098.51  4193.0 2096.17  4336.8 2095.90  4402.6 2097.00  4417.5 2096.06
  4504.4 2097.22  4510.4 2098.06  4633.2 2098.41  4726.1 2101.58  4762.0 2101.74
  4776.9 2100.32  4797.9 2100.44  4863.8 2097.47  4927.6 2097.40  4941.7 2095.01
  4950.6 2089.94  4956.6 2087.90  4963.8 2086.25  4971.6 2086.20  4977.6 2081.31
  4982.0 2075.21  4984.3 2074.71  5009.0 2075.21  5013.6 2081.52  5028.2 2088.80
  5049.7 2089.59  5093.0 2088.16  5228.8 2094.34  5508.7 2092.49  5969.3 2093.93
#Mann=3,-1,0
  3680.8    0.05       0  4982.0   0.033       0  5009.0    0.05       0
#XS Ineff=2,0
    0.00 4726.40 2102.08               0
Permanent Ineff=
       F       F
Bank Sta=4982,5009
Exp/Cntr=0.3,0.1

Type RM Length L Ch R = 1,36893,688,688,688
BEGIN DESCRIPTION:
Buffalo Creek 35.0
END DESCRIPTION:
XS GIS Cut Line= 4
      1325056.24      6947621.53      1326541.11      6947346.33
      1326667.96      6947336.95      1327097.24      6946331.40
#Sta/Elev= 30
  3729.9 2097.36  3962.6 2096.29  3982.9 2096.97  4227.0 2096.58  4298.2 2095.75
  4430.3 2092.21  4440.6 2091.06  4460.9 2092.56  4481.2 2091.64  4552.4 2091.36
  4767.8 2091.70  4815.6 2089.72  4873.5 2089.36  4918.6 2086.55  4938.9 2087.46
  4999.9 2086.58  5010.1 2083.47  5020.3 2075.59  5032.1 2072.66  5034.4 2072.16
  5059.1 2072.66  5060.9 2087.14  5081.3 2085.46  5132.1 2091.09  5223.7 2089.91
  5264.0 2090.68  5294.1 2089.37  5363.3 2089.14  5898.9 2089.37  6460.6 2091.69
#Mann=3,-1,0
  3729.9    0.05       0  5032.1   0.033       0  5059.1    0.05       0
#XS Ineff=2,0
    0.00 3542.00 2095.55 6458.00    0.00 2095.55
Permanent Ineff=
       F       F
Bank Sta=5032.1,5059.1
Exp/Cntr=0.3,0.1

Type RM Length L Ch R = 1,36205,699,699,699
BEGIN DESCRIPTION:
Buffalo Creek 34.1
END DESCRIPTION:
XS GIS Cut Line= 4
      1325451.64      6947845.56      1326307.67      6948064.67
      1326500.67      6947906.25      1327173.62      6946331.43
#Sta/Elev= 30
  4275.4 2099.02  4549.9 2094.11  4650.5 2090.15  4722.7 2090.56  4774.3 2087.00
  4789.6 2088.30  4805.3 2087.12  4815.6 2084.23  4825.2 2086.53  4846.6 2086.08
  4871.2 2089.81  4898.2 2089.56  4947.7 2084.53  4980.8 2085.31  4988.5 2082.82
  4988.6 2070.67  4990.9 2070.17  5015.6 2070.67  5022.1 2084.76  5035.7 2083.42
  5053.0 2082.70  5070.1 2086.73  5104.7 2089.24  5156.1 2089.70  5254.4 2092.00
  5361.3 2089.70  5450.3 2090.89  5896.2 2089.02  6600.4 2089.14  7121.3 2091.44
#Mann=5,-1,0
  4275.4    0.05       0  4988.6    0.05       0  5015.6   0.033       0
  5035.7    0.05       0  5156.1    0.05       0
Bank Sta=4988.6,5015.6
Exp/Cntr=0.3,0.1

Type RM Length L Ch R = 1,35506,598,598,598
BEGIN DESCRIPTION:
Buffalo Creek 34.0
END DESCRIPTION:
XS GIS Cut Line= 3
      1325904.99      6948838.01      1326305.00      6948538.00
      1327243.73      6946364.58
#Sta/Elev= 30
  4495.9 2115.32  4567.8 2119.18  4638.6 2108.53  4774.0 2097.30  4782.4 2098.20
  4788.6 2092.13  4795.9 2092.73  4803.2 2096.70  4817.8 2096.27  4832.4 2095.08
  4838.6 2091.19  4853.2 2092.26  4859.5 2089.18  4882.4 2085.26  4917.8 2084.45
  4953.2 2080.13  4959.5 2083.00  4967.8 2080.21  4974.0 2075.88  4975.7 2071.85
  4978.0 2071.35  5002.7 2071.85  5017.7 2084.36  5039.5 2085.38  5109.8 2081.69
  5232.8 2086.88  5413.7 2085.82  5529.7 2089.97  6547.5 2088.59  7363.4 2091.13
#Mann=3,-1,0
  4495.9    0.05       0  4975.7   0.033       0  5002.7    0.05       0
Bank Sta=4975.7,5002.7
Exp/Cntr=0.3,0.1