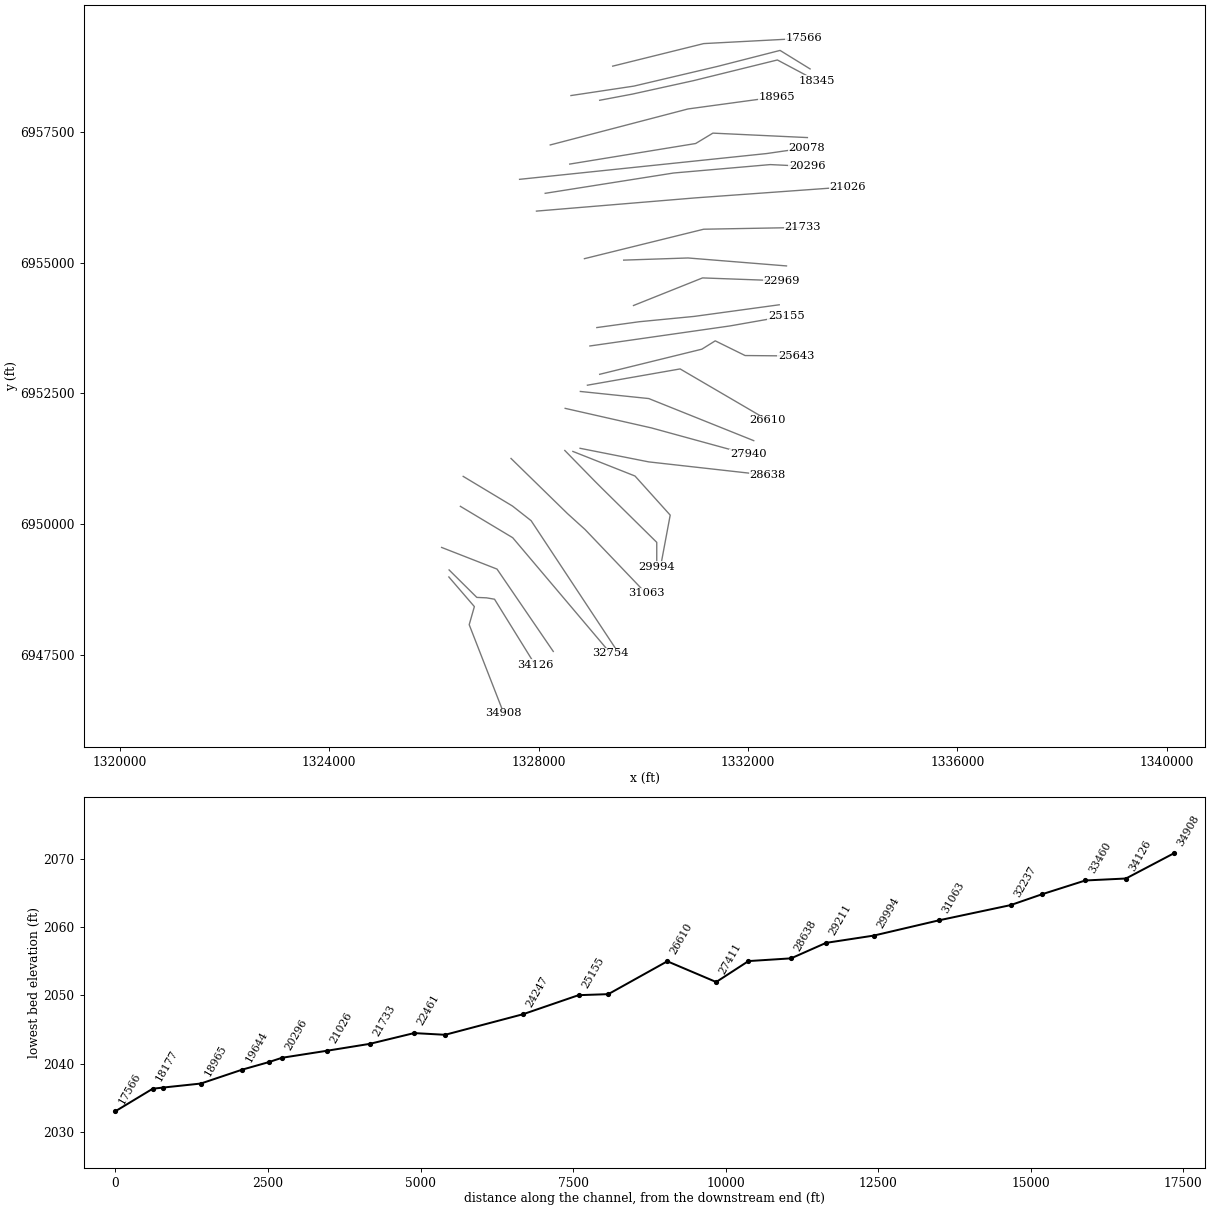
HEC-RAS study Buffalo Creek.prj: Buffalo Creek Base Level Engineering

--- Buffalo Creek.g01 (geometry) --- (continued)

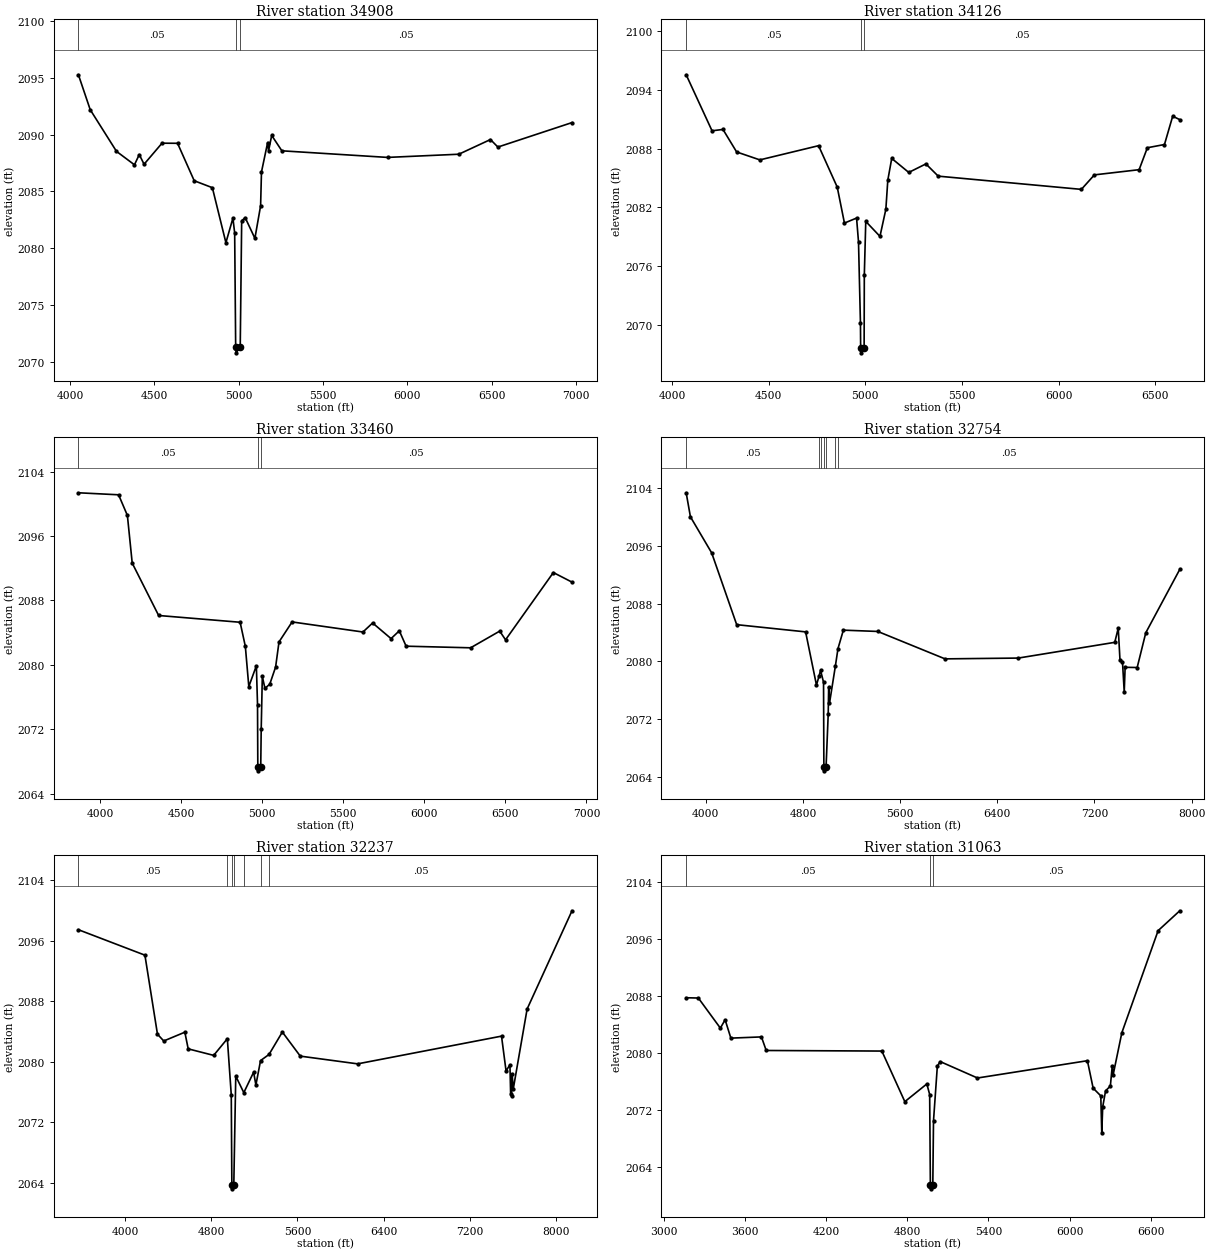
Type RM Length L Ch R = 1,34908,782,782,782
BEGIN DESCRIPTION:
Buffalo Creek 33.1
END DESCRIPTION:
XS GIS Cut Line= 4
      1326284.98      6948987.01      1326772.35      6948420.60
      1326673.48      6948074.56      1327334.02      6946378.45
#Sta/Elev= 30
  4049.8 2095.25  4119.9 2092.18  4275.7 2088.52  4382.2 2087.34  4410.7 2088.24
  4439.2 2087.39  4545.7 2089.24  4637.8 2089.23  4736.6 2085.94  4844.2 2085.33
  4924.5 2080.50  4966.1 2082.65  4976.5 2081.36  4982.5 2071.32  4984.7 2070.82
  5009.5 2071.32  5018.1 2082.42  5038.9 2082.70  5096.5 2080.88  5130.3 2083.74
  5135.5 2086.71  5172.1 2089.30  5177.5 2088.56  5196.1 2089.92  5256.4 2088.57
  5883.0 2087.99  6305.8 2088.27  6493.4 2089.56  6537.6 2088.90  6977.1 2091.05
#Mann=3,-1,0
  4049.8    0.05       0  4982.5   0.033       0  5009.5    0.05       0
Bank Sta=4982.5,5009.5
Exp/Cntr=0.3,0.1

Type RM Length L Ch R = 1,34126,666,666,666
BEGIN DESCRIPTION:
Buffalo Creek 33.0
END DESCRIPTION:
XS GIS Cut Line= 5
      1326289.28      6949121.60      1326818.80      6948596.42
      1327005.00      6948588.00      1327157.35      6948561.70
      1327930.00      6947313.00
#Sta/Elev= 30
  4072.5 2095.53  4206.4 2089.81  4263.0 2089.95  4333.7 2087.65  4453.9 2086.84
  4757.9 2088.29  4854.5 2084.06  4891.8 2080.39  4954.6 2080.90  4964.6 2078.47
  4974.7 2070.14  4975.7 2067.64  4977.2 2067.14  4993.7 2067.64  4994.7 2075.08
  5002.2 2080.56  5075.7 2079.03  5106.2 2081.80  5116.3 2084.77  5136.6 2086.99
  5224.8 2085.56  5313.5 2086.43  5377.3 2085.18  6118.3 2083.83  6185.7 2085.31
  6417.3 2085.84  6459.9 2088.08  6548.5 2088.41  6591.1 2091.30  6627.7 2090.95
#Mann=3,-1,0
  4072.5    0.05       0  4975.7   0.033       0  4993.7    0.05       0
Bank Sta=4975.7,4993.7
Exp/Cntr=0.3,0.1

Type RM Length L Ch R = 1,33460,706,706,706
BEGIN DESCRIPTION:
Buffalo Creek 32.0
END DESCRIPTION:
XS GIS Cut Line= 3
      1326146.46      6949552.10      1327205.00      6949138.00
      1328279.97      6947563.04
#Sta/Elev= 30
  3867.4 2101.36  4115.1 2101.11  4169.4 2098.55  4199.2 2092.63  4362.1 2086.13
  4864.5 2085.29  4896.7 2082.30  4918.1 2077.31  4964.7 2079.89  4971.8 2075.08
  4973.6 2067.35  4975.1 2066.85  4991.6 2067.35  4994.5 2071.99  5001.4 2078.57
  5017.6 2077.08  5047.4 2077.61  5083.3 2079.73  5104.3 2082.85  5185.0 2085.33
  5621.8 2084.08  5681.5 2085.20  5795.2 2083.26  5846.1 2084.23  5888.0 2082.32
  6285.7 2082.12  6465.2 2084.19  6501.1 2083.11  6795.9 2091.46  6910.9 2090.27
#Mann=3,-1,0
  3867.4    0.05       0  4973.6   0.033       0  4991.6    0.05       0
Bank Sta=4973.6,4991.6
Exp/Cntr=0.3,0.1

Type RM Length L Ch R = 1,32754,517,517,517
BEGIN DESCRIPTION:
Buffalo Creek 31.0
END DESCRIPTION:
XS GIS Cut Line= 3
      1326504.97      6950338.02      1327505.00      6949738.00
      1329375.69      6947524.29
#Sta/Elev= 30
  3838.0 2103.38  3873.0 2100.05  4048.0 2095.05  4254.0 2085.10  4821.5 2084.10
  4910.9 2076.73  4932.7 2078.00  4944.4 2078.78  4969.2 2077.11  4971.9 2065.34
  4973.4 2064.84  4989.9 2065.34  5007.5 2072.66  5011.4 2076.46  5017.9 2074.18
  5066.4 2079.34  5088.2 2081.79  5132.3 2084.34  5415.7 2084.16  5969.5 2080.36
  6572.8 2080.47  7367.2 2082.65  7395.8 2084.61  7410.0 2080.26  7430.9 2079.93
  7445.2 2075.77  7452.5 2079.19  7551.8 2079.16  7622.7 2083.98  7902.5 2092.76
#Mann=7,-1,0
  3838.0    0.05       0  4932.7    0.12       0  4944.4    0.05       0
  4971.9    0.05       0  4989.9    0.05       0  5066.4    0.12       0
  5088.2    0.05       0
Bank Sta=4971.9,4989.9
Exp/Cntr=0.3,0.1

Type RM Length L Ch R = 1,32237,1174,1174,1174
BEGIN DESCRIPTION:
Buffalo Creek 30.0
END DESCRIPTION:
XS GIS Cut Line= 4
      1326558.94      6950910.64      1327500.67      6950343.75
      1327857.00      6950063.43      1329527.87      6947532.13
#Sta/Elev= 30
  3565.1 2097.45  4183.0 2094.09  4299.5 2083.66  4357.8 2082.76  4553.9 2083.92
  4585.0 2081.72  4821.7 2080.86  4948.8 2083.06  4985.2 2075.64  4990.7 2063.74
  4992.2 2063.24  5008.7 2063.74  5026.9 2078.12  5101.7 2075.94  5192.9 2078.64
  5214.0 2076.95  5257.2 2080.17  5335.9 2080.98  5459.7 2083.94  5626.4 2080.76
  6159.2 2079.74  7495.9 2083.40  7538.0 2078.81  7574.1 2079.61  7580.5 2075.80
  7589.2 2075.49  7595.2 2078.34  7604.2 2076.36  7733.7 2086.98  8150.7 2099.95
#Mann=7,-1,0
  3565.1    0.05       0  4948.8    0.12       0  4990.7    0.07       0
  5008.7    0.12       0  5101.7    0.05       0  5257.2    0.12       0
  5335.9    0.05       0
Bank Sta=4990.7,5008.7
Exp/Cntr=0.3,0.1

Type RM Length L Ch R = 1,31063,1069,1069,1069
BEGIN DESCRIPTION:
Buffalo Creek 29.1
END DESCRIPTION:
XS GIS Cut Line= 4
      1327472.87      6951253.51      1328551.96      6950198.85
      1328888.77      6949893.29      1330054.83      6948671.61
#Sta/Elev= 30
  3162.9 2087.75  3253.1 2087.71  3415.9 2083.50  3451.1 2084.67  3493.6 2082.10
  3719.9 2082.27  3755.2 2080.37  4610.9 2080.29  4780.9 2073.21  4943.8 2075.69
  4964.7 2074.21  4969.9 2061.51  4971.4 2061.01  4987.9 2061.51  4993.1 2070.53
  5021.5 2078.18  5042.4 2078.82  5318.6 2076.52  6131.9 2078.94  6174.4 2075.10
  6231.0 2074.02  6238.2 2068.82  6245.1 2072.47  6266.5 2074.73  6301.7 2075.39
  6315.9 2078.21  6322.8 2077.00  6386.7 2082.85  6655.2 2097.14  6815.4 2099.92
#Mann=3,-1,0
  3162.9    0.05       0  4969.9    0.05       0  4987.9    0.05       0
Bank Sta=4969.9,4987.9
Exp/Cntr=0.3,0.1

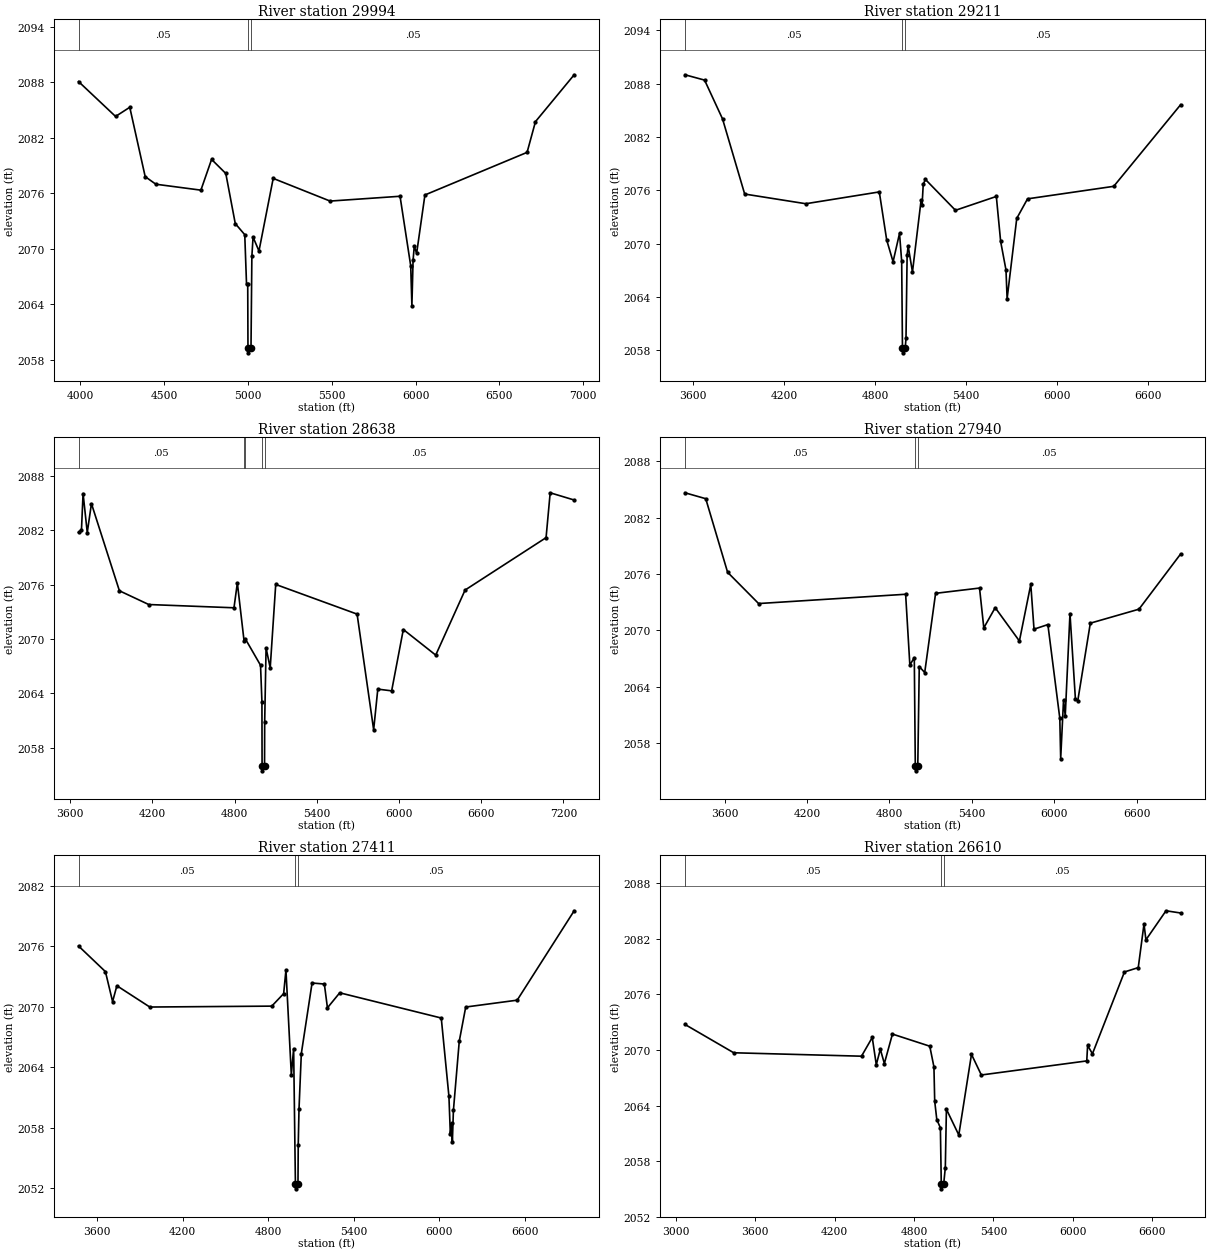
Type RM Length L Ch R = 1,29994,783,783,783
BEGIN DESCRIPTION:
Buffalo Creek 29.0
END DESCRIPTION:
XS GIS Cut Line= 5
      1328500.70      6951406.23      1329080.00      6950813.00
      1329205.00      6950688.00      1330257.62      6949649.31
      1330257.62      6949177.06
#Sta/Elev= 30
  3989.0 2088.07  4210.1 2084.30  4294.8 2085.29  4386.8 2077.80  4450.4 2076.98
  4719.1 2076.34  4782.9 2079.66  4867.7 2078.14  4924.2 2072.73  4980.8 2071.53
  4991.4 2066.17  4998.5 2066.17  5000.0 2059.27  5001.5 2058.77  5018.0 2059.27
  5023.2 2069.20  5030.3 2071.27  5065.6 2069.77  5150.5 2077.61  5489.9 2075.16
  5907.2 2075.68  5970.8 2068.18  5977.9 2063.86  5984.9 2068.75  5992.0 2070.28
  6006.2 2069.52  6055.6 2075.82  6665.1 2080.42  6715.1 2083.74  6946.0 2088.80
#Mann=3,-1,0
  3989.0    0.05       0  5000.0    0.05       0  5018.0    0.05       0
Bank Sta=5000,5018
Exp/Cntr=0.3,0.1

Type RM Length L Ch R = 1,29211,573,573,573
BEGIN DESCRIPTION:
Buffalo Creek 28.0
END DESCRIPTION:
XS GIS Cut Line= 4
      1328654.98      6951388.01      1329841.76      6950917.86
      1330514.57      6950170.15      1330334.01      6949204.87
#Sta/Elev= 30
  3548.6 2089.01  3677.7 2088.41  3796.0 2084.04  3941.8 2075.58  4344.4 2074.49
  4828.4 2075.82  4877.2 2070.40  4919.1 2067.96  4961.6 2071.15  4975.8 2068.00
  4981.0 2058.20  4982.5 2057.70  4999.0 2058.20  5004.2 2059.32  5011.7 2068.71
  5018.4 2069.74  5046.8 2066.80  5103.6 2074.88  5110.3 2074.37  5117.8 2076.68
  5132.0 2077.23  5330.1 2073.75  5599.2 2075.31  5627.6 2070.24  5662.7 2067.04
  5670.2 2063.80  5733.7 2072.84  5804.7 2075.04  6372.4 2076.45  6813.0 2085.64
#Mann=3,-1,0
  3548.6    0.05       0  4981.0    0.05       0  4999.0    0.05       0
Bank Sta=4981,4999
Exp/Cntr=0.3,0.1

Type RM Length L Ch R = 1,28638,698,698,698
BEGIN DESCRIPTION:
Buffalo Creek 27.0
END DESCRIPTION:
XS GIS Cut Line= 3
      1328792.38      6951447.91      1330105.00      6951188.00
      1332368.69      6950934.04
#Sta/Elev= 30
  3661.9 2081.78  3683.5 2082.06  3695.2 2086.08  3725.7 2081.77  3756.3 2084.96
  3960.2 2075.33  4174.3 2073.81  4796.1 2073.45  4820.7 2076.19  4869.4 2069.82
  4879.1 2070.01  4989.8 2067.10  5000.0 2063.06  5001.1 2055.93  5002.6 2055.43
  5019.1 2055.93  5020.1 2060.82  5030.2 2069.01  5060.4 2066.81  5100.6 2076.03
  5694.3 2072.75  5815.1 2059.97  5845.3 2064.46  5946.4 2064.27  6031.5 2071.05
  6267.9 2068.22  6482.1 2075.41  7072.9 2081.20  7102.9 2086.16  7277.9 2085.36
#Mann=5,-1,0
  3661.9    0.05       0  4869.4     0.1       0  4879.1    0.05       0
  5001.1    0.05       0  5019.1    0.05       0
Bank Sta=5001.1,5019.1
Exp/Cntr=0.3,0.1

Type RM Length L Ch R = 1,27940,529,529,529
BEGIN DESCRIPTION:
Buffalo Creek 26.0
END DESCRIPTION:
XS GIS Cut Line= 3
      1328507.60      6952211.81      1330155.00      6951838.00
      1332007.60      6951329.87
#Sta/Elev= 30
  3310.7 2084.65  3461.9 2084.02  3621.2 2076.18  3847.0 2072.85  4917.9 2073.84
  4948.7 2066.30  4981.0 2067.09  4988.4 2055.53  4989.9 2055.03  5006.4 2055.53
  5017.2 2066.14  5056.9 2065.50  5136.1 2073.94  5456.2 2074.50  5487.3 2070.26
  5570.3 2072.41  5746.6 2068.86  5829.5 2074.89  5853.0 2070.12  5954.0 2070.61
  6040.9 2060.63  6047.3 2056.33  6068.0 2062.56  6080.5 2060.89  6115.0 2071.78
  6154.6 2062.67  6171.7 2062.49  6263.2 2070.76  6617.6 2072.25  6921.0 2078.13
#Mann=3,-1,0
  3310.7    0.05       0  4988.4   0.033       0  5006.4    0.05       0
Bank Sta=4988.4,5006.4
Exp/Cntr=0.3,0.1

Type RM Length L Ch R = 1,27411,801,801,801
BEGIN DESCRIPTION:
Mapping XS eea8700f
END DESCRIPTION:
XS GIS Cut Line= 3
      1328797.30      6952535.07      1330104.84      6952399.31
      1332110.91      6951594.11
#Sta/Elev= 30
  3469.3 2076.03  3658.0 2073.49  3708.3 2070.52  3738.4 2072.09  3969.1 2069.98
  4824.7 2070.07  4908.1 2071.31  4924.1 2073.65  4961.9 2063.25  4978.0 2065.86
  4990.5 2052.46  4992.0 2051.96  5008.5 2052.46  5010.3 2056.31  5015.6 2059.83
  5031.9 2065.36  5107.3 2072.36  5193.5 2072.26  5215.1 2069.90  5301.3 2071.39
  6013.4 2068.89  6067.1 2061.14  6077.1 2057.40  6085.9 2058.49  6091.3 2056.60
  6098.6 2059.73  6139.7 2066.60  6184.9 2069.98  6545.8 2070.66  6945.5 2079.52
#Mann=3,-1,0
  3469.3    0.05       0  4990.5   0.033       0  5008.5    0.05       0
Bank Sta=4990.5,5008.5
Exp/Cntr=0.3,0.1

Type RM Length L Ch R = 1,26610,967,967,967
BEGIN DESCRIPTION:
Mapping XS d02c1f6c
END DESCRIPTION:
XS GIS Cut Line= 3
      1328932.64      6952654.86      1330703.94      6952966.00
      1332381.12      6951984.86
#Sta/Elev= 30
  3071.2 2072.76  3439.1 2069.70  4403.7 2069.33  4484.9 2071.35  4515.3 2068.41
  4545.8 2070.08  4576.3 2068.54  4637.2 2071.72  4919.1 2070.41  4950.5 2068.17
  4956.3 2064.47  4972.0 2062.49  4999.2 2061.59  5005.9 2055.50  5007.4 2055.00
  5023.9 2055.50  5036.4 2057.29  5044.6 2063.60  5138.1 2060.82  5233.9 2069.53
  5308.3 2067.30  6104.1 2068.82  6110.5 2070.49  6147.0 2069.59  6388.5 2078.43
  6492.8 2078.90  6536.2 2083.61  6550.7 2081.90  6702.3 2085.04  6812.7 2084.80
#Mann=3,-1,0
  3071.2    0.05       0  5005.9    0.05       0  5023.9    0.05       0
Bank Sta=5005.9,5023.9
Exp/Cntr=0.3,0.1

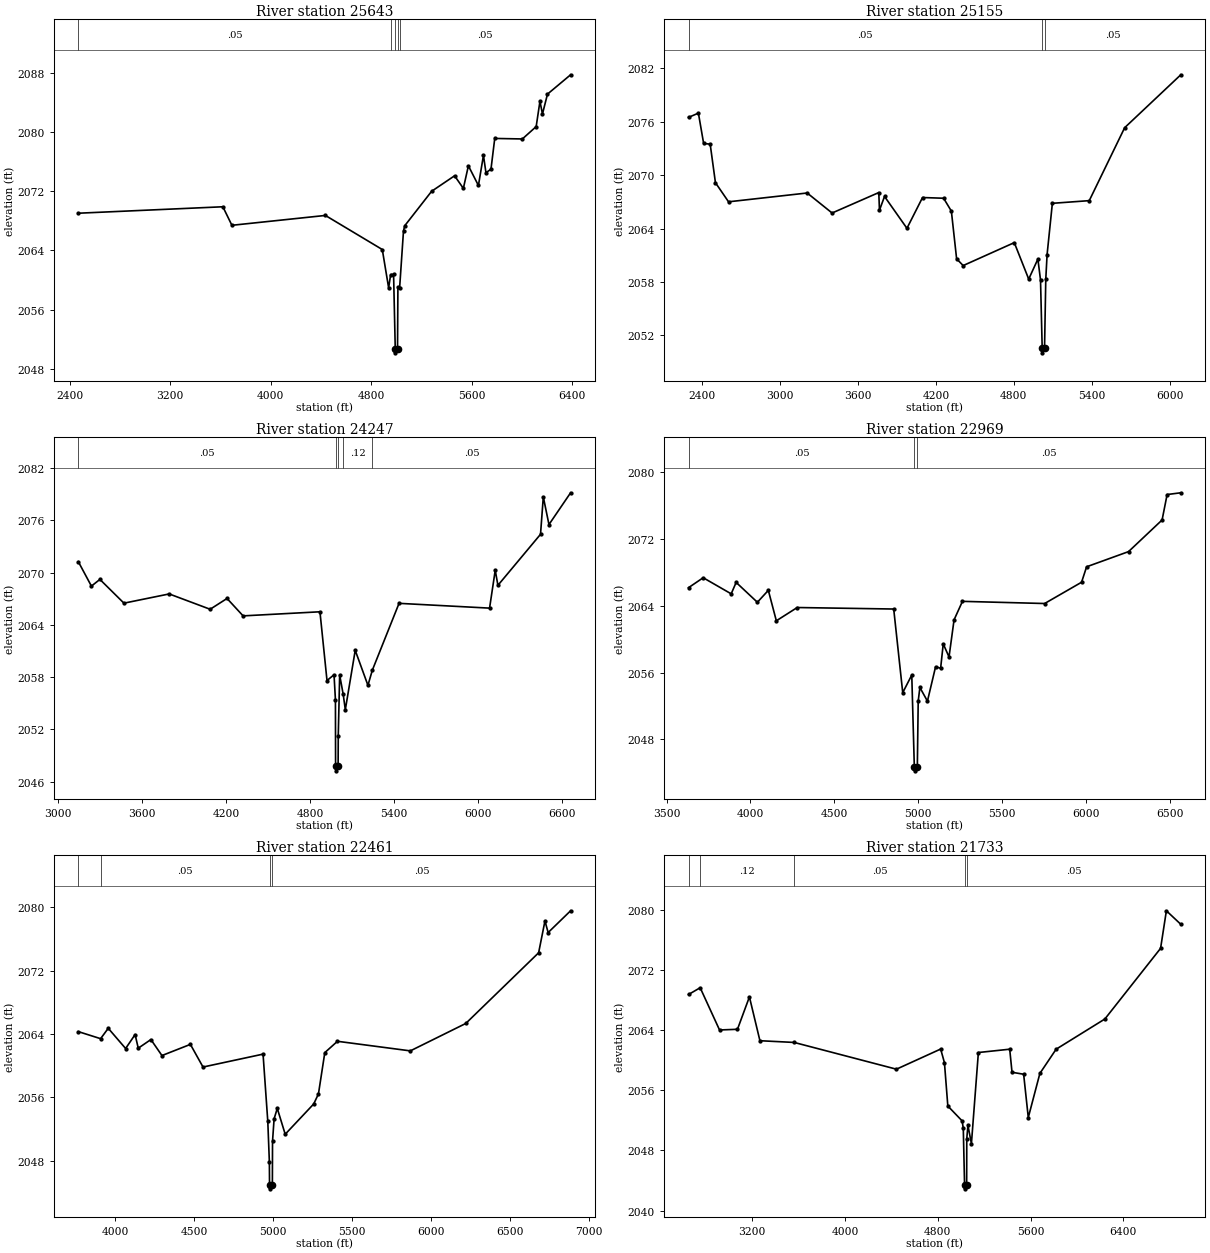
Type RM Length L Ch R = 1,25643,488,488,488
BEGIN DESCRIPTION:
Mapping XS cc0a645e
END DESCRIPTION:
XS GIS Cut Line= 5
      1329167.00      6952863.19      1331119.31      6953343.61
      1331375.24      6953503.04      1331945.84      6953221.94
      1332919.24      6953213.55
#Sta/Elev= 30
  2467.7 2069.02  3619.1 2069.89  3691.1 2067.39  4435.8 2068.72  4889.2 2064.12
  4939.7 2058.95  4955.7 2060.74  4979.1 2060.77  4992.5 2050.68  4994.0 2050.18
  5010.5 2050.68  5013.6 2059.07  5027.3 2058.97  5058.2 2066.67  5068.9 2067.35
  5282.2 2071.98  5465.0 2074.07  5535.0 2072.37  5575.0 2075.42  5655.0 2072.76
  5695.0 2076.82  5715.0 2074.49  5755.0 2074.96  5785.0 2079.11  6005.0 2079.04
  6115.1 2080.71  6145.1 2084.13  6165.1 2082.41  6205.1 2085.09  6389.3 2087.70
#Mann=5,-1,0
  2467.7    0.05       0  4955.7    0.12       0  4992.5    0.07       0
  5010.5    0.12       0  5027.3    0.05       0
Bank Sta=4992.5,5010.5
Exp/Cntr=0.3,0.1

Type RM Length L Ch R = 1,25155,908,908,908
BEGIN DESCRIPTION:
Buffalo Creek 24.0
END DESCRIPTION:
XS GIS Cut Line= 3
      1328979.88      6953404.99      1331655.00      6953788.00
      1332729.83      6953977.44
#Sta/Elev= 30
  2293.1 2076.50  2369.0 2076.98  2409.4 2073.57  2459.9 2073.49  2500.3 2069.16
  2601.3 2067.01  3207.4 2068.00  3399.4 2065.75  3759.4 2068.05  3764.4 2066.06
  3803.5 2067.61  3976.3 2064.03  4096.4 2067.49  4258.9 2067.41  4318.7 2065.96
  4359.1 2060.60  4409.6 2059.84  4803.6 2062.42  4914.7 2058.32  4985.4 2060.57
  5005.7 2058.23  5018.7 2050.53  5020.2 2050.03  5036.7 2050.53  5046.3 2058.31
  5056.4 2061.08  5097.0 2066.84  5381.4 2067.14  5654.2 2075.34  6086.9 2081.29
#Mann=3,-1,0
  2293.1    0.05       0  5018.7    0.05       0  5036.7    0.05       0
Bank Sta=5018.7,5036.7
Exp/Cntr=0.3,0.1

Type RM Length L Ch R = 1,24247,1278,1278,1278
BEGIN DESCRIPTION:
Buffalo Creek 23.0
END DESCRIPTION:
XS GIS Cut Line= 4
      1329112.58      6953756.94      1329920.73      6953868.29
      1330972.94      6953970.51      1332597.96      6954192.73
#Sta/Elev= 30
  3145.5 2071.26  3238.8 2068.46  3299.4 2069.23  3471.0 2066.50  3794.0 2067.56
  4086.1 2065.80  4206.7 2067.04  4321.3 2065.04  4869.8 2065.51  4920.1 2057.61
  4970.3 2058.28  4980.3 2055.38  4981.4 2047.74  4982.9 2047.24  4999.4 2047.74
  5000.4 2051.23  5010.5 2058.25  5035.8 2056.02  5050.8 2054.26  5121.5 2061.08
  5212.3 2057.06  5243.6 2058.80  5434.3 2066.48  6080.3 2065.93  6120.7 2070.28
  6139.9 2068.55  6443.9 2074.41  6463.8 2078.70  6504.2 2075.53  6658.6 2079.18
#Mann=5,-1,0
  3145.5    0.05       0  4981.4    0.05       0  4999.4    0.05       0
  5035.8    0.12       0  5243.6    0.05       0
Bank Sta=4981.4,4999.4
Exp/Cntr=0.3,0.1

Type RM Length L Ch R = 1,22969,508,508,508
BEGIN DESCRIPTION:
Buffalo Creek 22.0
END DESCRIPTION:
XS GIS Cut Line= 3
      1329813.18      6954178.82      1331132.66      6954706.62
      1332646.52      6954651.06
#Sta/Elev= 30
  3630.9 2066.17  3718.3 2067.36  3885.2 2065.43  3914.8 2066.80  4041.4 2064.42
  4106.8 2065.85  4154.5 2062.20  4279.1 2063.79  4854.6 2063.61  4908.4 2053.59
  4962.3 2055.70  4977.5 2044.72  4979.0 2044.22  4995.5 2044.72  5000.7 2052.57
  5010.7 2054.21  5055.7 2052.57  5104.4 2056.70  5134.4 2056.51  5150.0 2059.43
  5184.5 2057.87  5214.5 2062.31  5264.5 2064.53  5754.8 2064.27  5975.0 2066.82
  6005.0 2068.67  6255.2 2070.49  6455.3 2074.28  6485.3 2077.33  6566.9 2077.54
#Mann=3,-1,0
  3630.9    0.05       0  4977.5    0.05       0  4995.5    0.05       0
Bank Sta=4977.5,4995.5
Exp/Cntr=0.3,0.1

Type RM Length L Ch R = 1,22461,728,728,728
BEGIN DESCRIPTION:
Buffalo Creek 21.0
END DESCRIPTION:
XS GIS Cut Line= 3
      1329625.69      6955046.89      1330855.00      6955088.00
      1332736.86      6954935.78
#Sta/Elev= 30
  3765.9 2064.31  3906.9 2063.42  3955.3 2064.73  4065.4 2062.18  4125.4 2063.94
  4145.4 2062.22  4225.5 2063.31  4295.5 2061.29  4475.6 2062.70  4555.6 2059.84
  4935.9 2061.47  4965.9 2052.98  4975.9 2047.86  4976.9 2044.97  4978.4 2044.47
  4994.9 2044.97  4995.9 2050.49  5005.9 2053.31  5026.0 2054.62  5076.2 2051.36
  5256.7 2055.18  5286.8 2056.45  5327.0 2061.66  5407.2 2063.09  5868.7 2061.88
  6219.9 2065.34  6681.4 2074.26  6721.5 2078.28  6741.6 2076.81  6883.9 2079.56
#Mann=4,-1,0
  3765.9    0.12       0  3906.9    0.05       0  4976.9    0.05       0
  4994.9    0.05       0
Bank Sta=4976.9,4994.9
Exp/Cntr=0.3,0.1

Type RM Length L Ch R = 1,21733,707,707,707
BEGIN DESCRIPTION:
Buffalo Creek 20.0
END DESCRIPTION:
XS GIS Cut Line= 3
      1328875.71      6955074.67      1331155.00      6955638.00
      1333049.32      6955671.89
#Sta/Elev= 30
  2652.0 2068.75  2752.2 2069.65  2919.1 2064.03  3073.6 2064.12  3176.6 2068.43
  3267.2 2062.60  3562.5 2062.37  4443.6 2058.81  4824.8 2061.49  4857.4 2059.68
  4886.6 2053.91  5009.9 2051.93  5019.9 2050.93  5030.9 2043.39  5032.4 2042.89
  5048.9 2043.39  5049.9 2049.56  5059.9 2051.34  5089.9 2048.90  5149.9 2061.03
  5419.9 2061.47  5439.9 2058.40  5540.0 2058.14  5580.0 2052.38  5680.0 2058.25
  5820.0 2061.47  6240.1 2065.49  6720.2 2074.89  6770.2 2079.89  6894.5 2078.09
#Mann=5,-1,0
  2652.0    0.05       0  2752.2    0.12       0  3562.5    0.05       0
  5030.9    0.05       0  5048.9    0.05       0
Bank Sta=5030.9,5048.9
Exp/Cntr=0.3,0.1

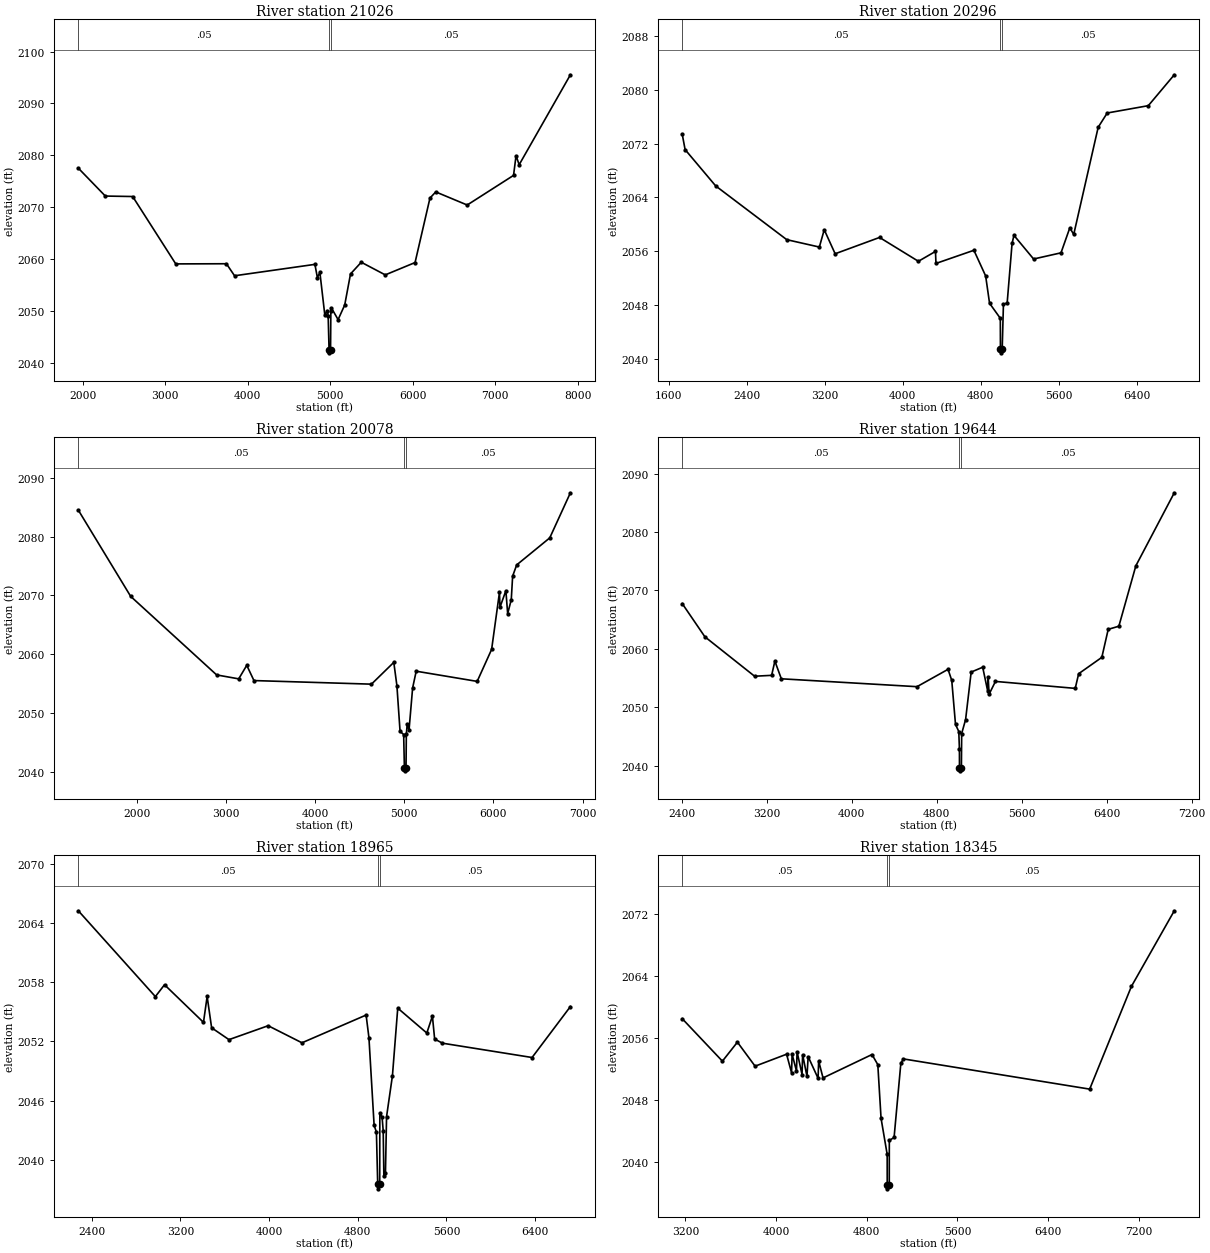
Type RM Length L Ch R = 1,21026,730,730,730
BEGIN DESCRIPTION:
Buffalo Creek 19.0
END DESCRIPTION:
XS GIS Cut Line= 3
      1327959.01      6955984.39      1331005.00      6956238.00
      1333901.90      6956447.55
#Sta/Elev= 30
  1948.4 2077.50  2275.5 2072.12  2606.7 2072.03  3128.5 2059.03  3742.5 2059.06
  3840.9 2056.74  4814.3 2058.94  4844.4 2056.38  4874.5 2057.40  4934.7 2049.12
  4964.8 2050.03  4974.8 2049.06  4985.9 2042.37  4987.3 2041.87  5003.9 2042.37
  5007.4 2049.96  5015.0 2050.51  5095.2 2048.28  5175.4 2051.10  5245.6 2057.09
  5375.9 2059.35  5666.7 2056.91  6027.6 2059.29  6208.1 2071.73  6278.2 2072.92
  6659.2 2070.39  7220.7 2076.11  7250.8 2079.90  7288.9 2078.17  7909.4 2095.52
#Mann=3,-1,0
  1948.4    0.05       0  4985.9    0.05       0  5003.9    0.05       0
Bank Sta=4985.9,5003.9
Exp/Cntr=0.3,0.1

Type RM Length L Ch R = 1,20296,218,218,218
BEGIN DESCRIPTION:
Buffalo Creek 18.2
END DESCRIPTION:
XS GIS Cut Line= 4
      1328125.73      6956324.67      1330580.00      6956713.00
      1332426.64      6956873.86      1333134.41      6956840.30
#Sta/Elev= 30
  1736.9 2073.41  1766.5 2071.11  2080.4 2065.70  2809.1 2057.70  3143.5 2056.60
  3193.5 2059.18  3305.4 2055.60  3761.0 2058.03  4159.3 2054.48  4334.5 2055.95
  4339.5 2054.16  4728.6 2056.12  4849.1 2052.30  4889.2 2048.23  4999.6 2045.99
  5000.7 2041.35  5002.1 2040.85  5018.7 2041.35  5031.5 2048.05  5069.9 2048.30
  5120.1 2057.14  5139.4 2058.34  5340.9 2054.82  5622.0 2055.74  5712.3 2059.46
  5752.5 2058.48  6003.4 2074.44  6096.1 2076.56  6517.5 2077.65  6783.9 2082.25
#Mann=3,-1,0
  1736.9    0.05       0  5000.7    0.05       0  5018.7    0.05       0
Bank Sta=5000.7,5018.7
Exp/Cntr=0.3,0.1

Type RM Length L Ch R = 1,20078,434,434,434
BEGIN DESCRIPTION:
Buffalo Creek 18.1
END DESCRIPTION:
XS GIS Cut Line= 3
      1327636.17      6956592.04      1332358.36      6957085.09
      1333121.17      6957196.04
#Sta/Elev= 30
  1344.8 2084.48  1931.8 2069.84  2895.9 2056.50  3143.4 2055.83  3233.8 2058.13
  3314.3 2055.54  4632.3 2054.93  4882.8 2058.63  4917.5 2054.70  4953.1 2046.91
  4993.4 2046.38  5001.8 2040.71  5003.3 2040.21  5019.9 2040.71  5023.5 2046.39
  5033.6 2048.20  5053.7 2047.14  5093.9 2054.28  5134.1 2057.13  5817.8 2055.40
  5980.0 2060.83  6068.3 2070.55  6073.4 2067.98  6139.8 2070.80  6160.0 2066.90
  6200.4 2069.29  6215.6 2073.27  6261.1 2075.18  6631.9 2079.77  6863.5 2087.43
#Mann=3,-1,0
  1344.8    0.05       0  5001.8   0.033       0  5019.9    0.05       0
Bank Sta=5001.8,5019.9
Exp/Cntr=0.3,0.1

Type RM Length L Ch R = 1,19644,679,679,679
BEGIN DESCRIPTION:
Buffalo Creek 18.0
END DESCRIPTION:
XS GIS Cut Line= 4
      1328594.43      6956883.69      1331000.98      6957276.98
      1331330.00      6957475.50      1333136.16      6957390.64
#Sta/Elev= 30
  2405.2 2067.75  2618.6 2062.06  3086.3 2055.31  3246.8 2055.46  3277.2 2057.90
  3338.0 2054.87  4614.7 2053.52  4906.8 2056.49  4941.8 2054.60  4977.1 2047.06
  5008.1 2045.84  5014.0 2042.78  5014.5 2039.61  5016.0 2039.11  5032.6 2039.61
  5035.3 2045.50  5072.2 2047.90  5124.6 2056.02  5233.0 2056.85  5279.6 2052.81
  5284.6 2055.19  5293.0 2052.22  5353.1 2054.42  6103.9 2053.23  6136.2 2055.74
  6354.2 2058.54  6414.3 2063.34  6514.4 2063.87  6674.5 2074.22  7036.1 2086.72
#Mann=3,-1,0
  2405.2    0.05       0  5014.5   0.033       0  5032.6    0.05       0
Bank Sta=5014.5,5032.6
Exp/Cntr=0.3,0.1

Type RM Length L Ch R = 1,18965,620,620,620
BEGIN DESCRIPTION:
Buffalo Creek 17.0
END DESCRIPTION:
XS GIS Cut Line= 3
      1328222.37      6957249.77      1330855.00      6957938.00
      1332558.93      6958170.28
#Sta/Elev= 30
  2278.5 2065.23  2973.7 2056.54  3056.4 2057.74  3407.9 2053.93  3441.0 2056.55
  3481.4 2053.38  3638.0 2052.18  3991.6 2053.59  4296.8 2051.86  4875.6 2054.67
  4901.1 2052.38  4947.9 2043.50  4968.6 2042.82  4980.2 2037.57  4981.7 2037.07
  4998.3 2037.57  4999.6 2044.73  5019.8 2044.33  5029.9 2042.96  5035.8 2038.37
  5050.1 2038.65  5060.2 2044.38  5113.2 2048.52  5161.1 2055.37  5423.5 2052.85
  5474.0 2054.56  5494.1 2052.24  5564.8 2051.82  6373.3 2050.37  6719.3 2055.53
#Mann=3,-1,0
  2278.5    0.05       0  4980.2   0.033       0  4998.3    0.05       0
Bank Sta=4980.2,4998.3
Exp/Cntr=0.3,0.1

Type RM Length L Ch R = 1,18345,168,168,168
BEGIN DESCRIPTION:
Buffalo Creek 16.0
END DESCRIPTION:
XS GIS Cut Line= 5
      1329166.75      6958103.92      1329791.79      6958221.98
      1330958.46      6958478.93      1332562.63      6958874.76
      1333318.66      6958472.47
#Sta/Elev= 30
  3172.4 2058.51  3526.8 2053.01  3659.1 2055.47  3815.1 2052.36  4092.8 2053.91
  4136.5 2051.51  4141.6 2053.90  4180.2 2051.73  4185.3 2054.22  4229.1 2051.28
  4234.2 2053.85  4272.6 2051.04  4283.0 2053.60  4370.5 2050.79  4375.6 2053.04
  4414.2 2050.84  4846.0 2053.87  4897.2 2052.56  4925.9 2045.61  4979.9 2040.94
  4980.3 2036.98  4981.8 2036.48  4998.4 2036.98  4998.8 2042.74  5040.8 2043.13
  5100.5 2052.75  5123.2 2053.30  6765.6 2049.39  7133.8 2062.69  7511.8 2072.48
#Mann=3,-1,0
  3172.4    0.05       0  4980.3    0.05       0  4998.4    0.05       0
Bank Sta=4980.3,4998.4
Exp/Cntr=0.3,0.1

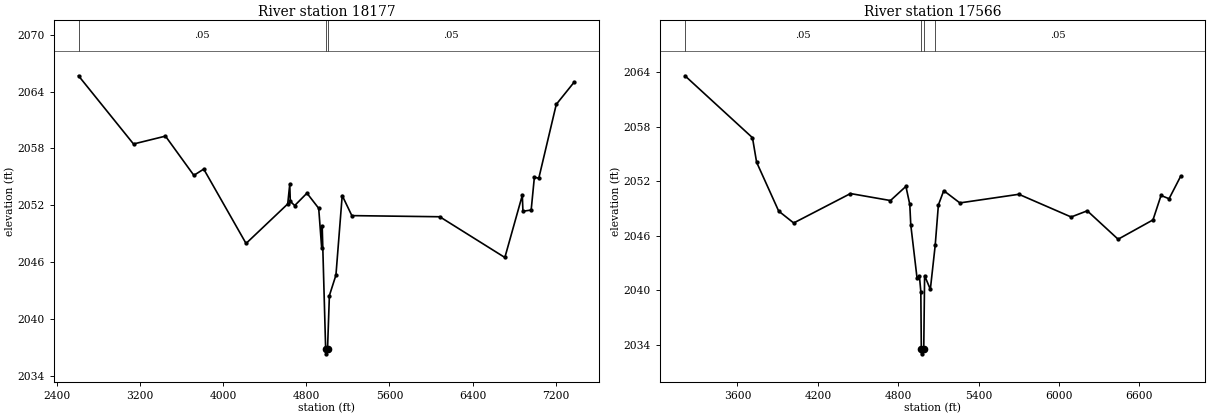
Type RM Length L Ch R = 1,18177,611,611,611
BEGIN DESCRIPTION:
Buffalo Creek 15.1
END DESCRIPTION:
XS GIS Cut Line= 5
      1328618.18      6958194.21      1329819.57      6958374.76
      1331416.47      6958751.13      1332613.65      6959057.53
      1333187.74      6958703.46
#Sta/Elev= 30
  2610.0 2065.66  3138.9 2058.46  3446.1 2059.29  3719.1 2055.15  3814.1 2055.81
  4220.9 2047.96  4621.6 2052.13  4641.2 2054.21  4646.3 2052.41  4688.7 2051.96
  4806.5 2053.27  4919.5 2051.67  4947.9 2047.52  4953.0 2049.80  4986.3 2036.81
  4987.8 2036.31  5004.4 2036.81  5022.2 2042.46  5085.2 2044.62  5145.5 2053.02
  5238.0 2050.90  6083.4 2050.78  6709.4 2046.48  6877.3 2053.05  6883.2 2051.36
  6962.4 2051.49  6993.2 2054.95  7035.8 2054.85  7203.7 2062.64  7375.8 2064.99
#Mann=3,-1,0
  2610.0    0.05       0  4986.3   0.033       0  5004.4    0.05       0
Bank Sta=4986.3,5004.4
Exp/Cntr=0.3,0.1

Type RM Length L Ch R = 1,17566,610,610,610
BEGIN DESCRIPTION:
Buffalo Creek 15.0
END DESCRIPTION:
XS GIS Cut Line= 3
      1329415.96      6958756.72      1331155.00      6959188.00
      1333061.13      6959288.50
#Sta/Elev= 30
  3207.9 2063.63  3711.8 2056.81  3742.7 2054.11  3907.5 2048.73  4019.5 2047.42
  4443.6 2050.66  4742.0 2049.89  4857.4 2051.45  4886.3 2049.46  4893.6 2047.22
  4940.1 2041.40  4958.4 2041.54  4968.7 2039.87  4972.4 2033.51  4973.9 2033.01
  4990.5 2033.51  4997.0 2041.62  5039.7 2040.11  5076.0 2044.95  5099.8 2049.40
  5139.8 2050.98  5260.0 2049.63  5700.6 2050.58  6091.1 2048.08  6211.3 2048.76
  6441.6 2045.63  6702.0 2047.76  6762.1 2050.45  6822.1 2050.09  6908.4 2052.56
#Mann=4,-1,0
  3207.9    0.05       0  4972.4    0.07       0  4990.5    0.05       0
  5076.0    0.05       0
Bank Sta=4972.4,4990.5
Exp/Cntr=0.3,0.1