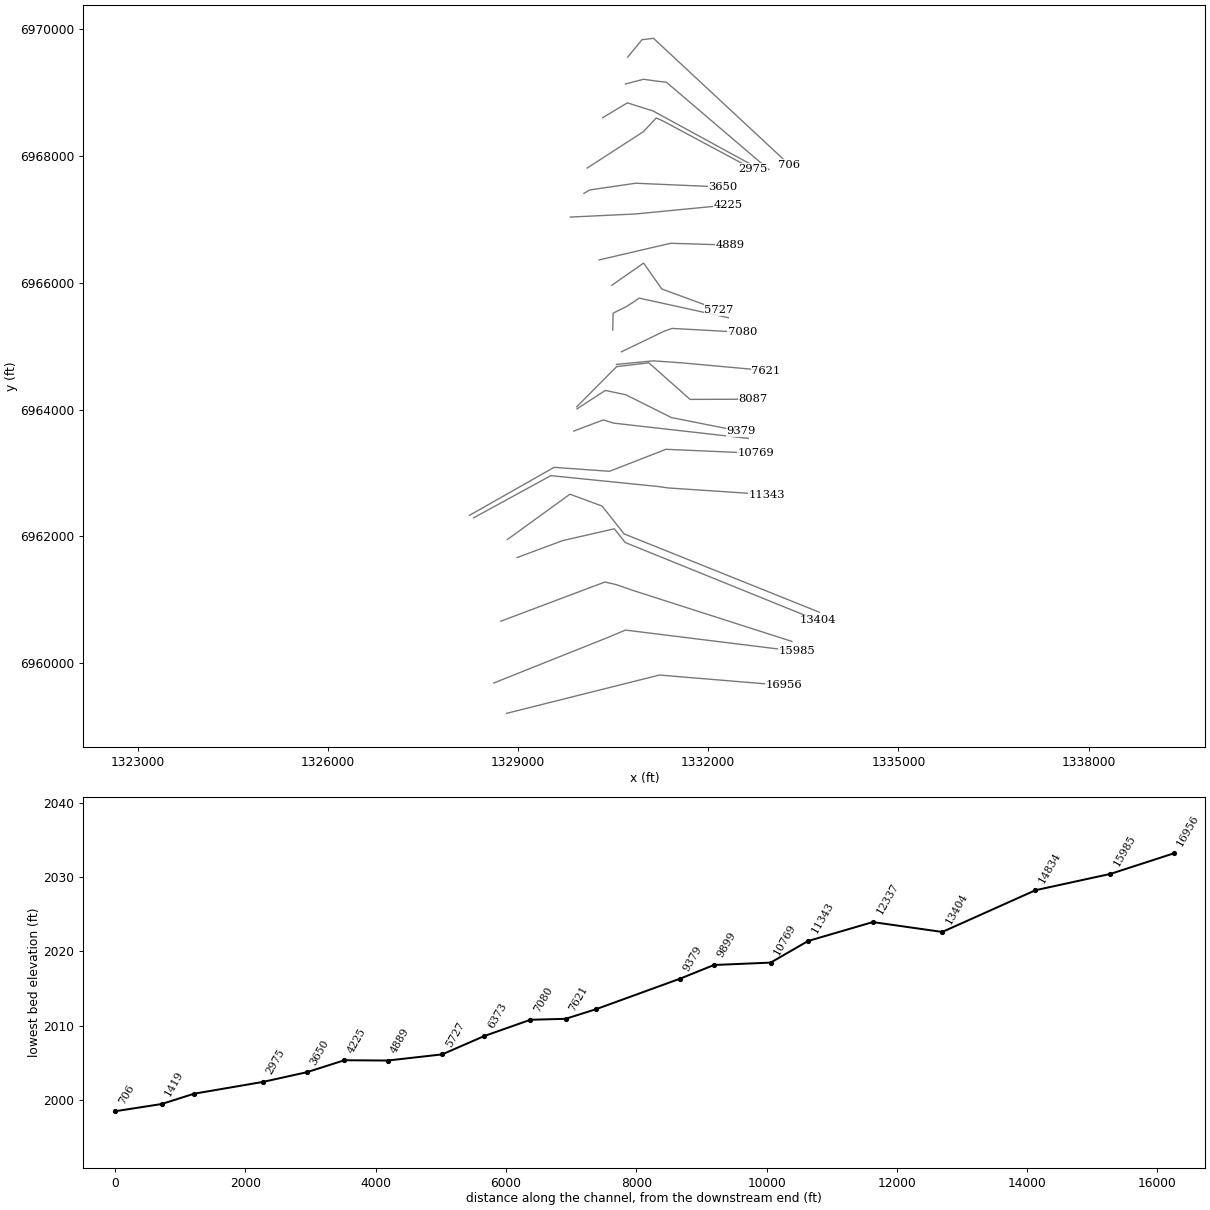
HEC-RAS study Buffalo Creek.prj: Buffalo Creek Base Level Engineering

--- Buffalo Creek.g01 (geometry) --- (continued)

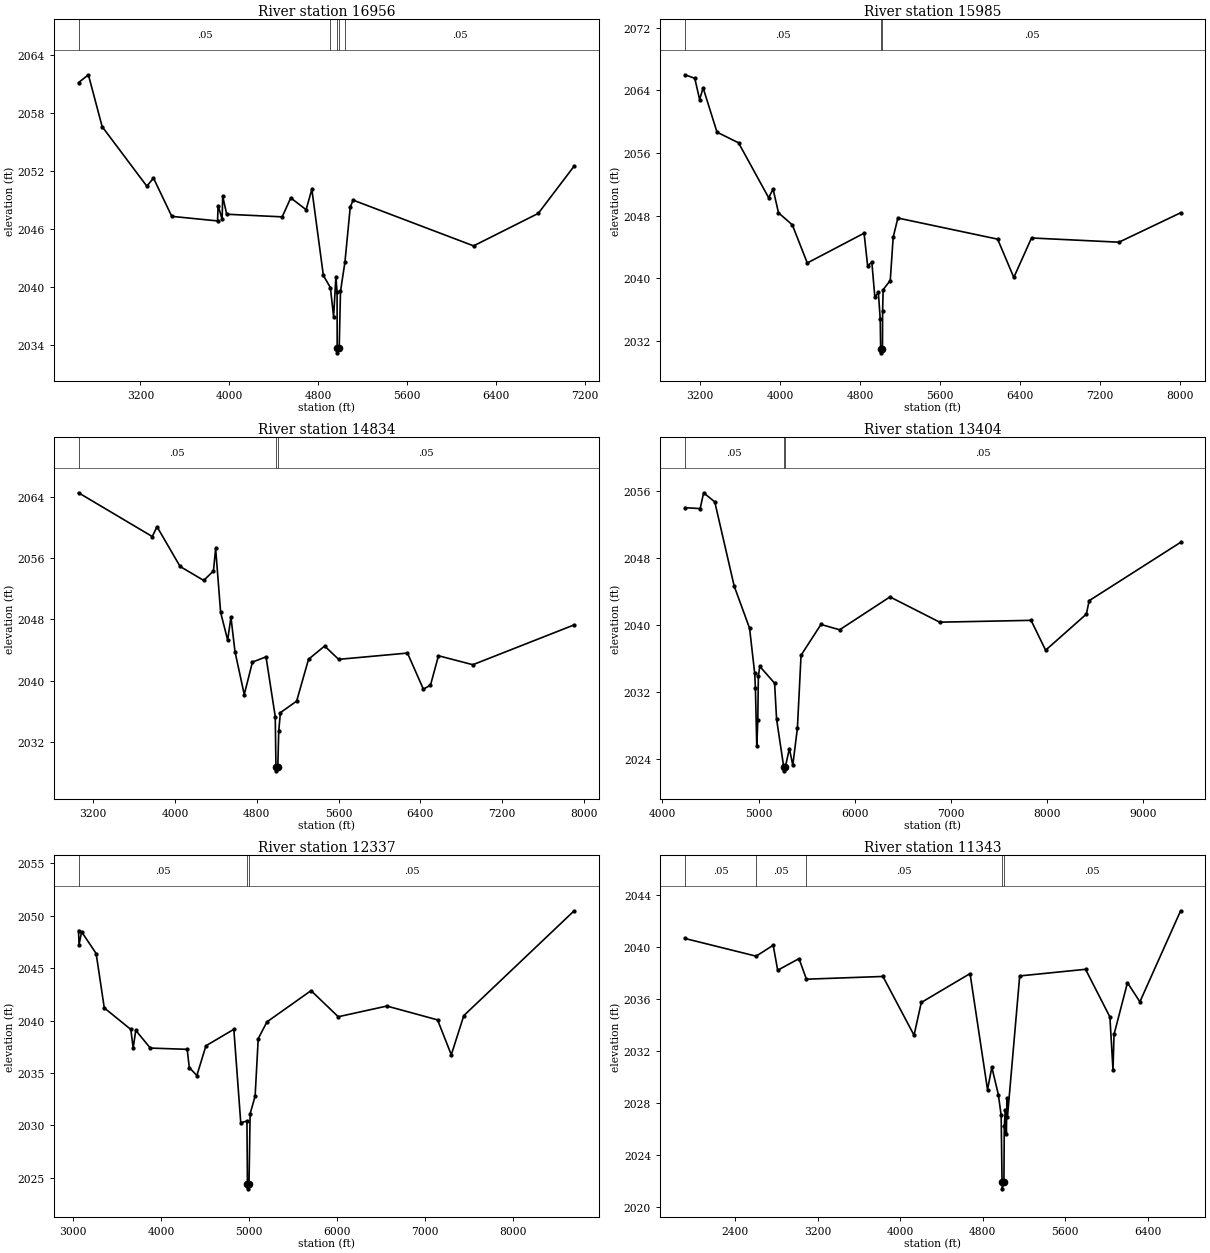
Type RM Length L Ch R = 1,16956,971,971,971
BEGIN DESCRIPTION:
Buffalo Creek 14.4
END DESCRIPTION:
XS GIS Cut Line= 3
      1328818.73      6959208.10      1331230.00      6959813.00
      1333196.82      6959649.35
#Sta/Elev= 30
  2642.6 2061.14  2731.5 2061.95  2855.3 2056.59  3257.3 2050.43  3317.2 2051.27
  3481.8 2047.31  3893.5 2046.84  3898.7 2048.43  3934.7 2047.00  3939.9 2049.38
  3975.9 2047.53  4475.0 2047.26  4552.2 2049.22  4690.4 2048.00  4742.0 2050.11
  4845.6 2041.20  4908.7 2039.95  4937.9 2036.94  4958.5 2041.09  4969.1 2039.44
  4970.0 2033.70  4971.5 2033.20  4988.1 2033.70  4999.7 2039.55  5040.1 2042.62
  5087.4 2048.26  5113.1 2048.99  6197.3 2044.26  6779.3 2047.62  7102.2 2052.51
#Mann=5,-1,0
  2642.6    0.05       0  4908.7     0.1       0  4970.0    0.07       0
  4988.1     0.1       0  5040.1    0.05       0
Bank Sta=4970,4988.1
Exp/Cntr=0.3,0.1

Type RM Length L Ch R = 1,15985,1151,1151,1151
BEGIN DESCRIPTION:
Buffalo Creek 14.2
END DESCRIPTION:
XS GIS Cut Line= 4
      1328617.28      6959687.25      1330449.64      6960419.05
      1330694.00      6960522.43      1333396.51      6960187.54
#Sta/Elev= 30
  3046.7 2066.00  3144.8 2065.55  3193.3 2062.83  3228.3 2064.33  3367.3 2058.66
  3582.7 2057.30  3884.2 2050.28  3928.8 2051.38  3982.7 2048.35  4121.1 2046.81
  4271.0 2041.93  4839.4 2045.74  4874.8 2041.60  4917.5 2042.00  4947.2 2037.58
  4982.5 2038.16  5001.1 2034.77  5005.6 2030.94  5007.1 2030.44  5023.7 2030.94
  5025.1 2035.81  5030.5 2038.52  5101.6 2039.69  5130.7 2045.21  5177.6 2047.68
  6176.4 2044.98  6338.4 2040.08  6515.5 2045.13  7390.9 2044.59  8008.3 2048.35
#Mann=3,-1,0
  3046.7    0.05       0  5005.6    0.05       0  5023.7    0.05       0
Bank Sta=5005.6,5023.7
Exp/Cntr=0.3,0.1

Type RM Length L Ch R = 1,14834,1430,1430,1430
BEGIN DESCRIPTION:
Buffalo Creek 14.0
END DESCRIPTION:
XS GIS Cut Line= 5
      1328730.01      6960663.00      1330371.08      6961280.96
      1330555.00      6961238.00      1330787.75      6961155.96
      1333318.40      6960343.79
#Sta/Elev= 30
  3057.3 2064.53  3778.6 2058.82  3825.1 2060.10  4050.8 2054.91  4281.8 2053.09
  4376.9 2054.33  4398.3 2057.27  4447.1 2048.92  4515.9 2045.30  4547.9 2048.30
  4587.5 2043.79  4678.1 2038.20  4758.1 2042.43  4890.9 2043.12  4981.0 2035.33
  4988.1 2028.74  4989.6 2028.24  5006.2 2028.74  5015.2 2033.39  5031.5 2035.83
  5190.3 2037.34  5306.6 2042.80  5464.2 2044.53  5600.7 2042.79  6274.4 2043.61
  6429.7 2038.90  6499.2 2039.42  6577.4 2043.26  6913.5 2042.09  7904.3 2047.29
#Mann=3,-1,0
  3057.3    0.05       0  4988.1    0.05       0  5006.2    0.05       0
Bank Sta=4988.1,5006.2
Exp/Cntr=0.3,0.1

Type RM Length L Ch R = 1,13404,1067,1067,1067
BEGIN DESCRIPTION:
Buffalo Creek 13.0
END DESCRIPTION:
XS GIS Cut Line= 5
      1328985.41      6961666.44      1329702.91      6961933.83
      1330518.61      6962120.42      1330690.14      6961904.26
      1333726.41      6960673.64
#Sta/Elev= 30
  4234.3 2054.06  4392.4 2053.95  4428.1 2055.84  4544.1 2054.75  4746.1 2044.69
  4906.2 2039.65  4959.5 2034.25  4966.9 2032.46  4980.9 2025.55  4991.6 2028.65
  4997.3 2033.93  5012.4 2035.10  5166.3 2033.09  5186.8 2028.81  5260.6 2023.12
  5262.1 2022.62  5278.7 2023.12  5320.2 2025.28  5355.5 2023.29  5403.6 2027.74
  5441.4 2036.43  5648.4 2040.11  5842.6 2039.47  6366.1 2043.40  6883.4 2040.38
  7833.6 2040.60  7984.8 2037.03  8408.2 2041.34  8437.8 2042.95  9388.9 2049.92
#Mann=3,-1,0
  4234.3    0.05       0  5260.6    0.05       0  5278.7    0.05       0
Bank Sta=5260.6,5278.7
Exp/Cntr=0.3,0.1

Type RM Length L Ch R = 1,12337,994,994,994
BEGIN DESCRIPTION:
Mapping XS e2af7d8c
END DESCRIPTION:
XS GIS Cut Line= 5
      1328832.59      6961951.15      1329818.70      6962666.43
      1330325.65      6962478.93      1330673.14      6962040.14
      1333751.19      6960804.35
#Sta/Elev= 30
  3061.7 2048.59  3067.9 2047.26  3097.2 2048.47  3262.3 2046.40  3354.7 2041.21
  3656.2 2039.16  3683.3 2037.39  3712.6 2039.07  3878.1 2037.38  4297.3 2037.26
  4321.3 2035.52  4407.2 2034.76  4510.5 2037.60  4827.7 2039.17  4906.2 2030.27
  4976.7 2030.41  4982.1 2024.45  4983.6 2023.95  5000.2 2024.45  5012.9 2031.11
  5069.7 2032.80  5104.9 2038.28  5204.3 2039.88  5705.4 2042.86  6014.6 2040.37
  6567.5 2041.39  7144.0 2040.07  7299.9 2036.74  7442.4 2040.48  8697.0 2050.48
#Mann=3,-1,0
  3061.7    0.05       0  4982.1   0.033       0  5000.2    0.05       0
Bank Sta=4982.1,5000.2
Exp/Cntr=0.3,0.1

Type RM Length L Ch R = 1,11343,574,574,574
BEGIN DESCRIPTION:
Buffalo Creek 12.0
END DESCRIPTION:
XS GIS Cut Line= 5
      1328299.57      6962293.15      1329517.70      6962959.18
      1331205.00      6962788.00      1331365.88      6962765.33
      1332919.06      6962661.50
#Sta/Elev= 30
  1915.2 2040.65  2604.8 2039.29  2770.0 2040.13  2813.6 2038.21  3020.4 2039.10
  3092.0 2037.52  3833.5 2037.73  4135.1 2033.21  4205.4 2035.73  4677.8 2037.95
  4847.3 2029.02  4888.9 2030.75  4952.1 2028.65  4979.4 2027.04  4987.9 2021.90
  4989.4 2021.40  5006.0 2021.90  5009.6 2026.21  5019.7 2027.49  5029.8 2025.58
  5035.1 2028.38  5040.1 2026.91  5159.0 2037.77  5797.0 2038.28  6033.0 2034.62
  6063.1 2030.54  6073.1 2033.27  6203.4 2037.25  6323.7 2035.78  6718.6 2042.78
#Mann=5,-1,0
  1915.2    0.05       0  2604.8    0.05       0  3092.0    0.05       0
  4987.9    0.05       0  5006.0    0.05       0
Bank Sta=4987.9,5006
Exp/Cntr=0.3,0.1

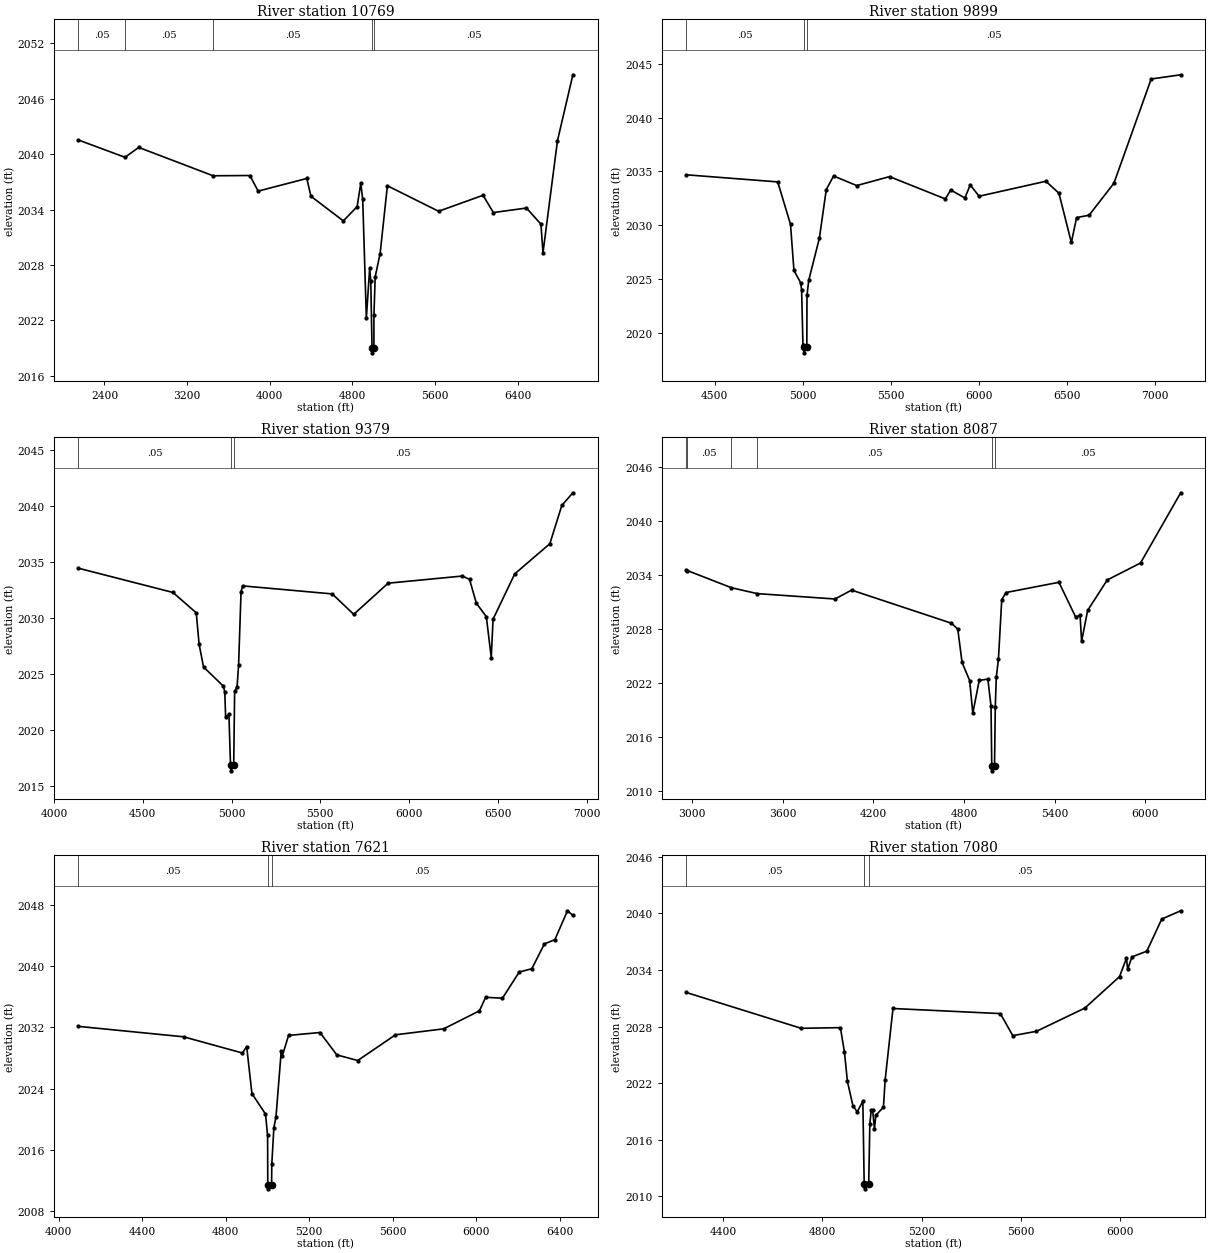
Type RM Length L Ch R = 1,10769,870,870,870
BEGIN DESCRIPTION:
Mapping XS 79cce6ec
END DESCRIPTION:
XS GIS Cut Line= 5
      1328235.41      6962333.12      1329568.70      6963090.04
      1330443.70      6963027.54      1331332.59      6963374.76
      1332754.13      6963312.54
#Sta/Elev= 30
  2148.0 2041.52  2599.1 2039.65  2731.7 2040.72  3452.0 2037.65  3807.8 2037.68
  3888.0 2035.99  4359.2 2037.36  4399.3 2035.43  4713.1 2032.77  4846.3 2034.31
  4881.9 2036.84  4900.6 2035.09  4935.8 2022.25  4967.8 2027.63  4978.5 2026.28
  4990.9 2018.99  4992.4 2018.49  5009.0 2018.99  5009.2 2022.54  5021.4 2026.72
  5068.9 2029.22  5139.5 2036.57  5635.2 2033.81  6065.6 2035.54  6165.7 2033.67
  6486.0 2034.16  6626.2 2032.42  6646.2 2029.33  6786.3 2041.44  6935.6 2048.58
#Mann=5,-1,0
  2148.0    0.05       0  2599.1    0.05       0  3452.0    0.05       0
  4990.9    0.05       0  5009.0    0.05       0
Bank Sta=4990.9,5009
Exp/Cntr=0.3,0.1

Type RM Length L Ch R = 1,9899,520,520,520
BEGIN DESCRIPTION:
Buffalo Creek 11.0
END DESCRIPTION:
XS GIS Cut Line= 4
      1329879.97      6963662.99      1330345.04      6963838.25
      1330505.00      6963788.00      1332631.33      6963547.06
#Sta/Elev= 30
  4339.3 2034.69  4858.1 2034.03  4930.6 2030.09  4950.1 2025.82  4987.8 2024.68
  4993.5 2024.04  5001.3 2018.87  5005.0 2018.67  5006.4 2018.17  5023.1 2018.67
  5024.1 2023.52  5034.2 2024.91  5094.5 2028.82  5133.5 2033.32  5175.0 2034.58
  5305.9 2033.69  5492.3 2034.52  5809.1 2032.45  5839.3 2033.28  5919.8 2032.54
  5950.0 2033.75  6000.3 2032.70  6379.2 2034.09  6453.2 2032.98  6523.6 2028.41
  6553.5 2030.72  6624.3 2030.94  6765.2 2033.91  6976.5 2043.58  7143.9 2043.97
#Mann=3,-1,0
  4339.3    0.05       0  5005.0    0.05       0  5023.1    0.05       0
Bank Sta=5005,5023.1
Exp/Cntr=0.3,0.1

Type RM Length L Ch R = 1,9379,1292,1292,1292
BEGIN DESCRIPTION:
Buffalo Creek 10.0
END DESCRIPTION:
XS GIS Cut Line= 5
      1329929.97      6964012.98      1330376.43      6964303.27
      1330699.48      6964235.57      1331418.53      6963875.63
      1332516.04      6963657.46
#Sta/Elev= 30
  4137.4 2034.46  4669.7 2032.29  4801.3 2030.47  4817.1 2027.66  4842.2 2025.62
  4954.6 2023.90  4961.7 2023.39  4966.8 2021.14  4985.2 2021.38  4994.1 2016.83
  4995.6 2016.33  5012.2 2016.83  5017.4 2023.44  5031.1 2023.86  5039.7 2025.80
  5053.5 2032.35  5062.1 2032.88  5567.6 2032.16  5688.3 2030.33  5882.1 2033.12
  6300.1 2033.76  6340.9 2033.46  6379.2 2031.33  6435.4 2030.13  6463.2 2026.46
  6473.4 2029.90  6595.8 2033.96  6793.3 2036.65  6860.9 2040.08  6923.1 2041.21
#Mann=3,-1,0
  4137.4    0.05       0  4994.1   0.033       0  5012.2    0.05       0
Bank Sta=4994.1,5012.2
Exp/Cntr=0.3,0.1

Type RM Length L Ch R = 1,8087,466,466,466
BEGIN DESCRIPTION:
Mapping XS 463e01db
END DESCRIPTION:
XS GIS Cut Line= 5
      1329925.44      6964044.87      1330554.81      6964678.58
      1331062.63      6964739.34      1331713.67      6964162.09
      1332710.68      6964165.28
#Sta/Elev= 30
  2961.5 2034.56  2968.2 2034.52  3259.3 2032.61  3430.5 2031.95  3945.5 2031.35
  4055.7 2032.34  4716.2 2028.65  4758.0 2028.00  4786.4 2024.29  4836.6 2022.27
  4857.5 2018.63  4900.2 2022.29  4957.1 2022.42  4978.0 2019.44  4983.1 2012.71
  4984.6 2012.21  5001.3 2012.71  5006.4 2019.36  5013.1 2022.65  5027.3 2024.70
  5049.1 2031.28  5077.5 2032.07  5427.5 2033.21  5537.5 2029.36  5567.5 2029.52
  5577.5 2026.64  5617.5 2030.08  5747.5 2033.47  5967.5 2035.36  6233.2 2043.18
#Mann=6,-1,0
  2961.5    0.05       0  2968.2    0.05       0  3259.3    0.05       0
  3430.5    0.05       0  4983.1    0.05       0  5001.3    0.05       0
Bank Sta=4983.1,5001.3
Exp/Cntr=0.3,0.1

Type RM Length L Ch R = 1,7621,541,541,541
BEGIN DESCRIPTION:
Buffalo Creek 9.5
END DESCRIPTION:
XS GIS Cut Line= 4
      1330553.02      6964714.15      1331135.72      6964770.54
      1331585.24      6964738.34      1332910.79      6964617.89
#Sta/Elev= 30
  4094.8 2032.14  4598.0 2030.78  4880.0 2028.66  4900.1 2029.51  4925.4 2023.36
  4990.3 2020.69  5000.3 2017.92  5001.2 2011.42  5002.7 2010.92  5019.4 2011.42
  5020.4 2014.10  5030.4 2018.92  5040.4 2020.28  5065.6 2028.91  5070.6 2028.26
  5100.6 2030.96  5251.1 2031.34  5331.5 2028.42  5431.9 2027.68  5612.6 2031.04
  5843.6 2031.82  6014.3 2034.17  6044.4 2035.94  6124.7 2035.82  6205.1 2039.24
  6265.3 2039.67  6325.6 2042.91  6375.8 2043.47  6436.0 2047.24  6461.9 2046.65
#Mann=3,-1,0
  4094.8    0.05       0  5001.2    0.05       0  5019.4    0.05       0
Bank Sta=5001.2,5019.4
Exp/Cntr=0.3,0.1

Type RM Length L Ch R = 1,7080,707,707,707
BEGIN DESCRIPTION:
Buffalo Creek 9.0
END DESCRIPTION:
XS GIS Cut Line= 4
      1330630.02      6964913.01      1331305.00      6965238.00
      1331430.00      6965282.03      1332541.37      6965221.19
#Sta/Elev= 30
  4250.6 2031.61  4714.2 2027.81  4872.5 2027.88  4888.8 2025.27  4900.7 2022.18
  4923.3 2019.56  4940.4 2018.95  4963.0 2020.08  4968.4 2011.29  4969.9 2010.79
  4986.6 2011.29  4991.2 2017.68  4997.0 2019.16  5002.4 2019.16  5009.9 2017.16
  5015.2 2018.58  5046.2 2019.45  5052.8 2022.30  5084.6 2029.91  5517.8 2029.37
  5567.9 2027.03  5663.2 2027.49  5858.4 2029.95  5998.6 2033.29  6026.4 2035.23
  6031.4 2034.08  6048.6 2035.38  6108.7 2035.99  6168.8 2039.39  6245.3 2040.27
#Mann=3,-1,0
  4250.6    0.05       0  4968.4    0.05       0  4986.6    0.05       0
Bank Sta=4968.4,4986.6
Exp/Cntr=0.3,0.1

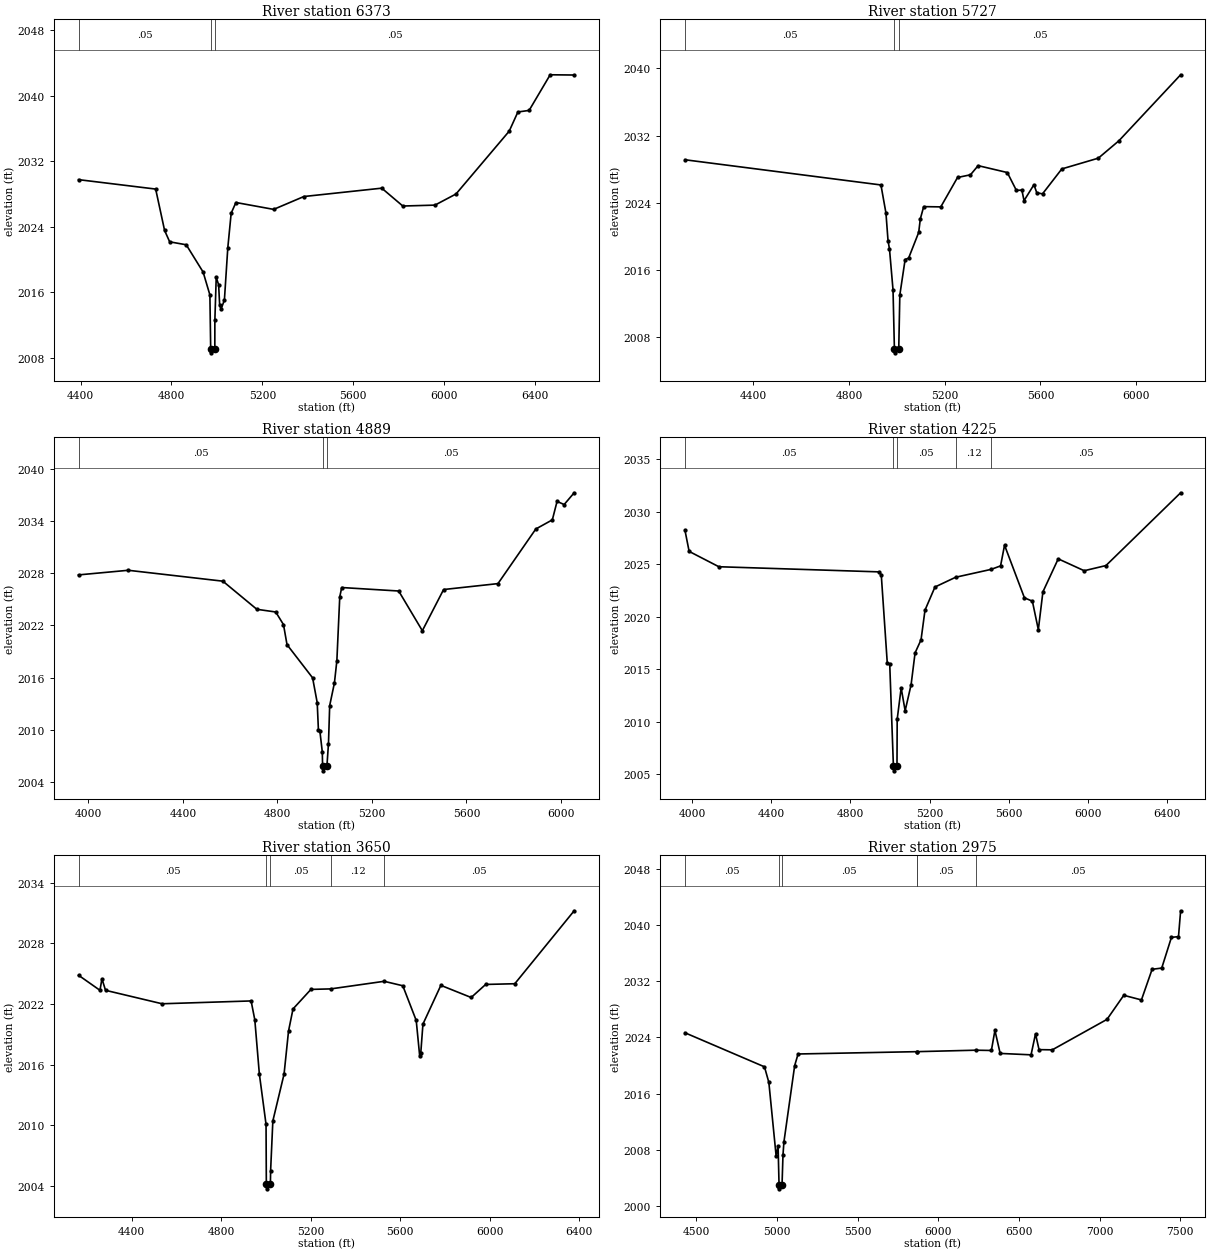
Type RM Length L Ch R = 1,6373,646,646,646
BEGIN DESCRIPTION:
Buffalo Creek 8.0
END DESCRIPTION:
XS GIS Cut Line= 6
      1330494.21      6965256.56      1330499.76      6965522.77
      1330701.08      6965622.27      1330805.00      6965688.00
      1330909.97      6965760.31      1332316.95      6965451.15
#Sta/Elev= 30
  4390.9 2029.74  4730.5 2028.59  4769.8 2023.54  4792.2 2022.15  4865.1 2021.79
  4939.4 2018.46  4969.2 2015.67  4972.7 2009.10  4974.2 2008.60  4990.9 2009.10
  4991.1 2012.57  4997.1 2017.81  5007.7 2016.91  5012.1 2014.49  5018.2 2013.93
  5033.1 2015.04  5048.0 2021.41  5062.9 2025.65  5083.8 2026.95  5249.9 2026.11
  5383.0 2027.68  5725.7 2028.70  5818.4 2026.52  5959.9 2026.63  6052.6 2027.99
  6286.8 2035.66  6325.0 2038.00  6374.4 2038.19  6467.1 2042.54  6572.7 2042.51
#Mann=3,-1,0
  4390.9    0.05       0  4972.7    0.05       0  4990.9    0.05       0
Bank Sta=4972.7,4990.9
Exp/Cntr=0.3,0.1

Type RM Length L Ch R = 1,5727,838,838,838
BEGIN DESCRIPTION:
Buffalo Creek 7.5
END DESCRIPTION:
XS GIS Cut Line= 4
      1330480.01      6965963.01      1330980.00      6966313.00
      1331266.98      6965904.60      1332168.94      6965572.84
#Sta/Elev= 30
  4114.9 2029.12  4933.5 2026.12  4954.4 2022.78  4963.1 2019.49  4969.2 2018.49
  4984.0 2013.62  4989.7 2006.63  4991.2 2006.13  5007.9 2006.63  5012.4 2013.02
  5034.5 2017.24  5049.1 2017.41  5091.2 2020.47  5098.0 2022.08  5112.1 2023.54
  5183.5 2023.51  5253.4 2027.01  5307.5 2027.33  5339.5 2028.42  5461.4 2027.60
  5499.3 2025.47  5522.3 2025.51  5531.2 2024.25  5572.6 2026.15  5584.5 2025.19
  5608.4 2025.06  5689.1 2028.03  5841.5 2029.31  5927.5 2031.38  6185.4 2039.24
#Mann=3,-1,0
  4114.9    0.05       0  4989.7    0.05       0  5007.9    0.05       0
Bank Sta=4989.7,5007.9
Exp/Cntr=0.3,0.1

Type RM Length L Ch R = 1,4889,664,664,664
BEGIN DESCRIPTION:
Buffalo Creek 7.0
END DESCRIPTION:
XS GIS Cut Line= 3
      1330279.98      6966363.00      1331406.02      6966625.16
      1332347.35      6966596.98
#Sta/Elev= 30
  3958.1 2027.80  4168.6 2028.33  4569.0 2027.08  4712.9 2023.85  4792.9 2023.54
  4825.7 2022.09  4840.6 2019.79  4948.9 2015.98  4968.4 2013.13  4973.5 2010.01
  4979.7 2009.87  4990.0 2007.46  4991.2 2005.80  4992.7 2005.30  5009.4 2005.80
  5016.1 2008.43  5021.2 2012.79  5041.3 2015.40  5051.6 2017.95  5063.8 2025.27
  5072.1 2026.35  5313.3 2025.95  5413.4 2021.39  5503.4 2026.12  5733.5 2026.80
  5893.6 2033.07  5963.6 2034.12  5983.6 2036.24  6013.6 2035.88  6056.0 2037.23
#Mann=3,-1,0
  3958.1    0.05       0  4991.2    0.05       0  5009.4    0.05       0
Bank Sta=4991.2,5009.4
Exp/Cntr=0.3,0.1

Type RM Length L Ch R = 1,4225,575,575,575
BEGIN DESCRIPTION:
Buffalo Creek 6.0
END DESCRIPTION:
XS GIS Cut Line= 3
      1329823.99      6967038.77      1330855.00      6967088.00
      1332320.70      6967230.61
#Sta/Elev= 30
  3963.8 2028.23  3984.8 2026.23  4135.0 2024.77  4945.9 2024.28  4955.9 2023.96
  4986.0 2015.63  4998.5 2015.52  5017.0 2005.84  5018.5 2005.34  5035.2 2005.84
  5036.2 2010.25  5056.3 2013.23  5076.4 2011.06  5106.5 2013.54  5126.6 2016.57
  5156.7 2017.81  5176.8 2020.64  5227.1 2022.84  5331.8 2023.77  5511.3 2024.52
  5558.6 2024.85  5578.7 2026.82  5679.2 2021.81  5719.4 2021.49  5749.5 2018.78
  5772.6 2022.38  5850.0 2025.52  5981.3 2024.39  6091.1 2024.88  6468.6 2031.81
#Mann=5,-1,0
  3963.8    0.05       0  5017.0    0.05       0  5035.2    0.05       0
  5331.8    0.12       0  5511.3    0.05       0
Bank Sta=5017,5035.2
Exp/Cntr=0.3,0.1

Type RM Length L Ch R = 1,3650,675,675,675
BEGIN DESCRIPTION:
Buffalo Creek 5.0
END DESCRIPTION:
XS GIS Cut Line= 4
      1330039.58      6967412.36      1330129.16      6967466.54
      1330854.62      6967572.87      1332230.02      6967513.00
#Sta/Elev= 30
  4162.1 2024.84  4258.0 2023.35  4266.8 2024.49  4282.8 2023.35  4535.5 2022.02
  4933.3 2022.30  4949.8 2020.43  4970.1 2015.08  5000.0 2010.10  5001.3 2004.23
  5002.8 2003.73  5019.5 2004.23  5020.4 2005.52  5030.4 2010.44  5080.5 2015.07
  5100.5 2019.33  5120.5 2021.51  5200.6 2023.44  5289.1 2023.49  5527.6 2024.24
  5611.0 2023.80  5671.0 2020.37  5686.5 2016.86  5691.5 2017.20  5701.0 2020.01
  5781.1 2023.84  5916.5 2022.64  5981.3 2023.93  6111.4 2024.00  6376.7 2031.21
#Mann=5,-1,0
  4162.1    0.05       0  5001.3    0.05       0  5019.5    0.05       0
  5289.1    0.12       0  5527.6    0.05       0
Bank Sta=5001.3,5019.5
Exp/Cntr=0.3,0.1

Type RM Length L Ch R = 1,2975,1058,1058,1058
BEGIN DESCRIPTION:
Mapping XS 17cbe847
END DESCRIPTION:
XS GIS Cut Line= 5
      1330090.43      6967812.28      1330975.82      6968385.18
      1331179.81      6968602.19      1331279.64      6968558.79
      1332700.98      6967796.34
#Sta/Elev= 30
  4428.6 2024.65  4921.7 2019.80  4948.8 2017.58  4993.9 2007.12  5006.1 2008.53
  5012.1 2002.92  5013.6 2002.42  5030.5 2002.92  5036.5 2007.27  5042.4 2009.12
  5109.0 2019.98  5130.1 2021.63  5864.9 2021.96  5865.0 2021.96  6232.0 2022.17
  6329.0 2022.13  6351.0 2024.99  6383.5 2021.71  6575.1 2021.51  6602.7 2024.50
  6624.6 2022.25  6706.7 2022.22  7046.1 2026.56  7150.1 2029.99  7259.7 2029.33
  7325.8 2033.69  7385.6 2033.87  7445.7 2038.24  7489.5 2038.35  7502.8 2042.03
#Mann=6,-1,0
  4428.6    0.05       0  5012.1    0.05       0  5030.5    0.05       0
  5864.9    0.05       0  5865.0    0.05       0  6232.0    0.05       0
Bank Sta=5012.1,5030.5
Exp/Cntr=0.3,0.1

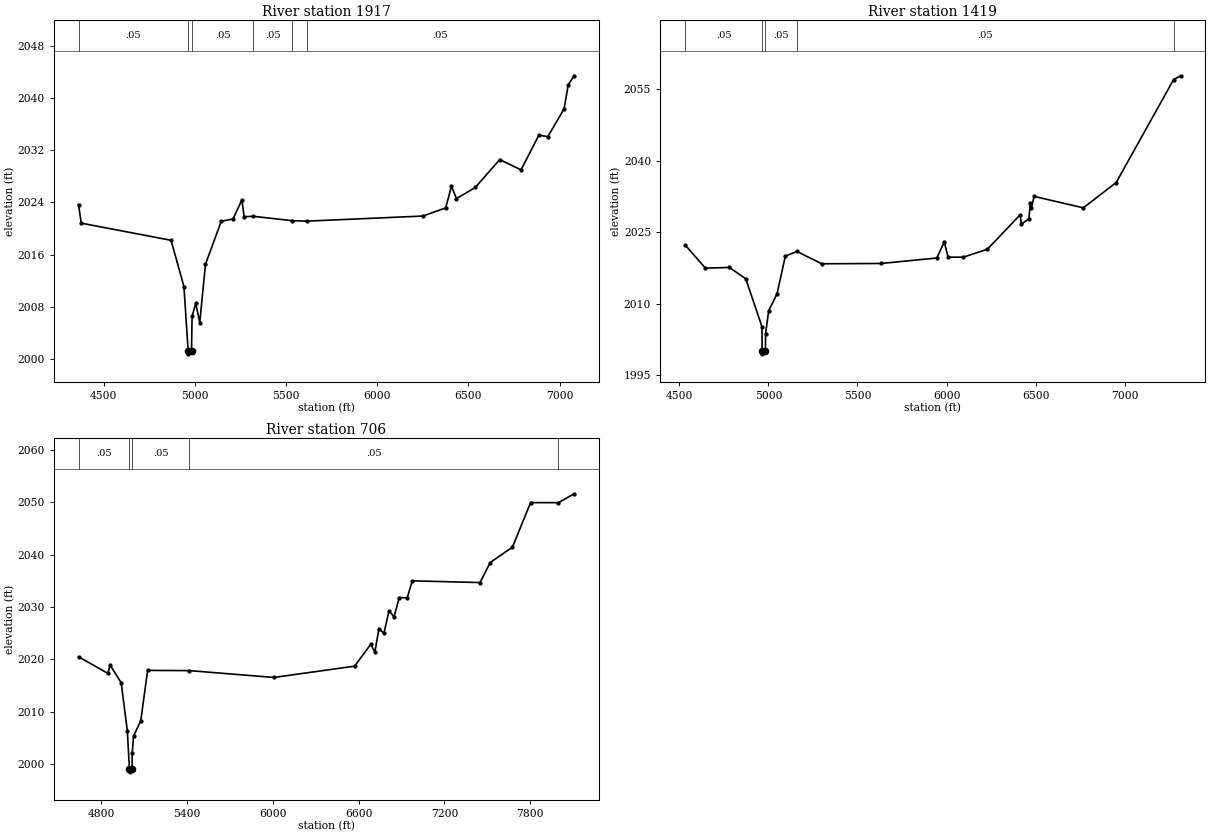
Type RM Length L Ch R = 1,1917,498,498,498
BEGIN DESCRIPTION:
Buffalo Creek 3.0
END DESCRIPTION:
XS GIS Cut Line= 4
      1330335.05      6968606.56      1330724.08      6968840.91
      1331130.00      6968713.00      1332743.09      6967832.31
#Sta/Elev= 30
  4361.9 2023.67  4376.9 2020.83  4869.4 2018.21  4939.9 2011.13  4963.1 2001.33
  4964.5 2000.83  4981.5 2001.33  4984.8 2006.57  5004.6 2008.57  5026.7 2005.62
  5058.2 2014.55  5144.6 2021.11  5209.3 2021.48  5257.8 2024.40  5270.1 2021.82
  5320.1 2021.88  5535.2 2021.21  5612.8 2021.14  6250.0 2021.92  6375.3 2023.17
  6407.0 2026.48  6434.5 2024.60  6538.0 2026.30  6671.5 2030.56  6788.5 2028.99
  6886.3 2034.30  6935.6 2034.08  7024.7 2038.34  7047.5 2042.02  7079.5 2043.39
#Mann=6,-1,0
  4361.9    0.05       0  4963.1    0.05       0  4981.5    0.05       0
  5320.1    0.05       0  5535.2    0.05       0  5612.8    0.05       0
Bank Sta=4963.1,4981.5
Exp/Cntr=0.3,0.1

Type RM Length L Ch R = 1,1419,713,713,713
BEGIN DESCRIPTION:
Buffalo Creek 2.0
END DESCRIPTION:
XS GIS Cut Line= 5
      1330694.15      6969138.89      1330980.46      6969213.25
      1331155.00      6969188.00      1331339.83      6969166.37
      1332954.98      6967788.02
#Sta/Elev= 30
  4532.1 2022.33  4646.6 2017.44  4780.9 2017.59  4872.9 2015.21  4963.8 2005.15
  4965.0 1999.94  4966.4 1999.44  4983.4 1999.94  4984.1 2003.69  5001.7 2008.49
  5048.4 2012.04  5094.9 2019.95  5159.7 2020.95  5299.6 2018.36  5632.2 2018.42
  5945.2 2019.57  5986.9 2022.93  6008.8 2019.74  6093.4 2019.75  6228.4 2021.39
  6412.9 2028.64  6419.8 2026.69  6462.3 2027.79  6470.0 2031.21  6476.5 2030.03
  6490.8 2032.52  6767.5 2030.11  6952.0 2035.43  7274.4 2057.06  7313.7 2057.85
#Mann=5,-1,0
  4532.1    0.05       0  4965.0    0.05       0  4983.4    0.05       0
  5159.7    0.05       0  7274.4    0.05       0
Bank Sta=4965,4983.4
Exp/Cntr=0.3,0.1

Type RM Length L Ch R = 1,706,0,0,0
BEGIN DESCRIPTION:
Buffalo Creek 1.0
END DESCRIPTION:
XS GIS Cut Line= 4
      1330729.98      6969562.97      1330955.00      6969838.00
      1331136.71      6969859.08      1333279.99      6967863.01
#Sta/Elev= 30
  4640.2 2020.46  4846.3 2017.29  4860.6 2018.91  4938.8 2015.49  4981.9 2006.27
  4996.4 1998.97  4997.8 1998.47  5014.8 1998.97  5015.7 2002.00  5025.8 2005.36
  5076.1 2008.28  5123.6 2017.86  5416.1 2017.82  6006.0 2016.51  6571.7 2018.67
  6685.1 2022.87  6713.4 2021.33  6741.8 2025.82  6776.9 2024.94  6812.6 2029.27
  6847.8 2028.07  6883.5 2031.78  6939.6 2031.72  6975.3 2034.98  7449.2 2034.65
  7520.1 2038.47  7675.9 2041.42  7802.9 2049.93  7997.8 2049.92  8107.3 2051.62
#Mann=5,-1,0
  4640.2    0.05       0  4996.4    0.05       0  5014.8    0.05       0
  5416.1    0.05       0  7997.8    0.05       0
Bank Sta=4996.4,5014.8
Exp/Cntr=0.3,0.1

Chan Stop Cuts=-1