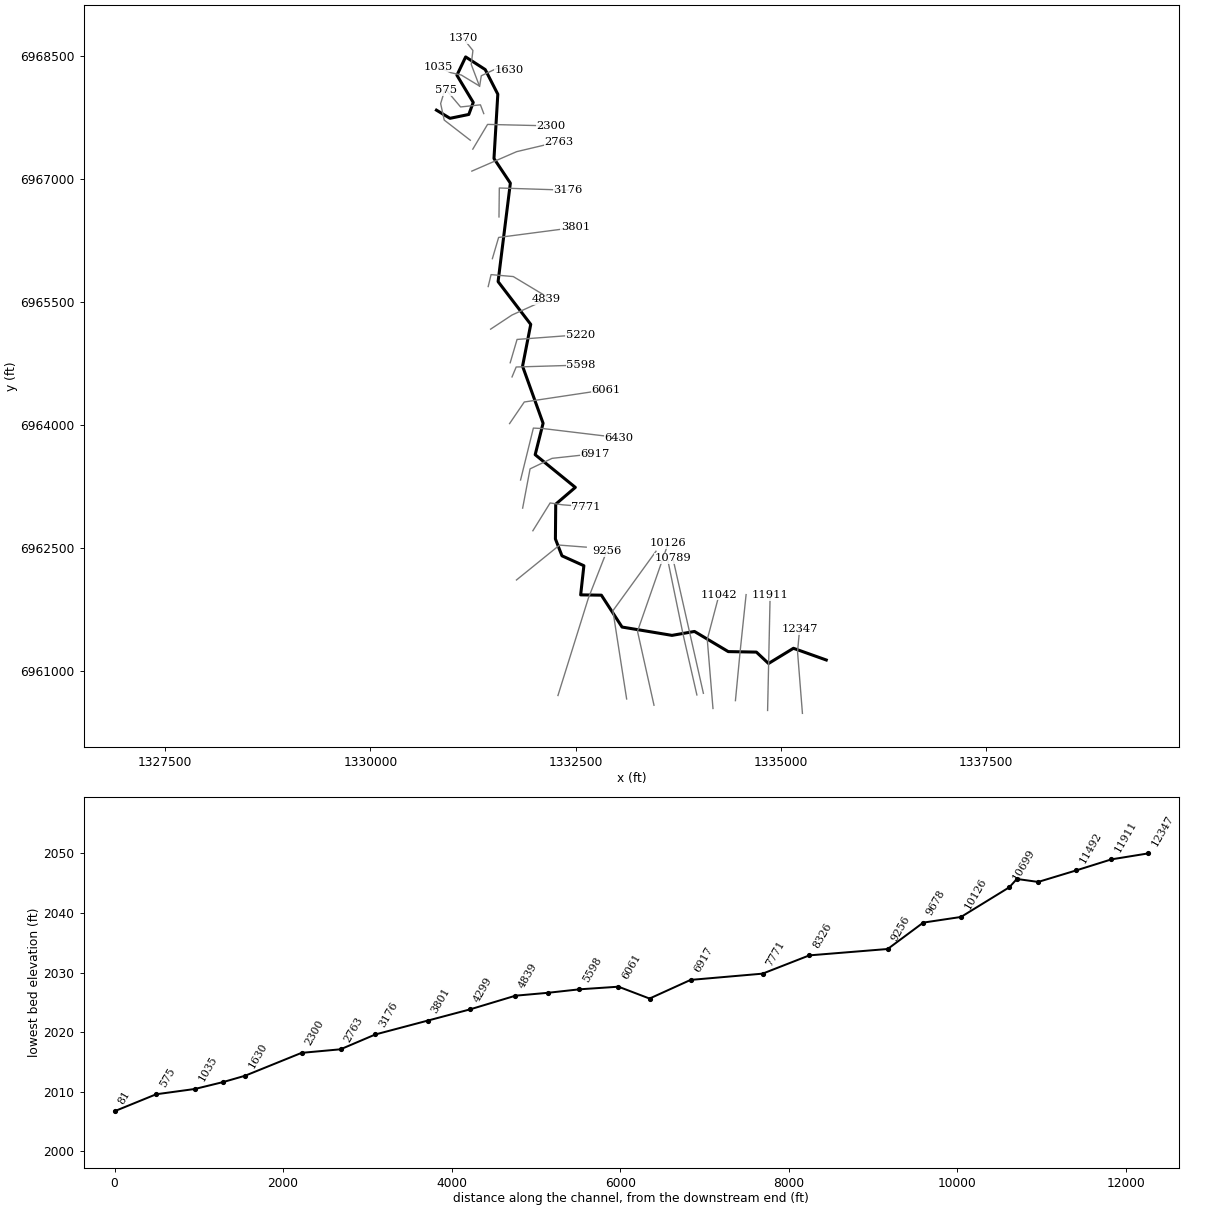
--- Buffalo Creek Trib 01.prj (project) ---

Proj Title=Buffalo Creek Trib 01 Base Level Engineering
Current Plan=p01
Default Exp/Contr=0.3,0.1
English Units
Geom File=g01
Flow File=f01
Plan File=p01
Y Axis Title=Elevation
X Axis Title(PF)=Main Channel Distance
X Axis Title(XS)=Station
BEGIN DESCRIPTION:
Buffalo Creek Trib 01
END DESCRIPTION:
DSS Export Rating Curves= 0
DSS Export Rating Curve Sorted= 0
DSS Export Volume Flow Curves= 0
DXF OffsetX= 0
DXF OffsetY= 0
DXF ScaleX= 1
DXF ScaleY= 10

--- Buffalo Creek Trib 01.p01 (plan) ---

Plan Title=Multiple Run
Short Identifier=Multiple
Geom File=g01
Flow File=f01
Subcritical Flow
K Sum by GR= 0
Std Step Tol= 0.01
Critical Tol= 0.01
Num of Std Step Trials= 20
Max Error Tol= 0.3
Flow Tol Ratio= 0.001
Split Flow NTrial= 30
Split Flow Tol= 0.02
Split Flow Ratio= 0.02
Log Output Level= 0
Friction Slope Method= 1
Unsteady Friction Slope Method= 2
Unsteady Bridges Friction Slope Method= 1
Parabolic Critical Depth
Global Vel Dist=  1 , 1 , 1
Global Log Level= 0
CheckData=True
Encroach Param= -1, 0, 0, 0
BEGIN DESCRIPTION:
Multiple Run
END DESCRIPTION:

--- Buffalo Creek Trib 01.f01 (steady flow) ---

Flow Title=Multiple
Number of Profiles=7
Profile Names=10-year,25-year,50-year,1pct_min,100-year,1pct_plu,500-year
River Rch & RM= Buffalo Creek Tr,Reach-1,12347
     446     650     826     522    1041    2077    1675
River Rch & RM= Buffalo Creek Tr,Reach-1,6917
     470     682     864     544    1085    2164    1733
Boundary for River Rch & Prof#=Buffalo Creek Tr,Reach-1,1
Up Type=0
Dn Type=3
Dn Slope=0.005
Boundary for River Rch & Prof#=Buffalo Creek Tr,Reach-1,2
Up Type=0
Dn Type=3
Dn Slope=0.005
Boundary for River Rch & Prof#=Buffalo Creek Tr,Reach-1,3
Up Type=0
Dn Type=3
Dn Slope=0.005
Boundary for River Rch & Prof#=Buffalo Creek Tr,Reach-1,4
Up Type=0
Dn Type=3
Dn Slope=0.005
Boundary for River Rch & Prof#=Buffalo Creek Tr,Reach-1,5
Up Type=0
Dn Type=3
Dn Slope=0.005
Boundary for River Rch & Prof#=Buffalo Creek Tr,Reach-1,6
Up Type=0
Dn Type=3
Dn Slope=0.005
Boundary for River Rch & Prof#=Buffalo Creek Tr,Reach-1,7
Up Type=0
Dn Type=3
Dn Slope=0.005

--- Buffalo Creek Trib 01.g01 (geometry) ---

Geom Title=Existing Conditions

River Reach=Buffalo Creek Tr,Reach-1
Reach XY= 30
      1335555.00      6961138.00      1335154.92      6961280.70
      1334851.43      6961095.53      1334703.48      6961234.26
      1334360.93      6961240.24      1333949.03      6961485.86
      1333675.04      6961438.05      1333066.54      6961539.52
      1332814.71      6961927.82      1332562.35      6961931.61
      1332601.56      6962286.78      1332334.43      6962407.58
      1332254.60      6962613.00      1332258.45      6963036.52
      1332497.42      6963241.32      1332008.12      6963639.63
      1332104.48      6964022.78      1331854.40      6964717.95
      1331953.95      6965227.57      1331556.20      6965748.50
      1331705.55      6966948.54      1331506.05      6967248.44
      1331552.76      6968032.07      1331399.41      6968332.39
      1331160.87      6968486.50      1331054.51      6968262.96
      1331253.38      6967931.96      1331199.29      6967785.42
      1330970.16      6967738.38      1330805.00      6967838.00

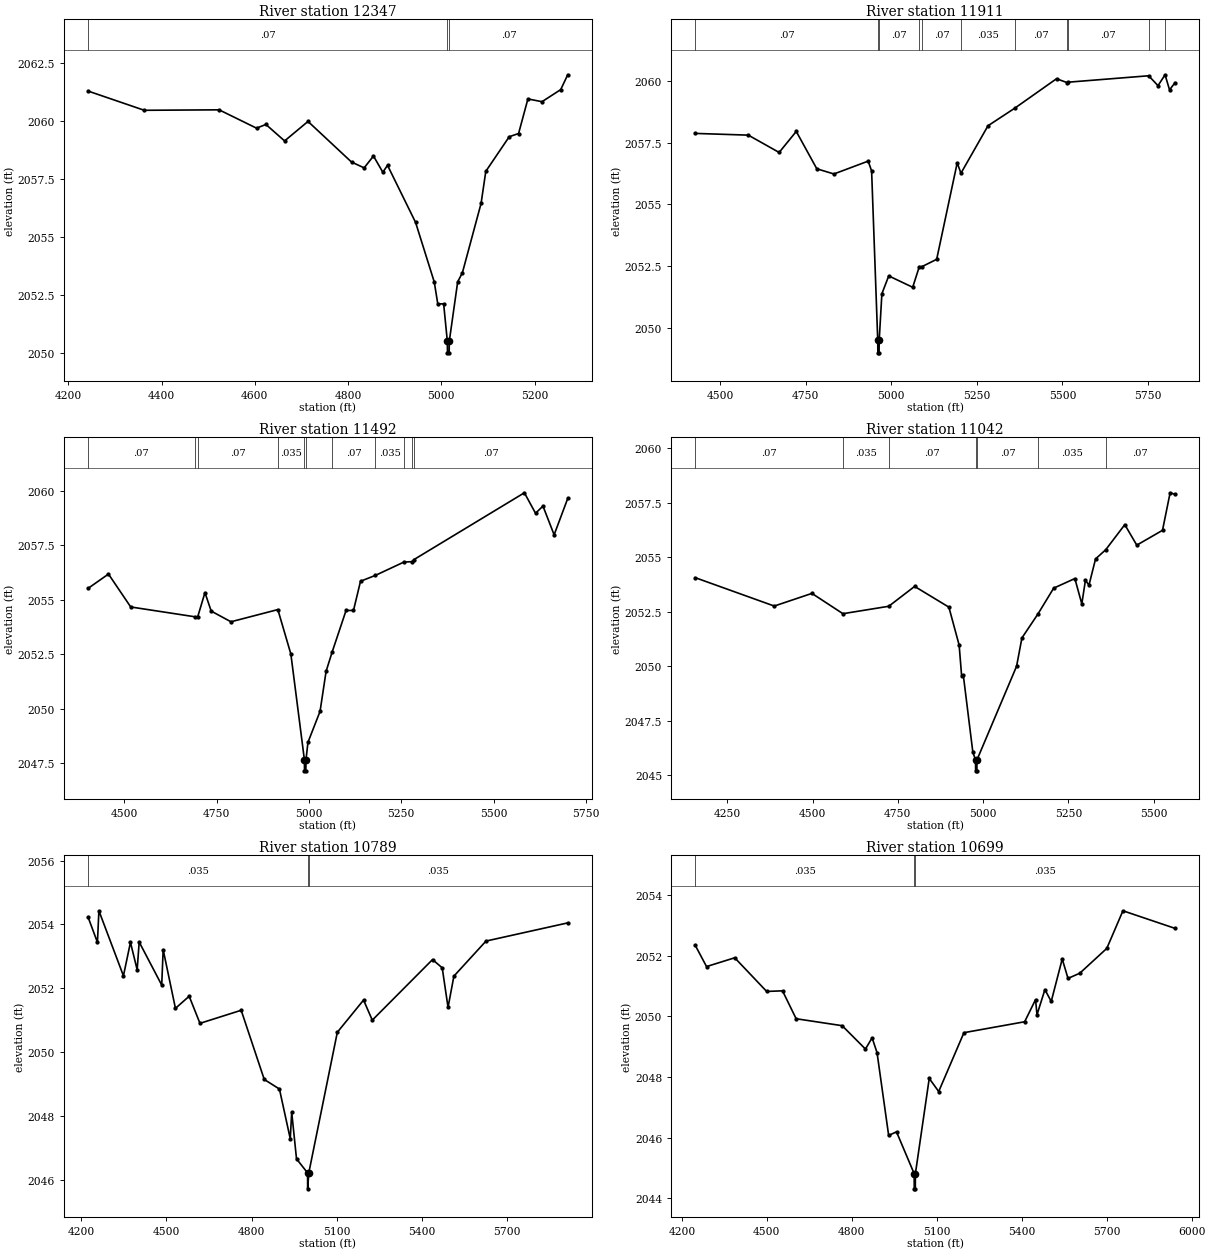
Type RM Length L Ch R = 1,12347,436,436,436
BEGIN DESCRIPTION:
Buffalo Creek Trib 01 8.0
END DESCRIPTION:
XS GIS Cut Line= 3
      1335264.56      6960487.60      1335205.00      6961238.00
      1335230.00      6961513.01
#Sta/Elev= 30
  4242.2 2061.28  4363.0 2060.45  4523.5 2060.47  4603.7 2059.68  4623.8 2059.84
  4663.9 2059.13  4714.1 2059.97  4807.4 2058.22  4834.5 2057.97  4854.5 2058.48
  4874.6 2057.78  4884.6 2058.08  4944.8 2055.62  4984.9 2053.05  4992.4 2052.11
  5005.0 2052.11  5012.9 2050.50  5013.2 2050.00  5016.8 2050.00  5017.1 2050.50
  5035.1 2053.06  5045.2 2053.45  5085.3 2056.44  5095.4 2057.82  5145.6 2059.31
  5165.7 2059.45  5185.7 2060.94  5215.9 2060.82  5256.0 2061.34  5271.1 2061.98
#Mann=3,-1,0
  4242.2    0.07       0  5012.9    0.07       0  5017.1    0.07       0
Bank Sta=5012.9,5017.1
Exp/Cntr=0.3,0.1

Type RM Length L Ch R = 1,11911,419,419,419
BEGIN DESCRIPTION:
Buffalo Creek Trib 01 7.5
END DESCRIPTION:
XS GIS Cut Line= 2
      1334840.11      6960523.07      1334871.07      6961924.03
#Sta/Elev= 30
  4427.6 2057.87  4582.6 2057.80  4672.6 2057.10  4722.6 2057.95  4782.6 2056.44
  4832.6 2056.23  4932.7 2056.75  4942.7 2056.35  4960.6 2049.50  4960.9 2049.00
  4964.5 2049.00  4964.8 2049.50  4972.7 2051.39  4992.7 2052.11  5062.7 2051.65
  5081.9 2052.48  5090.5 2052.49  5132.7 2052.78  5192.7 2056.68  5203.6 2056.26
  5282.7 2058.18  5360.9 2058.89  5482.8 2060.08  5514.3 2059.92  5516.2 2059.94
  5751.9 2060.20  5779.2 2059.80  5799.8 2060.24  5812.9 2059.63  5828.9 2059.92
#Mann=11,-1,0
  4427.6    0.07       0  4960.6    0.07       0  4964.8    0.07       0
  5081.9   0.035       0  5090.5    0.07       0  5203.6   0.035       0
  5360.9    0.07       0  5514.3   0.035       0  5516.2    0.07       0
  5751.9   0.035       0  5799.8    0.07       0
Bank Sta=4960.6,4964.8
Exp/Cntr=0.3,0.1

Type RM Length L Ch R = 1,11492,450,450,450
BEGIN DESCRIPTION:
Buffalo Creek Trib 01 7.0
END DESCRIPTION:
XS GIS Cut Line= 3
      1334448.08      6960642.79      1334505.00      6961238.00
      1334578.12      6961934.65
#Sta/Elev= 30
  4402.1 2055.51  4457.6 2056.17  4517.8 2054.66  4691.4 2054.21  4698.6 2054.18
  4718.7 2055.32  4735.6 2054.47  4789.1 2053.98  4916.0 2054.54  4951.2 2052.50
  4987.9 2047.64  4988.1 2047.14  4991.8 2047.14  4992.1 2047.64  4997.5 2048.45
  5030.2 2049.87  5046.6 2051.71  5062.9 2052.59  5100.6 2054.50  5120.7 2054.50
  5139.7 2055.84  5180.1 2056.11  5257.1 2056.72  5279.5 2056.74  5283.9 2056.83
  5583.2 2059.90  5613.4 2058.96  5633.5 2059.29  5663.7 2057.97  5700.5 2059.64
#Mann=11,-1,0
  4402.1    0.07       0  4691.4   0.035       0  4698.6    0.07       0
  4916.0   0.035       0  4987.9   0.035       0  4992.1   0.035       0
  5062.9    0.07       0  5180.1   0.035       0  5257.1    0.07       0
  5279.5   0.035       0  5283.9    0.07       0
Bank Sta=4987.9,4992.1
Exp/Cntr=0.3,0.1

Type RM Length L Ch R = 1,11042,253,253,253
BEGIN DESCRIPTION:
Buffalo Creek Trib 01 6.0
END DESCRIPTION:
XS GIS Cut Line= 3
      1334174.64      6960547.28      1334105.00      6961388.00
      1334248.43      6961931.91
#Sta/Elev= 30
  4156.4 2054.06  4387.9 2052.76  4498.3 2053.34  4589.2 2052.41  4723.5 2052.75
  4799.3 2053.66  4899.7 2052.71  4929.8 2050.97  4937.1 2049.55  4942.1 2049.58
  4969.9 2046.07  4977.8 2045.71  4978.1 2045.21  4981.8 2045.21  4982.0 2045.71
  5098.1 2050.00  5113.8 2051.30  5160.9 2052.40  5206.8 2053.58  5268.9 2054.02
  5289.3 2052.86  5299.9 2053.94  5310.3 2053.72  5329.6 2054.92  5359.4 2055.34
  5415.3 2056.49  5450.4 2055.55  5525.8 2056.23  5548.1 2057.95  5562.5 2057.88
#Mann=7,-1,0
  4156.4    0.07       0  4589.2   0.035       0  4723.5    0.07       0
  4977.8    0.07       0  4982.0    0.07       0  5160.9   0.035       0
  5359.4    0.07       0
Bank Sta=4977.8,4982
Exp/Cntr=0.3,0.1

Type RM Length L Ch R = 1,10789,90,90,90
BEGIN DESCRIPTION:
Buffalo Creek Trib 01 5.1
END DESCRIPTION:
XS GIS Cut Line= 2
      1334057.74      6960732.22      1333685.49      6962378.76
#Sta/Elev= 30
  4224.5 2054.24  4257.8 2053.44  4263.0 2054.43  4349.3 2052.39  4374.0 2053.44
  4397.6 2052.58  4404.7 2053.45  4484.0 2052.10  4489.1 2053.21  4532.3 2051.37
  4580.6 2051.75  4618.6 2050.90  4763.6 2051.31  4844.8 2049.14  4898.2 2048.84
  4936.3 2047.28  4941.4 2048.11  4958.3 2046.65  4997.2 2046.21  4997.5 2045.71
  5001.5 2046.21  5101.9 2050.62  5194.2 2051.63  5224.9 2051.00  5436.9 2052.90
  5471.0 2052.64  5491.5 2051.40  5512.0 2052.38  5625.0 2053.48  5912.6 2054.05
#Mann=3,-1,0
  4224.5   0.035       0  4997.2   0.035       0  5001.5   0.035       0
Bank Sta=4997.2,5001.5
Exp/Cntr=0.3,0.1

Type RM Length L Ch R = 1,10699,573,573,573
BEGIN DESCRIPTION:
Buffalo Creek Trib 01 5.0
END DESCRIPTION:
XS GIS Cut Line= 3
      1333978.38      6960712.17      1333811.06      6961446.14
      1333621.24      6962368.11
#Sta/Elev= 30
  4247.2 2052.34  4287.0 2051.64  4386.5 2051.93  4499.3 2050.82  4555.3 2050.84
  4603.4 2049.92  4766.0 2049.69  4848.1 2048.92  4871.7 2049.29  4889.1 2048.80
  4930.1 2046.07  4957.8 2046.19  5020.2 2044.81  5020.5 2044.31  5024.2 2044.31
  5024.5 2044.81  5073.4 2047.95  5106.8 2047.52  5195.9 2049.46  5410.3 2049.82
  5448.8 2050.55  5453.9 2050.05  5481.8 2050.88  5504.2 2050.49  5543.0 2051.89
  5563.4 2051.25  5604.9 2051.42  5700.4 2052.24  5757.4 2053.48  5941.3 2052.90
#Mann=3,-1,0
  4247.2   0.035       0  5020.2   0.035       0  5024.5   0.035       0
Bank Sta=5020.2,5024.5
Exp/Cntr=0.3,0.1

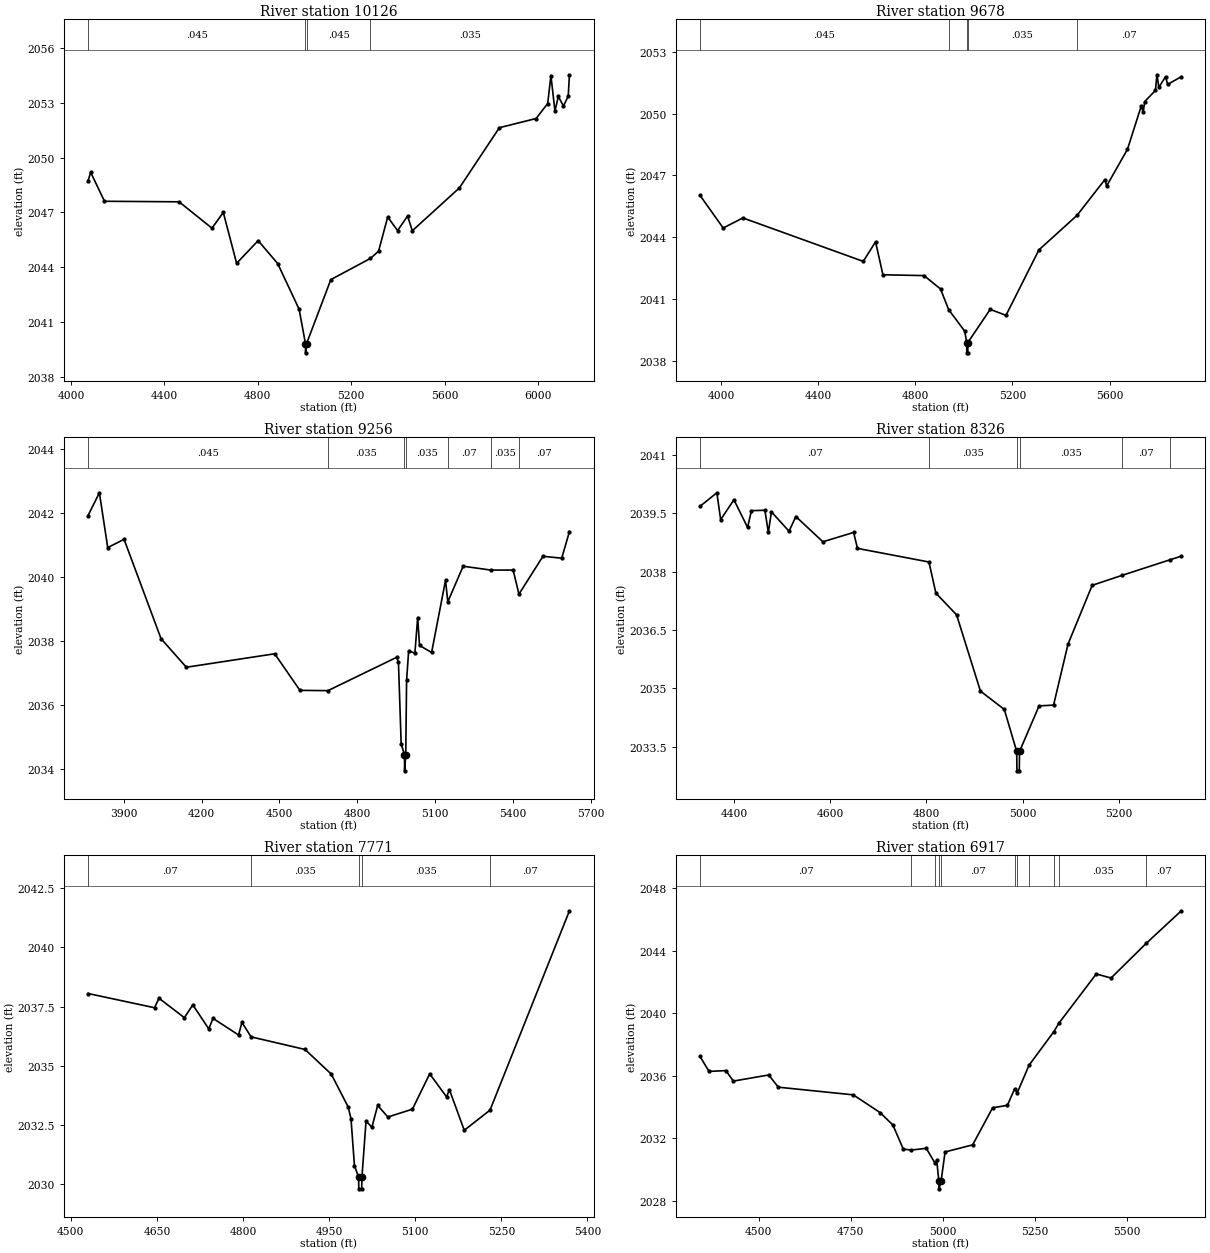
Type RM Length L Ch R = 1,10126,448,448,448
BEGIN DESCRIPTION:
Buffalo Creek Trib 01 4.0
END DESCRIPTION:
XS GIS Cut Line= 3
      1333455.89      6960586.94      1333255.00      6961488.00
      1333630.00      6962562.99
#Sta/Elev= 30
  4072.7 2048.73  4084.0 2049.19  4143.1 2047.61  4462.7 2047.58  4603.4 2046.14
  4651.9 2047.00  4709.0 2044.22  4801.2 2045.46  4884.7 2044.21  4976.7 2041.71
  5003.8 2039.83  5004.2 2039.33  5008.4 2039.83  5112.4 2043.33  5282.3 2044.49
  5316.8 2044.88  5356.0 2046.75  5398.3 2046.01  5441.1 2046.80  5461.5 2046.00
  5663.1 2048.34  5834.3 2051.63  5991.4 2052.13  6041.2 2052.95  6055.0 2054.48
  6072.3 2052.53  6086.8 2053.34  6108.6 2052.81  6129.1 2053.35  6134.4 2054.52
#Mann=4,-1,0
  4072.7   0.045       0  5003.8   0.045       0  5008.4   0.045       0
  5282.3   0.035       0
Bank Sta=5003.8,5008.4
Exp/Cntr=0.3,0.1

Type RM Length L Ch R = 1,9678,422,422,422
BEGIN DESCRIPTION:
Buffalo Creek Trib 01 3.0
END DESCRIPTION:
XS GIS Cut Line= 3
      1333122.56      6960663.33      1332955.00      6961738.00
      1333480.01      6962463.01
#Sta/Elev= 30
  3912.7 2046.03  4008.5 2044.44  4089.5 2044.93  4585.4 2042.82  4636.0 2043.77
  4666.4 2042.17  4835.7 2042.13  4903.6 2041.48  4937.0 2040.48  5003.4 2039.43
  5011.5 2038.88  5011.9 2038.38  5015.9 2038.38  5016.2 2038.88  5108.2 2040.49
  5173.2 2040.20  5309.0 2043.38  5465.5 2045.05  5580.6 2046.79  5587.7 2046.48
  5673.5 2048.26  5730.0 2050.35  5738.5 2050.07  5744.7 2050.58  5788.8 2051.12
  5794.9 2051.88  5802.9 2051.27  5830.5 2051.79  5839.0 2051.41  5895.5 2051.79
#Mann=5,-1,0
  3912.7   0.045       0  4937.0   0.035       0  5011.5   0.035       0
  5016.2   0.035       0  5465.5    0.07       0
Bank Sta=5011.5,5016.2
Exp/Cntr=0.3,0.1

Type RM Length L Ch R = 1,9256,930,930,930
BEGIN DESCRIPTION:
Buffalo Creek Trib 01 2.0
END DESCRIPTION:
XS GIS Cut Line= 3
      1332285.66      6960705.54      1332655.00      6961888.00
      1332880.02      6962463.04
#Sta/Elev= 30
  3762.1 2041.91  3805.8 2042.62  3838.0 2040.91  3900.9 2041.17  4043.6 2038.07
  4141.1 2037.18  4481.7 2037.60  4579.1 2036.46  4687.0 2036.45  4952.2 2037.49
  4959.0 2037.33  4969.5 2034.79  4982.3 2034.45  4982.6 2033.95  4987.1 2034.45
  4990.4 2036.77  4998.3 2037.69  5022.4 2037.62  5033.1 2038.73  5040.3 2037.86
  5086.8 2037.64  5140.5 2039.89  5149.3 2039.22  5208.5 2040.33  5314.8 2040.21
  5401.2 2040.21  5423.6 2039.46  5516.3 2040.64  5588.5 2040.58  5618.4 2041.41
#Mann=7,-1,0
  3762.1   0.045       0  4687.0   0.035       0  4982.3   0.035       0
  4987.1   0.035       0  5149.3    0.07       0  5314.8   0.035       0
  5423.6    0.07       0
Bank Sta=4982.3,4987.1
Exp/Cntr=0.3,0.1

Type RM Length L Ch R = 1,8326,555,555,555
BEGIN DESCRIPTION:
Buffalo Creek Trib 01 1.0
END DESCRIPTION:
XS GIS Cut Line= 3
      1331780.01      6962113.01      1332305.00      6962538.00
      1332630.00      6962513.00
#Sta/Elev= 30
  4329.0 2039.68  4364.2 2040.03  4372.1 2039.34  4399.7 2039.85  4428.1 2039.14
  4436.1 2039.57  4464.1 2039.58  4471.3 2039.01  4477.7 2039.54  4514.4 2039.04
  4528.4 2039.42  4584.8 2038.77  4648.7 2039.01  4656.7 2038.60  4805.4 2038.25
  4819.8 2037.45  4862.9 2036.89  4912.5 2034.93  4962.1 2034.46  4987.9 2033.38
  4988.4 2032.88  4993.3 2032.88  4993.8 2033.38  5034.5 2034.55  5064.6 2034.57
  5094.7 2036.14  5144.9 2037.65  5207.8 2037.91  5307.6 2038.31  5330.4 2038.40
#Mann=6,-1,0
  4329.0    0.07       0  4805.4   0.035       0  4987.9   0.035       0
  4993.8   0.035       0  5207.8    0.07       0  5307.6   0.035       0
Bank Sta=4987.9,4993.8
Exp/Cntr=0.3,0.1

Type RM Length L Ch R = 1,7771,854,854,854
BEGIN DESCRIPTION:
Buffalo Creek Trib 01 0.9
END DESCRIPTION:
XS GIS Cut Line= 4
      1331979.97      6962712.96      1332190.26      6963051.65
      1332341.31      6963029.08      1332627.73      6963006.52
#Sta/Elev= 30
  4530.0 2038.05  4645.8 2037.45  4653.6 2037.85  4697.8 2037.03  4712.5 2037.57
  4740.3 2036.56  4747.8 2037.00  4792.2 2036.30  4798.1 2036.83  4814.1 2036.22
  4908.0 2035.69  4953.7 2034.65  4983.1 2033.27  4988.1 2032.77  4994.1 2030.79
  5001.3 2030.31  5001.7 2029.81  5006.7 2029.81  5007.2 2030.31  5014.3 2032.67
  5024.5 2032.41  5034.6 2033.33  5052.3 2032.84  5095.1 2033.17  5125.2 2034.66
  5154.6 2033.69  5159.6 2033.99  5185.4 2032.28  5230.3 2033.13  5368.7 2041.54
#Mann=5,-1,0
  4530.0    0.07       0  4814.1   0.035       0  5001.3   0.035       0
  5007.2   0.035       0  5230.3    0.07       0
Bank Sta=5001.3,5007.2
Exp/Cntr=0.3,0.1

Type RM Length L Ch R = 1,6917,487,487,487
BEGIN DESCRIPTION:
Buffalo Creek Trib 01 0.7
END DESCRIPTION:
XS GIS Cut Line= 4
      1331855.41      6962988.71      1331945.91      6963467.02
      1332213.92      6963595.06      1332734.75      6963651.51
#Sta/Elev= 30
  4340.9 2037.23  4365.6 2036.27  4411.4 2036.32  4431.8 2035.65  4527.7 2036.04
  4553.9 2035.26  4757.4 2034.77  4830.0 2033.64  4865.1 2032.84  4893.3 2031.30
  4914.7 2031.24  4955.8 2031.35  4979.6 2030.40  4984.1 2030.58  4989.8 2029.26
  4990.3 2028.76  4996.0 2029.26  5006.8 2031.12  5081.6 2031.57  5135.9 2033.94
  5176.1 2034.10  5195.8 2035.16  5202.7 2034.89  5234.8 2036.66  5302.5 2038.82
  5315.6 2039.34  5417.5 2042.50  5457.7 2042.24  5553.7 2044.47  5648.6 2046.54
#Mann=11,-1,0
  4340.9    0.07       0  4914.7   0.035       0  4979.6    0.07       0
  4989.8    0.07       0  4996.0    0.07       0  5195.8   0.035       0
  5202.7    0.07       0  5234.8   0.035       0  5302.5    0.07       0
  5315.6   0.035       0  5553.7    0.07       0
Bank Sta=4989.8,4996
Exp/Cntr=0.3,0.1

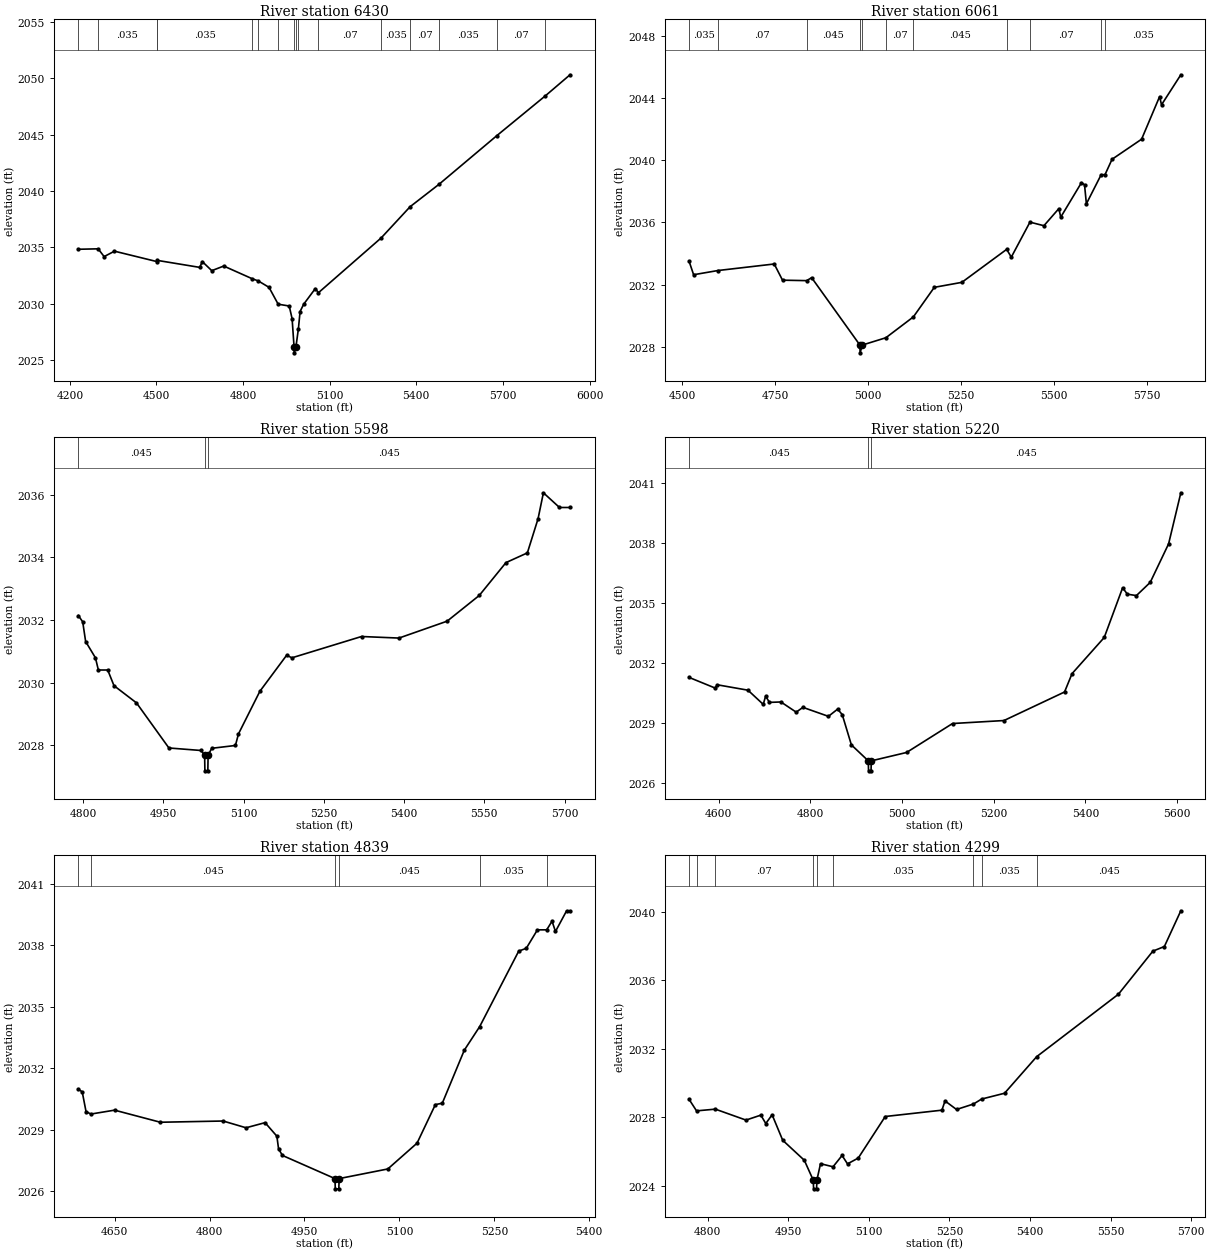
Type RM Length L Ch R = 1,6430,369,369,369
BEGIN DESCRIPTION:
Buffalo Creek Trib 01 0.8
END DESCRIPTION:
XS GIS Cut Line= 4
      1331830.01      6963331.21      1331986.05      6963963.76
      1332105.20      6963958.06      1333031.03      6963846.70
#Sta/Elev= 30
  4229.2 2034.83  4297.9 2034.87  4318.6 2034.18  4354.5 2034.66  4500.7 2033.74
  4503.3 2033.84  4650.0 2033.22  4658.5 2033.74  4691.5 2032.93  4733.0 2033.34
  4831.8 2032.21  4852.5 2032.02  4889.7 2031.45  4921.5 2029.95  4959.8 2029.79
  4969.8 2028.66  4976.6 2026.13  4977.1 2025.63  4982.9 2026.13  4991.6 2027.77
  4997.4 2029.30  5009.9 2029.95  5050.2 2031.34  5061.0 2030.97  5278.4 2035.84
  5378.5 2038.61  5478.6 2040.60  5678.8 2044.92  5847.5 2048.47  5932.5 2050.33
#Mann=16,-1,0
  4229.2    0.07       0  4297.9   0.035       0  4500.7    0.07       0
  4503.3   0.035       0  4831.8    0.07       0  4852.5   0.035       0
  4921.5    0.07       0  4976.6   0.035       0  4982.9    0.07       0
  4991.6   0.035       0  5061.0    0.07       0  5278.4   0.035       0
  5378.5    0.07       0  5478.6   0.035       0  5678.8    0.07       0
  5847.5   0.035       0
Bank Sta=4976.6,4982.9
Exp/Cntr=0.3,0.1

Type RM Length L Ch R = 1,6061,463,463,463
BEGIN DESCRIPTION:
Buffalo Creek Trib 01 0.99
END DESCRIPTION:
XS GIS Cut Line= 3
      1331696.17      6964018.66      1331875.44      6964281.80
      1332869.40      6964431.03
#Sta/Elev= 30
  4518.4 2033.50  4530.5 2032.64  4596.0 2032.91  4747.5 2033.33  4769.8 2032.29
  4834.7 2032.26  4848.2 2032.45  4978.1 2028.12  4978.6 2027.62  4984.5 2028.12
  5048.0 2028.59  5122.0 2029.93  5178.4 2031.83  5252.5 2032.15  5373.1 2034.27
  5385.6 2033.77  5435.8 2036.02  5473.4 2035.79  5513.6 2036.89  5518.7 2036.34
  5574.5 2038.56  5582.7 2038.42  5587.7 2037.20  5627.5 2039.07  5637.8 2039.07
  5656.8 2040.06  5736.3 2041.35  5784.8 2044.09  5789.9 2043.56  5841.9 2045.49
#Mann=11,-1,0
  4518.4   0.035       0  4596.0    0.07       0  4834.7   0.045       0
  4978.1   0.045       0  4984.5   0.045       0  5048.0    0.07       0
  5122.0   0.045       0  5373.1   0.035       0  5435.8    0.07       0
  5627.5   0.045       0  5637.8   0.035       0
Bank Sta=4978.1,4984.5
Exp/Cntr=0.3,0.1

Type RM Length L Ch R = 1,5598,378,378,378
BEGIN DESCRIPTION:
Buffalo Creek Trib 01 0.98
END DESCRIPTION:
XS GIS Cut Line= 3
      1331726.01      6964587.31      1331776.64      6964708.20
      1332564.73      6964731.53
#Sta/Elev= 30
  4790.8 2032.14  4799.0 2031.94  4804.5 2031.31  4822.8 2030.79  4828.3 2030.40
  4845.8 2030.40  4857.5 2029.90  4899.6 2029.35  4960.2 2027.91  5020.3 2027.83
  5027.0 2027.68  5027.5 2027.18  5033.0 2027.18  5033.5 2027.68  5040.3 2027.90
  5084.6 2027.99  5090.3 2028.36  5130.3 2029.72  5180.3 2030.87  5190.3 2030.79
  5320.4 2031.47  5390.4 2031.42  5480.5 2031.96  5540.5 2032.78  5590.5 2033.83
  5630.5 2034.14  5650.5 2035.23  5660.5 2036.06  5690.6 2035.59  5710.3 2035.59
#Mann=3,-1,0
  4790.8   0.045       0  5027.0   0.045       0  5033.5   0.045       0
Bank Sta=5027,5033.5
Exp/Cntr=0.3,0.1

Type RM Length L Ch R = 1,5220,381,381,381
BEGIN DESCRIPTION:
Buffalo Creek Trib 01 0.97
END DESCRIPTION:
XS GIS Cut Line= 3
      1331703.77      6964759.82      1331787.41      6965044.04
      1332561.66      6965102.05
#Sta/Elev= 30
  4535.4 2031.27  4591.9 2030.74  4597.1 2030.90  4663.8 2030.63  4697.1 2029.92
  4702.3 2030.33  4710.7 2030.02  4735.7 2030.04  4769.0 2029.53  4783.7 2029.77
  4839.3 2029.32  4859.3 2029.68  4869.4 2029.41  4889.4 2027.89  4926.3 2027.09
  4926.8 2026.59  4932.3 2026.59  4932.8 2027.09  5009.8 2027.51  5110.0 2028.96
  5222.3 2029.11  5354.4 2030.54  5370.8 2031.46  5441.0 2033.27  5481.1 2035.76
  5491.5 2035.44  5511.2 2035.37  5541.3 2036.03  5581.4 2037.96  5608.1 2040.52
#Mann=3,-1,0
  4535.4   0.045       0  4926.3   0.045       0  4932.8   0.045       0
Bank Sta=4926.3,4932.8
Exp/Cntr=0.3,0.1

Type RM Length L Ch R = 1,4839,540,540,540
BEGIN DESCRIPTION:
Buffalo Creek Trib 01 0.96
END DESCRIPTION:
XS GIS Cut Line= 3
      1331465.13      6965169.41      1331725.03      6965341.27
      1332148.82      6965533.42
#Sta/Elev= 30
  4592.7 2030.98  4598.9 2030.84  4604.9 2029.88  4612.6 2029.76  4650.0 2029.95
  4722.3 2029.36  4821.5 2029.42  4857.7 2029.09  4887.8 2029.34  4906.4 2028.68
  4909.1 2028.06  4915.2 2027.74  4998.2 2026.61  4998.7 2026.11  5004.3 2026.11
  5004.8 2026.61  5081.7 2027.08  5127.9 2028.34  5156.8 2030.22  5167.8 2030.29
  5202.6 2032.88  5226.9 2034.03  5288.5 2037.71  5300.5 2037.85  5318.1 2038.75
  5332.7 2038.75  5341.2 2039.17  5346.6 2038.67  5364.2 2039.68  5369.6 2039.65
#Mann=6,-1,0
  4592.7    0.07       0  4612.6   0.045       0  4998.2   0.045       0
  5004.8   0.045       0  5226.9   0.035       0  5332.7   0.045       0
Bank Sta=4998.2,5004.8
Exp/Cntr=0.3,0.1

Type RM Length L Ch R = 1,4299,498,498,498
BEGIN DESCRIPTION:
Buffalo Creek Trib 01 0.95
END DESCRIPTION:
XS GIS Cut Line= 4
      1331435.61      6965688.32      1331470.74      6965833.89
      1331741.30      6965810.01      1332164.08      6965555.95
#Sta/Elev= 30
  4765.8 2029.04  4779.6 2028.37  4814.6 2028.47  4871.6 2027.83  4899.2 2028.12
  4908.4 2027.63  4920.2 2028.14  4939.9 2026.65  4980.1 2025.48  4996.8 2024.31
  4997.3 2023.81  5002.9 2023.81  5003.4 2024.31  5010.2 2025.28  5033.5 2025.10
  5050.3 2025.76  5060.4 2025.27  5080.4 2025.61  5130.6 2028.04  5236.0 2028.41
  5241.8 2028.95  5263.2 2028.45  5294.7 2028.77  5309.8 2029.06  5352.5 2029.40
  5412.3 2031.54  5564.3 2035.19  5628.4 2037.71  5649.8 2037.98  5680.4 2040.07
#Mann=9,-1,0
  4765.8    0.07       0  4779.6   0.035       0  4814.6    0.07       0
  4996.8    0.07       0  5003.4    0.07       0  5033.5   0.035       0
  5294.7    0.07       0  5309.8   0.035       0  5412.3   0.045       0
Bank Sta=4996.8,5003.4
Exp/Cntr=0.3,0.1

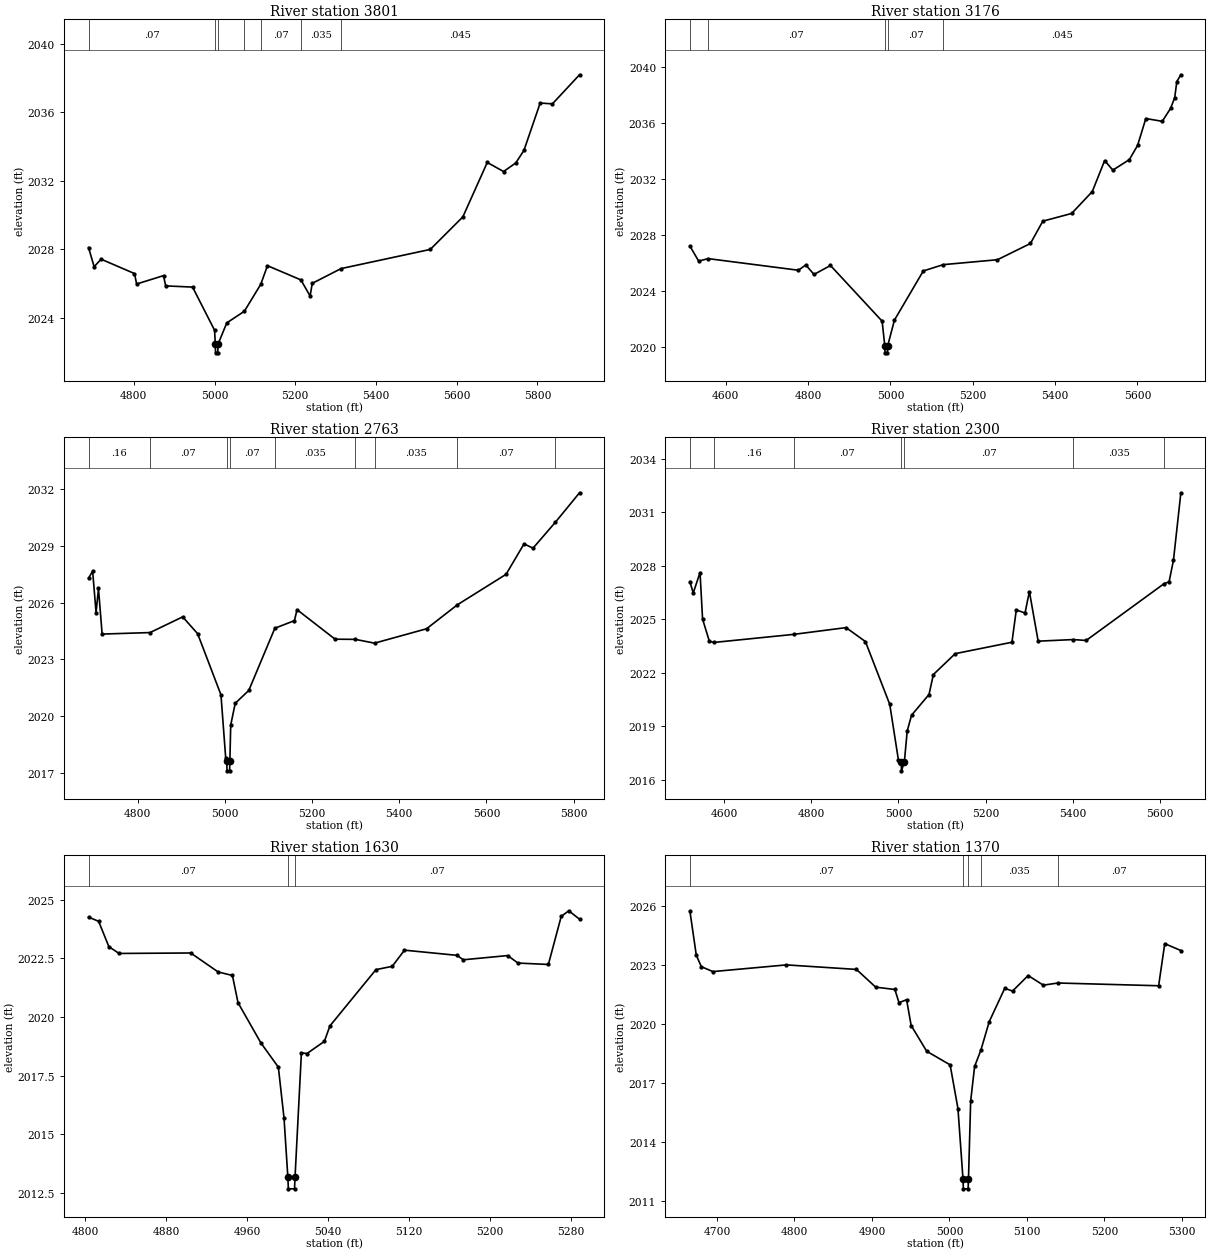
Type RM Length L Ch R = 1,3801,625,625,625
BEGIN DESCRIPTION:
Buffalo Creek Trib 01 0.94
END DESCRIPTION:
XS GIS Cut Line= 3
      1331486.53      6966028.18      1331562.56      6966286.73
      1332501.63      6966409.79
#Sta/Elev= 30
  4687.8 2028.09  4701.7 2026.97  4718.9 2027.41  4801.7 2026.57  4807.0 2025.96
  4873.7 2026.45  4878.9 2025.85  4945.6 2025.78  5000.1 2023.26  5002.0 2022.44
  5002.5 2021.94  5008.1 2021.94  5008.6 2022.44  5030.4 2023.69  5074.0 2024.37
  5114.5 2025.94  5131.2 2027.03  5214.0 2026.20  5236.8 2025.26  5242.2 2026.00
  5313.5 2026.86  5534.6 2027.98  5615.3 2029.88  5675.8 2033.06  5716.2 2032.53
  5746.4 2033.03  5766.6 2033.76  5806.9 2036.53  5837.2 2036.48  5904.4 2038.18
#Mann=7,-1,0
  4687.8    0.07       0  5002.0    0.07       0  5008.6    0.07       0
  5074.0   0.035       0  5114.5    0.07       0  5214.0   0.035       0
  5313.5   0.045       0
Bank Sta=5002,5008.6
Exp/Cntr=0.3,0.1

Type RM Length L Ch R = 1,3176,413,413,413
BEGIN DESCRIPTION:
Buffalo Creek Trib 01 0.93
END DESCRIPTION:
XS GIS Cut Line= 3
      1331567.09      6966536.63      1331571.03      6966889.37
      1332410.04      6966862.70
#Sta/Elev= 30
  4513.1 2027.22  4534.5 2026.14  4557.3 2026.32  4776.7 2025.49  4794.5 2025.87
  4814.5 2025.19  4854.5 2025.83  4979.9 2021.86  4986.4 2020.10  4986.9 2019.60
  4992.9 2019.60  4993.4 2020.10  5009.9 2021.94  5079.9 2025.44  5128.4 2025.89
  5260.0 2026.24  5340.1 2027.40  5370.1 2028.99  5440.1 2029.54  5490.2 2031.10
  5520.2 2033.31  5540.2 2032.63  5580.2 2033.38  5600.2 2034.39  5620.2 2036.31
  5660.2 2036.11  5680.2 2037.03  5690.3 2037.79  5695.5 2038.95  5705.3 2039.43
#Mann=5,-1,0
  4513.1   0.035       0  4557.3    0.07       0  4986.4    0.07       0
  4993.4    0.07       0  5128.4   0.045       0
Bank Sta=4986.4,4993.4
Exp/Cntr=0.3,0.1

Type RM Length L Ch R = 1,2763,463,463,463
BEGIN DESCRIPTION:
Buffalo Creek Trib 01 0.92
END DESCRIPTION:
XS GIS Cut Line= 3
      1331236.39      6967095.10      1331782.13      6967332.07
      1332298.87      6967454.47
#Sta/Elev= 30
  4687.5 2027.29  4696.9 2027.67  4704.8 2025.48  4710.3 2026.75  4718.7 2024.34
  4828.6 2024.42  4903.4 2025.25  4937.7 2024.36  4991.2 2021.13  5002.1 2017.78
  5004.6 2017.61  5005.1 2017.11  5011.1 2017.11  5011.6 2017.61  5013.6 2019.53
  5023.9 2020.68  5055.0 2021.36  5114.8 2024.65  5159.7 2025.05  5165.7 2025.63
  5252.9 2024.07  5299.5 2024.06  5343.4 2023.86  5462.6 2024.62  5533.5 2025.89
  5645.1 2027.50  5686.2 2029.11  5706.8 2028.88  5757.7 2030.24  5813.5 2031.81
#Mann=9,-1,0
  4687.5    0.16       0  4828.6    0.07       0  5004.6    0.07       0
  5011.6    0.07       0  5114.8   0.035       0  5299.5    0.07       0
  5343.4   0.035       0  5533.5    0.07       0  5757.7   0.035       0
Bank Sta=5004.6,5011.6
Exp/Cntr=0.3,0.1

Type RM Length L Ch R = 1,2300,670,670,670
BEGIN DESCRIPTION:
Buffalo Creek Trib 01 0.91
END DESCRIPTION:
XS GIS Cut Line= 3
      1331248.11      6967363.00      1331427.80      6967664.19
      1332201.96      6967645.92
#Sta/Elev= 30
  4522.0 2027.12  4529.7 2026.48  4545.3 2027.63  4551.1 2025.02  4566.7 2023.77
  4577.5 2023.71  4759.5 2024.16  4879.9 2024.54  4924.2 2023.76  4980.0 2020.24
  5000.0 2017.10  5006.4 2017.01  5006.9 2016.51  5013.5 2017.01  5020.0 2018.74
  5030.0 2019.63  5070.0 2020.79  5080.0 2021.91  5130.0 2023.08  5260.0 2023.72
  5270.0 2025.53  5290.0 2025.36  5300.0 2026.56  5320.1 2023.78  5400.4 2023.87
  5430.1 2023.82  5609.0 2027.01  5620.1 2027.11  5630.1 2028.31  5647.1 2032.10
#Mann=7,-1,0
  4522.0    0.07       0  4577.5    0.16       0  4759.5    0.07       0
  5006.4    0.07       0  5013.5    0.07       0  5400.4   0.035       0
  5609.0    0.07       0
Bank Sta=5006.4,5013.5
Exp/Cntr=0.3,0.1

Type RM Length L Ch R = 1,1630,260,260,260
BEGIN DESCRIPTION:
Buffalo Creek Trib 01 0.89
END DESCRIPTION:
XS GIS Cut Line= 4
      1331331.18      6968128.16      1331351.26      6968256.69
      1331540.35      6968346.51      1331685.58      6968330.78
#Sta/Elev= 30
  4803.0 2024.26  4813.0 2024.08  4823.1 2023.00  4833.2 2022.71  4904.0 2022.73
  4931.2 2021.92  4945.3 2021.77  4950.8 2020.61  4973.5 2018.89  4990.7 2017.86
  4996.3 2015.69  5000.1 2013.17  5000.6 2012.67  5006.7 2012.67  5007.2 2013.17
  5013.5 2018.47  5019.0 2018.44  5036.2 2018.96  5041.7 2019.62  5087.2 2022.02
  5103.3 2022.16  5115.4 2022.85  5167.2 2022.63  5173.6 2022.44  5217.5 2022.62
  5227.6 2022.30  5257.7 2022.24  5270.4 2024.29  5277.9 2024.53  5288.5 2024.17
#Mann=3,-1,0
  4803.0    0.07       0  5000.1    0.07       0  5007.2    0.07       0
Bank Sta=5000.1,5007.2
Exp/Cntr=0.3,0.1

Type RM Length L Ch R = 1,1370,335,335,335
BEGIN DESCRIPTION:
Buffalo Creek Trib 01 0.85
END DESCRIPTION:
XS GIS Cut Line= 4
      1331325.67      6968140.24      1331229.17      6968394.35
      1331249.38      6968564.69      1331130.03      6968712.97
#Sta/Elev= 30
  4665.0 2025.74  4673.3 2023.48  4679.8 2022.90  4694.7 2022.65  4789.6 2022.99
  4880.0 2022.76  4904.8 2021.86  4929.6 2021.74  4934.9 2021.07  4944.7 2021.22
  4950.6 2019.91  4970.7 2018.60  5000.9 2017.91  5011.0 2015.69  5017.5 2012.11
  5018.0 2011.61  5024.1 2011.61  5024.6 2012.11  5027.4 2016.07  5032.5 2017.83
  5040.7 2018.67  5051.3 2020.10  5071.4 2021.80  5081.5 2021.66  5101.6 2022.45
  5121.2 2021.96  5140.0 2022.07  5270.0 2021.93  5277.9 2024.07  5298.7 2023.72
#Mann=5,-1,0
  4665.0    0.07       0  5017.5    0.07       0  5024.6    0.07       0
  5040.7   0.035       0  5140.0    0.07       0
Bank Sta=5017.5,5024.6
Exp/Cntr=0.3,0.1

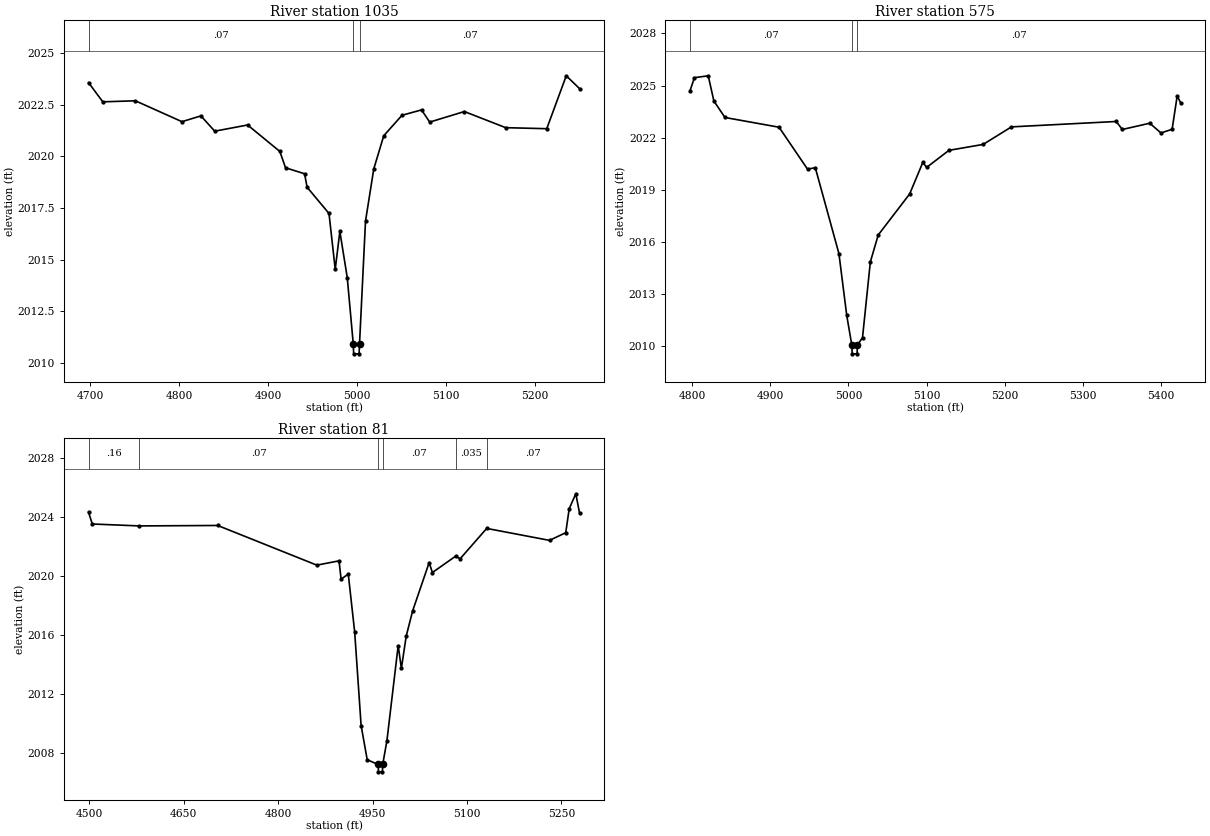
Type RM Length L Ch R = 1,1035,460,460,460
BEGIN DESCRIPTION:
Buffalo Creek Trib 01 0.88
END DESCRIPTION:
XS GIS Cut Line= 4
      1331318.71      6968138.05      1331107.68      6968265.93
      1330980.00      6968294.66      1330821.43      6968365.48
#Sta/Elev= 30
  4698.4 2023.57  4714.4 2022.64  4751.0 2022.69  4803.3 2021.68  4824.6 2021.96
  4840.1 2021.22  4877.0 2021.52  4913.2 2020.24  4919.6 2019.45  4941.0 2019.16
  4943.8 2018.51  4968.4 2017.24  4975.4 2014.54  4980.6 2016.37  4988.9 2014.14
  4995.6 2010.95  4996.1 2010.45  5002.2 2010.45  5002.7 2010.95  5009.4 2016.87
  5018.7 2019.40  5029.9 2021.00  5050.4 2021.99  5072.3 2022.25  5081.5 2021.66
  5120.4 2022.17  5166.8 2021.39  5212.9 2021.34  5234.8 2023.90  5249.7 2023.28
#Mann=3,-1,0
  4698.4    0.07       0  4995.6    0.07       0  5002.7    0.07       0
Bank Sta=4995.6,5002.7
Exp/Cntr=0.3,0.1

Type RM Length L Ch R = 1,575,494,494,494
BEGIN DESCRIPTION:
Buffalo Creek Trib 01 0.87
END DESCRIPTION:
XS GIS Cut Line= 4
      1331381.50      6967796.03      1331341.14      6967902.77
      1331099.03      6967876.83      1330924.54      6968083.64
#Sta/Elev= 30
  4797.2 2024.67  4803.0 2025.45  4820.7 2025.56  4827.9 2024.11  4842.1 2023.16
  4911.3 2022.60  4947.7 2020.19  4957.7 2020.27  4987.9 2015.33  4997.9 2011.77
  5004.4 2010.06  5004.9 2009.56  5011.1 2009.56  5011.6 2010.06  5018.1 2010.50
  5028.1 2014.85  5038.2 2016.40  5078.4 2018.76  5095.2 2020.57  5100.2 2020.29
  5128.7 2021.27  5172.4 2021.61  5208.7 2022.62  5342.7 2022.93  5350.5 2022.47
  5385.6 2022.83  5399.9 2022.27  5414.2 2022.48  5420.7 2024.40  5425.4 2023.98
#Mann=3,-1,0
  4797.2    0.07       0  5004.4    0.07       0  5011.6    0.07       0
Bank Sta=5004.4,5011.6
Exp/Cntr=0.3,0.1

Type RM Length L Ch R = 1,81,0,0,0
BEGIN DESCRIPTION:
Buffalo Creek Trib 01 0.86
END DESCRIPTION:
XS GIS Cut Line= 4
      1331217.41      6967471.41      1330899.72      6967717.06
      1330856.19      6967918.08      1330906.48      6968083.65
#Sta/Elev= 30
  4498.5 2024.32  4504.5 2023.52  4579.2 2023.39  4703.8 2023.42  4861.3 2020.73
  4896.6 2021.02  4899.9 2019.78  4911.3 2020.12  4921.5 2016.18  4931.7 2009.85
  4941.4 2007.53  4958.8 2007.21  4959.3 2006.71  4965.5 2006.71  4966.0 2007.21
  4972.7 2008.82  4990.6 2015.27  4995.7 2013.73  5003.4 2015.92  5013.6 2017.63
  5039.8 2020.90  5045.0 2020.23  5082.0 2021.34  5089.0 2021.16  5131.3 2023.22
  5231.1 2022.41  5256.9 2022.93  5262.4 2024.56  5272.9 2025.57  5278.8 2024.27
#Mann=6,-1,0
  4498.5    0.16       0  4579.2    0.07       0  4958.8    0.07       0
  4966.0    0.07       0  5082.0   0.035       0  5131.3    0.07       0
Bank Sta=4958.8,4966
Exp/Cntr=0.3,0.1

Chan Stop Cuts=-1