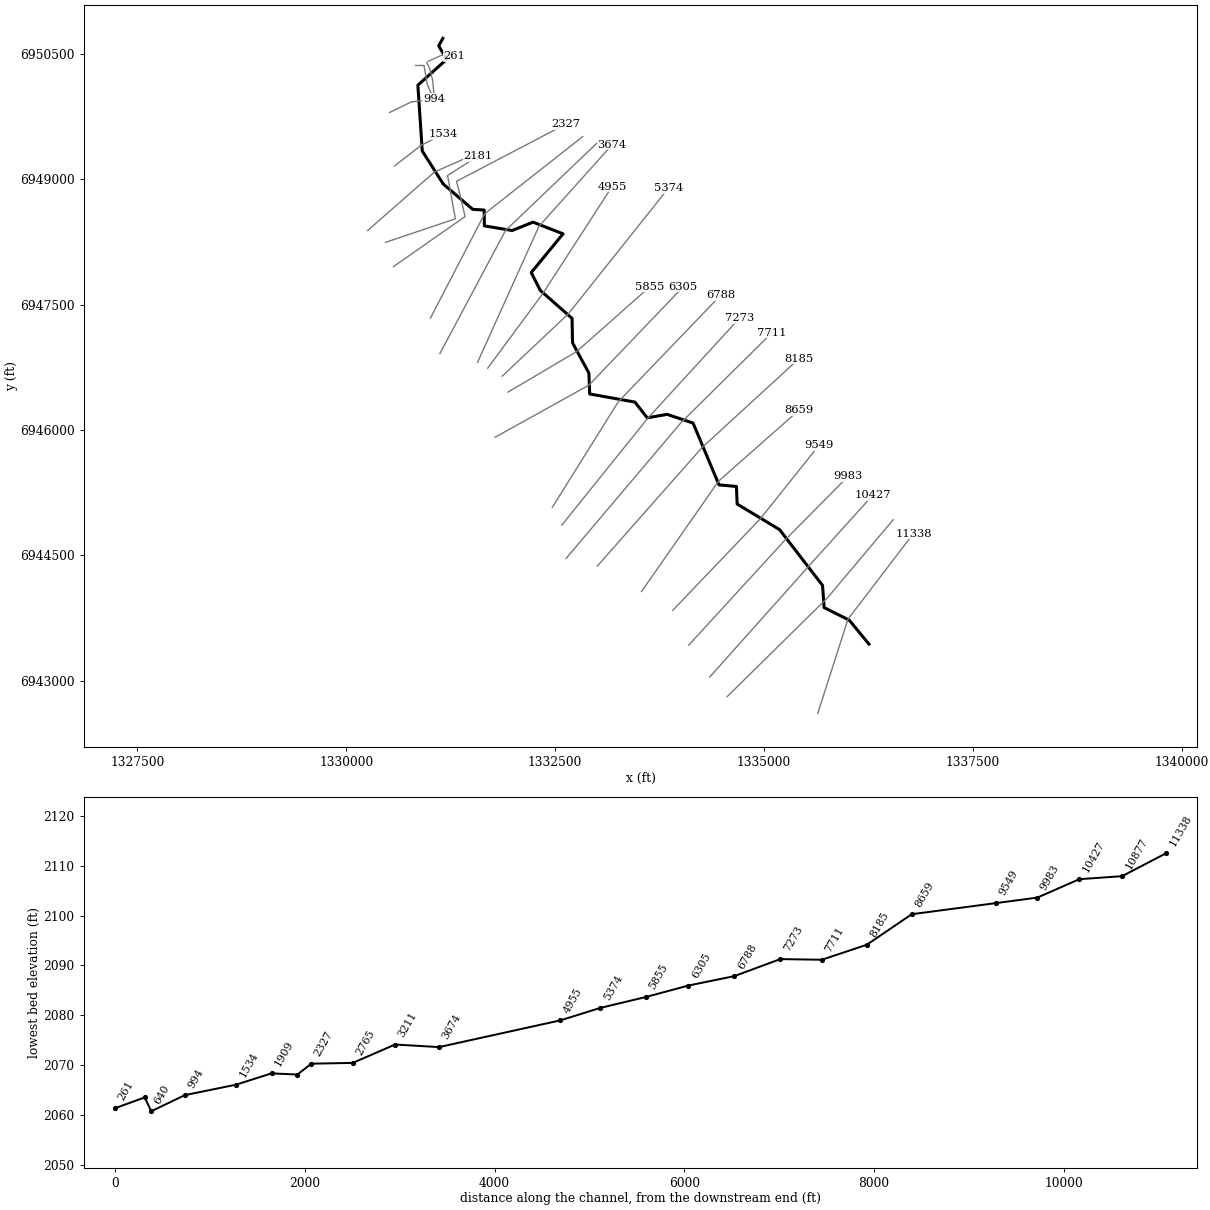
--- Buffalo Creek Trib 02-01.prj (project) ---

Proj Title=Buffalo Creek Trib 02-01 Base Level Engineering
Current Plan=p01
Default Exp/Contr=0.3,0.1
English Units
Geom File=g01
Flow File=f01
Plan File=p01
Y Axis Title=Elevation
X Axis Title(PF)=Main Channel Distance
X Axis Title(XS)=Station
BEGIN DESCRIPTION:
Buffalo Creek Trib 02-01
END DESCRIPTION:
DSS Export Rating Curves= 0
DSS Export Rating Curve Sorted= 0
DSS Export Volume Flow Curves= 0
DXF OffsetX= 0
DXF OffsetY= 0
DXF ScaleX= 1
DXF ScaleY= 10

--- Buffalo Creek Trib 02-01.p01 (plan) ---

Plan Title=Multiple Run
Short Identifier=Multiple
Geom File=g01
Flow File=f01
Subcritical Flow
K Sum by GR= 0
Std Step Tol= 0.01
Critical Tol= 0.01
Num of Std Step Trials= 20
Max Error Tol= 0.3
Flow Tol Ratio= 0.001
Split Flow NTrial= 30
Split Flow Tol= 0.02
Split Flow Ratio= 0.02
Log Output Level= 0
Friction Slope Method= 1
Unsteady Friction Slope Method= 2
Unsteady Bridges Friction Slope Method= 1
Parabolic Critical Depth
Global Vel Dist=  1 , 1 , 1
Global Log Level= 0
CheckData=True
Encroach Param= -1, 0, 0, 0
BEGIN DESCRIPTION:
Multiple Run
END DESCRIPTION:

--- Buffalo Creek Trib 02-01.f01 (steady flow) ---

Flow Title=Multiple
Number of Profiles=7
Profile Names=10-year,25-year,50-year,1pct_min,100-year,1pct_plu,500-year
River Rch & RM= Buffalo Creek Tr,Reach-1,11338
     422     614     779     492     981    1957    1574
River Rch & RM= Buffalo Creek Tr,Reach-1,3674
     550     809    1035     657    1311    2615    2132
River Rch & RM= Buffalo Creek Tr,Reach-1,994
     555     815    1042     661    1320    2633    2144
Boundary for River Rch & Prof#=Buffalo Creek Tr,Reach-1,1
Up Type=0
Dn Type=3
Dn Slope=0.005
Boundary for River Rch & Prof#=Buffalo Creek Tr,Reach-1,2
Up Type=0
Dn Type=3
Dn Slope=0.005
Boundary for River Rch & Prof#=Buffalo Creek Tr,Reach-1,3
Up Type=0
Dn Type=3
Dn Slope=0.005
Boundary for River Rch & Prof#=Buffalo Creek Tr,Reach-1,4
Up Type=0
Dn Type=3
Dn Slope=0.005
Boundary for River Rch & Prof#=Buffalo Creek Tr,Reach-1,5
Up Type=0
Dn Type=3
Dn Slope=0.005
Boundary for River Rch & Prof#=Buffalo Creek Tr,Reach-1,6
Up Type=0
Dn Type=3
Dn Slope=0.005
Boundary for River Rch & Prof#=Buffalo Creek Tr,Reach-1,7
Up Type=0
Dn Type=3
Dn Slope=0.005

--- Buffalo Creek Trib 02-01.g01 (geometry) ---

Geom Title=Existing Conditions

River Reach=Buffalo Creek Tr,Reach-1
Reach XY= 30
      1336255.00      6943438.00      1336018.65      6943724.74
      1335718.53      6943874.60      1335699.48      6944140.43
      1335185.16      6944807.93      1334677.51      6945114.29
      1334668.81      6945324.62      1334460.25      6945343.44
      1334149.92      6946082.97      1333839.84      6946187.61
      1333601.64      6946146.03      1333453.78      6946334.56
      1332912.68      6946431.48      1332902.76      6946682.07
      1332707.24      6947043.93      1332701.46      6947336.54
      1332321.49      6947670.95      1332212.84      6947884.77
      1332594.05      6948348.05      1332234.65      6948487.91
      1331984.97      6948388.04      1331651.99      6948443.46
      1331650.06      6948632.96      1331513.32      6948641.09
      1331160.62      6948943.62      1330908.76      6949339.56
      1330856.19      6950127.52      1331199.94      6950435.71
      1331105.50      6950598.55      1331155.00      6950688.00

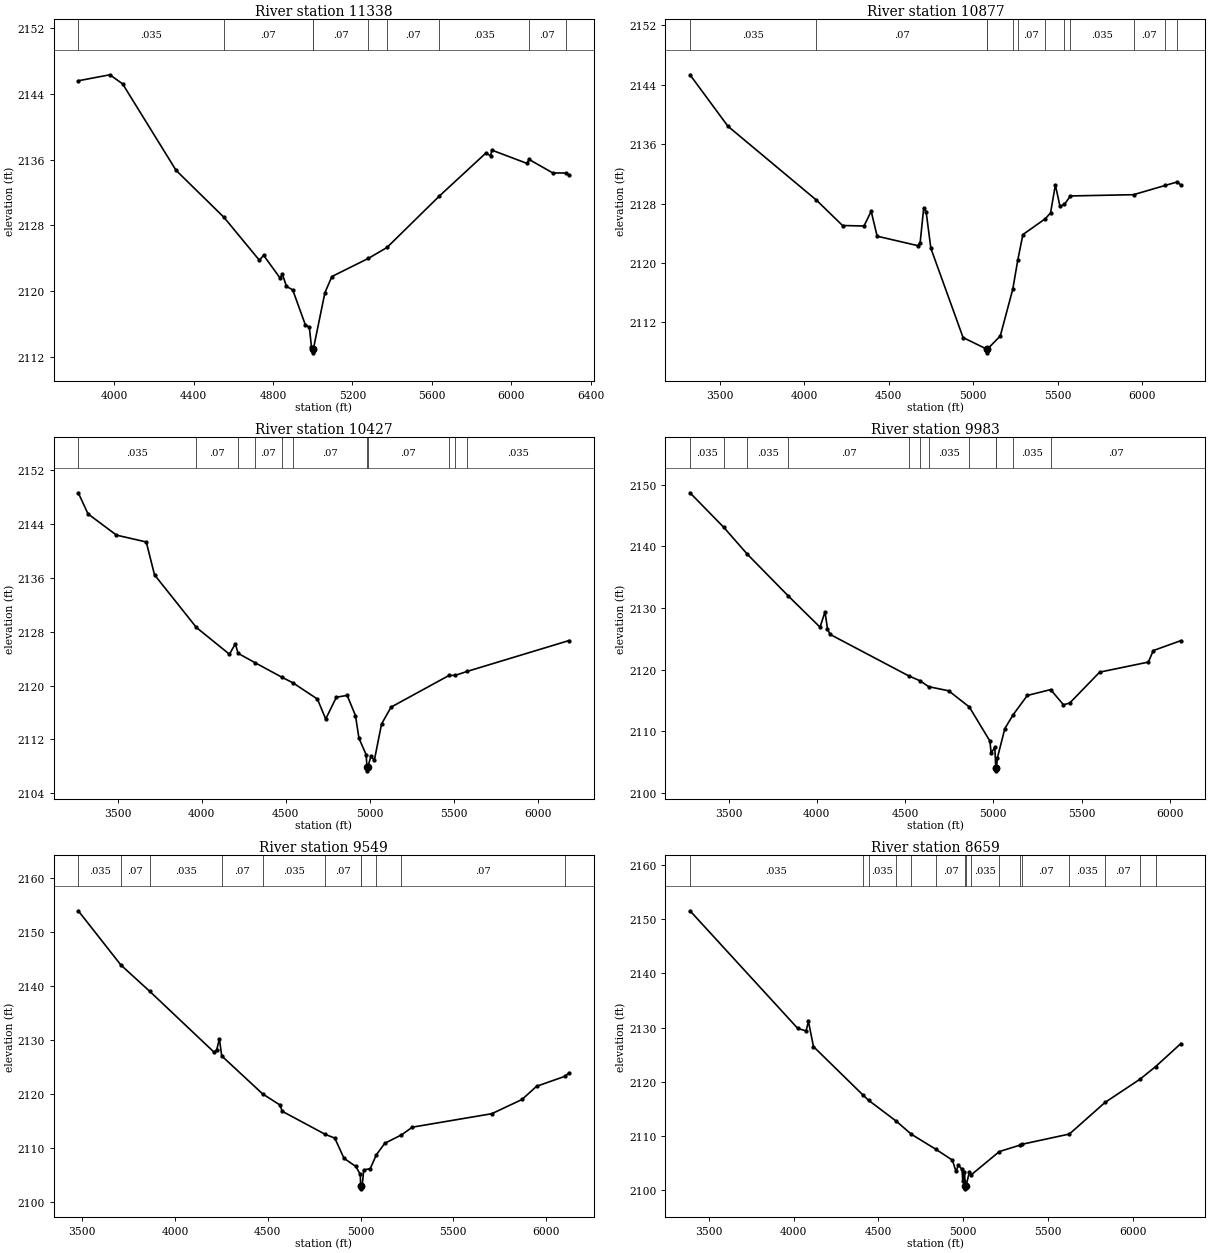
Type RM Length L Ch R = 1,11338,461,461,461
BEGIN DESCRIPTION:
Buffalo Creek Trib 02-01 20.0
END DESCRIPTION:
XS GIS Cut Line= 3
      1335642.02      6942608.74      1336005.00      6943738.00
      1336787.84      6944761.47
#Sta/Elev= 30
  3817.6 2145.63  3977.0 2146.36  4041.2 2145.25  4310.5 2134.72  4552.1 2128.99
  4731.0 2123.75  4751.7 2124.37  4835.7 2121.57  4846.2 2122.08  4867.2 2120.58
  4898.7 2120.15  4961.8 2115.93  4982.5 2115.57  4993.3 2113.20  4999.1 2112.98
  4999.4 2112.48  5003.1 2112.98  5060.9 2119.80  5096.2 2121.78  5279.5 2123.98
  5374.2 2125.32  5636.9 2131.56  5873.3 2136.84  5896.1 2136.46  5902.4 2137.18
  6081.0 2135.55  6089.1 2136.06  6209.8 2134.40  6276.2 2134.39  6292.3 2134.12
#Mann=9,-1,0
  3817.6   0.035       0  4552.1    0.07       0  4999.1    0.07       0
  5003.1    0.07       0  5279.5   0.035       0  5374.2    0.07       0
  5636.9   0.035       0  6089.1    0.07       0  6276.2   0.035       0
Bank Sta=4999.1,5003.1
Exp/Cntr=0.3,0.1

Type RM Length L Ch R = 1,10877,450,450,450
BEGIN DESCRIPTION:
Buffalo Creek Trib 02-01 19.0
END DESCRIPTION:
XS GIS Cut Line= 3
      1334556.91      6942808.32      1335755.00      6943988.00
      1336544.78      6944926.39
#Sta/Elev= 30
  3322.8 2145.36  3547.5 2138.43  4071.7 2128.48  4226.4 2125.06  4353.6 2124.99
  4396.1 2126.98  4431.4 2123.62  4671.8 2122.35  4686.0 2122.71  4707.2 2127.39
  4721.4 2126.94  4749.7 2121.99  4940.5 2109.97  5080.6 2108.41  5080.9 2107.91
  5084.6 2108.41  5160.9 2110.18  5235.1 2116.50  5264.3 2120.37  5294.9 2123.84
  5426.4 2125.95  5458.7 2126.75  5487.3 2130.53  5514.7 2127.62  5540.5 2127.90
  5576.8 2129.04  5950.1 2129.21  6137.0 2130.45  6206.2 2130.91  6230.7 2130.54
#Mann=12,-1,0
  3322.8   0.035       0  4071.7    0.07       0  5080.6    0.07       0
  5084.6    0.07       0  5235.1   0.035       0  5264.3    0.07       0
  5426.4   0.035       0  5540.5    0.07       0  5576.8   0.035       0
  5950.1    0.07       0  6137.0   0.035       0  6206.2    0.07       0
Bank Sta=5080.6,5084.6
Exp/Cntr=0.3,0.1

Type RM Length L Ch R = 1,10427,444,444,444
BEGIN DESCRIPTION:
Buffalo Creek Trib 02-01 18.0
END DESCRIPTION:
XS GIS Cut Line= 3
      1334348.64      6943042.76      1335505.00      6944338.00
      1336300.90      6945220.62
#Sta/Elev= 30
  3263.7 2148.68  3321.7 2145.54  3491.4 2142.38  3668.7 2141.36  3718.0 2136.47
  3967.5 2128.64  4164.4 2124.66  4199.5 2126.21  4216.0 2124.79  4315.2 2123.42
  4477.6 2121.23  4542.1 2120.41  4688.6 2117.99  4737.9 2115.02  4801.5 2118.26
  4865.8 2118.54  4915.2 2115.54  4936.1 2112.16  4978.7 2109.73  4984.2 2107.81
  4984.5 2107.31  4988.2 2107.81  5007.1 2109.45  5028.1 2108.92  5070.7 2114.28
  5127.4 2116.79  5472.5 2121.50  5510.2 2121.52  5581.6 2122.11  6188.5 2126.70
#Mann=11,-1,0
  3263.7   0.035       0  3967.5    0.07       0  4216.0   0.035       0
  4315.2    0.07       0  4477.6   0.035       0  4542.1    0.07       0
  4984.2    0.07       0  4988.2    0.07       0  5472.5   0.035       0
  5510.2    0.07       0  5581.6   0.035       0
Bank Sta=4984.2,4988.2
Exp/Cntr=0.3,0.1

Type RM Length L Ch R = 1,9983,434,434,434
BEGIN DESCRIPTION:
Buffalo Creek Trib 02-01 17.0
END DESCRIPTION:
XS GIS Cut Line= 3
      1334096.88      6943424.68      1335255.00      6944688.00
      1336006.62      6945447.26
#Sta/Elev= 30
  3280.9 2148.69  3473.0 2143.07  3605.5 2138.74  3838.8 2131.94  4018.0 2126.90
  4046.1 2129.39  4060.2 2126.63  4074.4 2125.74  4520.1 2119.01  4584.1 2118.22
  4633.5 2117.26  4747.2 2116.58  4863.8 2113.97  4980.9 2108.43  4987.6 2106.50
  5008.8 2107.40  5013.8 2104.11  5014.1 2103.61  5018.0 2104.11  5023.0 2105.69
  5065.4 2110.46  5112.6 2112.71  5192.7 2115.83  5324.8 2116.78  5397.8 2114.32
  5433.1 2114.60  5602.8 2119.61  5878.7 2121.24  5906.9 2123.11  6063.1 2124.72
#Mann=12,-1,0
  3280.9   0.035       0  3473.0    0.07       0  3605.5   0.035       0
  3838.8    0.07       0  4520.1   0.035       0  4584.1    0.07       0
  4633.5   0.035       0  4863.8    0.07       0  5013.8    0.07       0
  5018.0    0.07       0  5112.6   0.035       0  5324.8    0.07       0
Bank Sta=5013.8,5018
Exp/Cntr=0.3,0.1

Type RM Length L Ch R = 1,9549,890,890,890
BEGIN DESCRIPTION:
Buffalo Creek Trib 02-01 16.0
END DESCRIPTION:
XS GIS Cut Line= 3
      1333905.92      6943841.36      1334955.00      6944938.00
      1335659.39      6945820.53
#Sta/Elev= 30
  3478.2 2153.89  3708.2 2143.86  3863.8 2139.00  4210.7 2127.75  4224.8 2128.21
  4239.0 2130.22  4251.7 2127.07  4472.3 2120.05  4564.5 2118.03  4578.6 2116.83
  4809.6 2112.58  4861.4 2111.88  4911.1 2108.15  4974.6 2106.65  4999.0 2105.17
  5000.7 2103.01  5001.0 2102.51  5005.3 2103.01  5009.4 2103.22  5017.4 2105.99
  5052.7 2106.26  5085.6 2108.81  5131.1 2110.93  5220.3 2112.47  5280.0 2113.91
  5707.6 2116.39  5870.9 2119.02  5949.3 2121.46  6103.0 2123.31  6125.0 2123.97
#Mann=11,-1,0
  3478.2   0.035       0  3708.2    0.07       0  3863.8   0.035       0
  4251.7    0.07       0  4472.3   0.035       0  4809.6    0.07       0
  5000.7    0.07       0  5005.3    0.07       0  5085.6   0.035       0
  5220.3    0.07       0  6103.0   0.035       0
Bank Sta=5000.7,5005.3
Exp/Cntr=0.3,0.1

Type RM Length L Ch R = 1,8659,474,474,474
BEGIN DESCRIPTION:
Buffalo Creek Trib 02-01 15.0
END DESCRIPTION:
XS GIS Cut Line= 3
      1333532.64      6944067.04      1334455.00      6945388.00
      1335416.33      6946237.19
#Sta/Elev= 30
  3389.1 2151.52  4024.5 2129.84  4073.3 2129.38  4087.4 2131.13  4117.0 2126.49
  4408.5 2117.58  4442.9 2116.57  4604.3 2112.77  4694.5 2110.33  4838.5 2107.57
  4936.1 2105.56  4957.0 2103.50  4971.9 2104.65  4992.8 2103.85  4997.2 2101.73
  5003.6 2101.73  5007.3 2103.32  5011.7 2100.78  5012.0 2100.28  5016.4 2100.78
  5035.8 2103.35  5047.7 2102.88  5212.8 2107.15  5332.2 2108.31  5347.5 2108.50
  5625.8 2110.38  5835.7 2116.20  6042.7 2120.50  6133.8 2122.80  6282.9 2127.05
#Mann=16,-1,0
  3389.1   0.035       0  4408.5    0.07       0  4442.9   0.035       0
  4604.3    0.07       0  4694.5   0.035       0  4838.5    0.07       0
  5011.7    0.07       0  5016.4    0.07       0  5047.7   0.035       0
  5212.8    0.07       0  5332.2   0.035       0  5347.5    0.07       0
  5625.8   0.035       0  5835.7    0.07       0  6042.7   0.035       0
  6133.8    0.07       0
Bank Sta=5011.7,5016.4
Exp/Cntr=0.3,0.1

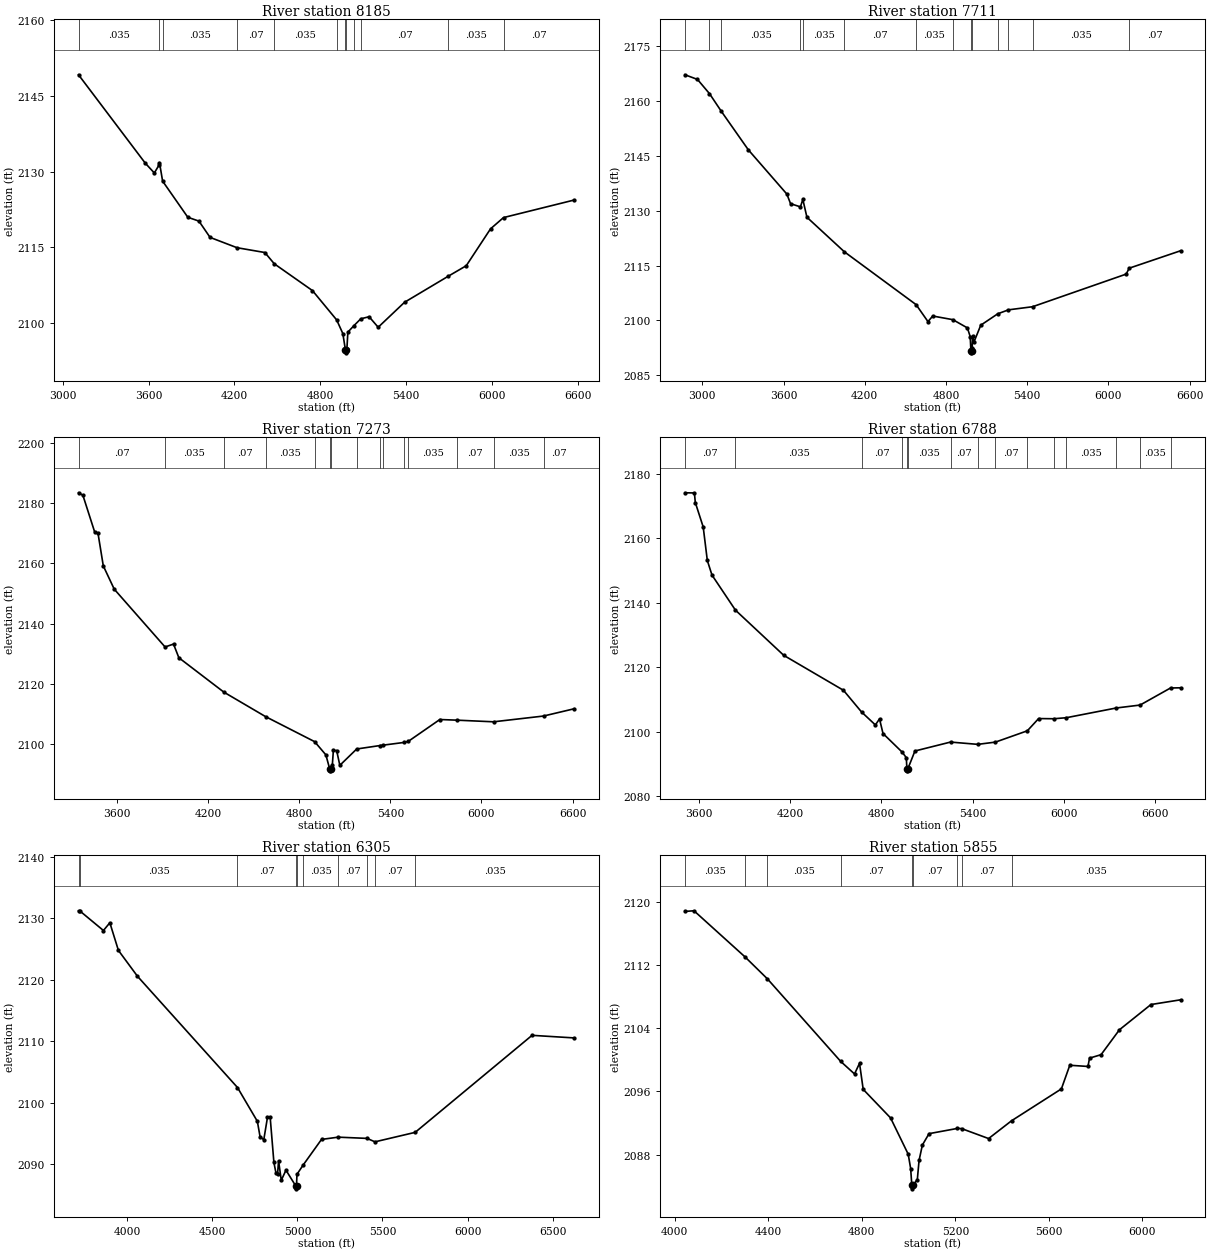
Type RM Length L Ch R = 1,8185,474,474,474
BEGIN DESCRIPTION:
Buffalo Creek Trib 02-01 14.0
END DESCRIPTION:
XS GIS Cut Line= 3
      1333003.13      6944370.86      1334255.00      6945788.00
      1335416.06      6946853.26
#Sta/Elev= 30
  3109.1 2149.14  3575.8 2131.67  3639.4 2129.72  3670.4 2131.20  3675.4 2131.78
  3697.3 2128.11  3873.6 2120.96  3951.4 2120.20  4029.2 2116.98  4217.8 2114.94
  4412.4 2113.99  4478.3 2111.76  4745.3 2106.46  4914.7 2100.66  4957.8 2097.96
  4976.3 2094.65  4976.6 2094.15  4981.1 2094.65  4986.2 2094.90  4992.9 2098.24
  5035.5 2099.53  5083.2 2100.88  5141.5 2101.29  5205.0 2099.21  5389.4 2104.15
  5695.5 2109.31  5821.0 2111.38  5990.7 2118.67  6081.5 2120.90  6575.7 2124.37
#Mann=12,-1,0
  3109.1   0.035       0  3670.4    0.07       0  3697.3   0.035       0
  4217.8    0.07       0  4478.3   0.035       0  4914.7    0.07       0
  4976.3    0.07       0  4981.1    0.07       0  5035.5   0.035       0
  5083.2    0.07       0  5695.5   0.035       0  6081.5    0.07       0
Bank Sta=4976.3,4981.1
Exp/Cntr=0.3,0.1

Type RM Length L Ch R = 1,7711,438,438,438
BEGIN DESCRIPTION:
Buffalo Creek Trib 02-01 13.0
END DESCRIPTION:
XS GIS Cut Line= 3
      1332630.01      6944463.01      1334005.00      6946088.00
      1335095.15      6947166.01
#Sta/Elev= 30
  2871.9 2167.18  2964.2 2165.91  3053.0 2162.02  3140.9 2157.16  3339.9 2146.66
  3624.5 2134.56  3651.9 2131.93  3724.8 2131.06  3742.6 2133.10  3772.8 2128.22
  4050.1 2118.75  4579.4 2104.32  4667.1 2099.68  4702.2 2101.21  4851.0 2100.21
  4958.3 2097.96  4979.1 2095.58  4984.4 2091.64  4984.8 2091.14  4989.3 2091.64
  4993.4 2092.57  4997.3 2095.62  5007.6 2094.17  5057.1 2098.70  5182.8 2101.82
  5261.9 2102.90  5439.8 2103.75  6131.9 2112.68  6153.1 2114.28  6533.7 2119.06
#Mann=14,-1,0
  2871.9   0.035       0  3053.0    0.07       0  3140.9   0.035       0
  3724.8    0.07       0  3742.6   0.035       0  4050.1    0.07       0
  4579.4   0.035       0  4851.0    0.07       0  4984.4    0.07       0
  4989.3    0.07       0  5182.8   0.035       0  5261.9    0.07       0
  5439.8   0.035       0  6153.1    0.07       0
Bank Sta=4984.4,4989.3
Exp/Cntr=0.3,0.1

Type RM Length L Ch R = 1,7273,485,485,485
BEGIN DESCRIPTION:
Buffalo Creek Trib 02-01 12.0
END DESCRIPTION:
XS GIS Cut Line= 3
      1332579.98      6944862.97      1333605.00      6946138.00
      1334704.97      6947337.97
#Sta/Elev= 30
  3346.5 2183.42  3375.3 2182.60  3453.7 2170.30  3474.5 2170.10  3509.7 2159.19
  3581.7 2151.48  3916.5 2132.32  3972.1 2133.28  4007.3 2128.75  4303.7 2117.35
  4577.9 2109.25  4901.3 2100.94  4975.3 2096.57  5001.2 2091.77  5001.5 2091.27
  5006.3 2091.77  5017.9 2093.22  5024.7 2098.02  5046.3 2098.00  5067.2 2093.09
  5178.3 2098.51  5328.7 2099.63  5353.7 2099.79  5492.7 2100.70  5517.6 2101.02
  5725.8 2108.28  5839.8 2108.06  6079.4 2107.52  6408.4 2109.43  6610.3 2111.84
#Mann=15,-1,0
  3346.5    0.07       0  3916.5   0.035       0  4303.7    0.07       0
  4577.9   0.035       0  4901.3    0.07       0  5001.2    0.07       0
  5006.3    0.07       0  5178.3   0.035       0  5328.7    0.07       0
  5353.7   0.035       0  5492.7    0.07       0  5517.6   0.035       0
  5839.8    0.07       0  6079.4   0.035       0  6408.4    0.07       0
Bank Sta=5001.2,5006.3
Exp/Cntr=0.3,0.1

Type RM Length L Ch R = 1,6788,483,483,483
BEGIN DESCRIPTION:
Buffalo Creek Trib 02-01 11.0
END DESCRIPTION:
XS GIS Cut Line= 3
      1332464.92      6945073.97      1333255.00      6946338.00
      1334480.03      6947613.03
#Sta/Elev= 30
  3509.4 2174.17  3571.4 2174.12  3577.3 2171.15  3629.2 2163.56  3656.3 2153.15
  3687.0 2148.62  3841.3 2137.73  4158.7 2123.71  4551.3 2112.86  4670.7 2106.10
  4761.2 2102.10  4788.4 2103.98  4811.4 2099.44  4937.5 2093.65  4964.7 2091.93
  4968.5 2088.35  4968.9 2087.85  4973.7 2088.35  5021.3 2094.01  5255.2 2096.78
  5434.8 2096.07  5550.6 2096.77  5760.4 2100.28  5834.5 2104.08  5934.6 2104.02
  6016.3 2104.34  6344.8 2107.36  6501.7 2108.27  6701.8 2113.57  6768.2 2113.63
#Mann=15,-1,0
  3509.4    0.07       0  3841.3   0.035       0  4670.7    0.07       0
  4937.5   0.035       0  4968.5   0.035       0  4973.7   0.035       0
  5255.2    0.07       0  5434.8   0.035       0  5550.6    0.07       0
  5760.4   0.035       0  5934.6    0.07       0  6016.3   0.035       0
  6344.8    0.07       0  6501.7   0.035       0  6701.8    0.07       0
Bank Sta=4968.5,4973.7
Exp/Cntr=0.3,0.1

Type RM Length L Ch R = 1,6305,450,450,450
BEGIN DESCRIPTION:
Buffalo Creek Trib 02-01 10.0
END DESCRIPTION:
XS GIS Cut Line= 3
      1331779.96      6945912.98      1332905.00      6946538.00
      1334029.98      6947712.98
#Sta/Elev= 30
  3713.1 2131.22  3719.7 2131.22  3859.6 2128.01  3897.3 2129.27  3947.7 2124.77
  4059.8 2120.56  4647.6 2102.46  4764.4 2096.96  4780.5 2094.43  4802.2 2093.96
  4823.9 2097.60  4839.9 2097.58  4861.7 2090.26  4874.3 2088.48  4883.4 2088.40
  4889.1 2090.55  4905.1 2087.36  4932.6 2089.01  4989.4 2086.47  4989.8 2085.97
  4994.7 2086.47  4997.2 2088.33  5033.6 2089.84  5141.5 2094.01  5239.4 2094.38
  5409.0 2094.18  5455.9 2093.62  5692.1 2095.16  6379.3 2110.95  6626.8 2110.53
#Mann=10,-1,0
  3713.1    0.07       0  3719.7   0.035       0  4647.6    0.07       0
  4989.4    0.07       0  4994.7    0.07       0  5033.6   0.035       0
  5239.4    0.07       0  5409.0   0.035       0  5455.9    0.07       0
  5692.1   0.035       0
Bank Sta=4989.4,4994.7
Exp/Cntr=0.3,0.1

Type RM Length L Ch R = 1,5855,481,481,481
BEGIN DESCRIPTION:
Buffalo Creek Trib 02-01 9.0
END DESCRIPTION:
XS GIS Cut Line= 3
      1331935.42      6946454.19      1332755.00      6946938.00
      1333630.01      6947713.00
#Sta/Elev= 30
  4043.4 2118.75  4082.0 2118.83  4300.5 2112.99  4396.4 2110.21  4709.5 2099.78
  4768.8 2098.19  4790.2 2099.54  4805.9 2096.24  4923.0 2092.63  4998.5 2088.04
  5008.9 2086.23  5013.8 2084.16  5014.2 2083.66  5019.1 2084.16  5037.4 2084.81
  5044.9 2087.25  5059.1 2089.20  5087.6 2090.64  5208.5 2091.30  5226.8 2091.28
  5342.4 2090.02  5440.6 2092.27  5653.8 2096.30  5689.8 2099.29  5767.5 2099.14
  5774.2 2100.19  5823.6 2100.63  5902.2 2103.78  6036.9 2106.97  6164.0 2107.57
#Mann=9,-1,0
  4043.4   0.035       0  4300.5    0.07       0  4396.4   0.035       0
  4709.5    0.07       0  5013.8    0.07       0  5019.1    0.07       0
  5208.5   0.035       0  5226.8    0.07       0  5440.6   0.035       0
Bank Sta=5013.8,5019.1
Exp/Cntr=0.3,0.1

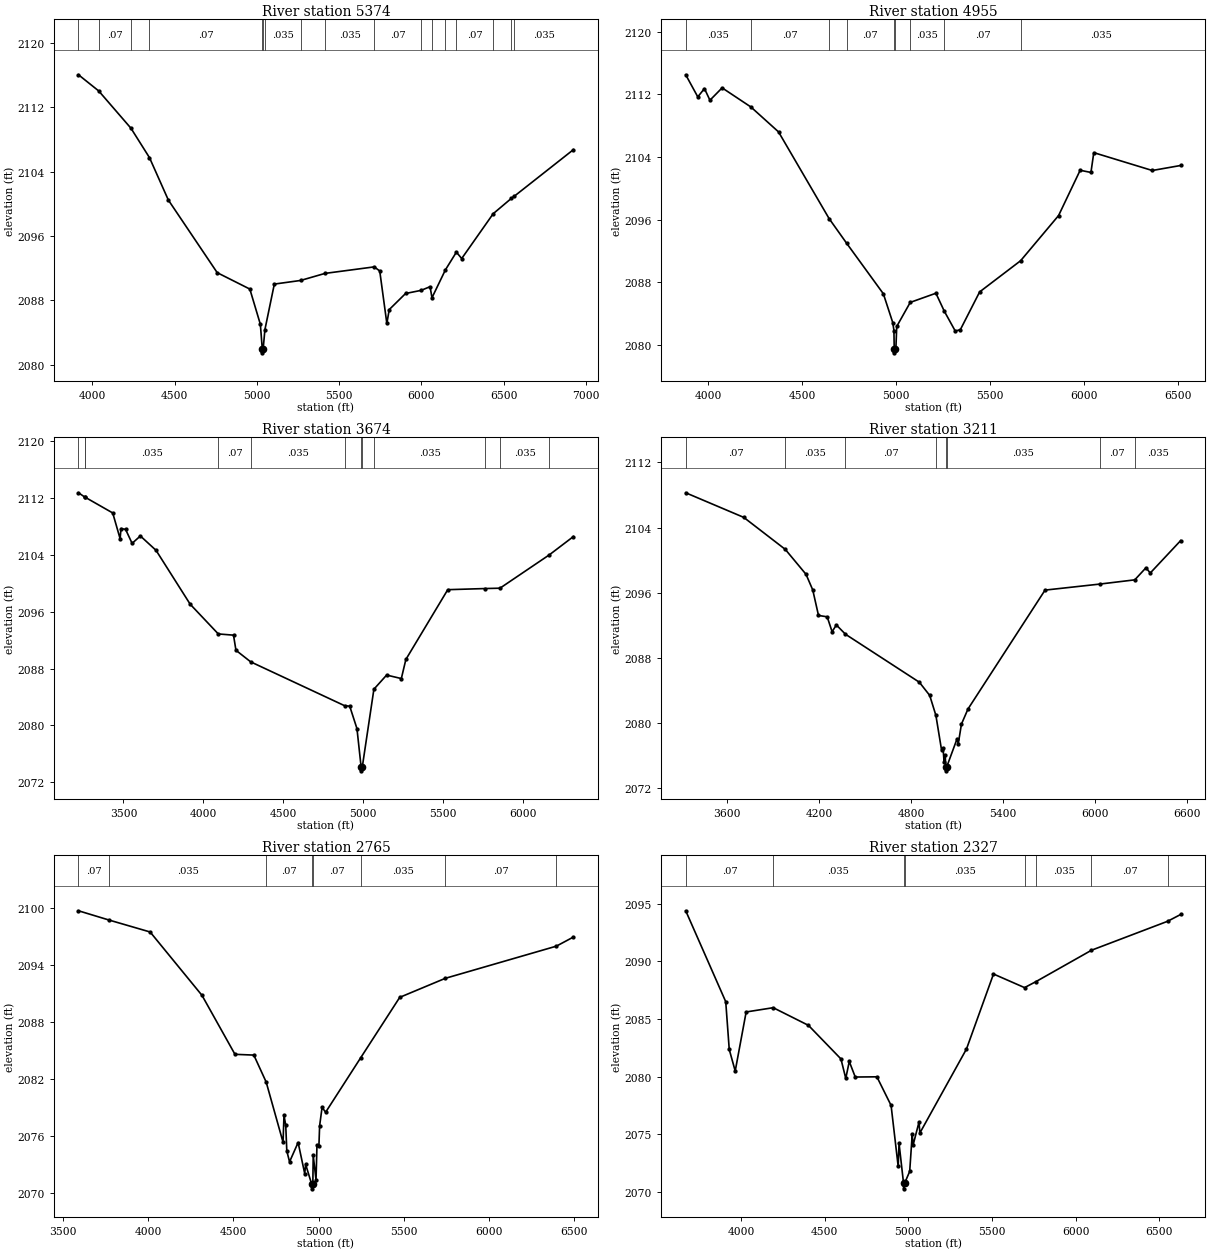
Type RM Length L Ch R = 1,5374,419,419,419
BEGIN DESCRIPTION:
Buffalo Creek Trib 02-01 8.0
END DESCRIPTION:
XS GIS Cut Line= 3
      1331866.00      6946645.18      1332655.00      6947388.00
      1333853.64      6948893.19
#Sta/Elev= 30
  3916.1 2116.05  4039.1 2114.04  4235.1 2109.40  4347.7 2105.74  4462.3 2100.47
  4759.2 2091.44  4957.5 2089.40  5021.4 2085.02  5033.0 2081.97  5033.5 2081.47
  5038.5 2081.97  5049.1 2084.36  5106.3 2090.02  5265.7 2090.47  5414.5 2091.35
  5713.5 2092.16  5746.9 2091.65  5790.1 2085.12  5804.6 2086.85  5903.9 2088.85
  5998.6 2089.24  6052.8 2089.70  6064.3 2088.32  6146.0 2091.79  6212.6 2093.99
  6245.0 2093.20  6436.3 2098.77  6546.2 2100.67  6565.3 2100.96  6923.9 2106.74
#Mann=17,-1,0
  3916.1   0.035       0  4039.1    0.07       0  4235.1   0.035       0
  4347.7    0.07       0  5033.0    0.07       0  5038.5    0.07       0
  5049.1   0.035       0  5265.7    0.07       0  5414.5   0.035       0
  5713.5    0.07       0  5998.6   0.035       0  6064.3    0.07       0
  6146.0   0.035       0  6212.6    0.07       0  6436.3   0.035       0
  6546.2    0.07       0  6565.3   0.035       0
Bank Sta=5033,5038.5
Exp/Cntr=0.3,0.1

Type RM Length L Ch R = 1,4955,1281,1281,1281
BEGIN DESCRIPTION:
Buffalo Creek Trib 02-01 7.0
END DESCRIPTION:
XS GIS Cut Line= 3
      1331692.39      6946740.69      1332355.00      6947638.00
      1333180.01      6948913.02
#Sta/Elev= 30
  3880.3 2114.48  3944.5 2111.66  3980.0 2112.72  4009.2 2111.23  4074.0 2112.81
  4227.1 2110.37  4374.2 2107.19  4643.4 2096.12  4736.4 2092.98  4932.1 2086.52
  4982.2 2082.84  4988.4 2081.83  4989.9 2079.48  4990.3 2078.98  4995.4 2079.48
  4998.7 2079.48  5003.3 2082.35  5075.2 2085.42  5211.8 2086.59  5256.6 2084.29
  5314.6 2081.77  5341.7 2081.93  5444.6 2086.76  5662.6 2090.74  5864.7 2096.51
  5979.5 2102.29  6036.9 2102.01  6052.0 2104.54  6363.3 2102.26  6514.4 2102.90
#Mann=9,-1,0
  3880.3   0.035       0  4227.1    0.07       0  4643.4   0.035       0
  4736.4    0.07       0  4989.9    0.07       0  4995.4    0.07       0
  5075.2   0.035       0  5256.6    0.07       0  5662.6   0.035       0
Bank Sta=4989.9,4995.4
Exp/Cntr=0.3,0.1

Type RM Length L Ch R = 1,3674,463,463,463
BEGIN DESCRIPTION:
Buffalo Creek Trib 02-01 6.0
END DESCRIPTION:
XS GIS Cut Line= 3
      1331570.85      6946810.12      1332305.00      6948438.00
      1333179.98      6949412.98
#Sta/Elev= 30
  3219.0 2112.75  3262.3 2112.09  3262.5 2112.10  3433.2 2109.91  3479.5 2106.28
  3485.0 2107.71  3513.6 2107.60  3554.4 2105.63  3606.1 2106.67  3704.1 2104.65
  3917.8 2097.06  4093.5 2092.88  4188.7 2092.71  4204.0 2090.58  4296.2 2088.95
  4883.4 2082.78  4915.6 2082.71  4960.9 2079.55  4987.1 2074.11  4987.6 2073.61
  4993.9 2074.11  5066.8 2085.10  5146.4 2087.09  5238.4 2086.60  5266.8 2089.29
  5528.8 2099.11  5763.5 2099.27  5855.4 2099.32  6164.5 2104.02  6314.8 2106.59
#Mann=12,-1,0
  3219.0   0.035       0  3262.3    0.07       0  3262.5   0.035       0
  4093.5    0.07       0  4296.2   0.035       0  4883.4    0.07       0
  4987.1    0.07       0  4993.9    0.07       0  5066.8   0.035       0
  5763.5    0.07       0  5855.4   0.035       0  6164.5    0.07       0
Bank Sta=4987.1,4993.9
Exp/Cntr=0.3,0.1

Type RM Length L Ch R = 1,3211,446,446,446
BEGIN DESCRIPTION:
Buffalo Creek Trib 02-01 5.0
END DESCRIPTION:
XS GIS Cut Line= 3
      1331119.46      6946914.28      1331905.00      6948388.00
      1333029.97      6949462.97
#Sta/Elev= 30
  3330.5 2108.27  3708.7 2105.25  3979.4 2101.32  4114.6 2098.26  4158.5 2096.34
  4195.9 2093.21  4252.6 2093.04  4284.6 2091.21  4312.3 2092.04  4371.9 2090.90
  4853.2 2085.01  4920.8 2083.39  4961.2 2080.93  4997.7 2076.72  5007.6 2076.95
  5014.5 2075.22  5021.7 2076.09  5025.2 2074.63  5025.7 2074.13  5032.0 2074.63
  5099.4 2078.08  5106.7 2077.44  5127.7 2079.87  5170.2 2081.72  5672.5 2096.32
  6029.4 2097.06  6257.4 2097.58  6330.1 2099.06  6358.4 2098.42  6556.5 2102.40
#Mann=8,-1,0
  3330.5    0.07       0  3979.4   0.035       0  4371.9    0.07       0
  4961.2   0.035       0  5025.2   0.035       0  5032.0   0.035       0
  6029.4    0.07       0  6257.4   0.035       0
Bank Sta=5025.2,5032
Exp/Cntr=0.3,0.1

Type RM Length L Ch R = 1,2765,438,438,438
BEGIN DESCRIPTION:
Buffalo Creek Trib 02-01 4.0
END DESCRIPTION:
XS GIS Cut Line= 3
      1331006.59      6947339.59      1331655.00      6948588.00
      1332830.02      6949513.02
#Sta/Elev= 30
  3592.0 2099.67  3772.3 2098.69  4012.2 2097.44  4316.2 2090.78  4509.6 2084.58
  4620.2 2084.50  4692.5 2081.67  4791.5 2075.34  4797.1 2078.16  4807.2 2077.15
  4813.6 2074.42  4829.7 2073.28  4879.9 2075.31  4918.5 2072.05  4924.2 2073.00
  4959.3 2070.94  4959.8 2070.44  4966.2 2070.94  4968.4 2073.96  4984.9 2071.39
  4990.5 2075.05  5001.9 2074.99  5006.0 2077.06  5020.4 2079.01  5041.2 2078.49
  5247.2 2084.23  5475.8 2090.57  5743.0 2092.57  6394.0 2095.95  6494.2 2096.91
#Mann=8,-1,0
  3592.0    0.07       0  3772.3   0.035       0  4692.5    0.07       0
  4959.3    0.07       0  4966.2    0.07       0  5247.2   0.035       0
  5743.0    0.07       0  6394.0   0.035       0
Bank Sta=4959.3,4966.2
Exp/Cntr=0.3,0.1

Type RM Length L Ch R = 1,2327,146,146,146
BEGIN DESCRIPTION:
Buffalo Creek Trib 02-01 3.0
END DESCRIPTION:
XS GIS Cut Line= 5
      1330563.88      6947955.92      1331421.41      6948554.64
      1331355.00      6948838.00      1331318.98      6948976.95
      1332629.98      6949662.99
#Sta/Elev= 30
  3668.6 2094.38  3907.9 2086.50  3928.9 2082.36  3964.6 2080.49  4030.0 2085.61
  4191.9 2085.98  4402.5 2084.45  4596.9 2081.54  4625.8 2079.85  4646.7 2081.32
  4682.5 2079.97  4811.9 2079.99  4896.8 2077.51  4939.3 2072.22  4944.4 2074.22
  4971.2 2070.78  4971.7 2070.28  4978.1 2070.78  5008.1 2071.79  5023.2 2075.00
  5028.4 2074.07  5063.8 2076.07  5069.0 2075.12  5347.7 2082.40  5509.3 2088.90
  5695.1 2087.72  5763.2 2088.24  6095.4 2090.96  6550.7 2093.47  6628.7 2094.06
#Mann=8,-1,0
  3668.6    0.07       0  4191.9   0.035       0  4971.2   0.035       0
  4978.1   0.035       0  5695.1    0.07       0  5763.2   0.035       0
  6095.4    0.07       0  6550.7   0.035       0
Bank Sta=4971.2,4978.1
Exp/Cntr=0.3,0.1

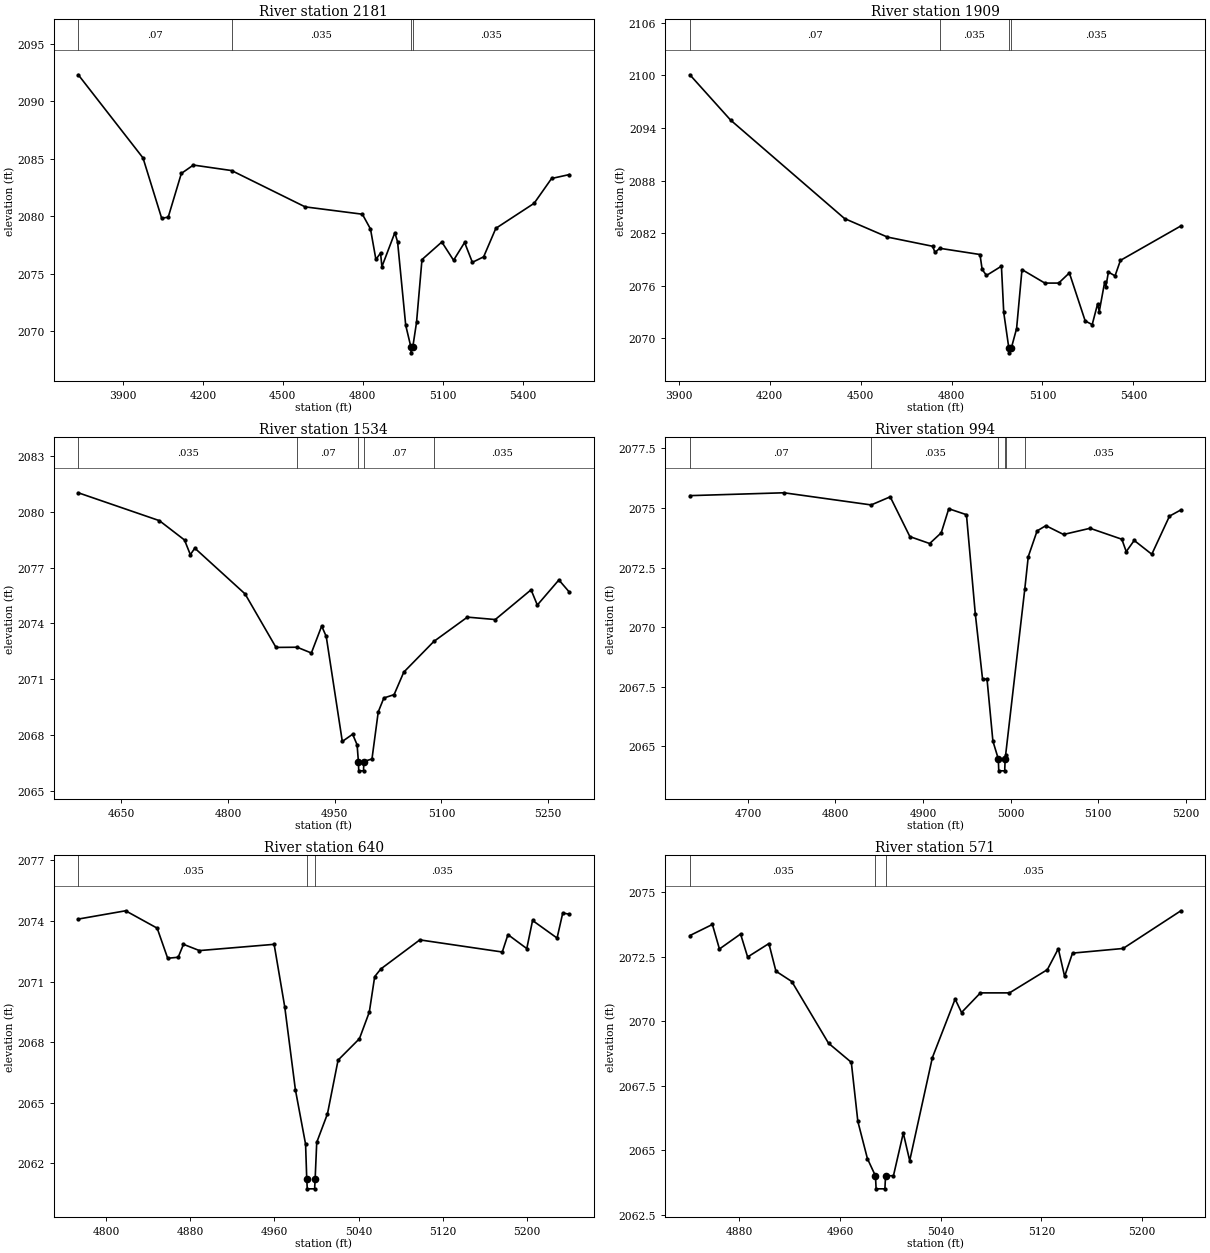
Type RM Length L Ch R = 1,2181,272,272,272
BEGIN DESCRIPTION:
Buffalo Creek Trib 02-01 2.5
END DESCRIPTION:
XS GIS Cut Line= 4
      1330468.63      6948245.88      1331304.88      6948527.73
      1331211.56      6949046.39      1331576.13      6949278.59
#Sta/Elev= 30
  3732.6 2092.31  3975.4 2085.07  4045.4 2079.82  4069.9 2079.91  4119.2 2083.72
  4164.3 2084.45  4307.8 2083.97  4583.5 2080.81  4798.2 2080.17  4828.7 2078.88
  4849.0 2076.23  4866.4 2076.79  4871.5 2075.60  4920.0 2078.56  4930.3 2077.76
  4960.8 2070.50  4980.3 2068.60  4980.8 2068.10  4987.3 2068.60  5001.4 2070.76
  5021.8 2076.22  5096.2 2077.75  5140.3 2076.16  5181.7 2077.71  5210.8 2075.98
  5253.1 2076.46  5298.8 2078.94  5442.5 2081.12  5507.9 2083.28  5574.3 2083.62
#Mann=4,-1,0
  3732.6    0.07       0  4307.8   0.035       0  4980.3   0.035       0
  4987.3   0.035       0
Bank Sta=4980.3,4987.3
Exp/Cntr=0.3,0.1

Type RM Length L Ch R = 1,1909,375,375,375
BEGIN DESCRIPTION:
Buffalo Creek Trib 02-01 2.0
END DESCRIPTION:
XS GIS Cut Line= 3
      1330255.00      6948388.00      1331055.00      6949088.00
      1331563.50      6949313.07
#Sta/Elev= 30
  3937.2 2100.07  4071.5 2094.90  4447.4 2083.66  4588.8 2081.55  4737.8 2080.50
  4745.4 2079.80  4761.1 2080.27  4893.9 2079.56  4901.0 2077.86  4915.3 2077.17
  4964.6 2078.23  4972.2 2072.95  4989.2 2068.84  4989.7 2068.34  4996.9 2068.84
  5014.6 2071.11  5032.4 2077.84  5107.7 2076.30  5153.3 2076.30  5188.6 2077.46
  5240.8 2071.98  5263.9 2071.56  5281.7 2073.92  5287.2 2073.05  5305.0 2076.41
  5309.0 2075.90  5317.4 2077.56  5339.2 2077.12  5357.0 2078.89  5556.3 2082.82
#Mann=4,-1,0
  3937.2    0.07       0  4761.1   0.035       0  4989.2   0.035       0
  4996.9   0.035       0
Bank Sta=4989.2,4996.9
Exp/Cntr=0.3,0.1

Type RM Length L Ch R = 1,1534,540,540,540
BEGIN DESCRIPTION:
Buffalo Creek Trib 02-01 1.5
END DESCRIPTION:
XS GIS Cut Line= 3
      1330580.01      6949163.01      1330898.21      6949409.98
      1331155.18      6949538.47
#Sta/Elev= 30
  4589.6 2081.03  4703.6 2079.53  4738.9 2078.49  4747.1 2077.70  4753.4 2078.05
  4824.0 2075.59  4867.5 2072.71  4897.2 2072.72  4917.2 2072.41  4931.7 2073.86
  4938.1 2073.30  4960.7 2067.65  4975.2 2068.04  4981.5 2067.47  4983.3 2066.57
  4983.8 2066.07  4990.5 2066.07  4991.0 2066.57  5002.4 2066.71  5011.2 2069.24
  5019.1 2069.99  5033.5 2070.17  5047.1 2071.38  5089.3 2073.03  5136.5 2074.34
  5175.7 2074.21  5226.0 2075.81  5234.8 2074.99  5265.1 2076.34  5279.7 2075.69
#Mann=5,-1,0
  4589.6   0.035       0  4897.2    0.07       0  4983.3    0.07       0
  4991.0    0.07       0  5089.3   0.035       0
Bank Sta=4983.3,4991
Exp/Cntr=0.3,0.1

Type RM Length L Ch R = 1,994,354,354,354
BEGIN DESCRIPTION:
Buffalo Creek Trib 02-01 1.0
END DESCRIPTION:
XS GIS Cut Line= 3
      1330518.36      6949800.77      1330776.40      6949926.55
      1331047.90      6949961.47
#Sta/Elev= 30
  4633.7 2075.52  4741.2 2075.64  4840.8 2075.13  4862.5 2075.47  4885.0 2073.80
  4907.6 2073.51  4920.8 2073.96  4929.4 2074.97  4949.6 2074.72  4959.7 2070.56
  4968.0 2067.82  4973.1 2067.82  4979.8 2065.22  4986.0 2064.47  4986.5 2063.97
  4993.3 2063.97  4993.8 2064.47  4994.4 2064.65  5016.2 2071.59  5020.2 2072.96
  5030.3 2074.04  5040.3 2074.26  5060.5 2073.89  5090.8 2074.15  5127.1 2073.69
  5132.1 2073.17  5141.2 2073.64  5161.3 2073.06  5181.5 2074.66  5194.5 2074.92
#Mann=6,-1,0
  4633.7    0.07       0  4840.8   0.035       0  4986.0    0.07       0
  4993.8   0.035       0  4994.4    0.07       0  5016.2   0.035       0
Bank Sta=4986,4993.8
Exp/Cntr=0.3,0.1

Type RM Length L Ch R = 1,640,69,69,69
BEGIN DESCRIPTION:
Buffalo Creek Trib 02-01 0.1
END DESCRIPTION:
XS GIS Cut Line= 4
      1330830.03      6950363.00      1330930.00      6950363.00
      1330967.50      6950139.70      1331024.22      6950011.27
#Sta/Elev= 30
  4773.5 2074.09  4818.5 2074.50  4848.5 2073.64  4858.5 2072.15  4868.5 2072.20
  4873.5 2072.84  4888.7 2072.53  4959.7 2072.84  4969.8 2069.74  4979.9 2065.65
  4989.6 2062.95  4990.7 2061.24  4991.2 2060.74  4998.2 2060.74  4998.7 2061.24
  5000.2 2063.04  5010.4 2064.45  5020.5 2067.11  5040.8 2068.17  5050.2 2069.49
  5055.3 2071.24  5061.1 2071.62  5098.2 2073.06  5176.6 2072.46  5182.0 2073.32
  5199.9 2072.63  5205.4 2074.02  5228.7 2073.15  5234.1 2074.39  5240.3 2074.33
#Mann=3,-1,0
  4773.5   0.035       0  4990.7   0.035       0  4998.7   0.035       0
Bank Sta=4990.7,4998.7
Exp/Cntr=0.3,0.1

Type RM Length L Ch R = 1,571,310,310,310
BEGIN DESCRIPTION:
Buffalo Creek Trib 02-01 0.9
END DESCRIPTION:
XS GIS Cut Line= 4
      1330962.08      6950399.01      1330997.88      6950326.33
      1331034.77      6950178.77      1331047.73      6950022.23
#Sta/Elev= 30
  4840.6 2073.32  4858.5 2073.75  4864.1 2072.80  4880.9 2073.38  4886.5 2072.49
  4903.4 2073.01  4909.0 2071.94  4921.6 2071.54  4950.8 2069.15  4968.9 2068.41
  4974.1 2066.12  4981.7 2064.68  4988.1 2064.01  4988.6 2063.51  4995.6 2063.51
  4996.1 2064.01  5002.4 2064.02  5010.2 2065.67  5015.3 2064.60  5033.3 2068.59
  5051.4 2070.86  5056.5 2070.34  5071.5 2071.10  5094.6 2071.10  5124.7 2072.00
  5133.4 2072.81  5138.4 2071.74  5144.7 2072.64  5184.9 2072.82  5230.8 2074.28
#Mann=3,-1,0
  4840.6   0.035       0  4988.1   0.035       0  4996.1   0.035       0
Bank Sta=4988.1,4996.1
Exp/Cntr=0.3,0.1

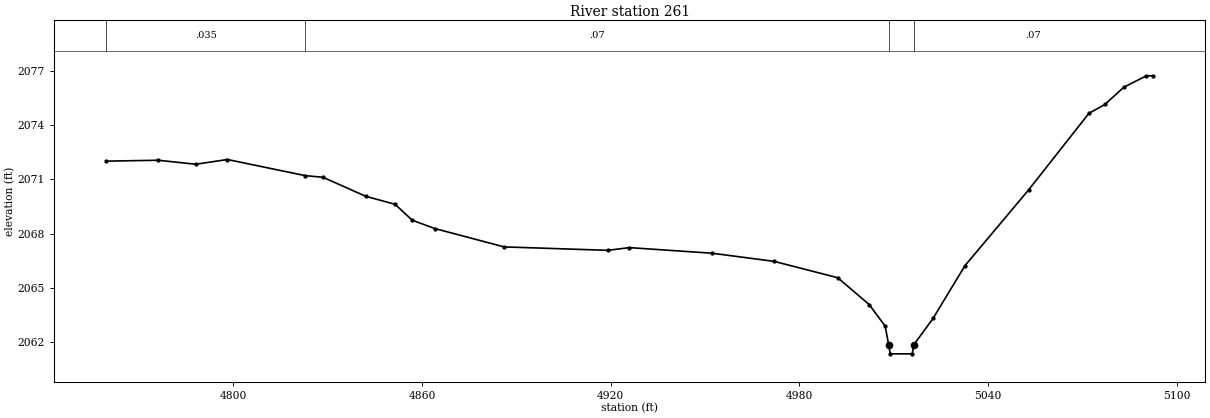
Type RM Length L Ch R = 1,261,0,0,0
BEGIN DESCRIPTION:
Buffalo Creek Trib 02-01 0.7
END DESCRIPTION:
XS GIS Cut Line= 3
      1330979.95      6950412.98      1331150.95      6950491.61
      1331294.21      6950470.65
#Sta/Elev= 30
  4759.5 2072.00  4776.1 2072.05  4788.0 2071.83  4798.1 2072.09  4822.9 2071.20
  4828.5 2071.11  4842.1 2070.06  4851.4 2069.62  4856.9 2068.74  4864.1 2068.28
  4886.1 2067.27  4919.1 2067.08  4925.9 2067.23  4952.3 2066.92  4972.0 2066.47
  4992.2 2065.57  5002.2 2064.09  5007.3 2062.90  5008.4 2061.87  5008.9 2061.37
  5015.9 2061.37  5016.4 2061.87  5022.5 2063.32  5032.7 2066.24  5052.9 2070.41
  5072.1 2074.64  5077.2 2075.13  5083.2 2076.08  5090.4 2076.71  5092.5 2076.71
#Mann=4,-1,0
  4759.5   0.035       0  4822.9    0.07       0  5008.4    0.07       0
  5016.4    0.07       0
Bank Sta=5008.4,5016.4
Exp/Cntr=0.3,0.1

Chan Stop Cuts=-1