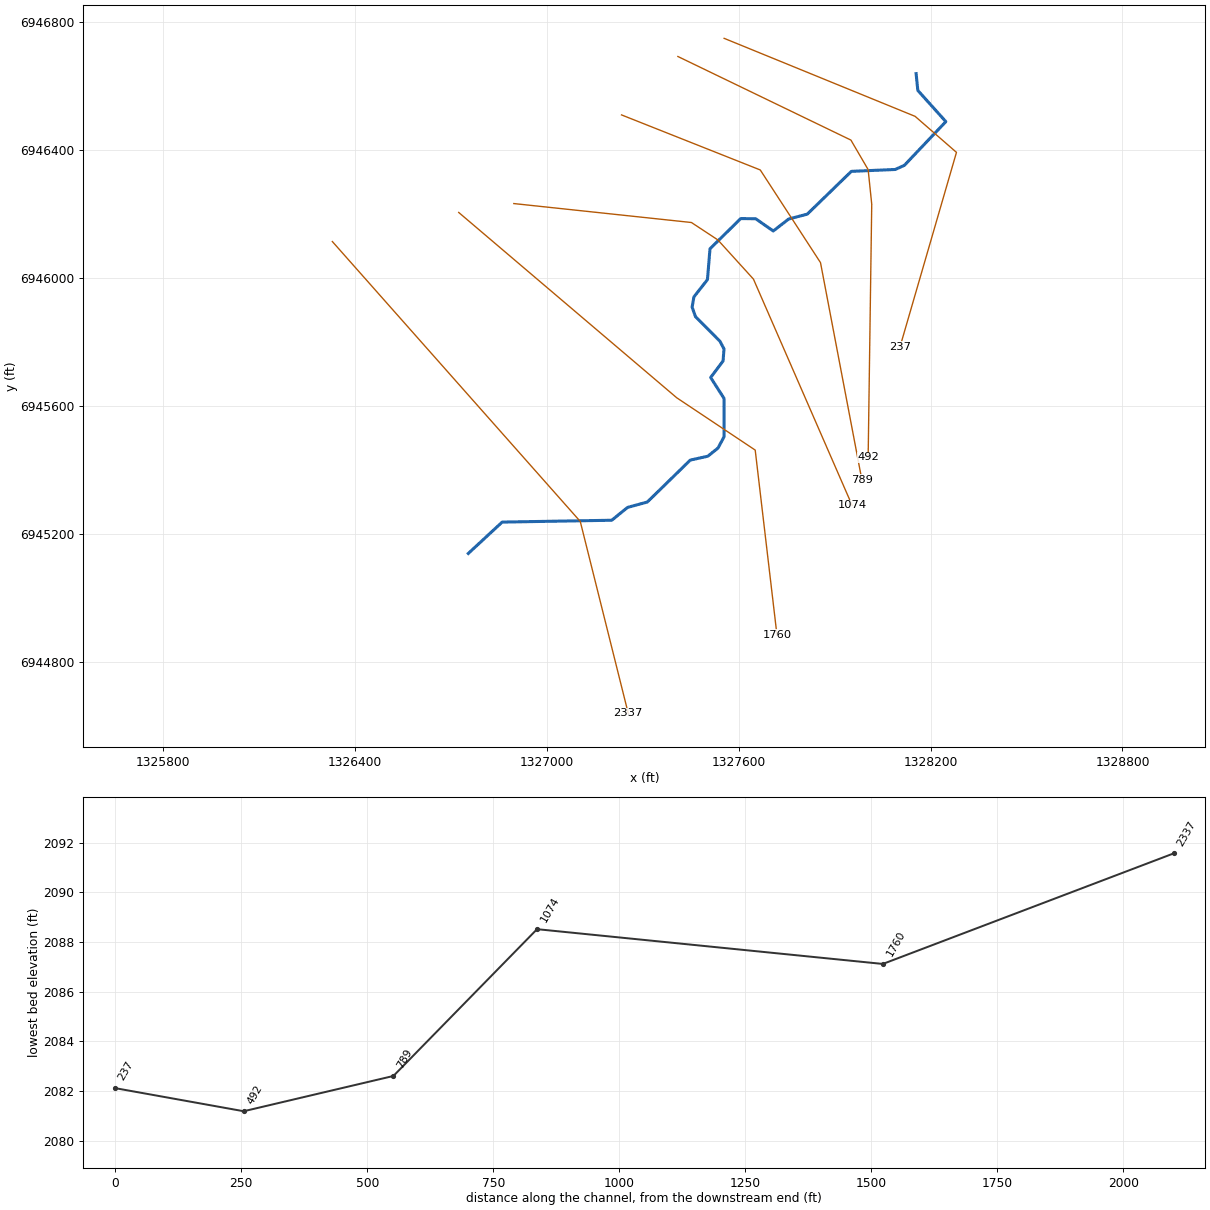
--- Buffalo Creek Trib 02-02.prj (project) ---

Proj Title=Buffalo Creek Trib 02-02 Base Level Engineering
Current Plan=p01
Default Exp/Contr=0.3,0.1
English Units
Geom File=g01
Flow File=f01
Plan File=p01
BEGIN DESCRIPTION:
Buffalo Creek Trib 02-02
END DESCRIPTION:

--- Buffalo Creek Trib 02-02.p01 (plan) ---

Plan Title=Multiple Run
Short Identifier=Multiple
Geom File=g01
Flow File=f01
Subcritical Flow
K Sum by GR= 0
Std Step Tol= 0.01
Critical Tol= 0.01
Num of Std Step Trials= 20
Max Error Tol= 0.3
Flow Tol Ratio= 0.001
Split Flow NTrial= 30
Split Flow Tol= 0.02
Split Flow Ratio= 0.02
Log Output Level= 0
Friction Slope Method= 1
Unsteady Friction Slope Method= 2
Unsteady Bridges Friction Slope Method= 1
Parabolic Critical Depth
Global Vel Dist=  1 , 1 , 1
Global Log Level= 0
CheckData=True
Encroach Param= -1, 0, 0, 0
BEGIN DESCRIPTION:
Multiple Run
END DESCRIPTION:

--- Buffalo Creek Trib 02-02.f01 (steady flow) ---

Flow Title=Multiple
Number of Profiles=7
Profile Names=10-year,25-year,50-year,1pct_min,100-year,1pct_plu,500-year
River Rch & RM= Buffalo Creek Tr,Reach-1,2337
     254     356     441     272     543    1084     833
Boundary for River Rch & Prof#=Buffalo Creek Tr,Reach-1,1
Up Type=0
Dn Type=3
Dn Slope=0.005
Boundary for River Rch & Prof#=Buffalo Creek Tr,Reach-1,2
Up Type=0
Dn Type=3
Dn Slope=0.005
Boundary for River Rch & Prof#=Buffalo Creek Tr,Reach-1,3
Up Type=0
Dn Type=3
Dn Slope=0.005
Boundary for River Rch & Prof#=Buffalo Creek Tr,Reach-1,4
Up Type=0
Dn Type=3
Dn Slope=0.005
Boundary for River Rch & Prof#=Buffalo Creek Tr,Reach-1,5
Up Type=0
Dn Type=3
Dn Slope=0.005
Boundary for River Rch & Prof#=Buffalo Creek Tr,Reach-1,6
Up Type=0
Dn Type=3
Dn Slope=0.005
Boundary for River Rch & Prof#=Buffalo Creek Tr,Reach-1,7
Up Type=0
Dn Type=3
Dn Slope=0.005

--- Buffalo Creek Trib 02-02.g01 (geometry) ---

Geom Title=Existing Conditions

River Reach=Buffalo Creek Tr,Reach-1
Reach XY= 30
      1326755.00      6945138.00      1326860.84      6945235.98
      1327203.45      6945241.75      1327252.83      6945281.86
      1327314.68      6945298.76      1327448.97      6945429.83
      1327503.60      6945441.87      1327535.56      6945467.45
      1327554.69      6945503.04      1327554.36      6945622.83
      1327512.59      6945688.01      1327551.42      6945739.65
      1327554.35      6945777.36      1327541.83      6945801.20
      1327465.21      6945878.32      1327454.61      6945908.13
      1327460.35      6945940.17      1327502.62      6945993.97
      1327510.52      6946090.44      1327606.63      6946184.85
      1327653.35      6946184.43      1327708.31      6946146.07
      1327756.65      6946183.55      1327814.68      6946198.75
      1327952.55      6946332.53      1328089.84      6946338.40
      1328118.32      6946351.37      1328247.94      6946488.00
      1328160.35      6946585.48      1328155.00      6946638.00

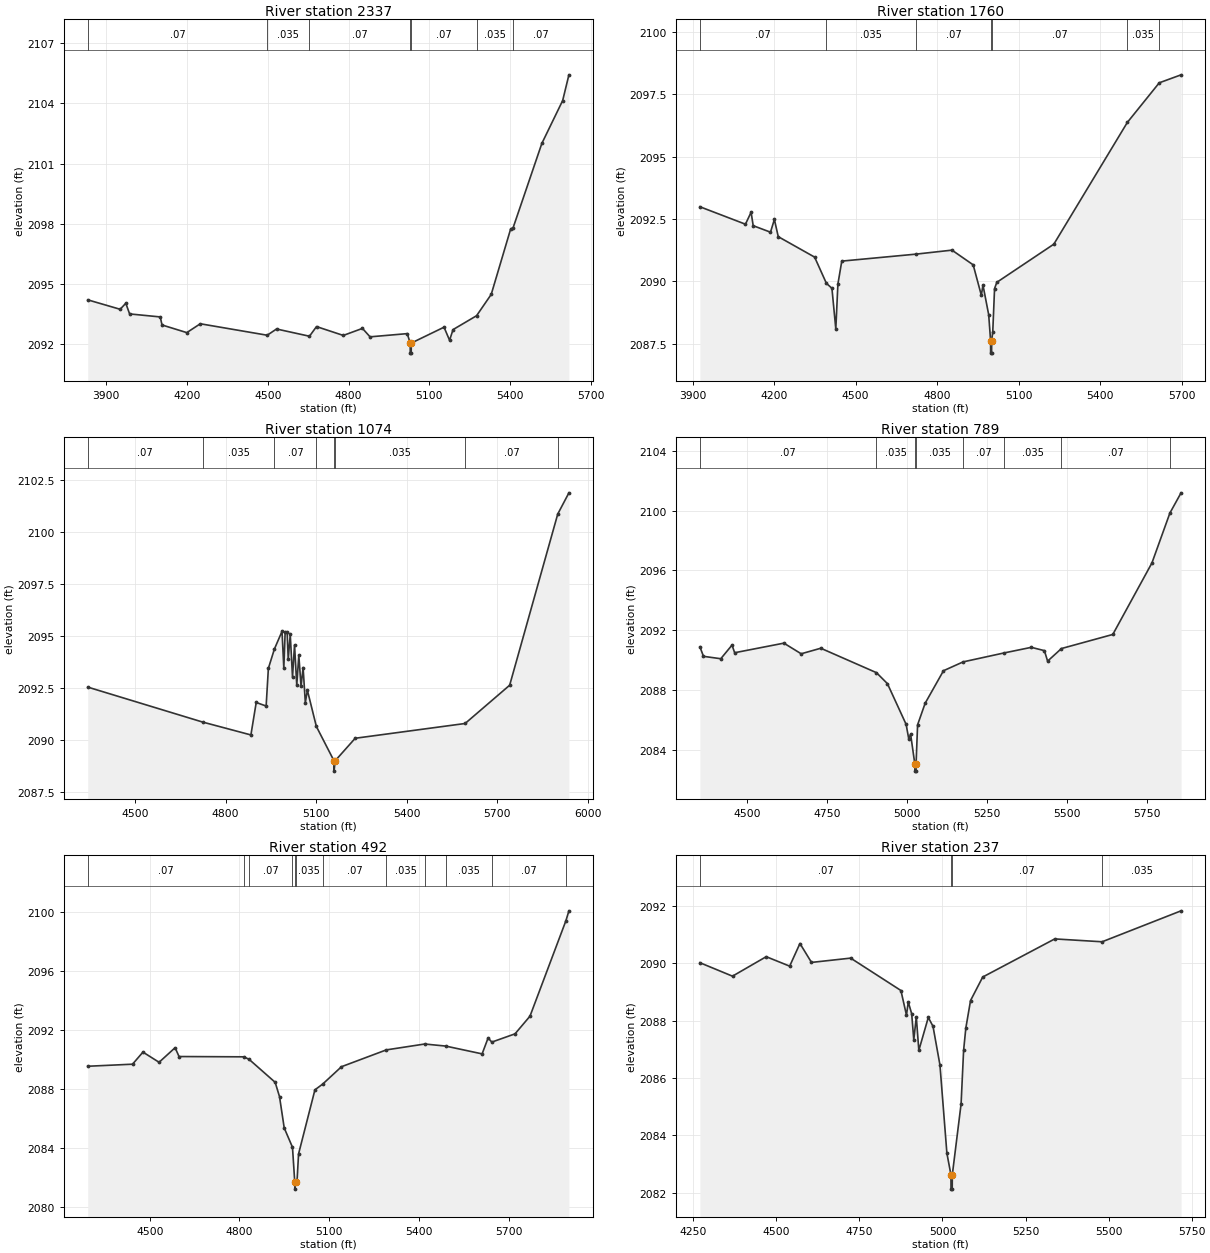
Type RM Length L Ch R = 1,2337,577,577,577
BEGIN DESCRIPTION:
Buffalo Creek Trib 02-02 3.0
END DESCRIPTION:
XS GIS Cut Line= 3
      1326329.97      6946113.03      1327105.00      6945238.00
      1327255.01      6944637.97
#Sta/Elev= 30
  3831.0 2094.22  3951.5 2093.75  3972.4 2094.05  3986.6 2093.52  4100.4 2093.37
  4107.0 2092.97  4199.0 2092.59  4249.2 2093.03  4497.7 2092.46  4532.4 2092.77
  4654.7 2092.41  4680.8 2092.89  4780.4 2092.45  4851.5 2092.80  4879.7 2092.38
  5017.9 2092.54  5028.8 2092.07  5029.1 2091.57  5032.6 2091.57  5032.8 2092.07
  5154.5 2092.86  5175.1 2092.21  5188.0 2092.74  5275.4 2093.43  5329.8 2094.49
  5401.9 2097.74  5411.0 2097.80  5517.9 2102.00  5595.2 2104.13  5618.4 2105.41
#Mann=7,-1,0
  3831.0    0.07       0  4497.7   0.035       0  4654.7    0.07       0
  5028.8    0.07       0  5032.8    0.07       0  5275.4   0.035       0
  5411.0    0.07       0
Bank Sta=5028.8,5032.8
Exp/Cntr=0.3,0.1

Type RM Length L Ch R = 1,1760,686,686,686
BEGIN DESCRIPTION:
Buffalo Creek Trib 02-02 2.5
END DESCRIPTION:
XS GIS Cut Line= 4
      1326724.97      6946204.03      1327406.57      6945624.67
      1327651.94      6945461.09      1327719.97      6944882.84
#Sta/Elev= 30
  3926.4 2092.99  4094.2 2092.29  4115.0 2092.77  4122.7 2092.23  4186.4 2091.97
  4200.7 2092.48  4215.0 2091.79  4348.9 2090.97  4392.2 2089.92  4412.6 2089.72
  4426.9 2088.09  4434.6 2089.89  4448.9 2090.81  4722.4 2091.09  4854.6 2091.25
  4932.7 2090.66  4962.7 2089.44  4968.7 2089.85  4989.8 2088.66  4996.8 2087.62
  4997.0 2087.12  5000.5 2087.12  5000.8 2087.62  5004.8 2087.98  5011.4 2089.71
  5019.8 2089.96  5229.7 2091.49  5500.2 2096.37  5617.8 2097.96  5698.1 2098.28
#Mann=7,-1,0
  3926.4    0.07       0  4392.2   0.035       0  4722.4    0.07       0
  4996.8    0.07       0  5000.8    0.07       0  5500.2   0.035       0
  5617.8    0.07       0
Bank Sta=4996.8,5000.8
Exp/Cntr=0.3,0.1

Type RM Length L Ch R = 1,1074,285,285,285
BEGIN DESCRIPTION:
Buffalo Creek Trib 02-02 2.0
END DESCRIPTION:
XS GIS Cut Line= 5
      1326897.15      6946231.83      1327452.52      6946172.60
      1327535.17      6946118.17      1327646.45      6945995.60
      1327955.01      6945287.98
#Sta/Elev= 30
  4343.1 2092.56  4723.7 2090.88  4884.0 2090.26  4901.6 2091.82  4934.5 2091.65
  4941.9 2093.46  4961.9 2094.39  4987.1 2095.24  4993.1 2093.47  4997.5 2095.20
  5004.1 2095.20  5007.7 2093.91  5014.4 2095.09  5021.9 2093.04  5028.6 2094.59
  5036.0 2092.65  5042.8 2094.09  5050.2 2092.60  5057.0 2093.50  5064.4 2091.81
  5071.2 2092.41  5100.9 2090.67  5159.3 2089.02  5159.6 2088.52  5163.4 2089.02
  5229.7 2090.10  5594.0 2090.81  5741.7 2092.65  5901.1 2100.88  5938.1 2101.90
#Mann=8,-1,0
  4343.1    0.07       0  4723.7   0.035       0  4961.9    0.07       0
  5100.9   0.035       0  5159.3    0.07       0  5163.4   0.035       0
  5594.0    0.07       0  5901.1   0.035       0
Bank Sta=5159.3,5163.4
Exp/Cntr=0.3,0.1

Type RM Length L Ch R = 1,789,297,297,297
BEGIN DESCRIPTION:
Buffalo Creek Trib 02-02 0.5
END DESCRIPTION:
XS GIS Cut Line= 4
      1327234.02      6946508.96      1327667.74      6946336.87
      1327856.06      6946047.15      1327985.28      6945368.60
#Sta/Elev= 30
  4353.6 2090.91  4364.9 2090.27  4418.9 2090.11  4454.0 2091.02  4462.2 2090.51
  4616.0 2091.15  4670.0 2090.44  4731.2 2090.81  4905.1 2089.18  4939.3 2088.45
  4997.8 2085.73  5005.8 2084.78  5011.8 2085.07  5024.8 2083.11  5025.1 2082.61
  5028.7 2082.61  5028.9 2083.11  5033.6 2085.70  5057.2 2087.14  5114.5 2089.31
  5175.9 2089.90  5302.4 2090.49  5388.8 2090.87  5429.6 2090.65  5439.7 2089.95
  5482.9 2090.79  5643.3 2091.73  5765.5 2096.50  5821.6 2099.83  5856.5 2101.18
#Mann=8,-1,0
  4353.6    0.07       0  4905.1   0.035       0  5024.8   0.035       0
  5028.9   0.035       0  5175.9    0.07       0  5302.4   0.035       0
  5482.9    0.07       0  5821.6   0.035       0
Bank Sta=5024.8,5028.9
Exp/Cntr=0.3,0.1

Type RM Length L Ch R = 1,492,255,255,255
BEGIN DESCRIPTION:
Buffalo Creek Trib 02-02 1.0
END DESCRIPTION:
XS GIS Cut Line= 5
      1327410.21      6946691.62      1327951.14      6946430.28
      1328005.00      6946338.00      1328016.24      6946229.76
      1328005.00      6945437.96
#Sta/Elev= 30
  4292.8 2089.53  4442.5 2089.67  4477.4 2090.49  4531.3 2089.80  4584.9 2090.79
  4598.0 2090.19  4814.6 2090.17  4832.1 2090.00  4919.3 2088.44  4933.8 2087.47
  4949.6 2085.34  4977.2 2084.03  4984.7 2081.69  4985.0 2081.19  4988.8 2081.69
  4992.5 2081.77  4997.5 2083.58  5052.2 2087.93  5078.1 2088.32  5141.0 2089.50
  5290.7 2090.64  5419.2 2091.04  5489.2 2090.90  5611.0 2090.37  5631.0 2091.45
  5643.4 2091.17  5721.0 2091.73  5771.0 2092.93  5891.1 2099.41  5901.1 2100.08
#Mann=12,-1,0
  4292.8    0.07       0  4814.6   0.035       0  4832.1    0.07       0
  4977.2   0.035       0  4984.7   0.035       0  4988.8   0.035       0
  5078.1    0.07       0  5290.7   0.035       0  5419.2    0.07       0
  5489.2   0.035       0  5643.4    0.07       0  5891.1   0.035       0
Bank Sta=4984.7,4988.8
Exp/Cntr=0.3,0.1

Type RM Length L Ch R = 1,237,0,0,0
BEGIN DESCRIPTION:
Buffalo Creek Trib 02-02 0.7
END DESCRIPTION:
XS GIS Cut Line= 4
      1327554.78      6946748.38      1328151.81      6946504.50
      1328281.13      6946391.88      1328104.92      6945784.84
#Sta/Elev= 30
  4269.7 2090.02  4367.9 2089.55  4469.4 2090.23  4540.0 2089.90  4570.9 2090.69
  4605.7 2090.03  4723.6 2090.18  4874.9 2089.05  4891.6 2088.19  4897.0 2088.65
  4907.3 2088.24  4913.6 2087.33  4921.2 2088.13  4928.8 2086.96  4957.3 2088.11
  4971.5 2087.80  4992.4 2086.45  5013.3 2083.37  5025.5 2082.62  5025.7 2082.12
  5029.3 2082.12  5029.6 2082.62  5056.0 2085.09  5063.6 2086.96  5070.3 2087.74
  5084.5 2088.70  5121.1 2089.52  5338.0 2090.85  5480.6 2090.75  5718.2 2091.83
#Mann=4,-1,0
  4269.7    0.07       0  5025.5    0.07       0  5029.6    0.07       0
  5480.6   0.035       0
Bank Sta=5025.5,5029.6
Exp/Cntr=0.3,0.1

Chan Stop Cuts=-1