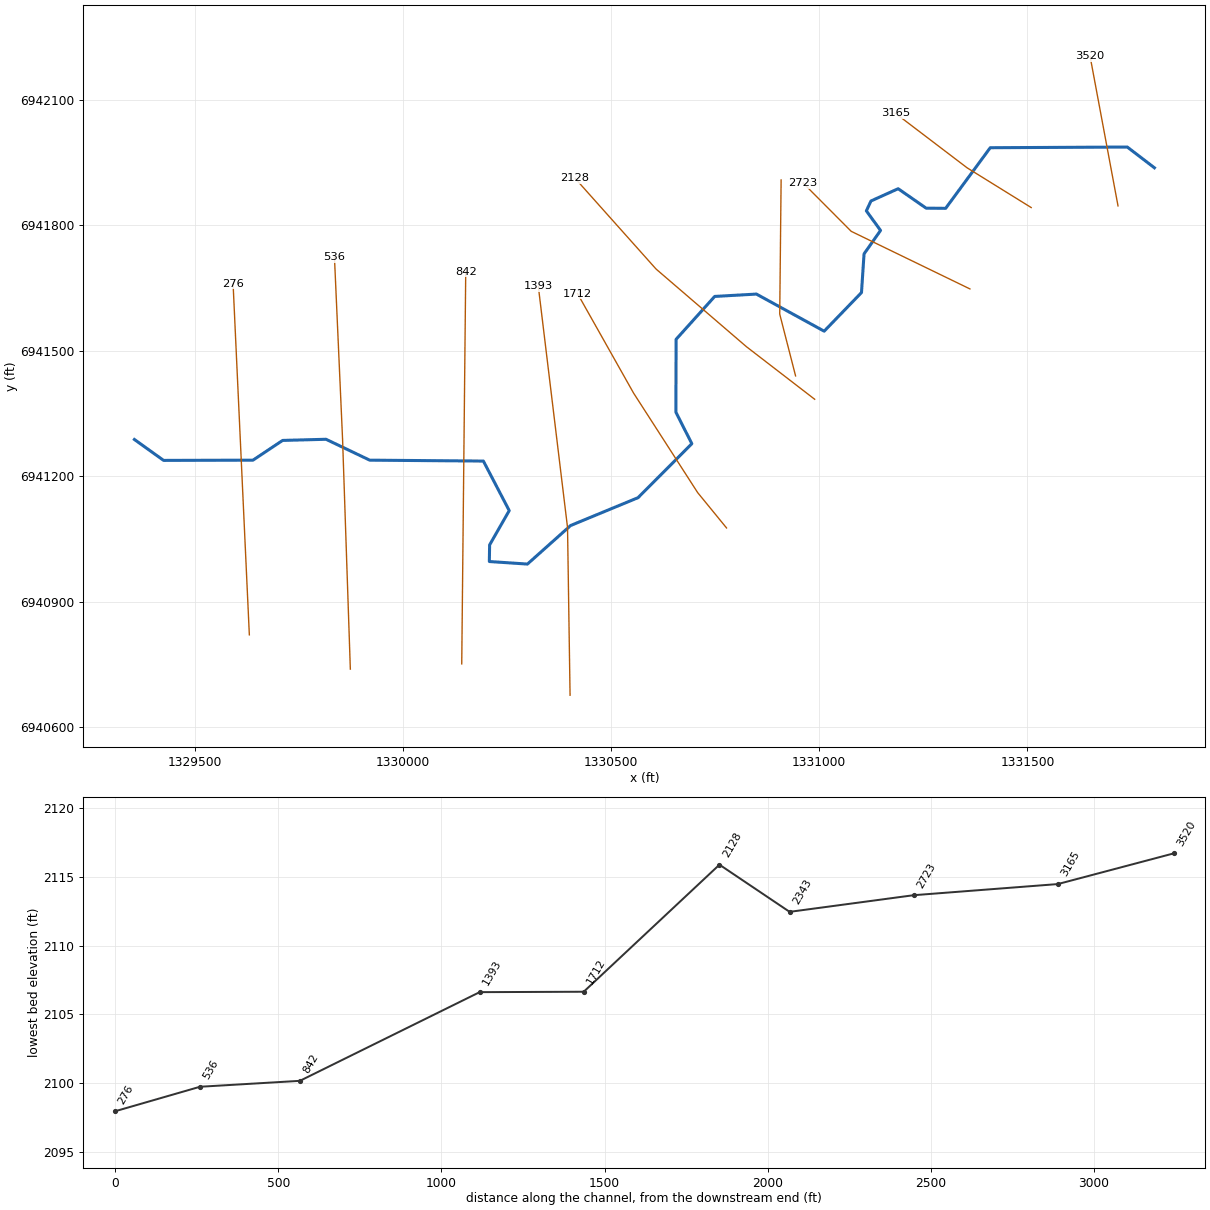
--- Buffalo Creek Trib 02-03.prj (project) ---

Proj Title=Buffalo Creek Trib 02-03 Base Level Engineering
Current Plan=p01
Default Exp/Contr=0.3,0.1
English Units
Geom File=g01
Flow File=f01
Plan File=p01
BEGIN DESCRIPTION:
Buffalo Creek Trib 02-03
END DESCRIPTION:

--- Buffalo Creek Trib 02-03.p01 (plan) ---

Plan Title=Multiple Run
Short Identifier=Multiple
Geom File=g01
Flow File=f01
Subcritical Flow
K Sum by GR= 0
Std Step Tol= 0.01
Critical Tol= 0.01
Num of Std Step Trials= 20
Max Error Tol= 0.3
Flow Tol Ratio= 0.001
Split Flow NTrial= 30
Split Flow Tol= 0.02
Split Flow Ratio= 0.02
Log Output Level= 0
Friction Slope Method= 1
Unsteady Friction Slope Method= 2
Unsteady Bridges Friction Slope Method= 1
Parabolic Critical Depth
Global Vel Dist=  1 , 1 , 1
Global Log Level= 0
CheckData=True
Encroach Param= -1, 0, 0, 0
BEGIN DESCRIPTION:
Multiple Run
END DESCRIPTION:

--- Buffalo Creek Trib 02-03.f01 (steady flow) ---

Flow Title=Multiple
Number of Profiles=7
Profile Names=10-year,25-year,50-year,1pct_min,100-year,1pct_plu,500-year
River Rch & RM= Buffalo Creek Tr,Reach-1,3520
     306     437     547     341     680    1357    1064
Boundary for River Rch & Prof#=Buffalo Creek Tr,Reach-1,1
Up Type=0
Dn Type=3
Dn Slope=0.005
Boundary for River Rch & Prof#=Buffalo Creek Tr,Reach-1,2
Up Type=0
Dn Type=3
Dn Slope=0.005
Boundary for River Rch & Prof#=Buffalo Creek Tr,Reach-1,3
Up Type=0
Dn Type=3
Dn Slope=0.005
Boundary for River Rch & Prof#=Buffalo Creek Tr,Reach-1,4
Up Type=0
Dn Type=3
Dn Slope=0.005
Boundary for River Rch & Prof#=Buffalo Creek Tr,Reach-1,5
Up Type=0
Dn Type=3
Dn Slope=0.005
Boundary for River Rch & Prof#=Buffalo Creek Tr,Reach-1,6
Up Type=0
Dn Type=3
Dn Slope=0.005
Boundary for River Rch & Prof#=Buffalo Creek Tr,Reach-1,7
Up Type=0
Dn Type=3
Dn Slope=0.005

--- Buffalo Creek Trib 02-03.g01 (geometry) ---

Geom Title=Existing Conditions

River Reach=Buffalo Creek Tr,Reach-1
Reach XY= 30
      1331805.00      6941938.00      1331739.85      6941987.64
      1331410.67      6941986.02      1331303.58      6941841.04
      1331256.76      6941841.36      1331189.47      6941887.95
      1331124.21      6941858.60      1331113.07      6941834.91
      1331147.19      6941788.11      1331107.55      6941732.11
      1331101.39      6941639.47      1331011.75      6941547.10
      1330849.03      6941635.86      1330748.81      6941630.25
      1330656.04      6941527.57      1330655.66      6941353.16
      1330693.90      6941277.94      1330564.68      6941148.76
      1330402.71      6941082.15      1330299.00      6940989.93
      1330207.50      6940996.03      1330208.19      6941035.82
      1330255.29      6941117.83      1330193.20      6941236.38
      1329920.22      6941238.52      1329815.17      6941288.50
      1329710.94      6941285.75      1329639.78      6941238.52
      1329424.99      6941237.98      1329355.00      6941288.00

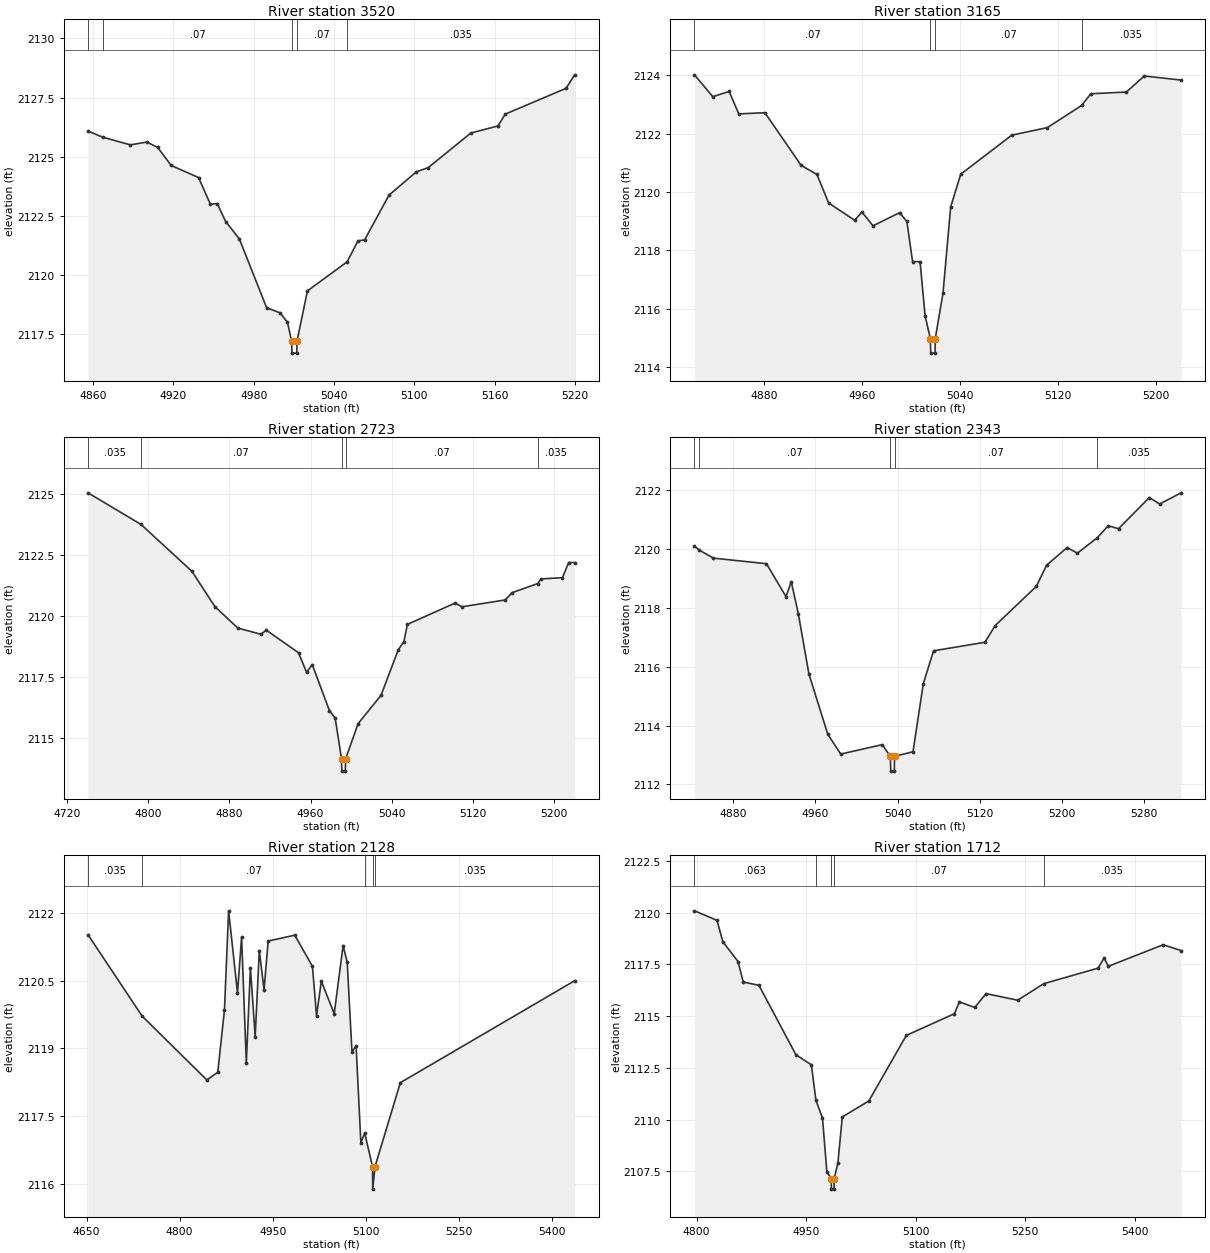
Type RM Length L Ch R = 1,3520,355,355,355
BEGIN DESCRIPTION:
Buffalo Creek Trib 02-03 6.0
END DESCRIPTION:
XS GIS Cut Line= 2
      1331717.56      6941846.83      1331650.54      6942204.30
#Sta/Elev= 30
  4856.1 2126.08  4867.4 2125.82  4887.8 2125.50  4900.1 2125.62  4908.2 2125.39
  4918.3 2124.63  4938.7 2124.12  4947.6 2122.99  4952.7 2123.02  4959.0 2122.26
  4969.2 2121.53  4989.6 2118.62  4999.7 2118.40  5005.2 2118.00  5008.3 2117.20
  5008.6 2116.70  5012.1 2116.70  5012.3 2117.20  5020.1 2119.33  5049.8 2120.56
  5057.8 2121.44  5062.9 2121.49  5081.1 2123.38  5101.5 2124.36  5110.4 2124.54
  5142.2 2126.00  5162.5 2126.30  5168.0 2126.80  5213.4 2127.89  5219.8 2128.46
#Mann=5,-1,0
  4856.1   0.035       0  4867.4    0.07       0  5008.3    0.07       0
  5012.3    0.07       0  5049.8   0.035       0
Bank Sta=5008.3,5012.3
Exp/Cntr=0.3,0.1

Type RM Length L Ch R = 1,3165,442,442,442
BEGIN DESCRIPTION:
Buffalo Creek Trib 02-03 5.0
END DESCRIPTION:
XS GIS Cut Line= 3
      1331509.06      6941842.86      1331355.00      6941938.00
      1331182.64      6942068.58
#Sta/Elev= 30
  4823.2 2124.02  4838.2 2123.27  4851.5 2123.45  4859.4 2122.68  4880.7 2122.72
  4910.2 2120.92  4923.2 2120.60  4932.8 2119.62  4954.0 2119.03  4959.9 2119.31
  4969.0 2118.84  4990.7 2119.29  4996.6 2118.99  5001.3 2117.61  5007.4 2117.61
  5011.5 2115.75  5015.8 2114.97  5016.1 2114.47  5019.6 2114.47  5019.8 2114.97
  5026.1 2116.52  5032.4 2119.49  5040.6 2120.61  5082.3 2121.95  5111.4 2122.21
  5139.3 2122.97  5146.8 2123.37  5175.9 2123.43  5190.4 2123.98  5220.5 2123.84
#Mann=4,-1,0
  4823.2    0.07       0  5015.8    0.07       0  5019.8    0.07       0
  5139.3   0.035       0
Bank Sta=5015.8,5019.8
Exp/Cntr=0.3,0.1

Type RM Length L Ch R = 1,2723,380,380,380
BEGIN DESCRIPTION:
Buffalo Creek Trib 02-03 5.5
END DESCRIPTION:
XS GIS Cut Line= 3
      1331361.88      6941648.20      1331076.77      6941785.95
      1330961.40      6941901.32
#Sta/Elev= 30
  4740.6 2125.04  4792.8 2123.75  4843.1 2121.83  4865.7 2120.39  4888.3 2119.51
  4910.9 2119.26  4916.5 2119.42  4948.2 2118.50  4956.1 2117.70  4961.7 2118.02
  4978.7 2116.13  4984.3 2115.83  4990.6 2114.16  4990.8 2113.66  4994.3 2113.66
  4994.6 2114.16  5006.9 2115.60  5029.5 2116.76  5046.5 2118.62  5052.1 2118.96
  5055.5 2119.66  5102.4 2120.53  5109.4 2120.38  5151.9 2120.66  5158.9 2120.96
  5184.0 2121.33  5187.2 2121.52  5208.4 2121.57  5214.5 2122.19  5220.4 2122.19
#Mann=5,-1,0
  4740.6   0.035       0  4792.8    0.07       0  4990.6    0.07       0
  4994.6    0.07       0  5184.0   0.035       0
Bank Sta=4990.6,4994.6
Exp/Cntr=0.3,0.1

Type RM Length L Ch R = 1,2343,215,215,215
BEGIN DESCRIPTION:
Buffalo Creek Trib 02-03 4.0
END DESCRIPTION:
XS GIS Cut Line= 3
      1330943.07      6941440.12      1330905.00      6941588.00
      1330908.36      6941908.88
#Sta/Elev= 30
  4842.3 2120.10  4847.1 2119.96  4860.8 2119.69  4912.4 2119.50  4931.4 2118.38
  4936.5 2118.89  4943.4 2117.80  4953.7 2115.75  4972.1 2113.70  4984.7 2113.03
  5025.0 2113.35  5033.0 2112.95  5033.3 2112.45  5036.8 2112.45  5037.0 2112.95
  5055.0 2113.11  5065.0 2115.42  5075.0 2116.54  5125.0 2116.83  5135.0 2117.40
  5175.0 2118.73  5185.0 2119.45  5205.0 2120.05  5215.0 2119.86  5233.9 2120.37
  5245.0 2120.79  5255.0 2120.69  5285.0 2121.75  5295.0 2121.53  5315.9 2121.91
#Mann=5,-1,0
  4842.3   0.035       0  4847.1    0.07       0  5033.0    0.07       0
  5037.0    0.07       0  5233.9   0.035       0
Bank Sta=5033,5037
Exp/Cntr=0.3,0.1

Type RM Length L Ch R = 1,2128,416,416,416
BEGIN DESCRIPTION:
Buffalo Creek Trib 02-03 2.5
END DESCRIPTION:
XS GIS Cut Line= 4
      1330988.95      6941384.24      1330824.89      6941510.10
      1330607.88      6941695.87      1330413.45      6941912.86
#Sta/Elev= 30
  4652.4 2121.52  4739.4 2119.72  4843.8 2118.30  4861.4 2118.47  4872.2 2119.85
  4878.9 2122.05  4893.2 2120.23  4899.8 2121.47  4907.4 2118.68  4914.0 2120.79
  4921.7 2119.26  4928.3 2121.17  4936.0 2120.30  4942.6 2121.38  4985.4 2121.51
  5013.9 2120.82  5020.5 2119.72  5028.2 2120.49  5049.0 2119.77  5063.3 2121.28
  5069.9 2120.91  5077.6 2118.92  5084.2 2119.06  5091.9 2116.91  5098.1 2117.12
  5110.7 2116.38  5111.0 2115.88  5114.7 2116.38  5155.5 2118.24  5436.2 2120.50
#Mann=5,-1,0
  4652.4   0.035       0  4739.4    0.07       0  5098.1   0.035       0
  5110.7    0.07       0  5114.7   0.035       0
Bank Sta=5110.7,5114.7
Exp/Cntr=0.3,0.1

Type RM Length L Ch R = 1,1712,319,319,319
BEGIN DESCRIPTION:
Buffalo Creek Trib 02-03 3.0
END DESCRIPTION:
XS GIS Cut Line= 4
      1330777.29      6941076.34      1330707.87      6941160.94
      1330553.96      6941399.02      1330419.37      6941636.96
#Sta/Elev= 30
  4797.0 2120.09  4827.9 2119.63  4835.8 2118.60  4856.6 2117.64  4863.8 2116.65
  4885.3 2116.49  4936.0 2113.13  4957.1 2112.65  4963.3 2110.93  4972.3 2110.08
  4978.3 2107.48  4984.3 2107.14  4984.5 2106.64  4988.0 2106.64  4988.3 2107.14
  4993.4 2107.90  4999.4 2110.13  5035.7 2110.90  5087.1 2114.07  5153.0 2115.12
  5159.7 2115.69  5180.8 2115.42  5196.2 2116.09  5239.5 2115.77  5275.3 2116.57
  5349.6 2117.32  5357.9 2117.81  5363.7 2117.41  5438.7 2118.45  5463.3 2118.17
#Mann=5,-1,0
  4797.0   0.063       0  4963.3    0.07       0  4984.3    0.07       0
  4988.3    0.07       0  5275.3   0.035       0
Bank Sta=4984.3,4988.3
Exp/Cntr=0.3,0.1

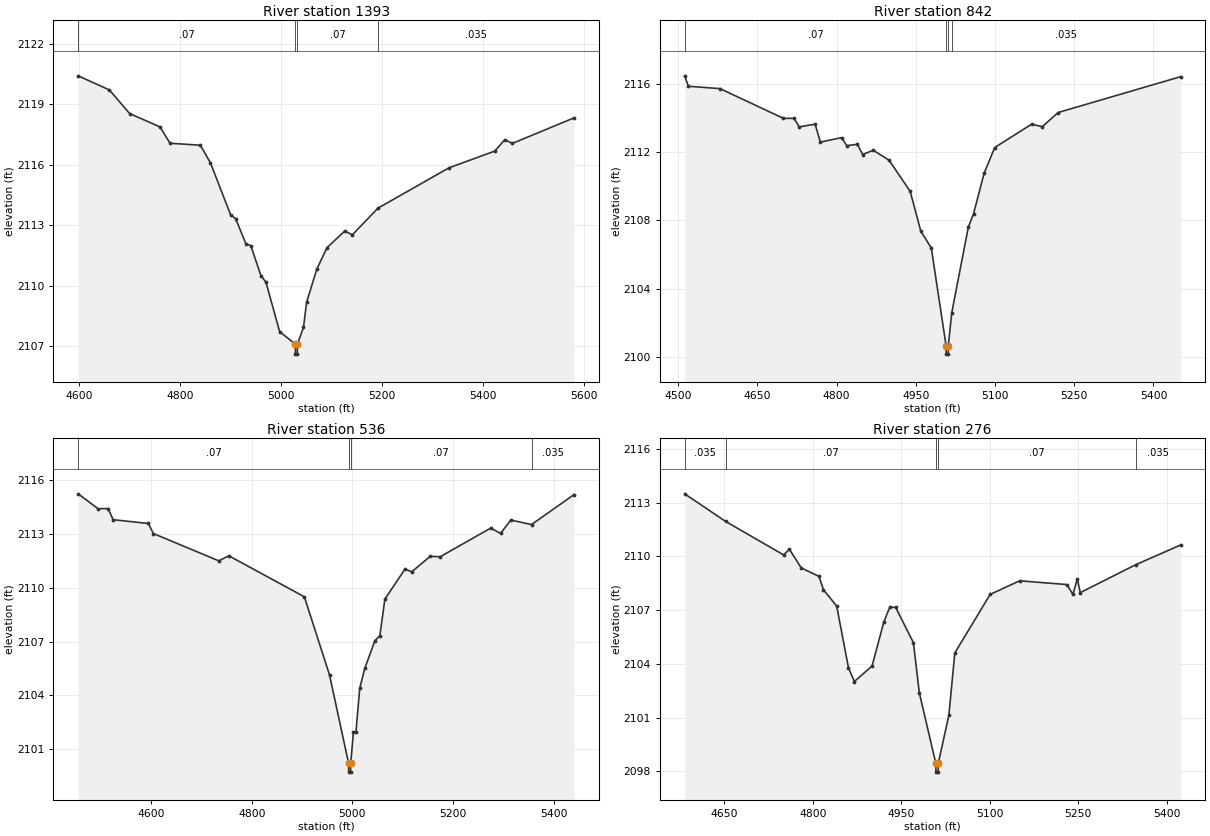
Type RM Length L Ch R = 1,1393,551,551,551
BEGIN DESCRIPTION:
Buffalo Creek Trib 02-03 2.0
END DESCRIPTION:
XS GIS Cut Line= 3
      1330401.42      6940676.16      1330395.33      6941077.21
      1330325.17      6941654.16
#Sta/Elev= 30
  4598.9 2120.40  4660.7 2119.70  4700.8 2118.53  4760.8 2117.87  4780.8 2117.06
  4840.8 2116.96  4860.8 2116.09  4900.8 2113.51  4910.8 2113.32  4930.8 2112.09
  4940.8 2111.98  4960.8 2110.50  4970.8 2110.17  4997.9 2107.72  5028.9 2107.11
  5029.2 2106.61  5032.9 2106.61  5033.1 2107.11  5045.1 2107.93  5051.2 2109.17
  5071.3 2110.81  5091.5 2111.88  5126.8 2112.71  5141.8 2112.52  5192.5 2113.84
  5333.2 2115.84  5423.9 2116.67  5444.0 2117.24  5458.8 2117.05  5581.2 2118.32
#Mann=4,-1,0
  4598.9    0.07       0  5028.9    0.07       0  5033.1    0.07       0
  5192.5   0.035       0
Bank Sta=5028.9,5033.1
Exp/Cntr=0.3,0.1

Type RM Length L Ch R = 1,842,306,306,306
BEGIN DESCRIPTION:
Buffalo Creek Trib 02-03 1.5
END DESCRIPTION:
XS GIS Cut Line= 2
      1330141.21      6940751.10      1330150.82      6941689.85
#Sta/Elev= 30
  4512.6 2116.46  4519.5 2115.85  4579.5 2115.71  4699.5 2113.97  4719.5 2113.97
  4729.5 2113.47  4759.5 2113.63  4769.5 2112.58  4809.5 2112.84  4819.5 2112.37
  4839.5 2112.45  4849.5 2111.85  4869.5 2112.10  4899.5 2111.52  4939.5 2109.69
  4959.5 2107.37  4979.5 2106.37  5007.4 2100.66  5007.7 2100.16  5011.4 2100.16
  5011.7 2100.66  5018.1 2102.57  5049.5 2107.59  5059.5 2108.39  5079.5 2110.76
  5099.5 2112.26  5169.5 2113.63  5189.5 2113.48  5219.5 2114.31  5451.4 2116.41
#Mann=4,-1,0
  4512.6    0.07       0  5007.4    0.07       0  5011.7    0.07       0
  5018.1   0.035       0
Bank Sta=5007.4,5011.7
Exp/Cntr=0.3,0.1

Type RM Length L Ch R = 1,536,260,260,260
BEGIN DESCRIPTION:
Buffalo Creek Trib 02-03 1.0
END DESCRIPTION:
XS GIS Cut Line= 3
      1329873.64      6940738.67      1329855.00      6941288.00
      1329835.48      6941723.92
#Sta/Elev= 30
  4455.0 2115.22  4494.4 2114.39  4514.4 2114.40  4524.4 2113.78  4594.4 2113.57
  4604.4 2113.01  4734.5 2111.49  4754.5 2111.77  4904.6 2109.49  4954.6 2105.14
  4992.5 2100.23  4992.8 2099.73  4996.5 2099.73  4996.8 2100.23  5002.1 2101.94
  5007.1 2101.94  5014.7 2104.39  5024.7 2105.50  5044.7 2107.04  5054.7 2107.32
  5064.7 2109.36  5104.7 2111.03  5118.1 2110.88  5154.8 2111.74  5174.8 2111.72
  5274.9 2113.31  5294.9 2113.02  5315.0 2113.76  5356.2 2113.51  5441.0 2115.18
#Mann=4,-1,0
  4455.0    0.07       0  4992.5    0.07       0  4996.8    0.07       0
  5356.2   0.035       0
Bank Sta=4992.5,4996.8
Exp/Cntr=0.3,0.1

Type RM Length L Ch R = 1,276,0,0,0
BEGIN DESCRIPTION:
Buffalo Creek Trib 02-03 0.5
END DESCRIPTION:
XS GIS Cut Line= 2
      1329631.05      6940820.62      1329591.99      6941660.52
#Sta/Elev= 30
  4582.6 2113.50  4651.9 2111.96  4750.2 2110.09  4760.2 2110.40  4780.2 2109.36
  4810.2 2108.89  4817.9 2108.14  4840.3 2107.23  4860.3 2103.78  4870.3 2103.01
  4900.3 2103.88  4920.3 2106.35  4930.4 2107.17  4940.4 2107.15  4970.4 2105.18
  4980.4 2102.38  5008.3 2098.45  5008.6 2097.95  5012.3 2097.95  5012.6 2098.45
  5030.5 2101.13  5040.6 2104.61  5100.5 2107.88  5150.6 2108.64  5230.7 2108.43
  5240.7 2107.88  5248.3 2108.74  5253.3 2107.98  5347.3 2109.54  5423.4 2110.64
#Mann=5,-1,0
  4582.6   0.035       0  4651.9    0.07       0  5008.3    0.07       0
  5012.6    0.07       0  5347.3   0.035       0
Bank Sta=5008.3,5012.6
Exp/Cntr=0.3,0.1

Chan Stop Cuts=-1