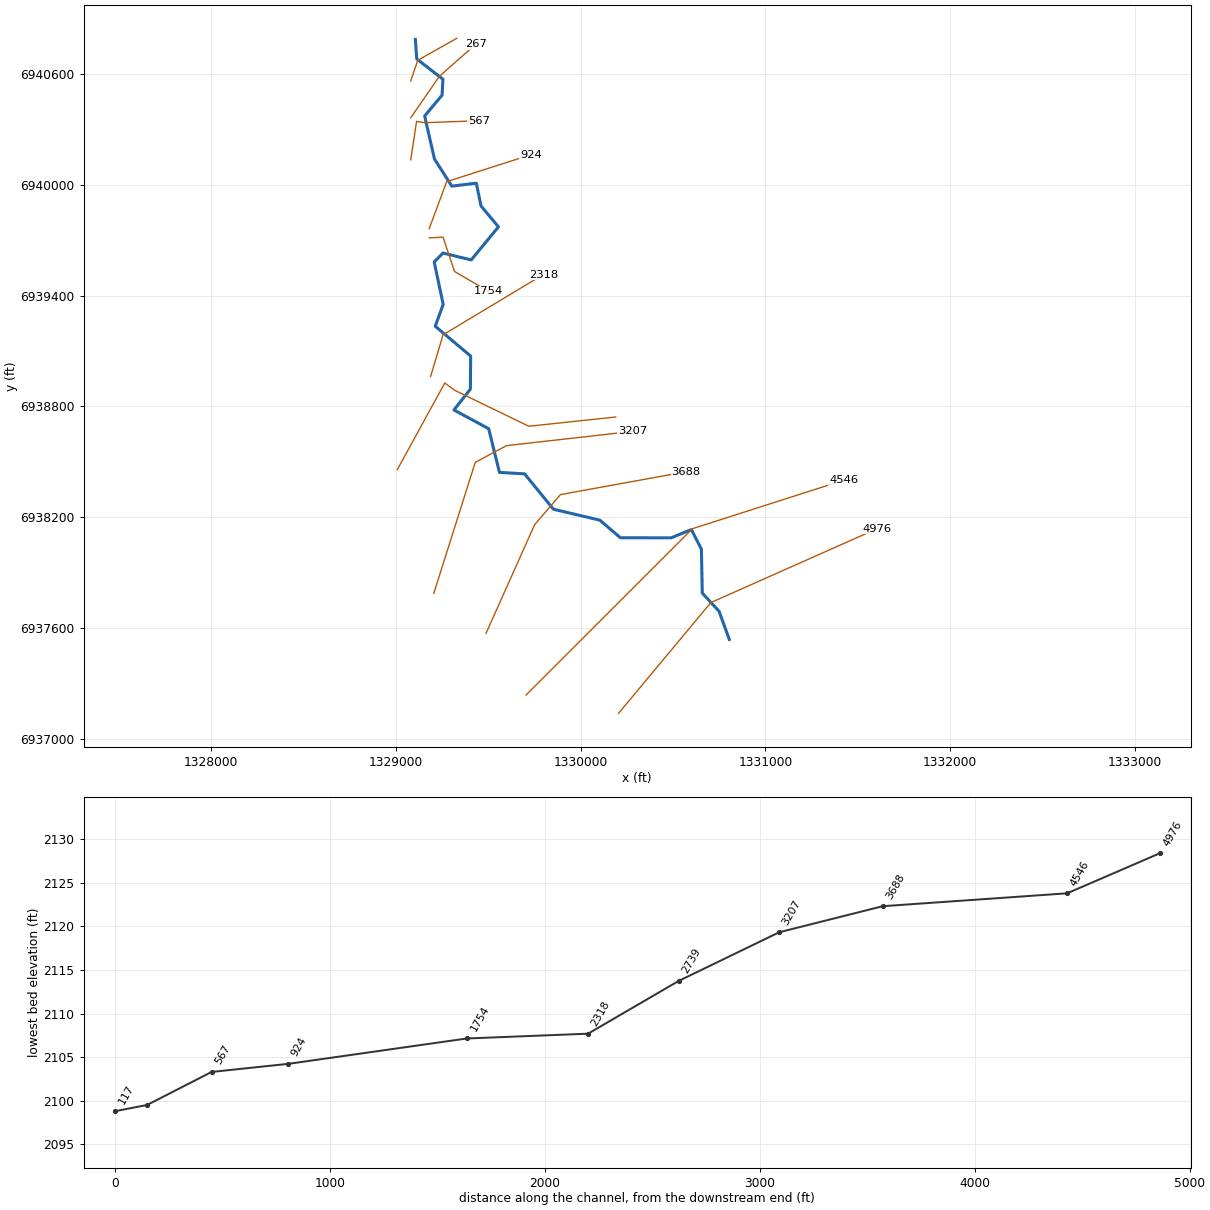
--- Buffalo Creek Trib 02-04.prj (project) ---

Proj Title=Buffalo Creek Trib 02-04 Base Level Engineering
Current Plan=p01
Default Exp/Contr=0.3,0.1
English Units
Geom File=g01
Flow File=f01
Plan File=p01
BEGIN DESCRIPTION:
Buffalo Creek Trib 02-04
END DESCRIPTION:

--- Buffalo Creek Trib 02-04.p01 (plan) ---

Plan Title=Multiple Run
Short Identifier=Multiple
Geom File=g01
Flow File=f01
Subcritical Flow
K Sum by GR= 0
Std Step Tol= 0.01
Critical Tol= 0.01
Num of Std Step Trials= 20
Max Error Tol= 0.3
Flow Tol Ratio= 0.001
Split Flow NTrial= 30
Split Flow Tol= 0.02
Split Flow Ratio= 0.02
Log Output Level= 0
Friction Slope Method= 1
Unsteady Friction Slope Method= 2
Unsteady Bridges Friction Slope Method= 1
Parabolic Critical Depth
Global Vel Dist=  1 , 1 , 1
Global Log Level= 0
CheckData=True
Encroach Param= -1, 0, 0, 0
BEGIN DESCRIPTION:
Multiple Run
END DESCRIPTION:

--- Buffalo Creek Trib 02-04.f01 (steady flow) ---

Flow Title=Multiple
Number of Profiles=7
Profile Names=10-year,25-year,50-year,1pct_min,100-year,1pct_plu,500-year
River Rch & RM= Buffalo Creek Tr,Reach-1,4976
     314     449     563     351     700    1397    1098
Boundary for River Rch & Prof#=Buffalo Creek Tr,Reach-1,1
Up Type=0
Dn Type=3
Dn Slope=0.005
Boundary for River Rch & Prof#=Buffalo Creek Tr,Reach-1,2
Up Type=0
Dn Type=3
Dn Slope=0.005
Boundary for River Rch & Prof#=Buffalo Creek Tr,Reach-1,3
Up Type=0
Dn Type=3
Dn Slope=0.005
Boundary for River Rch & Prof#=Buffalo Creek Tr,Reach-1,4
Up Type=0
Dn Type=3
Dn Slope=0.005
Boundary for River Rch & Prof#=Buffalo Creek Tr,Reach-1,5
Up Type=0
Dn Type=3
Dn Slope=0.005
Boundary for River Rch & Prof#=Buffalo Creek Tr,Reach-1,6
Up Type=0
Dn Type=3
Dn Slope=0.005
Boundary for River Rch & Prof#=Buffalo Creek Tr,Reach-1,7
Up Type=0
Dn Type=3
Dn Slope=0.005

--- Buffalo Creek Trib 02-04.g01 (geometry) ---

Geom Title=Existing Conditions

River Reach=Buffalo Creek Tr,Reach-1
Reach XY= 30
      1330805.00      6937538.00      1330749.48      6937690.43
      1330658.55      6937789.47      1330653.81      6938027.53
      1330599.42      6938133.24      1330489.80      6938088.54
      1330215.44      6938089.06      1330103.52      6938184.44
      1329852.63      6938243.54      1329696.69      6938434.92
      1329560.42      6938443.18      1329501.93      6938679.72
      1329313.84      6938781.05      1329402.93      6938893.85
      1329404.62      6939072.85      1329212.69      6939234.33
      1329255.69      6939353.05      1329207.04      6939582.55
      1329254.65      6939630.78      1329407.43      6939593.40
      1329555.10      6939772.64      1329460.54      6939885.58
      1329435.39      6940009.09      1329302.46      6939993.01
      1329208.82      6940139.58      1329155.25      6940372.78
      1329249.61      6940485.64      1329254.48      6940572.11
      1329112.73      6940681.76      1329105.00      6940788.00

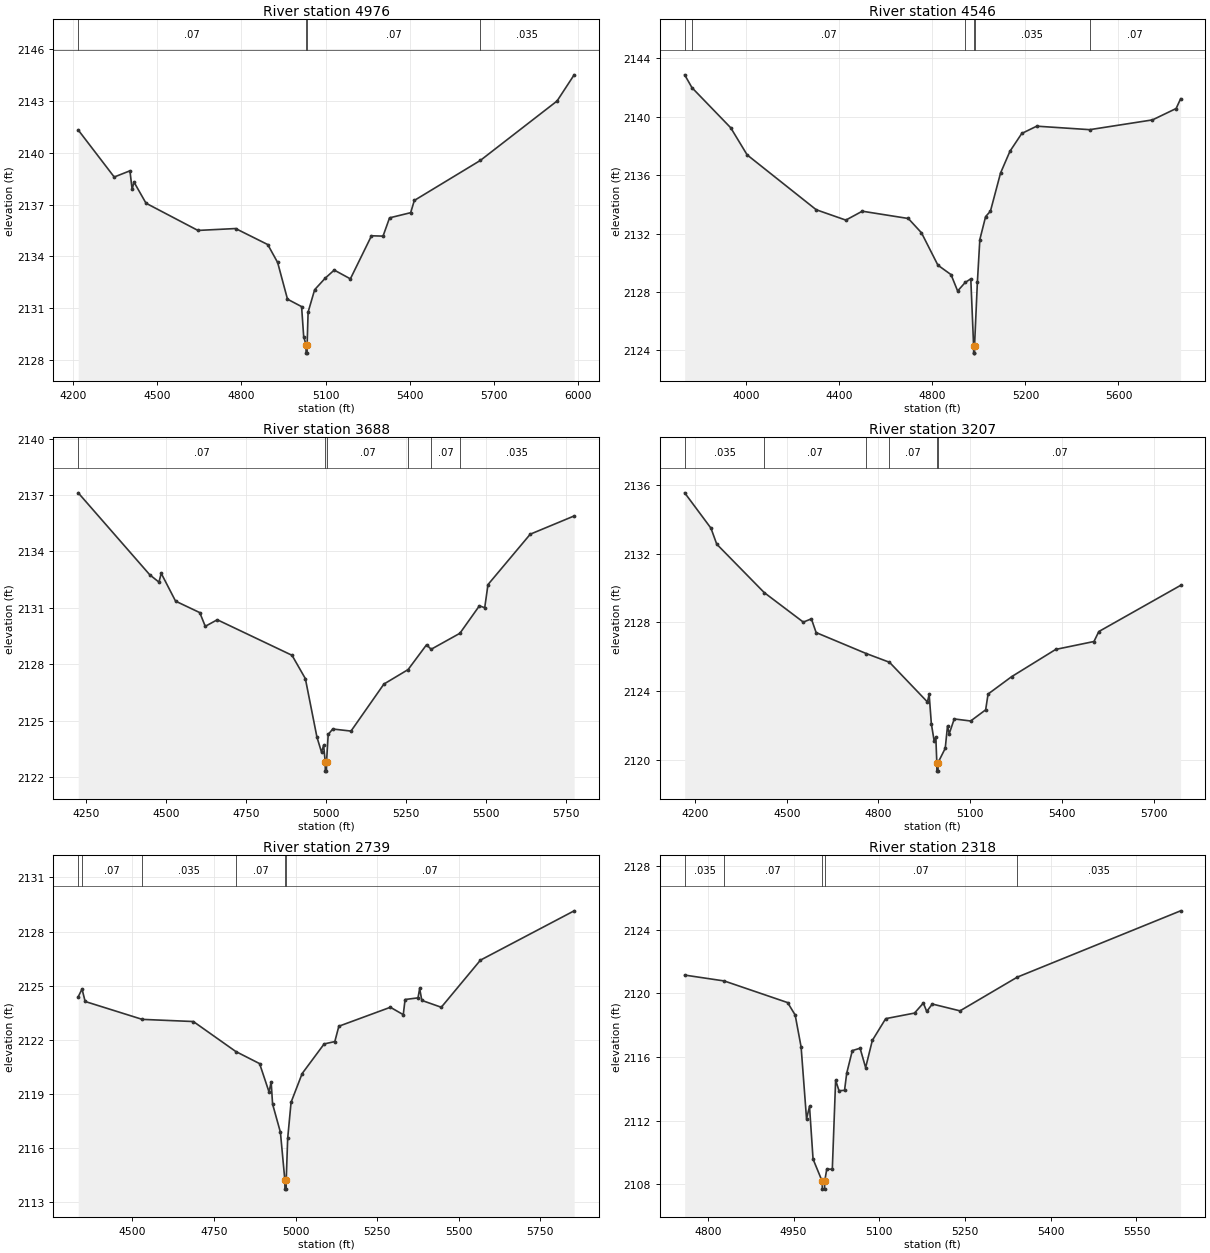
Type RM Length L Ch R = 1,4976,430,430,430
BEGIN DESCRIPTION:
Buffalo Creek Trib 02-04 5.0
END DESCRIPTION:
XS GIS Cut Line= 3
      1330205.02      6937138.02      1330705.00      6937738.00
      1331605.02      6938138.01
#Sta/Elev= 30
  4219.0 2141.33  4347.2 2138.60  4403.2 2138.96  4411.0 2137.88  4417.5 2138.31
  4460.4 2137.08  4645.3 2135.50  4779.4 2135.61  4893.9 2134.68  4929.1 2133.64
  4964.2 2131.51  5014.4 2131.08  5021.9 2129.33  5030.1 2128.88  5030.4 2128.38
  5033.9 2128.38  5034.1 2128.88  5037.6 2130.76  5060.9 2132.06  5098.5 2132.73
  5130.6 2133.20  5188.1 2132.69  5263.3 2135.19  5304.4 2135.17  5327.6 2136.23
  5402.8 2136.53  5415.8 2137.24  5650.7 2139.56  5924.0 2143.01  5984.9 2144.53
#Mann=4,-1,0
  4219.0    0.07       0  5030.1    0.07       0  5034.1    0.07       0
  5650.7   0.035       0
Bank Sta=5030.1,5034.1
Exp/Cntr=0.3,0.1

Type RM Length L Ch R = 1,4546,858,858,858
BEGIN DESCRIPTION:
Buffalo Creek Trib 02-04 4.0
END DESCRIPTION:
XS GIS Cut Line= 3
      1329704.99      6937237.99      1330605.00      6938138.00
      1331423.90      6938400.33
#Sta/Elev= 30
  3734.6 2142.88  3765.9 2142.00  3932.6 2139.25  4003.3 2137.39  4300.3 2133.63
  4427.6 2132.92  4498.3 2133.53  4696.3 2133.03  4752.9 2132.05  4823.6 2129.83
  4880.1 2129.18  4908.4 2128.06  4941.2 2128.65  4965.0 2128.89  4977.1 2124.30
  4977.4 2123.80  4980.9 2123.80  4981.1 2124.30  4993.3 2128.66  5003.9 2131.59
  5028.7 2133.16  5049.4 2133.53  5093.0 2136.15  5133.4 2137.64  5184.2 2138.86
  5248.5 2139.36  5476.4 2139.12  5746.3 2139.79  5848.0 2140.57  5867.3 2141.24
#Mann=6,-1,0
  3734.6   0.035       0  3765.9    0.07       0  4941.2   0.035       0
  4977.1   0.035       0  4981.1   0.035       0  5476.4    0.07       0
Bank Sta=4977.1,4981.1
Exp/Cntr=0.3,0.1

Type RM Length L Ch R = 1,3688,481,481,481
BEGIN DESCRIPTION:
Buffalo Creek Trib 02-04 3.5
END DESCRIPTION:
XS GIS Cut Line= 4
      1329487.52      6937571.25      1329750.90      6938159.97
      1329890.33      6938322.64      1330569.97      6938446.26
#Sta/Elev= 30
  4226.2 2137.12  4449.9 2132.76  4478.6 2132.37  4485.6 2132.84  4530.5 2131.36
  4606.1 2130.75  4623.3 2130.02  4660.8 2130.37  4894.4 2128.48  4936.1 2127.24
  4972.3 2124.13  4986.6 2123.33  4993.2 2123.69  4998.2 2122.82  4998.5 2122.32
  5002.0 2122.32  5002.3 2122.82  5007.5 2124.27  5021.7 2124.56  5078.8 2124.45
  5181.6 2126.95  5257.2 2127.72  5314.9 2129.04  5329.2 2128.80  5419.1 2129.65
  5480.0 2131.11  5496.7 2131.01  5506.9 2132.24  5639.0 2134.92  5776.2 2135.89
#Mann=6,-1,0
  4226.2    0.07       0  4998.2    0.07       0  5002.3    0.07       0
  5257.2   0.035       0  5329.2    0.07       0  5419.1   0.035       0
Bank Sta=4998.2,5002.3
Exp/Cntr=0.3,0.1

Type RM Length L Ch R = 1,3207,468,468,468
BEGIN DESCRIPTION:
Buffalo Creek Trib 02-04 3.0
END DESCRIPTION:
XS GIS Cut Line= 5
      1329205.00      6937787.99      1329429.07      6938496.67
      1329505.00      6938538.00      1329598.34      6938587.81
      1330280.89      6938664.92
#Sta/Elev= 30
  4166.2 2135.54  4252.2 2133.48  4271.1 2132.55  4426.4 2129.73  4554.3 2128.01
  4580.7 2128.20  4596.2 2127.40  4760.0 2126.18  4836.2 2125.67  4960.3 2123.36
  4966.0 2123.80  4973.1 2122.10  4982.1 2121.11  4987.8 2121.31  4991.0 2119.83
  4991.3 2119.33  4994.9 2119.33  4995.2 2119.83  5018.6 2120.66  5026.0 2121.96
  5031.7 2121.51  5048.0 2122.37  5101.7 2122.25  5150.8 2122.90  5158.7 2123.82
  5235.6 2124.83  5380.1 2126.42  5505.1 2126.88  5521.0 2127.46  5788.6 2130.15
#Mann=6,-1,0
  4166.2   0.035       0  4426.4    0.07       0  4760.0   0.035       0
  4836.2    0.07       0  4991.0    0.07       0  4995.2    0.07       0
Bank Sta=4991,4995.2
Exp/Cntr=0.3,0.1

Type RM Length L Ch R = 1,2739,421,421,421
BEGIN DESCRIPTION:
Buffalo Creek Trib 02-04 2.5
END DESCRIPTION:
XS GIS Cut Line= 5
      1329007.50      6938458.39      1329264.46      6938927.17
      1329317.11      6938888.11      1329719.32      6938692.80
      1330190.08      6938742.99
#Sta/Elev= 30
  4333.6 2124.39  4345.3 2124.82  4354.9 2124.13  4529.8 2123.14  4686.7 2123.02
  4816.8 2121.36  4889.8 2120.69  4918.7 2119.12  4925.2 2119.68  4929.6 2118.45
  4953.6 2116.89  4967.2 2114.24  4967.5 2113.74  4971.2 2113.74  4971.4 2114.24
  4975.9 2116.55  4986.3 2118.55  5020.3 2120.14  5087.7 2121.78  5120.4 2121.91
  5132.8 2122.76  5290.8 2123.81  5330.3 2123.40  5335.9 2124.24  5375.5 2124.33
  5380.6 2124.85  5387.2 2124.19  5446.9 2123.81  5567.0 2126.42  5854.3 2129.15
#Mann=6,-1,0
  4333.6   0.035       0  4345.3    0.07       0  4529.8   0.035       0
  4816.8    0.07       0  4967.2    0.07       0  4971.4    0.07       0
Bank Sta=4967.2,4971.4
Exp/Cntr=0.3,0.1

Type RM Length L Ch R = 1,2318,564,564,564
BEGIN DESCRIPTION:
Buffalo Creek Trib 02-04 2.0
END DESCRIPTION:
XS GIS Cut Line= 3
      1329187.78      6938962.82      1329255.00      6939188.00
      1329797.28      6939513.95
#Sta/Elev= 30
  4759.5 2121.15  4828.7 2120.78  4939.6 2119.42  4952.8 2118.64  4963.2 2116.63
  4972.7 2112.11  4977.9 2112.89  4984.1 2109.58  5000.0 2108.19  5000.4 2107.69
  5004.2 2107.69  5004.5 2108.19  5008.1 2108.95  5017.8 2108.94  5023.6 2114.54
  5029.5 2113.88  5039.2 2113.90  5043.0 2114.98  5052.8 2116.40  5066.4 2116.55
  5076.1 2115.33  5087.8 2117.04  5111.2 2118.41  5161.6 2118.76  5177.1 2119.39
  5183.0 2118.86  5192.7 2119.33  5241.2 2118.90  5341.4 2121.02  5627.2 2125.19
#Mann=5,-1,0
  4759.5   0.035       0  4828.7    0.07       0  5000.0    0.07       0
  5004.5    0.07       0  5341.4   0.035       0
Bank Sta=5000,5004.5
Exp/Cntr=0.3,0.1

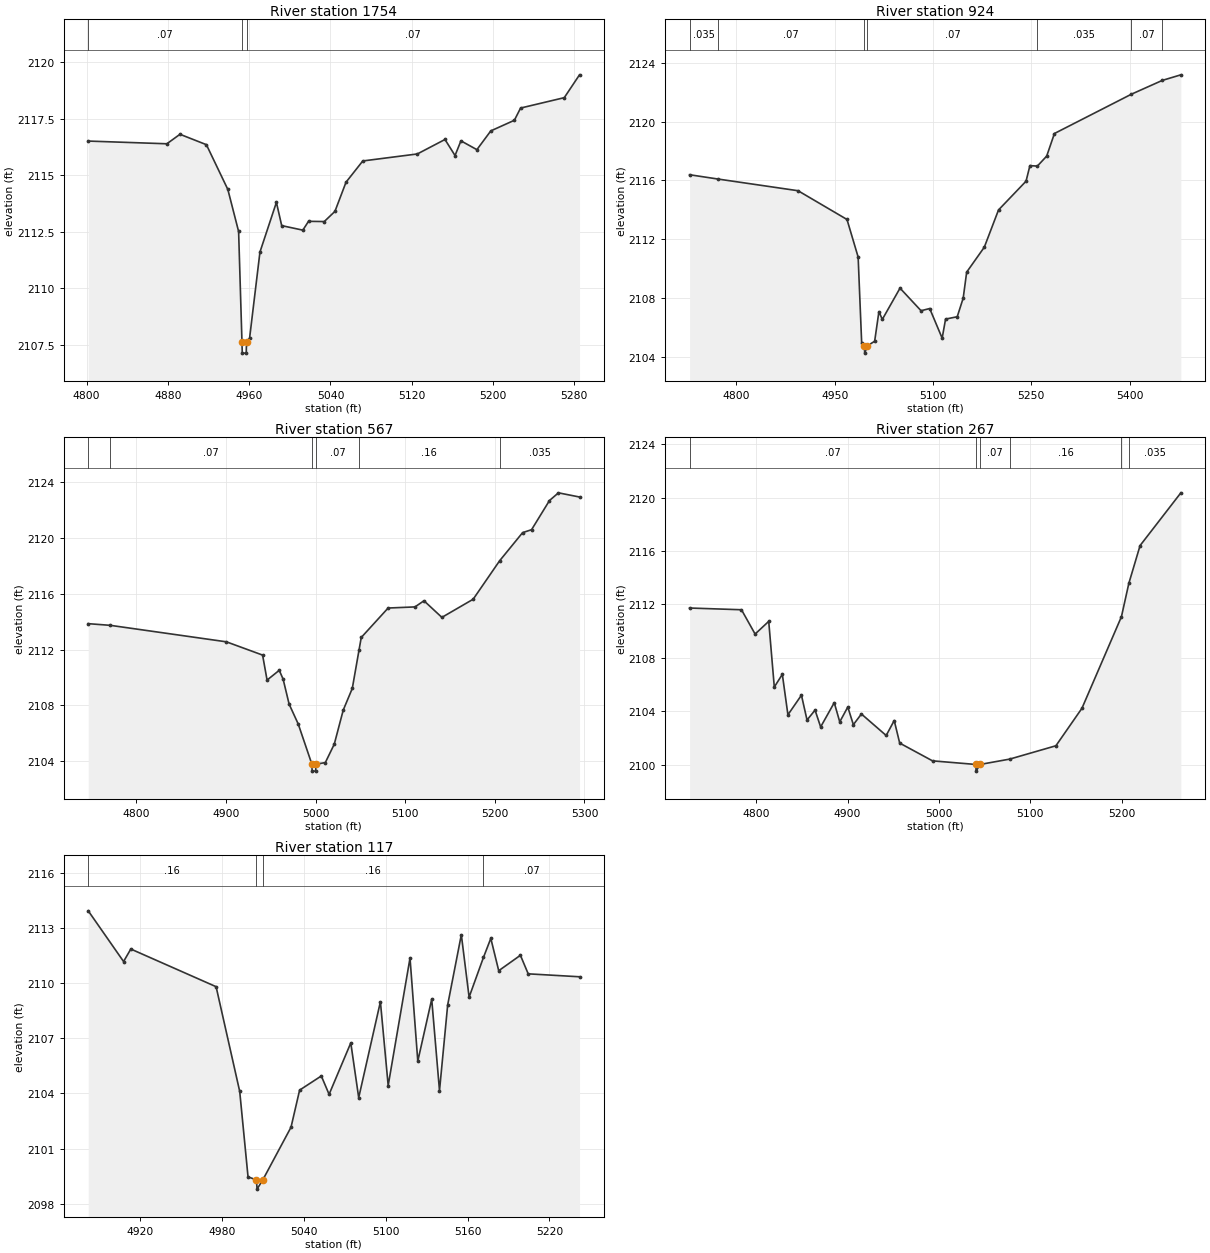
Type RM Length L Ch R = 1,1754,830,830,830
BEGIN DESCRIPTION:
Buffalo Creek Trib 02-04 2.4
END DESCRIPTION:
XS GIS Cut Line= 4
      1329179.96      6939713.00      1329255.14      6939716.94
      1329317.11      6939531.04      1329500.32      6939423.85
#Sta/Elev= 30
  4801.6 2116.52  4879.0 2116.40  4891.9 2116.82  4917.9 2116.36  4939.0 2114.38
  4949.6 2112.52  4952.9 2107.64  4953.2 2107.14  4957.1 2107.14  4957.4 2107.64
  4960.4 2107.80  4970.6 2111.61  4986.8 2113.81  4992.0 2112.78  5012.8 2112.58
  5018.4 2112.97  5033.9 2112.96  5044.4 2113.41  5055.3 2114.70  5071.8 2115.64
  5125.5 2115.95  5152.7 2116.59  5162.6 2115.88  5168.4 2116.53  5184.1 2116.14
  5197.8 2116.97  5221.0 2117.44  5227.1 2117.98  5270.1 2118.44  5285.1 2119.45
#Mann=3,-1,0
  4801.6    0.07       0  4952.9    0.07       0  4957.4    0.07       0
Bank Sta=4952.9,4957.4
Exp/Cntr=0.3,0.1

Type RM Length L Ch R = 1,924,357,357,357
BEGIN DESCRIPTION:
Buffalo Creek Trib 02-04 1.0
END DESCRIPTION:
XS GIS Cut Line= 3
      1329180.00      6939762.84      1329274.62      6940017.32
      1329729.99      6940163.00
#Sta/Elev= 30
  4728.5 2116.39  4771.3 2116.10  4894.0 2115.30  4968.7 2113.34  4985.7 2110.78
  4991.1 2104.91  4995.4 2104.73  4995.7 2104.23  4999.9 2104.73  5010.9 2105.04
  5017.4 2107.06  5022.6 2106.53  5049.6 2108.66  5081.7 2107.12  5094.9 2107.27
  5113.9 2105.25  5119.1 2106.55  5136.9 2106.71  5146.0 2107.98  5151.3 2109.75
  5178.2 2111.45  5199.9 2113.99  5241.9 2115.95  5247.8 2117.01  5259.2 2116.98
  5273.4 2117.66  5285.2 2119.20  5402.7 2121.88  5449.8 2122.82  5478.1 2123.20
#Mann=7,-1,0
  4728.5   0.035       0  4771.3    0.07       0  4995.4    0.07       0
  4999.9    0.07       0  5259.2   0.035       0  5402.7    0.07       0
  5449.8   0.035       0
Bank Sta=4995.4,4999.9
Exp/Cntr=0.3,0.1

Type RM Length L Ch R = 1,567,300,300,300
BEGIN DESCRIPTION:
Buffalo Creek Trib 02-04 0.5
END DESCRIPTION:
XS GIS Cut Line= 4
      1329080.00      6940135.53      1329111.68      6940343.84
      1329154.44      6940336.64      1329448.48      6940347.31
#Sta/Elev= 30
  4746.2 2113.86  4770.9 2113.74  4900.4 2112.56  4940.8 2111.61  4945.8 2109.82
  4959.4 2110.52  4963.7 2109.89  4970.4 2108.10  4980.6 2106.67  4995.8 2103.80
  4996.1 2103.30  5000.0 2103.30  5000.3 2103.80  5010.8 2103.91  5020.8 2105.23
  5030.8 2107.67  5040.9 2109.22  5048.4 2111.96  5050.9 2112.87  5080.9 2114.98
  5110.9 2115.06  5120.9 2115.50  5140.9 2114.31  5175.8 2115.61  5205.3 2118.36
  5231.0 2120.38  5241.0 2120.59  5261.0 2122.68  5271.0 2123.23  5294.5 2122.93
#Mann=6,-1,0
  4746.2    0.16       0  4770.9    0.07       0  4995.8    0.07       0
  5000.3    0.07       0  5048.4    0.16       0  5205.3   0.035       0
Bank Sta=4995.8,5000.3
Exp/Cntr=0.3,0.1

Type RM Length L Ch R = 1,267,150,150,150
BEGIN DESCRIPTION:
Buffalo Creek Trib 02-04 0.2
END DESCRIPTION:
XS GIS Cut Line= 3
      1329079.97      6940362.96      1329234.91      6940587.61
      1329433.32      6940762.68
#Sta/Elev= 30
  4727.1 2111.73  4783.9 2111.60  4798.8 2109.78  4813.7 2110.73  4819.8 2105.81
  4828.6 2106.76  4834.7 2103.73  4849.5 2105.20  4855.6 2103.34  4864.4 2104.08
  4870.5 2102.82  4885.4 2104.64  4891.4 2103.20  4900.2 2104.31  4906.3 2102.99
  4915.1 2103.79  4942.2 2102.18  4951.0 2103.30  4957.0 2101.61  4992.9 2100.28
  5040.3 2100.01  5040.6 2099.51  5044.9 2100.01  5077.3 2100.41  5127.9 2101.41
  5156.4 2104.22  5199.6 2111.08  5207.7 2113.58  5220.0 2116.41  5264.6 2120.36
#Mann=6,-1,0
  4727.1    0.07       0  5040.3    0.07       0  5044.9    0.07       0
  5077.3    0.16       0  5199.6    0.07       0  5207.7   0.035       0
Bank Sta=5040.3,5044.9
Exp/Cntr=0.3,0.1

Type RM Length L Ch R = 1,117,0,0,0
BEGIN DESCRIPTION:
Buffalo Creek Trib 02-04 0.3
END DESCRIPTION:
XS GIS Cut Line= 3
      1329080.02      6940563.05      1329118.34      6940674.65
      1329329.17      6940793.46
#Sta/Elev= 30
  4882.0 2113.94  4907.9 2111.18  4913.2 2111.86  4975.7 2109.81  4993.0 2104.11
  4999.1 2099.46  5005.3 2099.29  5005.7 2098.79  5009.9 2099.29  5030.6 2102.16
  5036.9 2104.18  5052.8 2104.95  5058.5 2103.95  5074.4 2106.75  5080.2 2103.77
  5096.1 2108.99  5101.8 2104.43  5117.8 2111.37  5123.5 2105.76  5133.7 2109.13
  5139.4 2104.15  5145.4 2108.82  5155.4 2112.64  5161.1 2109.24  5171.6 2111.40
  5177.0 2112.44  5182.8 2110.68  5198.7 2111.52  5204.4 2110.51  5242.0 2110.35
#Mann=4,-1,0
  4882.0    0.16       0  5005.3    0.07       0  5009.9    0.16       0
  5171.6    0.07       0
Bank Sta=5005.3,5009.9
Exp/Cntr=0.3,0.1

Chan Stop Cuts=-1