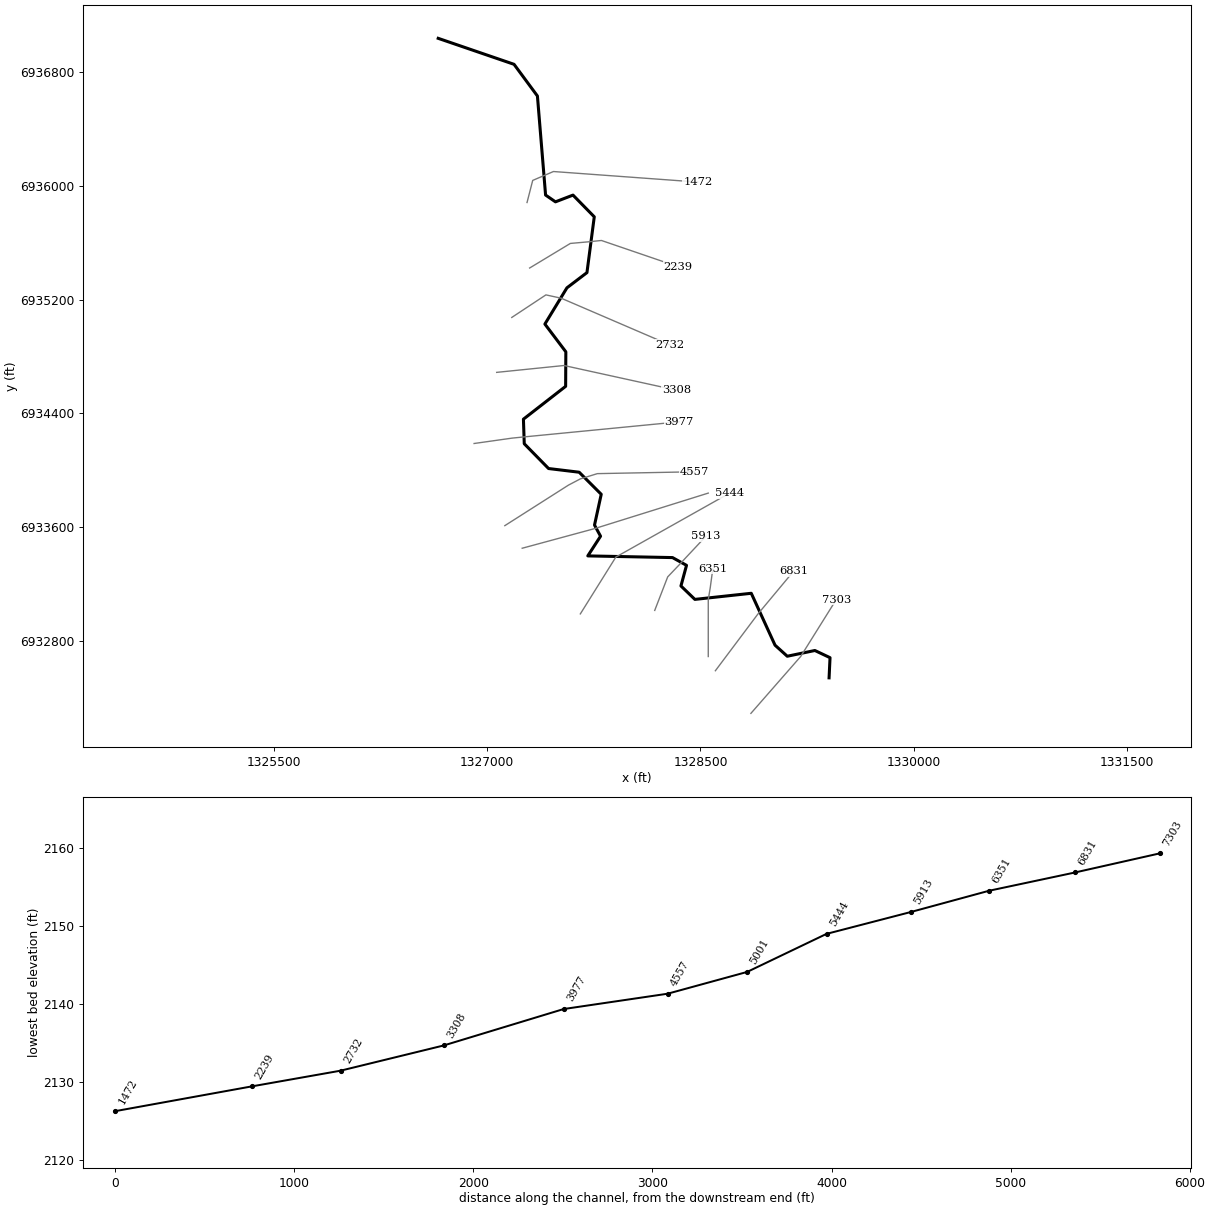
--- Buffalo Creek Trib 02-05.prj (project) ---

Proj Title=Buffalo Creek Trib 02-05 Base Level Engineering
Current Plan=p01
Default Exp/Contr=0.3,0.1
English Units
Geom File=g01
Flow File=f01
Plan File=p01
BEGIN DESCRIPTION:
Buffalo Creek Trib 02-05
END DESCRIPTION:

--- Buffalo Creek Trib 02-05.p01 (plan) ---

Plan Title=Multiple Run
Short Identifier=Multiple
Geom File=g01
Flow File=f01
Subcritical Flow
K Sum by GR= 0
Std Step Tol= 0.01
Critical Tol= 0.01
Num of Std Step Trials= 20
Max Error Tol= 0.3
Flow Tol Ratio= 0.001
Split Flow NTrial= 30
Split Flow Tol= 0.02
Split Flow Ratio= 0.02
Log Output Level= 0
Friction Slope Method= 1
Unsteady Friction Slope Method= 2
Unsteady Bridges Friction Slope Method= 1
Parabolic Critical Depth
Global Vel Dist=  1 , 1 , 1
Global Log Level= 0
CheckData=True
Encroach Param= -1, 0, 0, 0
BEGIN DESCRIPTION:
Multiple Run
END DESCRIPTION:

--- Buffalo Creek Trib 02-05.f01 (steady flow) ---

Flow Title=Multiple
Number of Profiles=7
Profile Names=10-year,25-year,50-year,1pct_min,100-year,1pct_plu,500-year
River Rch & RM= Buffalo Creek Tr,Reach-1,7303
     344     494     621     388     775    1547    1224
Boundary for River Rch & Prof#=Buffalo Creek Tr,Reach-1,1
Up Type=0
Dn Type=3
Dn Slope=0.005
Boundary for River Rch & Prof#=Buffalo Creek Tr,Reach-1,2
Up Type=0
Dn Type=3
Dn Slope=0.005
Boundary for River Rch & Prof#=Buffalo Creek Tr,Reach-1,3
Up Type=0
Dn Type=3
Dn Slope=0.005
Boundary for River Rch & Prof#=Buffalo Creek Tr,Reach-1,4
Up Type=0
Dn Type=3
Dn Slope=0.005
Boundary for River Rch & Prof#=Buffalo Creek Tr,Reach-1,5
Up Type=0
Dn Type=3
Dn Slope=0.005
Boundary for River Rch & Prof#=Buffalo Creek Tr,Reach-1,6
Up Type=0
Dn Type=3
Dn Slope=0.005
Boundary for River Rch & Prof#=Buffalo Creek Tr,Reach-1,7
Up Type=0
Dn Type=3
Dn Slope=0.005

--- Buffalo Creek Trib 02-05.g01 (geometry) ---

Geom Title=Existing Conditions

River Reach=Buffalo Creek Tr,Reach-1
Reach XY= 30
      1329405.00      6932538.00      1329411.69      6932679.90
      1329305.02      6932730.47      1329110.85      6932690.04
      1329024.77      6932767.87      1328857.58      6933133.03
      1328460.83      6933090.06      1328362.79      6933184.57
      1328402.03      6933329.68      1328303.48      6933384.26
      1327707.43      6933396.11      1327797.16      6933534.60
      1327754.69      6933612.96      1327801.94      6933829.69
      1327646.70      6933984.93      1327431.42      6934010.84
      1327260.39      6934185.32      1327254.56      6934358.18
      1327551.55      6934589.25      1327552.94      6934832.15
      1327405.55      6935027.36      1327560.59      6935282.39
      1327701.47      6935389.45      1327752.95      6935782.14
      1327603.37      6935934.87      1327479.87      6935887.47
      1327410.42      6935935.25      1327353.00      6936632.32
      1327188.55      6936855.14      1326655.00      6937038.00

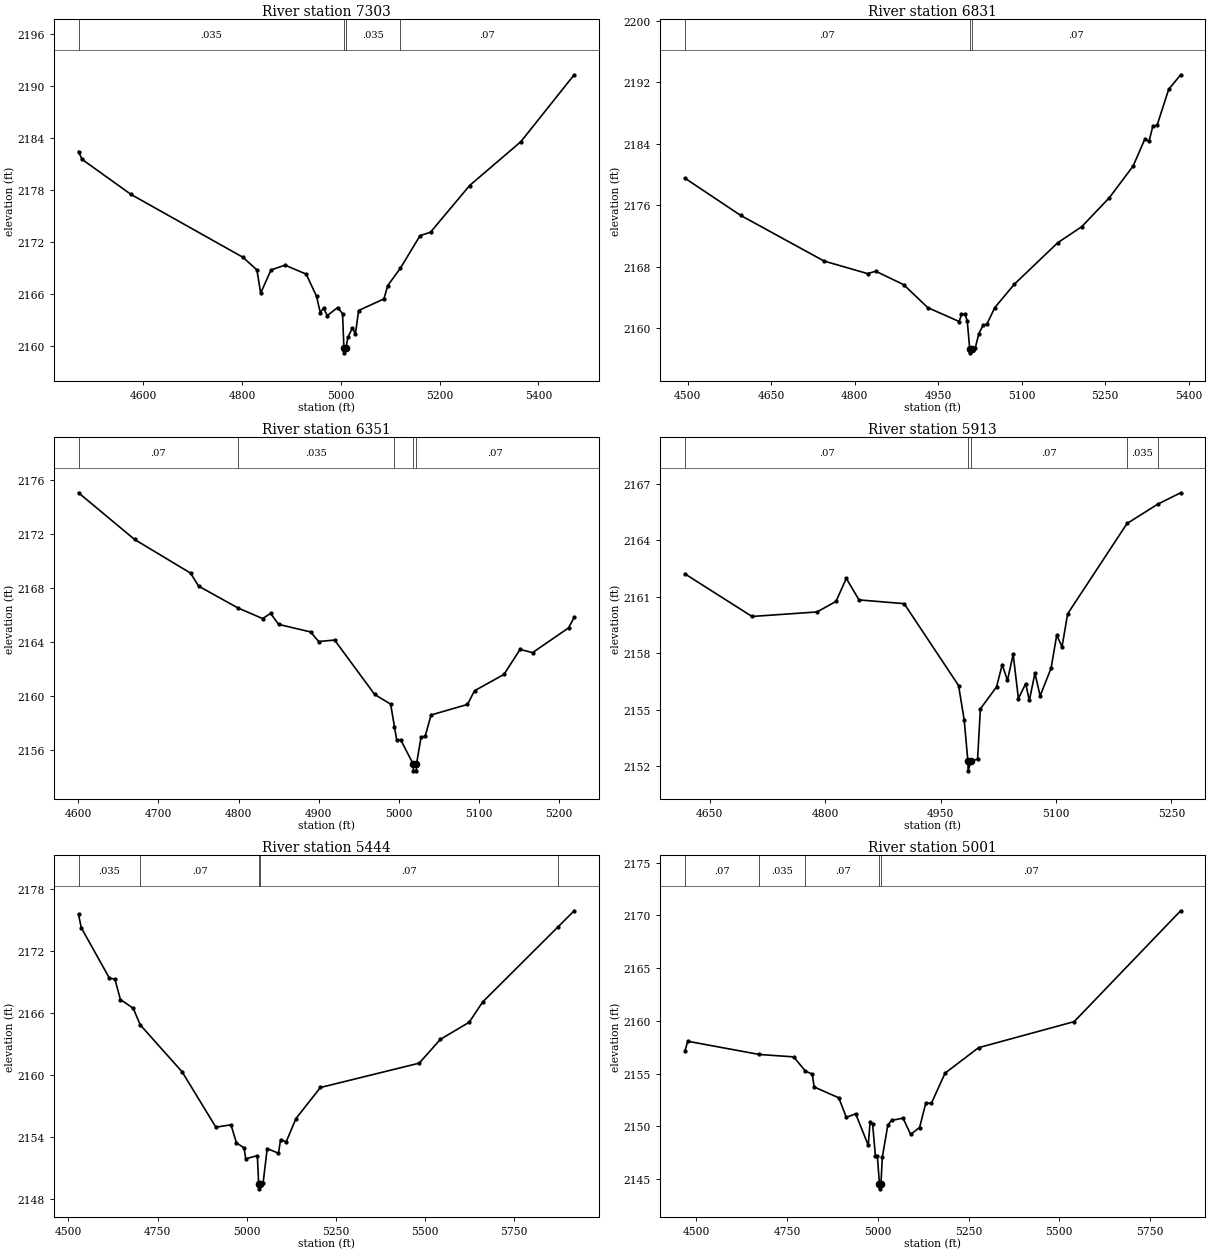
Type RM Length L Ch R = 1,7303,472,472,472
BEGIN DESCRIPTION:
Buffalo Creek Trib 02-05 7.0
END DESCRIPTION:
XS GIS Cut Line= 3
      1328855.00      6932288.00      1329205.00      6932688.00
      1329455.00      6933088.00
#Sta/Elev= 30
  4469.1 2182.43  4476.2 2181.53  4575.4 2177.49  4801.8 2170.26  4830.2 2168.80
  4837.8 2166.13  4858.7 2168.80  4887.2 2169.35  4929.9 2168.32  4950.8 2165.78
  4958.4 2163.90  4965.0 2164.41  4972.6 2163.55  4993.5 2164.47  5003.5 2163.77
  5006.3 2159.76  5006.5 2159.26  5010.3 2159.76  5014.2 2161.04  5023.6 2162.13
  5029.5 2161.42  5036.0 2164.13  5087.3 2165.47  5094.9 2167.00  5120.5 2168.99
  5160.4 2172.75  5181.6 2173.14  5260.6 2178.51  5364.4 2183.56  5472.3 2191.26
#Mann=4,-1,0
  4469.1   0.035       0  5006.3   0.035       0  5010.3   0.035       0
  5120.5    0.07       0
Bank Sta=5006.3,5010.3
Exp/Cntr=0.3,0.1

Type RM Length L Ch R = 1,6831,480,480,480
BEGIN DESCRIPTION:
Buffalo Creek Trib 02-05 6.0
END DESCRIPTION:
XS GIS Cut Line= 3
      1328605.03      6932588.04      1328905.00      6932988.00
      1329155.02      6933288.03
#Sta/Elev= 30
  4495.2 2179.52  4595.2 2174.69  4745.2 2168.75  4823.3 2167.12  4837.9 2167.43
  4887.9 2165.69  4931.6 2162.69  4987.9 2160.89  4992.0 2161.83  4998.4 2161.83
  5002.3 2160.98  5006.8 2157.32  5007.1 2156.82  5010.9 2157.32  5016.6 2157.42
  5023.1 2159.29  5031.0 2160.45  5037.5 2160.53  5051.8 2162.70  5086.9 2165.74
  5165.0 2171.14  5208.0 2173.22  5257.4 2176.97  5300.4 2181.11  5321.2 2184.58
  5329.0 2184.34  5335.6 2186.25  5343.4 2186.41  5364.2 2191.07  5385.7 2192.97
#Mann=3,-1,0
  4495.2    0.07       0  5006.8    0.07       0  5010.9    0.07       0
Bank Sta=5006.8,5010.9
Exp/Cntr=0.3,0.1

Type RM Length L Ch R = 1,6351,438,438,438
BEGIN DESCRIPTION:
Buffalo Creek Trib 02-05 5.0
END DESCRIPTION:
XS GIS Cut Line= 4
      1328555.00      6932688.01      1328555.00      6933088.00
      1328569.00      6933172.88      1328586.93      6933304.95
#Sta/Elev= 30
  4600.1 2175.04  4670.1 2171.59  4740.1 2169.10  4750.1 2168.14  4799.1 2166.53
  4830.1 2165.74  4840.1 2166.12  4850.1 2165.31  4890.1 2164.75  4900.1 2164.04
  4920.1 2164.15  4970.1 2160.13  4990.1 2159.41  4994.9 2157.73  4997.6 2156.78
  5002.6 2156.78  5018.3 2154.98  5018.6 2154.48  5022.2 2154.48  5022.4 2154.98
  5028.1 2156.97  5033.2 2157.03  5040.6 2158.61  5086.1 2159.39  5094.9 2160.40
  5131.7 2161.61  5151.8 2163.46  5167.4 2163.22  5212.4 2165.05  5219.4 2165.83
#Mann=5,-1,0
  4600.1    0.07       0  4799.1   0.035       0  4994.9    0.07       0
  5018.3    0.07       0  5022.4    0.07       0
Bank Sta=5018.3,5022.4
Exp/Cntr=0.3,0.1

Type RM Length L Ch R = 1,5913,469,469,469
BEGIN DESCRIPTION:
Buffalo Creek Trib 02-05 4.0
END DESCRIPTION:
XS GIS Cut Line= 5
      1328178.31      6933012.50      1328269.52      6933248.41
      1328355.00      6933338.00      1328399.73      6933386.43
      1328537.53      6933533.20
#Sta/Elev= 30
  4617.9 2162.21  4705.0 2159.95  4789.5 2160.19  4814.1 2160.75  4827.5 2161.97
  4844.0 2160.83  4902.7 2160.63  4973.4 2156.28  4980.7 2154.45  4985.5 2152.25
  4985.8 2151.75  4989.6 2152.25  4998.1 2152.38  5001.7 2155.04  5022.7 2156.21
  5030.1 2157.39  5036.9 2156.55  5044.3 2157.94  5051.1 2155.59  5060.6 2156.38
  5065.3 2155.49  5072.6 2156.93  5079.4 2155.73  5093.6 2157.21  5100.9 2158.96
  5107.8 2158.34  5115.1 2160.09  5192.3 2164.89  5232.4 2165.92  5261.9 2166.52
#Mann=5,-1,0
  4617.9    0.07       0  4985.5    0.07       0  4989.6    0.07       0
  5192.3   0.035       0  5232.4    0.07       0
Bank Sta=4985.5,4989.6
Exp/Cntr=0.3,0.1

Type RM Length L Ch R = 1,5444,443,443,443
BEGIN DESCRIPTION:
Buffalo Creek Trib 02-05 3.0
END DESCRIPTION:
XS GIS Cut Line= 3
      1327654.99      6932987.98      1327905.00      6933388.00
      1328705.00      6933838.00
#Sta/Elev= 30
  4528.3 2175.58  4536.0 2174.29  4615.0 2169.39  4630.3 2169.31  4645.7 2167.32
  4681.6 2166.48  4701.4 2164.86  4819.0 2160.30  4913.4 2154.94  4955.8 2155.17
  4971.1 2153.41  4992.4 2152.94  4997.1 2151.87  5029.7 2152.19  5033.3 2149.46
  5033.6 2148.96  5037.5 2149.46  5045.6 2149.48  5057.4 2152.87  5088.9 2152.41
  5094.7 2153.71  5110.6 2153.53  5138.0 2155.78  5206.5 2158.79  5483.5 2161.15
  5542.8 2163.46  5623.7 2165.12  5661.3 2167.08  5872.4 2174.36  5917.9 2175.93
#Mann=5,-1,0
  4528.3   0.035       0  4701.4    0.07       0  5033.3    0.07       0
  5037.5    0.07       0  5872.4   0.035       0
Bank Sta=5033.3,5037.5
Exp/Cntr=0.3,0.1

Type RM Length L Ch R = 1,5001,444,444,444
BEGIN DESCRIPTION:
Buffalo Creek Trib 02-05 2.0
END DESCRIPTION:
XS GIS Cut Line= 3
      1327245.99      6933450.03      1327755.00      6933588.00
      1328554.97      6933837.99
#Sta/Elev= 30
  4468.6 2157.17  4476.3 2158.07  4673.0 2156.82  4768.0 2156.59  4800.5 2155.24
  4819.3 2154.96  4824.5 2153.74  4892.4 2152.71  4913.1 2150.86  4938.8 2151.20
  4973.5 2148.22  4978.6 2150.41  4985.6 2150.19  4993.4 2147.16  4998.6 2147.16
  5004.4 2144.59  5004.6 2144.09  5008.6 2144.59  5012.2 2147.08  5027.4 2150.13
  5037.9 2150.57  5069.3 2150.79  5090.3 2149.25  5114.9 2149.90  5132.2 2152.22
  5147.4 2152.19  5185.1 2155.05  5277.3 2157.46  5540.8 2159.93  5834.1 2170.43
#Mann=5,-1,0
  4468.6    0.07       0  4673.0   0.035       0  4800.5    0.07       0
  5004.4    0.07       0  5008.6    0.07       0
Bank Sta=5004.4,5008.6
Exp/Cntr=0.3,0.1

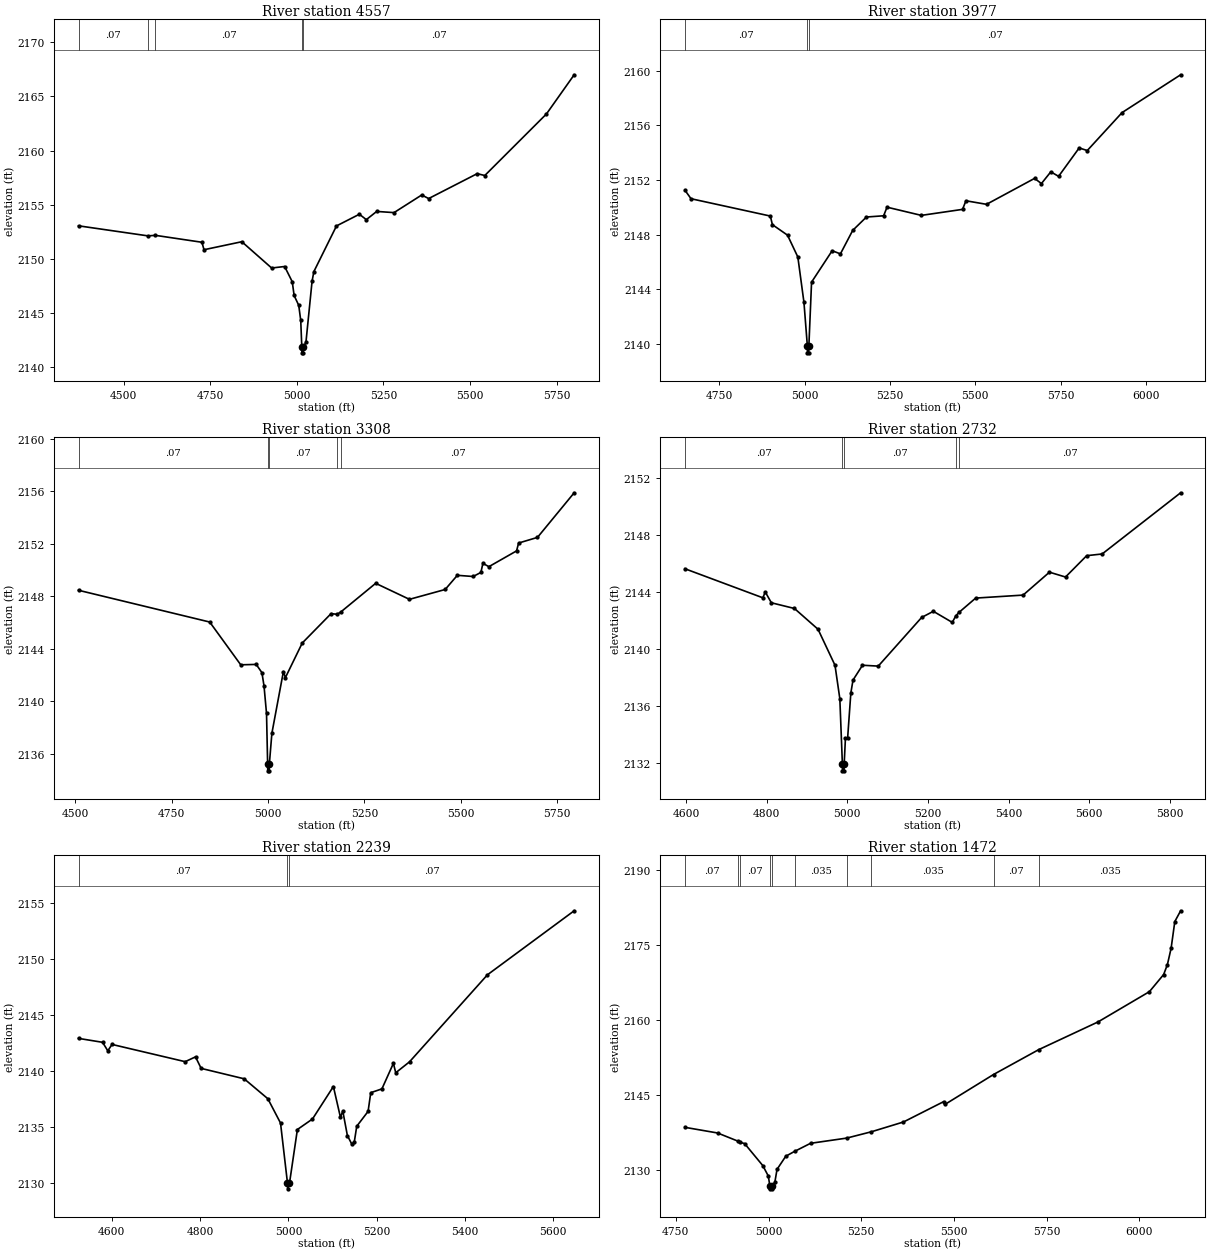
Type RM Length L Ch R = 1,4557,580,580,580
BEGIN DESCRIPTION:
Buffalo Creek Trib 02-05 1.0
END DESCRIPTION:
XS GIS Cut Line= 5
      1327123.63      6933608.89      1327571.60      6933894.24
      1327655.00      6933938.00      1327774.73      6933974.97
      1328454.98      6933988.00
#Sta/Elev= 30
  4370.0 2153.04  4570.6 2152.11  4591.8 2152.16  4726.3 2151.52  4732.3 2150.83
  4841.5 2151.57  4927.6 2149.14  4965.1 2149.28  4987.1 2147.87  4992.5 2146.60
  5005.8 2145.69  5011.6 2144.29  5014.7 2141.80  5015.0 2141.30  5018.7 2141.30
  5019.0 2141.80  5026.7 2142.30  5044.3 2147.92  5049.5 2148.81  5114.8 2153.03
  5180.9 2154.11  5200.9 2153.61  5230.9 2154.37  5280.9 2154.26  5360.9 2155.89
  5380.9 2155.56  5521.0 2157.86  5543.0 2157.69  5721.0 2163.38  5801.0 2167.00
#Mann=5,-1,0
  4370.0    0.07       0  4570.6   0.035       0  4591.8    0.07       0
  5014.7    0.07       0  5019.0    0.07       0
Bank Sta=5014.7,5019
Exp/Cntr=0.3,0.1

Type RM Length L Ch R = 1,3977,669,669,669
BEGIN DESCRIPTION:
Buffalo Creek Trib 02-05 1.2
END DESCRIPTION:
XS GIS Cut Line= 4
      1326907.49      6934187.02      1327175.77      6934224.97
      1327259.60      6934233.40      1328350.74      6934339.62
#Sta/Elev= 30
  4649.9 2151.25  4667.6 2150.63  4899.9 2149.36  4905.9 2148.73  4950.2 2147.96
  4980.4 2146.36  4998.3 2143.04  5008.3 2139.84  5008.6 2139.34  5012.4 2139.34
  5012.7 2139.84  5020.6 2144.52  5080.9 2146.82  5105.1 2146.59  5141.1 2148.31
  5181.3 2149.29  5231.6 2149.38  5241.6 2150.01  5342.1 2149.41  5462.7 2149.85
  5472.7 2150.48  5533.0 2150.22  5673.7 2152.12  5693.7 2151.74  5721.2 2152.60
  5744.0 2152.27  5804.3 2154.35  5828.0 2154.16  5929.9 2156.94  6101.4 2159.71
#Mann=3,-1,0
  4649.9    0.07       0  5008.3    0.07       0  5012.7    0.07       0
Bank Sta=5008.3,5012.7
Exp/Cntr=0.3,0.1

Type RM Length L Ch R = 1,3308,576,576,576
BEGIN DESCRIPTION:
Buffalo Creek Trib 02-05 0.8
END DESCRIPTION:
XS GIS Cut Line= 3
      1327066.32      6934687.52      1327539.80      6934735.84
      1328331.02      6934562.15
#Sta/Elev= 30
  4508.4 2148.44  4848.8 2146.02  4929.3 2142.76  4969.5 2142.79  4984.3 2142.16
  4989.7 2141.15  4996.2 2139.05  4999.1 2135.18  4999.4 2134.68  5003.2 2134.68
  5003.5 2135.18  5010.1 2137.54  5040.0 2142.25  5045.1 2141.78  5088.9 2144.42
  5163.7 2146.66  5179.5 2146.61  5189.1 2146.79  5279.4 2148.97  5367.0 2147.75
  5459.7 2148.50  5491.3 2149.58  5532.3 2149.49  5552.4 2149.80  5557.6 2150.49
  5573.2 2150.24  5644.9 2151.44  5650.3 2152.04  5699.2 2152.47  5794.4 2155.87
#Mann=5,-1,0
  4508.4    0.07       0  4999.1    0.07       0  5003.5    0.07       0
  5179.5   0.035       0  5189.1    0.07       0
Bank Sta=4999.1,5003.5
Exp/Cntr=0.3,0.1

Type RM Length L Ch R = 1,2732,493,493,493
BEGIN DESCRIPTION:
Buffalo Creek Trib 02-05 0.7
END DESCRIPTION:
XS GIS Cut Line= 4
      1327172.63      6935074.01      1327412.75      6935232.78
      1327520.48      6935209.28      1328283.77      6934880.78
#Sta/Elev= 30
  4597.3 2145.65  4790.4 2143.61  4796.4 2144.02  4811.5 2143.26  4868.7 2142.86
  4927.2 2141.40  4969.3 2138.87  4981.3 2136.52  4987.6 2131.95  4987.9 2131.45
  4991.7 2131.45  4992.1 2131.95  4995.2 2133.74  5000.6 2133.74  5008.6 2136.92
  5014.0 2137.83  5037.5 2138.87  5076.6 2138.81  5184.2 2142.23  5213.2 2142.66
  5260.2 2141.88  5268.6 2142.33  5276.6 2142.58  5318.2 2143.59  5435.8 2143.80
  5501.1 2145.41  5540.9 2145.07  5593.4 2146.57  5631.8 2146.69  5826.4 2150.99
#Mann=5,-1,0
  4597.3    0.07       0  4987.6    0.07       0  4992.1    0.07       0
  5268.6   0.035       0  5276.6    0.07       0
Bank Sta=4987.6,4992.1
Exp/Cntr=0.3,0.1

Type RM Length L Ch R = 1,2239,767,767,767
BEGIN DESCRIPTION:
Buffalo Creek Trib 02-05 0.6
END DESCRIPTION:
XS GIS Cut Line= 5
      1327298.24      6935421.85      1327584.63      6935594.76
      1327704.06      6935605.43      1327803.38      6935615.59
      1328340.85      6935431.83
#Sta/Elev= 30
  4524.8 2142.89  4579.3 2142.54  4591.1 2141.78  4600.7 2142.35  4766.3 2140.81
  4789.7 2141.24  4802.5 2140.21  4899.9 2139.28  4953.5 2137.50  4982.2 2135.33
  4998.0 2129.95  4998.3 2129.45  5002.5 2129.95  5020.4 2134.75  5054.6 2135.69
  5101.9 2138.59  5117.9 2135.84  5123.2 2136.40  5133.6 2134.21  5143.9 2133.42
  5149.2 2133.63  5154.8 2135.04  5180.5 2136.37  5186.5 2138.04  5211.8 2138.38
  5237.8 2140.66  5243.1 2139.82  5274.4 2140.80  5450.7 2148.57  5647.1 2154.29
#Mann=3,-1,0
  4524.8    0.07       0  4998.0    0.07       0  5002.5    0.07       0
Bank Sta=4998,5002.5
Exp/Cntr=0.3,0.1

Type RM Length L Ch R = 1,1472,0,0,0
BEGIN DESCRIPTION:
Buffalo Creek Trib 02-05 0.4
END DESCRIPTION:
XS GIS Cut Line= 4
      1327279.89      6935882.64      1327319.89      6936038.29
      1327465.73      6936100.79      1328480.65      6936026.62
#Sta/Elev= 30
  4774.7 2138.54  4862.8 2137.41  4917.6 2135.78  4924.1 2135.52  4935.4 2135.31
  4984.5 2130.91  4999.5 2128.82  5003.8 2126.76  5004.2 2126.26  5008.3 2126.26
  5008.6 2126.76  5017.1 2127.57  5023.0 2130.15  5046.6 2132.77  5070.4 2133.74
  5113.4 2135.35  5210.8 2136.39  5277.8 2137.66  5364.1 2139.61  5472.4 2143.67
  5477.4 2143.18  5607.0 2149.09  5728.8 2154.05  5888.7 2159.58  6027.5 2165.63
  6065.9 2169.05  6076.0 2171.04  6086.0 2174.28  6096.0 2179.63  6111.7 2181.78
#Mann=10,-1,0
  4774.7    0.07       0  4917.6   0.035       0  4924.1    0.07       0
  5003.8    0.07       0  5008.6    0.07       0  5070.4   0.035       0
  5210.8    0.07       0  5277.8   0.035       0  5607.0    0.07       0
  5728.8   0.035       0
Bank Sta=5003.8,5008.6
Exp/Cntr=0.3,0.1

Chan Stop Cuts=-1