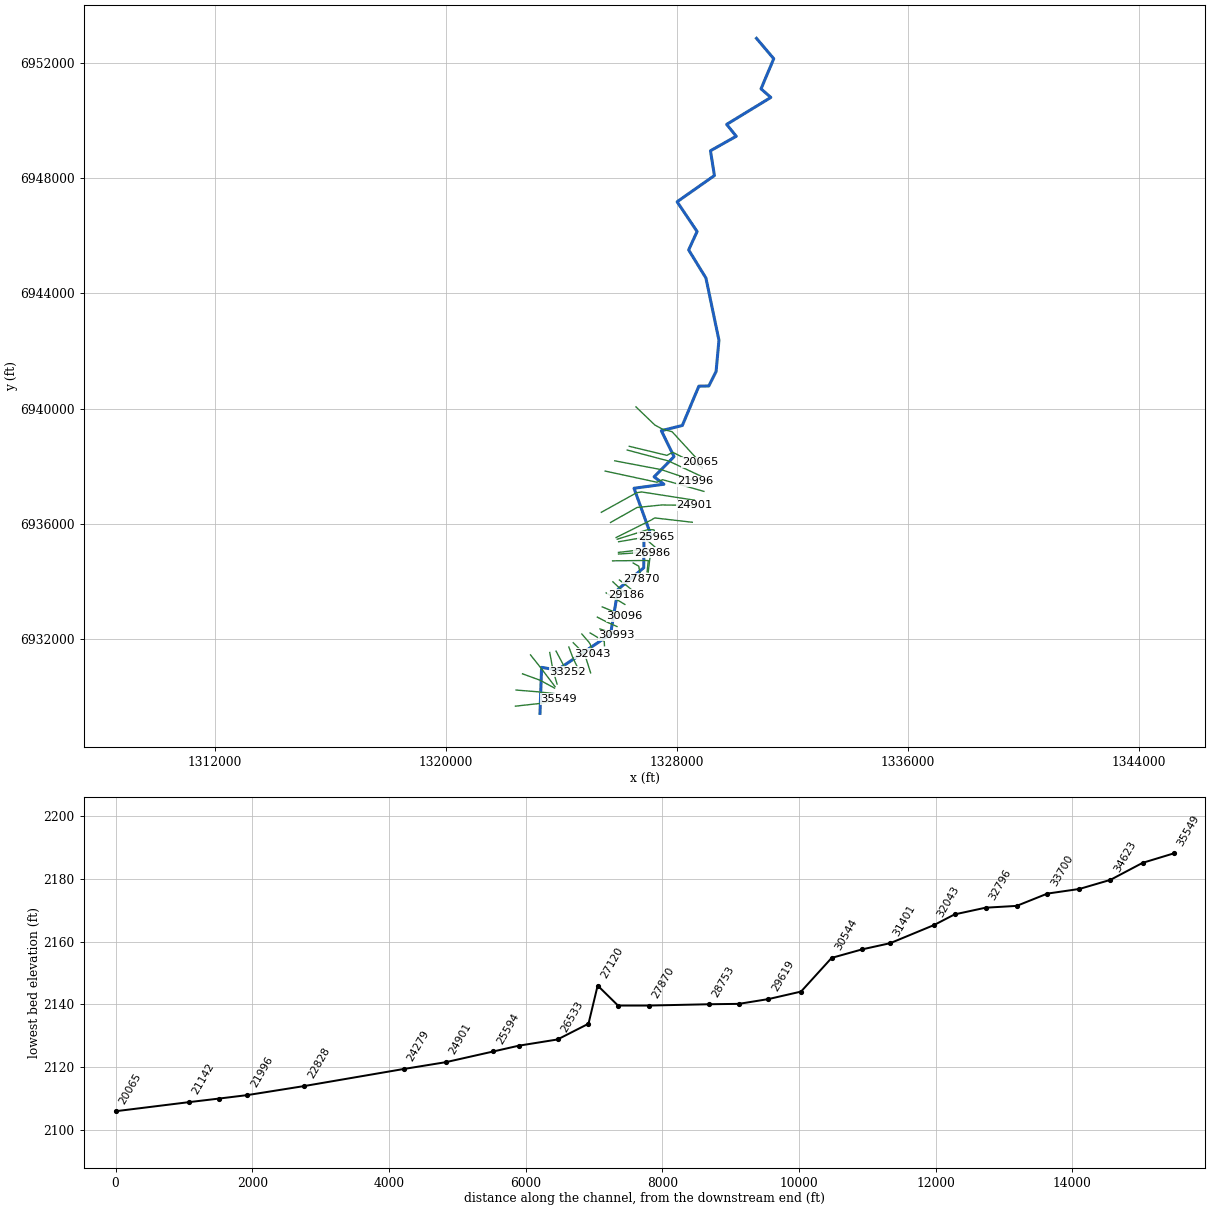
--- Buffalo Creek Trib 02.prj (project) ---

Proj Title=Buffalo Creek Trib 02 Base Level Engineering
Current Plan=p01
Default Exp/Contr=0.3,0.1
English Units
Geom File=g01
Flow File=f01
Plan File=p01
Y Axis Title=Elevation
X Axis Title(PF)=Main Channel Distance
X Axis Title(XS)=Station
BEGIN DESCRIPTION:
Buffalo Creek Trib 02
END DESCRIPTION:
DSS Export Rating Curves= 0
DSS Export Rating Curve Sorted= 0
DSS Export Volume Flow Curves= 0
DXF OffsetX= 0
DXF OffsetY= 0
DXF ScaleX= 1
DXF ScaleY= 10

--- Buffalo Creek Trib 02.p01 (plan) ---

Plan Title=Multiple Run
Short Identifier=Multiple
Geom File=g01
Flow File=f01
Subcritical Flow
K Sum by GR= 0
Std Step Tol= 0.01
Critical Tol= 0.01
Num of Std Step Trials= 20
Max Error Tol= 0.3
Flow Tol Ratio= 0.001
Split Flow NTrial= 30
Split Flow Tol= 0.02
Split Flow Ratio= 0.02
Log Output Level= 0
Friction Slope Method= 1
Unsteady Friction Slope Method= 2
Unsteady Bridges Friction Slope Method= 1
Parabolic Critical Depth
Global Vel Dist=  1 , 1 , 1
Global Log Level= 0
CheckData=True
Encroach Param= -1, 0, 0, 0
BEGIN DESCRIPTION:
Multiple Run
END DESCRIPTION:

--- Buffalo Creek Trib 02.f01 (steady flow) ---

Flow Title=Multiple
Program Version=4.10
Number of Profiles= 7
Profile Names=10-year,25-year,50-year,1pct_min,100-year,1pct_plu,500-year
River Rch & RM=Buffalo Creek Tr,Reach-1         ,35549
     306     436     545     339     676    1348    1053
River Rch & RM=Buffalo Creek Tr,Reach-1         ,30993
     458     667     846     533    1064    2123    1706
River Rch & RM=Buffalo Creek Tr,Reach-1         ,30544
     534     781     995     629    1254    2503    2023
River Rch & RM=Buffalo Creek Tr,Reach-1         ,25594
     755    1119    1438     916    1828    3647    2993
River Rch & RM=Buffalo Creek Tr,Reach-1         ,16677
     895    1337    1727    1105    2204    4398    3644
River Rch & RM=Buffalo Creek Tr,Reach-1         ,16263
    1023    1532    1982    1269    2532    5053    4195
River Rch & RM=Buffalo Creek Tr,Reach-1         ,9416
    1109    1663    2153    1380    2753    5493    4563
Boundary for River Rch & Prof#=Buffalo Creek Tr,Reach-1         , 1
Up Type= 0
Dn Type= 3
Dn Slope=0.003
Boundary for River Rch & Prof#=Buffalo Creek Tr,Reach-1         , 2
Up Type= 0
Dn Type= 3
Dn Slope=0.003
Boundary for River Rch & Prof#=Buffalo Creek Tr,Reach-1         , 3
Up Type= 0
Dn Type= 3
Dn Slope=0.003
Boundary for River Rch & Prof#=Buffalo Creek Tr,Reach-1         , 4
Up Type= 0
Dn Type= 3
Dn Slope=0.003
Boundary for River Rch & Prof#=Buffalo Creek Tr,Reach-1         , 5
Up Type= 0
Dn Type= 3
Dn Slope=0.003
Boundary for River Rch & Prof#=Buffalo Creek Tr,Reach-1         , 6
Up Type= 0
Dn Type= 3
Dn Slope=0.003
Boundary for River Rch & Prof#=Buffalo Creek Tr,Reach-1         , 7
Up Type= 0
Dn Type= 3
Dn Slope=0.003
DSS Import GetInterval= 0
DSS Import GetPeak= 0
DSS Import FillOption= 0

--- Buffalo Creek Trib 02.g01 (geometry) ---

Geom Title=Existing Conditions

River Reach=Buffalo Creek Tr,Reach-1
Reach XY= 30
      1323255.00      6929438.00      1323310.44      6931032.83
      1323853.54      6930941.53      1325699.17      6932185.70
      1325958.74      6933736.48      1326849.55      6934485.53
      1326855.65      6935622.74      1327104.46      6935603.53
      1326512.49      6937241.59      1327547.38      6937381.50
      1327208.08      6937636.32      1327898.02      6938338.20
      1327458.67      6939236.41      1328185.60      6939417.34
      1328758.35      6940779.92      1329105.00      6940788.00
      1329355.00      6941288.00      1329454.48      6942372.78
      1329003.80      6944527.50      1328405.51      6945503.21
      1328697.13      6946141.22      1328005.33      6947172.97
      1329297.19      6948081.81      1329160.28      6948940.71
      1330052.95      6949443.86      1329721.22      6949854.68
      1331251.63      6950789.55      1330912.30      6951087.91
      1331352.95      6952132.14      1330755.00      6952838.00

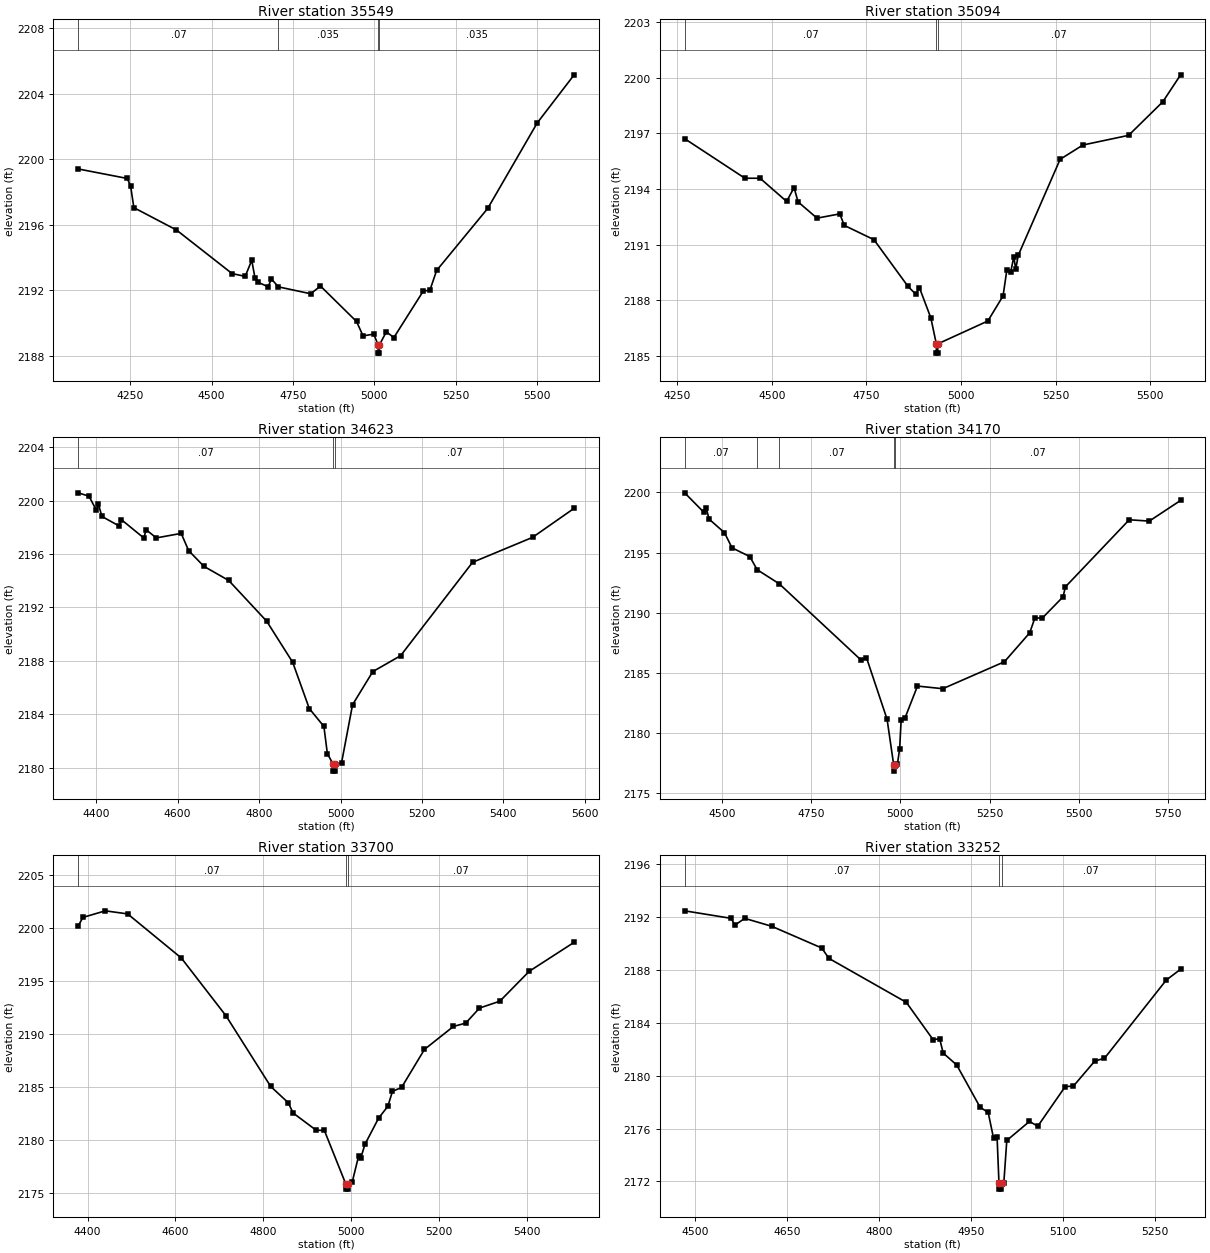
Type RM Length L Ch R = 1,35549,455,455,455
BEGIN DESCRIPTION:
Buffalo Creek Trib 02 37.0
END DESCRIPTION:
XS GIS Cut Line= 3
      1322405.00      6929688.00      1323305.00      6929788.00
      1323905.00      6929938.00
#Sta/Elev= 30
  4090.2 2199.41  4241.1 2198.83  4251.2 2198.37  4261.2 2197.05  4392.0 2195.69
  4563.1 2193.03  4603.3 2192.86  4623.5 2193.84  4633.5 2192.75  4643.6 2192.49
  4673.8 2192.23  4683.8 2192.70  4705.5 2192.22  4804.6 2191.80  4834.7 2192.27
  4945.4 2190.11  4965.5 2189.23  4998.3 2189.34  5011.8 2188.68  5012.0 2188.18
  5015.5 2188.18  5015.8 2188.68  5037.0 2189.48  5060.2 2189.13  5150.4 2191.96
  5171.0 2192.02  5191.6 2193.22  5348.8 2197.01  5500.8 2202.22  5614.2 2205.15
#Mann=4,-1,0
  4090.2    0.07       0  4705.5   0.035       0  5011.8   0.035       0
  5015.8   0.035       0
Bank Sta=5011.8,5015.8
Exp/Cntr=0.3,0.1

Type RM Length L Ch R = 1,35094,471,471,471
BEGIN DESCRIPTION:
Buffalo Creek Trib 02 36.0
END DESCRIPTION:
XS GIS Cut Line= 3
      1322426.35      6930246.54      1323155.00      6930188.00
      1323731.78      6930126.94
#Sta/Elev= 30
  4269.4 2196.71  4428.6 2194.58  4468.7 2194.58  4538.9 2193.33  4558.6 2194.08
  4569.0 2193.31  4619.2 2192.43  4679.4 2192.66  4691.3 2192.04  4769.7 2191.27
  4859.9 2188.75  4880.0 2188.34  4890.0 2188.68  4920.1 2187.06  4934.6 2185.66
  4934.8 2185.16  4938.3 2185.16  4938.6 2185.66  5070.8 2186.89  5111.0 2188.24
  5121.1 2189.64  5131.1 2189.52  5139.5 2190.35  5144.5 2189.68  5151.2 2190.43
  5261.9 2195.60  5322.2 2196.37  5442.9 2196.89  5533.4 2198.70  5580.4 2200.15
#Mann=3,-1,0
  4269.4    0.07       0  4934.6    0.07       0  4938.6    0.07       0
Bank Sta=4934.6,4938.6
Exp/Cntr=0.3,0.1

Type RM Length L Ch R = 1,34623,453,453,453
BEGIN DESCRIPTION:
Buffalo Creek Trib 02 35.0
END DESCRIPTION:
XS GIS Cut Line= 3
      1322650.30      6930809.04      1323255.00      6930588.00
      1323759.70      6930314.24
#Sta/Elev= 30
  4355.7 2200.59  4382.0 2200.34  4400.2 2199.30  4405.5 2199.72  4413.9 2198.82
  4455.9 2198.11  4461.3 2198.59  4517.0 2197.20  4522.3 2197.83  4547.5 2197.21
  4608.6 2197.55  4626.9 2196.26  4664.4 2195.08  4725.4 2194.02  4818.5 2190.97
  4882.4 2187.89  4923.2 2184.42  4959.1 2183.08  4967.6 2181.04  4982.2 2180.23
  4982.5 2179.73  4986.1 2179.73  4986.4 2180.23  5002.4 2180.35  5029.5 2184.71
  5079.2 2187.19  5147.4 2188.38  5324.2 2195.38  5471.5 2197.25  5573.7 2199.43
#Mann=3,-1,0
  4355.7    0.07       0  4982.2    0.07       0  4986.4    0.07       0
Bank Sta=4982.2,4986.4
Exp/Cntr=0.3,0.1

Type RM Length L Ch R = 1,34170,470,470,470
BEGIN DESCRIPTION:
Buffalo Creek Trib 02 34.0
END DESCRIPTION:
XS GIS Cut Line= 3
      1322926.35      6931465.30      1323305.00      6930988.00
      1323775.32      6930366.32
#Sta/Elev= 30
  4396.3 2199.96  4450.4 2198.33  4456.8 2198.66  4464.8 2197.77  4507.7 2196.65
  4528.9 2195.39  4578.6 2194.66  4599.3 2193.57  4661.1 2192.40  4891.0 2186.04
  4905.4 2186.26  4963.1 2181.14  4981.7 2177.33  4982.0 2176.83  4986.1 2177.33
  4992.0 2177.40  4998.3 2178.69  5002.4 2181.05  5012.8 2181.21  5048.2 2183.90
  5119.0 2183.68  5291.7 2185.92  5362.4 2188.32  5377.0 2189.56  5397.8 2189.55
  5456.0 2191.32  5462.3 2192.14  5641.2 2197.72  5697.4 2197.61  5785.1 2199.33
#Mann=5,-1,0
  4396.3    0.07       0  4599.3   0.035       0  4661.1    0.07       0
  4981.7    0.07       0  4986.1    0.07       0
Bank Sta=4981.7,4986.1
Exp/Cntr=0.3,0.1

Type RM Length L Ch R = 1,33700,448,448,448
BEGIN DESCRIPTION:
Buffalo Creek Trib 02 33.0
END DESCRIPTION:
XS GIS Cut Line= 3
      1323593.03      6931548.59      1323705.00      6930938.00
      1323847.73      6930451.37
#Sta/Elev= 30
  4378.8 2200.19  4389.6 2200.99  4440.4 2201.61  4491.2 2201.32  4613.2 2197.16
  4714.9 2191.70  4816.6 2185.03  4856.6 2183.49  4867.4 2182.53  4919.9 2180.90
  4938.6 2180.88  4987.2 2175.84  4987.5 2175.34  4991.3 2175.34  4991.6 2175.84
  5002.2 2176.05  5016.3 2178.43  5021.5 2178.28  5030.8 2179.56  5062.1 2182.05
  5082.9 2183.15  5093.5 2184.57  5114.2 2184.94  5166.3 2188.53  5232.3 2190.70
  5260.1 2191.01  5291.4 2192.43  5337.7 2193.08  5404.5 2195.90  5506.7 2198.64
#Mann=3,-1,0
  4378.8    0.07       0  4987.2    0.07       0  4991.6    0.07       0
Bank Sta=4987.2,4991.6
Exp/Cntr=0.3,0.1

Type RM Length L Ch R = 1,33252,456,456,456
BEGIN DESCRIPTION:
Buffalo Creek Trib 02 32.0
END DESCRIPTION:
XS GIS Cut Line= 3
      1323811.76      6931595.52      1324055.00      6931138.00
      1324205.00      6930888.00
#Sta/Elev= 30
  4482.5 2192.47  4558.6 2191.90  4564.3 2191.38  4580.6 2191.90  4624.6 2191.30
  4706.2 2189.66  4718.1 2188.87  4844.3 2185.55  4888.3 2182.71  4898.7 2182.81
  4904.6 2181.71  4926.6 2180.81  4964.9 2177.61  4978.0 2177.22  4986.8 2175.27
  4992.5 2175.40  4995.6 2171.92  4995.9 2171.42  4999.7 2171.42  5000.0 2171.92
  5003.6 2171.92  5008.4 2175.10  5045.4 2176.54  5059.0 2176.18  5103.7 2179.17
  5117.3 2179.22  5152.3 2181.12  5167.8 2181.31  5268.9 2187.24  5292.2 2188.05
#Mann=3,-1,0
  4482.5    0.07       0  4995.6    0.07       0  5000.0    0.07       0
Bank Sta=4995.6,5000
Exp/Cntr=0.3,0.1

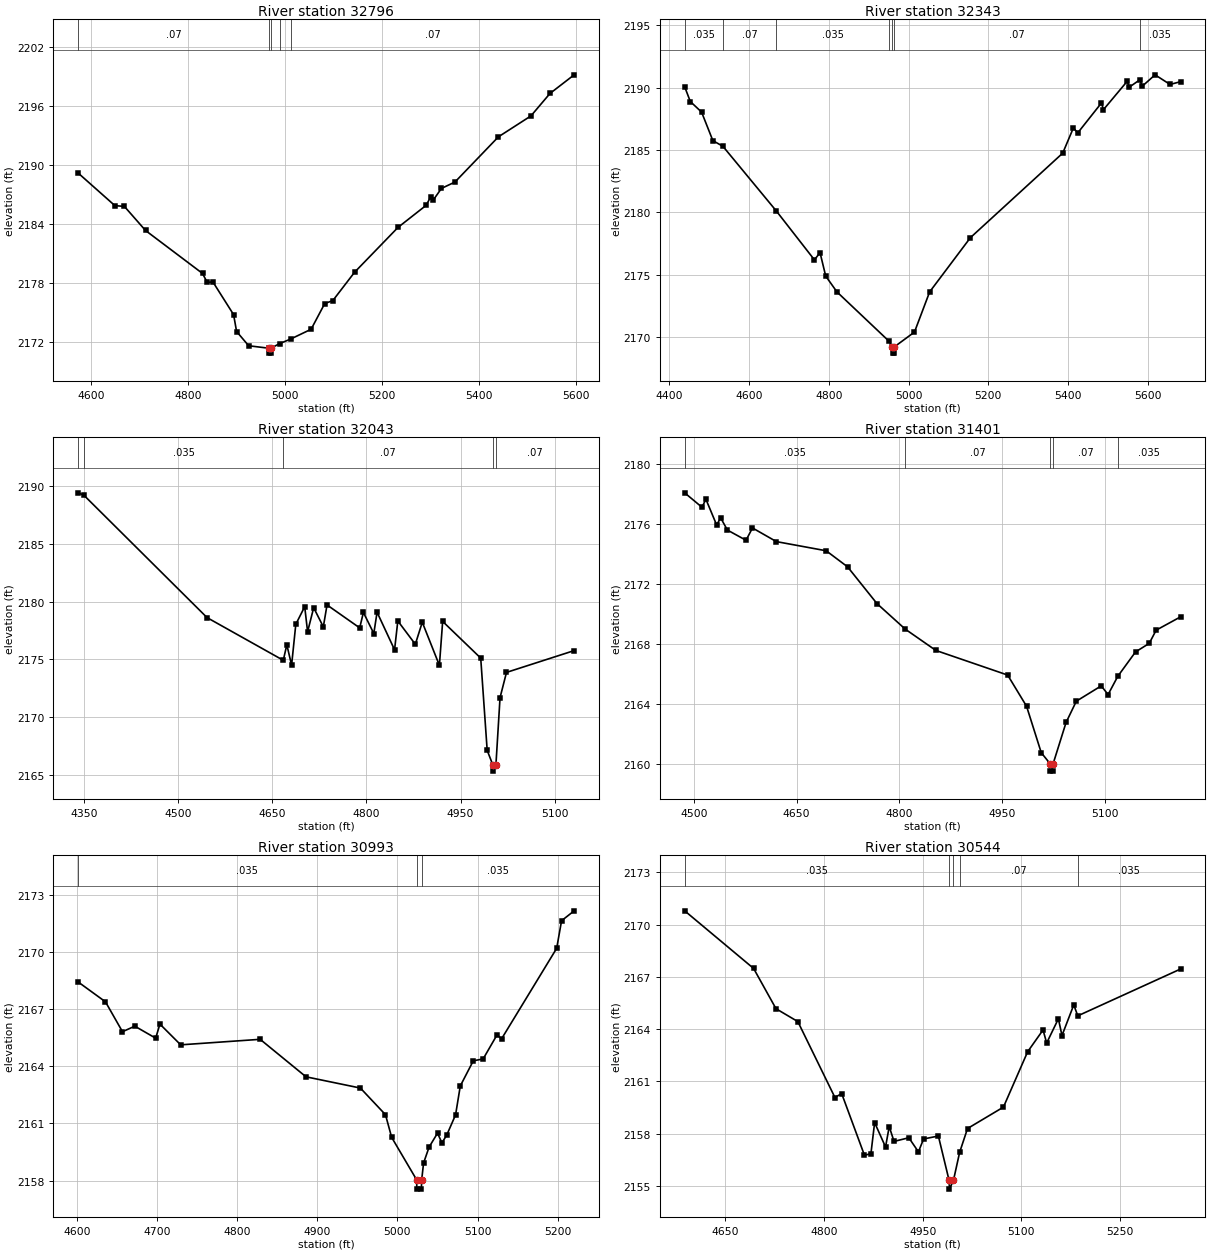
Type RM Length L Ch R = 1,32796,453,453,453
BEGIN DESCRIPTION:
Buffalo Creek Trib 02 31.0
END DESCRIPTION:
XS GIS Cut Line= 3
      1324255.01      6931737.98      1324405.00      6931338.00
      1324670.58      6930804.98
#Sta/Elev= 30
  4573.1 2189.16  4648.7 2185.85  4668.3 2185.77  4711.9 2183.32  4829.4 2178.95
  4839.2 2178.03  4850.8 2178.09  4893.5 2174.76  4899.7 2173.04  4924.6 2171.59
  4966.0 2171.34  4966.3 2170.84  4970.2 2170.84  4970.5 2171.34  4988.5 2171.81
  5011.0 2172.27  5053.4 2173.27  5081.4 2175.88  5098.2 2176.19  5143.0 2179.07
  5232.5 2183.63  5290.8 2185.89  5299.7 2186.73  5305.3 2186.42  5322.1 2187.60
  5350.0 2188.25  5439.6 2192.85  5506.7 2194.98  5545.9 2197.26  5595.8 2199.16
#Mann=5,-1,0
  4573.1    0.07       0  4966.0   0.035       0  4970.5    0.07       0
  4988.5   0.035       0  5011.0    0.07       0
Bank Sta=4966,4970.5
Exp/Cntr=0.3,0.1

Type RM Length L Ch R = 1,32343,300,300,300
BEGIN DESCRIPTION:
Buffalo Creek Trib 02 30.0
END DESCRIPTION:
XS GIS Cut Line= 3
      1324405.00      6931888.00      1324805.00      6931488.00
      1325009.25      6930841.69
#Sta/Elev= 30
  4438.6 2190.06  4452.7 2188.88  4481.0 2188.03  4509.3 2185.74  4534.4 2185.29
  4668.4 2180.10  4763.9 2176.18  4778.0 2176.76  4792.2 2174.88  4820.4 2173.61
  4951.1 2169.65  4959.6 2169.20  4959.9 2168.70  4963.8 2168.70  4964.2 2169.20
  5014.8 2170.39  5052.8 2173.61  5155.0 2177.96  5386.5 2184.74  5413.3 2186.77
  5424.1 2186.36  5483.5 2188.76  5488.7 2188.23  5548.1 2190.50  5553.4 2190.03
  5580.1 2190.63  5585.7 2190.10  5618.0 2191.02  5655.6 2190.25  5682.1 2190.47
#Mann=7,-1,0
  4438.6   0.035       0  4534.4    0.07       0  4668.4   0.035       0
  4951.1    0.07       0  4959.6    0.07       0  4964.2    0.07       0
  5580.1   0.035       0
Bank Sta=4959.6,4964.2
Exp/Cntr=0.3,0.1

Type RM Length L Ch R = 1,32043,642,642,642
BEGIN DESCRIPTION:
Buffalo Creek Trib 02 29.0
END DESCRIPTION:
XS GIS Cut Line= 5
      1324704.98      6932188.02      1324946.08      6931912.04
      1324998.16      6931827.40      1325035.05      6931703.70
      1325080.01      6931512.95
#Sta/Elev= 30
  4340.3 2189.44  4349.2 2189.24  4545.8 2178.62  4667.3 2174.92  4673.0 2176.26
  4680.6 2174.50  4687.3 2178.04  4701.5 2179.57  4706.1 2177.39  4715.8 2179.48
  4731.2 2177.82  4737.1 2179.72  4789.2 2177.73  4795.1 2179.07  4811.7 2177.24
  4816.9 2179.09  4844.8 2175.83  4850.0 2178.33  4877.9 2176.31  4889.0 2178.22
  4916.3 2174.48  4921.5 2178.29  4982.2 2175.11  4992.5 2167.11  5001.8 2165.81
  5002.1 2165.31  5006.4 2165.81  5013.0 2171.68  5023.3 2173.87  5131.2 2175.76
#Mann=5,-1,0
  4340.3    0.07       0  4349.2   0.035       0  4667.3    0.07       0
  5001.8    0.07       0  5006.4    0.07       0
Bank Sta=5001.8,5006.4
Exp/Cntr=0.3,0.1

Type RM Length L Ch R = 1,31401,408,408,408
BEGIN DESCRIPTION:
Buffalo Creek Trib 02 28.0
END DESCRIPTION:
XS GIS Cut Line= 4
      1324989.99      6932226.88      1325431.32      6931964.76
      1325482.29      6931931.23      1325488.76      6931782.28
#Sta/Elev= 30
  4486.7 2178.05  4511.9 2177.09  4517.7 2177.62  4533.3 2175.91  4539.2 2176.38
  4549.0 2175.57  4576.2 2174.89  4585.6 2175.71  4620.5 2174.80  4693.1 2174.19
  4724.3 2173.12  4767.2 2170.67  4808.4 2168.97  4853.1 2167.55  4957.8 2165.91
  4985.4 2163.83  5006.8 2160.74  5019.6 2160.01  5019.9 2159.51  5023.9 2159.51
  5024.2 2160.01  5043.0 2162.75  5058.0 2164.17  5094.3 2165.19  5104.3 2164.61
  5118.5 2165.83  5144.3 2167.45  5164.3 2168.02  5174.4 2168.90  5210.1 2169.79
#Mann=5,-1,0
  4486.7   0.035       0  4808.4    0.07       0  5019.6    0.07       0
  5024.2    0.07       0  5118.5   0.035       0
Bank Sta=5019.6,5024.2
Exp/Cntr=0.3,0.1

Type RM Length L Ch R = 1,30993,449,449,449
BEGIN DESCRIPTION:
Buffalo Creek Trib 02 27.0
END DESCRIPTION:
XS GIS Cut Line= 3
      1325332.81      6932365.79      1325705.00      6932238.00
      1325909.21      6932143.57
#Sta/Elev= 30
  4601.9 2168.43  4635.9 2167.39  4657.1 2165.82  4672.5 2166.11  4698.5 2165.48
  4703.8 2166.22  4729.7 2165.13  4828.8 2165.42  4886.0 2163.45  4953.8 2162.86
  4985.1 2161.46  4992.8 2160.27  5023.8 2158.05  5024.3 2157.55  5029.8 2157.55
  5030.3 2158.05  5032.6 2158.92  5039.5 2159.76  5050.0 2160.49  5055.5 2159.98
  5061.5 2160.39  5072.5 2161.45  5078.4 2162.97  5094.6 2164.29  5106.9 2164.39
  5124.3 2165.66  5129.8 2165.44  5198.6 2170.20  5204.7 2171.65  5220.4 2172.17
#Mann=3,-1,0
  4601.9   0.035       0  5023.8   0.035       0  5030.3   0.035       0
Bank Sta=5023.8,5030.3
Exp/Cntr=0.3,0.1

Type RM Length L Ch R = 1,30544,448,448,448
BEGIN DESCRIPTION:
Buffalo Creek Trib 02 26.0
END DESCRIPTION:
XS GIS Cut Line= 3
      1325241.69      6932773.77      1325605.00      6932588.00
      1325921.55      6932448.94
#Sta/Elev= 30
  4588.2 2170.79  4693.0 2167.48  4727.0 2165.17  4760.2 2164.43  4816.6 2160.07
  4826.8 2160.30  4861.5 2156.75  4871.3 2156.85  4876.9 2158.63  4893.5 2157.23
  4899.1 2158.40  4906.4 2157.55  4928.9 2157.76  4943.5 2156.95  4951.3 2157.69
  4973.8 2157.86  4990.1 2155.31  4990.6 2154.81  4996.7 2155.31  5006.1 2156.92
  5018.1 2158.29  5072.7 2159.52  5109.5 2162.70  5132.9 2163.95  5138.4 2163.20
  5156.2 2164.59  5161.7 2163.63  5179.6 2165.39  5185.7 2164.76  5342.0 2167.45
#Mann=5,-1,0
  4588.2   0.035       0  4990.1   0.035       0  4996.7   0.035       0
  5006.1    0.07       0  5185.7   0.035       0
Bank Sta=4990.1,4996.7
Exp/Cntr=0.3,0.1

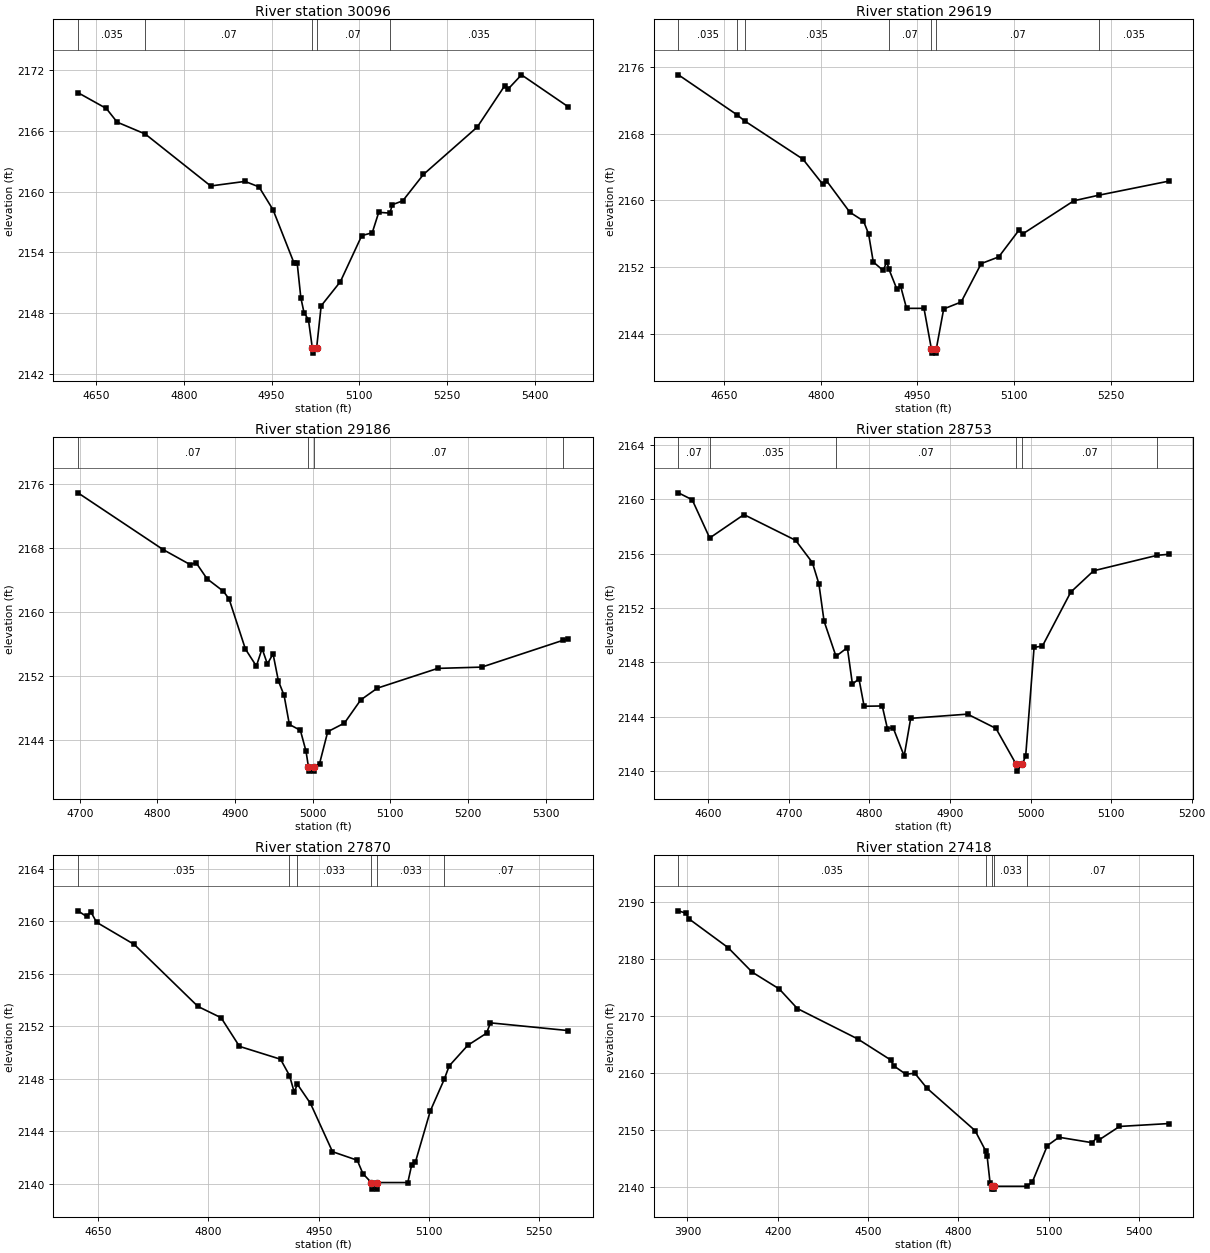
Type RM Length L Ch R = 1,30096,477,477,477
BEGIN DESCRIPTION:
Buffalo Creek Trib 02 25.0
END DESCRIPTION:
XS GIS Cut Line= 3
      1325410.92      6933129.69      1325755.00      6932988.00
      1326181.73      6932799.80
#Sta/Elev= 30
  4619.1 2169.76  4667.6 2168.20  4686.1 2166.85  4734.1 2165.68  4846.0 2160.55
  4904.7 2161.00  4928.6 2160.46  4952.6 2158.20  4988.5 2152.94  4993.9 2152.94
  5000.1 2149.53  5005.6 2148.04  5013.1 2147.36  5019.8 2144.55  5020.3 2144.05
  5027.1 2144.55  5034.9 2148.72  5067.7 2151.10  5104.3 2155.65  5122.2 2155.93
  5133.3 2157.95  5152.4 2157.87  5156.5 2158.70  5174.3 2159.08  5209.8 2161.69
  5301.8 2166.37  5348.5 2170.43  5353.9 2170.08  5377.3 2171.52  5457.6 2168.35
#Mann=5,-1,0
  4619.1   0.035       0  4734.1    0.07       0  5019.8    0.07       0
  5027.1    0.07       0  5152.4   0.035       0
Bank Sta=5019.8,5027.1
Exp/Cntr=0.3,0.1

Type RM Length L Ch R = 1,29619,433,433,433
BEGIN DESCRIPTION:
Buffalo Creek Trib 02 24.0
END DESCRIPTION:
XS GIS Cut Line= 3
      1325545.49      6933615.80      1325905.00      6933388.00
      1326193.91      6933215.69
#Sta/Elev= 30
  4578.6 2175.10  4669.2 2170.32  4681.5 2169.56  4772.0 2164.97  4802.5 2161.98
  4808.4 2162.40  4844.9 2158.59  4866.1 2157.54  4874.0 2155.99  4881.3 2152.62
  4896.6 2151.59  4902.5 2152.66  4905.5 2151.77  4917.8 2149.38  4923.7 2149.73
  4933.0 2147.04  4960.1 2147.04  4971.6 2142.16  4972.1 2141.66  4978.7 2141.66
  4979.2 2142.16  4990.7 2146.97  5017.8 2147.80  5049.0 2152.42  5076.2 2153.22
  5107.4 2156.41  5113.2 2155.97  5193.0 2159.97  5231.3 2160.63  5340.6 2162.33
#Mann=7,-1,0
  4578.6   0.035       0  4669.2    0.07       0  4681.5   0.035       0
  4905.5    0.07       0  4971.6    0.07       0  4979.2    0.07       0
  5231.3   0.035       0
Bank Sta=4971.6,4979.2
Exp/Cntr=0.3,0.1

Type RM Length L Ch R = 1,29186,433,433,433
BEGIN DESCRIPTION:
Buffalo Creek Trib 02 23.0
END DESCRIPTION:
XS GIS Cut Line= 3
      1325779.90      6933997.71      1326005.00      6933788.00
      1326227.12      6933552.33
#Sta/Elev= 30
  4697.7 2174.94  4807.2 2167.85  4842.4 2165.95  4849.7 2166.21  4863.9 2164.19
  4884.9 2162.63  4892.3 2161.66  4913.3 2155.40  4927.4 2153.27  4934.8 2155.45
  4941.6 2153.53  4948.9 2154.80  4955.8 2151.40  4963.1 2149.61  4969.9 2145.97
  4984.1 2145.23  4991.4 2142.59  4994.5 2140.63  4995.0 2140.13  5001.6 2140.13
  5002.1 2140.63  5008.8 2141.08  5019.3 2145.06  5040.8 2146.14  5061.8 2149.04
  5083.2 2150.51  5160.9 2152.98  5217.6 2153.14  5322.7 2156.51  5329.2 2156.68
#Mann=4,-1,0
  4697.7    0.07       0  4994.5    0.07       0  5002.1    0.07       0
  5322.7   0.035       0
Bank Sta=4994.5,5002.1
Exp/Cntr=0.3,0.1

Type RM Length L Ch R = 1,28753,883,883,883
BEGIN DESCRIPTION:
Buffalo Creek Trib 02 22.0
END DESCRIPTION:
XS GIS Cut Line= 3
      1326005.60      6934062.82      1326355.00      6933788.00
      1326477.81      6933679.20
#Sta/Elev= 30
  4563.1 2160.47  4580.2 2159.96  4601.9 2157.15  4644.4 2158.87  4708.5 2156.98
  4729.3 2155.34  4737.4 2153.78  4743.8 2151.04  4758.6 2148.45  4772.7 2149.09
  4779.0 2146.40  4787.1 2146.80  4793.5 2144.78  4816.0 2144.80  4822.4 2143.14
  4829.5 2143.20  4843.2 2141.12  4851.3 2143.89  4921.8 2144.20  4957.1 2143.15
  4982.2 2140.51  4982.7 2140.01  4989.8 2140.51  4994.0 2141.14  5004.4 2149.11
  5014.7 2149.20  5049.9 2153.17  5078.3 2154.74  5157.4 2155.88  5171.7 2155.95
#Mann=6,-1,0
  4563.1    0.07       0  4601.9   0.035       0  4758.6    0.07       0
  4982.2    0.07       0  4989.8    0.07       0  5157.4   0.035       0
Bank Sta=4982.2,4989.8
Exp/Cntr=0.3,0.1

Type RM Length L Ch R = 1,27870,452,452,452
BEGIN DESCRIPTION:
Buffalo Creek Trib 02 21.0
END DESCRIPTION:
XS GIS Cut Line= 4
      1326483.00      6934650.57      1326675.72      6934541.19
      1326705.00      6934388.00      1326761.67      6934103.65
#Sta/Elev= 30
  4622.4 2160.78  4634.1 2160.35  4639.8 2160.72  4647.7 2159.91  4699.0 2158.22
  4785.7 2153.50  4817.2 2152.64  4842.2 2150.46  4898.1 2149.48  4910.3 2148.24
  4916.7 2146.98  4921.0 2147.58  4938.9 2146.11  4968.8 2142.44  5002.5 2141.79
  5010.2 2140.77  5021.6 2140.09  5022.1 2139.59  5028.8 2139.59  5029.3 2140.09
  5071.3 2140.09  5076.6 2141.44  5081.7 2141.66  5101.9 2145.54  5120.8 2147.94
  5127.6 2148.97  5152.9 2150.54  5178.4 2151.46  5183.8 2152.25  5289.9 2151.66
#Mann=6,-1,0
  4622.4   0.035       0  4910.3    0.07       0  4921.0   0.033       0
  5021.6   0.033       0  5029.3   0.033       0  5120.8    0.07       0
Bank Sta=5021.6,5029.3
Exp/Cntr=0.3,0.1

Type RM Length L Ch R = 1,27418,298,298,298
BEGIN DESCRIPTION:
Buffalo Creek Trib 02 20.0
END DESCRIPTION:
XS GIS Cut Line= 4
      1325770.10      6934725.70      1326905.00      6934738.00
      1327006.05      6934735.30      1326965.82      6934344.73
#Sta/Elev= 30
  3870.1 2188.52  3895.0 2188.10  3905.0 2187.11  4035.0 2182.05  4115.0 2177.74
  4205.0 2174.78  4265.0 2171.34  4465.0 2166.01  4575.0 2162.30  4585.0 2161.27
  4625.0 2159.80  4655.1 2159.96  4695.1 2157.35  4855.1 2149.88  4890.1 2146.34
  4895.1 2145.42  4905.1 2140.59  4911.2 2140.09  4911.7 2139.59  4918.4 2139.59
  4918.9 2140.09  5027.9 2140.09  5045.1 2140.83  5095.1 2147.24  5133.6 2148.71
  5244.2 2147.75  5261.1 2148.75  5266.1 2148.22  5334.7 2150.61  5498.8 2151.12
#Mann=5,-1,0
  3870.1   0.035       0  4890.1   0.033       0  4911.2   0.033       0
  4918.9   0.033       0  5027.9    0.07       0
Bank Sta=4911.2,4918.9
Exp/Cntr=0.3,0.1

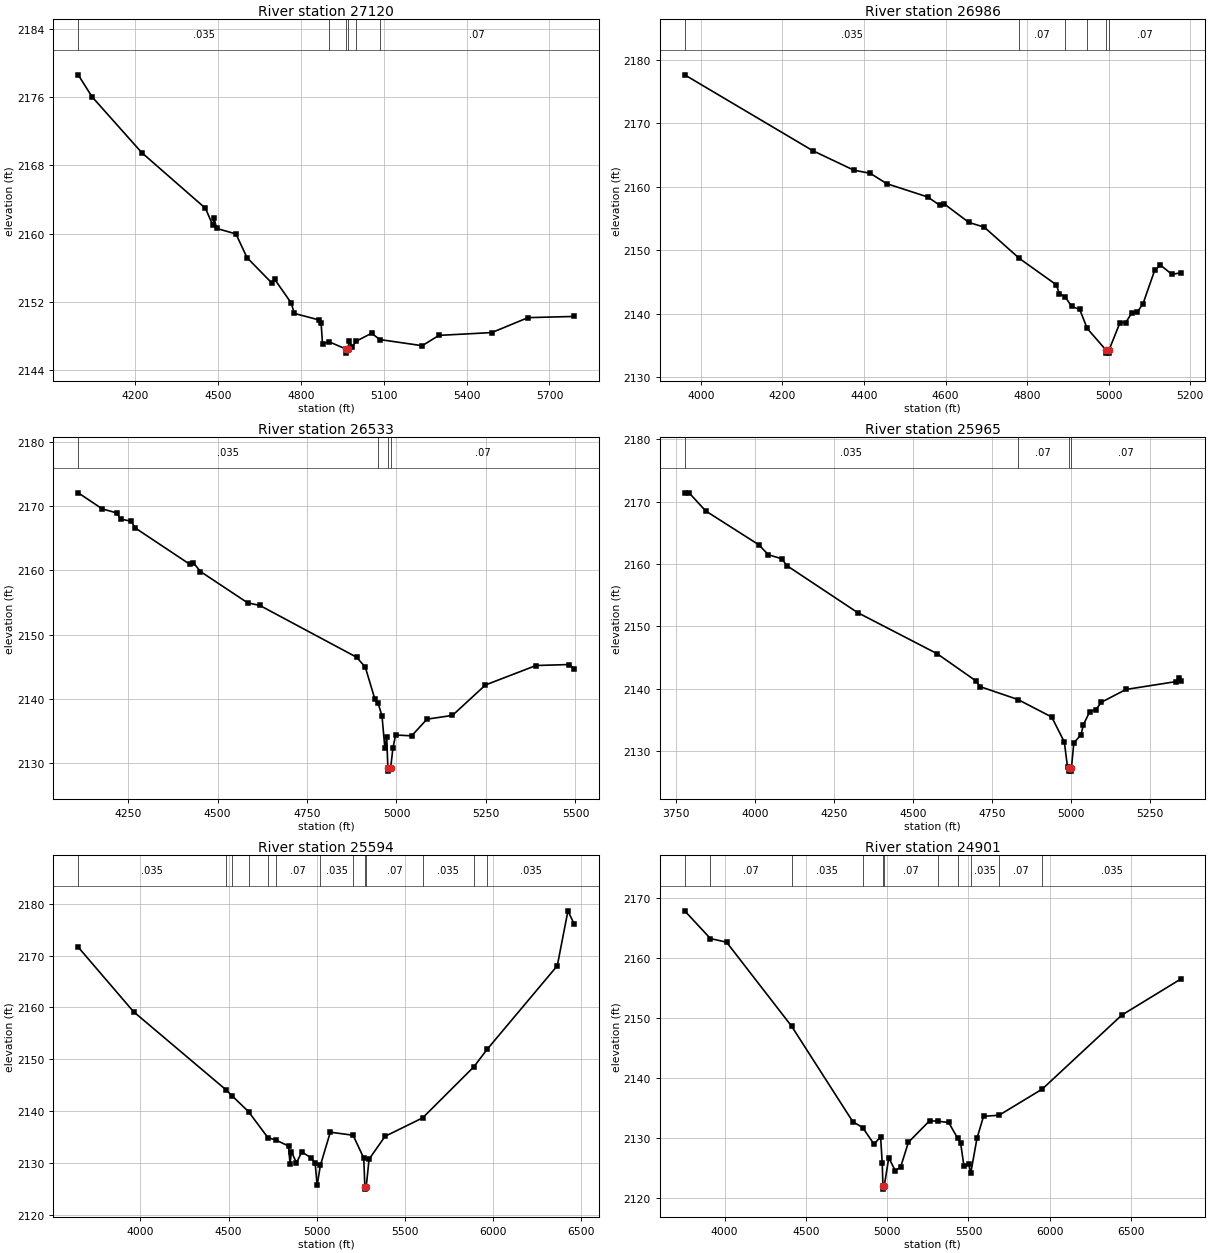
Type RM Length L Ch R = 1,27120,134,134,134
BEGIN DESCRIPTION:
Buffalo Creek Trib 02 19.5
END DESCRIPTION:
XS GIS Cut Line= 4
      1325975.53      6934961.72      1326786.31      6935013.80
      1327084.92      6935010.33      1327003.41      6934332.29
#Sta/Elev= 30
  3995.2 2178.60  4044.8 2176.04  4225.1 2169.48  4455.6 2162.95  4481.9 2160.97
  4486.9 2161.79  4495.7 2160.60  4565.8 2159.95  4605.9 2157.17  4696.1 2154.18
  4706.1 2154.62  4766.3 2151.83  4776.3 2150.64  4866.3 2149.87  4873.9 2149.46
  4878.9 2147.09  4902.4 2147.31  4962.5 2146.48  4963.0 2145.98  4970.2 2146.48
  4976.3 2147.38  4986.3 2146.74  5001.5 2147.39  5056.4 2148.31  5086.3 2147.57
  5239.6 2146.85  5300.0 2148.06  5491.4 2148.39  5622.3 2150.14  5789.2 2150.28
#Mann=6,-1,0
  3995.2   0.035       0  4902.4    0.07       0  4962.5    0.07       0
  4970.2    0.07       0  5001.5   0.035       0  5086.3    0.07       0
Bank Sta=4962.5,4970.2
Exp/Cntr=0.3,0.1

Type RM Length L Ch R = 1,26986,453,453,453
BEGIN DESCRIPTION:
Buffalo Creek Trib 02 19.0
END DESCRIPTION:
XS GIS Cut Line= 3
      1325973.24      6935017.37      1327005.00      6935138.00
      1327130.03      6935012.97
#Sta/Elev= 30
  3960.5 2177.60  4274.4 2165.66  4375.1 2162.59  4415.3 2162.10  4455.6 2160.47
  4556.3 2158.37  4586.5 2157.03  4596.6 2157.28  4657.0 2154.37  4695.0 2153.61
  4781.0 2148.69  4871.8 2144.53  4878.5 2143.15  4892.9 2142.69  4908.7 2141.16
  4928.8 2140.66  4947.2 2137.67  4992.9 2134.29  4993.4 2133.79  5000.2 2133.79
  5000.7 2134.29  5027.6 2138.61  5041.7 2138.61  5055.9 2140.07  5070.0 2140.24
  5084.1 2141.60  5112.4 2146.80  5126.6 2147.65  5154.8 2146.19  5176.1 2146.43
#Mann=6,-1,0
  3960.5   0.035       0  4781.0    0.07       0  4892.9   0.035       0
  4947.2    0.07       0  4992.9    0.07       0  5000.7    0.07       0
Bank Sta=4992.9,5000.7
Exp/Cntr=0.3,0.1

Type RM Length L Ch R = 1,26533,568,568,568
BEGIN DESCRIPTION:
Buffalo Creek Trib 02 18.0
END DESCRIPTION:
XS GIS Cut Line= 3
      1325978.45      6935387.16      1326855.00      6935538.00
      1327230.02      6935212.98
#Sta/Elev= 30
  4110.7 2172.05  4178.2 2169.54  4218.8 2168.92  4229.0 2167.96  4258.7 2167.64
  4269.6 2166.60  4421.8 2160.96  4431.9 2161.21  4452.2 2159.81  4584.1 2154.94
  4618.2 2154.53  4888.5 2146.48  4912.8 2144.94  4939.3 2140.02  4948.1 2139.43
  4959.5 2137.34  4967.6 2132.30  4972.7 2134.02  4975.9 2129.26  4976.4 2128.76
  4983.7 2129.26  4990.0 2132.34  4997.6 2134.38  5042.4 2134.25  5085.1 2136.84
  5156.4 2137.43  5248.5 2142.16  5390.0 2145.19  5482.1 2145.34  5496.4 2144.70
#Mann=4,-1,0
  4110.7   0.035       0  4948.1    0.07       0  4975.9    0.07       0
  4983.7    0.07       0
Bank Sta=4975.9,4983.7
Exp/Cntr=0.3,0.1

Type RM Length L Ch R = 1,25965,371,371,371
BEGIN DESCRIPTION:
Buffalo Creek Trib 02 17.0
END DESCRIPTION:
XS GIS Cut Line= 5
      1325931.61      6935475.72      1326981.24      6935804.35
      1327104.97      6935804.35      1327204.77      6935800.01
      1327280.01      6935562.96
#Sta/Elev= 30
  3776.4 2171.34  3790.4 2171.44  3842.8 2168.54  4010.5 2163.13  4041.9 2161.50
  4083.8 2160.86  4100.8 2159.74  4324.8 2152.21  4576.3 2145.63  4700.6 2141.22
  4712.6 2140.34  4833.0 2138.26  4940.0 2135.45  4980.0 2131.44  4990.0 2127.40
  4993.6 2127.27  4994.1 2126.77  5001.0 2126.77  5001.5 2127.27  5002.5 2127.27
  5010.0 2131.29  5033.1 2132.63  5040.1 2134.18  5060.1 2136.28  5080.1 2136.65
  5097.5 2137.83  5175.4 2139.88  5332.8 2141.13  5343.3 2141.75  5348.6 2141.30
#Mann=4,-1,0
  3776.4   0.035       0  4833.0    0.07       0  4993.6    0.07       0
  5001.5    0.07       0
Bank Sta=4993.6,5001.5
Exp/Cntr=0.3,0.1

Type RM Length L Ch R = 1,25594,693,693,693
BEGIN DESCRIPTION:
Buffalo Creek Trib 02 16.0
END DESCRIPTION:
XS GIS Cut Line= 4
      1325889.88      6935532.98      1327105.00      6936138.00
      1327230.00      6936213.00      1328529.99      6936063.00
#Sta/Elev= 30
  3647.9 2171.63  3961.4 2159.18  4486.1 2144.09  4522.4 2142.87  4613.8 2139.87
  4722.8 2134.89  4770.3 2134.37  4840.2 2133.26  4848.9 2129.84  4857.0 2132.16
  4885.0 2130.00  4915.9 2132.11  4968.9 2130.95  4991.3 2129.92  5002.5 2125.65
  5020.9 2129.51  5077.2 2135.92  5206.4 2135.33  5266.8 2130.92  5273.0 2125.43
  5273.5 2124.93  5280.9 2125.43  5297.0 2130.71  5387.6 2135.12  5600.7 2138.68
  5891.7 2148.56  5966.4 2151.91  6364.1 2168.04  6424.5 2178.64  6459.7 2176.08
#Mann=13,-1,0
  3647.9   0.035       0  4486.1    0.07       0  4522.4   0.035       0
  4613.8    0.07       0  4722.8   0.035       0  4770.3    0.07       0
  5020.9   0.035       0  5206.4    0.07       0  5273.0    0.07       0
  5280.9    0.07       0  5600.7   0.035       0  5891.7    0.07       0
  5966.4   0.035       0
Bank Sta=5273,5280.9
Exp/Cntr=0.3,0.1

Type RM Length L Ch R = 1,24901,622,622,622
BEGIN DESCRIPTION:
Buffalo Creek Trib 02 16.5
END DESCRIPTION:
XS GIS Cut Line= 4
      1325697.92      6936054.60      1326618.95      6936576.06
      1327480.00      6936663.00      1328606.83      6936645.50
#Sta/Elev= 30
  3754.1 2167.88  3912.4 2163.26  4012.0 2162.65  4412.4 2148.64  4788.4 2132.75
  4848.9 2131.78  4919.1 2129.00  4959.3 2130.25  4969.3 2125.85  4973.8 2122.02
  4974.3 2121.52  4981.8 2122.02  5009.5 2126.74  5049.8 2124.58  5082.8 2125.21
  5130.2 2129.32  5260.8 2132.91  5314.3 2132.82  5377.9 2132.63  5433.2 2130.00
  5451.8 2129.16  5471.9 2125.38  5502.0 2125.69  5513.8 2124.16  5552.3 2130.00
  5592.5 2133.65  5688.1 2133.83  5954.0 2138.19  6443.0 2150.51  6804.9 2156.50
#Mann=11,-1,0
  3754.1   0.035       0  3912.4    0.07       0  4412.4   0.035       0
  4848.9    0.07       0  4973.8    0.07       0  4981.8    0.07       0
  5314.3   0.035       0  5433.2    0.07       0  5513.8   0.035       0
  5688.1    0.07       0  5954.0   0.035       0
Bank Sta=4973.8,4981.8
Exp/Cntr=0.3,0.1

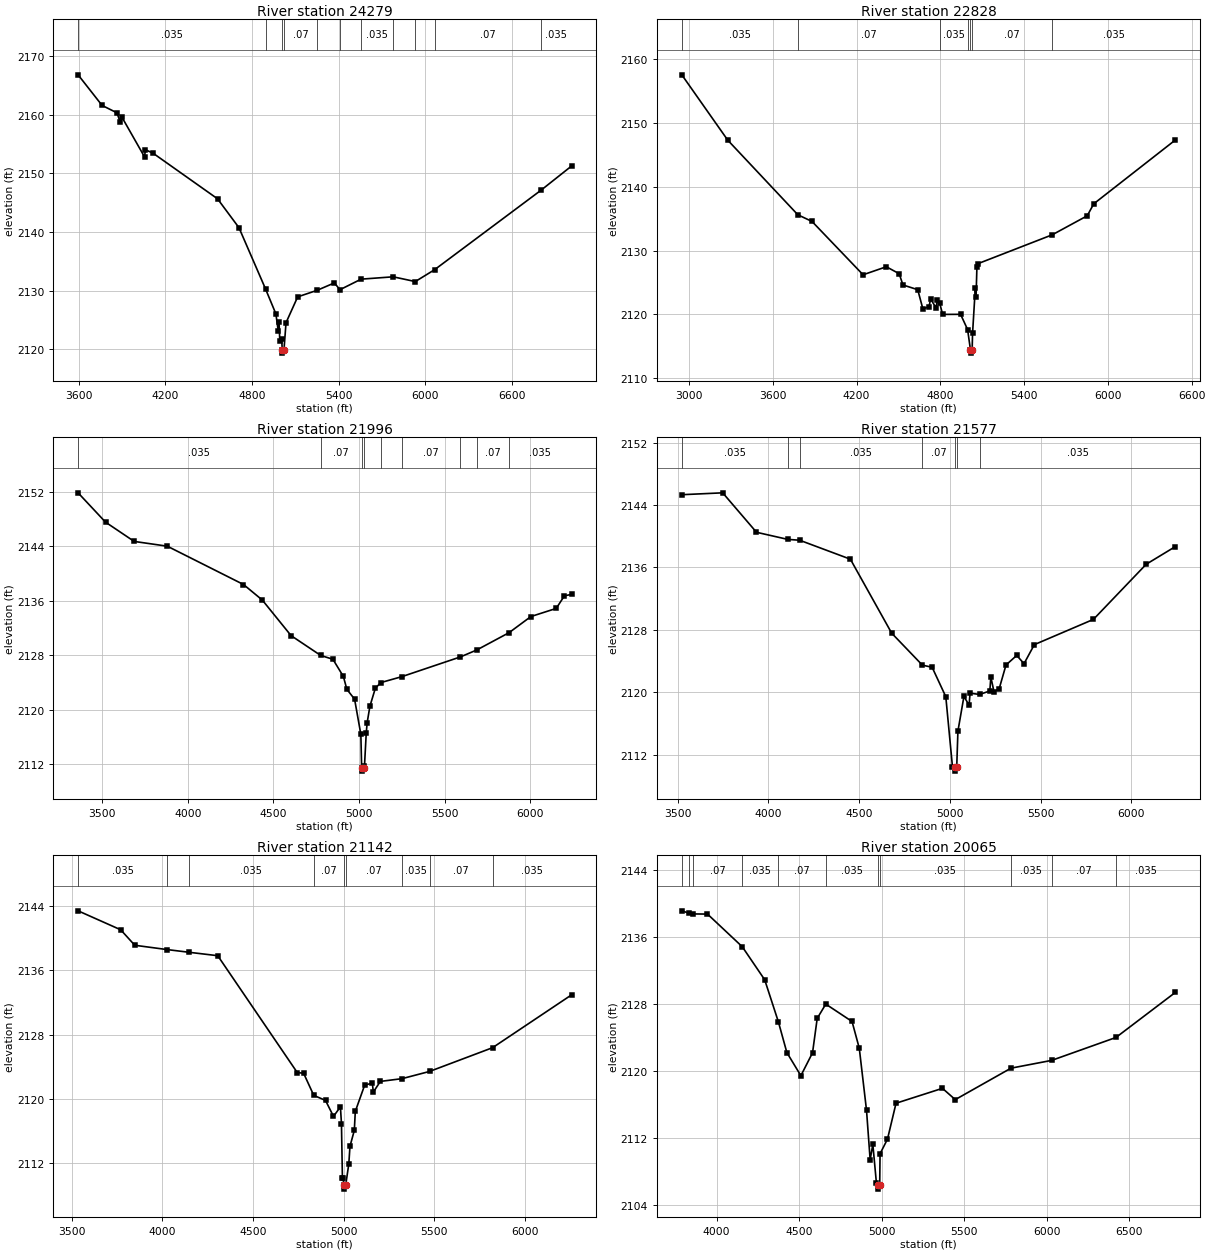
Type RM Length L Ch R = 1,24279,1451,1451,1451
BEGIN DESCRIPTION:
Buffalo Creek Trib 02 15.0
END DESCRIPTION:
XS GIS Cut Line= 5
      1325379.51      6936408.01      1326450.32      6937002.17
      1326605.00      6937088.00      1326780.00      6937113.00
      1328601.70      6936830.14
#Sta/Elev= 30
  3594.1 2166.80  3760.5 2161.58  3863.4 2160.32  3886.3 2158.74  3898.2 2159.57
  4055.0 2152.79  4060.7 2154.03  4114.5 2153.42  4561.0 2145.65  4709.7 2140.72
  4893.8 2130.28  4965.8 2126.01  4981.9 2123.14  4987.6 2124.60  4992.7 2121.44
  5005.7 2121.74  5010.1 2119.82  5010.6 2119.32  5021.6 2119.82  5036.0 2124.51
  5116.8 2128.92  5251.1 2130.03  5371.3 2131.30  5410.0 2130.14  5556.6 2131.94
  5779.1 2132.34  5932.4 2131.53  6066.1 2133.55  6805.2 2147.13  7015.9 2151.24
#Mann=11,-1,0
  3594.1   0.035       0  4893.8    0.07       0  5010.1    0.07       0
  5021.6    0.07       0  5251.1   0.035       0  5410.0    0.07       0
  5556.6   0.035       0  5779.1    0.07       0  5932.4   0.035       0
  6066.1    0.07       0  6805.2   0.035       0
Bank Sta=5010.1,5021.6
Exp/Cntr=0.3,0.1

Type RM Length L Ch R = 1,22828,832,832,832
BEGIN DESCRIPTION:
Buffalo Creek Trib 02 14.0
END DESCRIPTION:
XS GIS Cut Line= 4
      1325513.41      6937836.97      1327305.99      6937450.67
      1327505.00      6937538.00      1328931.84      6937134.33
#Sta/Elev= 30
  2948.8 2157.58  3277.8 2147.32  3779.7 2135.61  3881.3 2134.56  4246.9 2126.19
  4413.3 2127.45  4505.3 2126.36  4532.5 2124.59  4638.3 2123.85  4675.3 2120.82
  4719.5 2121.19  4730.4 2122.39  4768.8 2121.03  4779.5 2122.24  4795.1 2121.79
  4816.4 2119.97  4945.3 2119.98  4995.4 2117.59  5016.1 2114.39  5016.6 2113.89
  5027.9 2114.39  5031.0 2117.00  5050.8 2124.18  5056.0 2122.75  5062.2 2127.44
  5072.6 2127.96  5602.0 2132.47  5852.0 2135.45  5899.3 2137.34  6482.7 2147.34
#Mann=7,-1,0
  2948.8   0.035       0  3779.7    0.07       0  4795.1   0.035       0
  4995.4    0.07       0  5016.1    0.07       0  5027.9    0.07       0
  5602.0   0.035       0
Bank Sta=5016.1,5027.9
Exp/Cntr=0.3,0.1

Type RM Length L Ch R = 1,21996,419,419,419
BEGIN DESCRIPTION:
Buffalo Creek Trib 02 13.0
END DESCRIPTION:
XS GIS Cut Line= 3
      1325843.31      6938192.86      1327455.00      6937888.00
      1328629.75      6937489.74
#Sta/Elev= 30
  3359.7 2151.83  3519.8 2147.53  3687.1 2144.70  3880.5 2144.00  4325.3 2138.38
  4435.1 2136.10  4603.1 2130.88  4776.2 2127.97  4847.3 2127.41  4908.4 2124.89
  4928.7 2123.00  4973.8 2121.56  5010.4 2116.40  5015.1 2111.50  5015.6 2111.00
  5027.0 2111.50  5031.7 2111.80  5041.8 2116.54  5047.1 2118.09  5063.3 2120.52
  5095.0 2123.16  5127.0 2123.99  5249.6 2124.86  5592.1 2127.76  5687.6 2128.78
  5876.1 2131.32  6003.1 2133.68  6150.9 2134.87  6198.8 2136.72  6240.4 2136.93
#Mann=9,-1,0
  3359.7   0.035       0  4776.2    0.07       0  5015.1    0.07       0
  5027.0    0.07       0  5127.0   0.035       0  5249.6    0.07       0
  5592.1   0.035       0  5687.6    0.07       0  5876.1   0.035       0
Bank Sta=5015.1,5027
Exp/Cntr=0.3,0.1

Type RM Length L Ch R = 1,21577,435,435,435
BEGIN DESCRIPTION:
Buffalo Creek Trib 02 12.0
END DESCRIPTION:
XS GIS Cut Line= 3
      1326277.34      6938566.13      1327705.00      6938188.00
      1328830.04      6937662.98
#Sta/Elev= 30
  3523.1 2145.33  3748.3 2145.57  3934.5 2140.51  4106.6 2139.60  4172.3 2139.49
  4451.7 2137.06  4679.3 2127.57  4848.4 2123.47  4902.0 2123.20  4977.3 2119.43
  5014.2 2110.41  5025.6 2110.38  5026.1 2109.88  5037.5 2110.38  5044.1 2115.00
  5077.2 2119.46  5105.6 2118.34  5111.1 2119.88  5163.9 2119.71  5219.9 2120.17
  5225.4 2121.94  5242.8 2120.08  5271.1 2120.42  5309.0 2123.49  5368.1 2124.72
  5408.3 2123.66  5465.0 2126.10  5790.6 2129.34  6081.4 2136.41  6241.5 2138.67
#Mann=7,-1,0
  3523.1   0.035       0  4106.6    0.07       0  4172.3   0.035       0
  4848.4    0.07       0  5025.6    0.07       0  5037.5    0.07       0
  5163.9   0.035       0
Bank Sta=5025.6,5037.5
Exp/Cntr=0.3,0.1

Type RM Length L Ch R = 1,21142,1077,1077,1077
BEGIN DESCRIPTION:
Buffalo Creek Trib 02 11.0
END DESCRIPTION:
XS GIS Cut Line= 5
      1326346.80      6938696.33      1327650.42      6938382.09
      1327755.00      6938438.00      1327866.57      6938483.65
      1328879.96      6937963.02
#Sta/Elev= 30
  3536.3 2143.42  3771.0 2141.06  3848.7 2139.13  4027.7 2138.59  4146.5 2138.26
  4305.9 2137.83  4744.2 2123.27  4779.1 2123.19  4835.1 2120.43  4899.9 2119.80
  4943.8 2117.81  4982.0 2119.00  4987.7 2116.92  4993.0 2110.12  4998.5 2110.12
  4999.1 2109.25  4999.6 2108.75  5011.1 2109.25  5028.3 2111.91  5034.6 2114.08
  5058.6 2116.07  5064.0 2118.43  5115.5 2121.70  5157.8 2121.96  5163.4 2120.84
  5202.1 2122.17  5321.1 2122.51  5473.0 2123.41  5820.6 2126.37  6255.7 2132.95
#Mann=9,-1,0
  3536.3   0.035       0  4027.7    0.07       0  4146.5   0.035       0
  4835.1    0.07       0  4999.1    0.07       0  5011.1    0.07       0
  5321.1   0.035       0  5473.0    0.07       0  5820.6   0.035       0
Bank Sta=4999.1,5011.1
Exp/Cntr=0.3,0.1

Type RM Length L Ch R = 1,20065,746,746,746
BEGIN DESCRIPTION:
Buffalo Creek Trib 02 10.0
END DESCRIPTION:
XS GIS Cut Line= 5
      1326580.01      6940062.99      1327235.27      6939431.96
      1327500.78      6939289.75      1327832.77      6939200.52
      1328802.35      6938141.91
#Sta/Elev= 30
  3789.1 2139.11  3829.7 2138.85  3856.7 2138.74  3944.7 2138.72  4155.3 2134.82
  4291.3 2130.87  4374.7 2125.81  4425.6 2122.17  4510.5 2119.40  4581.2 2122.14
  4609.5 2126.25  4661.5 2127.96  4820.6 2125.88  4864.5 2122.68  4908.4 2115.25
  4930.3 2109.36  4946.6 2111.19  4968.5 2106.53  4976.0 2106.34  4976.5 2105.84
  4988.2 2106.34  4990.4 2110.07  5035.4 2111.82  5087.2 2116.11  5368.4 2117.89
  5446.1 2116.54  5783.7 2120.30  6030.1 2121.23  6419.9 2123.97  6779.3 2129.35
#Mann=11,-1,0
  3789.1    0.07       0  3829.7   0.035       0  3856.7    0.07       0
  4155.3   0.035       0  4374.7    0.07       0  4661.5   0.035       0
  4976.0    0.07       0  4988.2   0.035       0  5783.7   0.035       0
  6030.1    0.07       0  6419.9   0.035       0
Bank Sta=4976,4988.2
Exp/Cntr=0.3,0.1