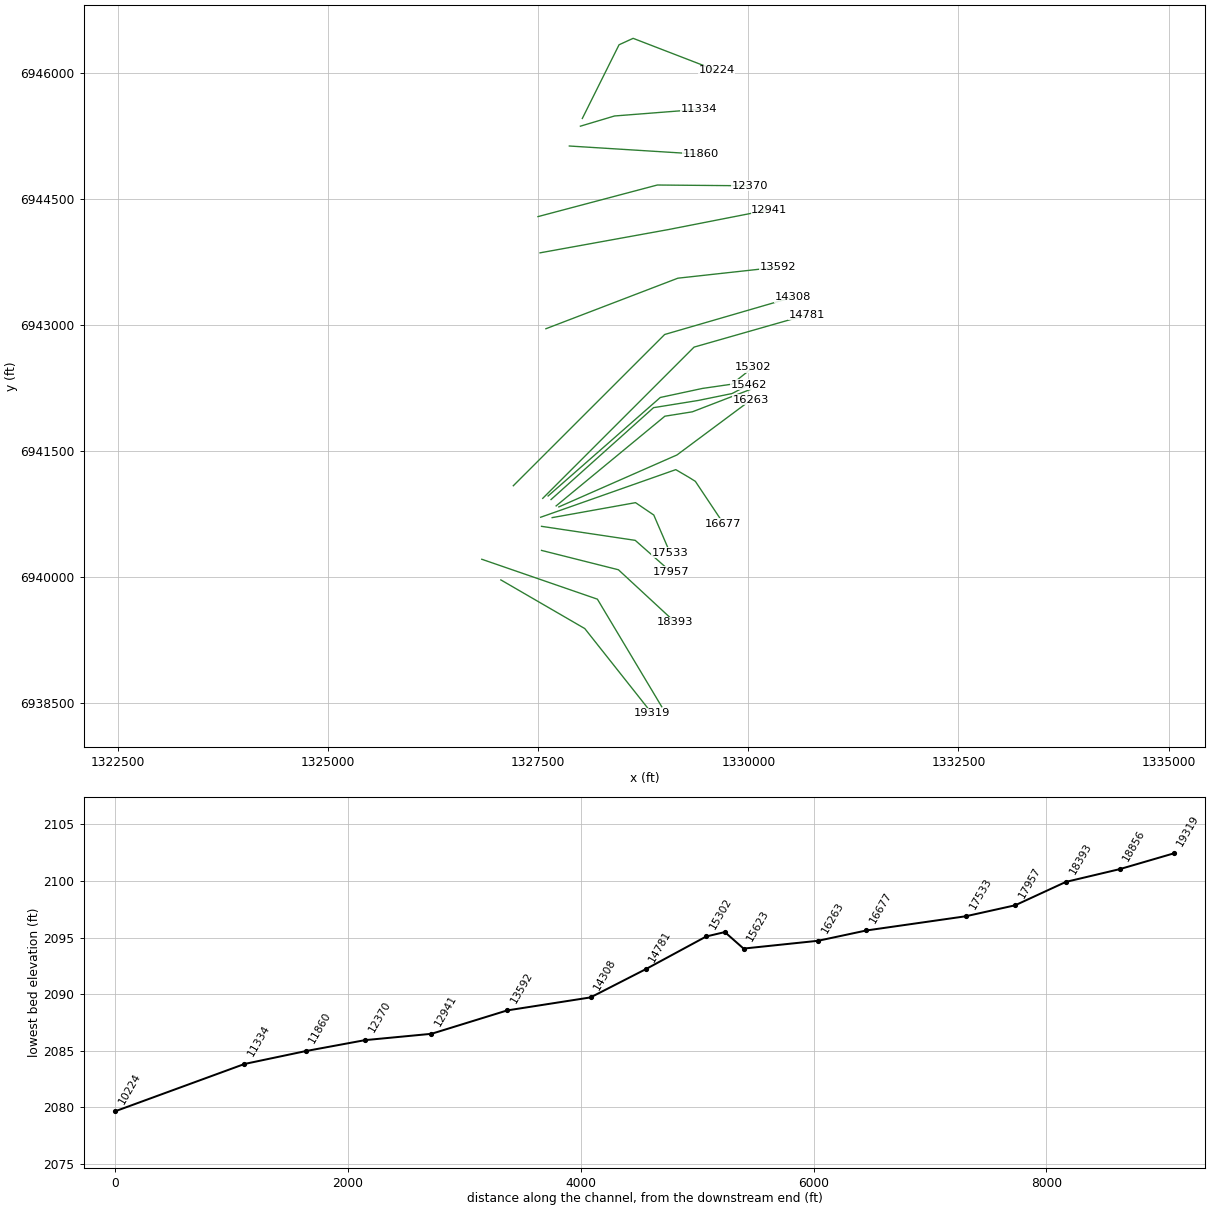
HEC-RAS study Buffalo Creek Trib 02.prj: Buffalo Creek Trib 02 Base Level Engineering

--- Buffalo Creek Trib 02.g01 (geometry) --- (continued)

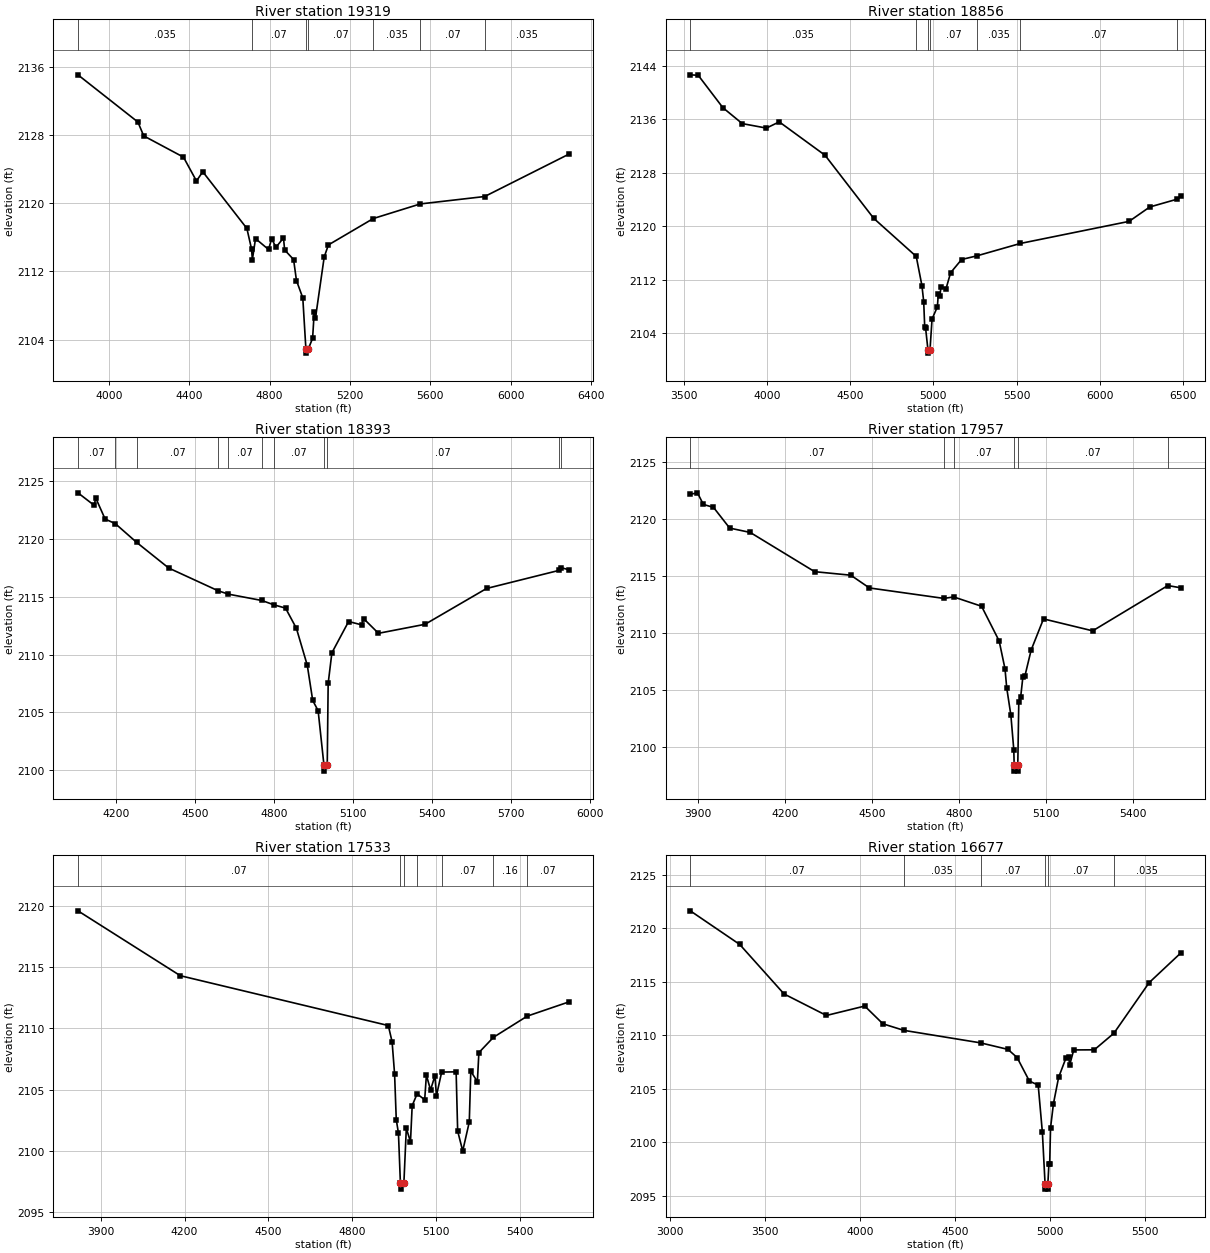
Type RM Length L Ch R = 1,19319,463,463,463
BEGIN DESCRIPTION:
Buffalo Creek Trib 02 9.0
END DESCRIPTION:
XS GIS Cut Line= 3
      1327056.90      6939967.15      1328055.00      6939388.00
      1328853.71      6938378.65
#Sta/Elev= 30
  3846.7 2135.03  4145.1 2129.50  4173.9 2127.88  4371.8 2125.39  4436.4 2122.60
  4467.8 2123.68  4687.3 2117.04  4710.4 2114.64  4714.6 2113.39  4730.3 2115.85
  4794.9 2114.58  4810.6 2115.82  4832.2 2114.84  4869.4 2115.93  4875.2 2114.52
  4919.7 2113.40  4934.0 2110.94  4965.5 2108.91  4980.9 2102.94  4981.4 2102.44
  4993.2 2102.94  5014.3 2104.18  5022.3 2107.21  5028.7 2106.56  5072.0 2113.69
  5092.8 2115.11  5316.2 2118.20  5549.8 2119.91  5870.6 2120.78  6287.8 2125.72
#Mann=7,-1,0
  3846.7   0.035       0  4710.4    0.07       0  4980.9    0.07       0
  4993.2    0.07       0  5316.2   0.035       0  5549.8    0.07       0
  5870.6   0.035       0
Bank Sta=4980.9,4993.2
Exp/Cntr=0.3,0.1

Type RM Length L Ch R = 1,18856,463,463,463
BEGIN DESCRIPTION:
Buffalo Creek Trib 02 8.0
END DESCRIPTION:
XS GIS Cut Line= 3
      1326830.04      6940212.98      1328205.00      6939738.00
      1328970.45      6938457.54
#Sta/Elev= 30
  3540.3 2142.64  3587.9 2142.57  3736.0 2137.73  3852.4 2135.35  3997.4 2134.68
  4074.5 2135.61  4349.6 2130.62  4641.7 2121.20  4897.3 2115.50  4931.5 2111.14
  4942.1 2108.76  4948.2 2104.96  4953.5 2104.80  4967.6 2101.55  4968.1 2101.05
  4980.0 2101.55  4992.3 2106.15  5024.2 2107.96  5030.0 2109.88  5039.7 2109.60
  5045.6 2110.98  5076.5 2110.70  5103.9 2113.07  5169.7 2115.04  5263.4 2115.60
  5522.7 2117.44  6175.8 2120.74  6299.8 2122.89  6460.5 2124.03  6486.8 2124.46
#Mann=7,-1,0
  3540.3   0.035       0  4897.3    0.07       0  4967.6    0.07       0
  4980.0    0.07       0  5263.4   0.035       0  5522.7    0.07       0
  6460.5   0.035       0
Bank Sta=4967.6,4980
Exp/Cntr=0.3,0.1

Type RM Length L Ch R = 1,18393,436,436,436
BEGIN DESCRIPTION:
Buffalo Creek Trib 02 7.0
END DESCRIPTION:
XS GIS Cut Line= 3
      1327540.49      6940318.33      1328455.00      6940088.00
      1329130.01      6939462.99
#Sta/Elev= 30
  4056.5 2124.01  4118.6 2122.92  4123.7 2123.58  4159.7 2121.74  4198.5 2121.34
  4279.4 2119.72  4401.1 2117.50  4589.0 2115.53  4627.7 2115.24  4754.9 2114.69
  4800.0 2114.32  4844.9 2114.03  4886.1 2112.28  4927.4 2109.08  4948.0 2106.04
  4968.6 2105.15  4990.8 2100.42  4991.3 2099.92  5003.2 2100.42  5006.7 2107.51
  5020.8 2110.16  5084.3 2112.87  5134.2 2112.58  5141.0 2113.13  5197.7 2111.85
  5374.6 2112.63  5608.2 2115.73  5884.0 2117.30  5889.7 2117.54  5919.5 2117.36
#Mann=11,-1,0
  4056.5    0.07       0  4198.5   0.035       0  4279.4    0.07       0
  4589.0   0.035       0  4627.7    0.07       0  4754.9   0.035       0
  4800.0    0.07       0  4990.8    0.07       0  5003.2    0.07       0
  5884.0   0.035       0  5889.7    0.07       0
Bank Sta=4990.8,5003.2
Exp/Cntr=0.3,0.1

Type RM Length L Ch R = 1,17957,424,424,424
BEGIN DESCRIPTION:
Buffalo Creek Trib 02 6.0
END DESCRIPTION:
XS GIS Cut Line= 3
      1327540.47      6940604.80      1328655.00      6940438.00
      1329079.97      6940063.02
#Sta/Elev= 30
  3872.8 2122.18  3897.6 2122.31  3917.8 2121.29  3952.9 2121.03  4008.8 2119.21
  4079.6 2118.83  4302.1 2115.38  4426.9 2115.07  4491.1 2113.95  4748.3 2113.03
  4782.2 2113.16  4878.4 2112.34  4939.1 2109.29  4959.3 2106.84  4965.2 2105.17
  4979.5 2102.78  4989.6 2099.74  4991.0 2098.35  4991.5 2097.85  5002.9 2097.85
  5003.4 2098.35  5006.9 2103.94  5013.5 2104.39  5021.1 2106.15  5027.8 2106.19
  5049.5 2108.49  5092.2 2111.23  5262.0 2110.18  5521.5 2114.16  5566.5 2113.96
#Mann=6,-1,0
  3872.8    0.07       0  4748.3   0.035       0  4782.2    0.07       0
  4991.0    0.07       0  5003.4    0.07       0  5521.5    0.16       0
Bank Sta=4991,5003.4
Exp/Cntr=0.3,0.1

Type RM Length L Ch R = 1,17533,856,856,856
BEGIN DESCRIPTION:
Buffalo Creek Trib 02 5.5
END DESCRIPTION:
XS GIS Cut Line= 4
      1327667.23      6940708.46      1328658.69      6940886.61
      1328875.58      6940739.43      1329068.61      6940291.62
#Sta/Elev= 30
  3818.2 2119.61  4185.0 2114.31  4929.8 2110.24  4943.4 2108.91  4952.3 2106.28
  4958.3 2102.55  4966.1 2101.46  4973.1 2097.38  4973.6 2096.88  4985.6 2097.38
  4994.3 2101.85  5009.2 2100.74  5015.3 2103.70  5032.9 2104.66  5060.1 2104.18
  5066.2 2106.19  5081.1 2104.98  5096.7 2106.14  5102.2 2104.51  5120.9 2106.44
  5172.7 2106.46  5178.2 2101.62  5196.3 2100.00  5219.8 2102.36  5225.2 2106.51
  5248.8 2105.66  5254.2 2108.03  5306.4 2109.28  5427.4 2111.01  5575.3 2112.16
#Mann=7,-1,0
  3818.2    0.07       0  4973.1    0.07       0  4985.6    0.07       0
  5032.9    0.16       0  5120.9    0.07       0  5306.4    0.16       0
  5427.4    0.07       0
Bank Sta=4973.1,4985.6
Exp/Cntr=0.3,0.1

Type RM Length L Ch R = 1,16677,414,414,414
BEGIN DESCRIPTION:
Buffalo Creek Trib 02 5.0
END DESCRIPTION:
XS GIS Cut Line= 5
      1327530.03      6940713.01      1329137.40      6941279.66
      1329297.13      6941185.91      1329370.16      6941140.26
      1329705.00      6940638.00
#Sta/Elev= 30
  3108.5 2121.63  3368.2 2118.49  3601.5 2113.86  3824.2 2111.85  4025.6 2112.73
  4121.1 2111.07  4231.0 2110.46  4634.6 2109.29  4778.5 2108.68  4826.7 2107.92
  4891.2 2105.72  4937.6 2105.34  4959.6 2100.92  4973.7 2096.12  4974.2 2095.62
  4988.0 2095.62  4988.5 2096.12  4993.9 2097.97  4998.0 2097.97  5002.5 2101.35
  5017.8 2103.61  5044.9 2106.06  5084.1 2107.90  5097.4 2107.97  5103.4 2107.24
  5124.4 2108.63  5232.6 2108.64  5335.7 2110.19  5521.0 2114.92  5687.8 2117.70
#Mann=6,-1,0
  3108.5    0.07       0  4231.0   0.035       0  4634.6    0.07       0
  4973.7    0.07       0  4988.5    0.07       0  5335.7   0.035       0
Bank Sta=4973.7,4988.5
Exp/Cntr=0.3,0.1

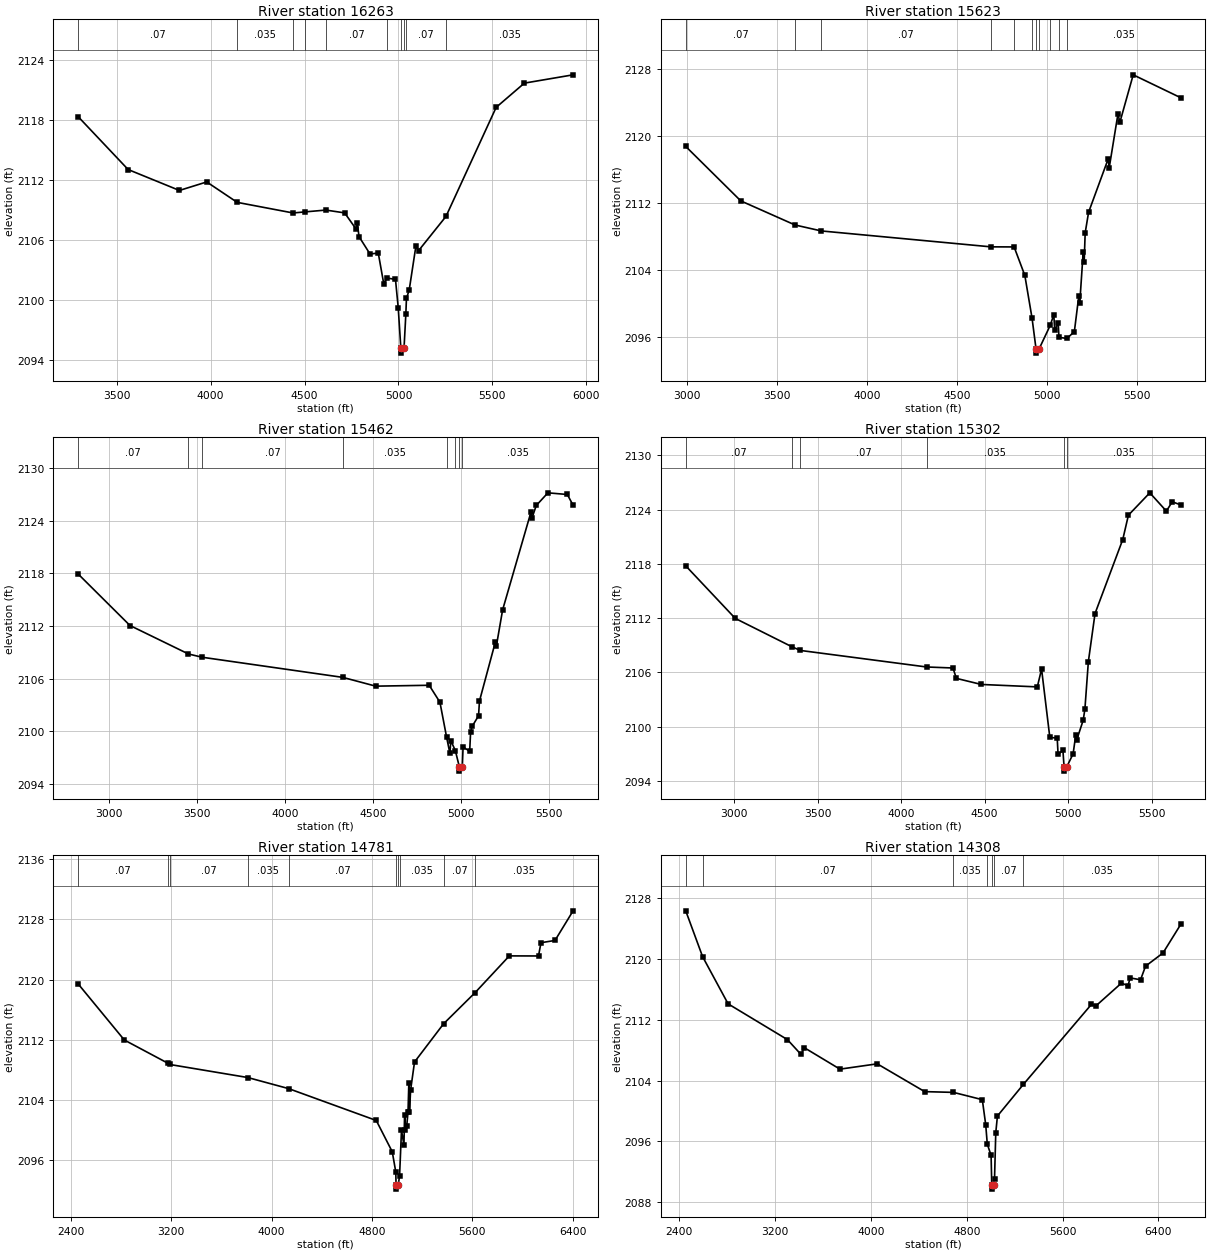
Type RM Length L Ch R = 1,16263,640,640,640
BEGIN DESCRIPTION:
Buffalo Creek Trib 02 5.55
END DESCRIPTION:
XS GIS Cut Line= 3
      1327746.26      6940835.98      1329151.45      6941454.34
      1330033.90      6942111.17
#Sta/Elev= 30
  3294.5 2118.33  3560.5 2113.05  3833.6 2110.96  3979.1 2111.81  4141.3 2109.77
  4439.0 2108.71  4503.6 2108.82  4613.4 2109.00  4713.4 2108.72  4775.1 2107.08
  4780.6 2107.74  4789.9 2106.35  4848.5 2104.61  4892.4 2104.71  4921.4 2101.66
  4940.6 2102.21  4984.1 2102.07  4998.7 2099.25  5012.6 2095.21  5013.1 2094.71
  5029.6 2095.21  5039.2 2098.59  5042.5 2100.18  5057.1 2101.01  5092.6 2105.38
  5107.2 2104.95  5253.1 2108.37  5520.1 2119.26  5670.3 2121.68  5929.8 2122.51
#Mann=10,-1,0
  3294.5    0.07       0  4141.3   0.035       0  4439.0    0.07       0
  4503.6   0.035       0  4613.4    0.07       0  4940.6    0.16       0
  5012.6    0.07       0  5029.6    0.16       0  5039.2    0.07       0
  5253.1   0.035       0
Bank Sta=5012.6,5029.6
Exp/Cntr=0.3,0.1

Type RM Length L Ch R = 1,15623,161,161,161
BEGIN DESCRIPTION:
Buffalo Creek Trib 02 4.0
END DESCRIPTION:
XS GIS Cut Line= 4
      1327714.10      6940847.88      1329007.47      6941915.56
      1329335.08      6941967.97      1330030.90      6942236.40
#Sta/Elev= 30
  2991.1 2118.70  3297.3 2112.20  3599.5 2109.32  3745.4 2108.61  4689.7 2106.71
  4818.8 2106.70  4878.4 2103.30  4918.6 2098.20  4940.8 2094.52  4941.3 2094.02
  4957.8 2094.52  5019.4 2097.32  5039.6 2098.61  5045.0 2096.74  5064.2 2097.65
  5068.3 2095.91  5112.9 2095.77  5154.1 2096.59  5178.7 2100.82  5184.1 2099.98
  5203.3 2106.11  5208.7 2104.90  5214.3 2108.38  5233.3 2110.84  5342.5 2117.22
  5347.8 2116.11  5396.5 2122.55  5407.8 2121.61  5481.6 2127.25  5745.8 2124.52
#Mann=11,-1,0
  2991.1    0.07       0  3599.5   0.035       0  3745.4    0.07       0
  4689.7   0.035       0  4818.8    0.07       0  4918.6   0.035       0
  4940.8   0.035       0  4957.8   0.035       0  5019.4    0.16       0
  5068.3    0.07       0  5112.9   0.035       0
Bank Sta=4940.8,4957.8
Exp/Cntr=0.3,0.1

Type RM Length L Ch R = 1,15462,160,160,160
BEGIN DESCRIPTION:
Buffalo Creek Trib 02 3.3
END DESCRIPTION:
XS GIS Cut Line= 5
      1327653.76      6940923.85      1328872.89      6942017.30
      1329404.87      6942103.06      1329807.49      6942185.54
      1330006.13      6942289.75
#Sta/Elev= 30
  2823.5 2117.91  3117.9 2112.05  3450.1 2108.81  3527.9 2108.44  4326.5 2106.15
  4513.9 2105.15  4817.8 2105.25  4878.8 2103.32  4917.0 2099.31  4935.6 2097.49
  4940.6 2098.96  4966.5 2097.80  4988.9 2095.98  4989.4 2095.48  5005.9 2095.98
  5010.3 2098.23  5047.8 2097.74  5052.9 2099.88  5061.4 2100.56  5098.2 2101.78
  5103.3 2103.45  5194.0 2110.20  5199.1 2109.68  5234.9 2113.83  5395.7 2124.94
  5400.8 2124.23  5426.1 2125.71  5492.2 2127.15  5602.5 2126.96  5635.3 2125.74
#Mann=8,-1,0
  2823.5    0.07       0  3450.1   0.035       0  3527.9    0.07       0
  4326.5   0.035       0  4917.0    0.07       0  4966.5   0.035       0
  4988.9   0.035       0  5005.9   0.035       0
Bank Sta=4988.9,5005.9
Exp/Cntr=0.3,0.1

Type RM Length L Ch R = 1,15302,521,521,521
BEGIN DESCRIPTION:
Buffalo Creek Trib 02 3.2
END DESCRIPTION:
XS GIS Cut Line= 5
      1327618.64      6940965.99      1328953.32      6942138.67
      1329455.34      6942246.34      1329804.02      6942296.65
      1330055.86      6942497.15
#Sta/Elev= 30
  2709.9 2117.78  3006.5 2111.97  3344.3 2108.85  3396.1 2108.43  4152.8 2106.60
  4310.2 2106.49  4331.1 2105.34  4480.1 2104.67  4815.6 2104.40  4841.1 2106.37
  4890.5 2098.82  4934.8 2098.74  4939.9 2096.94  4969.0 2097.38  4975.7 2095.59
  4976.2 2095.09  4992.7 2095.59  5030.0 2097.00  5045.9 2099.09  5050.9 2098.50
  5090.6 2100.73  5100.7 2101.96  5121.3 2107.19  5161.3 2112.51  5327.4 2120.69
  5361.2 2123.38  5489.3 2125.85  5588.6 2123.83  5623.9 2124.86  5674.2 2124.52
#Mann=6,-1,0
  2709.9    0.07       0  3344.3   0.035       0  3396.1    0.07       0
  4152.8   0.035       0  4975.7   0.035       0  4992.7   0.035       0
Bank Sta=4975.7,4992.7
Exp/Cntr=0.3,0.1

Type RM Length L Ch R = 1,14781,473,473,473
BEGIN DESCRIPTION:
Buffalo Creek Trib 02 3.0
END DESCRIPTION:
XS GIS Cut Line= 3
      1327555.02      6940938.02      1329355.00      6942738.00
      1330700.07      6943122.13
#Sta/Elev= 30
  2458.8 2119.42  2826.5 2111.98  3173.7 2108.90  3188.9 2108.73  3810.2 2107.00
  4135.7 2105.53  4834.6 2101.30  4961.9 2097.15  4990.2 2094.46  4992.3 2092.69
  4992.8 2092.19  5009.4 2092.69  5020.4 2093.98  5035.6 2100.02  5055.1 2098.02
  5060.3 2102.09  5066.8 2100.03  5077.2 2100.57  5087.6 2102.41  5094.1 2106.23
  5099.3 2102.45  5108.3 2105.35  5139.5 2109.06  5371.0 2114.13  5622.5 2118.27
  5895.0 2123.14  6127.5 2123.13  6147.3 2124.89  6259.1 2125.19  6403.2 2129.12
#Mann=10,-1,0
  2458.8    0.07       0  3173.7   0.035       0  3188.9    0.07       0
  3810.2   0.035       0  4135.7    0.07       0  4992.3    0.07       0
  5009.4    0.07       0  5020.4   0.035       0  5371.0    0.07       0
  5622.5   0.035       0
Bank Sta=4992.3,5009.4
Exp/Cntr=0.3,0.1

Type RM Length L Ch R = 1,14308,716,716,716
BEGIN DESCRIPTION:
Buffalo Creek Trib 02 2.0
END DESCRIPTION:
XS GIS Cut Line= 3
      1327205.00      6941088.00      1329005.00      6942888.00
      1330526.57      6943330.49
#Sta/Elev= 30
  2455.0 2126.35  2595.6 2120.32  2808.6 2114.10  3303.5 2109.39  3416.7 2107.44
  3445.0 2108.32  3741.9 2105.50  4053.1 2106.20  4449.0 2102.54  4689.2 2102.44
  4929.9 2101.48  4958.2 2098.20  4971.5 2095.62  5003.2 2094.14  5008.8 2090.20
  5009.3 2089.70  5026.0 2090.20  5031.8 2091.02  5042.2 2097.13  5056.1 2099.33
  5273.0 2103.50  5840.5 2114.03  5879.3 2113.85  6090.9 2116.83  6146.2 2116.49
  6163.1 2117.52  6250.3 2117.27  6292.0 2119.06  6437.8 2120.80  6585.2 2124.55
#Mann=7,-1,0
  2455.0   0.035       0  2595.6    0.07       0  4689.2   0.035       0
  4971.5    0.07       0  5008.8    0.07       0  5026.0    0.07       0
  5273.0   0.035       0
Bank Sta=5008.8,5026
Exp/Cntr=0.3,0.1

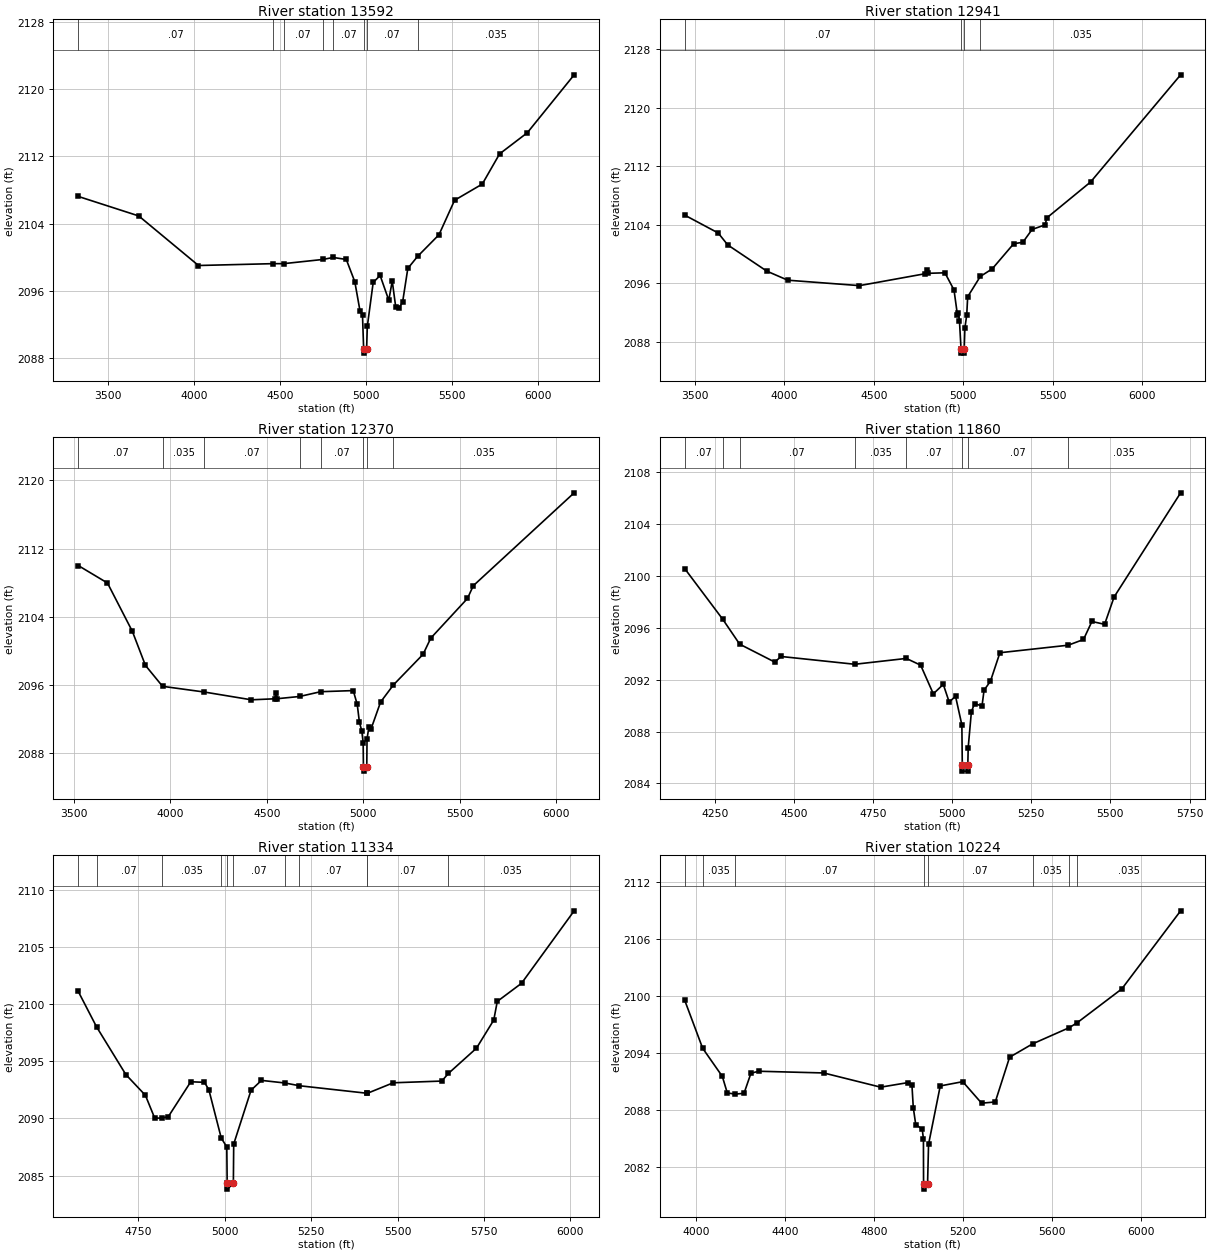
Type RM Length L Ch R = 1,13592,651,651,651
BEGIN DESCRIPTION:
Buffalo Creek Trib 02 0.75
END DESCRIPTION:
XS GIS Cut Line= 3
      1327592.49      6942956.71      1329162.05      6943558.22
      1330355.65      6943689.79
#Sta/Elev= 30
  3326.5 2107.24  3678.3 2104.91  4025.3 2099.00  4457.6 2099.22  4519.8 2099.22
  4747.7 2099.72  4808.2 2099.96  4884.2 2099.72  4933.6 2097.07  4963.6 2093.62
  4978.4 2093.10  4985.0 2089.05  4985.5 2088.55  5002.3 2089.05  5006.3 2091.73
  5040.5 2096.98  5080.8 2097.81  5131.1 2094.86  5151.2 2097.15  5171.3 2094.07
  5191.4 2093.94  5211.5 2094.65  5241.7 2098.65  5298.2 2100.08  5422.8 2102.67
  5513.4 2106.78  5674.3 2108.71  5774.9 2112.31  5935.9 2114.83  6208.2 2121.74
#Mann=8,-1,0
  3326.5    0.07       0  4457.6   0.035       0  4519.8    0.07       0
  4747.7   0.035       0  4808.2    0.07       0  4985.0    0.07       0
  5002.3    0.07       0  5298.2   0.035       0
Bank Sta=4985,5002.3
Exp/Cntr=0.3,0.1

Type RM Length L Ch R = 1,12941,571,571,571
BEGIN DESCRIPTION:
Buffalo Creek Trib 02 1.0
END DESCRIPTION:
XS GIS Cut Line= 3
      1327523.13      6943860.01      1329055.00      6944138.00
      1330248.77      6944372.15
#Sta/Elev= 30
  3442.7 2105.33  3630.0 2102.89  3683.4 2101.26  3901.9 2097.68  4019.2 2096.44
  4420.3 2095.70  4786.2 2097.32  4796.3 2097.86  4802.5 2097.38  4898.0 2097.45
  4948.8 2095.11  4967.8 2091.75  4972.9 2091.96  4979.3 2090.90  4988.3 2086.98
  4988.8 2086.48  5005.2 2086.48  5005.7 2086.98  5009.8 2089.94  5020.0 2091.68
  5025.3 2094.18  5095.8 2096.95  5162.6 2097.99  5282.6 2101.42  5334.0 2101.62
  5385.5 2103.37  5458.2 2104.00  5468.3 2104.96  5712.9 2109.86  6216.1 2124.49
#Mann=4,-1,0
  3442.7    0.07       0  4988.3    0.07       0  5005.7    0.07       0
  5095.8   0.035       0
Bank Sta=4988.3,5005.7
Exp/Cntr=0.3,0.1

Type RM Length L Ch R = 1,12370,510,510,510
BEGIN DESCRIPTION:
Buffalo Creek Trib 02 0.7
END DESCRIPTION:
XS GIS Cut Line= 3
      1327498.50      6944291.29      1328917.69      6944667.23
      1330017.31      6944657.84
#Sta/Elev= 30
  3523.7 2110.02  3675.2 2107.97  3804.1 2102.30  3871.8 2098.31  3960.4 2095.86
  4177.0 2095.19  4420.1 2094.28  4542.4 2094.40  4547.6 2095.11  4554.6 2094.41
  4670.0 2094.67  4779.0 2095.23  4947.7 2095.36  4968.4 2093.74  4979.6 2091.66
  4991.8 2090.65  4999.1 2089.25  5000.4 2086.42  5000.9 2085.92  5017.8 2086.42
  5019.1 2089.70  5029.1 2091.14  5039.1 2090.81  5089.1 2094.01  5155.5 2096.02
  5309.2 2099.61  5349.2 2101.51  5539.2 2106.16  5569.2 2107.65  6091.5 2118.54
#Mann=8,-1,0
  3523.7    0.07       0  3960.4   0.035       0  4177.0    0.07       0
  4670.0   0.035       0  4779.0    0.07       0  5000.4    0.07       0
  5017.8    0.07       0  5155.5   0.035       0
Bank Sta=5000.4,5017.8
Exp/Cntr=0.3,0.1

Type RM Length L Ch R = 1,11860,526,526,526
BEGIN DESCRIPTION:
Buffalo Creek Trib 02 0.65
END DESCRIPTION:
XS GIS Cut Line= 3
      1327871.09      6945131.43      1328682.73      6945080.77
      1329434.65      6945033.77
#Sta/Elev= 30
  4155.3 2100.57  4275.8 2096.65  4329.0 2094.74  4439.8 2093.36  4459.8 2093.79
  4692.7 2093.19  4855.4 2093.64  4900.7 2093.12  4940.7 2090.91  4972.2 2091.64
  4990.8 2090.28  5010.9 2090.72  5030.9 2088.51  5032.2 2085.45  5032.7 2084.95
  5049.2 2084.95  5049.7 2085.45  5050.9 2086.77  5061.0 2089.53  5071.0 2090.16
  5094.5 2089.97  5101.0 2091.19  5121.1 2091.88  5151.1 2094.08  5366.8 2094.66
  5415.1 2095.10  5441.7 2096.49  5481.8 2096.27  5511.8 2098.38  5721.9 2106.41
#Mann=8,-1,0
  4155.3    0.07       0  4275.8   0.035       0  4329.0    0.07       0
  4692.7   0.035       0  4855.4    0.07       0  5032.2    0.07       0
  5049.7    0.07       0  5366.8   0.035       0
Bank Sta=5032.2,5049.7
Exp/Cntr=0.3,0.1

Type RM Length L Ch R = 1,11334,1110,1110,1110
BEGIN DESCRIPTION:
Buffalo Creek Trib 02 0.6
END DESCRIPTION:
XS GIS Cut Line= 3
      1328003.01      6945367.54      1328409.03      6945488.98
      1329416.75      6945567.85
#Sta/Elev= 30
  4576.2 2101.14  4629.3 2098.03  4714.0 2093.85  4770.6 2092.03  4797.5 2090.03
  4817.5 2090.04  4836.8 2090.16  4901.8 2093.22  4941.3 2093.17  4954.0 2092.53
  4990.0 2088.28  5006.0 2087.51  5007.1 2084.31  5007.6 2083.81  5025.0 2084.31
  5026.0 2087.76  5076.2 2092.48  5106.3 2093.34  5174.5 2093.11  5216.2 2092.87
  5412.2 2092.21  5412.8 2092.21  5487.5 2093.13  5627.9 2093.28  5647.1 2093.95
  5728.2 2096.16  5778.3 2098.63  5788.4 2100.26  5858.6 2101.85  6010.8 2108.20
#Mann=11,-1,0
  4576.2   0.035       0  4629.3    0.07       0  4817.5   0.035       0
  4990.0    0.07       0  5007.1    0.07       0  5025.0    0.07       0
  5174.5   0.035       0  5216.2    0.07       0  5412.2    0.16       0
  5412.8    0.07       0  5647.1   0.035       0
Bank Sta=5007.1,5025
Exp/Cntr=0.3,0.1

Type RM Length L Ch R = 1,10224,808,808,808
BEGIN DESCRIPTION:
Buffalo Creek Trib 02 0.55
END DESCRIPTION:
XS GIS Cut Line= 4
      1328025.84      6945459.54      1328462.48      6946336.28
      1328630.00      6946413.00      1329621.26      6946030.52
#Sta/Elev= 30
  3950.3 2099.57  4030.9 2094.50  4119.2 2091.53  4141.6 2089.78  4176.5 2089.66
  4216.7 2089.74  4247.9 2091.87  4283.7 2092.07  4574.2 2091.89  4830.0 2090.39
  4954.5 2090.88  4970.5 2090.58  4976.5 2088.23  4987.5 2086.44  5016.5 2085.96
  5022.0 2084.96  5022.6 2080.13  5023.1 2079.63  5040.5 2080.13  5045.0 2084.36
  5097.5 2090.52  5198.5 2090.97  5283.1 2088.70  5344.5 2088.83  5408.8 2093.55
  5512.0 2094.96  5676.5 2096.67  5713.3 2097.21  5912.5 2100.76  6176.5 2109.00
#Mann=8,-1,0
  3950.3    0.07       0  4030.9   0.035       0  4176.5    0.07       0
  5022.6    0.07       0  5040.5    0.07       0  5512.0   0.035       0
  5676.5    0.07       0  5713.3   0.035       0
Bank Sta=5022.6,5040.5
Exp/Cntr=0.3,0.1