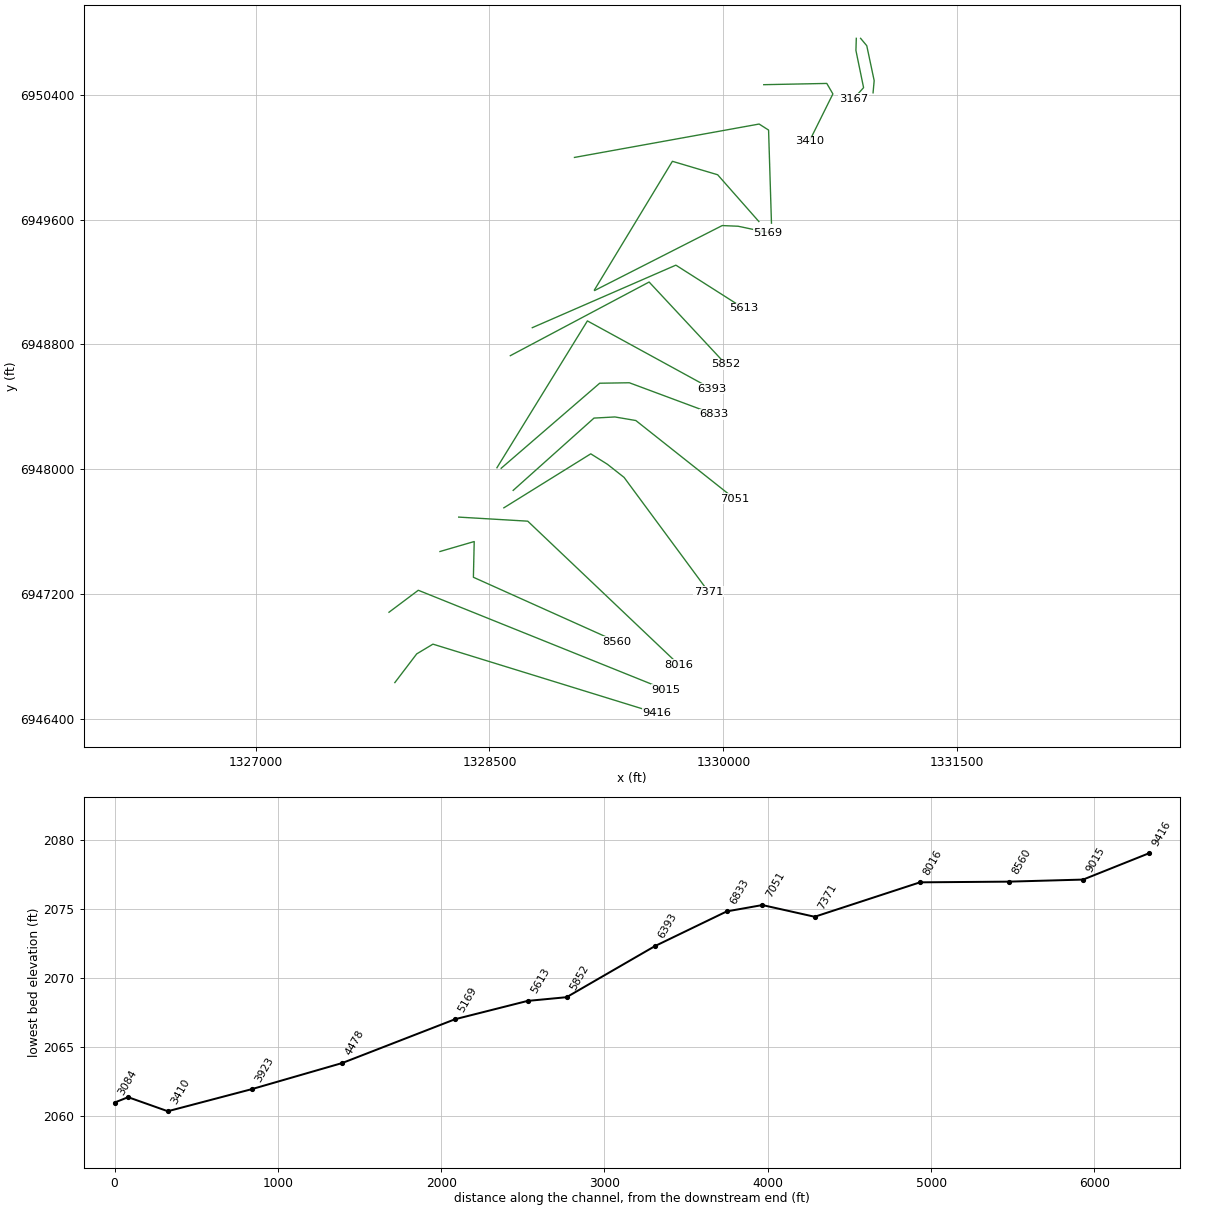
HEC-RAS study Buffalo Creek Trib 02.prj: Buffalo Creek Trib 02 Base Level Engineering

--- Buffalo Creek Trib 02.g01 (geometry) --- (continued)

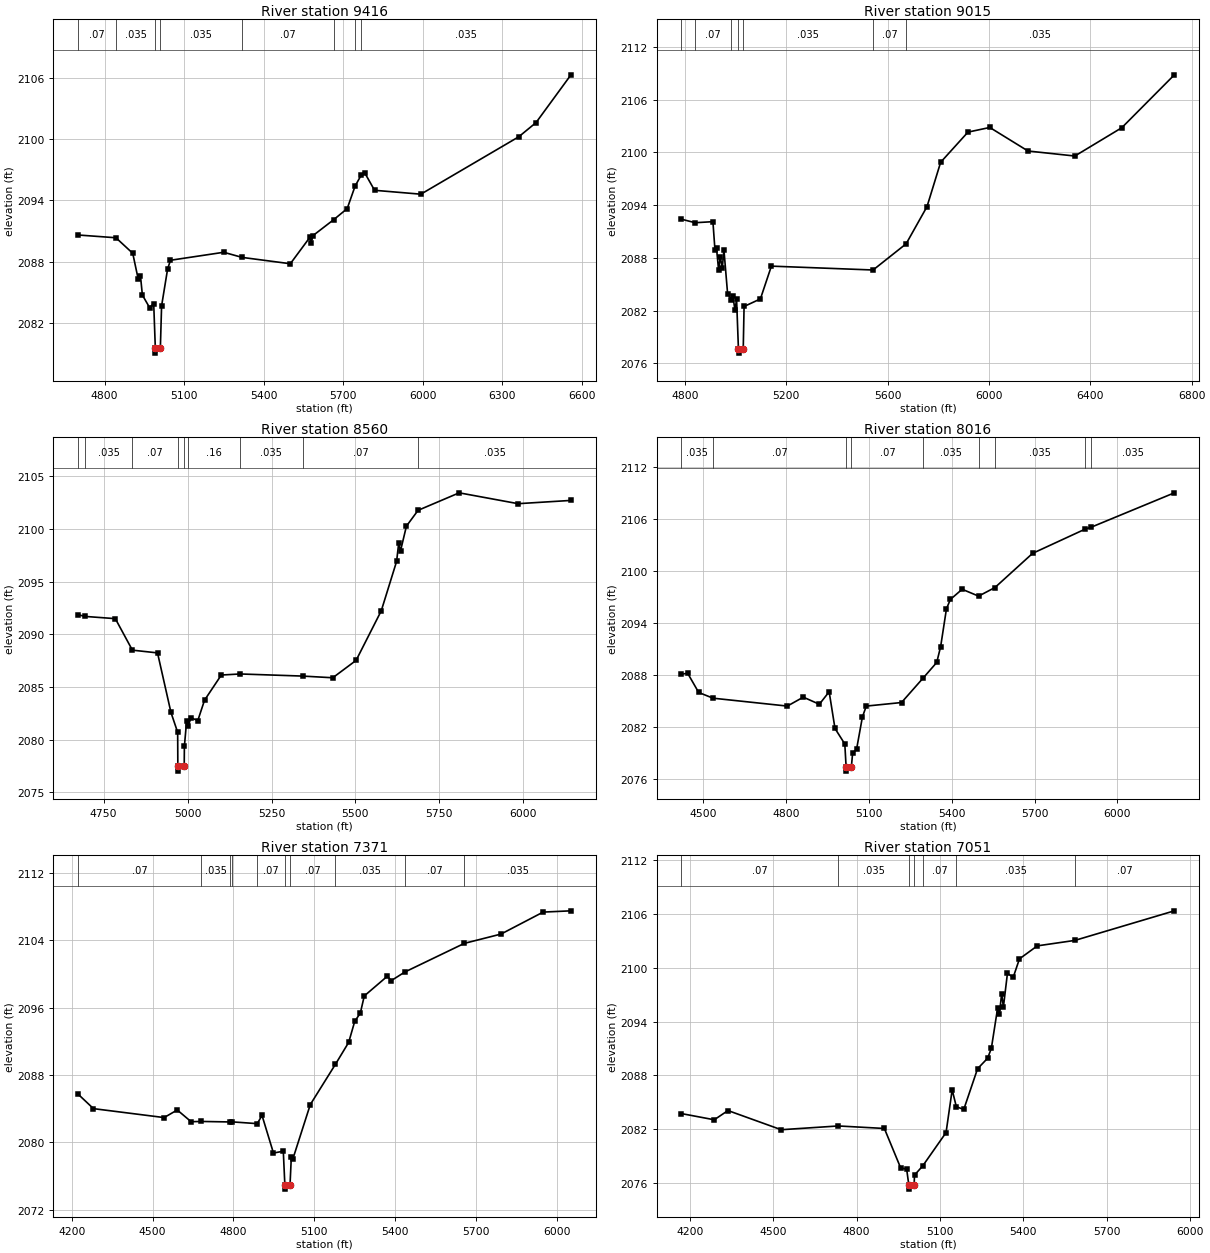
Type RM Length L Ch R = 1,9416,401,401,401
BEGIN DESCRIPTION:
Buffalo Creek Trib 02 0.5
END DESCRIPTION:
XS GIS Cut Line= 4
      1327893.28      6946631.54      1328033.42      6946815.61
      1328137.58      6946878.11      1329575.59      6946434.14
#Sta/Elev= 30
  4700.3 2090.61  4843.1 2090.34  4906.4 2088.82  4927.2 2086.27  4935.5 2086.62
  4942.7 2084.74  4969.9 2083.51  4985.4 2083.91  4991.5 2079.56  4992.0 2079.06
  5010.5 2079.56  5015.1 2083.67  5037.9 2087.30  5048.7 2088.14  5249.3 2088.92
  5318.5 2088.42  5500.4 2087.80  5573.7 2090.37  5578.9 2089.78  5584.2 2090.52
  5663.9 2092.11  5714.7 2093.19  5744.6 2095.40  5768.5 2096.51  5780.0 2096.72
  5817.9 2094.98  5992.3 2094.60  6361.2 2100.21  6426.5 2101.60  6558.1 2106.27
#Mann=8,-1,0
  4700.3    0.07       0  4843.1   0.035       0  4991.5   0.035       0
  5010.5   0.035       0  5318.5    0.07       0  5663.9   0.035       0
  5744.6    0.07       0  5768.5   0.035       0
Bank Sta=4991.5,5010.5
Exp/Cntr=0.3,0.1

Type RM Length L Ch R = 1,9015,455,455,455
BEGIN DESCRIPTION:
Buffalo Creek Trib 02 0.45
END DESCRIPTION:
XS GIS Cut Line= 3
      1327855.68      6947082.65      1328043.63      6947223.61
      1329631.01      6946584.91
#Sta/Elev= 30
  4785.8 2092.40  4840.0 2092.00  4910.0 2092.12  4918.0 2088.92  4924.2 2089.10
  4932.5 2086.59  4938.8 2088.12  4947.1 2086.85  4953.4 2088.93  4968.0 2083.91
  4983.0 2083.26  4988.8 2083.68  4997.1 2082.03  5003.4 2083.29  5010.7 2077.66
  5011.2 2077.16  5029.7 2077.66  5033.0 2082.47  5097.5 2083.33  5140.8 2087.06
  5542.4 2086.62  5672.8 2089.60  5755.2 2093.83  5809.1 2098.88  5916.9 2102.31
  6003.1 2102.84  6154.0 2100.16  6338.9 2099.59  6524.2 2102.81  6731.8 2108.83
#Mann=7,-1,0
  4785.8   0.035       0  4840.0    0.07       0  4983.0   0.035       0
  5010.7   0.035       0  5029.7   0.035       0  5542.4    0.07       0
  5672.8   0.035       0
Bank Sta=5010.7,5029.7
Exp/Cntr=0.3,0.1

Type RM Length L Ch R = 1,8560,544,544,544
BEGIN DESCRIPTION:
Buffalo Creek Trib 02 0.67
END DESCRIPTION:
XS GIS Cut Line= 4
      1328182.71      6947472.20      1328402.20      6947536.08
      1328396.99      6947306.91      1329318.67      6946892.94
#Sta/Elev= 30
  4673.8 2091.85  4695.4 2091.69  4784.8 2091.48  4835.6 2088.49  4910.5 2088.23
  4950.5 2082.58  4970.5 2080.69  4971.0 2077.51  4971.5 2077.01  4990.0 2077.51
  4990.5 2079.37  4997.3 2081.79  5001.2 2081.28  5010.5 2082.07  5030.5 2081.81
  5050.5 2083.74  5100.5 2086.13  5157.1 2086.23  5342.5 2086.03  5432.5 2085.87
  5502.0 2087.52  5577.0 2092.23  5622.7 2096.92  5628.8 2098.63  5634.3 2097.91
  5651.9 2100.26  5686.6 2101.76  5809.1 2103.42  5984.5 2102.39  6142.0 2102.70
#Mann=9,-1,0
  4673.8    0.07       0  4695.4   0.035       0  4835.6    0.07       0
  4971.0    0.07       0  4990.0    0.07       0  5001.2    0.16       0
  5157.1   0.035       0  5342.5    0.07       0  5686.6   0.035       0
Bank Sta=4971,4990
Exp/Cntr=0.3,0.1

Type RM Length L Ch R = 1,8016,645,645,645
BEGIN DESCRIPTION:
Buffalo Creek Trib 02 0.4
END DESCRIPTION:
XS GIS Cut Line= 3
      1328302.79      6947692.77      1328745.51      6947666.72
      1329716.54      6946744.31
#Sta/Elev= 30
  4423.0 2088.13  4445.3 2088.25  4485.3 2086.03  4537.3 2085.37  4805.9 2084.46
  4863.7 2085.49  4921.7 2084.67  4957.2 2086.11  4978.3 2081.88  5013.8 2080.09
  5018.5 2077.46  5019.0 2076.96  5037.6 2077.46  5042.2 2079.08  5056.3 2079.47
  5077.4 2083.19  5091.5 2084.46  5218.9 2084.87  5297.6 2087.71  5346.3 2089.49
  5360.5 2091.33  5381.5 2095.68  5395.7 2096.76  5438.2 2097.93  5497.7 2097.14
  5556.9 2098.13  5693.0 2102.07  5883.4 2104.87  5903.8 2105.07  6205.8 2109.05
#Mann=9,-1,0
  4423.0   0.035       0  4537.3    0.07       0  5018.5    0.07       0
  5037.6    0.07       0  5297.6   0.035       0  5497.7    0.07       0
  5556.9   0.035       0  5883.4    0.07       0  5903.8   0.035       0
Bank Sta=5018.5,5037.6
Exp/Cntr=0.3,0.1

Type RM Length L Ch R = 1,7371,320,320,320
BEGIN DESCRIPTION:
Buffalo Creek Trib 02 0.35
END DESCRIPTION:
XS GIS Cut Line= 5
      1328592.30      6947752.22      1329149.59      6948098.58
      1329256.03      6948031.88      1329363.13      6947947.54
      1329904.52      6947214.23
#Sta/Elev= 30
  4223.2 2085.73  4280.4 2084.01  4542.6 2082.95  4591.4 2083.85  4642.9 2082.46
  4681.2 2082.49  4787.9 2082.43  4795.1 2082.44  4888.3 2082.23  4906.1 2083.20
  4948.5 2078.74  4985.0 2078.96  4990.8 2074.96  4991.3 2074.46  5010.0 2074.96
  5014.7 2078.22  5021.0 2078.09  5085.2 2084.49  5178.5 2089.27  5227.7 2091.87
  5250.1 2094.36  5271.0 2095.35  5285.6 2097.38  5371.2 2099.72  5385.8 2099.20
  5436.2 2100.22  5657.1 2103.62  5793.0 2104.72  5949.5 2107.33  6052.8 2107.48
#Mann=10,-1,0
  4223.2    0.07       0  4681.2   0.035       0  4787.9    0.07       0
  4795.1   0.035       0  4888.3    0.07       0  4990.8    0.07       0
  5010.0    0.07       0  5178.5   0.035       0  5436.2    0.07       0
  5657.1   0.035       0
Bank Sta=4990.8,5010
Exp/Cntr=0.3,0.1

Type RM Length L Ch R = 1,7051,218,218,218
BEGIN DESCRIPTION:
Buffalo Creek Trib 02 0.47
END DESCRIPTION:
XS GIS Cut Line= 5
      1328652.19      6947864.20      1329170.43      6948327.75
      1329304.40      6948335.04      1329438.65      6948312.12
      1330071.54      6947810.74
#Sta/Elev= 30
  4169.9 2083.74  4287.9 2083.05  4337.2 2084.08  4528.7 2081.94  4734.0 2082.36
  4899.8 2082.08  4958.4 2077.68  4980.0 2077.54  4987.6 2075.81  4988.1 2075.31
  5006.8 2075.81  5008.3 2076.88  5037.5 2077.89  5121.7 2081.62  5143.7 2086.39
  5158.7 2084.51  5185.4 2084.20  5235.1 2088.75  5271.3 2089.92  5284.7 2091.03
  5307.2 2095.51  5313.6 2094.84  5321.7 2097.13  5328.0 2095.63  5342.5 2099.39
  5363.3 2098.95  5385.8 2101.01  5449.9 2102.46  5585.2 2103.07  5943.0 2106.37
#Mann=7,-1,0
  4169.9    0.07       0  4734.0   0.035       0  4987.6   0.035       0
  5006.8   0.035       0  5037.5    0.07       0  5158.7   0.035       0
  5585.2    0.07       0
Bank Sta=4987.6,5006.8
Exp/Cntr=0.3,0.1

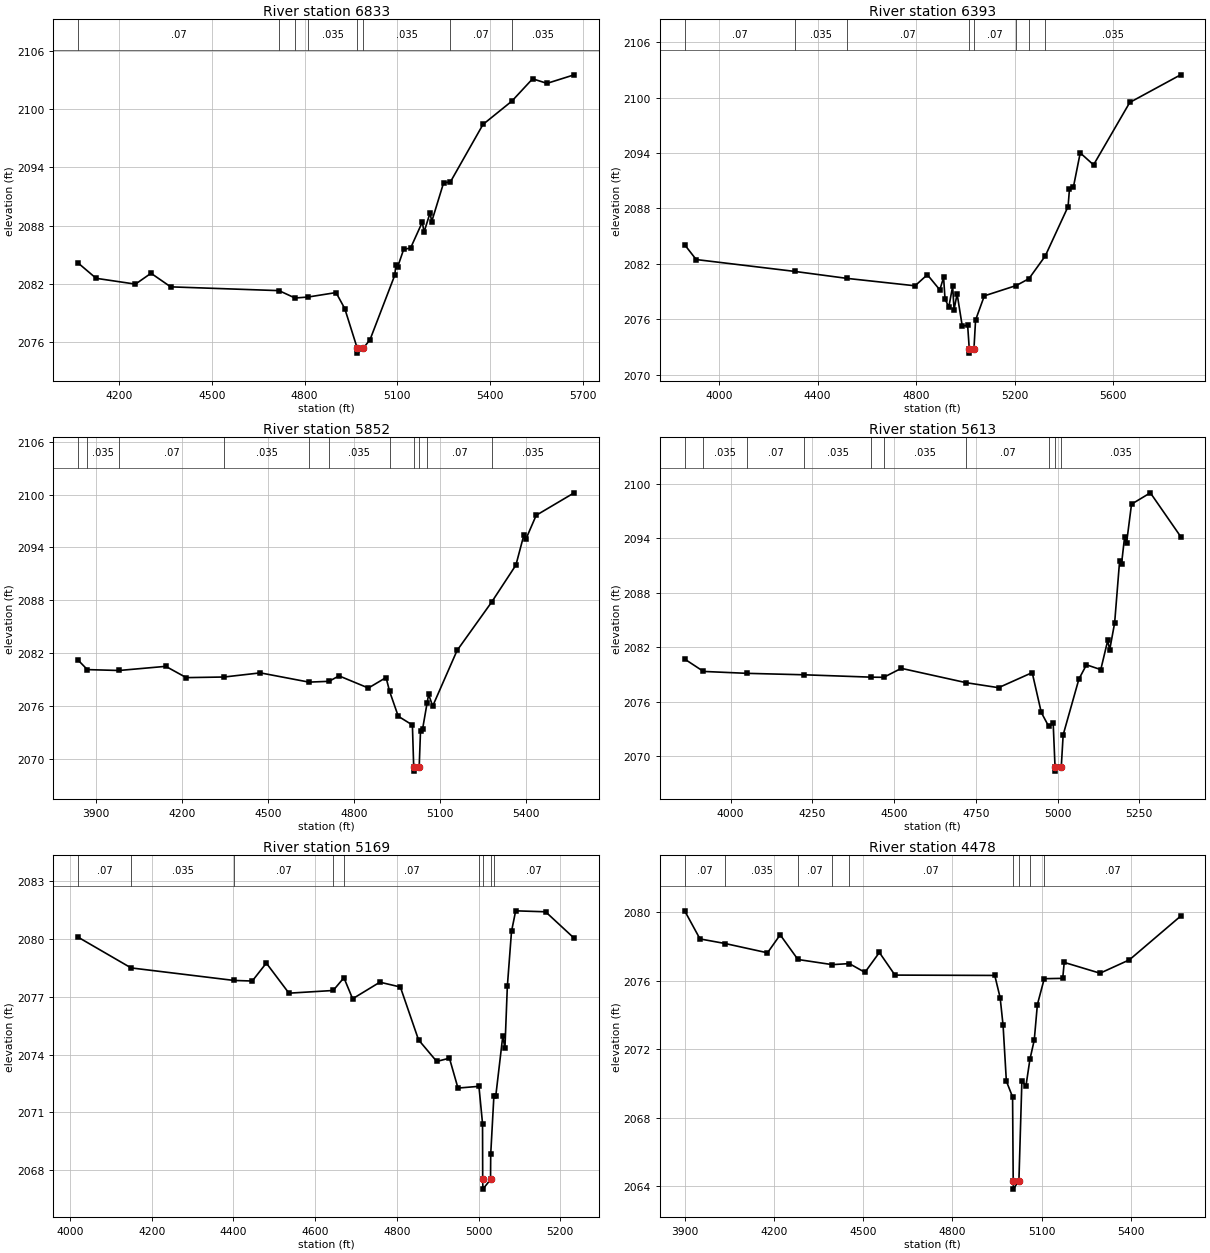
Type RM Length L Ch R = 1,6833,440,440,440
BEGIN DESCRIPTION:
Buffalo Creek Trib 02 0.3
END DESCRIPTION:
XS GIS Cut Line= 4
      1328575.10      6948005.96      1329206.78      6948551.33
      1329396.99      6948554.31      1329941.07      6948351.82
#Sta/Elev= 30
  4067.2 2084.13  4125.2 2082.56  4252.5 2081.96  4302.9 2083.08  4366.5 2081.68
  4717.2 2081.29  4769.0 2080.53  4811.0 2080.63  4901.7 2081.09  4930.0 2079.44
  4970.4 2075.35  4970.9 2074.85  4989.6 2075.35  5011.7 2076.23  5092.0 2082.89
  5095.4 2083.98  5100.8 2083.69  5120.5 2085.53  5143.2 2085.69  5181.1 2088.36
  5186.5 2087.31  5206.1 2089.30  5211.5 2088.41  5249.9 2092.40  5271.9 2092.49
  5377.5 2098.42  5470.9 2100.82  5538.0 2103.12  5584.6 2102.65  5672.5 2103.53
#Mann=8,-1,0
  4067.2    0.07       0  4717.2   0.035       0  4769.0    0.07       0
  4811.0   0.035       0  4970.4   0.035       0  4989.6   0.035       0
  5271.9    0.07       0  5470.9   0.035       0
Bank Sta=4970.4,4989.6
Exp/Cntr=0.3,0.1

Type RM Length L Ch R = 1,6393,541,541,541
BEGIN DESCRIPTION:
Buffalo Creek Trib 02 0.37
END DESCRIPTION:
XS GIS Cut Line= 3
      1328547.88      6948009.24      1329128.08      6948951.00
      1329924.08      6948515.46
#Sta/Elev= 30
  3860.1 2084.06  3906.9 2082.46  4306.0 2081.18  4519.8 2080.42  4795.4 2079.62
  4845.3 2080.82  4895.9 2079.18  4911.3 2080.52  4917.2 2078.16  4932.6 2077.34
  4948.0 2079.56  4953.8 2077.04  4966.2 2078.74  4987.1 2075.25  5008.9 2075.35
  5015.4 2072.83  5015.9 2072.33  5034.6 2072.83  5041.1 2075.91  5076.7 2078.53
  5206.5 2079.65  5257.8 2080.39  5323.9 2082.84  5416.7 2088.20  5422.4 2090.12
  5438.5 2090.33  5466.0 2094.01  5520.1 2092.71  5667.1 2099.47  5873.6 2102.46
#Mann=8,-1,0
  3860.1    0.07       0  4306.0   0.035       0  4519.8    0.07       0
  5015.4    0.07       0  5034.6    0.07       0  5206.5   0.035       0
  5257.8    0.07       0  5323.9   0.035       0
Bank Sta=5015.4,5034.6
Exp/Cntr=0.3,0.1

Type RM Length L Ch R = 1,5852,239,239,239
BEGIN DESCRIPTION:
Buffalo Creek Trib 02 0.25
END DESCRIPTION:
XS GIS Cut Line= 3
      1328633.79      6948727.95      1329523.87      6949200.30
      1330016.36      6948672.00
#Sta/Elev= 30
  3838.4 2081.20  3870.3 2080.14  3980.7 2080.04  4143.8 2080.51  4215.4 2079.23
  4347.4 2079.30  4473.7 2079.77  4643.2 2078.72  4713.2 2078.81  4748.1 2079.43
  4850.5 2078.05  4912.2 2079.24  4924.7 2077.66  4954.7 2074.85  5004.1 2073.85
  5008.6 2069.12  5009.1 2068.62  5027.8 2069.12  5032.4 2073.20  5039.7 2073.41
  5055.1 2076.30  5060.7 2077.32  5074.9 2076.00  5159.9 2082.31  5280.5 2087.80
  5365.1 2092.00  5393.4 2095.47  5400.3 2094.97  5435.9 2097.65  5568.3 2100.20
#Mann=11,-1,0
  3838.4    0.07       0  3870.3   0.035       0  3980.7    0.07       0
  4347.4   0.035       0  4643.2    0.07       0  4713.2   0.035       0
  4924.7    0.07       0  5008.6    0.07       0  5027.8    0.07       0
  5055.1    0.07       0  5280.5   0.035       0
Bank Sta=5008.6,5027.8
Exp/Cntr=0.3,0.1

Type RM Length L Ch R = 1,5613,444,444,444
BEGIN DESCRIPTION:
Buffalo Creek Trib 02 0.27
END DESCRIPTION:
XS GIS Cut Line= 3
      1328774.68      6948907.52      1329695.40      6949308.47
      1330128.00      6949033.19
#Sta/Elev= 30
  3859.4 2080.69  3916.8 2079.33  4049.4 2079.12  4224.9 2078.96  4429.1 2078.70
  4468.1 2078.68  4522.0 2079.67  4720.4 2078.09  4819.5 2077.54  4922.4 2079.20
  4950.2 2074.81  4973.1 2073.27  4986.6 2073.63  4992.2 2068.85  4992.7 2068.35
  5011.4 2068.85  5017.1 2072.34  5065.3 2078.49  5088.4 2080.06  5132.2 2079.53
  5153.4 2082.74  5159.5 2081.71  5174.6 2084.68  5189.8 2091.51  5195.7 2091.18
  5205.0 2094.12  5211.0 2093.46  5226.2 2097.75  5283.8 2099.00  5376.4 2094.19
#Mann=10,-1,0
  3859.4    0.07       0  3916.8   0.035       0  4049.4    0.07       0
  4224.9   0.035       0  4429.1    0.07       0  4468.1   0.035       0
  4720.4    0.07       0  4973.1   0.035       0  4992.2   0.035       0
  5011.4   0.035       0
Bank Sta=4992.2,5011.4
Exp/Cntr=0.3,0.1

Type RM Length L Ch R = 1,5169,691,691,691
BEGIN DESCRIPTION:
Buffalo Creek Trib 02 0.2
END DESCRIPTION:
XS GIS Cut Line= 4
      1329175.43      6949146.46      1329992.64      6949562.36
      1330094.64      6949558.02      1330285.00      6949517.85
#Sta/Elev= 30
  4020.2 2080.08  4149.6 2078.49  4401.5 2077.84  4446.1 2077.81  4480.5 2078.74
  4535.9 2077.18  4644.1 2077.32  4670.4 2077.98  4691.7 2076.89  4758.4 2077.75
  4808.5 2077.50  4853.0 2074.76  4897.5 2073.64  4928.6 2073.81  4949.5 2072.26
  5000.8 2072.35  5009.6 2070.42  5010.0 2067.52  5010.5 2067.02  5029.2 2067.52
  5029.6 2068.82  5037.4 2071.85  5042.0 2071.85  5059.2 2074.96  5064.4 2074.32
  5070.3 2077.53  5080.5 2080.38  5090.7 2081.45  5163.9 2081.40  5233.8 2080.03
#Mann=9,-1,0
  4020.2    0.07       0  4149.6   0.035       0  4401.5    0.07       0
  4644.1   0.035       0  4670.4    0.07       0  5000.8   0.035       0
  5010.0    0.07       0  5029.2   0.035       0  5037.4    0.07       0
Bank Sta=5010,5029.2
Exp/Cntr=0.3,0.1

Type RM Length L Ch R = 1,4478,555,555,555
BEGIN DESCRIPTION:
Buffalo Creek Trib 02 0.17
END DESCRIPTION:
XS GIS Cut Line= 4
      1329173.06      6949149.32      1329673.07      6949974.46
      1329963.30      6949888.17      1330227.71      6949588.17
#Sta/Elev= 30
  3899.8 2080.08  3951.3 2078.44  4036.4 2078.17  4178.2 2077.63  4220.9 2078.68
  4280.6 2077.24  4395.9 2076.94  4453.3 2077.00  4505.9 2076.49  4554.4 2077.65
  4606.8 2076.33  4942.4 2076.31  4960.5 2075.01  4970.4 2073.39  4981.4 2070.14
  5002.3 2069.22  5004.4 2064.34  5004.9 2063.84  5023.6 2064.34  5033.6 2070.16
  5047.2 2069.85  5060.6 2071.41  5075.2 2072.54  5085.7 2074.61  5108.8 2076.12
  5170.9 2076.14  5175.9 2077.07  5296.4 2076.44  5395.1 2077.22  5567.3 2079.77
#Mann=9,-1,0
  3899.8    0.07       0  4036.4   0.035       0  4280.6    0.07       0
  4395.9   0.035       0  4453.3    0.07       0  5004.4    0.07       0
  5023.6    0.07       0  5060.6   0.035       0  5108.8    0.07       0
Bank Sta=5004.4,5023.6
Exp/Cntr=0.3,0.1

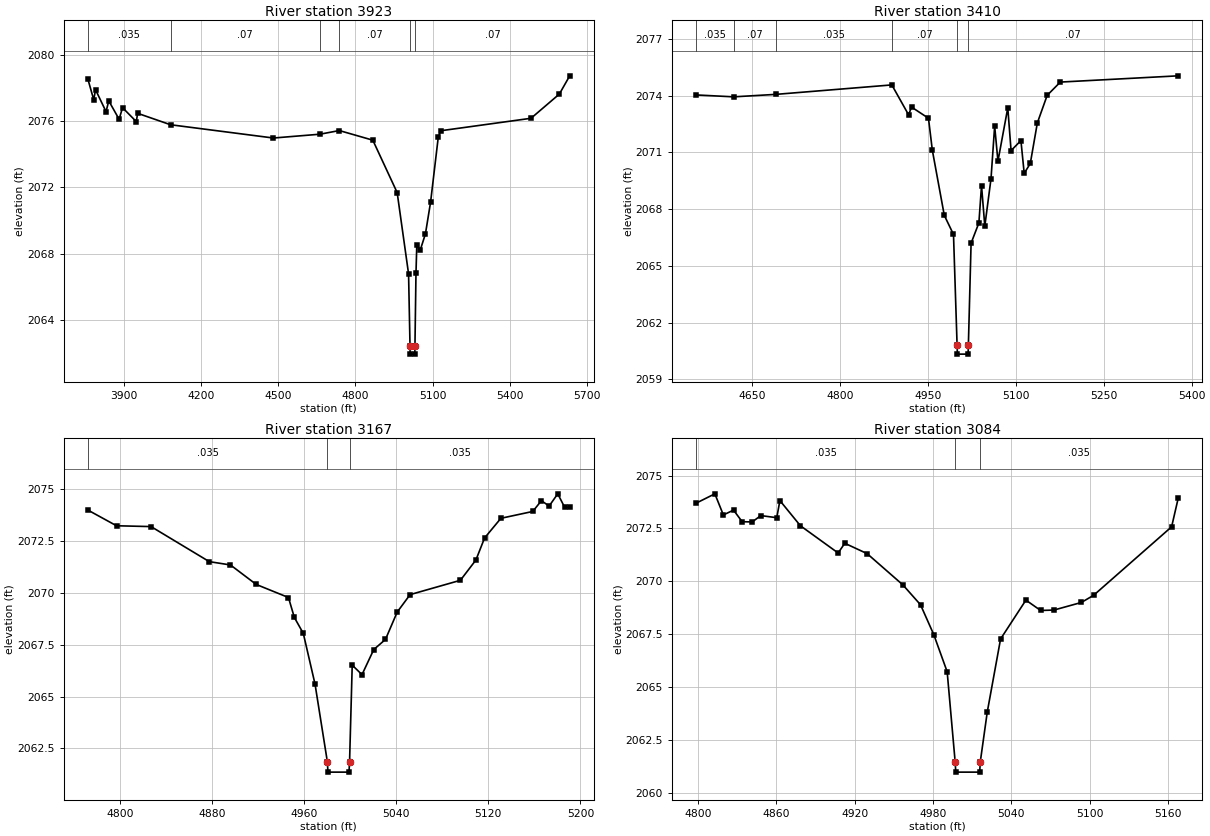
Type RM Length L Ch R = 1,3923,513,513,513
BEGIN DESCRIPTION:
Buffalo Creek Trib 02 0.15
END DESCRIPTION:
XS GIS Cut Line= 4
      1329045.15      6949999.29      1330229.19      6950213.40
      1330289.86      6950174.73      1330308.45      6949577.71
#Sta/Elev= 30
  3759.8 2078.55  3782.9 2077.28  3790.1 2077.88  3830.8 2076.56  3841.4 2077.21
  3881.6 2076.10  3894.9 2076.80  3948.4 2075.96  3953.5 2076.46  4081.6 2075.77
  4481.2 2074.97  4661.8 2075.20  4737.2 2075.42  4867.3 2074.84  4961.9 2071.68
  5006.2 2066.78  5011.8 2062.44  5012.3 2061.94  5030.5 2061.94  5031.0 2062.44
  5035.0 2066.81  5038.1 2068.50  5051.7 2068.22  5071.7 2069.19  5091.7 2071.10
  5121.8 2075.05  5131.8 2075.41  5481.9 2076.16  5592.0 2077.62  5632.3 2078.72
#Mann=6,-1,0
  3759.8   0.035       0  4081.6    0.07       0  4661.8   0.035       0
  4737.2    0.07       0  5011.8    0.07       0  5031.0    0.07       0
Bank Sta=5011.8,5031
Exp/Cntr=0.3,0.1

Type RM Length L Ch R = 1,3410,243,243,243
BEGIN DESCRIPTION:
Buffalo Creek Trib 02 0.1
END DESCRIPTION:
XS GIS Cut Line= 4
      1330258.93      6950465.77      1330663.22      6950473.82
      1330702.28      6950406.54      1330551.08      6950102.08
#Sta/Elev= 30
  4554.9 2074.03  4618.9 2073.93  4690.6 2074.06  4888.6 2074.56  4917.2 2072.98
  4922.2 2073.39  4951.1 2072.80  4957.7 2071.11  4978.1 2067.67  4993.8 2066.66
  4999.9 2060.84  5000.4 2060.34  5018.7 2060.34  5019.2 2060.84  5023.8 2066.20
  5037.1 2067.27  5041.6 2069.24  5047.2 2067.10  5057.8 2069.61  5064.0 2072.39
  5069.6 2070.53  5086.4 2073.35  5092.0 2071.09  5108.8 2071.62  5114.4 2069.89
  5124.8 2070.41  5136.8 2072.55  5153.6 2074.01  5176.0 2074.71  5377.0 2075.04
#Mann=6,-1,0
  4554.9   0.035       0  4618.9    0.07       0  4690.6   0.035       0
  4888.6    0.07       0  4999.9    0.07       0  5019.2    0.07       0
Bank Sta=4999.9,5019.2
Exp/Cntr=0.3,0.1

Type RM Length L Ch R = 1,3167,83,83,83
BEGIN DESCRIPTION:
Buffalo Creek Trib 02 0.09
END DESCRIPTION:
XS GIS Cut Line= 4
      1330852.48      6950762.98      1330850.05      6950685.20
      1330899.14      6950446.78      1330834.06      6950374.10
#Sta/Elev= 30
  4771.9 2074.00  4796.9 2073.24  4826.9 2073.20  4877.5 2071.51  4895.9 2071.35
  4918.3 2070.41  4946.3 2069.78  4951.4 2068.82  4959.2 2068.05  4969.4 2065.60
  4980.1 2061.86  4980.6 2061.36  4998.9 2061.36  4999.4 2061.86  5001.7 2066.52
  5010.2 2066.06  5020.4 2067.27  5030.6 2067.76  5040.8 2069.08  5052.0 2069.92
  5095.7 2070.61  5109.2 2071.59  5116.7 2072.65  5130.9 2073.60  5158.6 2073.93
  5166.1 2074.45  5172.8 2074.19  5180.3 2074.78  5186.3 2074.13  5190.7 2074.13
#Mann=3,-1,0
  4771.9   0.035       0  4980.1   0.035       0  4999.4   0.035       0
Bank Sta=4980.1,4999.4
Exp/Cntr=0.3,0.1

Type RM Length L Ch R = 1,3084,0,0,0
BEGIN DESCRIPTION:
Buffalo Creek Trib 02 0.08
END DESCRIPTION:
XS GIS Cut Line= 4
      1330879.99      6950763.01      1330919.56      6950715.67
      1330967.04      6950491.82      1330959.95      6950413.56
#Sta/Elev= 30
  4798.7 2073.70  4813.0 2074.14  4819.5 2073.14  4827.3 2073.37  4833.9 2072.82
  4841.6 2072.81  4848.2 2073.11  4860.4 2073.01  4862.8 2073.82  4878.5 2072.63
  4907.4 2071.34  4912.5 2071.80  4929.6 2071.31  4957.0 2069.83  4970.5 2068.89
  4980.7 2067.47  4990.9 2065.72  4997.0 2061.47  4997.5 2060.97  5015.8 2060.97
  5016.3 2061.47  5021.6 2063.81  5031.8 2067.27  5051.2 2069.11  5062.5 2068.62
  5072.7 2068.64  5093.7 2069.00  5103.1 2069.34  5162.8 2072.58  5167.8 2073.92
#Mann=3,-1,0
  4798.7   0.035       0  4997.0   0.035       0  5016.3   0.035       0
Bank Sta=4997,5016.3
Exp/Cntr=0.3,0.1

Chan Stop Cuts=-1