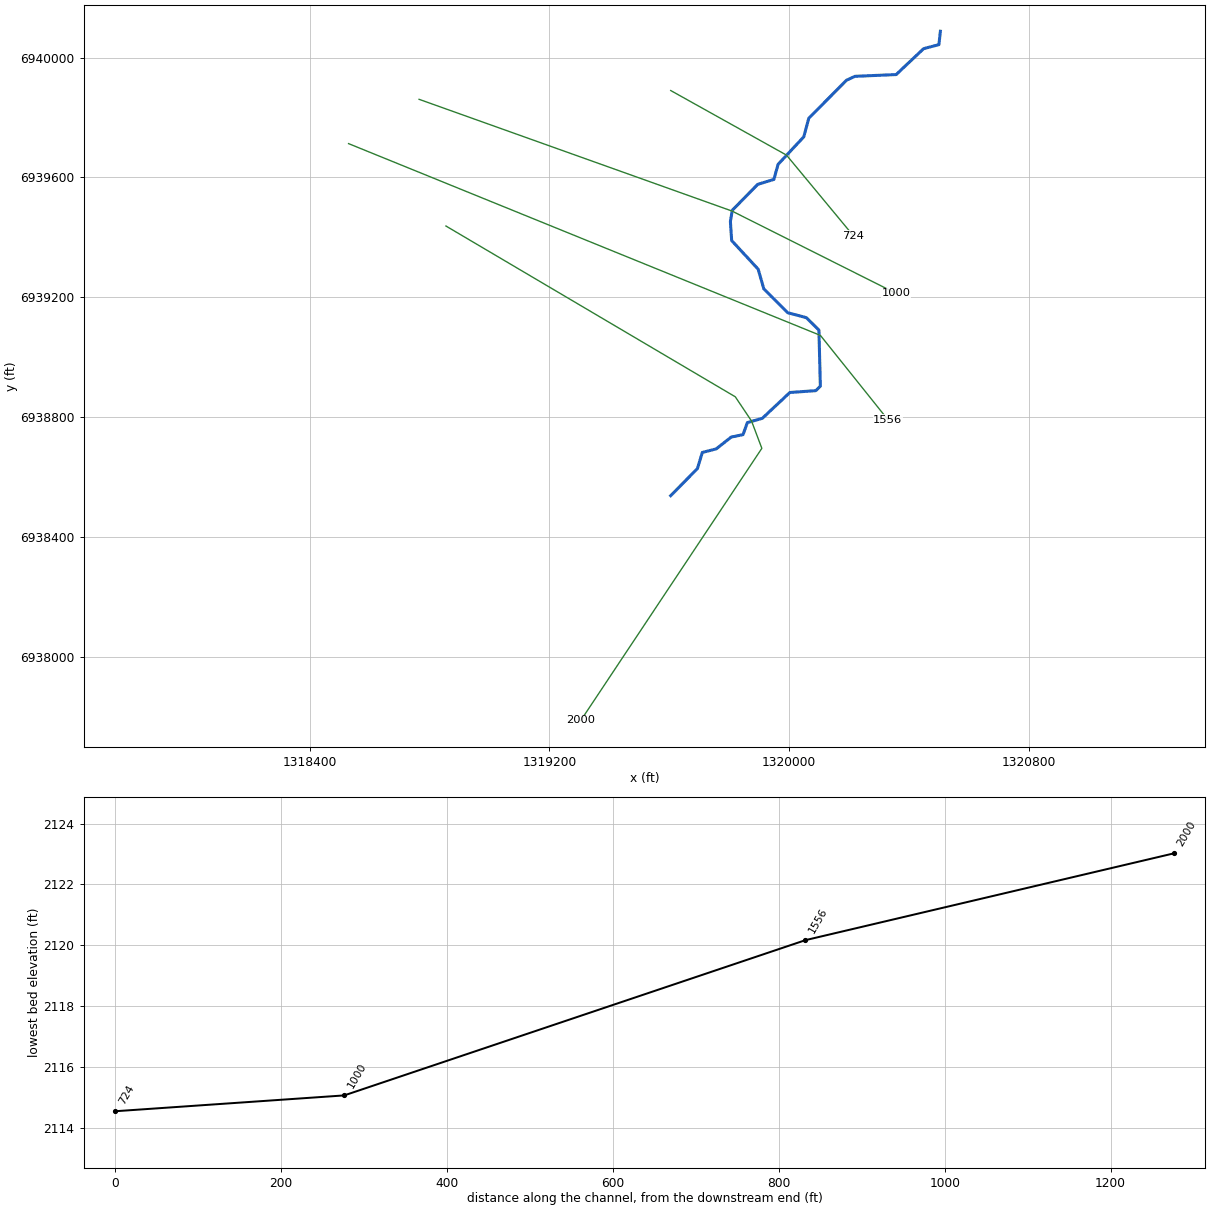
--- Buffalo Creek Trib 03.prj (project) ---

Proj Title=Buffalo Creek Trib 03 Base Level Engineering
Current Plan=p01
Default Exp/Contr=0.3,0.1
English Units
Geom File=g01
Flow File=f01
Plan File=p01
BEGIN DESCRIPTION:
Buffalo Creek Trib 03
END DESCRIPTION:

--- Buffalo Creek Trib 03.p01 (plan) ---

Plan Title=Multiple Run
Short Identifier=Multiple
Geom File=g01
Flow File=f01
Subcritical Flow
K Sum by GR= 0
Std Step Tol= 0.01
Critical Tol= 0.01
Num of Std Step Trials= 20
Max Error Tol= 0.3
Flow Tol Ratio= 0.001
Split Flow NTrial= 30
Split Flow Tol= 0.02
Split Flow Ratio= 0.02
Log Output Level= 0
Friction Slope Method= 1
Unsteady Friction Slope Method= 2
Unsteady Bridges Friction Slope Method= 1
Parabolic Critical Depth
Global Vel Dist=  1 , 1 , 1
Global Log Level= 0
CheckData=True
Encroach Param= -1, 0, 0, 0
BEGIN DESCRIPTION:
Multiple Run
END DESCRIPTION:

--- Buffalo Creek Trib 03.f01 (steady flow) ---

Flow Title=Multiple
Number of Profiles=7
Profile Names=10-year,25-year,50-year,1pct_min,100-year,1pct_plu,500-year
River Rch & RM= Buffalo Creek Tr,Reach-1,2000
     309     443     557     349     696    1388    1099
Boundary for River Rch & Prof#=Buffalo Creek Tr,Reach-1,1
Up Type=0
Dn Type=3
Dn Slope=0.005
Boundary for River Rch & Prof#=Buffalo Creek Tr,Reach-1,2
Up Type=0
Dn Type=3
Dn Slope=0.005
Boundary for River Rch & Prof#=Buffalo Creek Tr,Reach-1,3
Up Type=0
Dn Type=3
Dn Slope=0.005
Boundary for River Rch & Prof#=Buffalo Creek Tr,Reach-1,4
Up Type=0
Dn Type=3
Dn Slope=0.005
Boundary for River Rch & Prof#=Buffalo Creek Tr,Reach-1,5
Up Type=0
Dn Type=3
Dn Slope=0.005
Boundary for River Rch & Prof#=Buffalo Creek Tr,Reach-1,6
Up Type=0
Dn Type=3
Dn Slope=0.005
Boundary for River Rch & Prof#=Buffalo Creek Tr,Reach-1,7
Up Type=0
Dn Type=3
Dn Slope=0.005

--- Buffalo Creek Trib 03.g01 (geometry) ---

Geom Title=Existing Conditions

River Reach=Buffalo Creek Tr,Reach-1
Reach XY= 30
      1319605.00      6938538.00      1319694.17      6938628.58
      1319710.60      6938682.42      1319756.89      6938694.23
      1319807.04      6938733.74      1319846.38      6938741.84
      1319860.77      6938782.01      1319910.76      6938796.25
      1320002.64      6938882.44      1320089.40      6938888.68
      1320104.45      6938903.58      1320099.64      6939090.70
      1320057.57      6939132.26      1319995.32      6939148.78
      1319915.77      6939228.30      1319896.82      6939294.04
      1319808.47      6939389.50      1319804.21      6939453.08
      1319810.39      6939490.44      1319895.56      6939577.12
      1319949.38      6939593.62      1319963.30      6939643.74
      1320049.13      6939735.72      1320065.78      6939797.68
      1320191.68      6939924.63      1320220.16      6939937.60
      1320357.45      6939943.48      1320449.11      6940029.92
      1320500.08      6940043.32      1320505.00      6940088.00

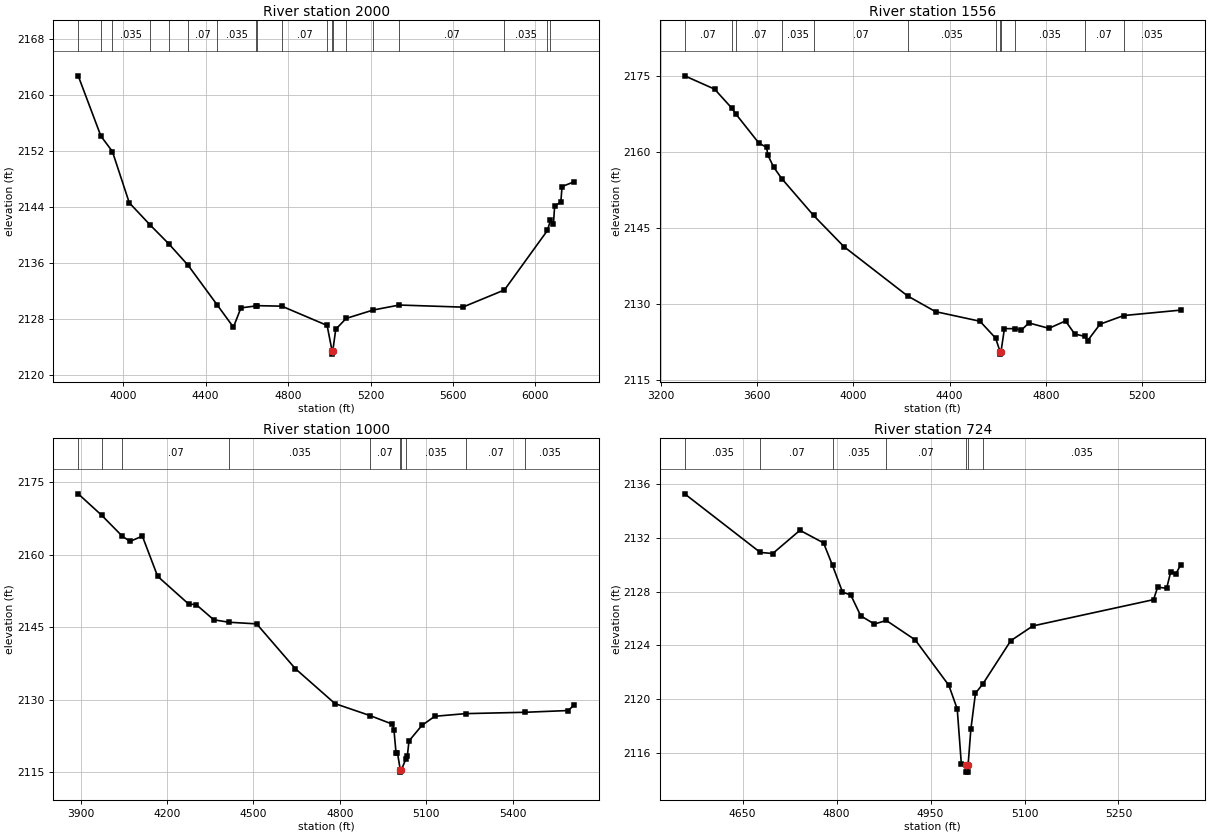
Type RM Length L Ch R = 1,2000,444,444,444
BEGIN DESCRIPTION:
Buffalo Creek Trib 03 4.0
END DESCRIPTION:
XS GIS Cut Line= 5
      1318855.00      6939438.00      1319820.64      6938868.07
      1319874.75      6938787.19      1319909.18      6938696.19
      1319305.00      6937788.00
#Sta/Elev= 30
  3781.4 2162.70  3891.5 2154.11  3947.3 2151.91  4029.2 2144.60  4131.2 2141.41
  4220.5 2138.76  4315.1 2135.67  4454.5 2130.09  4534.6 2126.86  4571.0 2129.61
  4646.2 2129.90  4649.7 2129.93  4769.1 2129.86  4989.3 2127.11  5013.0 2123.52
  5013.2 2123.02  5017.0 2123.52  5031.2 2126.56  5081.6 2128.11  5212.9 2129.31
  5339.7 2130.02  5647.6 2129.72  5849.8 2132.17  6058.4 2140.65  6073.1 2142.10
  6087.4 2141.52  6093.4 2144.11  6123.5 2144.73  6129.5 2146.92  6188.1 2147.59
#Mann=19,-1,0
  3781.4   0.035       0  3891.5    0.07       0  3947.3   0.035       0
  4131.2    0.07       0  4220.5   0.035       0  4315.1    0.07       0
  4454.5   0.035       0  4646.2    0.07       0  4649.7   0.035       0
  4769.1    0.07       0  4989.3   0.035       0  5013.0   0.035       0
  5017.0   0.035       0  5081.6    0.07       0  5212.9   0.035       0
  5339.7    0.07       0  5849.8   0.035       0  6058.4    0.07       0
  6073.1   0.035       0
Bank Sta=5013,5017
Exp/Cntr=0.3,0.1

Type RM Length L Ch R = 1,1556,556,556,556
BEGIN DESCRIPTION:
Buffalo Creek Trib 03 3.0
END DESCRIPTION:
XS GIS Cut Line= 3
      1318529.98      6939713.01      1320104.67      6939072.97
      1320329.41      6938792.24
#Sta/Elev= 30
  3300.2 2175.00  3424.4 2172.38  3495.9 2168.63  3514.2 2167.39  3607.9 2161.77
  3640.2 2160.90  3645.6 2159.38  3669.6 2157.02  3703.3 2154.75  3835.3 2147.50
  3961.4 2141.35  4225.7 2131.64  4341.9 2128.54  4526.3 2126.65  4591.3 2123.33
  4609.8 2120.67  4610.0 2120.17  4613.8 2120.67  4628.0 2125.20  4672.1 2125.18
  4698.1 2124.90  4729.7 2126.31  4812.7 2125.25  4881.6 2126.71  4919.8 2124.14
  4961.0 2123.67  4973.4 2122.82  5025.0 2126.07  5123.3 2127.77  5359.6 2128.84
#Mann=12,-1,0
  3300.2    0.07       0  3495.9   0.035       0  3514.2    0.07       0
  3703.3   0.035       0  3835.3    0.07       0  4225.7   0.035       0
  4591.3    0.07       0  4609.8    0.07       0  4613.8    0.07       0
  4672.1   0.035       0  4961.0    0.07       0  5123.3   0.035       0
Bank Sta=4609.8,4613.8
Exp/Cntr=0.3,0.1

Type RM Length L Ch R = 1,1000,276,276,276
BEGIN DESCRIPTION:
Buffalo Creek Trib 03 2.0
END DESCRIPTION:
XS GIS Cut Line= 3
      1318765.30      6939860.87      1319809.25      6939488.13
      1320357.60      6939213.00
#Sta/Elev= 30
  3891.5 2172.59  3973.1 2168.15  4045.1 2163.80  4071.7 2162.77  4114.2 2163.85
  4167.3 2155.54  4275.3 2149.79  4300.8 2149.71  4362.3 2146.55  4415.2 2146.05
  4511.0 2145.71  4645.1 2136.47  4783.1 2129.23  4904.6 2126.76  4982.5 2124.98
  4987.8 2123.78  4995.1 2119.05  5000.0 2119.05  5009.7 2115.57  5009.9 2115.07
  5013.8 2115.57  5029.5 2117.83  5034.1 2118.31  5040.0 2121.51  5084.8 2124.72
  5129.5 2126.61  5236.4 2127.16  5443.1 2127.44  5592.5 2127.80  5613.5 2128.93
#Mann=10,-1,0
  3891.5    0.07       0  3973.1   0.035       0  4045.1    0.07       0
  4415.2   0.035       0  4904.6    0.07       0  5009.7    0.07       0
  5013.8    0.07       0  5029.5   0.035       0  5236.4    0.07       0
  5443.1   0.035       0
Bank Sta=5009.7,5013.8
Exp/Cntr=0.3,0.1

Type RM Length L Ch R = 1,724,0,0,0
BEGIN DESCRIPTION:
Buffalo Creek Trib 03 1.0
END DESCRIPTION:
XS GIS Cut Line= 3
      1319605.00      6939890.24      1319991.45      6939674.70
      1320214.34      6939405.88
#Sta/Elev= 30
  4557.5 2135.30  4678.2 2130.93  4698.1 2130.85  4741.5 2132.58  4779.2 2131.64
  4793.5 2129.96  4809.4 2127.98  4822.7 2127.75  4838.6 2126.20  4860.4 2125.59
  4879.3 2125.86  4925.5 2124.41  4979.2 2121.02  4992.6 2119.26  4999.2 2115.13
  5005.8 2115.05  5006.0 2114.55  5009.6 2114.55  5009.9 2115.05  5014.3 2117.73
  5021.7 2120.43  5033.4 2121.12  5078.1 2124.35  5113.3 2125.45  5306.0 2127.41
  5312.5 2128.34  5326.9 2128.26  5333.5 2129.50  5341.2 2129.29  5349.2 2130.00
#Mann=7,-1,0
  4557.5   0.035       0  4678.2    0.07       0  4793.5   0.035       0
  4879.3    0.07       0  5005.8    0.07       0  5009.9    0.07       0
  5033.4   0.035       0
Bank Sta=5005.8,5009.9
Exp/Cntr=0.3,0.1

Chan Stop Cuts=-1