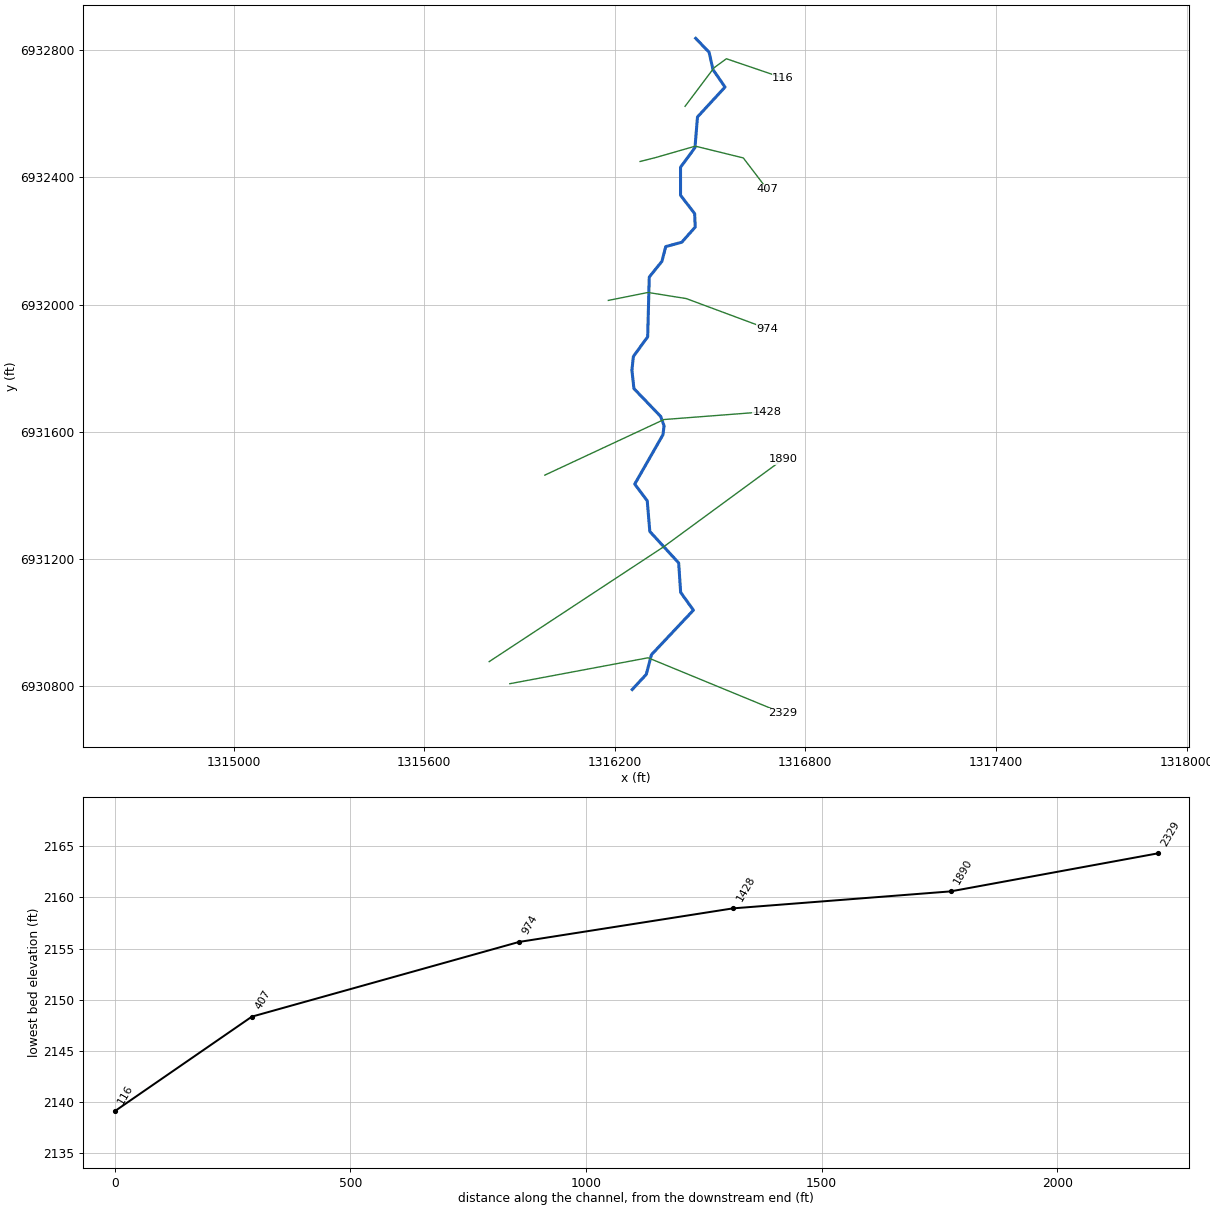
--- Buffalo Creek Trib 04.prj (project) ---

Proj Title=Buffalo Creek Trib 04 Base Level Engineering
Current Plan=p01
Default Exp/Contr=0.3,0.1
English Units
Geom File=g01
Flow File=f01
Plan File=p01
BEGIN DESCRIPTION:
Buffalo Creek Trib 04
END DESCRIPTION:

--- Buffalo Creek Trib 04.p01 (plan) ---

Plan Title=Multiple Run
Short Identifier=Multiple
Geom File=g01
Flow File=f01
Subcritical Flow
K Sum by GR= 0
Std Step Tol= 0.01
Critical Tol= 0.01
Num of Std Step Trials= 20
Max Error Tol= 0.3
Flow Tol Ratio= 0.001
Split Flow NTrial= 30
Split Flow Tol= 0.02
Split Flow Ratio= 0.02
Log Output Level= 0
Friction Slope Method= 1
Unsteady Friction Slope Method= 2
Unsteady Bridges Friction Slope Method= 1
Parabolic Critical Depth
Global Vel Dist=  1 , 1 , 1
Global Log Level= 0
CheckData=True
Encroach Param= -1, 0, 0, 0
BEGIN DESCRIPTION:
Multiple Run
END DESCRIPTION:

--- Buffalo Creek Trib 04.f01 (steady flow) ---

Flow Title=Multiple
Number of Profiles=7
Profile Names=10-year,25-year,50-year,1pct_min,100-year,1pct_plu,500-year
River Rch & RM= Buffalo Creek Tr,Reach-1,2329
     265     375     468     290     580    1156     900
Boundary for River Rch & Prof#=Buffalo Creek Tr,Reach-1,1
Up Type=0
Dn Type=3
Dn Slope=0.005
Boundary for River Rch & Prof#=Buffalo Creek Tr,Reach-1,2
Up Type=0
Dn Type=3
Dn Slope=0.005
Boundary for River Rch & Prof#=Buffalo Creek Tr,Reach-1,3
Up Type=0
Dn Type=3
Dn Slope=0.005
Boundary for River Rch & Prof#=Buffalo Creek Tr,Reach-1,4
Up Type=0
Dn Type=3
Dn Slope=0.005
Boundary for River Rch & Prof#=Buffalo Creek Tr,Reach-1,5
Up Type=0
Dn Type=3
Dn Slope=0.005
Boundary for River Rch & Prof#=Buffalo Creek Tr,Reach-1,6
Up Type=0
Dn Type=3
Dn Slope=0.005
Boundary for River Rch & Prof#=Buffalo Creek Tr,Reach-1,7
Up Type=0
Dn Type=3
Dn Slope=0.005

--- Buffalo Creek Trib 04.g01 (geometry) ---

Geom Title=Existing Conditions

River Reach=Buffalo Creek Tr,Reach-1
Reach XY= 30
      1316255.00      6930788.00      1316299.29      6930835.65
      1316315.70      6930897.71      1316447.69      6931037.90
      1316407.56      6931093.89      1316401.38      6931186.50
      1316310.53      6931285.58      1316302.44      6931382.10
      1316263.05      6931434.71      1316351.69      6931589.73
      1316355.40      6931617.87      1316344.79      6931647.67
      1316260.41      6931735.58      1316254.17      6931793.02
      1316258.70      6931836.40      1316303.78      6931898.50
      1316308.74      6932086.48      1316348.72      6932136.16
      1316360.63      6932182.38      1316411.13      6932196.17
      1316453.43      6932243.86      1316451.67      6932286.23
      1316407.19      6932343.96      1316407.17      6932432.03
      1316452.64      6932493.98      1316460.55      6932590.43
      1316547.23      6932684.60      1316509.34      6932739.58
      1316497.12      6932794.14      1316455.00      6932838.00

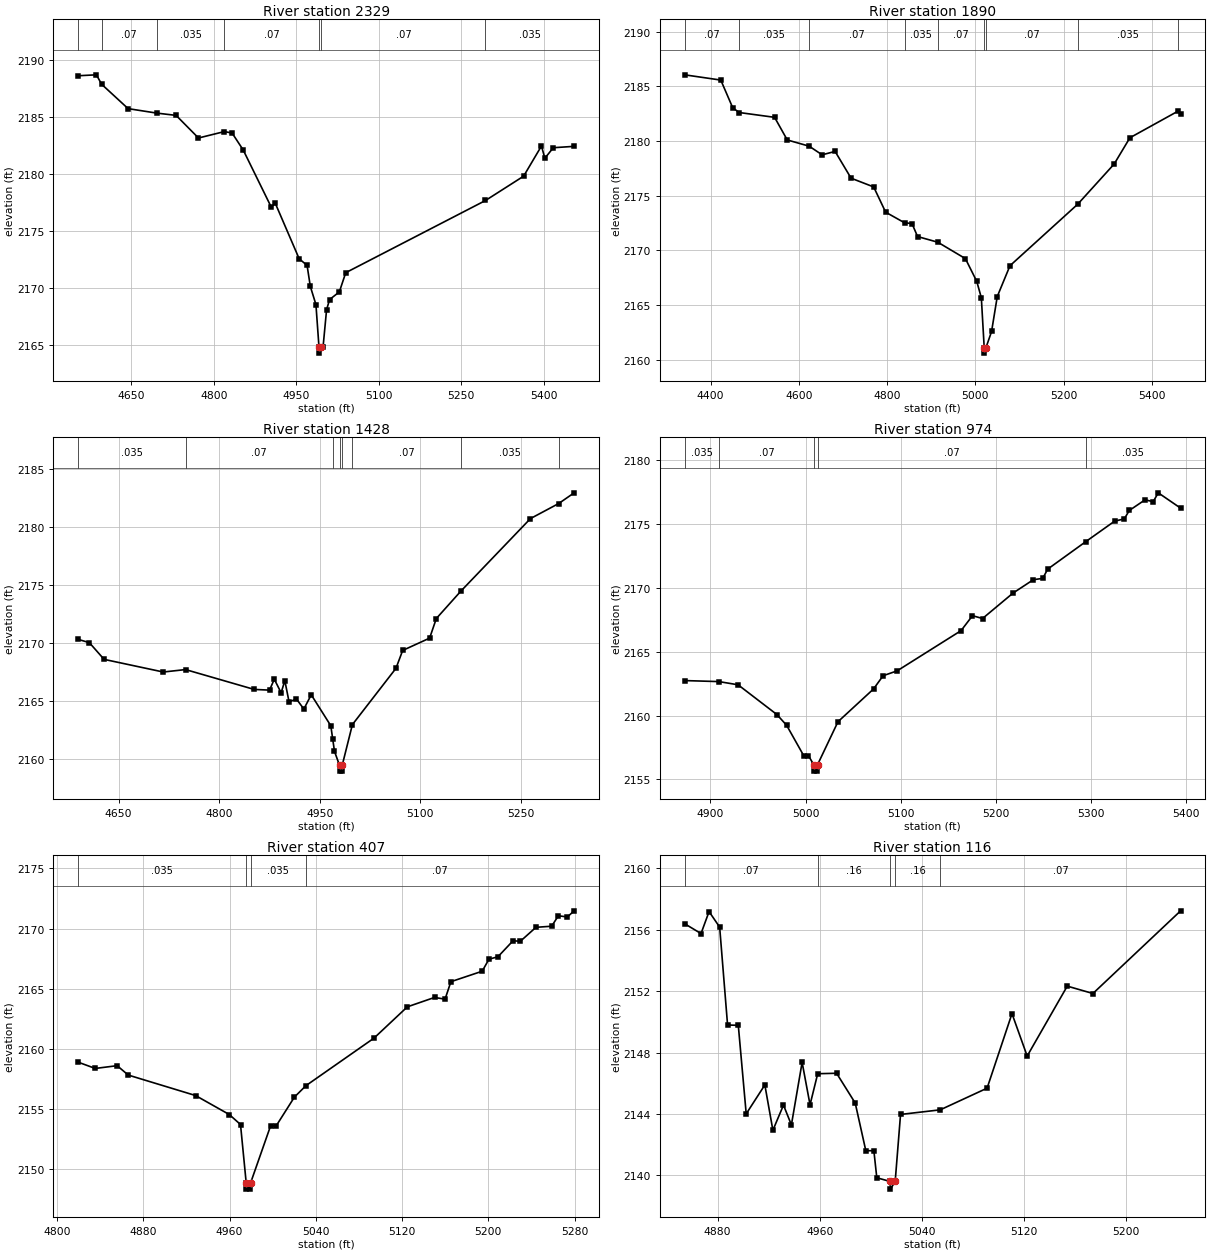
Type RM Length L Ch R = 1,2329,439,439,439
BEGIN DESCRIPTION:
Buffalo Creek Trib 04 4.0
END DESCRIPTION:
XS GIS Cut Line= 3
      1315869.90      6930806.44      1316305.00      6930888.00
      1316730.00      6930713.00
#Sta/Elev= 30
  4553.2 2188.58  4586.3 2188.66  4595.9 2187.83  4644.0 2185.70  4696.1 2185.31
  4731.3 2185.11  4772.0 2183.13  4819.0 2183.69  4833.1 2183.57  4853.4 2182.08
  4904.3 2177.09  4911.9 2177.40  4955.2 2172.56  4969.6 2171.98  4975.5 2170.14
  4985.7 2168.55  4991.3 2164.80  4991.6 2164.30  4995.3 2164.80  4998.6 2164.80
  5005.1 2168.11  5010.6 2168.99  5028.3 2169.66  5039.9 2171.34  5294.2 2177.66
  5363.6 2179.79  5396.0 2182.43  5402.2 2181.36  5417.6 2182.28  5455.5 2182.40
#Mann=7,-1,0
  4553.2   0.035       0  4595.9    0.07       0  4696.1   0.035       0
  4819.0    0.07       0  4991.3    0.07       0  4995.3    0.07       0
  5294.2   0.035       0
Bank Sta=4991.3,4995.3
Exp/Cntr=0.3,0.1

Type RM Length L Ch R = 1,1890,462,462,462
BEGIN DESCRIPTION:
Buffalo Creek Trib 04 3.0
END DESCRIPTION:
XS GIS Cut Line= 3
      1315804.85      6930875.91      1316355.00      6931238.00
      1316729.97      6931512.98
#Sta/Elev= 30
  4341.4 2186.06  4423.2 2185.58  4450.3 2183.04  4465.0 2182.61  4545.1 2182.17
  4573.8 2180.10  4623.4 2179.53  4652.8 2178.74  4682.2 2179.05  4718.4 2176.60
  4769.6 2175.80  4796.7 2173.49  4839.5 2172.52  4856.4 2172.45  4869.0 2171.26
  4914.9 2170.74  4977.4 2169.24  5003.1 2167.16  5013.5 2165.66  5020.0 2161.09
  5020.2 2160.59  5024.0 2161.09  5036.7 2162.57  5049.6 2165.77  5078.4 2168.59
  5231.9 2174.22  5314.5 2177.90  5350.1 2180.30  5458.0 2182.71  5465.0 2182.51
#Mann=9,-1,0
  4341.4    0.07       0  4465.0   0.035       0  4623.4    0.07       0
  4839.5   0.035       0  4914.9    0.07       0  5020.0    0.07       0
  5024.0    0.07       0  5231.9   0.035       0  5458.0    0.07       0
Bank Sta=5020,5024
Exp/Cntr=0.3,0.1

Type RM Length L Ch R = 1,1428,454,454,454
BEGIN DESCRIPTION:
Buffalo Creek Trib 04 2.0
END DESCRIPTION:
XS GIS Cut Line= 3
      1315979.98      6931462.99      1316355.00      6931638.00
      1316680.00      6931663.00
#Sta/Elev= 30
  4589.7 2170.28  4606.3 2170.00  4628.3 2168.56  4716.6 2167.47  4749.8 2167.68
  4852.2 2165.97  4875.1 2165.91  4882.2 2166.85  4892.4 2165.68  4897.9 2166.73
  4904.2 2164.90  4915.3 2165.14  4926.3 2164.28  4937.3 2165.51  4966.5 2162.84
  4969.3 2161.71  4972.0 2160.63  4979.5 2159.43  4979.7 2158.93  4983.2 2158.93
  4983.5 2159.43  4998.7 2162.94  5063.7 2167.79  5073.7 2169.33  5113.9 2170.39
  5123.9 2172.08  5160.2 2174.42  5264.3 2180.69  5306.5 2181.99  5329.5 2182.91
#Mann=8,-1,0
  4589.7   0.035       0  4749.8    0.07       0  4969.3    0.16       0
  4979.5    0.07       0  4983.5    0.16       0  4998.7    0.07       0
  5160.2   0.035       0  5306.5    0.07       0
Bank Sta=4979.5,4983.5
Exp/Cntr=0.3,0.1

Type RM Length L Ch R = 1,974,567,567,567
BEGIN DESCRIPTION:
Buffalo Creek Trib 04 1.0
END DESCRIPTION:
XS GIS Cut Line= 4
      1316179.97      6932012.99      1316305.00      6932038.00
      1316425.10      6932018.82      1316680.03      6931924.07
#Sta/Elev= 30
  4872.9 2162.74  4908.9 2162.66  4929.0 2162.41  4969.8 2160.08  4980.0 2159.24
  4997.9 2156.87  5002.9 2156.87  5008.5 2156.15  5008.8 2155.65  5012.3 2155.65
  5012.5 2156.15  5034.0 2159.52  5071.3 2162.08  5081.4 2163.12  5096.1 2163.50
  5163.3 2166.65  5175.3 2167.82  5185.9 2167.60  5217.9 2169.59  5239.3 2170.64
  5249.1 2170.74  5254.4 2171.47  5294.2 2173.61  5324.6 2175.22  5334.8 2175.40
  5340.1 2176.06  5356.6 2176.89  5365.2 2176.75  5370.5 2177.44  5394.0 2176.24
#Mann=5,-1,0
  4872.9   0.035       0  4908.9    0.07       0  5008.5    0.07       0
  5012.5    0.07       0  5294.2   0.035       0
Bank Sta=5008.5,5012.5
Exp/Cntr=0.3,0.1

Type RM Length L Ch R = 1,407,291,291,291
BEGIN DESCRIPTION:
Buffalo Creek Trib 04 0.5
END DESCRIPTION:
XS GIS Cut Line= 5
      1316279.99      6932450.33      1316330.00      6932463.00
      1316453.67      6932498.65      1316604.79      6932461.53
      1316680.02      6932362.97
#Sta/Elev= 30
  4819.7 2158.90  4835.5 2158.38  4855.8 2158.61  4866.1 2157.83  4928.5 2156.13
  4959.8 2154.55  4970.2 2153.72  4975.5 2148.85  4975.7 2148.35  4979.2 2148.35
  4979.5 2148.85  4998.1 2153.61  5003.3 2153.61  5020.2 2156.00  5030.9 2156.95
  5094.0 2160.90  5124.9 2163.50  5150.1 2164.28  5159.9 2164.14  5165.3 2165.59
  5194.3 2166.46  5200.6 2167.46  5208.9 2167.66  5222.9 2168.99  5229.7 2168.95
  5244.2 2170.11  5258.7 2170.20  5265.0 2171.07  5273.3 2170.97  5279.6 2171.48
#Mann=4,-1,0
  4819.7   0.035       0  4975.5   0.035       0  4979.5   0.035       0
  5030.9    0.07       0
Bank Sta=4975.5,4979.5
Exp/Cntr=0.3,0.1

Type RM Length L Ch R = 1,116,0,0,0
BEGIN DESCRIPTION:
Buffalo Creek Trib 04 0.4
END DESCRIPTION:
XS GIS Cut Line= 4
      1316421.41      6932623.93      1316512.75      6932745.42
      1316551.63      6932773.69      1316730.02      6932712.99
#Sta/Elev= 30
  4854.2 2156.38  4867.0 2155.74  4873.3 2157.17  4881.6 2156.16  4887.8 2149.79
  4896.2 2149.77  4902.4 2144.01  4917.0 2145.89  4923.3 2142.94  4931.6 2144.58
  4937.8 2143.29  4946.2 2147.36  4952.4 2144.60  4958.4 2146.62  4973.2 2146.65
  4987.8 2144.71  4996.1 2141.61  5002.4 2141.61  5004.7 2139.85  5015.1 2139.61
  5015.4 2139.11  5019.1 2139.61  5023.3 2143.97  5054.4 2144.27  5091.1 2145.68
  5110.6 2150.53  5122.5 2147.77  5153.9 2152.32  5174.0 2151.84  5242.7 2157.22
#Mann=5,-1,0
  4854.2    0.07       0  4958.4    0.16       0  5015.1    0.07       0
  5019.1    0.16       0  5054.4    0.07       0
Bank Sta=5015.1,5019.1
Exp/Cntr=0.3,0.1

Chan Stop Cuts=-1