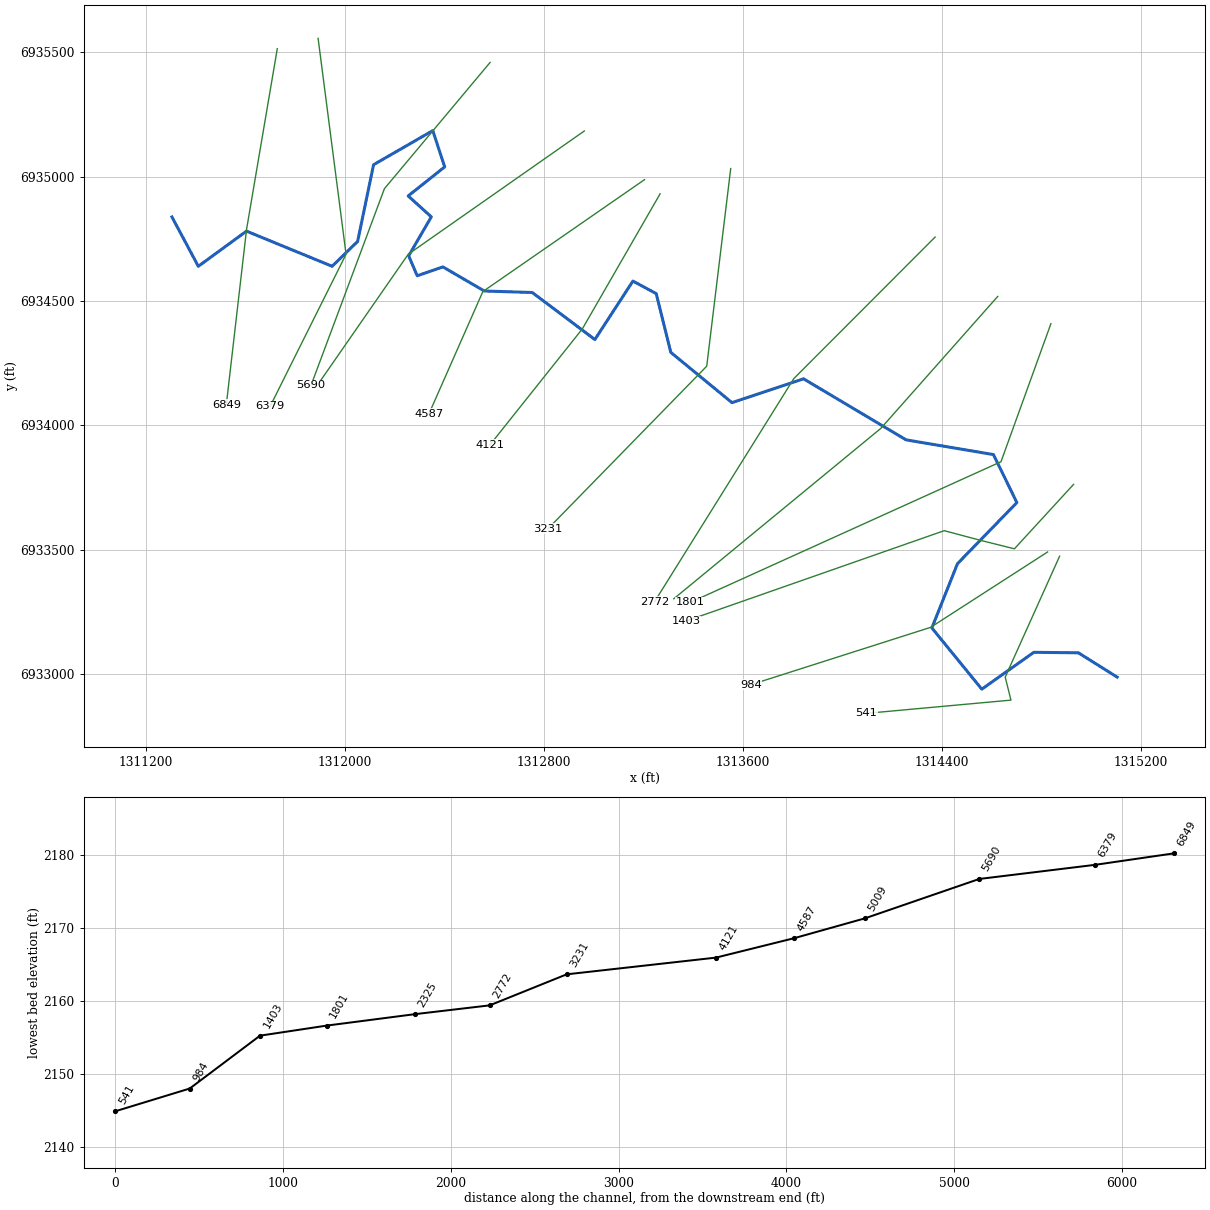
--- Buffalo Creek Trib 05.prj (project) ---

Proj Title=Buffalo Creek Trib 05 Base Level Engineering
Current Plan=p01
Default Exp/Contr=0.3,0.1
English Units
Geom File=g01
Flow File=f01
Plan File=p01
BEGIN DESCRIPTION:
Buffalo Creek Trib 05
END DESCRIPTION:

--- Buffalo Creek Trib 05.p01 (plan) ---

Plan Title=Multiple Run
Short Identifier=Multiple
Geom File=g01
Flow File=f01
Subcritical Flow
K Sum by GR= 0
Std Step Tol= 0.01
Critical Tol= 0.01
Num of Std Step Trials= 20
Max Error Tol= 0.3
Flow Tol Ratio= 0.001
Split Flow NTrial= 30
Split Flow Tol= 0.02
Split Flow Ratio= 0.02
Log Output Level= 0
Friction Slope Method= 1
Unsteady Friction Slope Method= 2
Unsteady Bridges Friction Slope Method= 1
Parabolic Critical Depth
Global Vel Dist=  1 , 1 , 1
Global Log Level= 0
CheckData=True
Encroach Param= -1, 0, 0, 0
BEGIN DESCRIPTION:
Multiple Run
END DESCRIPTION:

--- Buffalo Creek Trib 05.f01 (steady flow) ---

Flow Title=Multiple
Number of Profiles=7
Profile Names=10-year,25-year,50-year,1pct_min,100-year,1pct_plu,500-year
River Rch & RM= Buffalo Creek Tr,Reach-1,6849
     427     620     786     495     988    1971    1581
Boundary for River Rch & Prof#=Buffalo Creek Tr,Reach-1,1
Up Type=0
Dn Type=3
Dn Slope=0.005
Boundary for River Rch & Prof#=Buffalo Creek Tr,Reach-1,2
Up Type=0
Dn Type=3
Dn Slope=0.005
Boundary for River Rch & Prof#=Buffalo Creek Tr,Reach-1,3
Up Type=0
Dn Type=3
Dn Slope=0.005
Boundary for River Rch & Prof#=Buffalo Creek Tr,Reach-1,4
Up Type=0
Dn Type=3
Dn Slope=0.005
Boundary for River Rch & Prof#=Buffalo Creek Tr,Reach-1,5
Up Type=0
Dn Type=3
Dn Slope=0.005
Boundary for River Rch & Prof#=Buffalo Creek Tr,Reach-1,6
Up Type=0
Dn Type=3
Dn Slope=0.005
Boundary for River Rch & Prof#=Buffalo Creek Tr,Reach-1,7
Up Type=0
Dn Type=3
Dn Slope=0.005

--- Buffalo Creek Trib 05.g01 (geometry) ---

Geom Title=Existing Conditions

River Reach=Buffalo Creek Tr,Reach-1
Reach XY= 30
      1311305.00      6934838.00      1311411.03      6934639.61
      1311604.79      6934780.98      1311948.98      6934639.61
      1312051.47      6934739.45      1312115.63      6935048.00
      1312353.60      6935185.00      1312401.63      6935039.29
      1312254.71      6934922.42      1312347.77      6934838.29
      1312256.76      6934681.80      1312291.13      6934601.40
      1312394.29      6934637.20      1312560.93      6934540.24
      1312753.45      6934534.25      1313005.30      6934345.17
      1313158.26      6934580.19      1313251.92      6934529.75
      1313310.58      6934293.58      1313556.49      6934091.46
      1313844.31      6934187.24      1314256.58      6933941.83
      1314607.70      6933882.64      1314701.88      6933689.63
      1314463.14      6933444.06      1314360.09      6933185.70
      1314560.86      6932939.54      1314770.04      6933087.66
      1314949.08      6933085.77      1315105.00      6932988.00

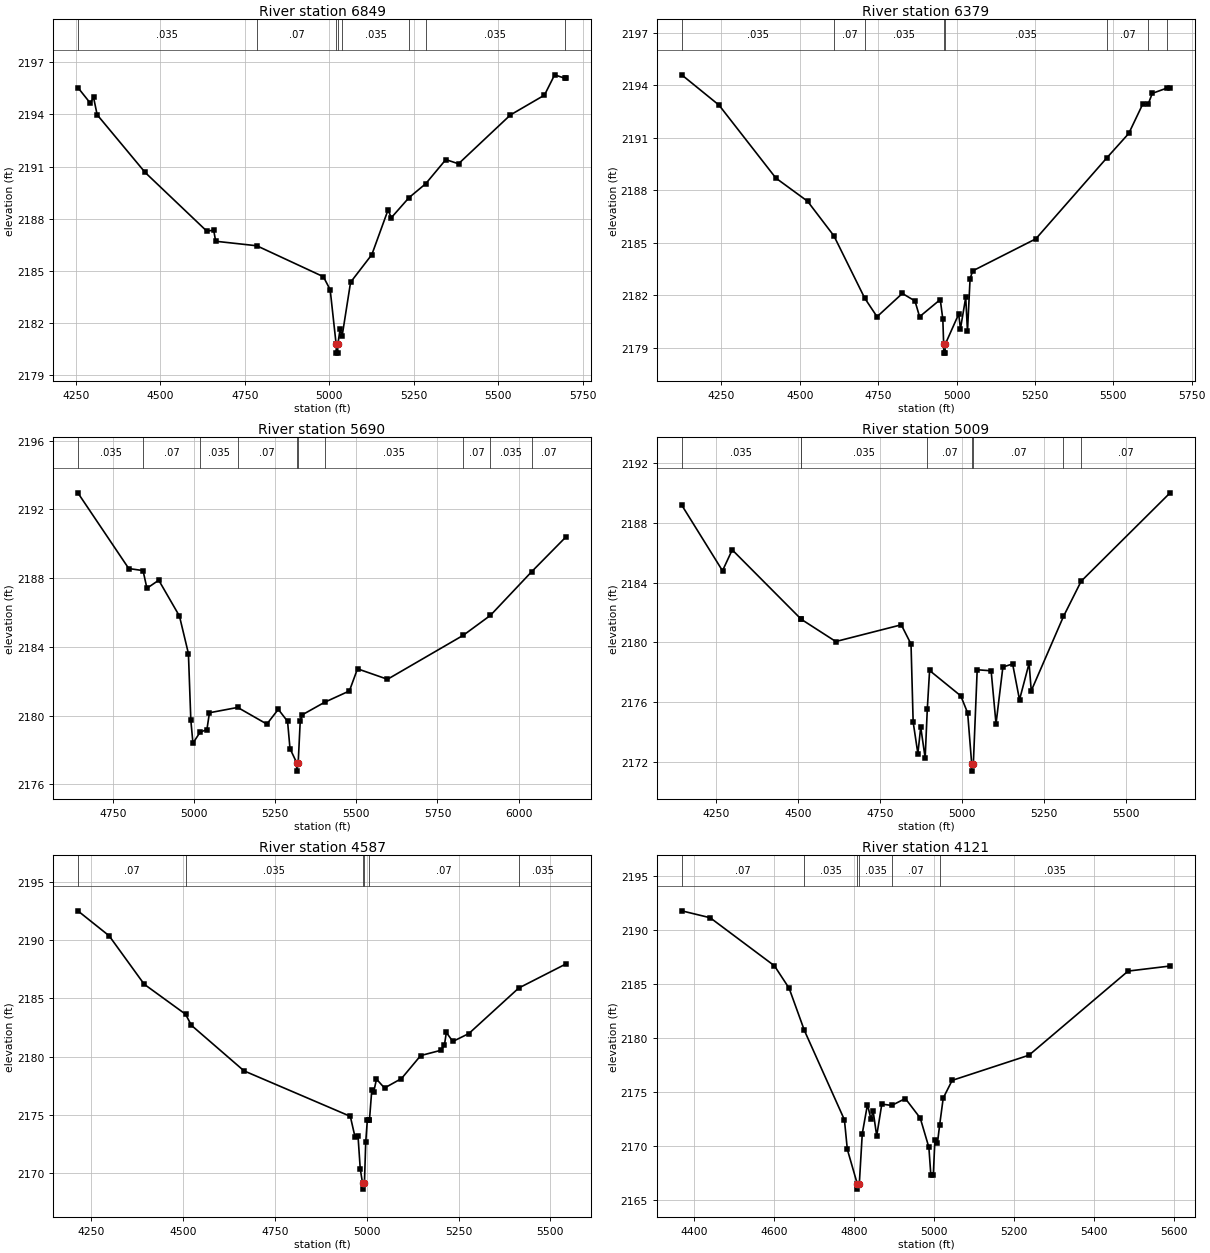
Type RM Length L Ch R = 1,6849,470,470,470
BEGIN DESCRIPTION:
Buffalo Creek Trib 05 11.0
END DESCRIPTION:
XS GIS Cut Line= 3
      1311728.55      6935514.40      1311605.00      6934788.00
      1311523.68      6934083.82
#Sta/Elev= 30
  4256.0 2195.55  4292.9 2194.65  4302.5 2194.98  4313.2 2193.98  4455.2 2190.66
  4637.8 2187.28  4658.1 2187.34  4664.0 2186.70  4785.7 2186.44  4982.7 2184.66
  5002.9 2183.91  5020.6 2180.76  5020.9 2180.26  5025.1 2180.26  5025.5 2180.76
  5032.2 2181.63  5038.5 2181.27  5063.3 2184.34  5126.2 2185.93  5174.0 2188.49
  5184.1 2188.06  5236.2 2189.21  5285.6 2190.01  5345.2 2191.40  5382.8 2191.16
  5536.4 2193.97  5637.1 2195.11  5667.3 2196.28  5698.0 2196.08  5701.7 2196.08
#Mann=8,-1,0
  4256.0   0.035       0  4785.7    0.07       0  5020.6    0.07       0
  5025.5    0.07       0  5038.5   0.035       0  5236.2    0.07       0
  5285.6   0.035       0  5698.0    0.07       0
Bank Sta=5020.6,5025.5
Exp/Cntr=0.3,0.1

Type RM Length L Ch R = 1,6379,689,689,689
BEGIN DESCRIPTION:
Buffalo Creek Trib 05 10.0
END DESCRIPTION:
XS GIS Cut Line= 3
      1311892.61      6935556.05      1312005.00      6934688.00
      1311699.97      6934077.01
#Sta/Elev= 30
  4123.1 2194.59  4242.1 2192.86  4423.6 2188.69  4524.5 2187.37  4608.7 2185.39
  4707.0 2181.83  4746.3 2180.77  4827.0 2182.10  4867.3 2181.67  4882.0 2180.77
  4948.0 2181.75  4956.2 2180.62  4958.8 2179.19  4959.2 2178.69  4963.4 2178.69
  4963.7 2179.19  5006.8 2180.92  5012.4 2180.08  5029.2 2181.87  5034.8 2179.94
  5043.1 2182.94  5051.5 2183.39  5252.9 2185.22  5478.5 2189.83  5549.3 2191.24
  5594.0 2192.92  5611.0 2192.90  5624.3 2193.53  5670.6 2193.83  5681.3 2193.85
#Mann=8,-1,0
  4123.1   0.035       0  4608.7    0.07       0  4707.0   0.035       0
  4958.8   0.035       0  4963.7   0.035       0  5478.5    0.07       0
  5611.0   0.035       0  5670.6    0.07       0
Bank Sta=4958.8,4963.7
Exp/Cntr=0.3,0.1

Type RM Length L Ch R = 1,5690,681,681,681
BEGIN DESCRIPTION:
Buffalo Creek Trib 05 9.5
END DESCRIPTION:
XS GIS Cut Line= 3
      1312584.18      6935459.24      1312159.26      6934951.69
      1311864.57      6934161.92
#Sta/Elev= 30
  4641.9 2192.97  4798.8 2188.56  4842.8 2188.44  4854.8 2187.41  4891.2 2187.88
  4955.0 2185.79  4982.6 2183.61  4990.1 2179.71  4996.6 2178.39  5018.7 2179.03
  5039.6 2179.18  5047.4 2180.16  5134.5 2180.47  5224.3 2179.50  5259.5 2180.36
  5288.1 2179.66  5295.6 2178.07  5315.9 2177.26  5316.3 2176.76  5320.9 2177.26
  5327.1 2179.67  5332.4 2180.03  5402.2 2180.77  5478.6 2181.43  5503.6 2182.72
  5596.0 2182.11  5829.3 2184.67  5913.0 2185.83  6040.4 2188.38  6146.8 2190.42
#Mann=10,-1,0
  4641.9   0.035       0  4842.8    0.07       0  5018.7   0.035       0
  5134.5    0.07       0  5315.9    0.07       0  5320.9    0.07       0
  5402.2   0.035       0  5829.3    0.07       0  5913.0   0.035       0
  6040.4    0.07       0
Bank Sta=5315.9,5320.9
Exp/Cntr=0.3,0.1

Type RM Length L Ch R = 1,5009,422,422,422
BEGIN DESCRIPTION:
Buffalo Creek Trib 05 9.0
END DESCRIPTION:
XS GIS Cut Line= 3
      1312962.92      6935183.64      1312255.00      6934688.00
      1311898.92      6934174.82
#Sta/Elev= 30
  4144.6 2189.19  4269.0 2184.79  4298.6 2186.19  4508.6 2181.55  4509.0 2181.54
  4614.3 2180.05  4813.9 2181.17  4843.6 2179.88  4850.1 2174.66  4864.5 2172.54
  4873.2 2174.32  4886.7 2172.25  4893.2 2175.52  4900.2 2178.11  4995.3 2176.41
  5016.2 2175.27  5028.5 2171.87  5028.9 2171.37  5033.6 2171.87  5045.3 2178.16
  5087.8 2178.09  5102.7 2174.54  5123.6 2178.34  5153.3 2178.55  5174.3 2176.15
  5203.5 2178.59  5210.1 2176.75  5308.3 2181.73  5362.2 2184.09  5633.4 2190.01
#Mann=8,-1,0
  4144.6   0.035       0  4508.6    0.07       0  4509.0   0.035       0
  4893.2    0.07       0  5028.5    0.07       0  5033.6    0.07       0
  5308.3   0.035       0  5362.2    0.07       0
Bank Sta=5028.5,5033.6
Exp/Cntr=0.3,0.1

Type RM Length L Ch R = 1,4587,466,466,466
BEGIN DESCRIPTION:
Buffalo Creek Trib 05 8.0
END DESCRIPTION:
XS GIS Cut Line= 3
      1313204.96      6934987.97      1312555.00      6934538.00
      1312337.93      6934045.65
#Sta/Elev= 30
  4214.5 2192.51  4299.6 2190.37  4394.9 2186.22  4507.7 2183.64  4523.2 2182.70
  4666.5 2178.79  4955.7 2174.89  4968.5 2173.12  4976.6 2173.22  4982.7 2170.39
  4989.0 2169.15  4989.4 2168.65  4994.1 2169.15  4997.6 2172.67  5002.0 2174.58
  5006.1 2174.58  5007.8 2174.58  5014.0 2177.11  5019.4 2177.00  5026.9 2178.08
  5048.7 2177.32  5094.9 2178.13  5147.1 2180.10  5201.7 2180.55  5211.5 2180.97
  5216.9 2182.08  5234.5 2181.31  5278.2 2181.99  5413.8 2185.89  5543.1 2187.97
#Mann=6,-1,0
  4214.5    0.07       0  4507.7   0.035       0  4989.0   0.035       0
  4994.1   0.035       0  5006.1    0.07       0  5413.8   0.035       0
Bank Sta=4989,4994.1
Exp/Cntr=0.3,0.1

Type RM Length L Ch R = 1,4121,890,890,890
BEGIN DESCRIPTION:
Buffalo Creek Trib 05 7.0
END DESCRIPTION:
XS GIS Cut Line= 3
      1313267.60      6934931.03      1312955.00      6934388.00
      1312583.65      6933921.80
#Sta/Elev= 30
  4368.1 2191.76  4439.3 2191.12  4600.2 2186.67  4637.0 2184.59  4675.2 2180.68
  4775.4 2172.41  4782.7 2169.67  4807.5 2166.49  4807.9 2165.99  4812.7 2166.49
  4820.1 2171.13  4833.1 2173.82  4841.6 2172.50  4847.4 2173.18  4856.2 2170.92
  4869.0 2173.86  4893.8 2173.74  4927.9 2174.38  4965.2 2172.57  4986.8 2169.86
  4991.8 2167.27  4997.9 2167.27  5001.9 2170.56  5008.3 2170.27  5013.9 2171.96
  5022.7 2174.42  5045.1 2176.06  5237.3 2178.39  5485.5 2186.18  5590.7 2186.65
#Mann=6,-1,0
  4368.1    0.07       0  4675.2   0.035       0  4807.5    0.07       0
  4812.7   0.035       0  4893.8    0.07       0  5013.9   0.035       0
Bank Sta=4807.5,4812.7
Exp/Cntr=0.3,0.1

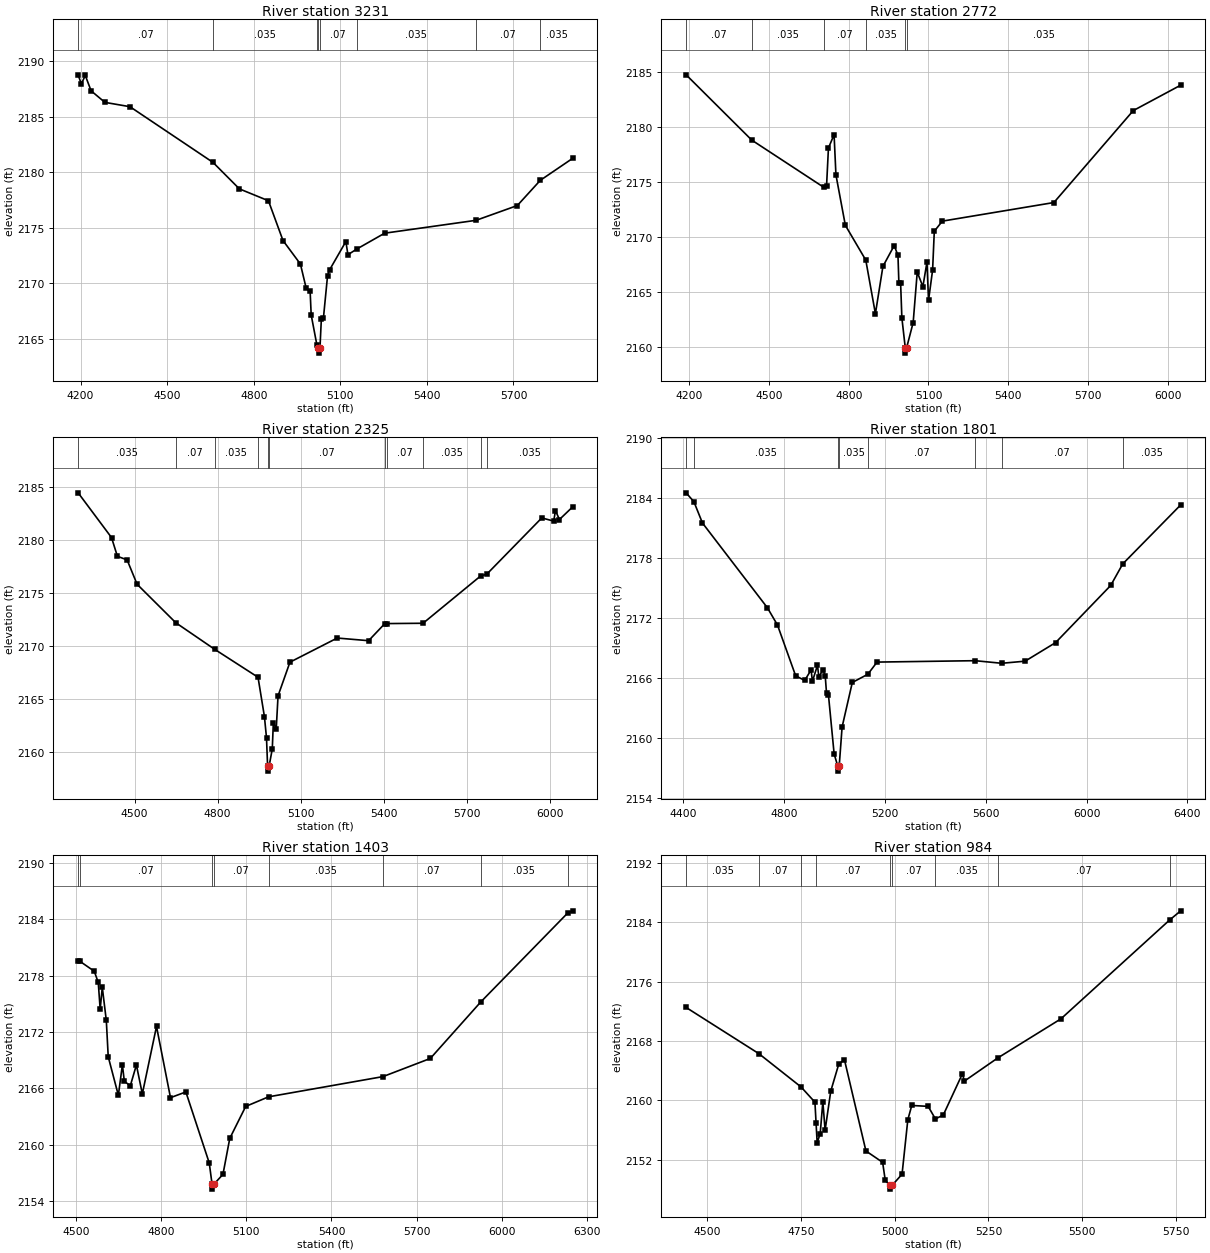
Type RM Length L Ch R = 1,3231,459,459,459
BEGIN DESCRIPTION:
Buffalo Creek Trib 05 6.0
END DESCRIPTION:
XS GIS Cut Line= 3
      1313551.46      6935032.62      1313455.00      6934238.00
      1312817.06      6933584.66
#Sta/Elev= 30
  4191.6 2188.76  4202.5 2187.94  4216.4 2188.70  4236.5 2187.32  4284.3 2186.28
  4371.1 2185.89  4659.1 2180.87  4750.3 2178.49  4851.0 2177.42  4901.4 2173.84
  4961.8 2171.72  4982.0 2169.52  4995.5 2169.25  4999.1 2167.14  5018.7 2164.46
  5024.3 2164.20  5024.8 2163.70  5029.6 2164.20  5034.4 2166.81  5041.6 2166.88
  5055.7 2170.64  5062.7 2171.19  5119.3 2173.75  5126.4 2172.56  5156.3 2173.06
  5253.7 2174.50  5570.5 2175.66  5713.4 2176.99  5793.0 2179.26  5905.2 2181.24
#Mann=8,-1,0
  4191.6    0.07       0  4659.1   0.035       0  5018.7    0.07       0
  5024.3   0.035       0  5029.6    0.07       0  5156.3   0.035       0
  5570.5    0.07       0  5793.0   0.035       0
Bank Sta=5024.3,5029.6
Exp/Cntr=0.3,0.1

Type RM Length L Ch R = 1,2772,447,447,447
BEGIN DESCRIPTION:
Buffalo Creek Trib 05 5.0
END DESCRIPTION:
XS GIS Cut Line= 3
      1314373.08      6934757.02      1313805.00      6934188.00
      1313245.53      6933291.50
#Sta/Elev= 30
  4188.2 2184.73  4435.1 2178.80  4706.2 2174.51  4716.5 2174.63  4723.6 2178.08
  4744.8 2179.30  4751.8 2175.64  4787.2 2171.06  4864.1 2167.90  4900.3 2163.03
  4928.6 2167.33  4971.0 2169.22  4985.2 2168.33  4988.7 2165.78  4995.2 2165.78
  4999.9 2162.65  5012.6 2159.95  5013.0 2159.45  5017.9 2159.95  5042.4 2162.23
  5057.7 2166.81  5079.0 2165.49  5094.3 2167.72  5100.2 2164.24  5115.5 2166.99
  5121.9 2170.52  5152.1 2171.44  5572.0 2173.13  5870.5 2181.48  6049.0 2183.79
#Mann=6,-1,0
  4188.2    0.07       0  4435.1   0.035       0  4706.2    0.07       0
  4864.1   0.035       0  5012.6   0.035       0  5017.9   0.035       0
Bank Sta=5012.6,5017.9
Exp/Cntr=0.3,0.1

Type RM Length L Ch R = 1,2325,524,524,524
BEGIN DESCRIPTION:
Buffalo Creek Trib 05 4.0
END DESCRIPTION:
XS GIS Cut Line= 3
      1314624.79      6934518.28      1314155.00      6933988.00
      1313322.69      6933302.99
#Sta/Elev= 30
  4296.4 2184.42  4417.0 2180.21  4438.2 2178.45  4473.3 2178.11  4509.3 2175.82
  4649.1 2172.20  4790.1 2169.69  4946.2 2167.07  4969.3 2163.37  4976.8 2161.37
  4980.7 2158.74  4981.1 2158.24  4986.4 2158.74  4997.7 2160.33  5001.5 2162.79
  5012.0 2162.23  5018.5 2165.32  5061.5 2168.49  5232.3 2170.76  5345.6 2170.51
  5404.3 2172.12  5413.5 2172.12  5542.3 2172.15  5750.8 2176.61  5771.9 2176.75
  5971.2 2182.06  6014.2 2181.76  6020.7 2182.74  6035.0 2181.91  6082.8 2183.10
#Mann=11,-1,0
  4296.4   0.035       0  4649.1    0.07       0  4790.1   0.035       0
  4946.2    0.07       0  4980.7    0.07       0  4986.4    0.07       0
  5404.3   0.035       0  5413.5    0.07       0  5542.3   0.035       0
  5750.8    0.07       0  5771.9   0.035       0
Bank Sta=4980.7,4986.4
Exp/Cntr=0.3,0.1

Type RM Length L Ch R = 1,1801,398,398,398
BEGIN DESCRIPTION:
Buffalo Creek Trib 05 3.5
END DESCRIPTION:
XS GIS Cut Line= 3
      1314838.69      6934408.72      1314638.03      6933853.95
      1313388.42      6933288.09
#Sta/Elev= 30
  4411.4 2184.55  4442.3 2183.65  4476.0 2181.53  4733.7 2173.04  4773.7 2171.31
  4845.7 2166.23  4881.7 2165.76  4907.0 2166.82  4912.3 2165.67  4932.3 2167.28
  4937.6 2166.15  4954.5 2166.80  4963.0 2166.24  4968.3 2164.46  4975.8 2164.32
  4998.4 2158.40  5012.8 2157.18  5013.2 2156.68  5018.5 2157.18  5030.0 2161.10
  5070.5 2165.56  5132.1 2166.38  5168.6 2167.60  5557.5 2167.74  5663.1 2167.48
  5755.9 2167.69  5876.9 2169.55  6095.7 2175.28  6143.2 2177.43  6373.1 2183.34
#Mann=8,-1,0
  4411.4    0.07       0  4442.3   0.035       0  5012.8   0.035       0
  5018.5   0.035       0  5132.1    0.07       0  5557.5   0.035       0
  5663.1    0.07       0  6143.2   0.035       0
Bank Sta=5012.8,5018.5
Exp/Cntr=0.3,0.1

Type RM Length L Ch R = 1,1403,419,419,419
BEGIN DESCRIPTION:
Buffalo Creek Trib 05 3.0
END DESCRIPTION:
XS GIS Cut Line= 5
      1314930.03      6933763.03      1314691.98      6933503.76
      1314555.00      6933538.00      1314409.75      6933576.73
      1313371.32      6933213.29
#Sta/Elev= 30
  4506.8 2179.59  4512.8 2179.52  4563.6 2178.46  4577.7 2177.27  4584.5 2174.42
  4591.9 2176.75  4606.1 2173.23  4612.9 2169.37  4648.6 2165.27  4662.8 2168.51
  4669.6 2166.78  4690.6 2166.27  4712.2 2168.50  4733.1 2165.42  4783.1 2172.59
  4832.4 2165.02  4886.6 2165.63  4969.1 2158.08  4979.1 2155.80  4979.5 2155.30
  4984.8 2155.80  5017.4 2156.87  5041.4 2160.69  5097.6 2164.09  5178.1 2165.11
  5581.7 2167.26  5748.6 2169.19  5926.3 2175.19  6232.4 2184.63  6250.5 2184.88
#Mann=8,-1,0
  4506.8   0.035       0  4512.8    0.07       0  4979.1    0.07       0
  4984.8    0.07       0  5178.1   0.035       0  5581.7    0.07       0
  5926.3   0.035       0  6232.4    0.07       0
Bank Sta=4979.1,4984.8
Exp/Cntr=0.3,0.1

Type RM Length L Ch R = 1,984,443,443,443
BEGIN DESCRIPTION:
Buffalo Creek Trib 05 2.0
END DESCRIPTION:
XS GIS Cut Line= 3
      1314825.39      6933491.11      1314355.00      6933188.00
      1313631.81      6932957.24
#Sta/Elev= 30
  4444.0 2172.53  4637.9 2166.31  4750.5 2161.82  4787.4 2159.77  4790.4 2157.00
  4793.3 2154.33  4801.4 2155.51  4808.5 2159.84  4814.5 2155.99  4829.6 2161.26
  4850.8 2164.88  4866.0 2165.51  4923.4 2153.20  4967.9 2151.67  4974.9 2149.25
  4987.2 2148.56  4987.6 2148.06  4993.0 2148.56  5019.7 2150.07  5035.1 2157.41
  5045.6 2159.33  5089.3 2159.21  5108.6 2157.52  5129.6 2158.04  5180.7 2163.60
  5185.9 2162.61  5275.2 2165.74  5443.4 2171.00  5733.1 2184.31  5762.7 2185.55
#Mann=9,-1,0
  4444.0   0.035       0  4637.9    0.07       0  4750.5   0.035       0
  4790.4    0.07       0  4987.2    0.07       0  4993.0    0.07       0
  5108.6   0.035       0  5275.2    0.07       0  5733.1   0.035       0
Bank Sta=4987.2,4993
Exp/Cntr=0.3,0.1

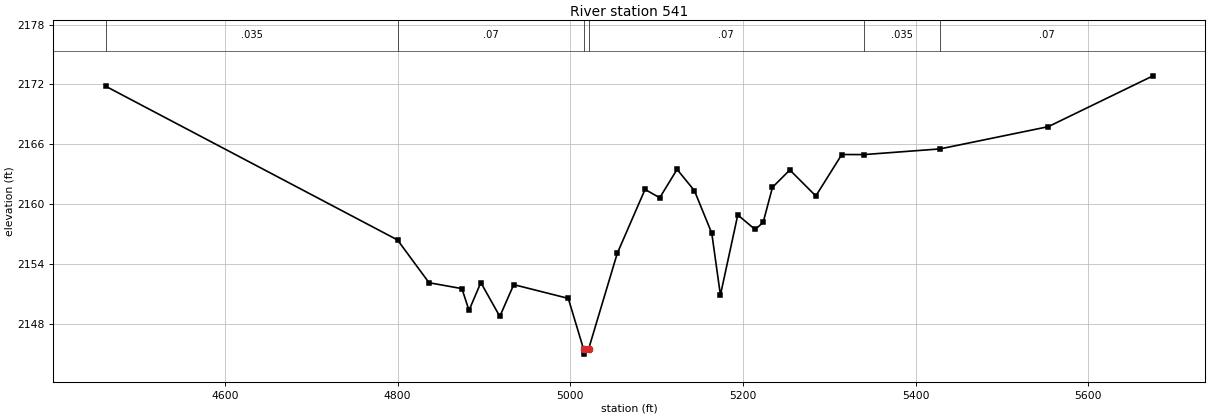
Type RM Length L Ch R = 1,541,0,0,0
BEGIN DESCRIPTION:
Buffalo Creek Trib 05 1.0
END DESCRIPTION:
XS GIS Cut Line= 4
      1314873.75      6933474.18      1314655.00      6932988.00
      1314678.12      6932895.52      1314096.00      6932842.21
#Sta/Elev= 30
  4461.9 2171.81  4799.8 2156.40  4836.3 2152.11  4874.4 2151.52  4882.6 2149.34
  4896.3 2152.12  4918.3 2148.73  4934.4 2151.92  4997.6 2150.54  5015.3 2145.45
  5015.8 2144.95  5021.1 2145.45  5054.3 2155.05  5086.5 2161.47  5103.5 2160.63
  5123.6 2163.48  5143.7 2161.34  5163.8 2157.07  5173.8 2150.87  5193.9 2158.91
  5214.0 2157.45  5223.3 2158.16  5234.1 2161.68  5254.2 2163.42  5284.3 2160.81
  5314.4 2164.97  5340.0 2164.96  5428.1 2165.53  5553.5 2167.76  5674.9 2172.86
#Mann=6,-1,0
  4461.9   0.035       0  4799.8    0.07       0  5015.3    0.07       0
  5021.1    0.07       0  5340.0   0.035       0  5428.1    0.07       0
Bank Sta=5015.3,5021.1
Exp/Cntr=0.3,0.1

Chan Stop Cuts=-1