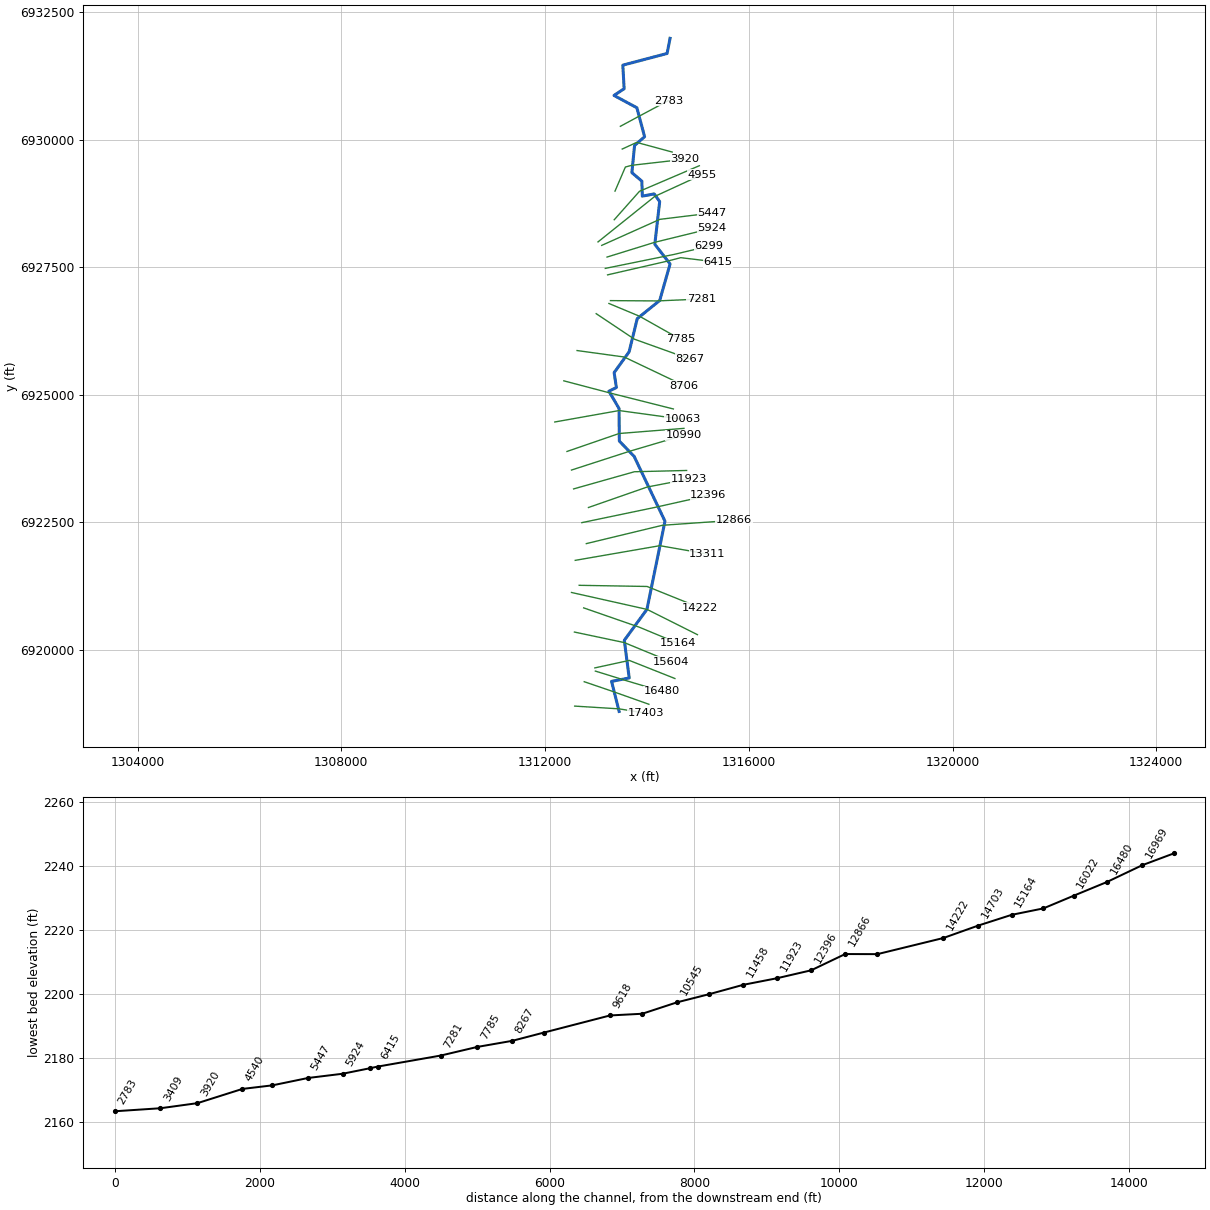
--- Buffalo Creek Trib 06.prj (project) ---

Proj Title=Buffalo Creek Trib 06 Base Level Engineering
Current Plan=p01
Default Exp/Contr=0.3,0.1
English Units
Geom File=g01
Flow File=f01
Plan File=p01
Y Axis Title=Elevation
X Axis Title(PF)=Main Channel Distance
X Axis Title(XS)=Station
BEGIN DESCRIPTION:
Buffalo Creek Trib 06
END DESCRIPTION:
DSS Export Rating Curves= 0
DSS Export Rating Curve Sorted= 0
DSS Export Volume Flow Curves= 0
DXF OffsetX= 0
DXF OffsetY= 0
DXF ScaleX= 1
DXF ScaleY= 10

--- Buffalo Creek Trib 06.p01 (plan) ---

Plan Title=Multiple Run
Short Identifier=Multiple
Geom File=g01
Flow File=f01
Subcritical Flow
K Sum by GR= 0
Std Step Tol= 0.01
Critical Tol= 0.01
Num of Std Step Trials= 20
Max Error Tol= 0.3
Flow Tol Ratio= 0.001
Split Flow NTrial= 30
Split Flow Tol= 0.02
Split Flow Ratio= 0.02
Log Output Level= 0
Friction Slope Method= 1
Unsteady Friction Slope Method= 2
Unsteady Bridges Friction Slope Method= 1
Parabolic Critical Depth
Global Vel Dist=  1 , 1 , 1
Global Log Level= 0
CheckData=True
Encroach Param= -1, 0, 0, 0
BEGIN DESCRIPTION:
Multiple Run
END DESCRIPTION:

--- Buffalo Creek Trib 06.f01 (steady flow) ---

Flow Title=Multiple
Number of Profiles=7
Profile Names=10-year,25-year,50-year,1pct_min,100-year,1pct_plu,500-year
River Rch & RM= Buffalo Creek Tr,Reach-1,17403
     431     628     800     506    1009    2013    1628
River Rch & RM= Buffalo Creek Tr,Reach-1,10990
     546     804    1028     653    1303    2599    2121
River Rch & RM= Buffalo Creek Tr,Reach-1,3920
     582     858    1098     698    1392    2777    2267
Boundary for River Rch & Prof#=Buffalo Creek Tr,Reach-1,1
Up Type=0
Dn Type=3
Dn Slope=0.005
Boundary for River Rch & Prof#=Buffalo Creek Tr,Reach-1,2
Up Type=0
Dn Type=3
Dn Slope=0.005
Boundary for River Rch & Prof#=Buffalo Creek Tr,Reach-1,3
Up Type=0
Dn Type=3
Dn Slope=0.005
Boundary for River Rch & Prof#=Buffalo Creek Tr,Reach-1,4
Up Type=0
Dn Type=3
Dn Slope=0.005
Boundary for River Rch & Prof#=Buffalo Creek Tr,Reach-1,5
Up Type=0
Dn Type=3
Dn Slope=0.005
Boundary for River Rch & Prof#=Buffalo Creek Tr,Reach-1,6
Up Type=0
Dn Type=3
Dn Slope=0.005
Boundary for River Rch & Prof#=Buffalo Creek Tr,Reach-1,7
Up Type=0
Dn Type=3
Dn Slope=0.005

--- Buffalo Creek Trib 06.g01 (geometry) ---

Geom Title=Existing Conditions
Program Version=4.10

River Reach=Buffalo Creek Tr,Reach-1
Reach XY= 30
        1313455.        6918788.      1313306.48      6919376.52
      1313653.12      6919443.68      1313557.05      6920182.14
      1314001.19      6920789.56      1314355.39      6922517.87
      1313749.19      6923790.29      1313458.74      6924089.52
      1313453.97      6924727.57      1313254.79      6925067.96
      1313401.56      6925139.22      1313356.94      6925432.02
      1313651.45      6925839.48      1313810.46      6926490.45
      1314251.84      6926846.34      1314455.49      6927563.04
      1314155.54      6927948.47      1314251.45      6928786.53
      1314142.99      6928936.83      1313910.38      6928893.17
      1313901.47      6929186.53      1313705.66      6929353.84
      1313758.46       6929886.5      1313955.31      6930058.34
       1313803.5      6930626.47      1313354.52      6930867.84
      1313553.51      6930999.54      1313527.66      6931462.02
      1314396.99      6931691.03        1314455.        6931988.

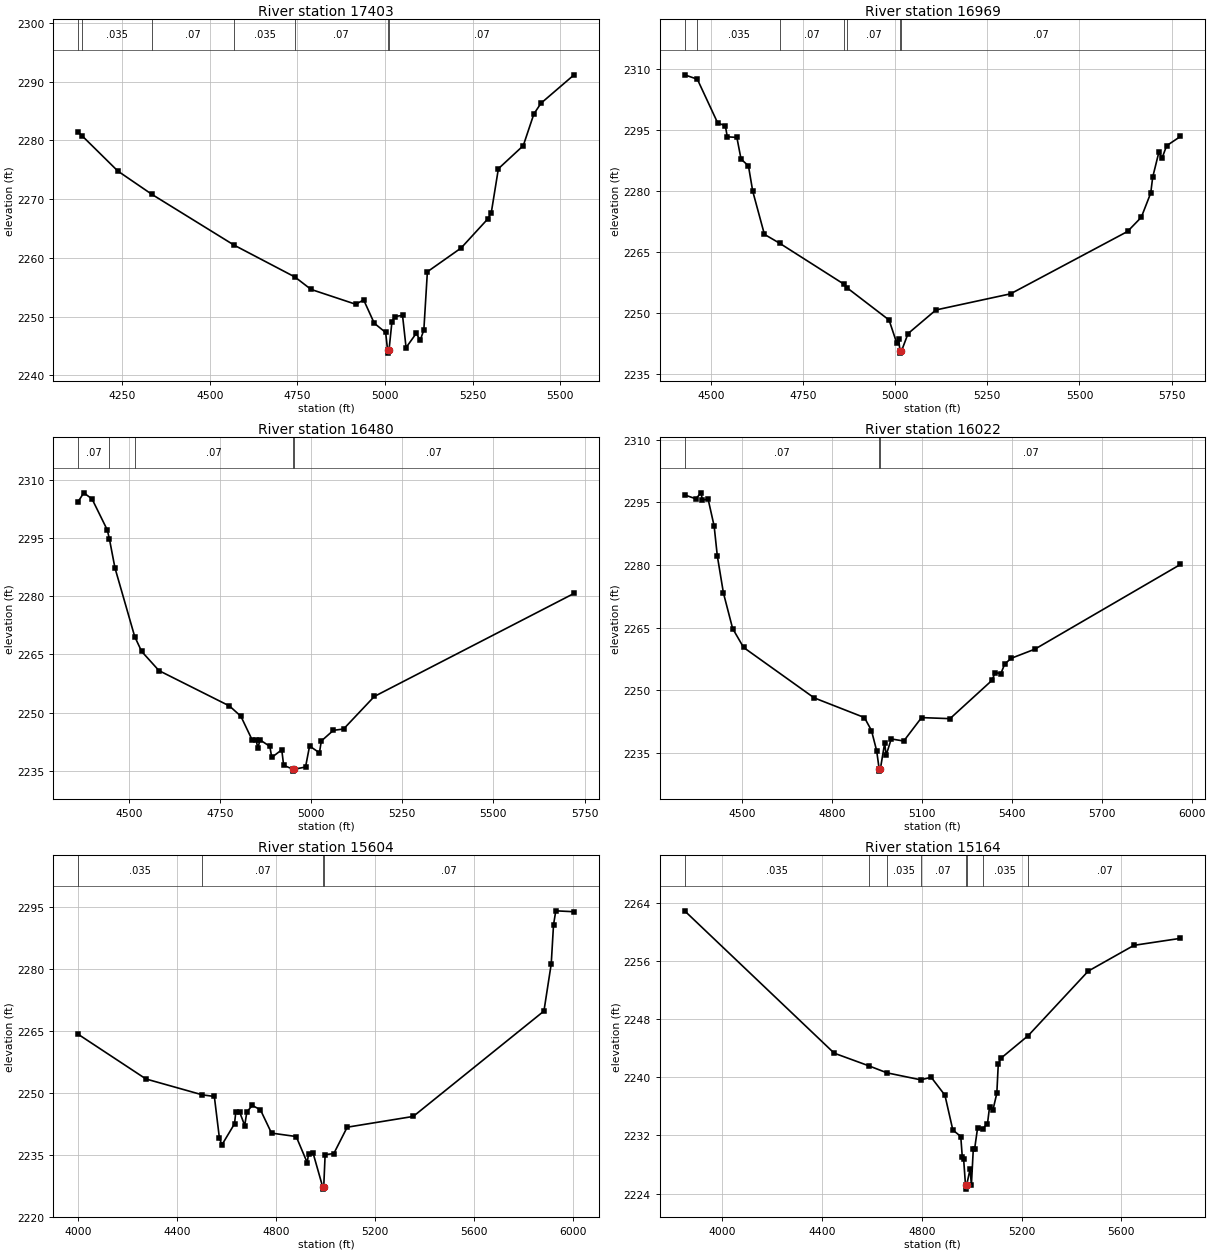
Type RM Length L Ch R = 1 ,17403   ,434,434,434
BEGIN DESCRIPTION:
Buffalo Creek Trib 06 27.0
END DESCRIPTION:
XS GIS Cut Line= 3
      1312581.94      6918891.81        1313455.        6918838.
      1313988.16      6918751.19
#Sta/Elev= 30
  4124.6 2281.39  4136.6 2280.71  4237.9 2274.76  4335.3 2270.79  4569.4 2262.17
  4742.7 2256.76  4788.9 2254.64  4916.1 2252.12  4939.2 2252.84  4969.3 2248.89
  5001.8 2247.31  5007.4  2244.3  5007.7  2243.8  5011.4  2244.3  5019.6 2249.04
  5027.5 2250.02    5050 2250.22  5060.1 2244.74    5089 2247.15  5100.6    2246
  5110.8 2247.74  5120.9 2257.64  5217.1 2261.68  5293.1 2266.62  5303.3 2267.72
  5323.5 2275.17  5394.5 2279.09  5424.8 2284.49  5445.1 2286.31  5539.5 2291.14
#Mann= 7 ,-1 , 0
  4124.6     .07       0  4136.6    .035       0  4335.3     .07       0
  4569.4    .035       0  4742.7     .07       0  5007.4     .07       0
  5011.4     .07       0
Bank Sta=5007.4,5011.4
XS Rating Curve= 0 ,0
Exp/Cntr=0.3,0.1

Type RM Length L Ch R = 1 ,16969   ,489,489,489
BEGIN DESCRIPTION:
Buffalo Creek Trib 06 26.0
END DESCRIPTION:
XS GIS Cut Line= 3
      1312770.05      6919370.19        1313305.        6919188.
      1314040.45      6918927.64
#Sta/Elev= 30
  4428.7 2308.47  4463.2  2307.4  4518.4 2296.66  4539.2 2295.95  4544.5 2293.25
  4570.5  2293.1  4581.8 2287.78  4601.9 2286.11  4613.5 2279.89  4645.2  2269.3
  4686.4 2267.12  4859.8 2257.13  4868.5 2256.23  4983.4 2248.26    5004 2242.66
  5009.3 2243.67    5013 2240.63  5013.3 2240.13    5017 2240.63  5034.9 2244.93
  5110.5 2250.73  5312.9 2254.69  5630.3    2270  5667.7 2273.49  5693.3 2279.45
  5698.6 2283.33  5715.2 2289.42  5724.2 2288.06  5736.4 2291.06    5774 2293.34
#Mann= 7 ,-1 , 0
  4428.7     .07       0  4463.2    .035       0  4686.4     .07       0
  4859.8    .035       0  4868.5     .07       0    5013     .07       0
    5017     .07       0
Bank Sta=5013,5017
XS Rating Curve= 0 ,0
Exp/Cntr=0.3,0.1

Type RM Length L Ch R = 1 ,16480   ,458,458,458
BEGIN DESCRIPTION:
Buffalo Creek Trib 06 25.0
END DESCRIPTION:
XS GIS Cut Line= 3
      1312988.82      6919578.52        1313605.        6919388.
      1314289.91      6919182.98
#Sta/Elev= 30
  4361.4 2304.48  4376.6 2306.74  4399.3 2305.16  4441.1 2297.16  4447.2 2294.71
  4462.1 2287.38  4516.3 2269.62  4535.3 2265.79  4582.8 2260.83  4776.1  2251.7
  4807.5 2249.04  4838.9 2242.83  4849.1 2242.87  4854.3  2240.8  4859.8 2242.94
  4886.9 2241.27  4892.2  2238.4  4919.6 2240.38  4924.8 2236.38  4950.2 2235.37
  4950.4 2234.87  4954.2 2235.37  4984.8 2235.93  4995.9 2241.35  5022.9 2239.61
  5028.1 2242.65  5061.2 2245.41  5089.1 2245.74  5173.4 2254.15  5721.3 2280.77
#Mann= 5 ,-1 , 0
  4361.4     .07       0  4447.2    .035       0  4516.3     .07       0
  4950.2     .07       0  4954.2     .07       0
Bank Sta=4950.2,4954.2
XS Rating Curve= 0 ,0
Exp/Cntr=0.3,0.1

Type RM Length L Ch R = 1 ,16022   ,418,418,418
BEGIN DESCRIPTION:
Buffalo Creek Trib 06 24.0
END DESCRIPTION:
XS GIS Cut Line= 3
      1312978.38      6919641.03        1313655.        6919788.
      1314550.22      6919433.12
#Sta/Elev= 30
  4307.5 2296.76    4345 2295.83  4362.1 2297.26  4367.2 2295.52  4385.9 2295.77
  4406.1  2289.3  4416.6 2282.19  4437.1 2273.26  4467.8 2264.76  4504.4 2260.22
  4739.9 2248.15  4907.8 2243.43  4931.3 2240.33  4948.7 2235.46    4957  2231.1
  4957.2  2230.6    4961  2231.1  4975.3 2237.29  4980.4 2234.43  4997.3 2238.31
  5039.1 2237.81  5098.5 2243.42  5193.5 2243.17  5333.4 2252.33  5344.3  2254.2
  5363.2 2253.95  5376.4  2256.3  5398.3 2257.64  5476.7 2259.81  5962.9 2280.11
#Mann= 3 ,-1 , 0
  4307.5     .07       0    4957     .07       0    4961     .07       0
Bank Sta=4957,4961
XS Rating Curve= 0 ,0
Exp/Cntr=0.3,0.1

Type RM Length L Ch R = 1 ,15604   ,440,440,440
BEGIN DESCRIPTION:
Buffalo Creek Trib 06 23.0
END DESCRIPTION:
XS GIS Cut Line= 3
      1312577.38      6920344.15        1313555.        6920138.
      1314481.77      6919756.36
#Sta/Elev= 30
  4001.4 2264.17  4274.9 2253.34  4502.8 2249.49  4550.8  2249.1  4571.3    2239
  4581.5 2237.38  4632.3 2242.48  4637.4 2245.31    4653 2245.31  4673.5 2242.04
    4682 2245.36  4704.1 2246.93  4736.9 2245.86  4781.6 2240.22  4881.2 2239.39
  4925.8 2233.05    4931 2235.25  4949.4 2235.37  4988.3 2227.14  4988.6 2226.64
  4992.3 2227.14    4998 2234.99    5033 2235.26    5087 2241.65  5353.5 2244.26
  5881.1  2269.8  5910.5 2281.21  5919.8 2290.71    5929  2294.1  6002.8 2293.88
#Mann= 4 ,-1 , 0
  4001.4    .035       0  4502.8     .07       0  4988.3     .07       0
  4992.3     .07       0
Bank Sta=4988.3,4992.3
XS Rating Curve= 0 ,0
Exp/Cntr=0.3,0.1

Type RM Length L Ch R = 1 ,15164   ,461,461,461
BEGIN DESCRIPTION:
Buffalo Creek Trib 06 22.0
END DESCRIPTION:
XS GIS Cut Line= 3
      1312759.66       6920818.1        1313855.        6920438.
      1314619.02      6920120.19
#Sta/Elev= 30
    3850 2262.86  4449.4  2243.3  4589.1 2241.55  4660.7  2240.6    4796 2239.64
  4838.2 2239.98    4893 2237.53  4924.7 2232.75  4956.5 2231.85  4962.7    2229
    4968 2228.76  4975.6 2225.12  4975.8 2224.62  4979.8 2225.12  4993.9 2227.38
  4999.1 2225.19  5006.8 2230.16  5012.1 2230.16    5024 2233.05    5044 2232.92
  5063.6 2233.62  5071.7 2235.85  5085.2 2235.46    5101 2237.79  5106.9 2241.85
  5117.7 2242.61    5227 2245.72  5467.4 2254.58  5650.6 2258.12  5836.9 2259.08
#Mann= 8 ,-1 , 0
    3850    .035       0  4589.1     .07       0  4660.7    .035       0
    4796     .07       0  4975.6     .07       0  4979.8     .07       0
    5044    .035       0    5227     .07       0
Bank Sta=4975.6,4979.8
XS Rating Curve= 0 ,0
Exp/Cntr=0.3,0.1

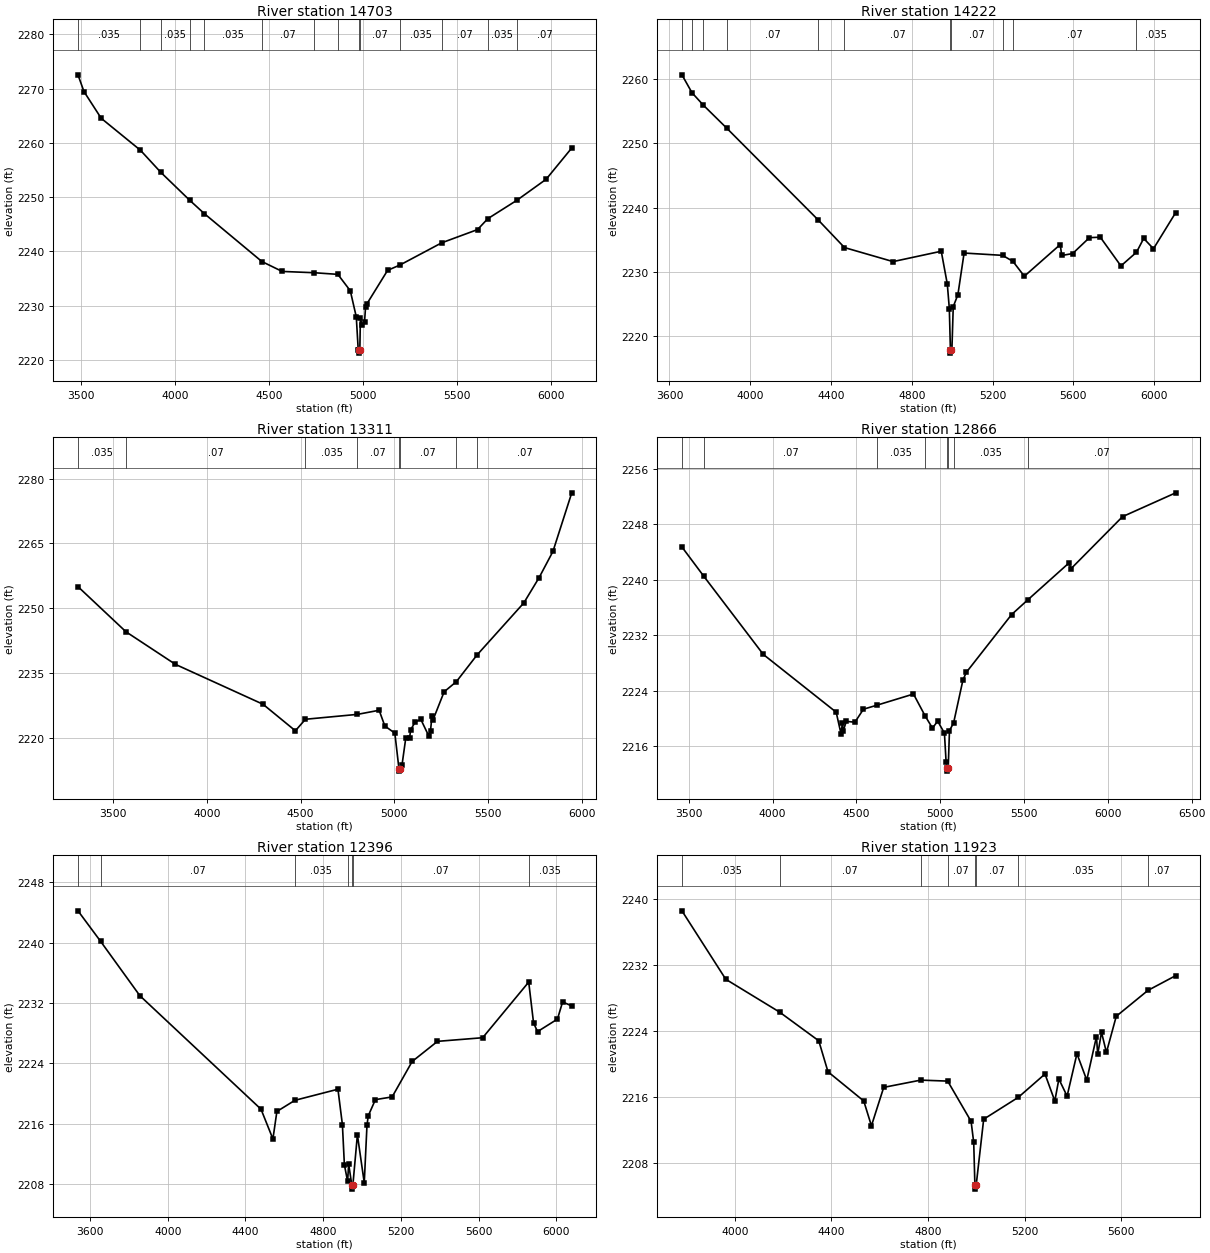
Type RM Length L Ch R = 1 ,14703   ,481,481,481
BEGIN DESCRIPTION:
Buffalo Creek Trib 06 21.0
END DESCRIPTION:
XS GIS Cut Line= 3
      1312520.07      6921120.19        1314005.        6920788.
       1314993.1      6920292.52
#Sta/Elev= 30
  3482.6 2272.54  3514.4 2269.46  3606.3 2264.53  3815.1 2258.64  3922.9 2254.59
  4076.8 2249.44  4154.1 2246.99  4460.7 2238.15  4568.9 2236.32  4740.5 2236.08
  4865.2 2235.78  4931.4 2232.76  4963.2 2227.96  4973.5 2221.93  4977.8 2221.77
  4978.1 2221.27  4982.1 2221.77  4985.1 2227.76    4994 2226.36    5007 2226.97
  5012.6 2229.75  5018.2 2230.26  5129.9 2236.52    5196 2237.51  5417.6 2241.59
  5608.3 2244.03  5663.1 2246.04  5817.8 2249.43  5973.3  2253.3  6109.6 2259.06
#Mann= 14 ,-1 , 0
  3482.6    .035       0  3815.1     .07       0  3922.9    .035       0
  4076.8     .07       0  4154.1    .035       0  4460.7     .07       0
  4740.5    .035       0  4865.2     .07       0  4977.8     .07       0
  4982.1     .07       0    5196    .035       0  5417.6     .07       0
  5663.1    .035       0  5817.8     .07       0
Bank Sta=4977.8,4982.1
XS Rating Curve= 0 ,0
Exp/Cntr=0.3,0.1

Type RM Length L Ch R = 1 ,14222   ,911,911,911
BEGIN DESCRIPTION:
Buffalo Creek Trib 06 20.0
END DESCRIPTION:
XS GIS Cut Line= 3
      1312671.08      6921260.82        1314005.        6921238.
      1315035.69      6920823.31
#Sta/Elev= 30
  3661.8  2260.6  3711.6 2257.82  3767.2 2255.91  3883.3 2252.33  4337.7 2238.03
  4466.7 2233.78  4707.3  2231.6  4945.9 2233.21  4975.9 2228.11  4985.9  2224.3
  4991.3 2217.89  4991.6 2217.39  4995.6 2217.89  4998.6 2217.89  5005.3 2224.61
  5028.3 2226.46    5059 2232.93  5249.3 2232.57  5300.8 2231.64  5357.3 2229.33
  5534.9 2234.24  5542.7 2232.55  5596.4 2232.85  5679.7 2235.32  5733.5 2235.39
  5835.6 2230.93  5912.6 2233.05  5948.4  2235.2  5996.8  2233.6  6106.9 2239.21
#Mann= 11 ,-1 , 0
  3661.8    .035       0  3711.6     .07       0  3767.2    .035       0
  3883.3     .07       0  4337.7    .035       0  4466.7     .07       0
  4991.3     .07       0  4995.6     .07       0  5249.3    .035       0
  5300.8     .07       0  5912.6    .035       0
Bank Sta=4991.3,4995.6
XS Rating Curve= 0 ,0
Exp/Cntr=0.3,0.1

Type RM Length L Ch R = 1 ,13311   ,445,445,445
BEGIN DESCRIPTION:
Buffalo Creek Trib 06 19.0
END DESCRIPTION:
XS GIS Cut Line= 3
      1312592.95       6921750.4        1314255.        6922038.
      1315186.67      6921875.41
#Sta/Elev= 30
  3312.9    2255    3569 2244.56  3832.6 2237.03  4299.4 2227.81  4471.9 2221.68
  4525.6 2224.34  4802.8 2225.47  4918.5 2226.42  4948.9 2222.78  5002.2 2221.13
  5024.3 2212.85  5024.7 2212.35  5029.4 2212.85  5040.3 2213.71  5060.6 2220.03
  5080.9    2220  5086.4 2221.91  5111.3 2223.73  5140.9  2224.3  5182.4 2220.54
  5192.5 2221.73  5200.4 2225.21  5205.5 2224.17    5265 2230.69  5330.3 2233.04
  5440.9 2239.23  5689.9 2251.24  5771.1 2257.07  5845.2 2263.15  5945.4 2276.69
#Mann= 8 ,-1 , 0
  3312.9    .035       0    3569     .07       0  4525.6    .035       0
  4802.8     .07       0  5024.3     .07       0  5029.4     .07       0
  5330.3    .035       0  5440.9     .07       0
Bank Sta=5024.3,5029.4
XS Rating Curve= 0 ,0
Exp/Cntr=0.3,0.1

Type RM Length L Ch R = 1 ,12866   ,470,470,470
BEGIN DESCRIPTION:
Buffalo Creek Trib 06 18.0
END DESCRIPTION:
XS GIS Cut Line= 3
      1312811.72      6922078.54        1314305.        6922438.
       1315711.4      6922536.77
#Sta/Elev= 30
  3459.2 2244.74  3590.7 2240.48  3944.6 2229.23  4379.4 2220.89  4408.9 2217.69
  4416.1 2219.33  4421.3 2218.15  4439.7 2219.57  4491.1 2219.44    4542 2221.32
  4621.3 2221.89  4840.6 2223.51  4911.2  2220.3    4954 2218.59  4984.8  2219.6
  5025.2 2217.87  5035.2 2213.68  5042.7 2212.88  5043.1 2212.38  5047.9 2212.88
  5055.3 2218.23  5079.9 2219.34  5135.5 2225.52  5155.5 2226.63  5426.2 2234.99
  5524.5 2237.15    5767 2242.41  5781.1 2241.62  6087.8 2249.12    6405 2252.56
#Mann= 8 ,-1 , 0
  3459.2    .035       0  3590.7     .07       0  4621.3    .035       0
  4911.2     .07       0  5042.7     .07       0  5047.9     .07       0
  5079.9    .035       0  5524.5     .07       0
Bank Sta=5042.7,5047.9
XS Rating Curve= 0 ,0
Exp/Cntr=0.3,0.1

Type RM Length L Ch R = 1 ,12396   ,473,473,473
BEGIN DESCRIPTION:
Buffalo Creek Trib 06 17.0
END DESCRIPTION:
XS GIS Cut Line= 3
      1312723.13      6922489.98        1314155.        6922788.
      1315206.81      6923023.04
#Sta/Elev= 30
  3538.2 2244.21  3654.4 2240.17  3856.7 2232.95  4479.8  2217.9  4541.1 2213.95
  4561.5  2217.6  4654.3 2219.08  4875.6 2220.55  4898.6 2215.85  4908.8 2210.52
  4925.4 2208.32  4930.7 2210.64  4947.1  2207.8  4947.5  2207.3  4952.3  2207.8
  4975.7 2214.51    5011 2208.14    5025 2215.76  5031.5 2217.02  5068.4 2219.17
  5154.4 2219.53  5257.5 2224.23  5387.8  2226.9  5620.2 2227.38  5857.1 2234.76
    5882 2229.34  5902.5 2228.19  6004.9 2229.85  6031.5 2232.13  6078.5 2231.59
#Mann= 7 ,-1 , 0
  3538.2    .035       0  3654.4     .07       0  4654.3    .035       0
  4925.4     .07       0  4947.1     .07       0  4952.3     .07       0
  5857.1    .035       0
Bank Sta=4947.1,4952.3
XS Rating Curve= 0 ,0
Exp/Cntr=0.3,0.1

Type RM Length L Ch R = 1 ,11923   ,465,465,465
BEGIN DESCRIPTION:
Buffalo Creek Trib 06 16.0
END DESCRIPTION:
XS GIS Cut Line= 3
       1312853.4      6922786.88        1314005.        6923188.
      1314816.96      6923344.17
#Sta/Elev= 30
  3780.2 2238.57  3961.9 2230.27  4184.8 2226.29  4347.2 2222.81  4385.5 2219.05
  4533.7 2215.51  4565.5  2212.5  4616.4 2217.16  4769.7 2218.04  4881.5 2217.92
  4978.5 2213.04  4989.4 2210.48  4994.3 2205.32  4994.7 2204.82  4999.7 2205.32
  5030.7  2213.3  5174.5 2215.96  5284.8 2218.78  5325.5 2215.51  5342.3 2218.17
  5376.4  2216.1  5417.2 2221.24  5457.9 2218.04  5498.1 2223.31  5503.2 2221.15
    5519 2223.84  5539.4  2221.4  5580.1 2225.78  5711.4 2228.92  5826.5 2230.71
#Mann= 8 ,-1 , 0
  3780.2    .035       0  4184.8     .07       0  4769.7    .035       0
  4881.5     .07       0  4994.3     .07       0  4999.7     .07       0
  5174.5    .035       0  5711.4     .07       0
Bank Sta=4994.3,4999.7
XS Rating Curve= 0 ,0
Exp/Cntr=0.3,0.1

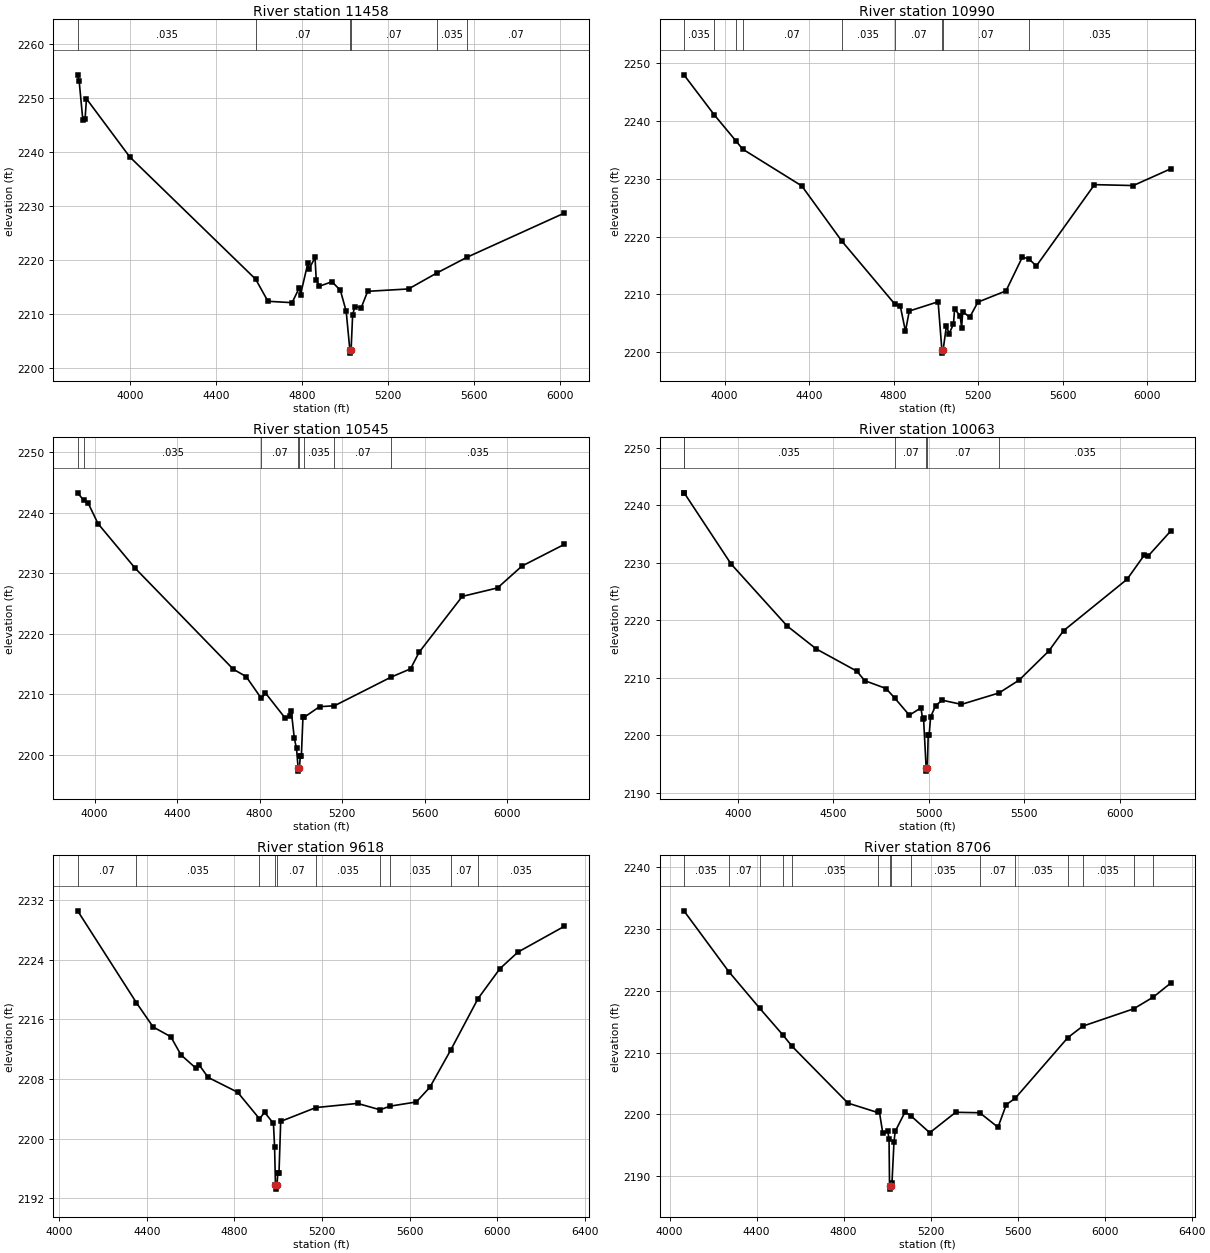
Type RM Length L Ch R = 1 ,11458   ,468,468,468
BEGIN DESCRIPTION:
Buffalo Creek Trib 06 15.0
END DESCRIPTION:
XS GIS Cut Line= 3
      1312561.66      6923151.43        1313755.        6923488.
        1314780.        6923513.
#Sta/Elev= 30
  3755.6 2254.24  3762.8 2253.08  3779.9 2245.85  3790.2  2246.1  3796.8 2249.81
    3998 2239.07  4584.4 2216.43  4641.3 2212.36  4753.7  2212.1  4787.7 2214.89
  4792.9 2213.58  4826.9 2219.36  4832.1 2218.26  4860.4 2220.46  4866.1 2216.37
  4881.2 2215.15  4939.3 2215.97  4978.5 2214.39  5005.5 2210.49  5022.8 2203.27
  5023.2 2202.77  5028.2 2203.27  5035.5 2209.81  5045.5 2211.38  5075.5 2211.18
  5105.5  2214.2  5295.6 2214.64    5427 2217.58  5569.3 2220.53  6020.8 2228.67
#Mann= 6 ,-1 , 0
  3755.6    .035       0  4584.4     .07       0  5022.8     .07       0
  5028.2     .07       0    5427    .035       0  5569.3     .07       0
Bank Sta=5022.8,5028.2
XS Rating Curve= 0 ,0
Exp/Cntr=0.3,0.1

Type RM Length L Ch R = 1 ,10990   ,445,445,445
BEGIN DESCRIPTION:
Buffalo Creek Trib 06 14.0
END DESCRIPTION:
XS GIS Cut Line= 3
      1312520.02      6923521.24        1313655.        6923888.
      1314720.71      6924202.81
#Sta/Elev= 30
  3807.2 2247.99  3950.4 2241.09  4053.5 2236.55  4085.2 2235.14    4365 2228.78
    4555 2219.22  4805.9 2208.32  4831.8 2207.93  4855.9 2203.64  4873.9 2207.14
  5010.4 2208.74  5028.4 2200.36  5028.9 2199.86    5034 2200.36  5049.9 2204.62
  5062.5 2203.21  5083.2  2204.9  5088.4 2207.47  5114.7 2206.33  5121.7 2204.26
  5126.9 2207.03  5160.2 2206.07  5198.7 2208.68  5331.9 2210.63  5408.9 2216.44
    5439  2216.2  5475.5 2214.93  5750.7    2229  5934.3 2228.84  6111.2 2231.73
#Mann= 9 ,-1 , 0
  3807.2    .035       0  3950.4     .07       0  4053.5    .035       0
  4085.2     .07       0    4555    .035       0  4805.9     .07       0
  5028.4     .07       0    5034     .07       0    5439    .035       0
Bank Sta=5028.4,5034
XS Rating Curve= 0 ,0
Exp/Cntr=0.3,0.1

Type RM Length L Ch R = 1 ,10545   ,482,482,482
BEGIN DESCRIPTION:
Buffalo Creek Trib 06 13.0
END DESCRIPTION:
XS GIS Cut Line= 3
      1312431.47      6923885.82        1313455.        6924238.
      1314728.38      6924338.95
#Sta/Elev= 30
  3917.5 2243.26  3947.4    2242  3968.8 2241.54  4016.4 2238.17  4196.2 2230.82
    4672 2214.14  4734.5 2212.92  4808.4 2209.31  4828.2 2210.21  4921.8 2206.15
    4947  2206.4  4953.1 2207.29  4968.2  2202.7  4978.8 2201.06  4986.5 2197.81
    4987 2197.31  4992.7 2197.81  4997.3 2199.89  5002.4 2199.89    5010 2206.24
  5015.4 2206.19  5090.2 2207.95  5162.6  2208.1  5436.5 2212.82  5531.6  2214.2
    5573 2216.93  5782.4 2226.16  5953.4 2227.56  6071.9 2231.17  6277.3 2234.75
#Mann= 8 ,-1 , 0
  3917.5     .07       0  3947.4    .035       0  4808.4     .07       0
  4986.5     .07       0  4992.7     .07       0  5015.4    .035       0
  5162.6     .07       0  5436.5    .035       0
Bank Sta=4986.5,4992.7
XS Rating Curve= 0 ,0
Exp/Cntr=0.3,0.1

Type RM Length L Ch R = 1 ,10063   ,445,445,445
BEGIN DESCRIPTION:
Buffalo Creek Trib 06 12.0
END DESCRIPTION:
XS GIS Cut Line= 3
      1312191.93      6924463.95        1313455.        6924688.
      1314711.33      6924516.23
#Sta/Elev= 30
  3716.7 2242.18  3717.8 2242.18  3963.6  2229.8  4258.1 2218.98  4410.4    2215
    4623 2211.13  4664.3 2209.48  4776.1 2208.11    4821 2206.47  4897.9 2203.47
  4958.9 2204.74  4967.4 2202.85  4972.5 2202.93  4986.2 2194.23  4986.7 2193.73
  4992.5 2194.23  4996.9  2200.1    5002  2200.1  5009.6 2203.16  5035.6 2205.12
  5070.1 2206.08  5171.1 2205.35    5368 2207.34  5473.9 2209.59  5628.6 2214.63
    5706 2218.17  6039.1 2227.13  6129.9 2231.36  6150.1 2231.19  6267.5 2235.52
#Mann= 6 ,-1 , 0
  3716.7     .07       0  3717.8    .035       0    4821     .07       0
  4986.2     .07       0  4992.5     .07       0    5368    .035       0
Bank Sta=4986.2,4992.5
XS Rating Curve= 0 ,0
Exp/Cntr=0.3,0.1

Type RM Length L Ch R = 1 ,9618    ,912,912,912
BEGIN DESCRIPTION:
Buffalo Creek Trib 06 11.0
END DESCRIPTION:
XS GIS Cut Line= 3
      1312368.95      6925271.25        1313255.        6925038.
        1314520.      6924719.17
#Sta/Elev= 30
  4084.8  2230.6  4353.3 2218.24  4429.3 2214.99  4509.9 2213.68  4556.4 2211.24
  4625.7 2209.42  4639.1  2209.9  4680.5 2208.21  4814.9 2206.22  4914.6 2202.65
    4938 2203.52  4978.3 2202.03  4983.5 2198.85  4987.5  2193.7    4988  2193.2
  4993.9  2193.7  4998.5 2195.38  5003.6 2195.38  5011.4  2202.3  5171.9 2204.16
    5362 2204.72  5464.7 2203.86  5510.2 2204.35  5630.1 2204.91    5692 2206.89
  5786.6 2211.86  5911.7  2218.8  6011.7 2222.83  6094.2 2225.06  6305.6 2228.52
#Mann= 10 ,-1 , 0
  4084.8     .07       0  4353.3    .035       0  4914.6     .07       0
  4987.5     .07       0  4993.9     .07       0  5171.9    .035       0
  5464.7     .07       0  5510.2    .035       0  5786.6     .07       0
  5911.7    .035       0
Bank Sta=4987.5,4993.9
XS Rating Curve= 0 ,0
Exp/Cntr=0.3,0.1

Type RM Length L Ch R = 1 ,8706    ,439,439,439
BEGIN DESCRIPTION:
Buffalo Creek Trib 06 10.0
END DESCRIPTION:
XS GIS Cut Line= 3
      1312629.38      6925864.99        1313555.        6925738.
      1314731.81      6925178.33
#Sta/Elev= 30
    4066 2232.96  4271.9 2223.12  4414.1 2217.18  4520.2 2212.87  4563.6 2210.99
    4820  2201.8  4956.2 2200.28  4964.2 2200.47  4980.1 2196.92  5003.1 2197.26
  5008.9 2195.93  5011.2 2188.36  5011.7 2187.86  5017.7 2188.36  5022.4 2188.87
  5031.6 2195.51  5037.1 2197.21  5082.6 2200.37  5109.9 2199.72  5196.1    2197
  5315.2 2200.31  5425.7 2200.24  5509.7 2197.89  5547.9 2201.56  5588.2 2202.56
    5831 2212.42  5899.4 2214.27  6133.5 2217.08    6224 2218.99  6303.4 2221.24
#Mann= 15 ,-1 , 0
    4066    .035       0  4271.9     .07       0  4414.1    .035       0
  4520.2     .07       0  4563.6    .035       0  4956.2     .07       0
  5011.2     .07       0  5017.7     .07       0  5109.9    .035       0
  5425.7     .07       0  5588.2    .035       0    5831     .07       0
  5899.4    .035       0  6133.5     .07       0    6224    .035       0
Bank Sta=5011.2,5017.7
XS Rating Curve= 0 ,0
Exp/Cntr=0.3,0.1

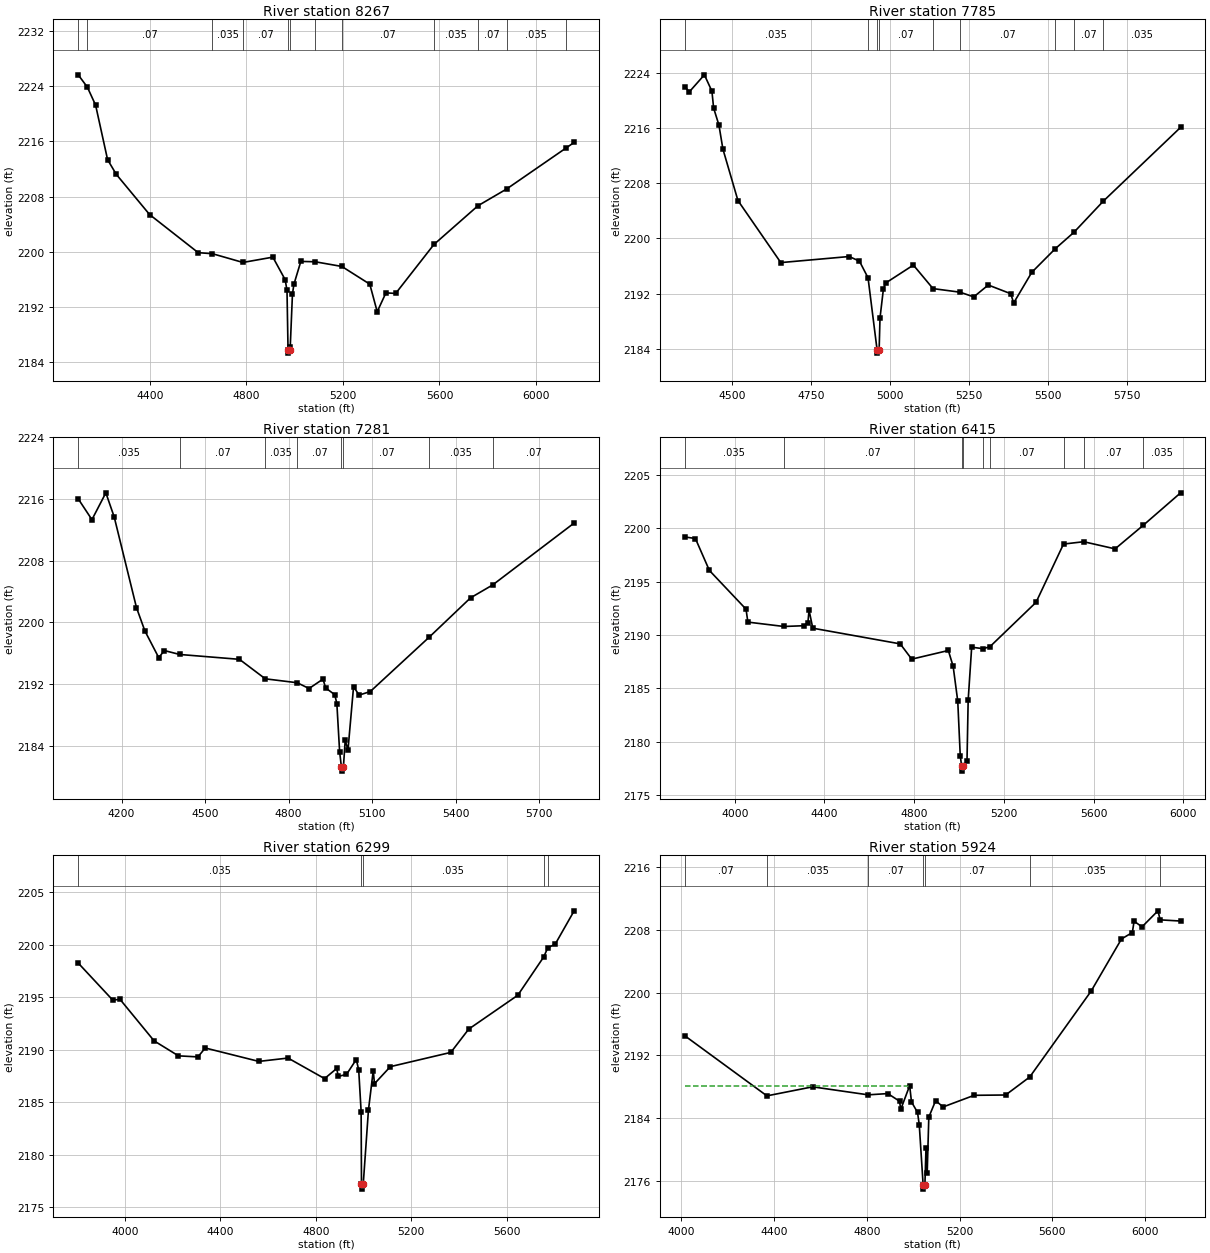
Type RM Length L Ch R = 1 ,8267    ,482,482,482
BEGIN DESCRIPTION:
Buffalo Creek Trib 06 9.0
END DESCRIPTION:
XS GIS Cut Line= 3
      1313005.01      6926587.99        1313755.        6926088.
      1314841.44      6925698.87
#Sta/Elev= 30
  4102.8 2225.66  4140.7 2223.87  4174.9 2221.26  4224.5 2213.35  4260.5 2211.22
  4398.7 2205.38  4600.1 2199.85  4658.9  2199.7  4785.4 2198.43  4909.5  2199.2
  4960.6 2195.92  4968.1 2194.36  4972.4 2185.77  4972.9 2185.27  4978.9 2185.77
  4981.6 2186.22  4990.7 2193.84  4996.7 2195.25  5025.4 2198.58  5084.5 2198.53
  5195.3 2197.85  5311.2 2195.28    5342 2191.28  5378.1 2194.02  5418.4 2193.93
  5577.1 2201.04  5759.6 2206.66  5877.9 2209.08    6123    2215  6158.2 2215.85
#Mann= 12 ,-1 , 0
  4102.8    .035       0  4140.7     .07       0  4658.9    .035       0
  4785.4     .07       0  4972.4     .07       0  4978.9     .07       0
  5084.5    .035       0  5195.3     .07       0  5577.1    .035       0
  5759.6     .07       0  5877.9    .035       0    6123     .07       0
Bank Sta=4972.4,4978.9
XS Rating Curve= 0 ,0
Exp/Cntr=0.3,0.1

Type RM Length L Ch R = 1 ,7785    ,504,504,504
BEGIN DESCRIPTION:
Buffalo Creek Trib 06 8.0
END DESCRIPTION:
XS GIS Cut Line= 3
      1313255.02      6926787.99        1313855.        6926538.
      1314655.04      6926087.98
#Sta/Elev= 30
  4350.3    2222  4364.9 2221.23  4412.6  2223.7  4436.4 2221.33  4441.8 2218.89
  4458.6 2216.41  4471.1 2212.95  4518.7 2205.48  4654.2 2196.49  4870.3 2197.37
  4902.8  2196.7    4930 2194.28  4958.5 2183.87    4959 2183.37  4965.1 2183.87
  4967.8 2188.46  4978.6 2192.67  4985.7 2193.53  5073.3 2196.13  5135.4 2192.72
    5221  2192.2  5264.2 2191.52  5310.1 2193.24  5381.1 2191.98  5390.4 2190.64
  5447.7 2195.08  5521.5 2198.48  5580.5 2200.86  5673.7 2205.39  5918.2 2216.09
#Mann= 9 ,-1 , 0
  4350.3    .035       0    4930     .07       0  4958.5     .07       0
  4965.1     .07       0  5135.4    .035       0    5221     .07       0
  5521.5    .035       0  5580.5     .07       0  5673.7    .035       0
Bank Sta=4958.5,4965.1
XS Rating Curve= 0 ,0
Exp/Cntr=0.3,0.1

Type RM Length L Ch R = 1 ,7281    ,866,866,866
BEGIN DESCRIPTION:
Buffalo Creek Trib 06 7.0
END DESCRIPTION:
XS GIS Cut Line= 3
      1313285.65      6926844.16        1314205.        6926838.
      1315066.92      6926875.41
#Sta/Elev= 30
  4044.1 2216.02  4093.4 2213.32  4143.4  2216.8  4173.4 2213.67  4253.5  2201.9
  4283.5 2198.89  4333.5 2195.41  4353.5 2196.33  4408.9 2195.82  4623.5 2195.19
  4716.4 2192.66  4831.4 2192.15  4873.5  2191.4  4923.5 2192.62  4933.5 2191.47
    4966  2190.6  4973.5 2189.44  4983.5 2183.18    4990 2181.18  4990.5 2180.68
    4997 2181.18  5003.5 2184.67  5013.5 2183.43  5033.5 2191.63  5053.6 2190.55
  5093.6 2191.01  5306.3  2198.1  5453.9 2203.17  5533.2 2204.84  5826.2 2212.88
#Mann= 8 ,-1 , 0
  4044.1    .035       0  4408.9     .07       0  4716.4    .035       0
  4831.4     .07       0    4990     .07       0    4997     .07       0
  5306.3    .035       0  5533.2     .07       0
Bank Sta=4990,4997
XS Rating Curve= 0 ,0
Exp/Cntr=0.3,0.1

Type RM Length L Ch R = 1 ,6415    ,116,116,116
BEGIN DESCRIPTION:
Buffalo Creek Trib 06 6.0
END DESCRIPTION:
XS GIS Cut Line= 4
      1313228.38      6927349.37       1314420.3       6927622.7
      1314664.43      6927686.28      1315395.05      6927599.36
#Sta/Elev= 30
  3776.7 2199.19  3824.5 2199.04  3886.8 2196.05  4050.2 2192.42  4058.4 2191.21
  4219.1  2190.8  4306.7 2190.87    4326 2191.14  4331.1 2192.33  4347.8 2190.64
  4737.6 2189.17  4788.9 2187.74  4952.1 2188.55  4973.6 2187.06  4994.1  2183.8
  5005.2 2178.69  5011.2 2177.75  5011.7 2177.25  5018.3 2177.75  5035.3 2178.22
  5040.5 2183.91  5056.1 2188.86    5107 2188.72  5137.2  2188.9    5343 2193.06
  5465.5 2198.52  5555.6 2198.74  5695.5 2198.07    5821 2200.28  5987.6 2203.32
#Mann= 9 ,-1 , 0
  3776.7    .035       0  4219.1     .07       0  5011.2     .07       0
  5018.3     .07       0    5107    .035       0  5137.2     .07       0
  5465.5    .035       0  5555.6     .07       0    5821    .035       0
Bank Sta=5011.2,5018.3
XS Rating Curve= 0 ,0
Exp/Cntr=0.3,0.1

Type RM Length L Ch R = 1 ,6299    ,375,375,375
BEGIN DESCRIPTION:
Buffalo Creek Trib 06 5.5
END DESCRIPTION:
XS GIS Cut Line= 3
      1313183.44       6927476.1      1314538.48       6927751.2
      1315214.75      6927911.96
#Sta/Elev= 30
  3804.7 2198.26  3949.2 2194.73  3979.8  2194.8  4122.6 2190.84  4224.7 2189.41
  4306.3 2189.31  4336.9 2190.16  4561.4 2188.88  4683.8  2189.2  4836.9 2187.24
  4887.9 2188.21    4894 2187.45  4928.7 2187.64  4969.6 2189.06  4979.8 2188.09
    4990  2184.1  4991.5  2177.2    4992  2176.7  4998.9  2177.2  5020.6 2184.22
  5040.8 2188.01  5045.9 2186.75  5112.4 2188.38  5365.9 2189.74  5440.8 2191.96
  5646.4 2195.19  5754.3 2198.82  5772.3 2199.72  5803.1 2200.06  5882.5 2203.24
#Mann= 5 ,-1 , 0
  3804.7    .035       0  4991.5    .035       0  4998.9    .035       0
  5754.3     .07       0  5772.3    .035       0
#XS Ineff= 2 , 0
       0  4969.6 2189.06               0
Permanent Ineff=
       F       F
Bank Sta=4991.5,4998.9
XS Rating Curve= 0 ,0
Exp/Cntr=0.3,0.1

Type RM Length L Ch R = 1 ,5924    ,477,477,477
BEGIN DESCRIPTION:
Buffalo Creek Trib 06 5.0
END DESCRIPTION:
XS GIS Cut Line= 3
      1313217.94      6927698.32        1314155.        6927988.
      1315279.97      6928262.99
#Sta/Elev= 30
  4014.2 2194.52  4368.9 2186.86  4565.9 2188.01  4805.6 2186.99  4890.3 2187.15
  4940.8 2186.18  4946.1 2185.14  4984.5 2188.16  4992.4 2186.09  5018.4 2184.76
  5025.9 2183.18  5042.7 2175.49  5043.2 2174.99  5050.2 2175.49  5054.9  2180.2
  5060.1 2176.99  5067.1 2184.15  5096.5 2186.25  5128.8 2185.45  5262.7 2186.93
  5398.4 2186.97  5502.3 2189.26  5767.1 2200.19  5898.1 2206.83  5944.9 2207.65
  5952.4 2209.09  5986.6 2208.37  6055.3 2210.41  6064.9 2209.26  6153.1 2209.11
#Mann= 7 ,-1 , 0
  4014.2     .07       0  4368.9    .035       0  4805.6     .07       0
  5042.7     .07       0  5050.2     .07       0  5502.3    .035       0
  6064.9    .045       0
#XS Ineff= 2 , 0
       0  4978.7 2188.07               0
Permanent Ineff=
       F       F
Bank Sta=5042.7,5050.2
XS Rating Curve= 0 ,0
Exp/Cntr=0.3,0.1

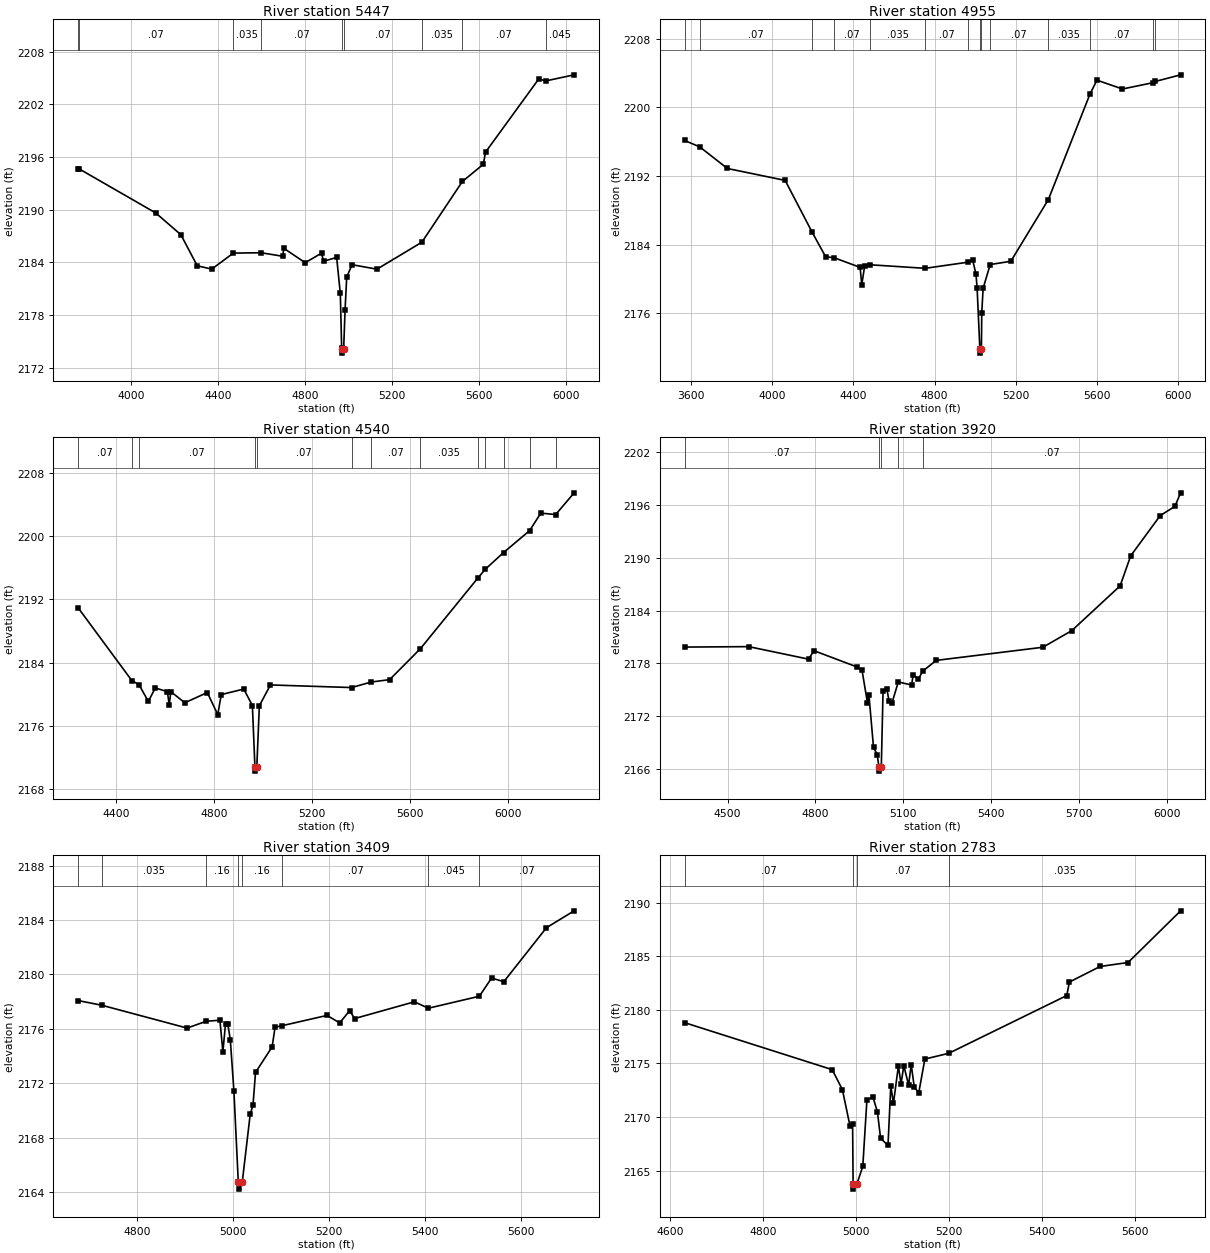
Type RM Length L Ch R = 1 ,5447    ,492,492,492
BEGIN DESCRIPTION:
Buffalo Creek Trib 06 4.0
END DESCRIPTION:
XS GIS Cut Line= 3
      1313113.76      6927927.47        1314255.        6928438.
      1315279.98        6928563.
#Sta/Elev= 30
  3756.3 2194.69  3757.8 2194.69  4113.2 2189.63  4228.7 2187.16  4304.3 2183.61
  4371.1 2183.24  4470.4 2185.06  4598.4  2185.1  4697.4  2184.7  4702.8  2185.6
  4801.1 2183.97  4876.2 2185.05    4886 2184.13  4945.8 2184.57  4962.7 2180.49
    4969 2174.22  4970.7 2174.17  4971.2 2173.67  4978.2 2174.17  4984.6 2178.59
  4992.2 2182.32  5016.6 2183.74  5131.4 2183.23  5338.1  2186.3  5524.8 2193.22
    5621 2195.17  5631.1 2196.55  5875.9 2204.88  5909.1 2204.67  6039.1 2205.36
#Mann= 9 ,-1 , 0
  3756.3    .035       0  3757.8     .07       0  4470.4    .035       0
  4598.4     .07       0  4970.7     .07       0  4978.2     .07       0
  5338.1    .035       0  5524.8     .07       0  5909.1    .045       0
#XS Ineff= 2 , 0
       0  4876.2 2185.05               0
Permanent Ineff=
       F       F
Bank Sta=4970.7,4978.2
XS Rating Curve= 0 ,0
Exp/Cntr=0.3,0.1

Type RM Length L Ch R = 1 ,4955    ,415,415,415
BEGIN DESCRIPTION:
Buffalo Creek Trib 06 3.0
END DESCRIPTION:
XS GIS Cut Line= 3
      1313040.86      6927995.19        1314155.        6928888.
        1315080.        6929313.
#Sta/Elev= 30
  3567.6 2196.14  3642.3 2195.39  3778.2 2192.88  4063.1 2191.49  4196.5 2185.44
  4263.1 2182.58  4302.6  2182.5  4432.8 2181.36  4440.8 2179.33  4455.2 2181.53
  4483.4 2181.66  4753.5 2181.25  4963.8 2181.96  4988.1  2182.2  5004.1 2180.57
  5009.6    2179  5023.3 2171.87  5023.8 2171.37  5030.9 2171.87  5032.6 2176.06
  5039.4 2178.93  5074.3 2181.69  5175.9 2182.07  5361.1 2189.26  5565.9 2201.53
  5600.6 2203.17  5726.5 2202.14  5878.5 2202.88  5888.6 2203.02  6013.3 2203.79
#Mann= 14 ,-1 , 0
  3567.6    .035       0  3642.3     .07       0  4196.5    .035       0
  4302.6     .07       0  4483.4    .035       0  4753.5     .07       0
  4963.8    .035       0  5023.3    .035       0  5030.9    .035       0
  5074.3     .07       0  5361.1    .035       0  5565.9     .07       0
  5878.5    .035       0  5888.6    .045       0
Bank Sta=5023.3,5030.9
XS Rating Curve= 0 ,0
Exp/Cntr=0.3,0.1

Type RM Length L Ch R = 1 ,4540    ,620,620,620
BEGIN DESCRIPTION:
Buffalo Creek Trib 06 2.0
END DESCRIPTION:
XS GIS Cut Line= 3
      1313359.01      6928430.02        1313855.        6928988.
      1315030.26      6929489.91
#Sta/Elev= 30
  4244.6 2190.91  4463.3 2181.72  4492.7  2181.2  4530.8 2179.07  4559.2 2180.78
  4608.6 2180.31  4616.1 2178.64  4622.8 2180.31  4679.7  2178.9  4771.6  2180.2
  4814.3  2177.4  4828.5 2179.94  4920.5 2180.64  4955.6 2178.55    4966 2170.75
  4966.5 2170.25  4973.6 2170.75    4984 2178.52  5029.3 2181.16  5360.7 2180.83
  5440.6 2181.53  5515.8 2181.83  5640.9 2185.73  5874.6 2194.64  5906.1  2195.8
  5980.9 2197.92  6087.3 2200.69  6132.9 2202.91  6193.6 2202.73  6269.1 2205.48
#Mann= 13 ,-1 , 0
  4244.6     .07       0  4463.3    .035       0  4492.7     .07       0
    4966     .07       0  4973.6     .07       0  5360.7    .035       0
  5440.6     .07       0  5640.9    .035       0  5874.6     .07       0
  5906.1    .035       0  5980.9     .07       0  6087.3    .035       0
  6193.6    .045       0
Bank Sta=4966,4973.6
XS Rating Curve= 0 ,0
Exp/Cntr=0.3,0.1

Type RM Length L Ch R = 1 ,3920    ,511,511,511
BEGIN DESCRIPTION:
Buffalo Creek Trib 06 0.7
END DESCRIPTION:
XS GIS Cut Line= 4
      1313374.14      6928990.83      1313577.91      6929464.22
      1313705.54       6929498.4      1314744.24      6929616.44
#Sta/Elev= 30
  4353.5 2179.86  4572.1 2179.91  4776.7 2178.49  4794.8 2179.45  4942.5  2177.6
    4959 2177.22  4977.4 2173.54  4982.5 2174.41  4998.1  2168.5  5010.5 2167.69
  5016.5 2166.31    5017 2165.81  5024.7 2166.31  5030.7 2174.94  5043.8 2175.11
  5050.8 2173.79  5060.9 2173.51  5082.7 2175.91  5128.3 2175.56  5133.3 2176.72
  5151.4 2176.25  5165.8 2177.12  5211.8 2178.35  5576.2 2179.84  5674.8 2181.72
  5839.8 2186.79  5876.1  2190.2  5976.7 2194.75    6027  2195.8  6046.4 2197.33
#Mann= 5 ,-1 , 0
  4353.5     .07       0  5016.5     .07       0  5024.7     .07       0
  5082.7    .035       0  5165.8     .07       0
Bank Sta=5016.5,5024.7
XS Rating Curve= 0 ,0
Exp/Cntr=0.3,0.1

Type RM Length L Ch R = 1 ,3409    ,626,626,626
BEGIN DESCRIPTION:
Buffalo Creek Trib 06 0.5
END DESCRIPTION:
XS GIS Cut Line= 3
      1313516.67      6929817.09      1313799.97      6929946.94
      1314496.37      6929758.09
#Sta/Elev= 30
  4677.2 2178.08  4726.2 2177.74  4904.1 2176.06  4943.8 2176.56  4972.4 2176.64
  4978.6 2174.31  4984.1 2176.38  4988.8 2176.38  4994.1 2175.19  5001.6 2171.41
  5010.7 2164.72  5011.2 2164.22  5018.9 2164.72  5035.5 2169.72  5041.4 2170.42
  5046.6  2172.8  5081.2 2174.68  5087.3 2176.13  5102.6 2176.24  5195.5 2176.99
    5222 2176.44  5242.7 2177.34  5253.1 2176.76  5377.4 2177.99  5406.8 2177.52
  5512.9  2178.4  5538.4 2179.74  5563.9 2179.47  5652.7 2183.44  5710.4 2184.68
#Mann= 8 ,-1 , 0
  4677.2     .07       0  4726.2    .035       0  4943.8     .16       0
  5010.7     .07       0  5018.9     .16       0  5102.6     .07       0
  5406.8    .045       0  5512.9     .07       0
Bank Sta=5010.7,5018.9
XS Rating Curve= 0 ,0
Exp/Cntr=0.3,0.1

Type RM Length L Ch R = 1 ,2783    ,620,620,620
BEGIN DESCRIPTION:
Buffalo Creek Trib 06 1.0
END DESCRIPTION:
XS GIS Cut Line= 3
      1313480.02      6930263.01        1313805.        6930438.
      1314420.17      6930765.91
#Sta/Elev= 30
  4631.4  2178.8  4948.6 2174.42  4970.5 2172.55  4986.7 2169.19  4992.4 2169.34
  4993.5 2163.78    4994 2163.28  5001.8 2163.78  5014.3  2165.4  5023.2 2171.61
  5036.3 2171.85  5045.8 2170.47  5052.6 2168.02  5068.5 2167.36  5074.5 2172.93
  5080.2 2171.27  5090.8 2174.75  5096.5  2173.1  5102.5 2174.78  5112.8    2173
  5118.4 2174.88  5125.1 2172.77  5134.7 2172.28  5147.8 2175.41  5198.9 2175.94
  5452.8 2181.33  5458.5 2182.59  5524.4 2184.04  5584.6 2184.41  5697.6 2189.23
#Mann= 4 ,-1 , 0
  4631.4     .07       0  4993.5     .07       0  5001.8     .07       0
  5198.9    .035       0
Bank Sta=4993.5,5001.8
XS Rating Curve= 0 ,0
Exp/Cntr=0.3,0.1