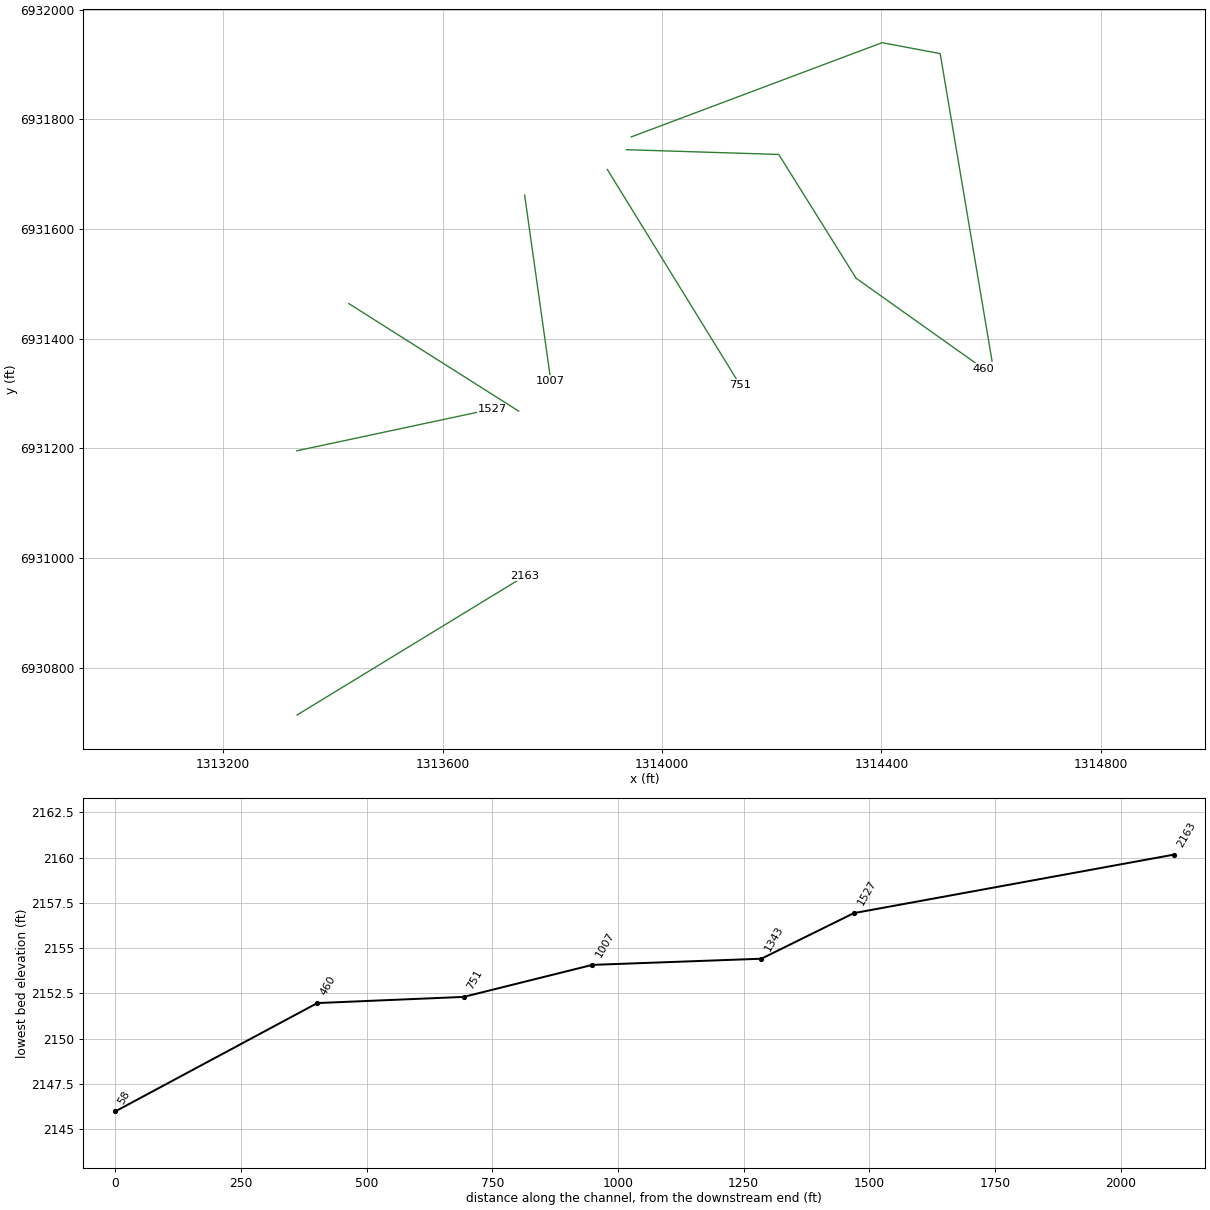
HEC-RAS study Buffalo Creek Trib 06.prj: Buffalo Creek Trib 06 Base Level Engineering

--- Buffalo Creek Trib 06.g01 (geometry) --- (continued)

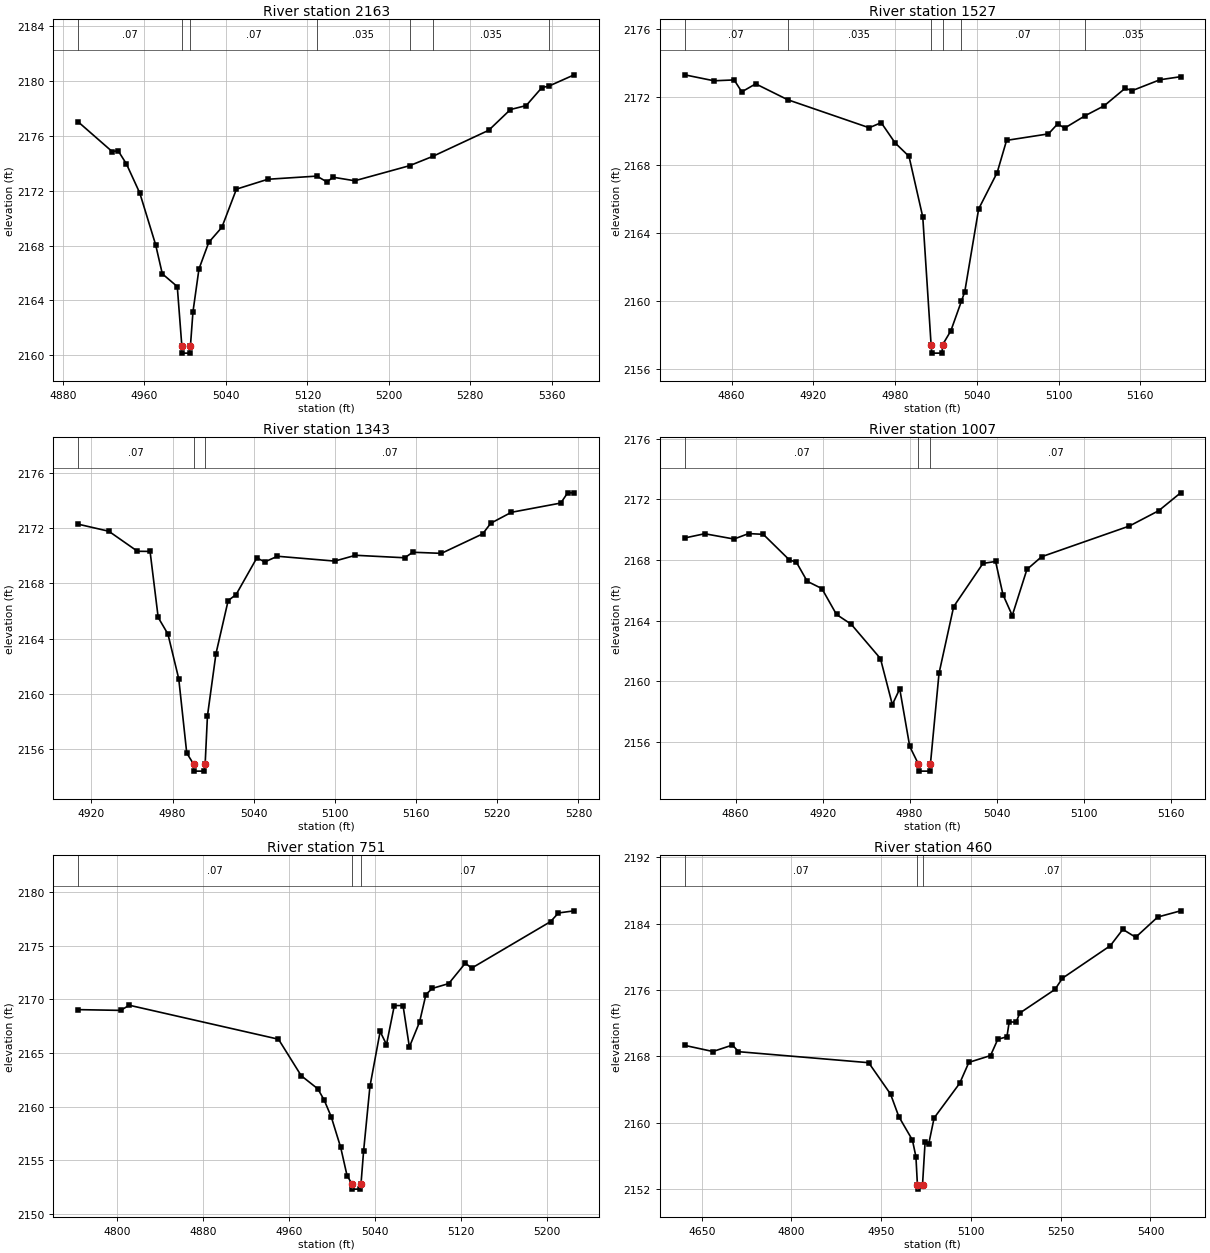
Type RM Length L Ch R = 1 ,2163    ,636,636,636
BEGIN DESCRIPTION:
Buffalo Creek Trib 06 0.9
END DESCRIPTION:
XS GIS Cut Line= 2
      1313334.51      6930713.83      1313750.37      6930967.46
#Sta/Elev= 30
  4894.9 2177.01  4928.2 2174.85  4934.1 2174.91  4942.3 2173.94  4955.4 2171.82
  4970.9 2168.07  4977.5 2165.94  4992.2 2165.01  4996.7 2160.66  4997.2 2160.16
  5004.6 2160.16  5005.1 2160.66  5007.6 2163.17  5013.5 2166.29  5023.1 2168.23
    5036 2169.33  5050.3 2172.11  5081.2 2172.83  5129.3 2173.06  5139.3 2172.63
  5145.1 2172.98  5166.5 2172.72  5220.4 2173.82  5243.2  2174.5  5298.1  2176.4
  5319.4 2177.91  5334.9  2178.2  5350.3 2179.51  5357.2 2179.62    5382 2180.44
#Mann= 7 ,-1 , 0
  4894.9     .07       0  4996.7     .07       0  5005.1     .07       0
  5129.3    .035       0  5220.4     .07       0  5243.2    .035       0
  5357.2     .07       0
Bank Sta=4996.7,5005.1
XS Rating Curve= 0 ,0
Exp/Cntr=0.3,0.1

Type RM Length L Ch R = 1 ,1527    ,184,184,184
BEGIN DESCRIPTION:
Buffalo Creek Trib 06 0.8
END DESCRIPTION:
XS GIS Cut Line= 2
      1313334.02      6931195.51       1313689.9      6931271.46
#Sta/Elev= 30
  4825.6 2173.28  4847.1 2172.93  4861.9 2172.98  4867.5 2172.28  4877.7 2172.75
  4901.1 2171.82    4961 2170.17  4969.8 2170.47    4980 2169.28  4990.2 2168.49
  5000.3 2164.93  5006.4 2157.43  5006.9 2156.93  5014.4 2156.93  5014.9 2157.43
  5020.9 2158.24  5028.6 2159.97  5031.1 2160.53  5041.3  2165.4  5054.9 2167.54
  5061.8 2169.43  5092.5 2169.81  5099.3  2170.4  5104.4 2170.15  5119.5 2170.88
  5133.4 2171.46  5148.8 2172.49  5153.9 2172.35  5174.3 2172.99  5189.5 2173.17
#Mann= 6 ,-1 , 0
  4825.6     .07       0  4901.1    .035       0  5006.4    .035       0
  5014.9    .035       0  5028.6     .07       0  5119.5    .035       0
Bank Sta=5006.4,5014.9
XS Rating Curve= 0 ,0
Exp/Cntr=0.3,0.1

Type RM Length L Ch R = 1 ,1343    ,336,336,336
BEGIN DESCRIPTION:
Buffalo Creek Trib 06 0.75
END DESCRIPTION:
XS GIS Cut Line= 2
      1313429.01       6931463.9      1313738.68      6931267.87
#Sta/Elev= 30
  4910.3 2172.28  4932.9 2171.77  4954.1 2170.32  4963.4 2170.31  4969.4 2165.53
  4976.6 2164.33  4984.6 2161.09  4990.5 2155.72  4995.6 2154.91  4996.1 2154.41
  5003.6 2154.41  5004.1 2154.91  5005.8  2158.4  5012.1 2162.91  5021.1 2166.75
    5027 2167.19  5042.3 2169.84  5048.2 2169.55  5057.5 2169.96  5099.9 2169.61
  5115.2 2170.03  5151.6 2169.85  5157.5 2170.25  5178.7 2170.17  5209.2 2171.58
  5215.2 2172.35  5230.4 2173.14  5266.9 2173.81    5272 2174.55  5276.8 2174.55
#Mann= 3 ,-1 , 0
  4910.3     .07       0  4995.6     .07       0  5004.1     .07       0
Bank Sta=4995.6,5004.1
XS Rating Curve= 0 ,0
Exp/Cntr=0.3,0.1

Type RM Length L Ch R = 1 ,1007    ,256,256,256
BEGIN DESCRIPTION:
Buffalo Creek Trib 06 0.65
END DESCRIPTION:
XS GIS Cut Line= 2
      1313749.56      6931661.67      1313797.29      6931323.01
#Sta/Elev= 30
  4824.9 2169.46  4838.7 2169.74  4858.9 2169.39    4869 2169.75  4879.1  2169.7
    4897 2168.02    4902 2167.85  4909.4  2166.6  4919.5 2166.12  4929.6 2164.41
  4939.7 2163.77  4959.9  2161.5  4968.1 2158.46  4973.2  2159.5  4980.1  2155.7
  4985.9 2154.57  4986.4 2154.07  4993.9 2154.07  4994.4 2154.57  5000.3 2160.53
  5010.4 2164.93  5030.6 2167.78  5039.3 2167.91  5044.4 2165.72  5050.8 2164.34
  5060.9 2167.38    5071 2168.22  5131.6 2170.25  5151.8 2171.26  5166.9 2172.44
#Mann= 3 ,-1 , 0
  4824.9     .07       0  4985.9     .07       0  4994.4     .07       0
Bank Sta=4985.9,4994.4
XS Rating Curve= 0 ,0
Exp/Cntr=0.3,0.1

Type RM Length L Ch R = 1 ,751     ,291,291,291
BEGIN DESCRIPTION:
Buffalo Creek Trib 06 0.6
END DESCRIPTION:
XS GIS Cut Line= 2
      1313900.36      6931708.42      1314142.36      6931315.58
#Sta/Elev= 30
  4763.8 2169.05  4803.3 2168.98  4811.3 2169.46  4950.1 2166.29  4971.3 2162.88
  4986.7 2161.66  4992.6 2160.62  4999.2 2159.05    5008 2156.19  5013.9 2153.57
  5018.4  2152.8  5018.9  2152.3  5026.4  2152.3  5026.9  2152.8  5029.3 2155.84
  5035.2 2161.88  5044.7 2167.01  5050.6 2165.79  5057.9 2169.43    5066 2169.43
  5071.9 2165.56  5081.4  2167.9  5087.3 2170.46  5093.2 2171.03  5108.5 2171.48
    5124 2173.39  5129.8 2172.92  5203.2 2177.26  5210.6 2178.07  5225.2 2178.27
#Mann= 3 ,-1 , 0
  4763.8     .07       0  5018.4     .07       0  5026.9     .07       0
Bank Sta=5018.4,5026.9
XS Rating Curve= 0 ,0
Exp/Cntr=0.3,0.1

Type RM Length L Ch R = 1 ,460     ,402,402,402
BEGIN DESCRIPTION:
Buffalo Creek Trib 06 0.3
END DESCRIPTION:
XS GIS Cut Line= 4
      1313935.15      6931744.55       1314212.9      6931735.87
      1314353.96      6931510.17       1314586.2      6931345.22
#Sta/Elev= 30
  4621.5 2169.31  4668.7 2168.57  4701.4 2169.35  4711.4 2168.55    4929 2167.22
  4965.6 2163.43  4979.4 2160.71  5002.1 2157.89    5008 2155.87  5010.5 2152.46
    5011 2151.96    5019 2152.46  5023.3  2157.6  5029.2 2157.35  5038.4 2160.55
  5081.1 2164.73  5096.5 2167.26  5132.7 2168.08  5144.8 2170.04  5160.1 2170.35
  5163.9 2172.15  5175.4 2172.11  5181.6 2173.21  5240.4 2176.06  5252.9 2177.42
  5332.9 2181.34  5353.8 2183.31  5375.3 2182.36  5412.1  2184.8  5450.4 2185.55
#Mann= 3 ,-1 , 0
  4621.5     .07       0  5010.5     .07       0    5019     .07       0
Bank Sta=5010.5,5019
XS Rating Curve= 0 ,0
Exp/Cntr=0.3,0.1

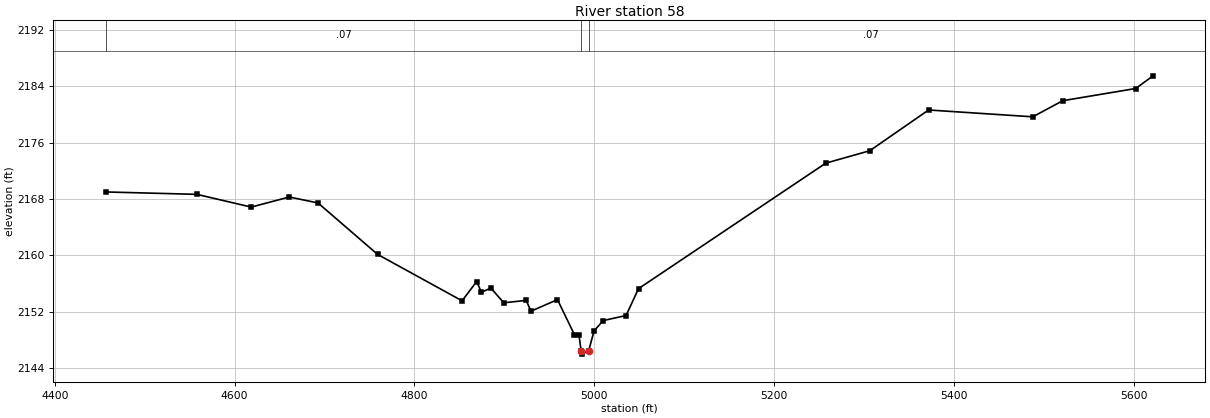
Type RM Length L Ch R = 1 ,58      ,0,0,0
BEGIN DESCRIPTION:
Buffalo Creek Trib 06 0.1
END DESCRIPTION:
XS GIS Cut Line= 4
      1313943.94      6931767.82      1314401.39      6931939.69
      1314507.29      6931919.72       1314601.9      6931358.98
#Sta/Elev= 30
  4456.6    2169  4557.9 2168.66  4618.4 2166.85  4660.7 2168.28  4692.7 2167.44
  4758.9 2160.14    4853 2153.54  4869.2 2156.28  4874.5 2154.76    4885 2155.35
  4899.4 2153.26  4924.3  2153.6  4929.7 2152.07  4959.1 2153.71  4977.9 2148.75
    4983  2148.7  4985.4 2146.47  4985.9 2145.97  4993.9 2146.47  4999.8 2149.27
    5010 2150.74  5035.4 2151.45  5049.3 2155.27  5257.6 2173.09  5306.5 2174.85
    5372 2180.64  5487.9 2179.67  5521.3 2181.96  5602.4 2183.69  5621.7 2185.49
#Mann= 3 ,-1 , 0
  4456.6     .07       0  4985.4     .07       0  4993.9     .07       0
Bank Sta=4985.4,4993.9
XS Rating Curve= 0 ,0
Exp/Cntr=0.3,0.1

Chan Stop Cuts=-1
Use User Specified Reach Order=0
Composite Channel Slope=5