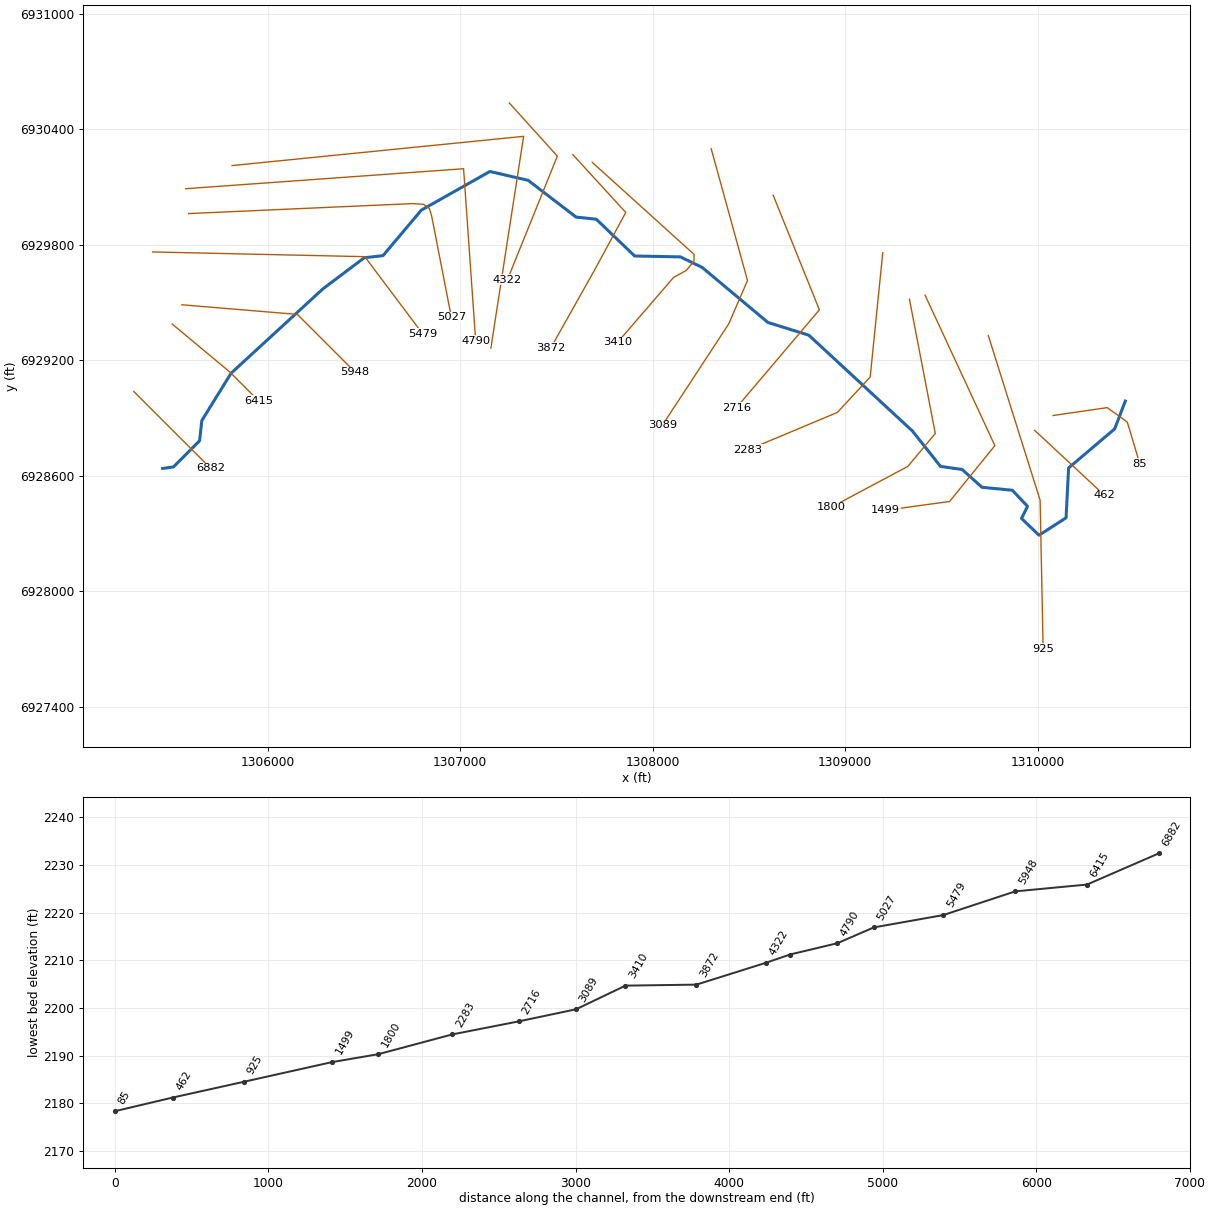
--- Buffalo Creek Trib 07-01.prj (project) ---

Proj Title=Buffalo Creek Trib 07-01 Base Level Engineering
Current Plan=p01
Default Exp/Contr=0.3,0.1
English Units
Geom File=g01
Flow File=f01
Plan File=p01
BEGIN DESCRIPTION:
Buffalo Creek Trib 07-01
END DESCRIPTION:

--- Buffalo Creek Trib 07-01.p01 (plan) ---

Plan Title=Multiple Run
Short Identifier=Multiple
Geom File=g01
Flow File=f01
Subcritical Flow
K Sum by GR= 0
Std Step Tol= 0.01
Critical Tol= 0.01
Num of Std Step Trials= 20
Max Error Tol= 0.3
Flow Tol Ratio= 0.001
Split Flow NTrial= 30
Split Flow Tol= 0.02
Split Flow Ratio= 0.02
Log Output Level= 0
Friction Slope Method= 1
Unsteady Friction Slope Method= 2
Unsteady Bridges Friction Slope Method= 1
Parabolic Critical Depth
Global Vel Dist=  1 , 1 , 1
Global Log Level= 0
CheckData=True
Encroach Param= -1, 0, 0, 0
BEGIN DESCRIPTION:
Multiple Run
END DESCRIPTION:

--- Buffalo Creek Trib 07-01.f01 (steady flow) ---

Flow Title=Multiple
Number of Profiles=7
Profile Names=10-year,25-year,50-year,1pct_min,100-year,1pct_plu,500-year
River Rch & RM= Buffalo Creek Tr,Reach-1,6882
     379     549     694     436     870    1737    1388
Boundary for River Rch & Prof#=Buffalo Creek Tr,Reach-1,1
Up Type=0
Dn Type=3
Dn Slope=0.005
Boundary for River Rch & Prof#=Buffalo Creek Tr,Reach-1,2
Up Type=0
Dn Type=3
Dn Slope=0.005
Boundary for River Rch & Prof#=Buffalo Creek Tr,Reach-1,3
Up Type=0
Dn Type=3
Dn Slope=0.005
Boundary for River Rch & Prof#=Buffalo Creek Tr,Reach-1,4
Up Type=0
Dn Type=3
Dn Slope=0.005
Boundary for River Rch & Prof#=Buffalo Creek Tr,Reach-1,5
Up Type=0
Dn Type=3
Dn Slope=0.005
Boundary for River Rch & Prof#=Buffalo Creek Tr,Reach-1,6
Up Type=0
Dn Type=3
Dn Slope=0.005
Boundary for River Rch & Prof#=Buffalo Creek Tr,Reach-1,7
Up Type=0
Dn Type=3
Dn Slope=0.005

--- Buffalo Creek Trib 07-01.g01 (geometry) ---

Geom Title=Existing Conditions

River Reach=Buffalo Creek Tr,Reach-1
Reach XY= 30
      1305455.00      6928638.00      1305511.21      6928645.76
      1305647.14      6928781.83      1305658.63      6928886.50
      1305810.59      6929132.39      1306288.33      6929571.35
      1306502.63      6929732.45      1306599.53      6929743.26
      1306798.95      6929979.86      1307154.99      6930180.47
      1307353.53      6930134.45      1307602.58      6929943.54
      1307707.43      6929932.48      1307906.46      6929741.54
      1308144.50      6929736.80      1308257.30      6929682.17
      1308598.95      6929396.16      1308811.17      6929330.14
      1309349.38      6928832.38      1309495.21      6928648.52
      1309607.42      6928632.46      1309710.86      6928540.08
      1309868.37      6928524.63      1309947.00      6928441.35
      1309916.24      6928377.97      1310006.96      6928291.02
      1310147.26      6928381.54      1310160.46      6928640.45
      1310399.77      6928843.45      1310455.00      6928988.00

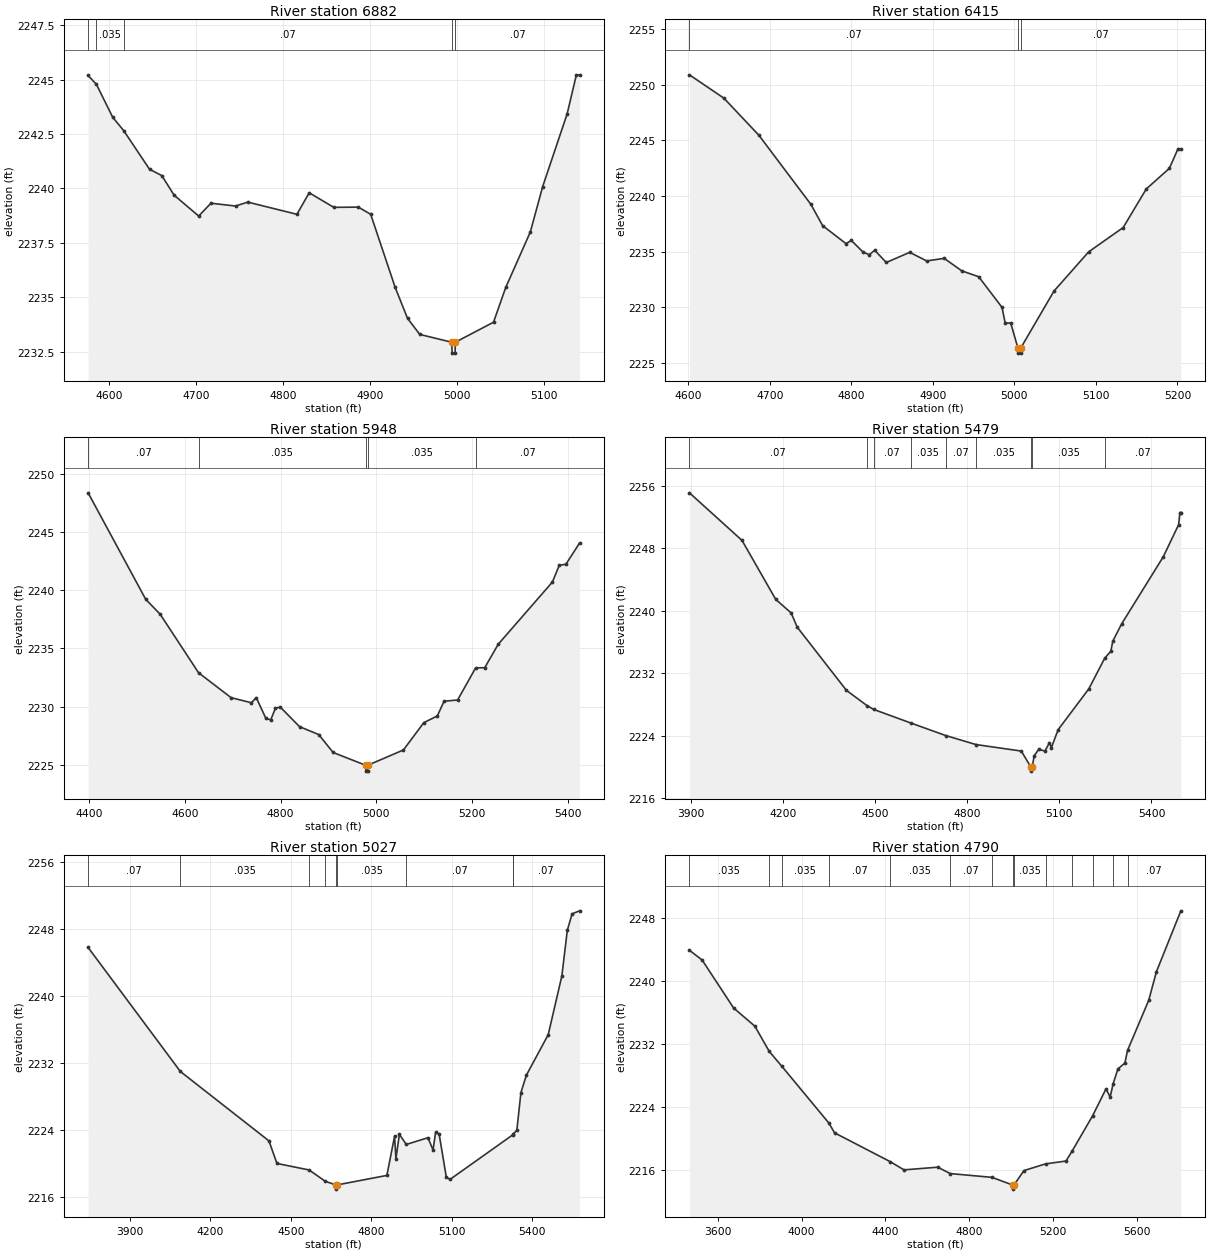
Type RM Length L Ch R = 1,6882,467,467,467
BEGIN DESCRIPTION:
Buffalo Creek Trib 07-01 4.5
END DESCRIPTION:
XS GIS Cut Line= 3
      1305305.01      6929037.99      1305605.00      6928738.00
      1305705.02      6928637.98
#Sta/Elev= 30
  4575.5 2245.19  4585.1 2244.78  4603.8 2243.27  4616.4 2242.66  4646.2 2240.88
  4660.3 2240.59  4674.5 2239.69  4702.8 2238.73  4716.9 2239.32  4745.2 2239.19
  4759.3 2239.37  4815.9 2238.81  4830.0 2239.80  4858.3 2239.13  4886.6 2239.14
  4900.8 2238.81  4929.0 2235.45  4943.2 2234.03  4957.3 2233.29  4994.2 2232.93
  4994.5 2232.43  4998.0 2232.43  4998.2 2232.93  5042.2 2233.85  5056.3 2235.45
  5084.6 2238.00  5098.7 2240.07  5127.0 2243.43  5137.6 2245.22  5141.2 2245.22
#Mann=5,-1,0
  4575.5    0.07       0  4585.1   0.035       0  4616.4    0.07       0
  4994.2    0.07       0  4998.2    0.07       0
Bank Sta=4994.2,4998.2
Exp/Cntr=0.3,0.1

Type RM Length L Ch R = 1,6415,467,467,467
BEGIN DESCRIPTION:
Buffalo Creek Trib 07-01 3.5
END DESCRIPTION:
XS GIS Cut Line= 3
      1305505.03      6929387.98      1305805.00      6929138.00
      1305954.99      6928988.01
#Sta/Elev= 30
  4601.6 2250.88  4643.9 2248.78  4686.8 2245.45  4750.6 2239.24  4764.9 2237.34
  4793.6 2235.72  4800.1 2236.01  4814.4 2234.97  4822.2 2234.72  4828.7 2235.13
  4843.0 2234.03  4871.7 2234.94  4892.5 2234.17  4914.0 2234.40  4935.5 2233.28
  4956.3 2232.75  4984.9 2230.00  4988.8 2228.59  4995.6 2228.59  5004.2 2226.39
  5004.5 2225.89  5008.0 2225.89  5008.2 2226.39  5048.6 2231.46  5091.1 2234.98
  5133.5 2237.17  5161.8 2240.63  5190.1 2242.48  5200.7 2244.24  5204.2 2244.24
#Mann=3,-1,0
  4601.6    0.07       0  5004.2    0.07       0  5008.2    0.07       0
Bank Sta=5004.2,5008.2
Exp/Cntr=0.3,0.1

Type RM Length L Ch R = 1,5948,469,469,469
BEGIN DESCRIPTION:
Buffalo Creek Trib 07-01 2.5
END DESCRIPTION:
XS GIS Cut Line= 3
      1305554.97      6929488.00      1306155.00      6929438.00
      1306455.02      6929137.98
#Sta/Elev= 30
  4397.9 2248.36  4518.3 2239.21  4548.5 2237.93  4628.6 2232.91  4696.5 2230.77
  4739.1 2230.33  4749.1 2230.78  4769.2 2228.99  4779.3 2228.86  4789.3 2229.87
  4799.3 2229.96  4839.5 2228.28  4879.6 2227.60  4909.7 2226.06  4977.9 2224.96
  4978.2 2224.46  4981.7 2224.46  4981.9 2224.96  5056.6 2226.28  5099.0 2228.62
  5127.3 2229.20  5141.4 2230.46  5169.7 2230.57  5207.4 2233.33  5226.3 2233.34
  5254.6 2235.36  5367.7 2240.70  5381.9 2242.13  5396.0 2242.23  5424.3 2244.04
#Mann=5,-1,0
  4397.9    0.07       0  4628.6   0.035       0  4977.9   0.035       0
  4981.9   0.035       0  5207.4    0.07       0
Bank Sta=4977.9,4981.9
Exp/Cntr=0.3,0.1

Type RM Length L Ch R = 1,5479,452,452,452
BEGIN DESCRIPTION:
Buffalo Creek Trib 07-01 1.2
END DESCRIPTION:
XS GIS Cut Line= 3
      1305403.74      6929762.49      1306505.00      6929738.00
      1306804.98      6929338.02
#Sta/Elev= 30
  3894.3 2255.11  4065.6 2249.02  4175.6 2241.46  4225.6 2239.74  4245.6 2237.91
  4405.7 2229.83  4472.6 2227.88  4494.6 2227.38  4615.9 2225.64  4729.2 2224.04
  4828.3 2222.88  4975.8 2222.05  5007.4 2219.98  5007.6 2219.48  5011.4 2219.98
  5017.7 2221.43  5032.3 2222.26  5053.1 2222.06  5067.7 2223.13  5074.0 2222.50
  5095.8 2224.78  5195.8 2230.01  5247.7 2233.94  5267.7 2234.83  5274.0 2236.12
  5303.1 2238.35  5438.5 2246.92  5488.5 2251.03  5492.7 2252.59  5495.8 2252.59
#Mann=9,-1,0
  3894.3    0.07       0  4472.6   0.035       0  4494.6    0.07       0
  4615.9   0.035       0  4729.2    0.07       0  4828.3   0.035       0
  5007.4   0.035       0  5011.4   0.035       0  5247.7    0.07       0
Bank Sta=5007.4,5011.4
Exp/Cntr=0.3,0.1

Type RM Length L Ch R = 1,5027,237,237,237
BEGIN DESCRIPTION:
Buffalo Creek Trib 07-01 2.8
END DESCRIPTION:
XS GIS Cut Line= 6
      1305590.46      6929961.84      1306753.48      6930013.71
      1306810.77      6930009.81      1306840.72      6929988.00
      1306852.44      6929948.61      1306954.80      6929423.34
#Sta/Elev= 30
  3743.0 2245.79  4087.4 2230.96  4418.2 2222.66  4448.2 2219.96  4568.3 2219.18
  4628.4 2217.83  4668.1 2217.39  4668.3 2216.89  4672.1 2217.39  4858.6 2218.53
  4887.4 2223.22  4892.4 2220.52  4905.4 2223.44  4931.1 2222.23  5012.1 2223.04
  5031.0 2221.57  5040.5 2223.67  5053.6 2223.50  5080.6 2218.32  5094.3 2218.05
  5327.8 2223.36  5328.7 2223.44  5343.8 2223.91  5359.2 2228.44  5379.6 2230.52
  5461.1 2235.36  5512.0 2242.38  5532.4 2247.84  5550.2 2249.81  5577.9 2250.17
#Mann=9,-1,0
  3743.0    0.07       0  4087.4   0.035       0  4568.3    0.07       0
  4628.4   0.035       0  4668.1    0.07       0  4672.1   0.035       0
  4931.1    0.07       0  5327.8   0.035       0  5328.7    0.07       0
Bank Sta=4668.1,4672.1
Exp/Cntr=0.3,0.1

Type RM Length L Ch R = 1,4790,309,309,309
BEGIN DESCRIPTION:
Buffalo Creek Trib 07-01 0.85
END DESCRIPTION:
XS GIS Cut Line= 3
      1305574.86      6930090.92      1307018.24      6930194.81
      1307080.83      6929302.01
#Sta/Elev= 30
  3465.7 2243.85  3526.0 2242.62  3676.4 2236.53  3777.5 2234.23  3846.1 2231.03
  3906.6 2229.13  4129.4 2221.98  4157.6 2220.71  4421.2 2217.08  4488.5 2216.02
  4648.9 2216.36  4709.0 2215.55  4908.3 2215.07  5007.9 2214.08  5008.1 2213.58
  5011.9 2214.08  5060.0 2215.93  5163.1 2216.78  5260.5 2217.14  5289.5 2218.40
  5387.4 2222.88  5450.9 2226.28  5471.0 2225.26  5485.3 2226.96  5508.0 2228.82
  5541.2 2229.56  5553.7 2231.16  5654.7 2237.51  5691.5 2241.14  5807.8 2248.85
#Mann=14,-1,0
  3465.7   0.035       0  3846.1    0.07       0  3906.6   0.035       0
  4129.4    0.07       0  4421.2   0.035       0  4709.0    0.07       0
  4908.3   0.035       0  5007.9   0.035       0  5011.9   0.035       0
  5163.1    0.07       0  5289.5   0.035       0  5387.4    0.07       0
  5485.3   0.035       0  5553.7    0.07       0
Bank Sta=5007.9,5011.9
Exp/Cntr=0.3,0.1

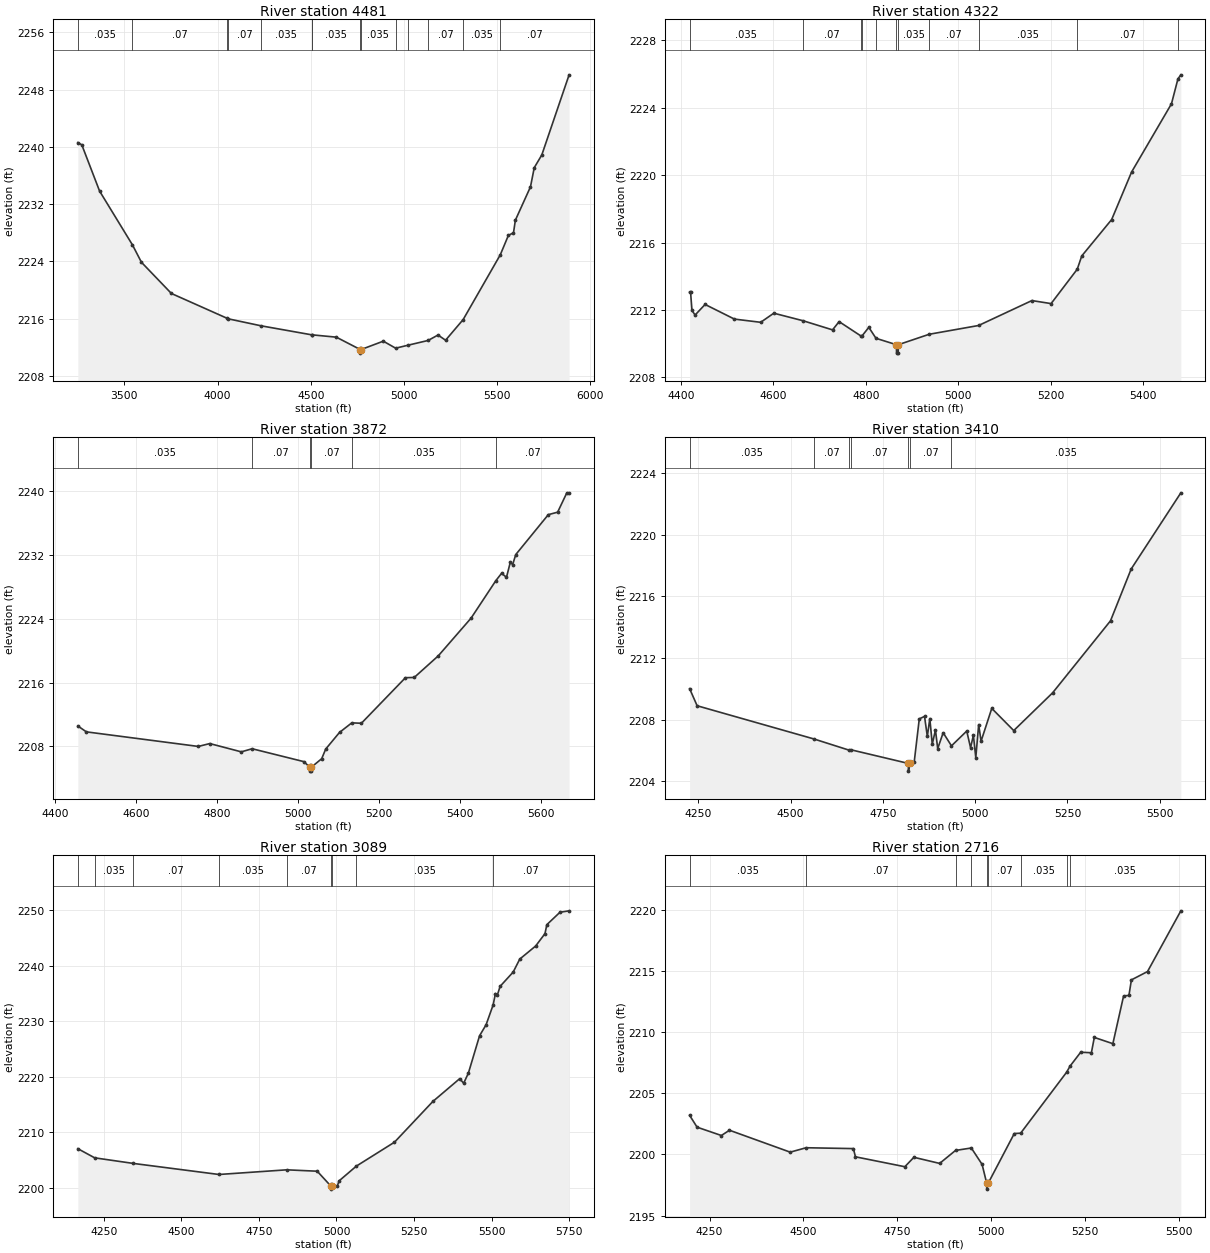
Type RM Length L Ch R = 1,4481,159,159,159
BEGIN DESCRIPTION:
Buffalo Creek Trib 07-01 0.5
END DESCRIPTION:
XS GIS Cut Line= 3
      1305815.74      6930211.20      1307330.00      6930363.00
      1307159.94      6929263.32
#Sta/Elev= 30
  3250.7 2240.61  3271.9 2240.29  3367.3 2233.83  3543.7 2226.31  3591.7 2223.89
  3752.5 2219.53  4049.1 2216.09  4057.6 2215.99  4234.4 2215.01  4504.0 2213.76
  4504.2 2213.76  4636.9 2213.43  4765.5 2211.70  4765.8 2211.20  4769.5 2211.70
  4888.9 2212.87  4955.0 2211.89  5018.8 2212.29  5129.2 2212.97  5182.4 2213.73
  5222.8 2213.00  5317.2 2215.89  5516.2 2224.93  5559.8 2227.65  5587.1 2228.01
  5597.2 2229.77  5678.2 2234.43  5698.4 2237.10  5738.9 2238.88  5885.3 2250.07
#Mann=14,-1,0
  3250.7   0.035       0  3543.7    0.07       0  4049.1   0.035       0
  4057.6    0.07       0  4234.4   0.035       0  4504.0    0.07       0
  4504.2   0.035       0  4765.5    0.07       0  4769.5   0.035       0
  4955.0    0.07       0  5018.8   0.035       0  5129.2    0.07       0
  5317.2   0.035       0  5516.2    0.07       0
Bank Sta=4765.5,4769.5
Exp/Cntr=0.3,0.1

Type RM Length L Ch R = 1,4322,450,450,450
BEGIN DESCRIPTION:
Buffalo Creek Trib 07-01 7.0
END DESCRIPTION:
XS GIS Cut Line= 3
      1307255.97      6930536.10      1307505.08      6930260.11
      1307246.21      6929619.20
#Sta/Elev= 30
  4418.8 2213.05  4420.9 2213.05  4423.9 2211.98  4430.6 2211.70  4452.3 2212.33
  4515.8 2211.46  4572.6 2211.27  4601.0 2211.81  4664.6 2211.36  4728.1 2210.82
  4742.3 2211.31  4788.9 2210.47  4792.1 2210.47  4806.6 2210.97  4822.1 2210.32
  4866.3 2209.94  4866.6 2209.44  4870.1 2209.44  4870.4 2209.94  4937.3 2210.56
  5044.1 2211.08  5159.5 2212.56  5201.0 2212.38  5257.6 2214.42  5267.4 2215.21
  5332.1 2217.37  5375.2 2220.19  5461.5 2224.24  5475.5 2225.72  5481.8 2225.96
#Mann=11,-1,0
  4418.8   0.035       0  4664.6    0.07       0  4788.9   0.035       0
  4792.1    0.07       0  4822.1   0.035       0  4866.3    0.07       0
  4870.4   0.035       0  4937.3    0.07       0  5044.1   0.035       0
  5257.6    0.07       0  5475.5   0.035       0
Bank Sta=4866.3,4870.4
Exp/Cntr=0.3,0.1

Type RM Length L Ch R = 1,3872,462,462,462
BEGIN DESCRIPTION:
Buffalo Creek Trib 07-01 6.0
END DESCRIPTION:
XS GIS Cut Line= 4
      1307585.50      6930268.17      1307860.56      6929967.61
      1307700.28      6929671.70      1307470.82      6929263.30
#Sta/Elev= 30
  4456.0 2210.55  4477.0 2209.81  4753.3 2207.98  4781.6 2208.34  4859.4 2207.30
  4886.1 2207.69  5014.0 2206.07  5028.1 2205.38  5028.4 2204.88  5032.1 2204.88
  5032.4 2205.38  5057.8 2206.44  5067.7 2207.65  5101.8 2209.74  5132.1 2210.94
  5155.8 2210.89  5264.5 2216.61  5286.2 2216.64  5345.5 2219.35  5426.5 2224.09
  5487.7 2228.80  5501.7 2229.71  5513.9 2229.22  5523.4 2231.12  5529.1 2230.81
  5536.8 2232.07  5617.1 2237.08  5640.1 2237.39  5662.8 2239.82  5668.4 2239.82
#Mann=6,-1,0
  4456.0   0.035       0  4886.1    0.07       0  5028.1    0.07       0
  5032.4    0.07       0  5132.1   0.035       0  5487.7    0.07       0
Bank Sta=5028.1,5032.4
Exp/Cntr=0.3,0.1

Type RM Length L Ch R = 1,3410,321,321,321
BEGIN DESCRIPTION:
Buffalo Creek Trib 07-01 5.99
END DESCRIPTION:
XS GIS Cut Line= 6
      1307686.37      6930227.96      1308215.29      6929749.74
      1308214.50      6929713.28      1308174.57      6929666.41
      1308108.59      6929629.95      1307819.25      6929294.36
#Sta/Elev= 30
  4226.4 2210.02  4246.8 2208.91  4562.7 2206.76  4658.5 2206.03  4662.6 2206.06
  4819.0 2205.17  4819.3 2204.67  4823.3 2205.17  4834.9 2205.25  4848.7 2208.06
  4862.9 2208.22  4870.5 2206.92  4877.2 2208.08  4883.9 2206.42  4892.5 2207.34
  4898.6 2206.13  4913.4 2207.16  4935.9 2206.31  4977.3 2207.27  4987.6 2206.19
  4995.3 2206.99  5001.8 2205.55  5009.6 2207.69  5016.1 2206.61  5045.1 2208.74
  5104.6 2207.30  5210.0 2209.75  5366.8 2214.42  5422.8 2217.78  5557.4 2222.72
#Mann=7,-1,0
  4226.4   0.035       0  4562.7    0.07       0  4658.5   0.035       0
  4662.6    0.07       0  4819.0   0.035       0  4823.3    0.07       0
  4935.9   0.035       0
Bank Sta=4819,4823.3
Exp/Cntr=0.3,0.1

Type RM Length L Ch R = 1,3089,373,373,373
BEGIN DESCRIPTION:
Buffalo Creek Trib 07-01 5.0
END DESCRIPTION:
XS GIS Cut Line= 4
      1308304.20      6930298.55      1308492.76      6929614.02
      1308395.06      6929388.30      1308050.84      6928862.89
#Sta/Elev= 30
  4166.0 2207.00  4220.3 2205.35  4345.4 2204.34  4621.0 2202.35  4839.5 2203.19
  4937.9 2202.94  4982.7 2200.21  4983.0 2199.71  4987.0 2200.21  5002.4 2200.23
  5008.4 2201.20  5064.1 2203.86  5187.0 2208.17  5310.7 2215.51  5397.3 2219.62
  5410.1 2218.80  5425.2 2220.60  5461.4 2227.36  5482.4 2229.34  5505.1 2232.91
  5512.6 2234.97  5518.6 2234.68  5527.7 2236.27  5569.9 2238.85  5591.0 2241.18
  5642.3 2243.54  5672.3 2245.77  5678.4 2247.39  5720.6 2249.62  5750.1 2249.88
#Mann=9,-1,0
  4166.0    0.07       0  4220.3   0.035       0  4345.4    0.07       0
  4621.0   0.035       0  4839.5    0.07       0  4982.7    0.07       0
  4987.0    0.07       0  5064.1   0.035       0  5505.1    0.07       0
Bank Sta=4982.7,4987
Exp/Cntr=0.3,0.1

Type RM Length L Ch R = 1,2716,433,433,433
BEGIN DESCRIPTION:
Buffalo Creek Trib 07-01 4.99
END DESCRIPTION:
XS GIS Cut Line= 3
      1308626.32      6930056.47      1308866.12      6929461.83
      1308434.74      6928952.67
#Sta/Elev= 30
  4196.7 2203.20  4216.6 2202.23  4281.3 2201.55  4302.9 2201.98  4464.6 2200.19
  4507.1 2200.55  4633.0 2200.48  4638.4 2199.81  4770.0 2199.00  4794.1 2199.77
  4862.7 2199.27  4905.0 2200.33  4947.1 2200.53  4975.8 2199.19  4987.9 2197.67
  4988.2 2197.17  4992.3 2197.67  5061.5 2201.71  5078.5 2201.74  5201.2 2206.73
  5209.9 2207.21  5238.4 2208.35  5266.9 2208.31  5274.7 2209.56  5324.1 2209.05
  5352.7 2212.95  5366.9 2212.99  5373.5 2214.26  5416.4 2214.94  5505.2 2219.90
#Mann=9,-1,0
  4196.7   0.035       0  4507.1    0.07       0  4905.0   0.035       0
  4947.1    0.07       0  4987.9    0.07       0  4992.3    0.07       0
  5078.5   0.035       0  5201.2    0.07       0  5209.9   0.035       0
Bank Sta=4987.9,4992.3
Exp/Cntr=0.3,0.1

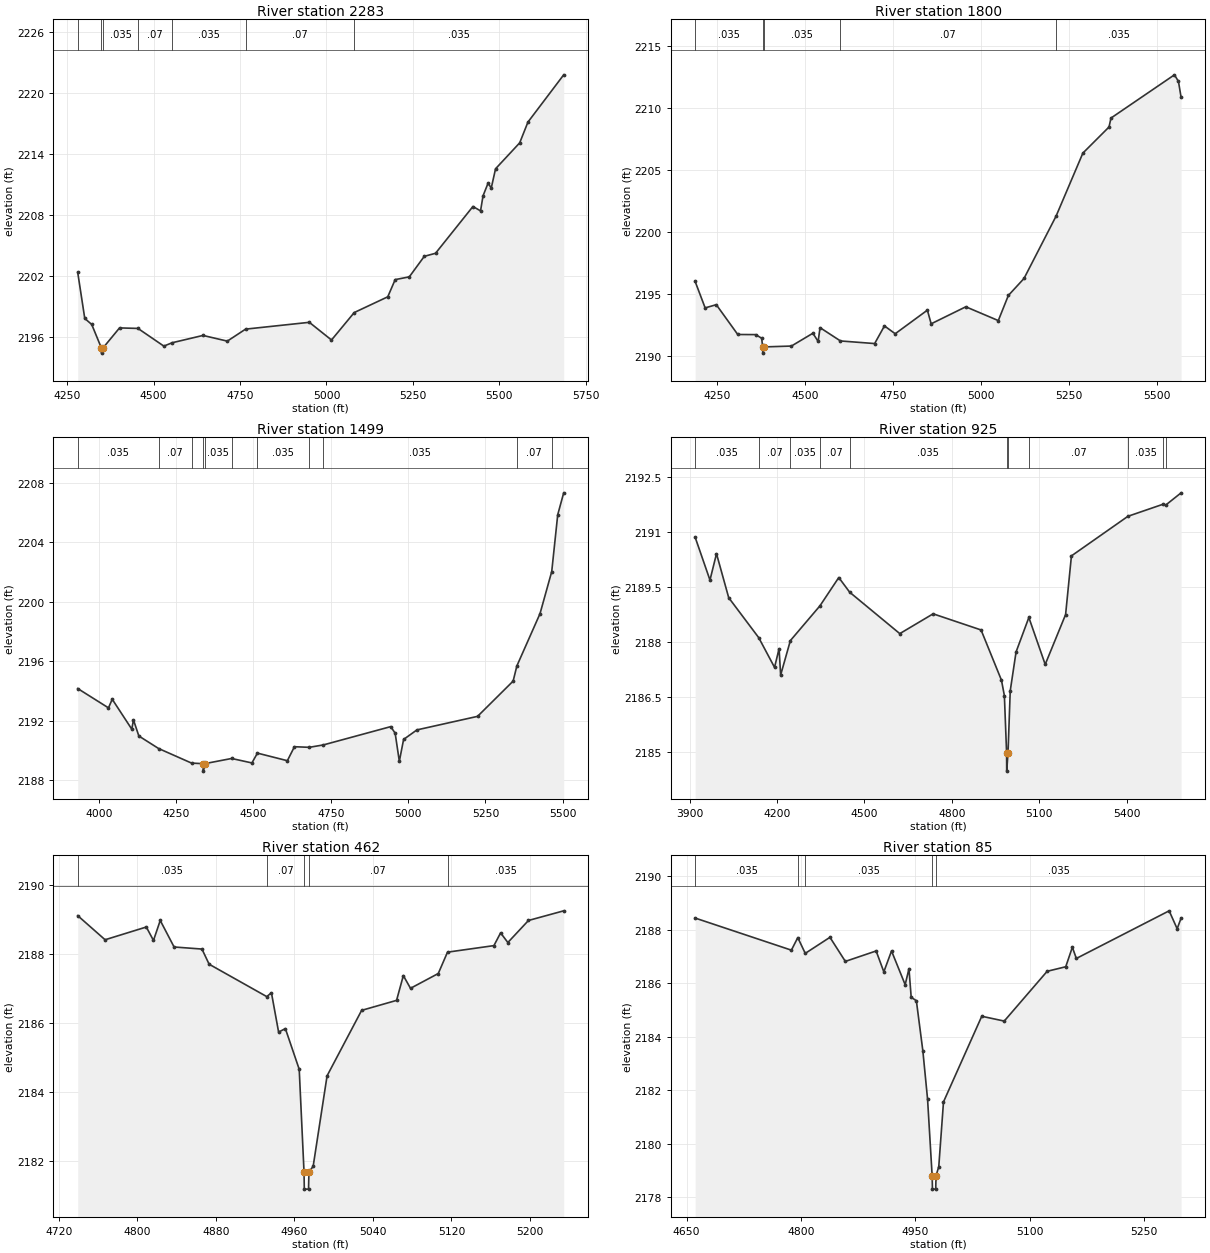
Type RM Length L Ch R = 1,2283,483,483,483
BEGIN DESCRIPTION:
Buffalo Creek Trib 07-01 4.0
END DESCRIPTION:
XS GIS Cut Line= 4
      1309195.31      6929758.31      1309130.00      6929113.00
      1308959.66      6928929.01      1308493.31      6928733.56
#Sta/Elev= 30
  4280.8 2202.37  4301.2 2197.84  4321.3 2197.25  4349.3 2194.93  4349.6 2194.43
  4353.7 2194.93  4401.7 2196.91  4455.0 2196.86  4529.8 2195.12  4553.7 2195.45
  4643.0 2196.17  4713.3 2195.61  4766.1 2196.79  4950.4 2197.46  5014.5 2195.72
  5080.2 2198.42  5177.2 2199.97  5198.6 2201.66  5239.4 2201.93  5282.8 2203.95
  5315.3 2204.25  5423.4 2208.85  5445.4 2208.42  5452.6 2209.90  5467.1 2211.14
  5476.4 2210.67  5488.8 2212.56  5558.6 2215.11  5582.4 2217.15  5685.8 2221.80
#Mann=7,-1,0
  4280.8   0.035       0  4349.3    0.07       0  4353.7   0.035       0
  4455.0    0.07       0  4553.7   0.035       0  4766.1    0.07       0
  5080.2   0.035       0
Bank Sta=4349.3,4353.7
Exp/Cntr=0.3,0.1

Type RM Length L Ch R = 1,1800,301,301,301
BEGIN DESCRIPTION:
Buffalo Creek Trib 07-01 3.0
END DESCRIPTION:
XS GIS Cut Line= 4
      1309333.86      6929517.09      1309468.12      6928819.79
      1309325.46      6928648.59      1308928.28      6928436.74
#Sta/Elev= 30
  4186.8 2196.04  4215.3 2193.91  4247.0 2194.17  4308.1 2191.77  4359.0 2191.76
  4376.1 2191.47  4379.0 2190.77  4379.3 2190.27  4383.4 2190.77  4460.8 2190.84
  4521.9 2191.87  4536.9 2191.21  4542.3 2192.32  4600.4 2191.25  4697.7 2191.04
  4725.6 2192.46  4756.2 2191.83  4847.8 2193.73  4858.5 2192.63  4957.1 2194.00
  5049.6 2192.89  5078.2 2194.91  5122.8 2196.28  5214.1 2201.30  5290.3 2206.37
  5364.7 2208.47  5370.3 2209.19  5550.9 2212.67  5562.3 2212.14  5569.9 2210.85
#Mann=5,-1,0
  4186.8   0.035       0  4379.0    0.07       0  4383.4   0.035       0
  4600.4    0.07       0  5214.1   0.035       0
Bank Sta=4379,4383.4
Exp/Cntr=0.3,0.1

Type RM Length L Ch R = 1,1499,574,574,574
BEGIN DESCRIPTION:
Buffalo Creek Trib 07-01 2.9
END DESCRIPTION:
XS GIS Cut Line= 4
      1309414.94      6929538.25      1309777.46      6928756.59
      1309542.39      6928466.38      1309209.13      6928420.61
#Sta/Elev= 30
  3931.6 2194.16  4031.1 2192.86  4043.2 2193.44  4106.4 2191.43  4111.9 2192.05
  4129.3 2190.97  4193.1 2190.13  4299.7 2189.15  4337.5 2189.11  4337.8 2188.61
  4341.9 2189.11  4429.3 2189.46  4494.9 2189.16  4512.7 2189.82  4609.5 2189.31
  4632.4 2190.25  4680.4 2190.21  4725.8 2190.37  4943.7 2191.60  4958.1 2191.16
  4971.6 2189.27  4985.4 2190.74  5028.5 2191.38  5224.6 2192.29  5339.6 2194.66
  5351.7 2195.68  5426.5 2199.19  5464.4 2202.02  5483.8 2205.84  5503.1 2207.31
#Mann=11,-1,0
  3931.6   0.035       0  4193.1    0.07       0  4299.7   0.035       0
  4337.5   0.035       0  4341.9   0.035       0  4429.3    0.07       0
  4512.7   0.035       0  4680.4    0.07       0  4725.8   0.035       0
  5351.7    0.07       0  5464.4   0.035       0
Bank Sta=4337.5,4341.9
Exp/Cntr=0.3,0.1

Type RM Length L Ch R = 1,925,463,463,463
BEGIN DESCRIPTION:
Buffalo Creek Trib 07-01 2.0
END DESCRIPTION:
XS GIS Cut Line= 3
      1309743.57      6929327.89      1310012.57      6928472.93
      1310028.17      6927701.67
#Sta/Elev= 30
  3919.2 2190.86  3970.1 2189.69  3992.5 2190.41  4034.4 2189.21  4137.4 2188.12
  4191.7 2187.31  4207.3 2187.82  4212.6 2187.10  4246.0 2188.04  4347.7 2188.99
  4412.1 2189.76  4449.5 2189.36  4621.5 2188.23  4735.9 2188.77  4900.4 2188.33
  4970.4 2186.96  4980.4 2186.54  4988.0 2184.98  4988.4 2184.48  4992.9 2184.98
  5000.5 2186.67  5020.5 2187.73  5064.4 2188.67  5120.5 2187.39  5190.5 2188.75
  5210.5 2190.35  5404.4 2191.43  5525.4 2191.76  5534.7 2191.74  5586.9 2192.07
#Mann=11,-1,0
  3919.2   0.035       0  4137.4    0.07       0  4246.0   0.035       0
  4347.7    0.07       0  4449.5   0.035       0  4988.0   0.035       0
  4992.9   0.035       0  5064.4    0.07       0  5404.4   0.035       0
  5525.4    0.07       0  5534.7   0.035       0
Bank Sta=4988,4992.9
Exp/Cntr=0.3,0.1

Type RM Length L Ch R = 1,462,377,377,377
BEGIN DESCRIPTION:
Buffalo Creek Trib 07-01 1.9
END DESCRIPTION:
XS GIS Cut Line= 2
      1309983.98      6928836.08      1310346.39      6928498.63
#Sta/Elev= 30
  4739.2 2189.11  4767.1 2188.41  4809.1 2188.78  4816.4 2188.39  4823.3 2188.97
  4837.4 2188.20  4865.8 2188.14  4873.1 2187.70  4931.8 2186.76  4936.6 2186.87
  4943.9 2185.73  4950.8 2185.83  4964.9 2184.65  4969.8 2181.67  4970.1 2181.17
  4974.4 2181.17  4974.8 2181.67  4979.1 2181.83  4993.3 2184.46  5028.5 2186.36
  5064.1 2186.65  5071.0 2187.37  5078.3 2187.00  5106.6 2187.43  5116.0 2188.05
  5163.3 2188.24  5170.1 2188.61  5177.5 2188.33  5198.5 2188.97  5234.4 2189.25
#Mann=5,-1,0
  4739.2   0.035       0  4931.8    0.07       0  4969.8    0.07       0
  4974.8    0.07       0  5116.0   0.035       0
Bank Sta=4969.8,4974.8
Exp/Cntr=0.3,0.1

Type RM Length L Ch R = 1,85,0,0,0
BEGIN DESCRIPTION:
Buffalo Creek Trib 07-01 1.0
END DESCRIPTION:
XS GIS Cut Line= 4
      1310079.98      6928913.00      1310361.10      6928953.84
      1310465.39      6928878.49      1310530.00      6928663.00
#Sta/Elev= 30
  4661.1 2188.43  4787.4 2187.23  4795.8 2187.70  4805.6 2187.11  4838.0 2187.71
  4858.2 2186.81  4898.6 2187.20  4908.7 2186.42  4918.8 2187.20  4936.7 2185.94
  4941.7 2186.54  4944.6 2185.47  4951.4 2185.34  4959.9 2183.47  4966.1 2181.66
  4972.1 2178.80  4972.5 2178.30  4976.8 2178.30  4977.2 2178.80  4980.8 2179.14
  4987.0 2181.56  5037.2 2184.76  5066.7 2184.58  5123.0 2186.44  5147.4 2186.61
  5156.1 2187.34  5161.3 2186.92  5283.1 2188.70  5293.6 2188.03  5298.8 2188.43
#Mann=5,-1,0
  4661.1   0.035       0  4795.8    0.07       0  4805.6   0.035       0
  4972.1   0.035       0  4977.2   0.035       0
Bank Sta=4972.1,4977.2
Exp/Cntr=0.3,0.1

Chan Stop Cuts=-1