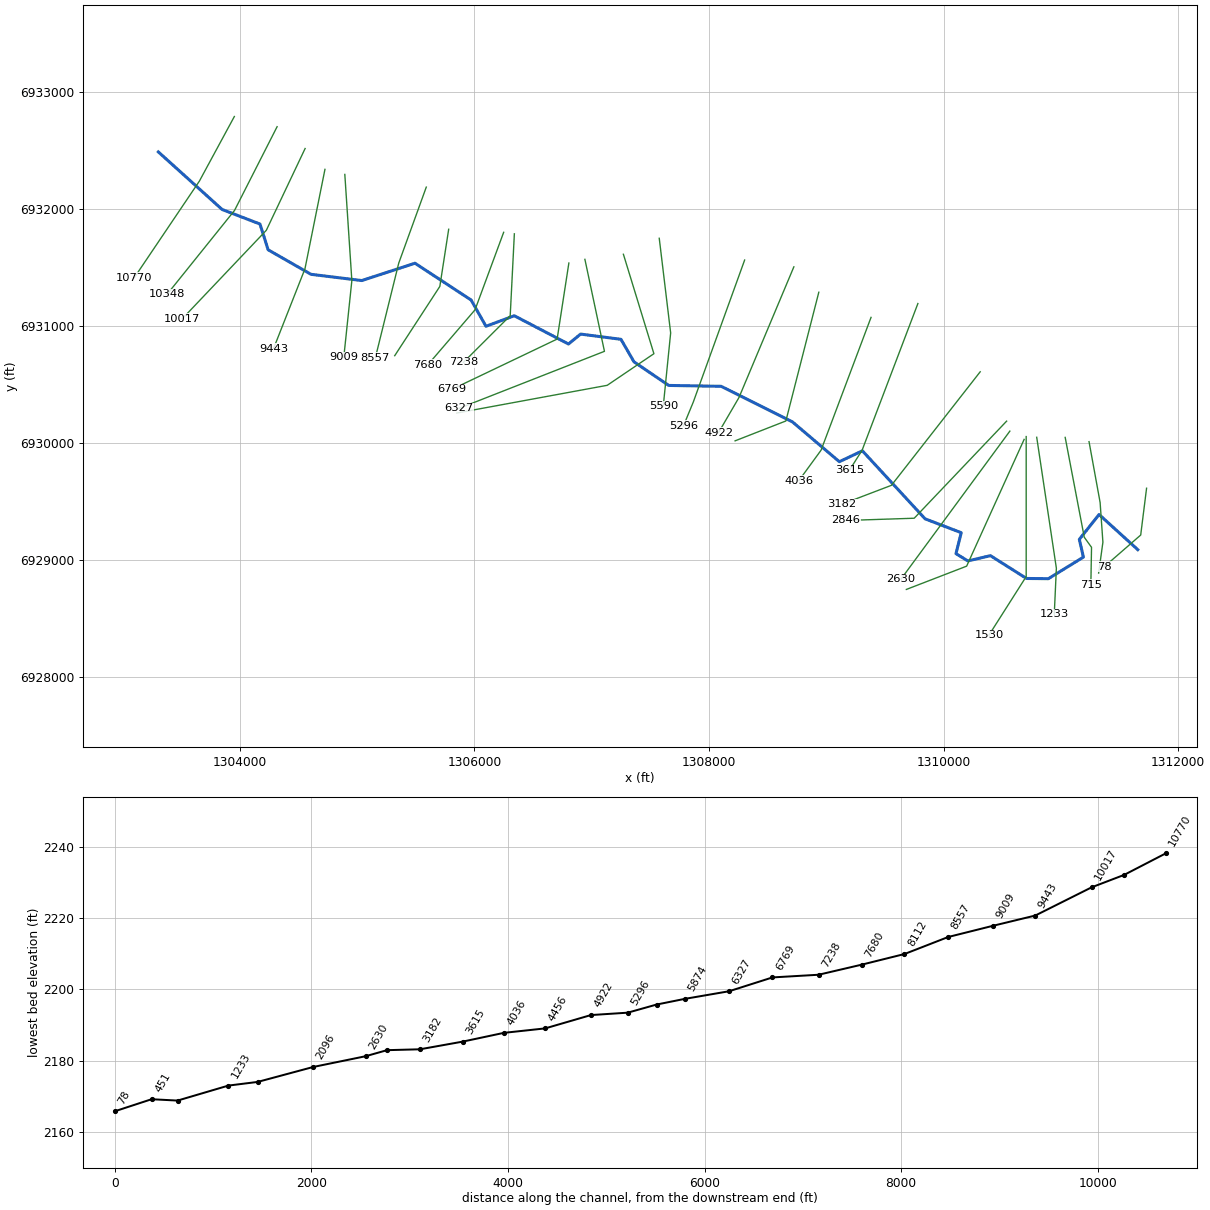
--- Buffalo Creek Trib 07.prj (project) ---

Proj Title=Buffalo Creek Trib 07 Base Level Engineering
Current Plan=p01
Default Exp/Contr=0.3,0.1
English Units
Geom File=g01
Flow File=f01
Plan File=p01
BEGIN DESCRIPTION:
Buffalo Creek Trib 07
END DESCRIPTION:

--- Buffalo Creek Trib 07.p01 (plan) ---

Plan Title=Multiple Run
Short Identifier=Multiple
Geom File=g01
Flow File=f01
Subcritical Flow
K Sum by GR= 0
Std Step Tol= 0.01
Critical Tol= 0.01
Num of Std Step Trials= 20
Max Error Tol= 0.3
Flow Tol Ratio= 0.001
Split Flow NTrial= 30
Split Flow Tol= 0.02
Split Flow Ratio= 0.02
Log Output Level= 0
Friction Slope Method= 1
Unsteady Friction Slope Method= 2
Unsteady Bridges Friction Slope Method= 1
Parabolic Critical Depth
Global Vel Dist=  1 , 1 , 1
Global Log Level= 0
CheckData=True
Encroach Param= -1, 0, 0, 0
BEGIN DESCRIPTION:
Multiple Run
END DESCRIPTION:

--- Buffalo Creek Trib 07.f01 (steady flow) ---

Flow Title=Multiple
Number of Profiles=7
Profile Names=10-year,25-year,50-year,1pct_min,100-year,1pct_plu,500-year
River Rch & RM= Buffalo Creek Tr,Reach-1,10770
     437     638     813     515    1027    2049    1661
River Rch & RM= Buffalo Creek Tr,Reach-1,1530
     717    1072    1387     890    1776    3544    2953
Boundary for River Rch & Prof#=Buffalo Creek Tr,Reach-1,1
Up Type=0
Dn Type=3
Dn Slope=0.005
Boundary for River Rch & Prof#=Buffalo Creek Tr,Reach-1,2
Up Type=0
Dn Type=3
Dn Slope=0.005
Boundary for River Rch & Prof#=Buffalo Creek Tr,Reach-1,3
Up Type=0
Dn Type=3
Dn Slope=0.005
Boundary for River Rch & Prof#=Buffalo Creek Tr,Reach-1,4
Up Type=0
Dn Type=3
Dn Slope=0.005
Boundary for River Rch & Prof#=Buffalo Creek Tr,Reach-1,5
Up Type=0
Dn Type=3
Dn Slope=0.005
Boundary for River Rch & Prof#=Buffalo Creek Tr,Reach-1,6
Up Type=0
Dn Type=3
Dn Slope=0.005
Boundary for River Rch & Prof#=Buffalo Creek Tr,Reach-1,7
Up Type=0
Dn Type=3
Dn Slope=0.005

--- Buffalo Creek Trib 07.g01 (geometry) ---

Geom Title=Existing Conditions

River Reach=Buffalo Creek Tr,Reach-1
Reach XY= 30
      1303305.00      6932488.00      1303848.83      6931995.86
      1304171.75      6931871.36      1304241.21      6931651.26
      1304606.47      6931441.55      1305039.78      6931388.25
      1305493.17      6931536.39      1305972.14      6931221.54
      1306098.40      6930997.22      1306339.78      6931087.51
      1306801.77      6930845.85      1306904.90      6930930.66
      1307249.16      6930885.95      1307360.26      6930693.47
      1307656.55      6930491.75      1308103.45      6930484.25
      1308711.34      6930179.98      1309111.12      6929839.76
      1309307.30      6929932.94      1309841.79      6929351.63
      1310150.07      6929232.96      1310105.23      6929054.00
      1310206.55      6928991.66      1310398.96      6929036.72
      1310706.55      6928841.75      1310893.05      6928839.92
      1311191.64      6929024.20      1311156.81      6929176.00
      1311325.06      6929388.52      1311655.00      6929088.00

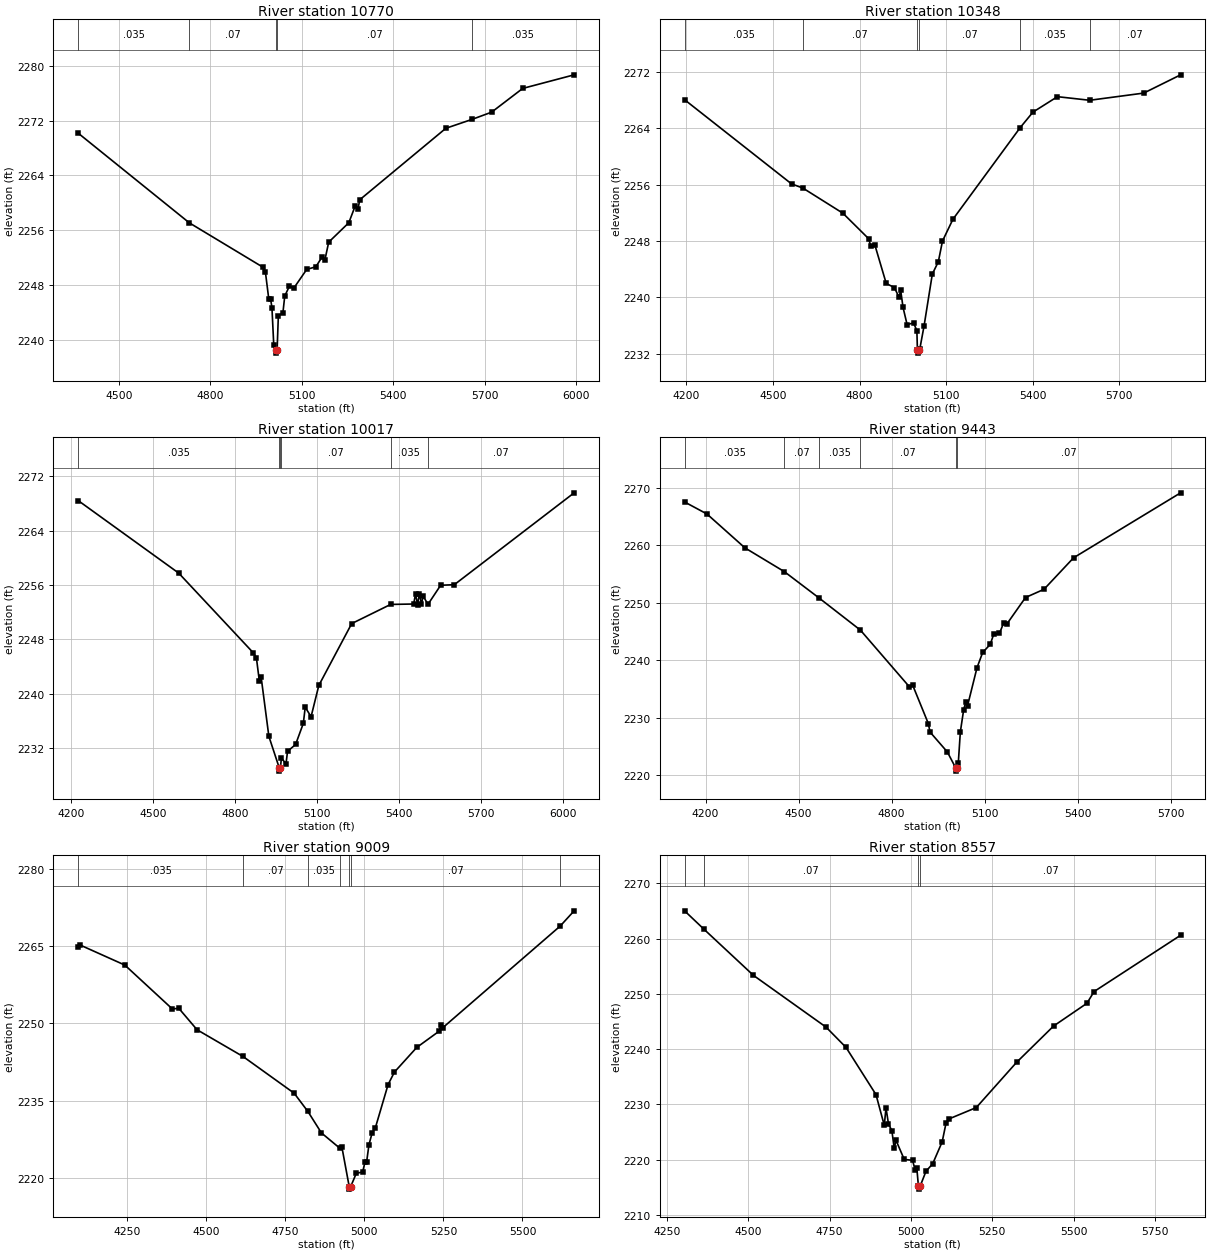
Type RM Length L Ch R = 1,10770,422,422,422
BEGIN DESCRIPTION:
Buffalo Creek Trib 07 20.0
END DESCRIPTION:
XS GIS Cut Line= 3
      1303953.23      6932790.29      1303655.00      6932238.00
      1303098.14      6931410.00
#Sta/Elev= 30
  4366.9 2270.17  4731.5 2257.09  4971.8 2250.65  4980.8 2249.88  4991.7 2246.02
  4997.6 2246.02  5002.1 2244.75  5008.1 2239.25  5014.9 2238.61  5015.2 2238.11
  5019.1 2238.61  5023.1 2243.53  5038.1 2244.00  5044.1 2246.43  5059.1 2247.84
  5074.1 2247.60  5116.1 2250.31  5146.0 2250.69  5167.1 2252.17  5175.3 2251.62
  5188.1 2254.28  5254.0 2257.11  5275.0 2259.56  5283.8 2259.08  5290.0 2260.46
  5572.0 2270.87  5658.5 2272.18  5722.0 2273.22  5823.9 2276.68  5992.4 2278.66
#Mann=5,-1,0
  4366.9   0.035       0  4731.5    0.07       0  5014.9    0.07       0
  5019.1    0.07       0  5658.5   0.035       0
Bank Sta=5014.9,5019.1
Exp/Cntr=0.3,0.1

Type RM Length L Ch R = 1,10348,331,331,331
BEGIN DESCRIPTION:
Buffalo Creek Trib 07 19.0
END DESCRIPTION:
XS GIS Cut Line= 3
      1304317.80      6932703.47      1303955.00      6931988.00
      1303381.03      6931272.08
#Sta/Elev= 30
  4193.4 2268.04  4564.2 2256.10  4603.4 2255.51  4742.3 2251.94  4831.4 2248.33
  4838.6 2247.34  4853.7 2247.36  4892.6 2241.97  4920.5 2241.40  4937.1 2240.02
  4942.7 2240.99  4950.8 2238.59  4965.0 2236.13  4987.3 2236.38  4998.8 2235.28
  5000.7 2232.59  5001.0 2232.09  5005.0 2232.59  5009.2 2232.73  5023.6 2235.91
  5052.4 2243.31  5073.2 2245.05  5087.6 2247.99  5123.8 2251.08  5357.2 2264.09
  5401.3 2266.28  5486.1 2268.47  5598.0 2267.96  5785.4 2268.98  5913.2 2271.57
#Mann=6,-1,0
  4193.4   0.035       0  4603.4    0.07       0  5000.7    0.07       0
  5005.0    0.07       0  5357.2   0.035       0  5598.0    0.07       0
Bank Sta=5000.7,5005
Exp/Cntr=0.3,0.1

Type RM Length L Ch R = 1,10017,574,574,574
BEGIN DESCRIPTION:
Buffalo Creek Trib 07 18.0
END DESCRIPTION:
XS GIS Cut Line= 3
      1304556.52      6932516.85      1304225.97      6931818.09
      1303510.60      6931062.93
#Sta/Elev= 30
  4227.0 2268.42  4594.7 2257.74  4867.4 2246.01  4878.8 2245.26  4889.5 2241.87
  4896.0 2242.45  4924.3 2233.72  4962.1 2229.10  4962.4 2228.60  4966.5 2229.10
  4970.2 2230.51  4987.0 2229.69  4992.6 2231.51  5022.0 2232.52  5050.3 2235.63
  5057.2 2238.00  5078.6 2236.61  5106.9 2241.21  5227.1 2250.31  5369.5 2253.13
  5453.6 2253.19  5460.5 2254.67  5467.8 2253.09  5474.7 2254.71  5481.9 2253.23
  5488.8 2254.32  5505.9 2253.14  5552.3 2255.95  5602.1 2256.03  6040.2 2269.55
#Mann=6,-1,0
  4227.0   0.035       0  4962.1    0.07       0  4966.5   0.035       0
  4970.2    0.07       0  5369.5   0.035       0  5505.9    0.07       0
Bank Sta=4962.1,4966.5
Exp/Cntr=0.3,0.1

Type RM Length L Ch R = 1,9443,434,434,434
BEGIN DESCRIPTION:
Buffalo Creek Trib 07 17.0
END DESCRIPTION:
XS GIS Cut Line= 3
      1304725.78      6932338.90      1304555.00      6931488.00
      1304287.40      6930806.74
#Sta/Elev= 30
  4132.1 2267.58  4204.4 2265.48  4326.8 2259.58  4454.1 2255.43  4565.3 2250.87
  4699.2 2245.25  4857.2 2235.37  4867.4 2235.71  4918.4 2228.95  4923.6 2227.50
  4979.6 2224.02  5007.1 2221.18  5007.5 2220.68  5011.8 2221.18  5014.9 2222.07
  5021.5 2227.51  5032.2 2231.37  5039.3 2232.79  5044.7 2232.06  5075.2 2238.69
  5093.5 2241.35  5117.9 2242.76  5128.9 2244.50  5147.7 2244.68  5161.1 2246.50
  5171.9 2246.34  5231.7 2250.93  5291.3 2252.36  5386.7 2257.85  5731.9 2269.17
#Mann=6,-1,0
  4132.1   0.035       0  4454.1    0.07       0  4565.3   0.035       0
  4699.2    0.07       0  5007.1    0.07       0  5011.8    0.07       0
Bank Sta=5007.1,5011.8
Exp/Cntr=0.3,0.1

Type RM Length L Ch R = 1,9009,452,452,452
BEGIN DESCRIPTION:
Buffalo Creek Trib 07 16.0
END DESCRIPTION:
XS GIS Cut Line= 3
      1304895.04      6932295.50      1304955.00      6931388.00
      1304886.36      6930732.97
#Sta/Elev= 30
  4095.2 2264.81  4102.7 2265.21  4243.0 2261.34  4393.3 2252.80  4413.4 2252.95
  4471.2 2248.77  4616.5 2243.57  4778.2 2236.43  4821.6 2232.88  4864.4 2228.71
  4921.7 2225.78  4929.2 2225.93  4952.2 2218.28  4952.5 2217.78  4957.0 2218.28
  4974.6 2220.85  4994.7 2221.12  5002.2 2223.04  5007.2 2223.04  5014.7 2226.42
  5024.8 2228.73  5034.8 2229.68  5075.1 2238.10  5095.2 2240.54  5165.6 2245.32
  5235.9 2248.46  5242.8 2249.76  5247.8 2249.15  5619.1 2268.92  5663.3 2271.89
#Mann=7,-1,0
  4095.2   0.035       0  4616.5    0.07       0  4821.6   0.035       0
  4921.7    0.07       0  4952.2    0.07       0  4957.0    0.07       0
  5619.1   0.035       0
Bank Sta=4952.2,4957
Exp/Cntr=0.3,0.1

Type RM Length L Ch R = 1,8557,445,445,445
BEGIN DESCRIPTION:
Buffalo Creek Trib 07 15.0
END DESCRIPTION:
XS GIS Cut Line= 3
      1305589.49      6932186.97      1305355.00      6931538.00
      1305155.47      6930728.66
#Sta/Elev= 30
  4304.6 2265.02  4364.2 2261.69  4516.2 2253.34  4739.3 2243.97  4800.6 2240.30
  4892.6 2231.76  4918.0 2226.20  4923.3 2229.36  4930.8 2226.52  4941.5 2225.17
  4948.6 2222.02  4954.0 2223.50  4979.3 2220.04  5004.9 2219.87  5012.8 2218.11
  5017.9 2218.49  5023.0 2215.16  5023.4 2214.66  5028.0 2215.16  5046.1 2217.89
  5066.7 2219.25  5095.8 2223.21  5107.9 2226.66  5118.2 2227.40  5200.6 2229.42
  5324.2 2237.59  5438.0 2244.17  5540.5 2248.29  5562.4 2250.41  5828.2 2260.60
#Mann=4,-1,0
  4304.6   0.035       0  4364.2    0.07       0  5023.0    0.07       0
  5028.0    0.07       0
Bank Sta=5023,5028
Exp/Cntr=0.3,0.1

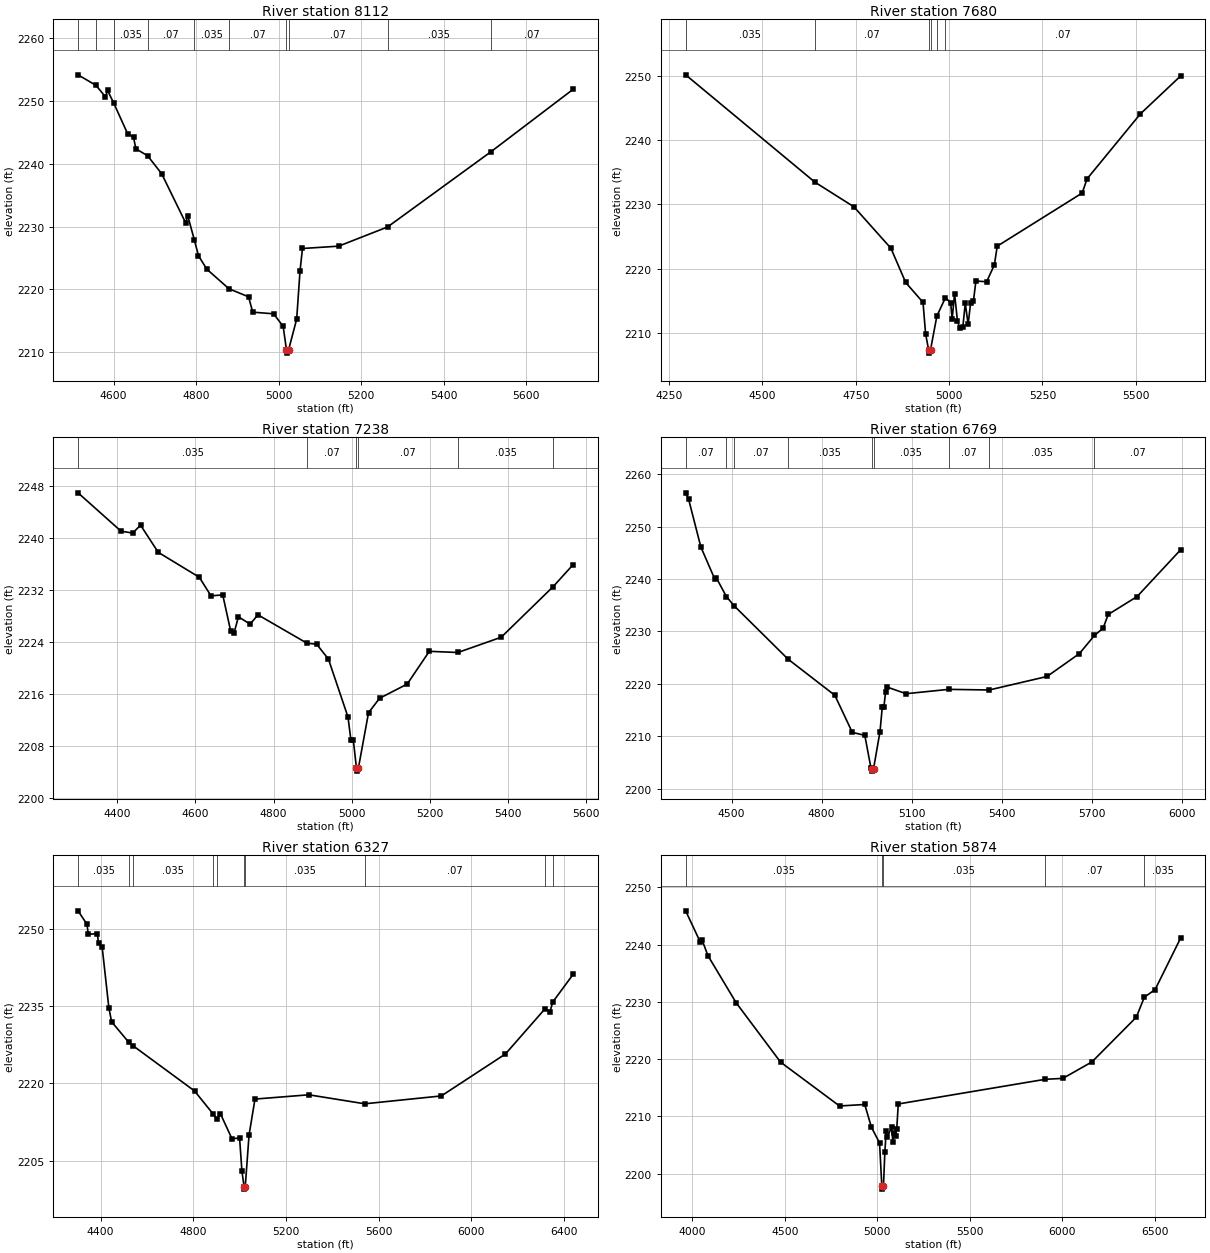
Type RM Length L Ch R = 1,8112,432,432,432
BEGIN DESCRIPTION:
Buffalo Creek Trib 07 14.0
END DESCRIPTION:
XS GIS Cut Line= 3
      1305780.45      6931826.67      1305705.00      6931338.00
      1305320.42      6930746.02
#Sta/Elev= 30
  4513.6 2254.11  4557.0 2252.44  4580.1 2250.62  4585.1 2251.63  4600.1 2249.63
  4633.7 2244.77  4648.2 2244.16  4653.9 2242.35  4682.3 2241.25  4716.4 2238.39
  4774.5 2230.59  4779.6 2231.72  4796.0 2227.78  4805.7 2225.35  4825.9 2223.22
  4879.5 2220.11  4927.1 2218.83  4937.2 2216.39  4987.8 2216.13  5011.0 2214.14
  5019.1 2210.38  5019.5 2209.88  5024.1 2210.38  5043.8 2215.29  5051.9 2222.94
  5057.8 2226.51  5145.5 2226.88  5264.2 2229.93  5515.4 2241.91  5714.0 2251.80
#Mann=10,-1,0
  4513.6   0.035       0  4557.0    0.07       0  4600.1   0.035       0
  4682.3    0.07       0  4796.0   0.035       0  4879.5    0.07       0
  5019.1    0.07       0  5024.1    0.07       0  5264.2   0.035       0
  5515.4    0.07       0
Bank Sta=5019.1,5024.1
Exp/Cntr=0.3,0.1

Type RM Length L Ch R = 1,7680,442,442,442
BEGIN DESCRIPTION:
Buffalo Creek Trib 07 13.0
END DESCRIPTION:
XS GIS Cut Line= 3
      1306249.20      6931800.65      1306005.00      6931138.00
      1305602.52      6930667.86
#Sta/Elev= 30
  4294.8 2250.13  4640.9 2233.46  4745.2 2229.64  4844.2 2223.21  4883.8 2217.89
  4930.2 2214.80  4937.1 2209.93  4945.2 2207.42  4945.6 2206.92  4950.3 2207.42
  4967.3 2212.68  4990.3 2215.53  5004.3 2214.75  5008.1 2212.18  5014.7 2216.14
  5022.4 2211.91  5029.0 2210.76  5036.7 2210.93  5043.3 2214.67  5051.0 2211.39
  5057.5 2214.67  5065.2 2215.02  5071.8 2218.12  5100.4 2218.00  5121.2 2220.62
  5128.9 2223.53  5356.1 2231.77  5369.6 2234.00  5512.0 2244.06  5619.9 2249.96
#Mann=6,-1,0
  4294.8   0.035       0  4640.9    0.07       0  4945.2    0.07       0
  4950.3    0.07       0  4967.3   0.035       0  4990.3    0.07       0
Bank Sta=4945.2,4950.3
Exp/Cntr=0.3,0.1

Type RM Length L Ch R = 1,7238,469,469,469
BEGIN DESCRIPTION:
Buffalo Creek Trib 07 12.0
END DESCRIPTION:
XS GIS Cut Line= 3
      1306340.36      6931787.66      1306305.00      6931088.00
      1305905.03      6930688.03
#Sta/Elev= 30
  4299.9 2246.93  4409.7 2241.03  4439.7 2240.73  4459.8 2241.95  4505.0 2237.77
  4610.0 2233.93  4640.0 2231.06  4670.0 2231.21  4690.1 2225.71  4699.2 2225.39
  4710.1 2227.84  4740.1 2226.71  4760.1 2228.14  4885.5 2223.77  4910.3 2223.62
  4940.4 2221.32  4990.4 2212.40  4997.9 2208.85  5004.0 2208.85  5012.0 2204.57
  5012.4 2204.07  5017.1 2204.57  5042.9 2213.06  5071.2 2215.29  5141.9 2217.48
  5198.4 2222.52  5271.5 2222.34  5382.3 2224.69  5515.3 2232.49  5566.1 2235.86
#Mann=6,-1,0
  4299.9   0.035       0  4885.5    0.07       0  5012.0    0.07       0
  5017.1    0.07       0  5271.5   0.035       0  5515.3    0.07       0
Bank Sta=5012,5017.1
Exp/Cntr=0.3,0.1

Type RM Length L Ch R = 1,6769,442,442,442
BEGIN DESCRIPTION:
Buffalo Creek Trib 07 11.0
END DESCRIPTION:
XS GIS Cut Line= 3
      1306805.00      6931538.00      1306705.00      6930888.00
      1305810.81      6930459.51
#Sta/Elev= 30
  4346.8 2256.45  4356.9 2255.18  4397.4 2246.12  4444.2 2239.93  4449.2 2240.20
  4482.6 2236.64  4508.0 2234.90  4688.3 2224.68  4843.8 2217.80  4902.0 2210.72
  4943.7 2210.15  4964.0 2203.96  4967.7 2203.82  4968.1 2203.32  4972.9 2203.82
  4994.3 2210.86  5001.9 2215.55  5007.2 2215.55  5013.0 2218.46  5018.5 2219.36
  5081.0 2218.10  5223.2 2218.93  5358.1 2218.81  5550.8 2221.39  5658.5 2225.75
  5708.9 2229.23  5737.6 2230.61  5754.7 2233.23  5850.9 2236.65  5996.0 2245.58
#Mann=9,-1,0
  4346.8    0.07       0  4482.6   0.035       0  4508.0    0.07       0
  4688.3   0.035       0  4967.7   0.035       0  4972.9   0.035       0
  5223.2    0.07       0  5358.1   0.035       0  5708.9    0.07       0
Bank Sta=4967.7,4972.9
Exp/Cntr=0.3,0.1

Type RM Length L Ch R = 1,6327,453,453,453
BEGIN DESCRIPTION:
Buffalo Creek Trib 07 10.0
END DESCRIPTION:
XS GIS Cut Line= 3
      1306941.72      6931569.73      1307108.37      6930783.30
      1305869.00      6930295.80
#Sta/Elev= 30
  4303.1 2253.58  4341.9 2250.95  4347.0 2249.02  4386.4 2249.13  4391.5 2247.25
  4407.1 2246.55  4436.1 2234.69  4448.0 2231.99  4522.3 2227.99  4542.3 2227.27
  4805.7 2218.54  4886.1 2214.05  4902.0 2213.03  4917.5 2214.10  4967.2 2209.24
  5000.0 2209.39  5010.2 2202.92  5019.3 2199.94  5019.7 2199.44  5024.5 2199.94
  5040.9 2209.97  5066.5 2216.96  5298.9 2217.79  5540.0 2216.04  5870.5 2217.57
  6146.8 2225.72  6318.6 2234.56  6339.1 2233.94  6351.4 2235.85  6438.8 2241.20
#Mann=10,-1,0
  4303.1   0.035       0  4522.3    0.07       0  4542.3   0.035       0
  4886.1    0.07       0  4902.0   0.035       0  5019.3   0.035       0
  5024.5   0.035       0  5540.0    0.07       0  6318.6   0.035       0
  6351.4    0.07       0
Bank Sta=5019.3,5024.5
Exp/Cntr=0.3,0.1

Type RM Length L Ch R = 1,5874,284,284,284
BEGIN DESCRIPTION:
Buffalo Creek Trib 07 9.9
END DESCRIPTION:
XS GIS Cut Line= 4
      1307269.96      6931613.03      1307530.00      6930763.00
      1307131.95      6930492.83      1305849.26      6930255.80
#Sta/Elev= 30
  3964.7 2245.89  4043.2 2240.47  4053.6 2240.79  4085.0 2238.07  4237.5 2229.84
  4477.4 2219.47  4796.1 2211.81  4932.2 2212.07  4968.4 2208.10  5012.3 2205.36
  5024.6 2197.79  5025.1 2197.29  5029.9 2197.79  5033.3 2197.80  5040.9 2203.73
  5048.2 2207.49  5054.3 2206.33  5077.2 2208.12  5084.2 2205.57  5090.2 2207.13
  5099.1 2206.57  5105.2 2207.84  5113.5 2212.16  5907.4 2216.47  6002.8 2216.63
  6159.8 2219.51  6399.4 2227.31  6442.7 2230.80  6501.1 2232.14  6639.1 2241.15
#Mann=5,-1,0
  3964.7   0.035       0  5024.6   0.035       0  5029.9   0.035       0
  5907.4    0.07       0  6442.7   0.035       0
Bank Sta=5024.6,5029.9
Exp/Cntr=0.3,0.1

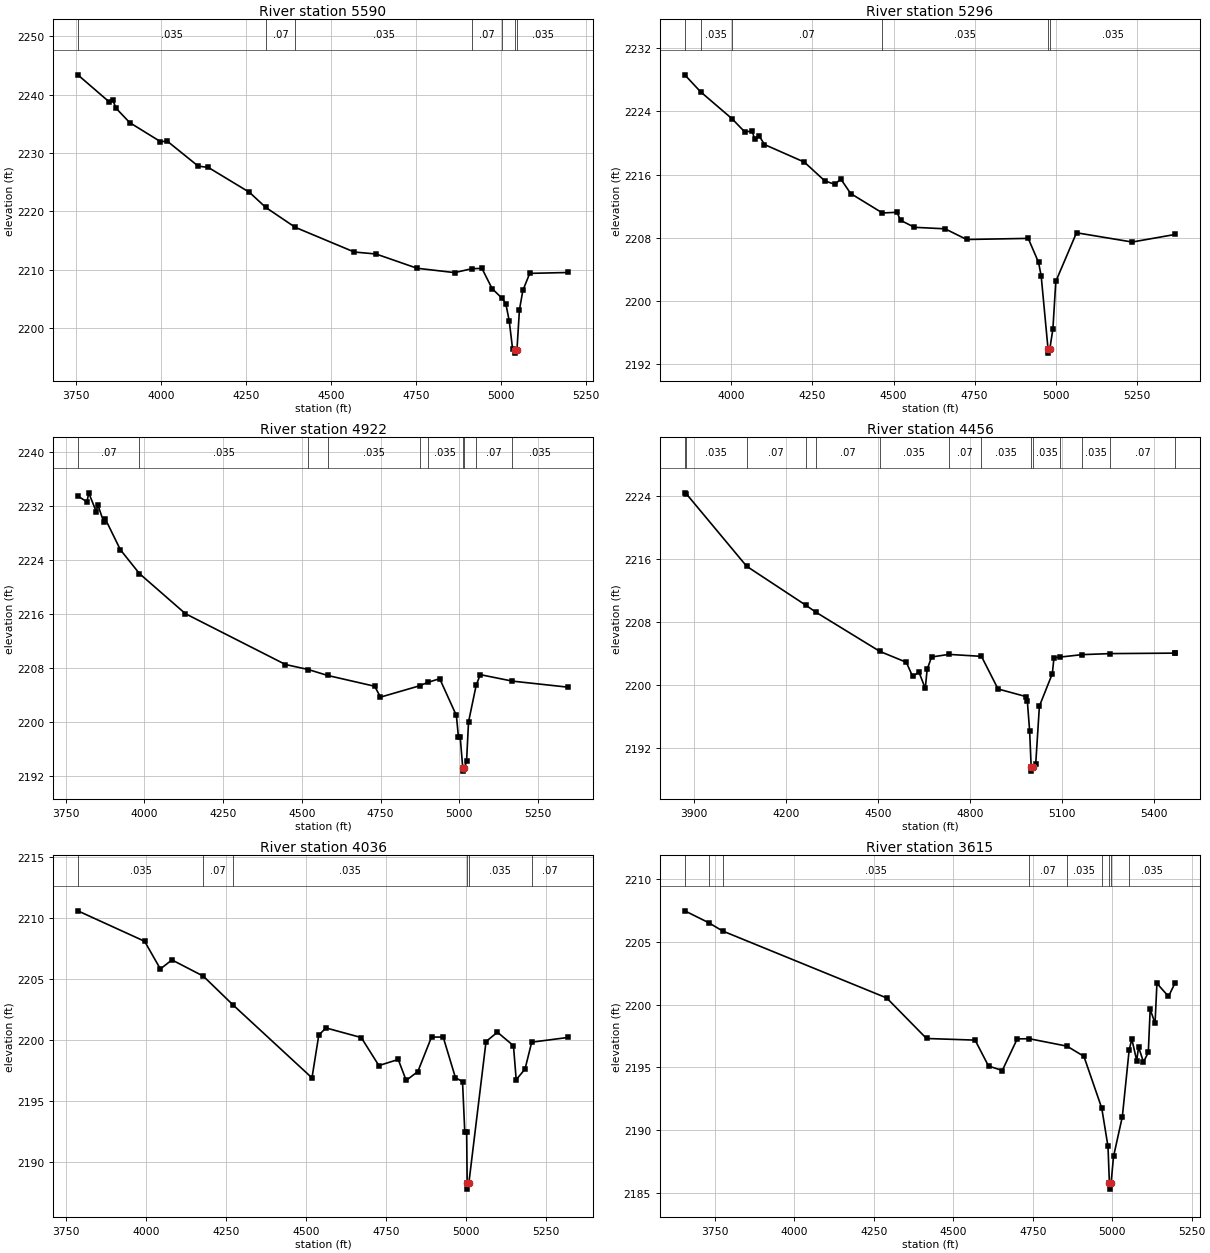
Type RM Length L Ch R = 1,5590,294,294,294
BEGIN DESCRIPTION:
Buffalo Creek Trib 07 9.0
END DESCRIPTION:
XS GIS Cut Line= 3
      1307575.57      6931749.58      1307672.78      6930940.59
      1307609.83      6930315.06
#Sta/Elev= 30
  3755.5 2243.41  3847.7 2238.78  3857.8 2239.18  3867.9 2237.69  3908.2 2235.22
  3998.8 2231.96  4019.0 2232.03  4109.6 2227.77  4139.8 2227.53  4260.7 2223.27
  4308.5 2220.69  4395.5 2217.27  4569.1 2213.04  4633.2 2212.70  4753.8 2210.26
  4864.4 2209.51  4914.5 2210.17  4944.8 2210.24  4974.9 2206.76  5004.7 2205.08
  5015.1 2204.20  5025.2 2201.24  5035.2 2196.37  5042.6 2196.21  5043.0 2195.71
  5047.9 2196.21  5055.3 2203.16  5065.4 2206.46  5085.5 2209.38  5199.0 2209.53
#Mann=7,-1,0
  3755.5   0.035       0  4308.5    0.07       0  4395.5   0.035       0
  4914.5    0.07       0  5004.7   0.035       0  5042.6    0.07       0
  5047.9   0.035       0
Bank Sta=5042.6,5047.9
Exp/Cntr=0.3,0.1

Type RM Length L Ch R = 1,5296,374,374,374
BEGIN DESCRIPTION:
Buffalo Creek Trib 07 8.0
END DESCRIPTION:
XS GIS Cut Line= 3
      1308303.51      6931563.51      1307865.59      6930349.11
      1307781.65      6930145.37
#Sta/Elev= 30
  3856.7 2228.60  3905.3 2226.46  4002.6 2223.04  4040.9 2221.41  4064.5 2221.47
  4071.6 2220.54  4085.8 2220.90  4102.3 2219.79  4225.1 2217.57  4287.8 2215.21
  4319.7 2214.75  4337.2 2215.45  4367.9 2213.60  4465.8 2211.14  4510.6 2211.23
  4521.6 2210.22  4564.2 2209.33  4658.8 2209.14  4725.4 2207.79  4915.0 2207.93
  4946.9 2204.89  4955.0 2203.16  4976.1 2193.93  4976.5 2193.43  4981.4 2193.93
  4991.0 2196.47  5000.0 2202.49  5063.8 2208.64  5235.4 2207.47  5368.0 2208.43
#Mann=6,-1,0
  3856.7    0.07       0  3905.3   0.035       0  4002.6    0.07       0
  4465.8   0.035       0  4976.1   0.035       0  4981.4   0.035       0
Bank Sta=4976.1,4981.4
Exp/Cntr=0.3,0.1

Type RM Length L Ch R = 1,4922,466,466,466
BEGIN DESCRIPTION:
Buffalo Creek Trib 07 7.0
END DESCRIPTION:
XS GIS Cut Line= 3
      1308723.16      6931505.50      1308255.00      6930388.00
      1308080.95      6930088.73
#Sta/Elev= 30
  3788.4 2233.51  3817.6 2232.64  3823.0 2233.98  3846.8 2231.21  3852.2 2232.16
  3870.6 2229.68  3876.0 2230.08  3923.6 2225.55  3984.1 2222.02  4130.1 2216.08
  4448.0 2208.55  4520.2 2207.81  4582.0 2206.93  4731.3 2205.33  4749.7 2203.72
  4874.0 2205.40  4899.7 2205.90  4937.8 2206.45  4990.8 2201.00  4997.3 2197.83
  5002.9 2197.83  5011.0 2193.26  5011.4 2192.76  5016.3 2193.26  5023.1 2194.19
  5029.4 2200.05  5053.7 2205.48  5066.6 2207.05  5168.8 2206.09  5346.2 2205.19
#Mann=10,-1,0
  3788.4    0.07       0  3984.1   0.035       0  4520.2    0.07       0
  4582.0   0.035       0  4874.0    0.07       0  4899.7   0.035       0
  5011.0   0.035       0  5016.3   0.035       0  5053.7    0.07       0
  5168.8   0.035       0
Bank Sta=5011,5016.3
Exp/Cntr=0.3,0.1

Type RM Length L Ch R = 1,4456,420,420,420
BEGIN DESCRIPTION:
Buffalo Creek Trib 07 6.0
END DESCRIPTION:
XS GIS Cut Line= 3
      1308935.84      6931288.51      1308655.00      6930188.00
      1308222.29      6930018.24
#Sta/Elev= 30
  3868.9 2224.35  3873.4 2224.25  4070.8 2215.03  4264.4 2210.07  4295.9 2209.22
  4505.5 2204.22  4591.9 2202.84  4612.5 2201.04  4633.1 2201.59  4653.8 2199.52
  4659.9 2201.94  4674.4 2203.51  4730.9 2203.84  4837.1 2203.59  4891.2 2199.45
  4981.7 2198.49  4986.8 2197.96  4994.4 2194.07  4999.4 2189.52  4999.8 2189.02
  5004.7 2189.52  5014.2 2189.93  5026.2 2197.27  5068.4 2201.39  5073.8 2203.43
  5094.0 2203.50  5166.0 2203.81  5257.6 2203.94  5468.3 2204.00  5469.5 2204.00
#Mann=14,-1,0
  3868.9    0.07       0  3873.4   0.035       0  4070.8    0.07       0
  4264.4   0.035       0  4295.9    0.07       0  4505.5   0.035       0
  4730.9    0.07       0  4837.1   0.035       0  4999.4   0.035       0
  5004.7   0.035       0  5094.0    0.07       0  5166.0   0.035       0
  5257.6    0.07       0  5468.3   0.035       0
Bank Sta=4999.4,5004.7
Exp/Cntr=0.3,0.1

Type RM Length L Ch R = 1,4036,421,421,421
BEGIN DESCRIPTION:
Buffalo Creek Trib 07 5.0
END DESCRIPTION:
XS GIS Cut Line= 3
      1309381.09      6931073.59      1308955.00      6929938.00
      1308766.06      6929678.61
#Sta/Elev= 30
  3787.1 2210.61  3996.0 2208.11  4045.2 2205.84  4081.5 2206.58  4179.5 2205.25
  4271.9 2202.90  4519.4 2196.90  4540.7 2200.41  4563.1 2201.00  4673.4 2200.21
  4728.6 2197.91  4789.1 2198.41  4814.0 2196.69  4850.5 2197.42  4893.2 2200.25
  4929.7 2200.25  4968.0 2196.92  4990.2 2196.59  4997.3 2192.42  5003.1 2192.42
  5004.7 2188.27  5005.1 2187.77  5010.0 2188.27  5063.7 2199.88  5099.3 2200.65
  5149.5 2199.54  5158.0 2196.75  5185.6 2197.62  5206.5 2199.83  5320.9 2200.22
#Mann=6,-1,0
  3787.1   0.035       0  4179.5    0.07       0  4271.9   0.035       0
  5004.7   0.035       0  5010.0   0.035       0  5206.5    0.07       0
Bank Sta=5004.7,5010
Exp/Cntr=0.3,0.1

Type RM Length L Ch R = 1,3615,433,433,433
BEGIN DESCRIPTION:
Buffalo Creek Trib 07 4.0
END DESCRIPTION:
XS GIS Cut Line= 3
      1309780.43      6931191.73      1309305.00      6929938.00
      1309197.20      6929767.47
#Sta/Elev= 30
  3655.6 2207.47  3730.3 2206.53  3775.0 2205.86  4290.6 2200.53  4415.9 2197.30
  4568.7 2197.17  4610.9 2195.11  4654.2 2194.75  4701.3 2197.27  4739.4 2197.28
  4857.7 2196.69  4910.9 2195.88  4967.1 2191.75  4986.7 2188.70  4991.1 2185.80
  4991.5 2185.30  4996.5 2185.80  5004.1 2187.90  5031.9 2191.08  5053.3 2196.39
  5061.7 2197.25  5077.0 2195.54  5082.9 2196.62  5098.2 2195.43  5113.5 2196.19
  5119.4 2199.63  5134.7 2198.50  5140.6 2201.69  5177.0 2200.65  5198.2 2201.75
#Mann=9,-1,0
  3655.6   0.035       0  3730.3    0.07       0  3775.0   0.035       0
  4739.4    0.07       0  4857.7   0.035       0  4967.1    0.07       0
  4991.1    0.07       0  4996.5    0.07       0  5053.3   0.035       0
Bank Sta=4991.1,4996.5
Exp/Cntr=0.3,0.1

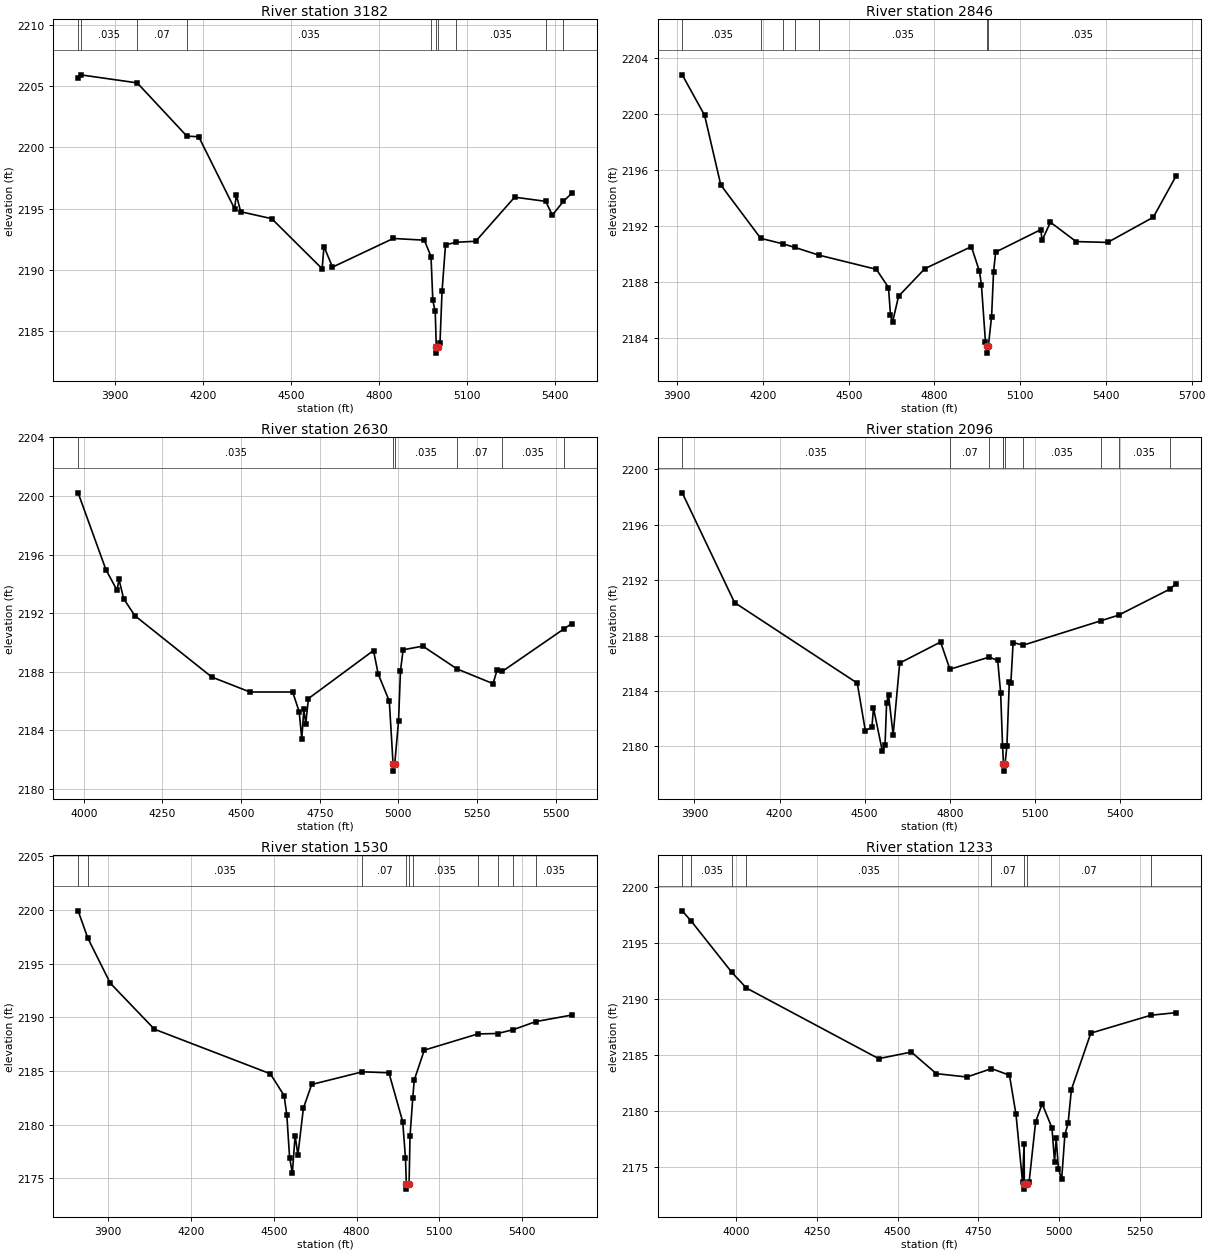
Type RM Length L Ch R = 1,3182,336,336,336
BEGIN DESCRIPTION:
Buffalo Creek Trib 07 3.0
END DESCRIPTION:
XS GIS Cut Line= 3
      1310311.69      6930608.39      1309555.00      6929638.00
      1309132.65      6929476.28
#Sta/Elev= 30
  3775.0 2205.71  3783.2 2205.95  3976.4 2205.29  4145.6 2200.93  4186.0 2200.88
  4308.1 2194.99  4314.4 2196.11  4328.9 2194.74  4434.9 2194.17  4606.6 2190.07
  4612.9 2191.89  4641.9 2190.20  4849.0 2192.55  4954.9 2192.41  4977.6 2191.07
  4983.8 2187.47  4992.0 2186.57  4995.6 2183.66  4996.1 2183.16  5001.0 2183.66
  5008.2 2183.98  5015.2 2188.22  5027.0 2192.03  5064.1 2192.24  5130.0 2192.32
  5262.5 2195.93  5368.5 2195.59  5391.0 2194.46  5429.1 2195.60  5457.8 2196.26
#Mann=10,-1,0
  3775.0    0.07       0  3783.2   0.035       0  3976.4    0.07       0
  4145.6   0.035       0  4977.6    0.07       0  4995.6    0.07       0
  5001.0    0.07       0  5064.1   0.035       0  5368.5    0.07       0
  5429.1   0.035       0
Bank Sta=4995.6,5001
Exp/Cntr=0.3,0.1

Type RM Length L Ch R = 1,2846,216,216,216
BEGIN DESCRIPTION:
Buffalo Creek Trib 07 2.0
END DESCRIPTION:
XS GIS Cut Line= 3
      1310536.91      6930186.58      1309749.12      6929356.68
      1309165.61      6929337.38
#Sta/Elev= 30
  3917.3 2202.77  3995.6 2199.88  4052.2 2194.91  4192.0 2191.10  4271.5 2190.70
  4310.7 2190.46  4394.3 2189.91  4596.7 2188.89  4639.1 2187.59  4646.1 2185.63
  4653.3 2185.12  4674.3 2186.97  4766.5 2188.94  4929.2 2190.51  4957.5 2188.74
  4964.4 2187.76  4978.5 2183.68  4983.1 2183.41  4983.5 2182.91  4988.5 2183.41
  4999.9 2185.52  5006.8 2188.72  5014.1 2190.12  5171.8 2191.72  5176.8 2190.97
  5205.8 2192.25  5295.8 2190.87  5405.9 2190.81  5566.0 2192.61  5645.4 2195.55
#Mann=7,-1,0
  3917.3   0.035       0  4192.0    0.07       0  4271.5   0.035       0
  4310.7    0.07       0  4394.3   0.035       0  4983.1   0.035       0
  4988.5   0.035       0
Bank Sta=4983.1,4988.5
Exp/Cntr=0.3,0.1

Type RM Length L Ch R = 1,2630,534,534,534
BEGIN DESCRIPTION:
Buffalo Creek Trib 07 1.8
END DESCRIPTION:
XS GIS Cut Line= 2
      1310564.46      6930101.13      1309636.16      6928835.84
#Sta/Elev= 30
  3982.1 2200.21  4070.4 2194.97  4105.9 2193.56  4112.1 2194.30  4126.7 2192.99
  4162.3 2191.83  4406.9 2187.64  4528.1 2186.62  4663.9 2186.62  4684.7 2185.27
  4692.9 2183.41  4699.4 2185.43  4705.6 2184.46  4714.0 2186.17  4920.9 2189.45
  4935.6 2187.86  4971.1 2185.99  4983.0 2181.72  4983.5 2181.22  4988.4 2181.72
  5000.4 2184.64  5006.6 2188.08  5015.0 2189.50  5077.6 2189.75  5186.5 2188.19
  5300.7 2187.19  5313.8 2188.13  5330.4 2188.03  5527.7 2190.95  5551.4 2191.29
#Mann=6,-1,0
  3982.1   0.035       0  4983.0   0.035       0  4988.4   0.035       0
  5186.5    0.07       0  5330.4   0.035       0  5527.7    0.07       0
Bank Sta=4983,4988.4
Exp/Cntr=0.3,0.1

Type RM Length L Ch R = 1,2096,566,566,566
BEGIN DESCRIPTION:
Buffalo Creek Trib 07 1.75
END DESCRIPTION:
XS GIS Cut Line= 3
      1310686.22      6930030.47      1310196.12      6928947.02
      1309682.16      6928747.99
#Sta/Elev= 30
  3857.1 2198.31  4041.5 2190.38  4473.9 2184.56  4502.5 2181.11  4525.6 2181.38
  4531.1 2182.76  4562.2 2179.66  4571.8 2180.06  4577.3 2183.12  4584.2 2183.71
  4600.4 2180.82  4623.5 2186.01  4767.6 2187.53  4800.5 2185.56  4938.8 2186.44
  4968.9 2186.20  4979.3 2183.84  4986.0 2180.01  4989.3 2178.70  4989.7 2178.20
  4994.7 2178.70  5001.3 2180.03  5009.7 2184.61  5015.2 2184.55  5023.2 2187.49
  5058.6 2187.30  5333.3 2189.07  5394.7 2189.47  5576.3 2191.36  5597.4 2191.75
#Mann=10,-1,0
  3857.1   0.035       0  4800.5    0.07       0  4938.8   0.035       0
  4986.0    0.07       0  4989.3    0.07       0  4994.7    0.07       0
  5058.6   0.035       0  5333.3    0.07       0  5394.7   0.035       0
  5576.3    0.07       0
Bank Sta=4989.3,4994.7
Exp/Cntr=0.3,0.1

Type RM Length L Ch R = 1,1530,297,297,297
BEGIN DESCRIPTION:
Buffalo Creek Trib 07 1.7
END DESCRIPTION:
XS GIS Cut Line= 3
      1310703.73      6930054.62      1310703.73      6928857.81
      1310386.04      6928356.98
#Sta/Elev= 30
  3790.9 2199.93  3826.4 2197.37  3907.5 2193.19  4067.5 2188.90  4487.5 2184.75
  4537.5 2182.72  4547.5 2180.89  4557.5 2176.92  4567.5 2175.50  4577.5 2178.99
  4587.5 2177.18  4607.5 2181.54  4637.5 2183.75  4821.0 2184.93  4917.5 2184.84
  4967.5 2180.28  4977.5 2176.89  4980.6 2174.50  4981.1 2174.00  4989.7 2174.50
  4990.6 2174.50  4994.0 2178.95  5003.8 2182.45  5009.3 2184.17  5045.7 2186.95
  5239.9 2188.46  5311.8 2188.50  5368.5 2188.86  5449.9 2189.61  5580.8 2190.22
#Mann=10,-1,0
  3790.9    0.07       0  3826.4   0.035       0  4821.0    0.07       0
  4980.6    0.07       0  4989.7    0.07       0  5003.8   0.035       0
  5239.9    0.07       0  5311.8   0.035       0  5368.5    0.07       0
  5449.9   0.035       0
Bank Sta=4980.6,4989.7
Exp/Cntr=0.3,0.1

Type RM Length L Ch R = 1,1233,518,518,518
BEGIN DESCRIPTION:
Buffalo Creek Trib 07 1.5
END DESCRIPTION:
XS GIS Cut Line= 3
      1310793.48      6930048.61      1310961.03      6928929.62
      1310943.08      6928534.69
#Sta/Elev= 30
  3834.1 2197.85  3861.3 2196.95  3987.8 2192.34  4032.6 2190.95  4441.4 2184.64
  4542.5 2185.23  4619.6 2183.30  4714.4 2183.00  4790.3 2183.75  4845.9 2183.16
  4866.1 2179.65  4886.2 2173.63  4891.2 2177.04  4891.8 2173.48  4892.3 2172.98
  4901.0 2173.48  4906.5 2173.59  4926.8 2179.01  4947.0 2180.60  4977.2 2178.46
  4985.3 2175.41  4990.3 2177.54  4997.2 2174.82  5007.2 2173.85  5017.2 2177.85
  5027.2 2178.88  5037.3 2181.87  5097.3 2186.92  5283.2 2188.52  5360.9 2188.75
#Mann=8,-1,0
  3834.1    0.07       0  3861.3   0.035       0  3987.8    0.07       0
  4032.6   0.035       0  4790.3    0.07       0  4891.8    0.07       0
  4901.0    0.07       0  5283.2   0.035       0
Bank Sta=4891.8,4901
Exp/Cntr=0.3,0.1

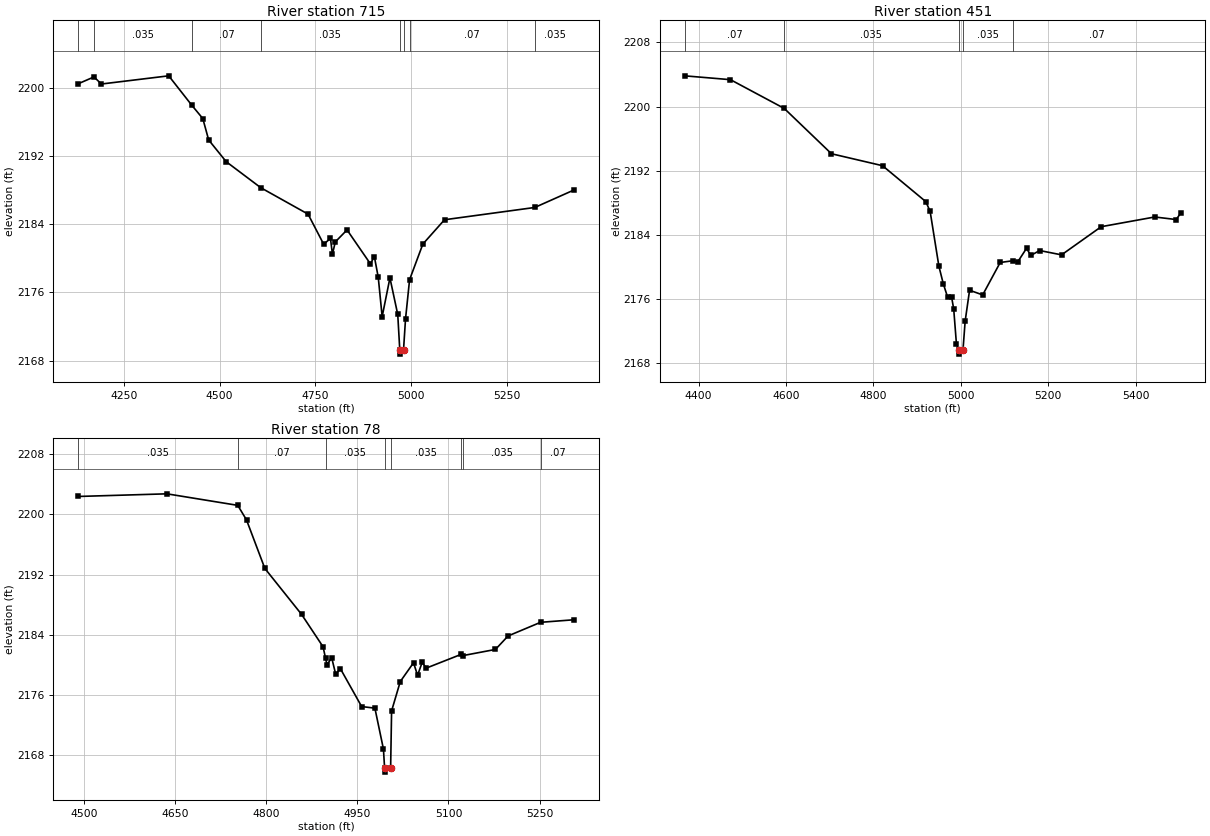
Type RM Length L Ch R = 1,715,264,264,264
BEGIN DESCRIPTION:
Buffalo Creek Trib 07 1.0
END DESCRIPTION:
XS GIS Cut Line= 4
      1311036.22      6930047.52      1311198.96      6929193.79
      1311260.75      6929108.03      1311255.00      6928787.99
#Sta/Elev= 30
  4130.9 2200.48  4172.0 2201.28  4191.5 2200.45  4367.2 2201.41  4428.0 2197.93
  4456.2 2196.40  4471.5 2193.89  4517.3 2191.34  4607.5 2188.29  4731.0 2185.19
  4771.8 2181.66  4789.5 2182.34  4794.6 2180.50  4802.3 2181.94  4832.8 2183.34
  4893.8 2179.36  4904.1 2180.22  4914.3 2177.78  4924.5 2173.17  4944.8 2177.71
  4965.2 2173.42  4970.5 2169.27  4971.0 2168.77  4980.3 2169.27  4985.5 2172.89
  4996.1 2177.50  5030.8 2181.68  5087.3 2184.53  5322.9 2185.97  5425.8 2188.03
#Mann=8,-1,0
  4130.9    0.07       0  4172.0   0.035       0  4428.0    0.07       0
  4607.5   0.035       0  4970.5    0.07       0  4980.3   0.035       0
  4996.1    0.07       0  5322.9   0.035       0
Bank Sta=4970.5,4980.3
Exp/Cntr=0.3,0.1

Type RM Length L Ch R = 1,451,373,373,373
BEGIN DESCRIPTION:
Buffalo Creek Trib 07 0.8
END DESCRIPTION:
XS GIS Cut Line= 4
      1311239.54      6930011.14      1311333.97      6929491.43
      1311357.77      6929151.71      1311321.40      6928887.98
#Sta/Elev= 30
  4368.0 2203.83  4472.8 2203.35  4595.8 2199.77  4703.9 2194.12  4820.8 2192.63
  4919.7 2188.16  4929.7 2186.95  4949.8 2180.10  4959.8 2177.93  4969.8 2176.24
  4978.7 2176.31  4983.7 2174.78  4989.9 2170.44  4995.0 2169.65  4995.5 2169.15
  5004.9 2169.65  5009.9 2173.27  5020.0 2177.11  5050.0 2176.53  5090.1 2180.57
  5118.3 2180.78  5130.4 2180.66  5150.3 2182.33  5160.3 2181.45  5180.3 2182.06
  5230.5 2181.52  5321.3 2185.03  5443.8 2186.24  5492.9 2185.92  5503.0 2186.71
#Mann=5,-1,0
  4368.0    0.07       0  4595.8   0.035       0  4995.0   0.035       0
  5004.9   0.035       0  5118.3    0.07       0
Bank Sta=4995,5004.9
Exp/Cntr=0.3,0.1

Type RM Length L Ch R = 1,78,0,0,0
BEGIN DESCRIPTION:
Buffalo Creek Trib 07 0.7
END DESCRIPTION:
XS GIS Cut Line= 3
      1311730.00      6929612.97      1311680.00      6929213.00
      1311368.29      6928941.29
#Sta/Elev= 30
  4490.3 2202.36  4636.4 2202.71  4753.0 2201.18  4767.4 2199.25  4797.6 2192.81
  4858.1 2186.71  4893.4 2182.42  4897.5 2180.92  4900.0 2180.01  4907.6 2180.98
  4914.3 2178.76  4921.9 2179.52  4957.0 2174.48  4978.8 2174.27  4992.9 2168.83
  4994.8 2166.28  4995.3 2165.78  5004.7 2166.28  5006.3 2173.90  5020.6 2177.80
  5042.4 2180.29  5049.1 2178.63  5056.7 2180.36  5063.3 2179.58  5120.3 2181.39
  5123.5 2181.24  5177.3 2182.06  5198.1 2183.85  5251.6 2185.66  5306.9 2186.00
#Mann=8,-1,0
  4490.3   0.035       0  4753.0    0.07       0  4897.5   0.035       0
  4994.8   0.035       0  5004.7   0.035       0  5120.3    0.07       0
  5123.5   0.035       0  5251.6    0.07       0
Bank Sta=4994.8,5004.7
Exp/Cntr=0.3,0.1

Chan Stop Cuts=-1