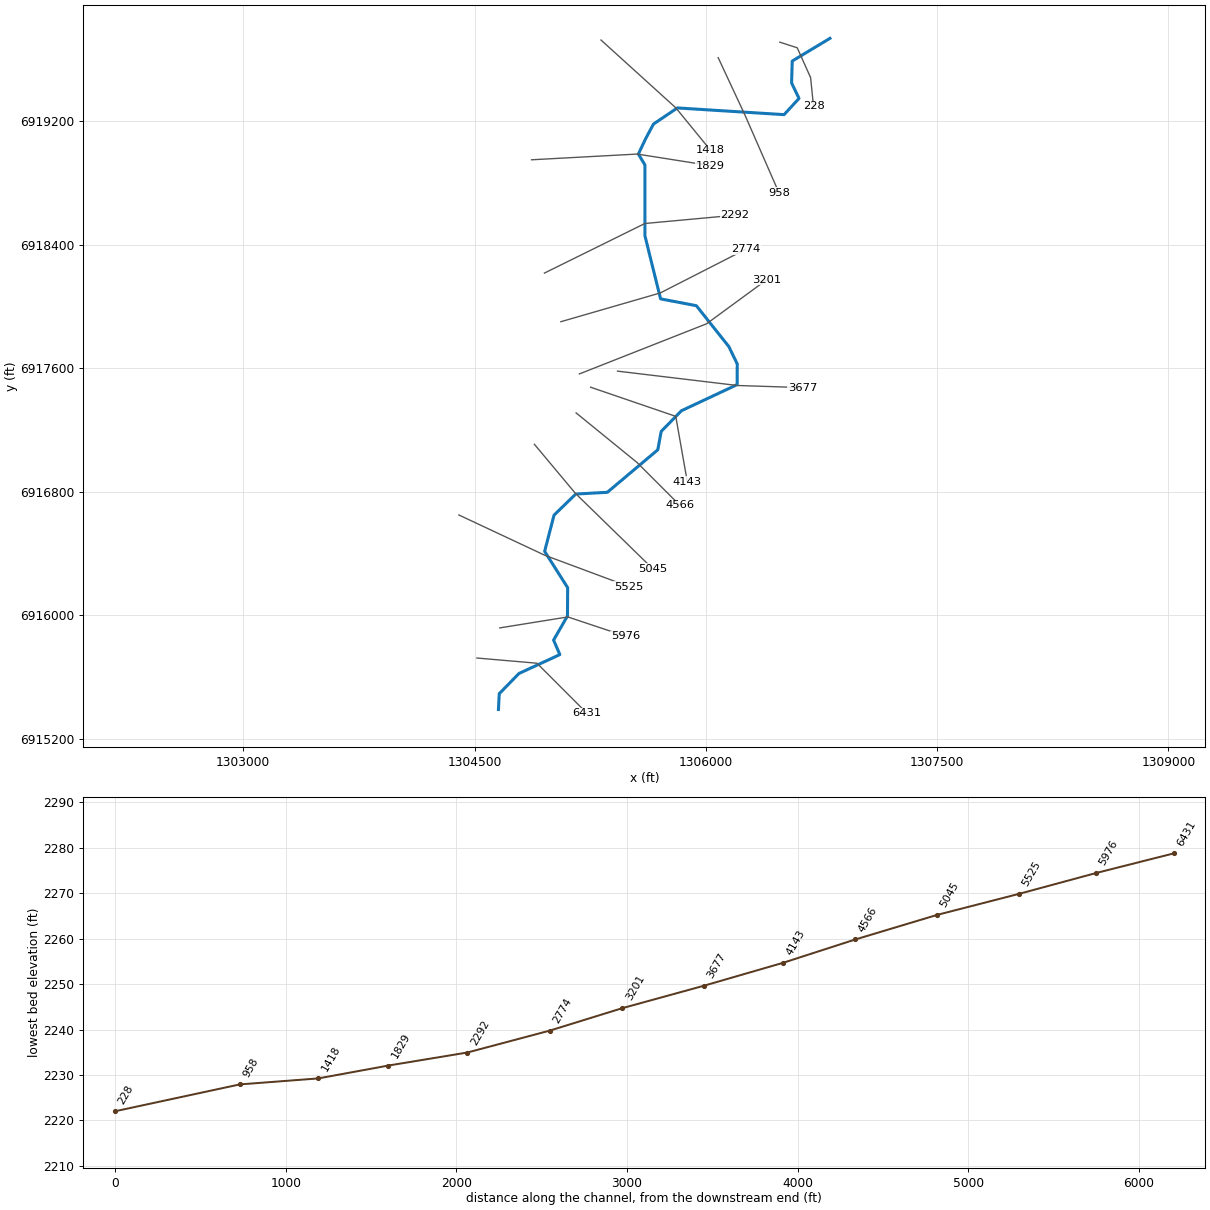
--- Buffalo Creek Trib 08-01.prj (project) ---

Proj Title=Buffalo Creek Trib 08-01 Base Level Engineering
Current Plan=p01
Default Exp/Contr=0.3,0.1
English Units
Geom File=g01
Flow File=f01
Plan File=p01
BEGIN DESCRIPTION:
Buffalo Creek Trib 08-01
END DESCRIPTION:

--- Buffalo Creek Trib 08-01.p01 (plan) ---

Plan Title=Multiple Run
Short Identifier=Multiple
Geom File=g01
Flow File=f01
Subcritical Flow
K Sum by GR= 0
Std Step Tol= 0.01
Critical Tol= 0.01
Num of Std Step Trials= 20
Max Error Tol= 0.3
Flow Tol Ratio= 0.001
Split Flow NTrial= 30
Split Flow Tol= 0.02
Split Flow Ratio= 0.02
Log Output Level= 0
Friction Slope Method= 1
Unsteady Friction Slope Method= 2
Unsteady Bridges Friction Slope Method= 1
Parabolic Critical Depth
Global Vel Dist=  1 , 1 , 1
Global Log Level= 0
CheckData=True
Encroach Param= -1, 0, 0, 0
BEGIN DESCRIPTION:
Multiple Run
END DESCRIPTION:

--- Buffalo Creek Trib 08-01.f01 (steady flow) ---

Flow Title=Multiple
Number of Profiles=7
Profile Names=10-year,25-year,50-year,1pct_min,100-year,1pct_plu,500-year
River Rch & RM= Buffalo Creek Tr,Reach-1,6431
     352     508     642     403     804    1605    1279
River Rch & RM= Buffalo Creek Tr,Reach-1,3677
     480     705     900     571    1139    2272    1849
River Rch & RM= Buffalo Creek Tr,Reach-1,1418
     558     824    1056     672    1342    2677    2196
Boundary for River Rch & Prof#=Buffalo Creek Tr,Reach-1,1
Up Type=0
Dn Type=3
Dn Slope=0.005
Boundary for River Rch & Prof#=Buffalo Creek Tr,Reach-1,2
Up Type=0
Dn Type=3
Dn Slope=0.005
Boundary for River Rch & Prof#=Buffalo Creek Tr,Reach-1,3
Up Type=0
Dn Type=3
Dn Slope=0.005
Boundary for River Rch & Prof#=Buffalo Creek Tr,Reach-1,4
Up Type=0
Dn Type=3
Dn Slope=0.005
Boundary for River Rch & Prof#=Buffalo Creek Tr,Reach-1,5
Up Type=0
Dn Type=3
Dn Slope=0.005
Boundary for River Rch & Prof#=Buffalo Creek Tr,Reach-1,6
Up Type=0
Dn Type=3
Dn Slope=0.005
Boundary for River Rch & Prof#=Buffalo Creek Tr,Reach-1,7
Up Type=0
Dn Type=3
Dn Slope=0.005

--- Buffalo Creek Trib 08-01.g01 (geometry) ---

Geom Title=Existing Conditions

River Reach=Buffalo Creek Tr,Reach-1
Reach XY= 30
      1304655.00      6915388.00      1304660.35      6915490.50
      1304788.27      6915621.54      1305053.43      6915743.85
      1305012.56      6915838.00      1305102.76      6915993.93
      1305103.95      6916177.56      1304954.59      6916413.00
      1305015.52      6916647.79      1305156.46      6916784.46
      1305361.19      6916795.81      1305688.56      6917071.21
      1305710.52      6917190.43      1305841.78      6917324.38
      1306203.04      6917493.65      1306203.81      6917627.50
      1306149.17      6917740.30      1305938.54      6918005.14
      1305706.60      6918049.53      1305605.07      6918458.03
      1305604.82      6918918.02      1305562.53      6918988.01
      1305611.04      6919090.22      1305660.59      6919182.39
      1305815.44      6919286.95      1306507.47      6919243.45
      1306604.41      6919348.61      1306556.23      6919448.50
      1306560.35      6919590.70      1306805.00      6919738.00

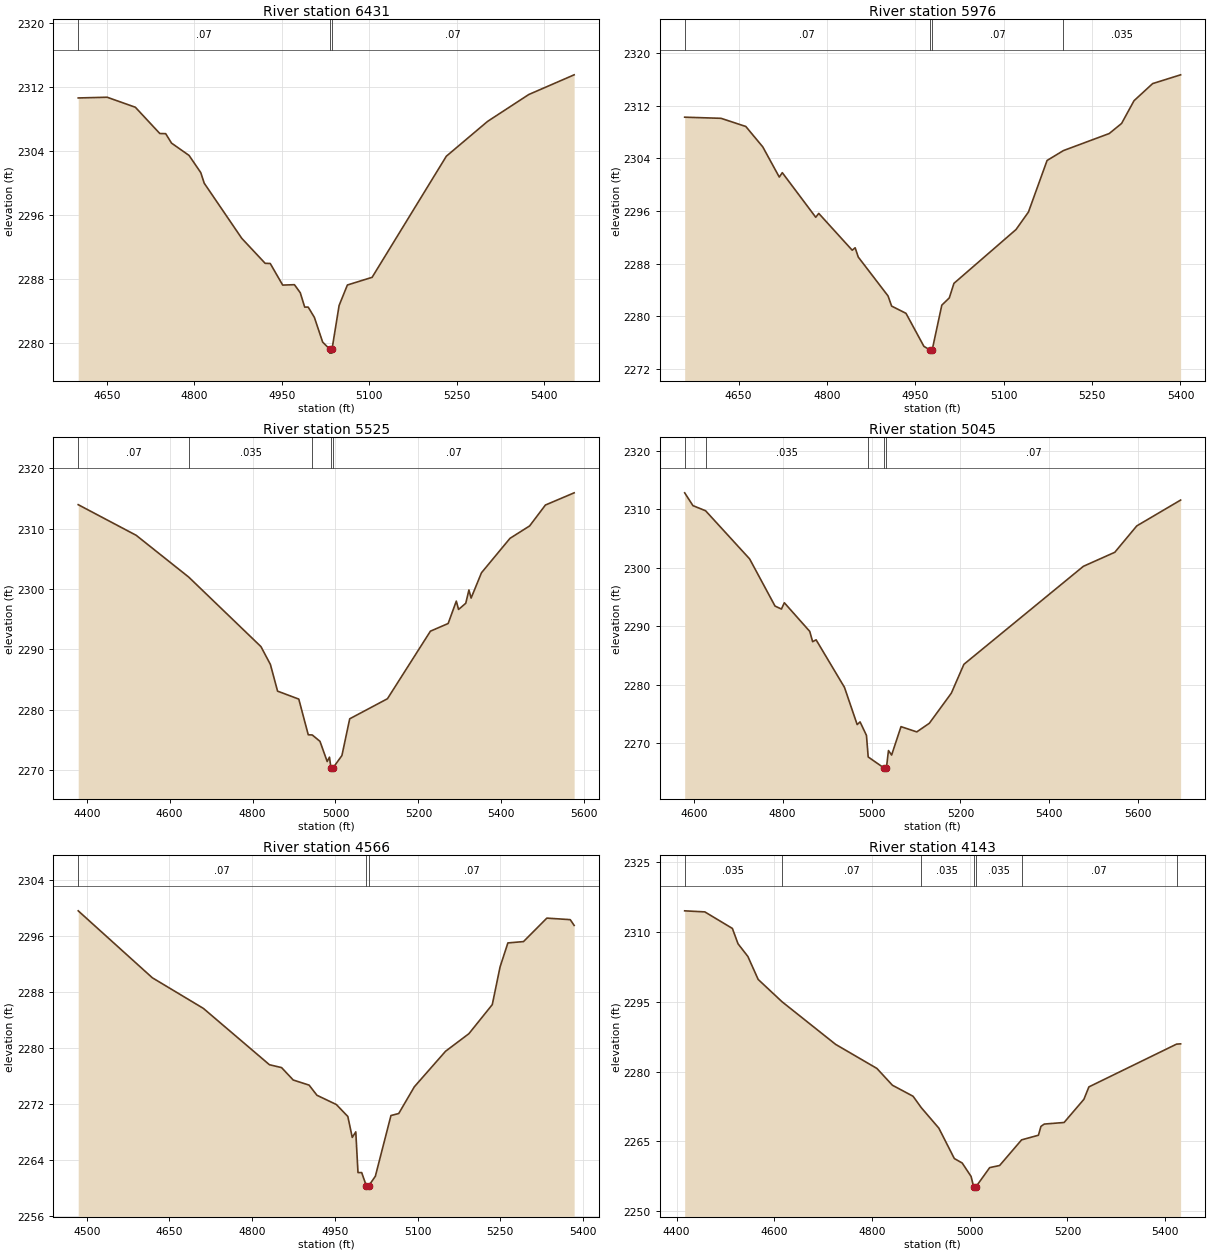
Type RM Length L Ch R = 1,6431,455,455,455
BEGIN DESCRIPTION:
Buffalo Creek Trib 08-01 13.0
END DESCRIPTION:
XS GIS Cut Line= 3
      1304515.59      6915721.73      1304905.00      6915688.00
      1305230.01      6915362.99
#Sta/Elev= 30
  4601.1 2310.64  4650.7 2310.73  4699.1 2309.48  4741.0 2306.20  4751.1 2306.18
  4761.1 2305.00  4791.2 2303.46  4811.3 2301.31  4817.2 2299.99  4881.6 2293.10
  4921.7 2289.98  4930.4 2289.96  4951.8 2287.26  4971.9 2287.31  4981.9 2286.31
  4989.5 2284.51  4995.5 2284.51  5006.1 2283.23  5020.3 2280.14  5032.4 2279.26
  5032.6 2278.76  5036.1 2278.76  5036.4 2279.26  5048.5 2284.71  5062.7 2287.27
  5105.1 2288.23  5232.4 2303.36  5303.1 2307.71  5373.8 2311.07  5451.6 2313.53
#Mann=3,-1,0
  4601.1    0.07       0  5032.4    0.07       0  5036.4    0.07       0
Bank Sta=5032.4,5036.4
Exp/Cntr=0.3,0.1

Type RM Length L Ch R = 1,5976,451,451,451
BEGIN DESCRIPTION:
Buffalo Creek Trib 08-01 12.0
END DESCRIPTION:
XS GIS Cut Line= 3
      1304664.08      6915917.05      1305105.00      6915988.00
      1305480.02      6915862.99
#Sta/Elev= 30
  4558.4 2310.25  4620.1 2310.08  4662.2 2308.84  4691.0 2305.74  4719.0 2301.16
  4724.1 2301.83  4780.9 2295.06  4786.0 2295.65  4842.8 2290.06  4847.8 2290.43
  4853.1 2289.02  4903.7 2283.11  4909.7 2281.58  4934.1 2280.48  4964.5 2275.47
  4974.5 2274.94  4974.8 2274.44  4978.6 2274.94  4994.9 2281.72  5007.6 2282.82
  5015.5 2285.03  5120.9 2293.20  5142.0 2295.86  5173.6 2303.68  5201.3 2305.18
  5279.1 2307.77  5300.1 2309.30  5321.2 2312.75  5352.8 2315.35  5400.3 2316.68
#Mann=4,-1,0
  4558.4    0.07       0  4974.5    0.07       0  4978.6    0.07       0
  5201.3   0.035       0
Bank Sta=4974.5,4978.6
Exp/Cntr=0.3,0.1

Type RM Length L Ch R = 1,5525,480,480,480
BEGIN DESCRIPTION:
Buffalo Creek Trib 08-01 11.0
END DESCRIPTION:
XS GIS Cut Line= 3
      1304398.45      6916648.81      1304955.00      6916388.00
      1305499.99      6916185.28
#Sta/Elev= 30
  4379.5 2313.96  4519.3 2308.89  4646.1 2301.97  4820.2 2290.47  4843.0 2287.52
  4860.3 2283.10  4911.5 2281.78  4934.3 2275.88  4944.1 2275.84  4962.6 2274.79
  4980.0 2271.45  4985.5 2272.17  4989.1 2270.36  4989.4 2269.86  4993.7 2270.36
  5015.5 2272.44  5034.3 2278.52  5125.3 2281.84  5228.9 2293.02  5271.7 2294.29
  5291.4 2298.00  5296.8 2296.62  5314.2 2297.64  5321.8 2299.84  5327.1 2298.50
  5352.1 2302.69  5420.9 2308.39  5468.2 2310.44  5506.3 2313.90  5575.6 2315.92
#Mann=5,-1,0
  4379.5    0.07       0  4646.1   0.035       0  4944.1    0.07       0
  4989.1    0.07       0  4993.7    0.07       0
Bank Sta=4989.1,4993.7
Exp/Cntr=0.3,0.1

Type RM Length L Ch R = 1,5045,479,479,479
BEGIN DESCRIPTION:
Buffalo Creek Trib 08-01 10.0
END DESCRIPTION:
XS GIS Cut Line= 3
      1304888.01      6917107.16      1305155.00      6916788.00
      1305656.27      6916299.84
#Sta/Elev= 30
  4579.6 2312.83  4598.2 2310.64  4626.7 2309.76  4725.7 2301.53  4782.9 2293.46
  4797.3 2292.95  4803.8 2294.03  4861.0 2289.13  4867.5 2287.37  4875.3 2287.69
  4939.1 2279.56  4967.7 2273.19  4974.2 2273.65  4988.6 2271.34  4991.0 2269.07
  4992.5 2267.65  5028.8 2265.73  5029.1 2265.23  5033.4 2265.73  5038.1 2268.75
  5045.2 2267.98  5066.3 2272.84  5101.8 2271.94  5130.1 2273.42  5179.5 2278.56
  5207.8 2283.50  5476.6 2300.26  5547.3 2302.66  5596.7 2307.17  5695.4 2311.59
#Mann=5,-1,0
  4579.6    0.07       0  4626.7   0.035       0  4991.0    0.07       0
  5028.8    0.07       0  5033.4    0.07       0
Bank Sta=5028.8,5033.4
Exp/Cntr=0.3,0.1

Type RM Length L Ch R = 1,4566,423,423,423
BEGIN DESCRIPTION:
Buffalo Creek Trib 08-01 9.0
END DESCRIPTION:
XS GIS Cut Line= 3
      1305158.85      6917310.28      1305555.00      6916988.00
      1305830.00      6916713.00
#Sta/Elev= 30
  4484.5 2299.54  4618.9 2289.99  4711.5 2285.62  4831.4 2277.58  4853.4 2277.17
  4874.5 2275.40  4903.3 2274.67  4917.6 2273.22  4952.8 2271.90  4973.6 2270.19
  4981.6 2267.21  4988.0 2268.00  4992.0 2262.19  4998.7 2262.19  5007.0 2260.33
  5007.3 2259.83  5011.7 2260.33  5023.5 2261.67  5051.8 2270.33  5065.9 2270.62
  5094.2 2274.43  5150.8 2279.50  5193.2 2282.01  5235.6 2286.16  5249.7 2291.53
  5263.9 2294.96  5292.2 2295.15  5334.6 2298.50  5377.0 2298.28  5384.1 2297.46
#Mann=3,-1,0
  4484.5    0.07       0  5007.0    0.07       0  5011.7    0.07       0
Bank Sta=5007,5011.7
Exp/Cntr=0.3,0.1

Type RM Length L Ch R = 1,4143,466,466,466
BEGIN DESCRIPTION:
Buffalo Creek Trib 08-01 8.0
END DESCRIPTION:
XS GIS Cut Line= 3
      1305252.58      6917476.95      1305805.00      6917288.00
      1305880.00      6916863.01
#Sta/Elev= 30
  4416.4 2314.59  4457.7 2314.36  4514.1 2310.80  4525.6 2307.50  4545.8 2304.77
  4566.9 2299.82  4616.0 2295.00  4725.5 2285.85  4810.0 2280.67  4841.7 2277.06
  4884.0 2274.69  4900.6 2272.26  4936.8 2267.82  4968.5 2261.28  4984.6 2260.32
  5002.8 2257.43  5008.0 2255.20  5008.4 2254.70  5012.7 2255.20  5040.9 2259.33
  5061.2 2259.78  5106.2 2265.30  5140.7 2266.30  5145.8 2268.20  5152.6 2268.70
  5193.2 2269.04  5233.8 2274.03  5244.0 2276.70  5423.6 2285.91  5431.8 2285.96
#Mann=7,-1,0
  4416.4   0.035       0  4616.0    0.07       0  4900.6   0.035       0
  5008.0   0.035       0  5012.7   0.035       0  5106.2    0.07       0
  5423.6   0.035       0
Bank Sta=5008,5012.7
Exp/Cntr=0.3,0.1

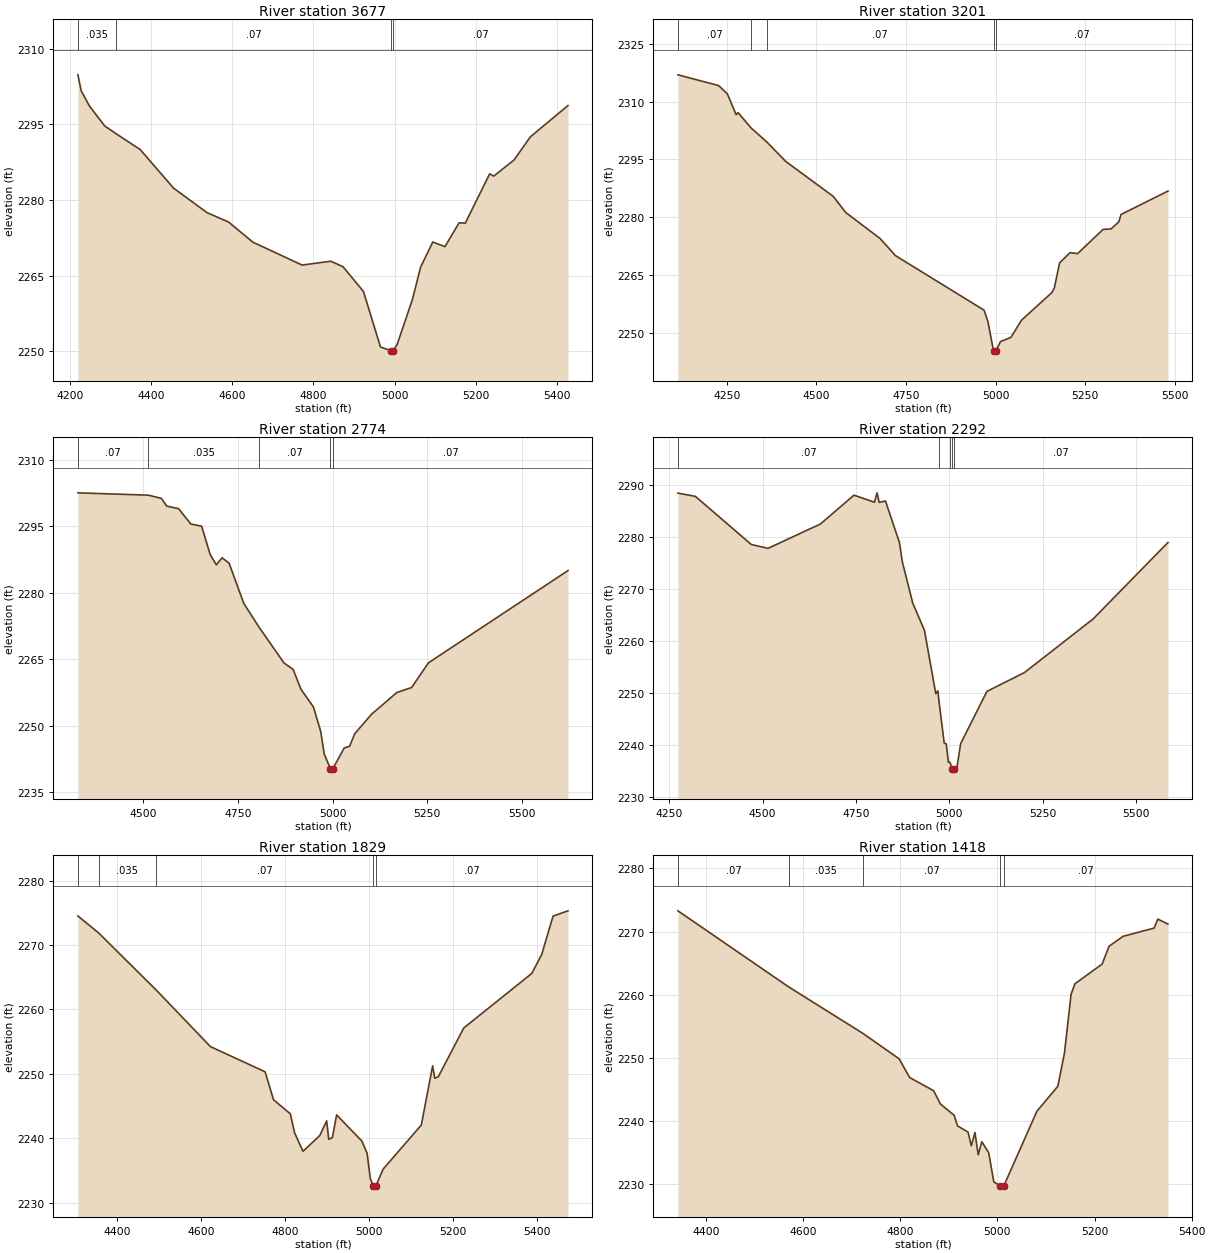
Type RM Length L Ch R = 1,3677,476,476,476
BEGIN DESCRIPTION:
Buffalo Creek Trib 08-01 7.0
END DESCRIPTION:
XS GIS Cut Line= 3
      1305427.13      6917581.10      1306205.00      6917488.00
      1306627.65      6917474.33
#Sta/Elev= 30
  4220.4 2304.81  4228.3 2301.67  4248.5 2298.66  4286.1 2294.69  4315.3 2293.08
  4373.5 2290.01  4455.9 2282.34  4538.3 2277.48  4590.9 2275.64  4651.3 2271.62
  4772.2 2267.09  4842.7 2267.85  4872.7 2266.78  4923.3 2261.85  4965.2 2250.84
  4990.8 2250.13  4991.3 2249.63  4996.7 2250.13  5006.3 2251.36  5043.8 2260.27
  5063.9 2266.67  5093.9 2271.66  5123.9 2270.75  5158.7 2275.47  5173.9 2275.40
  5233.9 2285.17  5244.0 2284.73  5294.0 2287.93  5334.0 2292.50  5426.7 2298.72
#Mann=4,-1,0
  4220.4   0.035       0  4315.3    0.07       0  4990.8    0.07       0
  4996.7    0.07       0
Bank Sta=4990.8,4996.7
Exp/Cntr=0.3,0.1

Type RM Length L Ch R = 1,3201,427,427,427
BEGIN DESCRIPTION:
Buffalo Creek Trib 08-01 6.0
END DESCRIPTION:
XS GIS Cut Line= 3
      1305179.97      6917562.99      1306005.00      6917888.00
      1306393.22      6918172.25
#Sta/Elev= 30
  4113.5 2316.92  4227.2 2314.13  4251.6 2311.97  4276.0 2306.58  4281.4 2307.11
  4317.3 2303.18  4361.8 2299.49  4414.1 2294.48  4546.8 2285.41  4581.9 2281.21
  4677.8 2274.46  4720.8 2270.01  4968.0 2255.87  4978.7 2252.96  4994.6 2245.22
  4995.1 2244.72  5000.6 2245.22  5013.8 2247.70  5043.1 2248.81  5072.4 2253.25
  5158.1 2260.49  5164.3 2261.67  5179.0 2268.14  5208.3 2270.79  5229.1 2270.53
  5300.2 2276.81  5322.5 2276.94  5344.2 2278.79  5350.4 2280.69  5481.4 2286.76
#Mann=5,-1,0
  4113.5    0.07       0  4317.3   0.035       0  4361.8    0.07       0
  4994.6    0.07       0  5000.6    0.07       0
Bank Sta=4994.6,5000.6
Exp/Cntr=0.3,0.1

Type RM Length L Ch R = 1,2774,482,482,482
BEGIN DESCRIPTION:
Buffalo Creek Trib 08-01 5.0
END DESCRIPTION:
XS GIS Cut Line= 3
      1305059.91      6917901.42      1305705.00      6918088.00
      1306257.82      6918370.17
#Sta/Elev= 30
  4328.7 2302.60  4514.5 2302.07  4548.9 2301.35  4563.0 2299.60  4594.2 2299.03
  4626.5 2295.55  4654.9 2295.07  4677.5 2288.64  4693.7 2286.34  4708.8 2287.93
  4727.3 2286.73  4766.1 2277.63  4805.6 2272.35  4872.2 2264.17  4896.1 2262.73
  4917.0 2258.23  4949.8 2254.23  4969.0 2248.70  4978.2 2243.62  4994.6 2240.26
  4995.1 2239.76  5000.6 2240.26  5030.8 2244.98  5045.1 2245.38  5058.6 2248.20
  5103.1 2252.62  5169.7 2257.51  5208.6 2258.64  5253.0 2264.22  5620.9 2285.04
#Mann=5,-1,0
  4328.7    0.07       0  4514.5   0.035       0  4805.6    0.07       0
  4994.6    0.07       0  5000.6    0.07       0
Bank Sta=4994.6,5000.6
Exp/Cntr=0.3,0.1

Type RM Length L Ch R = 1,2292,463,463,463
BEGIN DESCRIPTION:
Buffalo Creek Trib 08-01 4.0
END DESCRIPTION:
XS GIS Cut Line= 3
      1304953.16      6918216.54      1305605.00      6918538.00
      1306187.55      6918591.53
#Sta/Elev= 30
  4273.3 2288.53  4320.0 2287.90  4469.6 2278.63  4514.5 2277.88  4654.8 2282.57
  4744.7 2288.13  4799.4 2286.76  4806.4 2288.58  4812.0 2286.74  4828.9 2287.00
  4866.3 2279.00  4873.8 2275.36  4901.8 2267.35  4933.2 2262.08  4963.6 2249.86
  4969.2 2250.42  4972.3 2248.31  4986.1 2240.36  4991.7 2240.20  4997.3 2236.66
  5001.5 2236.66  5007.1 2235.45  5007.6 2234.95  5013.2 2235.45  5020.2 2235.66
  5030.2 2240.25  5100.5 2250.32  5200.9 2253.94  5384.7 2264.27  5585.1 2279.01
#Mann=5,-1,0
  4273.3    0.07       0  4972.3   0.035       0  5001.5    0.07       0
  5007.1   0.035       0  5013.2    0.07       0
Bank Sta=5007.1,5013.2
Exp/Cntr=0.3,0.1

Type RM Length L Ch R = 1,1829,411,411,411
BEGIN DESCRIPTION:
Buffalo Creek Trib 08-01 3.0
END DESCRIPTION:
XS GIS Cut Line= 3
      1304869.83      6918950.90      1305555.00      6918988.00
      1306030.04      6918912.99
#Sta/Elev= 30
  4306.0 2274.50  4355.1 2271.88  4491.7 2263.05  4621.6 2254.21  4751.8 2250.30
  4771.9 2245.96  4811.9 2243.77  4821.9 2240.84  4842.0 2237.95  4882.0 2240.40
  4898.4 2242.68  4903.4 2239.81  4912.1 2240.09  4922.1 2243.61  4982.2 2239.55
  4994.7 2237.66  5002.3 2233.73  5009.4 2232.58  5009.9 2232.08  5015.5 2232.58
  5032.7 2235.17  5123.8 2242.03  5150.8 2251.23  5155.8 2249.31  5164.3 2249.54
  5225.0 2257.11  5387.0 2265.58  5410.6 2268.53  5437.6 2274.48  5473.1 2275.30
#Mann=5,-1,0
  4306.0    0.07       0  4355.1   0.035       0  4491.7    0.07       0
  5009.4    0.07       0  5015.5    0.07       0
Bank Sta=5009.4,5015.5
Exp/Cntr=0.3,0.1

Type RM Length L Ch R = 1,1418,460,460,460
BEGIN DESCRIPTION:
Buffalo Creek Trib 08-01 2.0
END DESCRIPTION:
XS GIS Cut Line= 3
      1305320.31      6919726.94      1305805.00      6919288.00
      1306029.98      6919013.02
#Sta/Elev= 30
  4342.0 2273.30  4570.3 2261.25  4723.0 2253.90  4797.5 2249.88  4819.2 2246.92
  4868.5 2244.83  4882.7 2242.72  4911.1 2240.92  4917.8 2239.26  4939.5 2238.28
  4946.2 2236.11  4953.7 2238.22  4960.4 2234.70  4967.9 2236.74  4982.1 2235.01
  4992.5 2230.40  5005.9 2229.75  5006.4 2229.25  5013.1 2229.75  5081.3 2241.58
  5124.4 2245.53  5138.0 2250.76  5151.7 2260.10  5159.6 2261.75  5215.6 2264.87
  5229.9 2267.69  5258.6 2269.26  5322.5 2270.56  5330.4 2271.99  5351.2 2271.20
#Mann=5,-1,0
  4342.0    0.07       0  4570.3   0.035       0  4723.0    0.07       0
  5005.9    0.07       0  5013.1    0.07       0
Bank Sta=5005.9,5013.1
Exp/Cntr=0.3,0.1

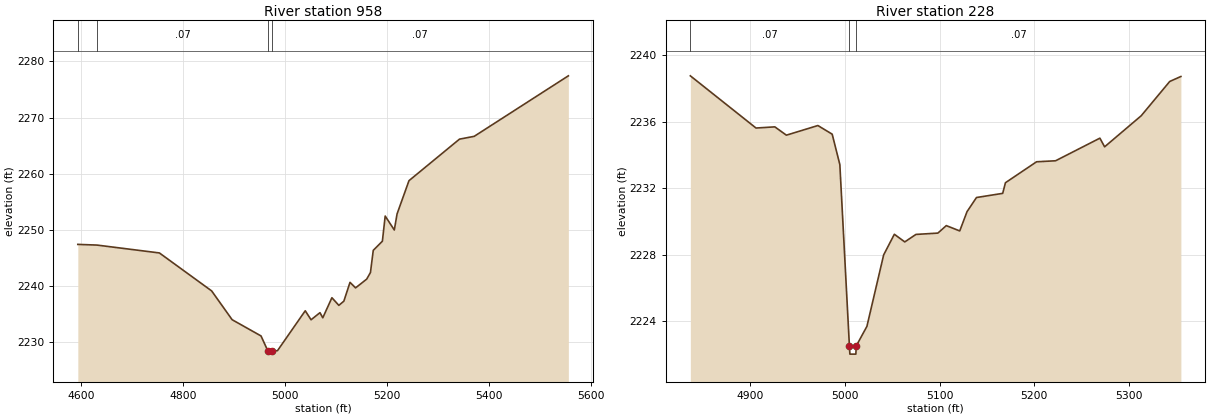
Type RM Length L Ch R = 1,958,730,730,730
BEGIN DESCRIPTION:
Buffalo Creek Trib 08-01 1.0
END DESCRIPTION:
XS GIS Cut Line= 3
      1306080.01      6919612.97      1306255.00      6919238.00
      1306474.84      6918735.59
#Sta/Elev= 30
  4592.9 2247.44  4630.3 2247.32  4752.9 2245.92  4855.4 2239.17  4895.6 2234.05
  4952.3 2231.16  4966.0 2228.43  4966.5 2227.93  4973.3 2228.43  4984.6 2228.55
  5039.0 2235.64  5050.4 2234.04  5067.9 2235.30  5073.4 2234.39  5091.3 2237.96
  5104.9 2236.60  5114.7 2237.34  5126.8 2240.69  5137.7 2239.71  5159.5 2241.26
  5166.9 2242.44  5172.4 2246.38  5190.3 2248.01  5195.8 2252.48  5213.7 2250.00
  5219.1 2252.86  5242.5 2258.77  5341.5 2266.15  5370.4 2266.65  5555.1 2277.41
#Mann=4,-1,0
  4592.9   0.035       0  4630.3    0.07       0  4966.0    0.07       0
  4973.3    0.07       0
Bank Sta=4966,4973.3
Exp/Cntr=0.3,0.1

Type RM Length L Ch R = 1,228,0,0,0
BEGIN DESCRIPTION:
Buffalo Creek Trib 08-01 0.5
END DESCRIPTION:
XS GIS Cut Line= 4
      1306480.02      6919712.99      1306592.67      6919676.77
      1306679.47      6919483.63      1306698.49      6919296.27
#Sta/Elev= 30
  4836.6 2238.77  4906.0 2235.63  4925.9 2235.70  4938.1 2235.20  4971.4 2235.78
  4986.5 2235.26  4994.6 2233.43  5004.7 2222.53  5005.2 2222.03  5011.5 2222.03
  5012.0 2222.53  5023.2 2223.70  5040.9 2228.00  5052.2 2229.24  5063.2 2228.78
  5075.0 2229.23  5098.2 2229.31  5107.1 2229.76  5121.3 2229.44  5129.0 2230.60
  5139.0 2231.45  5166.7 2231.70  5169.6 2232.34  5202.5 2233.60  5222.6 2233.66
  5269.4 2235.02  5274.4 2234.50  5313.1 2236.37  5343.2 2238.43  5355.0 2238.73
#Mann=3,-1,0
  4836.6    0.07       0  5004.7    0.07       0  5012.0    0.07       0
Bank Sta=5004.7,5012
Exp/Cntr=0.3,0.1

Chan Stop Cuts=-1