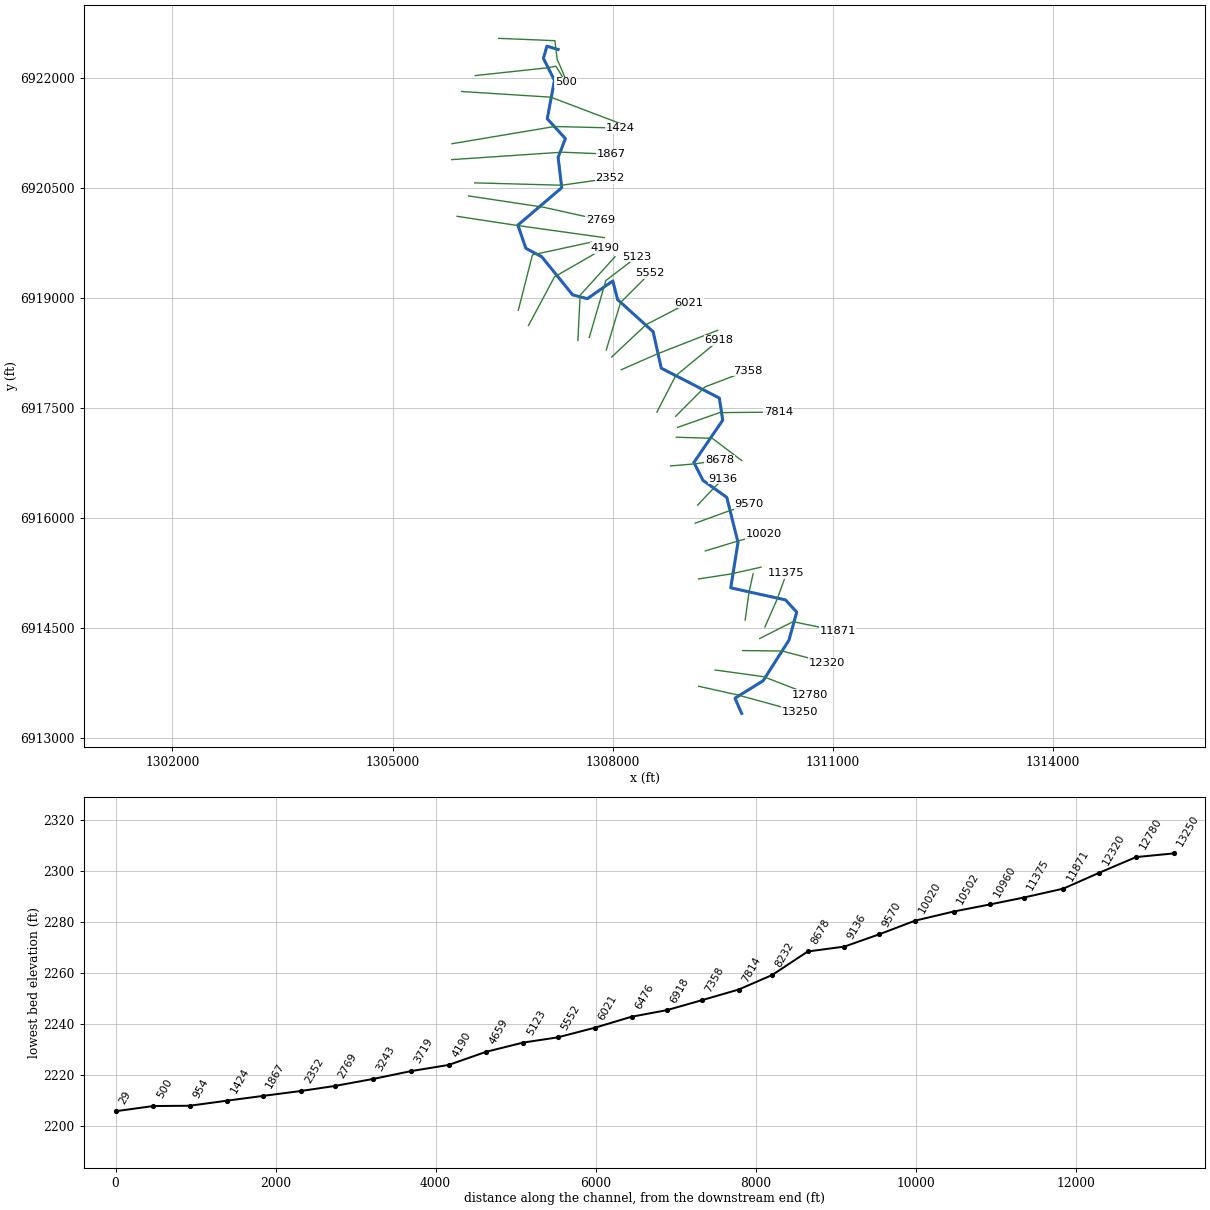
--- Buffalo Creek Trib 08.prj (project) ---

Proj Title=Buffalo Creek Trib 08 Base Level Engineering
Current Plan=p01
Default Exp/Contr=0.3,0.1
English Units
Geom File=g01
Flow File=f01
Plan File=p01
BEGIN DESCRIPTION:
Buffalo Creek Trib 08
END DESCRIPTION:

--- Buffalo Creek Trib 08.p01 (plan) ---

Plan Title=Multiple Run
Short Identifier=Multiple
Geom File=g01
Flow File=f01
Subcritical Flow
K Sum by GR= 0
Std Step Tol= 0.01
Critical Tol= 0.01
Num of Std Step Trials= 20
Max Error Tol= 0.3
Flow Tol Ratio= 0.001
Split Flow NTrial= 30
Split Flow Tol= 0.02
Split Flow Ratio= 0.02
Log Output Level= 0
Friction Slope Method= 1
Unsteady Friction Slope Method= 2
Unsteady Bridges Friction Slope Method= 1
Parabolic Critical Depth
Global Vel Dist=  1 , 1 , 1
Global Log Level= 0
CheckData=True
Encroach Param= -1, 0, 0, 0
BEGIN DESCRIPTION:
Multiple Run
END DESCRIPTION:

--- Buffalo Creek Trib 08.f01 (steady flow) ---

Flow Title=Multiple
Number of Profiles=7
Profile Names=10-year,25-year,50-year,1pct_min,100-year,1pct_plu,500-year
River Rch & RM= Buffalo Creek Tr,Reach-1,13250
     391     565     714     449     896    1787    1426
River Rch & RM= Buffalo Creek Tr,Reach-1,4190
     418     606     768     483     965    1925    1542
River Rch & RM= Buffalo Creek Tr,Reach-1,3243
     822    1232    1595    1024    2042    4075    3397
Boundary for River Rch & Prof#=Buffalo Creek Tr,Reach-1,1
Up Type=0
Dn Type=3
Dn Slope=0.005
Boundary for River Rch & Prof#=Buffalo Creek Tr,Reach-1,2
Up Type=0
Dn Type=3
Dn Slope=0.005
Boundary for River Rch & Prof#=Buffalo Creek Tr,Reach-1,3
Up Type=0
Dn Type=3
Dn Slope=0.005
Boundary for River Rch & Prof#=Buffalo Creek Tr,Reach-1,4
Up Type=0
Dn Type=3
Dn Slope=0.005
Boundary for River Rch & Prof#=Buffalo Creek Tr,Reach-1,5
Up Type=0
Dn Type=3
Dn Slope=0.005
Boundary for River Rch & Prof#=Buffalo Creek Tr,Reach-1,6
Up Type=0
Dn Type=3
Dn Slope=0.005
Boundary for River Rch & Prof#=Buffalo Creek Tr,Reach-1,7
Up Type=0
Dn Type=3
Dn Slope=0.005

--- Buffalo Creek Trib 08.g01 (geometry) ---

Geom Title=Existing Conditions

River Reach=Buffalo Creek Tr,Reach-1
Reach XY= 30
      1309755.00      6913338.00      1309664.10      6913544.75
      1310046.87      6913781.93      1310399.53      6914335.55
      1310505.41      6914717.87      1310353.50      6914884.39
      1309606.50      6915049.53      1309705.28      6915667.82
      1309552.95      6916282.16      1309228.05      6916514.66
      1309104.71      6916758.18      1309497.19      6917334.59
      1309451.47      6917636.55      1308660.58      6918043.58
      1308549.48      6918540.43      1308065.76      6918978.32
      1307999.96      6919233.08      1307653.37      6918991.13
      1307452.57      6919043.52      1307032.33      6919562.01
      1306815.50      6919678.18      1306706.74      6919994.16
      1307304.33      6920503.84      1307254.96      6920918.01
      1307354.52      6921172.80      1307107.06      6921443.85
      1307205.04      6921968.01      1307054.61      6922267.87
      1307102.40      6922433.04      1307255.00      6922388.00

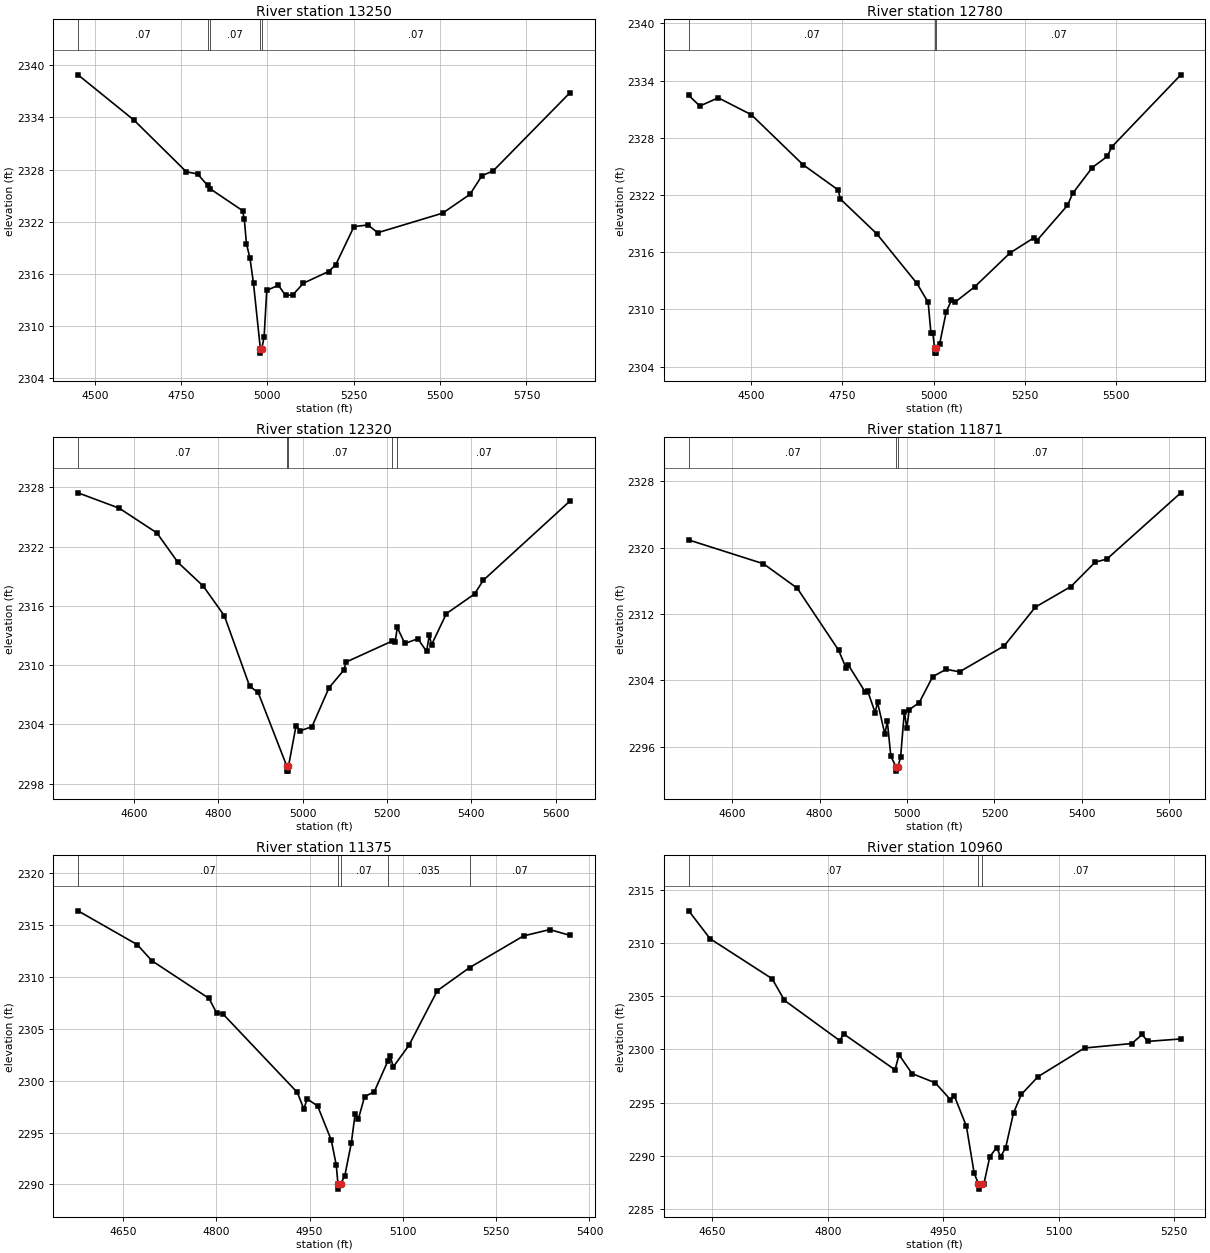
Type RM Length L Ch R = 1,13250,470,470,470
BEGIN DESCRIPTION:
Buffalo Creek Trib 08 29.0
END DESCRIPTION:
XS GIS Cut Line= 3
      1309169.17      6913707.96      1309705.00      6913588.00
      1310549.42      6913356.38
#Sta/Elev= 30
  4451.6 2338.91  4614.0 2333.68  4765.0 2327.75  4797.8 2327.49  4826.7 2326.18
  4834.1 2325.79  4927.9 2323.27  4933.1 2322.29  4939.2 2319.48  4949.5 2317.78
  4959.7 2314.88  4979.6 2307.36  4979.8 2306.86  4983.6 2307.36  4990.4 2308.73
  4998.1 2314.09  5031.8 2314.67  5052.4 2313.52  5073.3 2313.56  5104.4 2314.92
  5177.0 2316.26  5197.7 2317.03  5250.6 2321.43  5291.0 2321.62  5319.5 2320.73
  5507.3 2322.98  5586.6 2325.15  5621.1 2327.29  5654.0 2327.86  5876.3 2336.86
#Mann=5,-1,0
  4451.6    0.07       0  4826.7   0.035       0  4834.1    0.07       0
  4979.6    0.07       0  4983.6    0.07       0
Bank Sta=4979.6,4983.6
Exp/Cntr=0.3,0.1

Type RM Length L Ch R = 1,12780,460,460,460
BEGIN DESCRIPTION:
Buffalo Creek Trib 08 28.0
END DESCRIPTION:
XS GIS Cut Line= 3
      1309394.86      6913929.31      1310055.00      6913838.00
      1310691.32      6913591.27
#Sta/Elev= 30
  4329.0 2332.44  4359.4 2331.33  4409.9 2332.19  4500.8 2330.41  4642.1 2325.18
  4739.0 2322.52  4744.0 2321.60  4844.0 2317.95  4954.5 2312.73  4985.3 2310.74
  4992.9 2307.52  4998.1 2307.52  5003.0 2305.92  5003.3 2305.42  5006.8 2305.42
  5007.0 2305.92  5016.9 2306.41  5034.9 2309.78  5049.1 2310.94  5059.5 2310.78
  5113.4 2312.39  5209.9 2315.93  5274.3 2317.49  5282.8 2317.20  5367.2 2320.91
  5381.5 2322.17  5435.2 2324.88  5476.1 2326.04  5488.8 2327.05  5677.9 2334.60
#Mann=3,-1,0
  4329.0    0.07       0  5003.0    0.07       0  5007.0    0.07       0
Bank Sta=5003,5007
Exp/Cntr=0.3,0.1

Type RM Length L Ch R = 1,12320,449,449,449
BEGIN DESCRIPTION:
Buffalo Creek Trib 08 27.0
END DESCRIPTION:
XS GIS Cut Line= 3
      1309768.16      6914194.06      1310305.00      6914188.00
      1310914.04      6914029.12
#Sta/Elev= 30
  4467.7 2327.46  4565.5 2325.90  4654.6 2323.40  4704.6 2320.41  4764.6 2318.01
  4814.6 2315.00  4874.6 2307.86  4894.6 2307.24  4962.6 2299.77  4962.8 2299.27
  4966.3 2299.27  4966.6 2299.77  4984.6 2303.89  4994.6 2303.36  5022.2 2303.77
  5062.7 2307.72  5097.6 2309.49  5103.2 2310.32  5211.1 2312.42  5219.4 2312.30
  5224.4 2313.83  5242.3 2312.20  5273.3 2312.68  5293.9 2311.39  5300.4 2313.05
  5305.6 2312.06  5340.9 2315.23  5407.6 2317.21  5428.3 2318.60  5634.0 2326.64
#Mann=5,-1,0
  4467.7    0.07       0  4962.6    0.07       0  4966.6    0.07       0
  5211.1   0.035       0  5224.4    0.07       0
Bank Sta=4962.6,4966.6
Exp/Cntr=0.3,0.1

Type RM Length L Ch R = 1,11871,496,496,496
BEGIN DESCRIPTION:
Buffalo Creek Trib 08 26.0
END DESCRIPTION:
XS GIS Cut Line= 3
      1310002.55      6914359.00      1310455.00      6914588.00
      1311060.80      6914463.31
#Sta/Elev= 30
  4500.7 2320.91  4671.6 2318.04  4748.8 2315.10  4843.5 2307.62  4860.2 2305.52
  4865.8 2305.83  4904.7 2302.55  4910.3 2302.66  4927.0 2300.11  4932.6 2301.33
  4949.3 2297.51  4954.9 2299.07  4963.0 2294.82  4975.1 2293.55  4975.4 2293.05
  4979.2 2293.55  4985.4 2294.79  4993.9 2300.23  4999.5 2298.21  5005.0 2300.45
  5027.9 2301.31  5058.8 2304.44  5089.5 2305.32  5120.1 2305.02  5222.2 2308.14
  5293.7 2312.82  5375.0 2315.30  5430.5 2318.24  5457.0 2318.60  5626.3 2326.59
#Mann=3,-1,0
  4500.7    0.07       0  4975.1    0.07       0  4979.2    0.07       0
Bank Sta=4975.1,4979.2
Exp/Cntr=0.3,0.1

Type RM Length L Ch R = 1,11375,415,415,415
BEGIN DESCRIPTION:
Buffalo Creek Trib 08 25.0
END DESCRIPTION:
XS GIS Cut Line= 3
      1310071.97      6914515.21      1310241.87      6914901.83
      1310367.11      6915248.71
#Sta/Elev= 30
  4577.7 2316.39  4672.9 2313.13  4696.3 2311.58  4788.3 2307.94  4800.6 2306.53
  4810.1 2306.48  4930.3 2298.87  4940.7 2297.28  4946.2 2298.25  4963.0 2297.55
  4984.9 2294.26  4992.9 2291.86  4995.6 2290.04  4995.9 2289.54  4999.8 2290.04
  5006.6 2290.82  5017.2 2294.03  5023.2 2296.77  5028.5 2296.33  5038.5 2298.47
  5053.9 2298.92  5075.7 2301.88  5079.3 2302.43  5084.6 2301.34  5109.9 2303.43
  5155.4 2308.69  5207.2 2310.91  5294.0 2313.97  5336.1 2314.58  5368.8 2314.02
#Mann=5,-1,0
  4577.7    0.07       0  4995.6    0.07       0  4999.8    0.07       0
  5075.7   0.035       0  5207.2    0.07       0
Bank Sta=4995.6,4999.8
Exp/Cntr=0.3,0.1

Type RM Length L Ch R = 1,10960,458,458,458
BEGIN DESCRIPTION:
Buffalo Creek Trib 08 24.0
END DESCRIPTION:
XS GIS Cut Line= 3
      1309802.88      6914610.70      1309855.00      6914988.00
      1309911.40      6915240.09
#Sta/Elev= 30
  4619.2 2313.00  4646.8 2310.39  4727.5 2306.63  4743.5 2304.60  4815.4 2300.82
  4820.4 2301.45  4887.2 2298.08  4892.3 2299.50  4909.2 2297.73  4939.5 2296.86
  4959.1 2295.28  4964.1 2295.66  4979.9 2292.78  4990.0 2288.37  4995.5 2287.39
  4995.8 2286.89  4999.7 2287.39  5002.6 2287.39  5010.3 2289.94  5019.2 2290.79
  5024.3 2289.94  5030.8 2290.76  5041.1 2294.05  5051.3 2295.78  5072.9 2297.44
  5133.3 2300.13  5194.8 2300.55  5208.2 2301.40  5215.3 2300.75  5258.4 2300.98
#Mann=3,-1,0
  4619.2    0.07       0  4995.5    0.07       0  4999.7    0.07       0
Bank Sta=4995.5,4999.7
Exp/Cntr=0.3,0.1

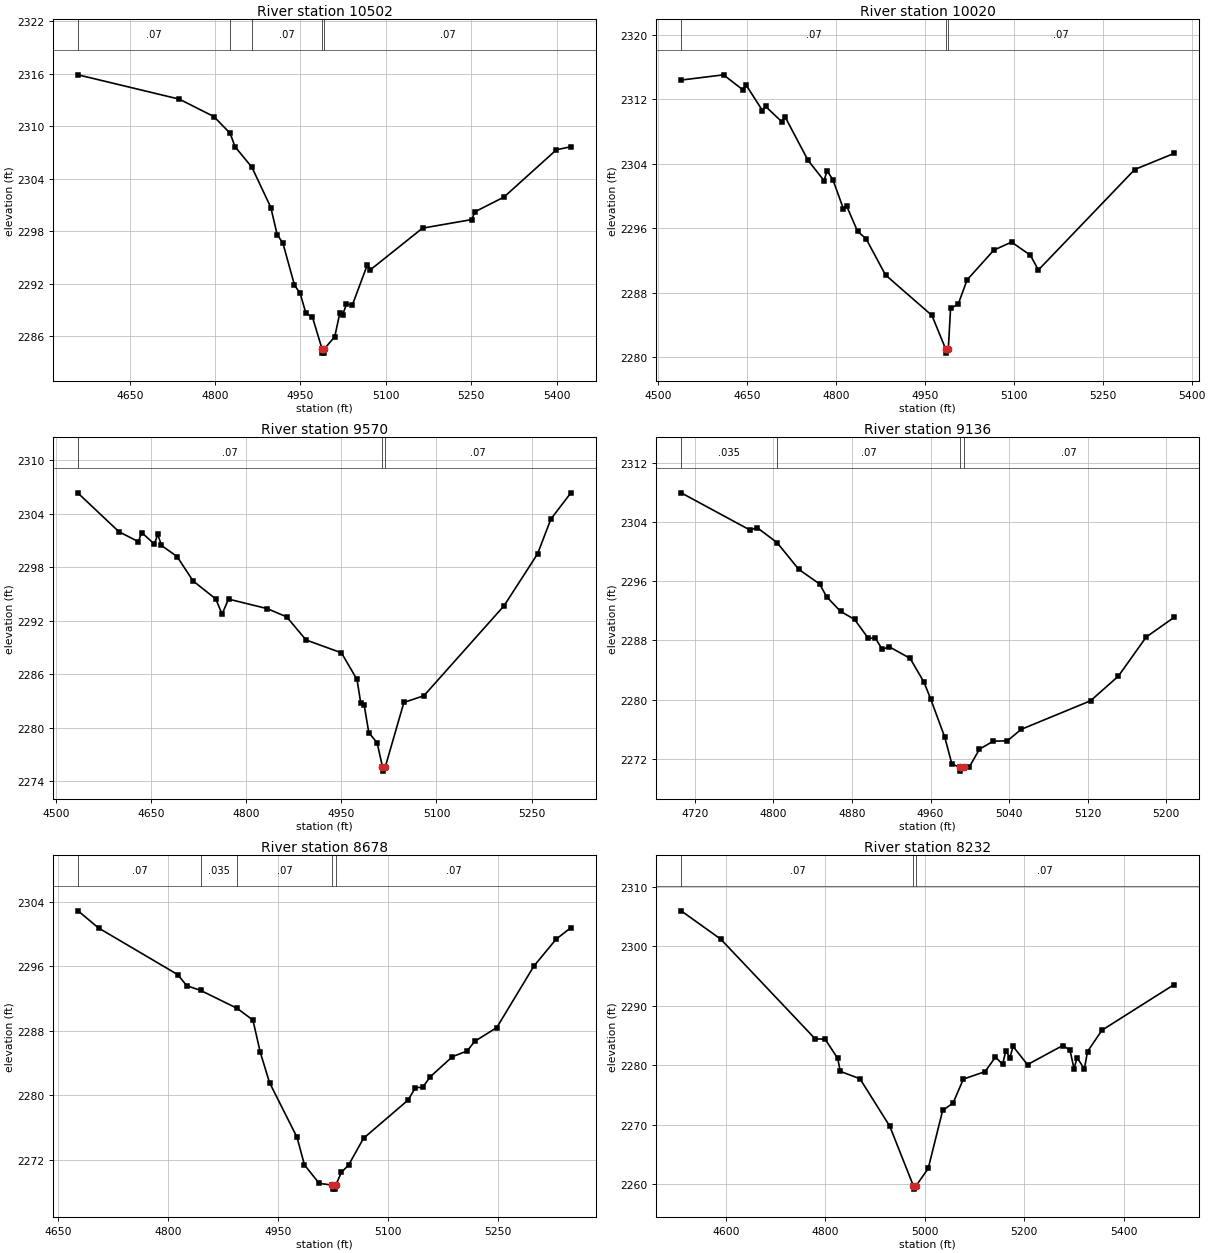
Type RM Length L Ch R = 1,10502,482,482,482
BEGIN DESCRIPTION:
Buffalo Creek Trib 08 23.0
END DESCRIPTION:
XS GIS Cut Line= 3
      1309169.20      6915170.62      1309605.00      6915238.00
      1310019.88      6915331.21
#Sta/Elev= 30
  4559.1 2315.90  4737.0 2313.12  4797.7 2311.13  4826.5 2309.21  4834.8 2307.69
  4864.6 2305.34  4897.9 2300.73  4909.0 2297.64  4919.1 2296.66  4939.4 2291.87
  4949.5 2290.90  4959.6 2288.62  4971.1 2288.19  4987.8 2284.58  4988.1 2284.08
  4991.9 2284.08  4992.2 2284.58  5010.3 2285.97  5019.2 2288.68  5024.3 2288.48
  5030.8 2289.68  5041.1 2289.57  5067.6 2294.19  5072.7 2293.60  5164.5 2298.37
  5251.1 2299.35  5256.3 2300.23  5307.6 2301.92  5399.8 2307.33  5425.3 2307.68
#Mann=5,-1,0
  4559.1    0.07       0  4826.5   0.035       0  4864.6    0.07       0
  4987.8    0.07       0  4992.2    0.07       0
Bank Sta=4987.8,4992.2
Exp/Cntr=0.3,0.1

Type RM Length L Ch R = 1,10020,450,450,450
BEGIN DESCRIPTION:
Buffalo Creek Trib 08 22.0
END DESCRIPTION:
XS GIS Cut Line= 3
      1309260.32      6915552.56      1309705.00      6915688.00
      1310058.93      6915782.59
#Sta/Elev= 30
  4539.0 2314.36  4610.5 2315.01  4643.3 2313.14  4648.6 2313.74  4676.2 2310.58
  4681.4 2311.09  4709.0 2309.18  4714.3 2309.80  4753.0 2304.41  4779.9 2301.90
  4785.2 2303.08  4794.8 2302.03  4812.8 2298.37  4818.0 2298.77  4836.6 2295.60
  4850.8 2294.69  4883.7 2290.19  4962.0 2285.17  4985.2 2281.00  4985.5 2280.50
  4989.6 2281.00  4993.4 2286.04  5006.4 2286.59  5021.3 2289.59  5066.5 2293.28
  5096.3 2294.27  5128.1 2292.63  5141.5 2290.81  5304.0 2303.27  5370.2 2305.26
#Mann=3,-1,0
  4539.0    0.07       0  4985.2    0.07       0  4989.6    0.07       0
Bank Sta=4985.2,4989.6
Exp/Cntr=0.3,0.1

Type RM Length L Ch R = 1,9570,434,434,434
BEGIN DESCRIPTION:
Buffalo Creek Trib 08 21.0
END DESCRIPTION:
XS GIS Cut Line= 3
      1309121.46      6915930.17      1309555.00      6916088.00
      1309855.00      6916188.00
#Sta/Elev= 30
  4534.5 2306.28  4599.0 2301.96  4629.6 2300.85  4634.9 2301.87  4654.9 2300.57
  4660.2 2301.67  4666.0 2300.43  4690.8 2299.17  4716.0 2296.44  4751.9 2294.42
  4761.7 2292.72  4771.9 2294.41  4833.0 2293.34  4863.6 2292.42  4894.2 2289.83
  4950.0 2288.39  4974.6 2285.40  4980.6 2282.73  4985.9 2282.55  4993.2 2279.45
  5006.4 2278.30  5014.7 2275.63  5015.0 2275.13  5019.3 2275.63  5048.6 2282.83
  5080.2 2283.58  5206.7 2293.67  5259.4 2299.47  5280.5 2303.38  5312.1 2306.32
#Mann=3,-1,0
  4534.5    0.07       0  5014.7    0.07       0  5019.3    0.07       0
Bank Sta=5014.7,5019.3
Exp/Cntr=0.3,0.1

Type RM Length L Ch R = 1,9136,458,458,458
BEGIN DESCRIPTION:
Buffalo Creek Trib 08 20.0
END DESCRIPTION:
XS GIS Cut Line= 3
      1309156.16      6916177.54      1309355.00      6916388.00
      1309505.02      6916538.02
#Sta/Elev= 30
  4706.1 2307.94  4776.2 2302.91  4783.4 2303.24  4803.7 2301.22  4825.9 2297.59
  4847.0 2295.63  4854.2 2293.90  4868.4 2291.91  4882.6 2290.84  4896.7 2288.26
  4903.6 2288.33  4910.9 2286.78  4917.8 2287.15  4939.2 2285.57  4953.4 2282.33
  4960.2 2280.05  4974.4 2274.94  4981.7 2271.31  4989.9 2270.83  4990.2 2270.33
  4994.5 2270.83  4999.2 2270.83  5009.8 2273.30  5023.9 2274.38  5038.1 2274.42
  5052.2 2275.97  5122.9 2279.84  5151.2 2283.17  5179.5 2288.45  5207.8 2291.10
#Mann=4,-1,0
  4706.1   0.035       0  4803.7    0.07       0  4989.9    0.07       0
  4994.5    0.07       0
Bank Sta=4989.9,4994.5
Exp/Cntr=0.3,0.1

Type RM Length L Ch R = 1,8678,446,446,446
BEGIN DESCRIPTION:
Buffalo Creek Trib 08 19.0
END DESCRIPTION:
XS GIS Cut Line= 3
      1308787.21      6916711.42      1309105.00      6916738.00
      1309455.05      6916788.01
#Sta/Elev= 30
  4677.1 2302.85  4705.0 2300.73  4813.2 2294.95  4825.4 2293.58  4844.4 2293.00
  4894.2 2290.78  4915.7 2289.33  4925.8 2285.32  4938.4 2281.58  4975.9 2274.82
  4986.0 2271.41  5006.1 2269.12  5024.0 2268.91  5024.3 2268.41  5028.3 2268.41
  5028.7 2268.91  5036.4 2270.47  5046.5 2271.43  5066.7 2274.71  5127.3 2279.42
  5137.4 2280.96  5147.5 2281.02  5157.6 2282.31  5187.9 2284.80  5208.1 2285.51
  5218.2 2286.69  5248.5 2288.41  5299.0 2296.00  5329.3 2299.33  5349.6 2300.77
#Mann=5,-1,0
  4677.1    0.07       0  4844.4   0.035       0  4894.2    0.07       0
  5024.0    0.07       0  5028.7    0.07       0
Bank Sta=5024,5028.7
Exp/Cntr=0.3,0.1

Type RM Length L Ch R = 1,8232,418,418,418
BEGIN DESCRIPTION:
Buffalo Creek Trib 08 18.0
END DESCRIPTION:
XS GIS Cut Line= 3
      1308865.37      6917102.05      1309355.00      6917088.00
      1309755.12      6916785.22
#Sta/Elev= 30
  4509.9 2305.94  4589.6 2301.18  4779.6 2284.42  4799.6 2284.36  4825.0 2281.13
  4830.0 2278.96  4869.7 2277.71  4929.7 2269.73  4977.4 2259.66  4977.7 2259.16
  4982.1 2259.66  5007.0 2262.63  5036.1 2272.40  5056.9 2273.61  5077.8 2277.66
  5121.4 2278.91  5142.3 2281.36  5156.8 2280.14  5163.1 2282.43  5171.4 2281.26
  5177.7 2283.15  5206.8 2280.09  5277.5 2283.29  5292.1 2282.56  5300.4 2279.41
  5306.6 2281.27  5321.2 2279.34  5327.5 2282.29  5356.6 2285.87  5501.5 2293.53
#Mann=3,-1,0
  4509.9    0.07       0  4977.4    0.07       0  4982.1    0.07       0
Bank Sta=4977.4,4982.1
Exp/Cntr=0.3,0.1

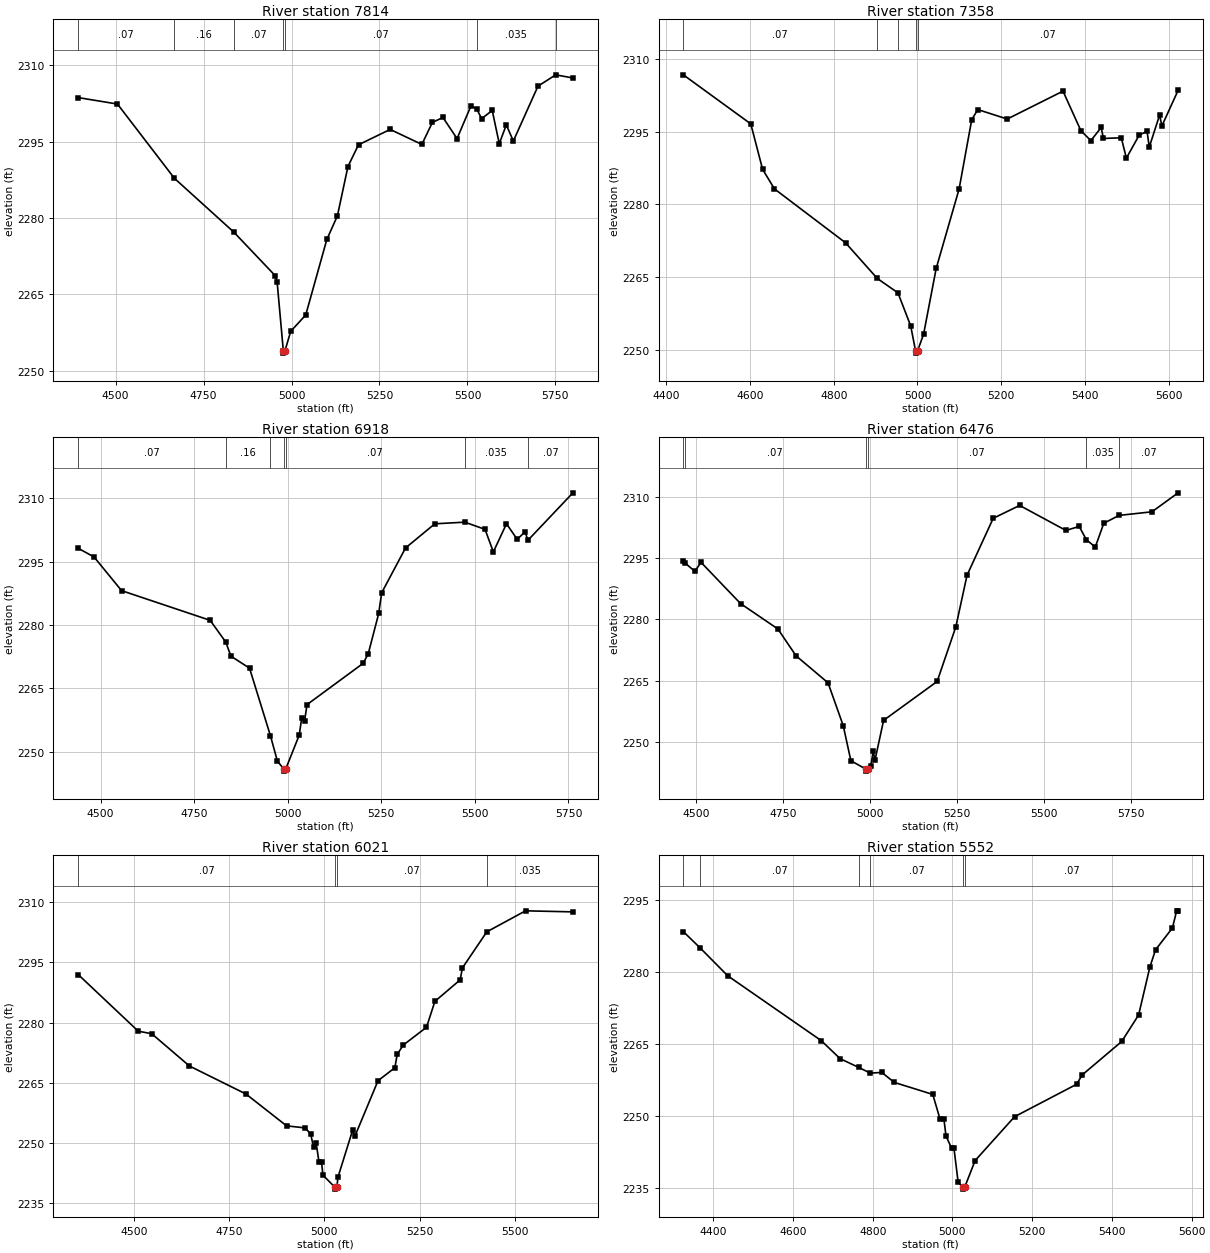
Type RM Length L Ch R = 1,7814,456,456,456
BEGIN DESCRIPTION:
Buffalo Creek Trib 08 17.0
END DESCRIPTION:
XS GIS Cut Line= 3
      1308882.75      6917236.59      1309455.00      6917438.00
      1310254.31      6917444.93
#Sta/Elev= 30
  4393.7 2303.68  4505.4 2302.41  4667.1 2287.83  4835.9 2277.26  4953.9 2268.68
  4959.2 2267.39  4976.7 2253.98  4977.1 2253.48  4981.6 2253.98  4997.7 2257.76
  5040.4 2260.97  5100.4 2275.81  5130.4 2280.44  5160.4 2290.14  5190.4 2294.41
  5280.4 2297.42  5370.4 2294.48  5400.4 2298.81  5430.4 2299.77  5470.4 2295.62
  5510.4 2302.12  5526.8 2301.36  5540.4 2299.54  5570.4 2301.15  5590.4 2294.63
  5610.4 2298.31  5630.4 2295.15  5700.4 2305.92  5750.8 2308.15  5799.7 2307.53
#Mann=7,-1,0
  4393.7    0.07       0  4667.1    0.16       0  4835.9    0.07       0
  4976.7    0.07       0  4981.6    0.07       0  5526.8   0.035       0
  5750.8    0.07       0
Bank Sta=4976.7,4981.6
Exp/Cntr=0.3,0.1

Type RM Length L Ch R = 1,7358,440,440,440
BEGIN DESCRIPTION:
Buffalo Creek Trib 08 16.0
END DESCRIPTION:
XS GIS Cut Line= 3
      1308856.71      6917388.51      1309255.00      6917788.00
      1309831.65      6918008.55
#Sta/Elev= 30
  4440.9 2306.68  4602.0 2296.57  4630.2 2287.21  4658.5 2283.18  4828.2 2272.08
  4903.9 2264.74  4953.4 2261.76  4983.8 2254.97  4995.4 2249.84  4995.8 2249.34
  5000.4 2249.84  5014.7 2253.25  5044.7 2266.78  5099.5 2283.17  5129.6 2297.44
  5144.2 2299.52  5214.4 2297.57  5347.6 2303.32  5390.4 2295.15  5414.1 2293.13
  5438.8 2295.83  5444.1 2293.57  5486.8 2293.71  5498.9 2289.51  5529.6 2294.27
  5548.3 2295.04  5553.6 2291.79  5578.3 2298.40  5583.7 2296.14  5622.4 2303.48
#Mann=5,-1,0
  4440.9    0.07       0  4903.9    0.16       0  4953.4    0.07       0
  4995.4    0.07       0  5000.4    0.07       0
Bank Sta=4995.4,5000.4
Exp/Cntr=0.3,0.1

Type RM Length L Ch R = 1,6918,442,442,442
BEGIN DESCRIPTION:
Buffalo Creek Trib 08 15.0
END DESCRIPTION:
XS GIS Cut Line= 3
      1308600.63      6917444.93      1308855.00      6917938.00
      1309446.98      6918425.83
#Sta/Elev= 30
  4439.9 2298.21  4482.4 2296.14  4555.9 2288.17  4792.7 2281.13  4834.5 2275.96
  4847.9 2272.66  4897.8 2269.80  4953.7 2253.78  4972.2 2247.78  4989.4 2245.91
  4989.8 2245.41  4994.5 2245.91  5030.6 2253.95  5037.0 2257.89  5044.9 2257.32
  5051.4 2261.17  5201.3 2270.94  5215.0 2273.22  5242.9 2282.76  5250.8 2287.65
  5314.6 2298.28  5392.8 2304.00  5473.0 2304.39  5527.0 2302.69  5549.2 2297.34
  5584.3 2304.01  5613.0 2300.32  5633.8 2302.10  5641.7 2300.11  5761.8 2311.34
#Mann=7,-1,0
  4439.9    0.07       0  4834.5    0.16       0  4953.7    0.07       0
  4989.4    0.07       0  4994.5    0.07       0  5473.0   0.035       0
  5641.7    0.07       0
Bank Sta=4989.4,4994.5
Exp/Cntr=0.3,0.1

Type RM Length L Ch R = 1,6476,455,455,455
BEGIN DESCRIPTION:
Buffalo Creek Trib 08 14.0
END DESCRIPTION:
XS GIS Cut Line= 3
      1308114.50      6918022.18      1308605.00      6918238.00
      1309429.64      6918560.39
#Sta/Elev= 30
  4464.2 2294.40  4468.0 2293.91  4497.5 2291.79  4514.9 2294.01  4628.6 2283.89
  4735.9 2277.66  4788.0 2271.09  4879.9 2264.47  4923.6 2253.96  4945.5 2245.38
  4988.5 2243.33  4988.9 2242.83  4993.7 2243.33  5002.8 2244.05  5009.6 2247.68
  5015.0 2245.60  5039.5 2255.27  5193.3 2264.80  5247.0 2278.18  5279.2 2290.83
  5354.4 2304.79  5430.4 2307.94  5563.4 2301.81  5601.4 2302.80  5622.0 2299.54
  5647.6 2297.74  5672.1 2303.57  5716.0 2305.50  5810.5 2306.38  5885.5 2311.03
#Mann=6,-1,0
  4464.2   0.035       0  4468.0    0.07       0  4988.5    0.07       0
  4993.7    0.07       0  5622.0   0.035       0  5716.0    0.07       0
Bank Sta=4988.5,4993.7
Exp/Cntr=0.3,0.1

Type RM Length L Ch R = 1,6021,469,469,469
BEGIN DESCRIPTION:
Buffalo Creek Trib 08 13.0
END DESCRIPTION:
XS GIS Cut Line= 3
      1307984.28      6918195.77      1308455.00      6918638.00
      1309034.61      6918937.96
#Sta/Elev= 30
  4354.1 2291.96  4511.8 2277.85  4547.2 2277.22  4646.1 2269.19  4794.6 2262.21
  4901.1 2254.29  4950.4 2253.77  4964.6 2252.18  4971.9 2248.93  4978.7 2250.02
  4986.0 2245.41  4992.9 2245.21  4996.5 2242.02  5027.7 2239.04  5028.2 2238.54
  5033.0 2239.04  5036.0 2241.52  5074.6 2253.26  5080.3 2251.69  5141.1 2265.53
  5185.3 2268.75  5191.4 2272.08  5207.5 2274.41  5268.3 2278.82  5290.4 2285.28
  5356.8 2290.64  5362.4 2293.57  5426.6 2302.58  5528.3 2307.81  5652.6 2307.55
#Mann=4,-1,0
  4354.1    0.07       0  5027.7    0.07       0  5033.0    0.07       0
  5426.6   0.035       0
Bank Sta=5027.7,5033
Exp/Cntr=0.3,0.1

Type RM Length L Ch R = 1,5552,429,429,429
BEGIN DESCRIPTION:
Buffalo Creek Trib 08 12.0
END DESCRIPTION:
XS GIS Cut Line= 3
      1307910.53      6918291.32      1308105.00      6918938.00
      1308505.02      6919338.02
#Sta/Elev= 30
  4325.0 2288.40  4367.4 2284.98  4436.4 2279.19  4670.9 2265.68  4718.3 2261.92
  4765.3 2260.08  4793.9 2258.91  4822.8 2259.05  4854.1 2256.97  4950.7 2254.47
  4969.0 2249.29  4978.6 2249.37  4983.8 2245.82  4997.7 2243.28  5003.8 2243.28
  5014.4 2236.12  5025.9 2235.23  5026.3 2234.73  5031.2 2235.23  5056.9 2240.68
  5155.8 2249.82  5311.4 2256.58  5325.6 2258.54  5424.6 2265.50  5467.0 2271.02
  5495.3 2281.03  5509.4 2284.60  5551.8 2289.16  5562.4 2292.73  5566.0 2292.73
#Mann=6,-1,0
  4325.0   0.035       0  4367.4    0.07       0  4765.3   0.035       0
  4793.9    0.07       0  5025.9    0.07       0  5031.2    0.07       0
Bank Sta=5025.9,5031.2
Exp/Cntr=0.3,0.1

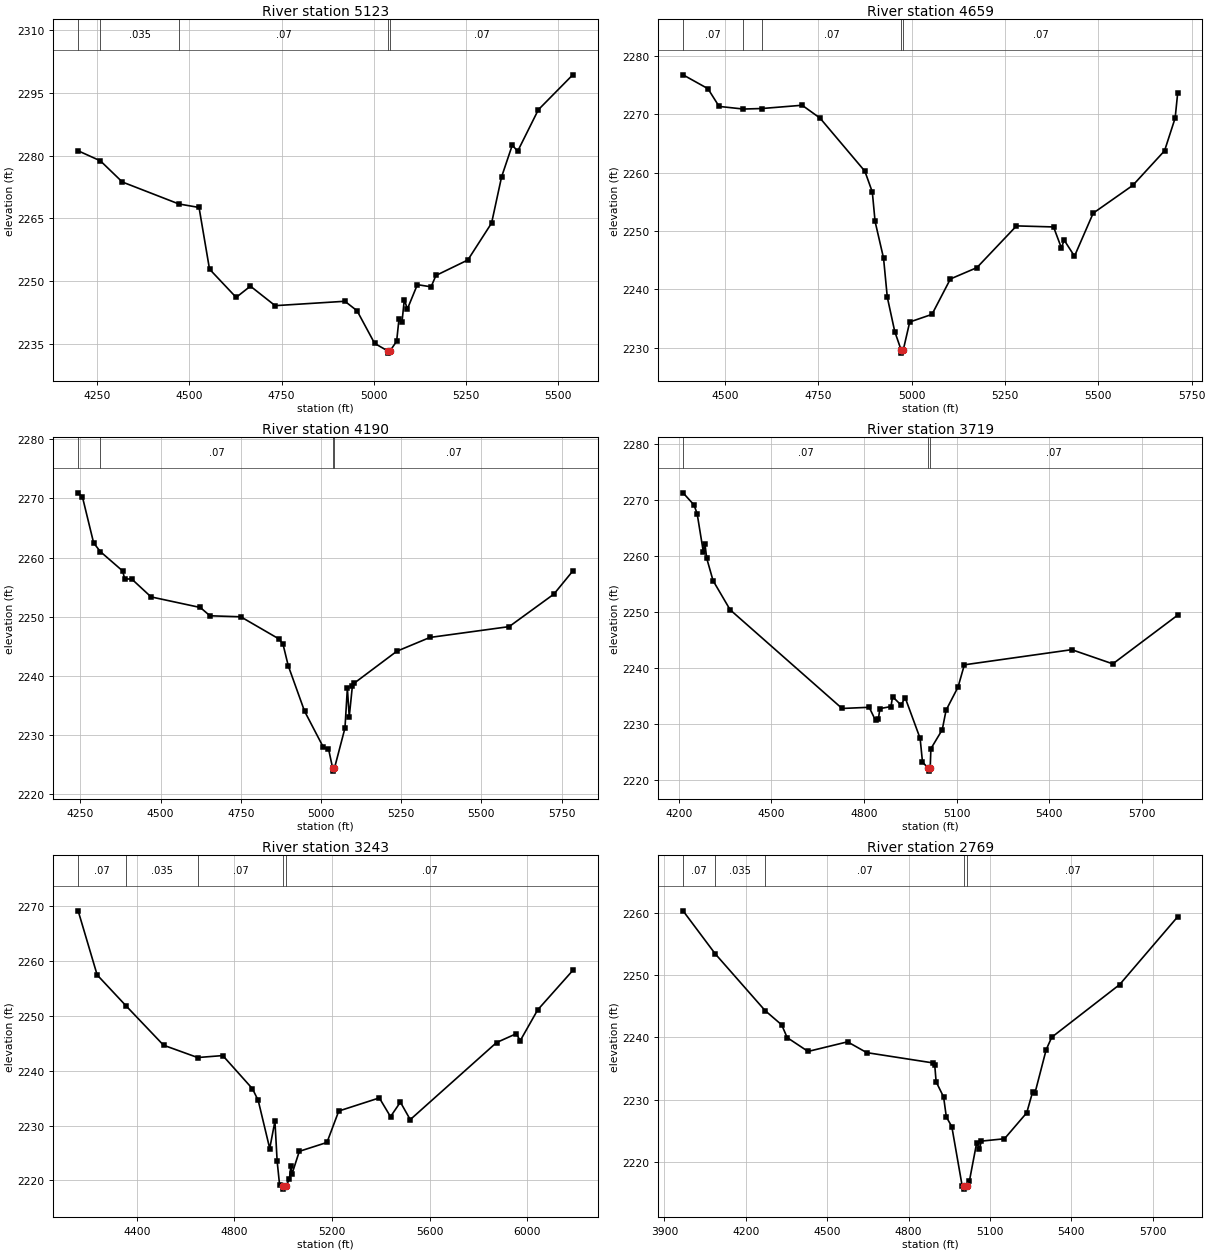
Type RM Length L Ch R = 1,5123,464,464,464
BEGIN DESCRIPTION:
Buffalo Creek Trib 08 11.0
END DESCRIPTION:
XS GIS Cut Line= 3
      1307680.00      6918462.99      1307905.00      6919238.00
      1308329.97      6919562.98
#Sta/Elev= 30
  4198.1 2281.16  4258.4 2278.76  4317.9 2273.69  4471.3 2268.43  4526.1 2267.59
  4554.5 2252.82  4626.8 2246.05  4665.5 2248.74  4732.6 2244.07  4921.8 2245.12
  4954.8 2242.85  5002.5 2235.03  5038.7 2233.20  5039.2 2232.70  5044.1 2233.20
  5062.2 2235.55  5068.5 2240.78  5076.8 2240.23  5083.1 2245.54  5091.3 2243.25
  5118.4 2249.10  5155.7 2248.58  5168.8 2251.30  5255.4 2255.01  5319.8 2263.85
  5346.9 2274.91  5376.0 2282.53  5390.5 2281.05  5446.7 2291.00  5540.1 2299.36
#Mann=5,-1,0
  4198.1    0.07       0  4258.4   0.035       0  4471.3    0.07       0
  5038.7    0.07       0  5044.1    0.07       0
Bank Sta=5038.7,5044.1
Exp/Cntr=0.3,0.1

Type RM Length L Ch R = 1,4659,469,469,469
BEGIN DESCRIPTION:
Buffalo Creek Trib 08 10.0
END DESCRIPTION:
XS GIS Cut Line= 3
      1307524.24      6918421.49      1307555.00      6919038.00
      1308030.02      6919563.02
#Sta/Elev= 30
  4387.3 2276.74  4453.9 2274.37  4483.9 2271.33  4548.9 2270.88  4598.7 2270.97
  4706.4 2271.53  4754.3 2269.33  4874.4 2260.24  4894.4 2256.67  4901.8 2251.63
  4924.5 2245.35  4934.5 2238.68  4954.5 2232.78  4971.8 2229.58  4972.3 2229.08
  4977.2 2229.58  4994.6 2234.41  5054.3 2235.72  5103.6 2241.78  5174.6 2243.72
  5280.7 2250.87  5380.0 2250.69  5401.0 2247.10  5408.4 2248.44  5436.1 2245.68
  5486.2 2253.05  5592.3 2257.81  5677.4 2263.73  5705.8 2269.34  5712.6 2273.63
#Mann=5,-1,0
  4387.3    0.07       0  4548.9   0.035       0  4598.7    0.07       0
  4971.8    0.07       0  4977.2    0.07       0
Bank Sta=4971.8,4977.2
Exp/Cntr=0.3,0.1

Type RM Length L Ch R = 1,4190,471,471,471
BEGIN DESCRIPTION:
Buffalo Creek Trib 08 9.0
END DESCRIPTION:
XS GIS Cut Line= 3
      1306851.51      6918625.51      1307205.00      6919288.00
      1307890.28      6919682.85
#Sta/Elev= 30
  4243.3 2270.93  4256.6 2270.25  4291.5 2262.48  4312.3 2261.01  4382.1 2257.73
  4388.3 2256.38  4410.3 2256.37  4470.5 2253.35  4624.1 2251.56  4654.2 2250.16
  4750.2 2249.99  4869.5 2246.24  4881.9 2245.35  4898.2 2241.72  4948.9 2234.06
  5007.9 2227.92  5023.6 2227.71  5036.6 2224.42  5037.0 2223.92  5042.3 2224.42
  5075.0 2231.20  5082.5 2237.94  5088.3 2233.08  5098.1 2238.30  5104.1 2238.79
  5236.6 2244.17  5339.7 2246.50  5586.8 2248.33  5726.2 2253.82  5785.1 2257.72
#Mann=4,-1,0
  4243.3   0.035       0  4312.3    0.07       0  5036.6    0.07       0
  5042.3    0.07       0
Bank Sta=5036.6,5042.3
Exp/Cntr=0.3,0.1

Type RM Length L Ch R = 1,3719,476,476,476
BEGIN DESCRIPTION:
Buffalo Creek Trib 08 8.0
END DESCRIPTION:
XS GIS Cut Line= 3
      1306712.61      6918833.84      1306905.00      6919588.00
      1307710.40      6919762.53
#Sta/Elev= 30
  4213.6 2271.29  4248.9 2269.13  4259.2 2267.58  4279.3 2260.73  4284.5 2262.18
  4290.1 2259.61  4310.8 2255.58  4366.2 2250.36  4728.8 2232.71  4816.5 2232.92
  4837.1 2230.59  4846.3 2230.85  4851.5 2232.69  4887.2 2233.05  4892.3 2234.83
  4919.7 2233.33  4933.2 2234.64  4981.6 2227.36  4989.3 2223.11  5008.5 2222.00
  5009.0 2221.50  5014.2 2222.00  5016.5 2225.51  5053.3 2228.91  5065.7 2232.40
  5104.5 2236.55  5124.9 2240.52  5472.8 2243.23  5605.8 2240.69  5816.0 2249.41
#Mann=3,-1,0
  4213.6    0.07       0  5008.5    0.07       0  5014.2    0.07       0
Bank Sta=5008.5,5014.2
Exp/Cntr=0.3,0.1

Type RM Length L Ch R = 1,3243,474,474,474
BEGIN DESCRIPTION:
Buffalo Creek Trib 08 7.0
END DESCRIPTION:
XS GIS Cut Line= 3
      1305879.25      6920114.20      1306705.00      6919988.00
      1307884.44      6919823.41
#Sta/Elev= 30
  4160.1 2269.15  4238.0 2257.46  4355.8 2251.85  4509.9 2244.65  4649.7 2242.40
  4752.6 2242.76  4874.0 2236.72  4897.7 2234.58  4944.9 2225.81  4966.2 2230.80
  4975.2 2223.53  4985.3 2219.17  4999.6 2218.91  5000.1 2218.41  5011.4 2218.91
  5025.7 2220.29  5031.2 2222.62  5036.2 2221.19  5066.1 2225.30  5179.3 2226.92
  5227.7 2232.65  5393.8 2235.04  5439.7 2231.62  5480.1 2234.27  5520.5 2231.08
  5873.9 2245.13  5954.6 2246.74  5971.0 2245.47  6042.5 2251.09  6186.3 2258.28
#Mann=5,-1,0
  4160.1    0.07       0  4355.8   0.035       0  4649.7    0.07       0
  4999.6    0.07       0  5011.4    0.07       0
Bank Sta=4999.6,5011.4
Exp/Cntr=0.3,0.1

Type RM Length L Ch R = 1,2769,417,417,417
BEGIN DESCRIPTION:
Buffalo Creek Trib 08 6.0
END DESCRIPTION:
XS GIS Cut Line= 3
      1306035.56      6920391.97      1307055.00      6920238.00
      1307828.09      6920066.45
#Sta/Elev= 30
  3968.7 2260.28  4087.1 2253.40  4271.2 2244.29  4332.2 2242.01  4352.4 2239.97
  4429.4 2237.75  4574.9 2239.29  4645.7 2237.56  4888.5 2235.92  4896.4 2235.50
  4901.4 2232.88  4928.9 2230.46  4939.0 2227.25  4959.2 2225.70  4997.2 2216.24
  5004.0 2216.19  5004.5 2215.69  5015.8 2216.19  5024.0 2216.99  5050.9 2223.13
  5061.2 2222.06  5067.6 2223.38  5153.3 2223.76  5235.3 2227.92  5257.2 2231.30
  5266.0 2231.15  5307.0 2238.04  5327.5 2240.03  5577.6 2248.46  5791.6 2259.33
#Mann=5,-1,0
  3968.7    0.07       0  4087.1   0.035       0  4271.2    0.07       0
  5004.0    0.07       0  5015.8    0.07       0
Bank Sta=5004,5015.8
Exp/Cntr=0.3,0.1

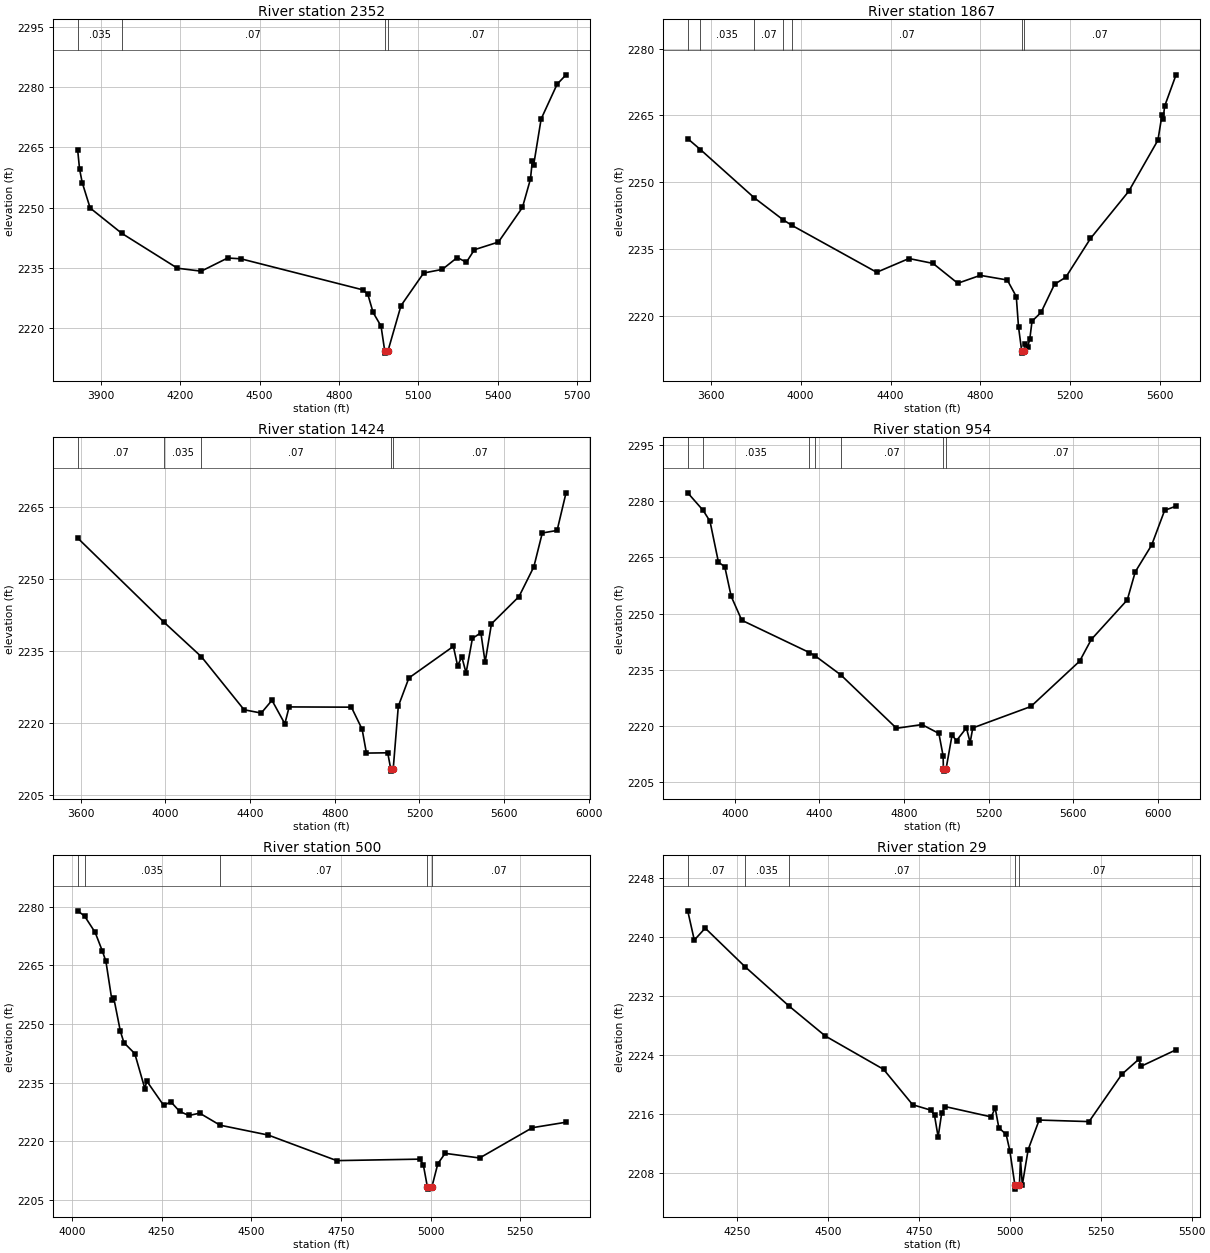
Type RM Length L Ch R = 1,2352,485,485,485
BEGIN DESCRIPTION:
Buffalo Creek Trib 08 5.0
END DESCRIPTION:
XS GIS Cut Line= 3
      1306117.99      6920569.93      1307305.00      6920538.00
      1307958.22      6920630.68
#Sta/Elev= 30
  3812.0 2264.24  3819.0 2259.60  3829.0 2256.24  3859.0 2249.89  3978.4 2243.60
  4189.1 2234.90  4279.2 2234.16  4379.2 2237.44  4429.2 2237.24  4889.4 2229.53
  4909.4 2228.41  4929.4 2223.87  4959.4 2220.48  4973.5 2214.25  4974.0 2213.75
  4985.4 2214.25  5034.9 2225.57  5120.6 2233.70  5191.3 2234.61  5247.7 2237.56
  5282.2 2236.38  5312.5 2239.50  5403.4 2241.41  5494.3 2250.03  5524.6 2257.10
  5531.5 2261.51  5536.6 2260.55  5565.0 2272.06  5625.6 2280.74  5659.2 2283.06
#Mann=4,-1,0
  3812.0   0.035       0  3978.4    0.07       0  4973.5    0.07       0
  4985.4    0.07       0
Bank Sta=4973.5,4985.4
Exp/Cntr=0.3,0.1

Type RM Length L Ch R = 1,1867,443,443,443
BEGIN DESCRIPTION:
Buffalo Creek Trib 08 4.0
END DESCRIPTION:
XS GIS Cut Line= 3
      1305805.50      6920886.77      1307305.00      6920988.00
      1307975.63      6920960.55
#Sta/Elev= 30
  3497.1 2259.81  3553.8 2257.36  3793.7 2246.55  3921.2 2241.66  3959.5 2240.43
  4338.5 2229.88  4482.1 2232.96  4589.1 2231.87  4699.3 2227.42  4799.6 2229.19
  4919.8 2228.15  4959.9 2224.44  4969.9 2217.61  4984.0 2212.27  4984.5 2211.77
  4995.9 2212.27  4997.5 2213.92  5010.0 2213.06  5020.0 2214.91  5030.0 2218.92
  5070.1 2220.88  5130.1 2227.19  5180.2 2228.76  5290.3 2237.45  5460.4 2248.01
  5590.5 2259.47  5608.4 2265.05  5613.4 2264.16  5620.5 2267.10  5671.2 2274.11
#Mann=7,-1,0
  3497.1    0.07       0  3553.8   0.035       0  3793.7    0.07       0
  3921.2   0.035       0  3959.5    0.07       0  4984.0    0.07       0
  4995.9    0.07       0
Bank Sta=4984,4995.9
Exp/Cntr=0.3,0.1

Type RM Length L Ch R = 1,1424,470,470,470
BEGIN DESCRIPTION:
Buffalo Creek Trib 08 3.0
END DESCRIPTION:
XS GIS Cut Line= 3
      1305809.86      6921103.79      1307205.00      6921338.00
      1308097.18      6921316.45
#Sta/Elev= 30
  3585.6 2258.50  3993.9 2240.94  4170.4 2233.75  4371.6 2222.72  4452.7 2222.03
  4503.4 2224.69  4564.2 2219.79  4584.5 2223.31  4878.6 2223.26  4929.3 2218.66
  4949.6 2213.69  5050.3 2213.75  5064.3 2210.43  5064.8 2209.93  5076.3 2210.43
  5100.3 2223.46  5150.3 2229.35  5360.4 2235.93  5380.4 2231.90  5400.4 2233.73
  5420.4 2230.40  5450.4 2237.59  5490.4 2238.76  5510.4 2232.62  5540.4 2240.63
  5670.5 2246.31  5740.5 2252.50  5780.5 2259.56  5850.5 2260.09  5892.7 2267.93
#Mann=5,-1,0
  3585.6    0.07       0  3993.9   0.035       0  4170.4    0.07       0
  5064.3    0.07       0  5076.3    0.07       0
Bank Sta=5064.3,5076.3
Exp/Cntr=0.3,0.1

Type RM Length L Ch R = 1,954,454,454,454
BEGIN DESCRIPTION:
Buffalo Creek Trib 08 2.0
END DESCRIPTION:
XS GIS Cut Line= 3
      1305940.06      6921815.58      1307155.00      6921738.00
      1308175.32      6921351.16
#Sta/Elev= 30
  3777.8 2282.25  3850.4 2277.58  3883.0 2274.67  3923.0 2263.74  3953.1 2262.49
  3983.2 2254.62  4033.3 2248.22  4353.5 2239.58  4380.2 2238.71  4501.9 2233.61
  4764.8 2219.37  4885.0 2220.36  4965.2 2218.00  4985.2 2211.99  4986.6 2208.43
  4987.1 2207.93  4998.8 2208.43  5027.3 2217.49  5048.7 2216.09  5095.4 2219.48
  5112.9 2215.56  5125.5 2219.47  5400.2 2225.19  5630.7 2237.30  5685.7 2243.09
  5855.8 2253.65  5893.6 2261.15  5971.1 2268.30  6032.6 2277.58  6086.4 2278.69
#Mann=7,-1,0
  3777.8    0.07       0  3850.4   0.035       0  4353.5    0.07       0
  4380.2   0.035       0  4501.9    0.07       0  4986.6    0.07       0
  4998.8    0.07       0
Bank Sta=4986.6,4998.8
Exp/Cntr=0.3,0.1

Type RM Length L Ch R = 1,500,471,471,471
BEGIN DESCRIPTION:
Buffalo Creek Trib 08 1.0
END DESCRIPTION:
XS GIS Cut Line= 4
      1306126.71      6922032.60      1307105.00      6922138.00
      1307226.07      6922159.82      1307358.32      6921942.00
#Sta/Elev= 30
  4016.1 2278.90  4035.2 2277.56  4064.7 2273.40  4084.8 2268.64  4094.8 2265.98
  4111.5 2256.03  4116.6 2256.67  4135.1 2248.13  4145.1 2245.21  4175.3 2242.43
  4203.5 2233.44  4208.5 2235.44  4255.8 2229.21  4275.9 2230.12  4300.4 2227.67
  4326.2 2226.63  4356.3 2227.22  4413.1 2224.15  4547.4 2221.63  4738.5 2215.10
  4969.9 2215.48  4979.9 2214.04  4991.4 2208.32  4991.9 2207.82  5003.6 2208.32
  5020.4 2214.31  5040.7 2216.96  5136.9 2215.77  5284.0 2223.51  5377.9 2224.91
#Mann=5,-1,0
  4016.1    0.07       0  4035.2   0.035       0  4413.1    0.07       0
  4991.4    0.07       0  5003.6    0.07       0
Bank Sta=4991.4,5003.6
Exp/Cntr=0.3,0.1

Type RM Length L Ch R = 1,29,0,0,0
BEGIN DESCRIPTION:
Buffalo Creek Trib 08 0.8
END DESCRIPTION:
XS GIS Cut Line= 4
      1306446.91      6922540.21      1307210.81      6922508.38
      1307242.64      6922253.74      1307369.96      6921958.18
#Sta/Elev= 30
  4114.1 2243.53  4132.2 2239.56  4162.2 2241.18  4271.7 2235.95  4392.3 2230.63
  4492.5 2226.55  4652.7 2222.03  4732.7 2217.23  4782.8 2216.49  4792.8 2215.78
  4802.8 2212.86  4812.8 2216.17  4822.8 2216.97  4948.7 2215.58  4959.7 2216.78
  4969.7 2214.11  4989.9 2213.19  5000.0 2210.99  5014.0 2206.28  5014.5 2205.78
  5026.3 2206.28  5029.3 2209.81  5034.3 2206.36  5050.4 2211.14  5080.6 2215.15
  5217.8 2214.94  5307.9 2221.35  5355.0 2223.41  5360.4 2222.43  5457.1 2224.68
#Mann=5,-1,0
  4114.1    0.07       0  4271.7   0.035       0  4392.3    0.07       0
  5014.0    0.07       0  5026.3    0.07       0
Bank Sta=5014,5026.3
Exp/Cntr=0.3,0.1

Chan Stop Cuts=-1