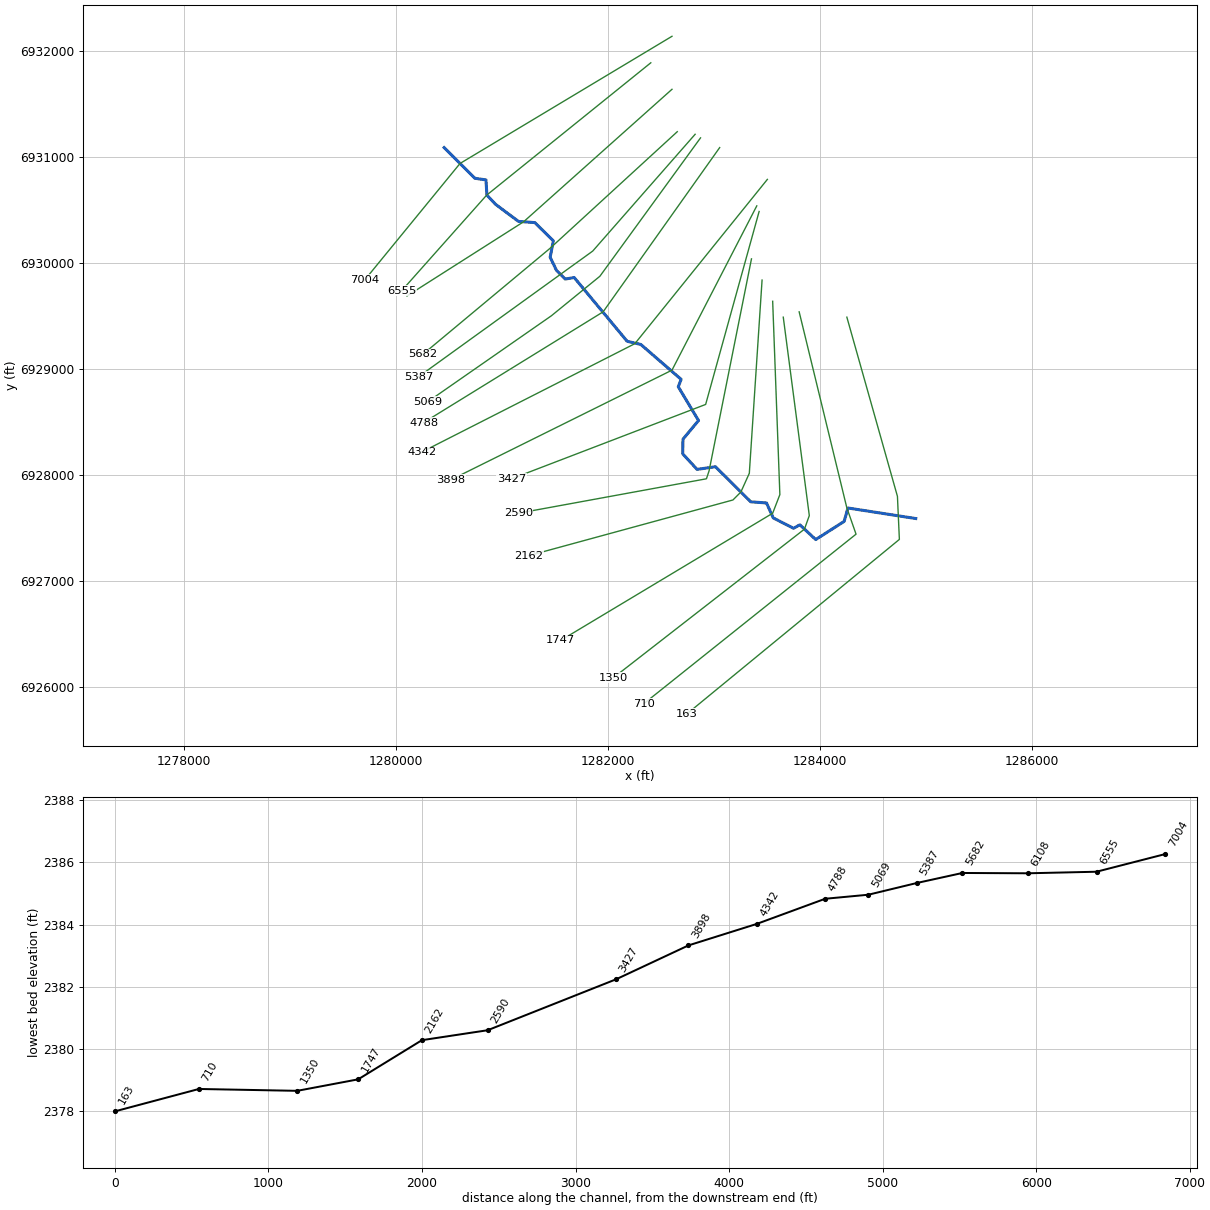
--- Buffalo Creek Trib 09-01.prj (project) ---

Proj Title=Buffalo Creek Trib 09-01 Base Level Engineering
Current Plan=p01
Default Exp/Contr=0.3,0.1
English Units
Geom File=g01
Flow File=f01
Plan File=p01
BEGIN DESCRIPTION:
Buffalo Creek Trib 09-01
END DESCRIPTION:

--- Buffalo Creek Trib 09-01.p01 (plan) ---

Plan Title=Multiple Run
Short Identifier=Multiple
Geom File=g01
Flow File=f01
Subcritical Flow
K Sum by GR= 0
Std Step Tol= 0.01
Critical Tol= 0.01
Num of Std Step Trials= 20
Max Error Tol= 0.3
Flow Tol Ratio= 0.001
Split Flow NTrial= 30
Split Flow Tol= 0.02
Split Flow Ratio= 0.02
Log Output Level= 0
Friction Slope Method= 1
Unsteady Friction Slope Method= 2
Unsteady Bridges Friction Slope Method= 1
Parabolic Critical Depth
Global Vel Dist=  1 , 1 , 1
Global Log Level= 0
CheckData=True
Encroach Param= -1, 0, 0, 0
BEGIN DESCRIPTION:
Multiple Run
END DESCRIPTION:

--- Buffalo Creek Trib 09-01.f01 (steady flow) ---

Flow Title=Multiple
Number of Profiles=7
Profile Names=10-year,25-year,50-year,1pct_min,100-year,1pct_plu,500-year
River Rch & RM= Buffalo Creek Tr,Reach-1,7004
     228     312     379     228     456     909     669
River Rch & RM= Buffalo Creek Tr,Reach-1,710
     289     399     489     297     594    1184     885
Boundary for River Rch & Prof#=Buffalo Creek Tr,Reach-1,1
Up Type=0
Dn Type=3
Dn Slope=0.005
Boundary for River Rch & Prof#=Buffalo Creek Tr,Reach-1,2
Up Type=0
Dn Type=3
Dn Slope=0.005
Boundary for River Rch & Prof#=Buffalo Creek Tr,Reach-1,3
Up Type=0
Dn Type=3
Dn Slope=0.005
Boundary for River Rch & Prof#=Buffalo Creek Tr,Reach-1,4
Up Type=0
Dn Type=3
Dn Slope=0.005
Boundary for River Rch & Prof#=Buffalo Creek Tr,Reach-1,5
Up Type=0
Dn Type=3
Dn Slope=0.005
Boundary for River Rch & Prof#=Buffalo Creek Tr,Reach-1,6
Up Type=0
Dn Type=3
Dn Slope=0.005
Boundary for River Rch & Prof#=Buffalo Creek Tr,Reach-1,7
Up Type=0
Dn Type=3
Dn Slope=0.005

--- Buffalo Creek Trib 09-01.g01 (geometry) ---

Geom Title=Existing Conditions

River Reach=Buffalo Creek Tr,Reach-1
Reach XY= 30
      1280455.00      6931088.00      1280745.26      6930798.54
      1280849.96      6930782.92      1280858.54      6930639.46
      1280941.76      6930551.62      1281156.47      6930391.54
      1281311.19      6930380.18      1281485.71      6930208.03
      1281455.37      6930053.27      1281515.76      6929928.27
      1281598.32      6929847.30      1281681.98      6929862.36
      1282181.43      6929260.86      1282311.17      6929230.14
      1282691.36      6928901.36      1282664.32      6928831.34
      1282855.51      6928512.96      1282708.53      6928336.53
      1282706.03      6928198.44      1282841.67      6928051.64
      1283014.99      6928076.75      1283348.55      6927745.74
      1283496.72      6927734.93      1283560.58      6927593.58
      1283751.77      6927496.25      1283811.67      6927528.70
      1283961.05      6927389.58      1284229.36      6927561.02
      1284265.30      6927687.40      1284905.00      6927588.00

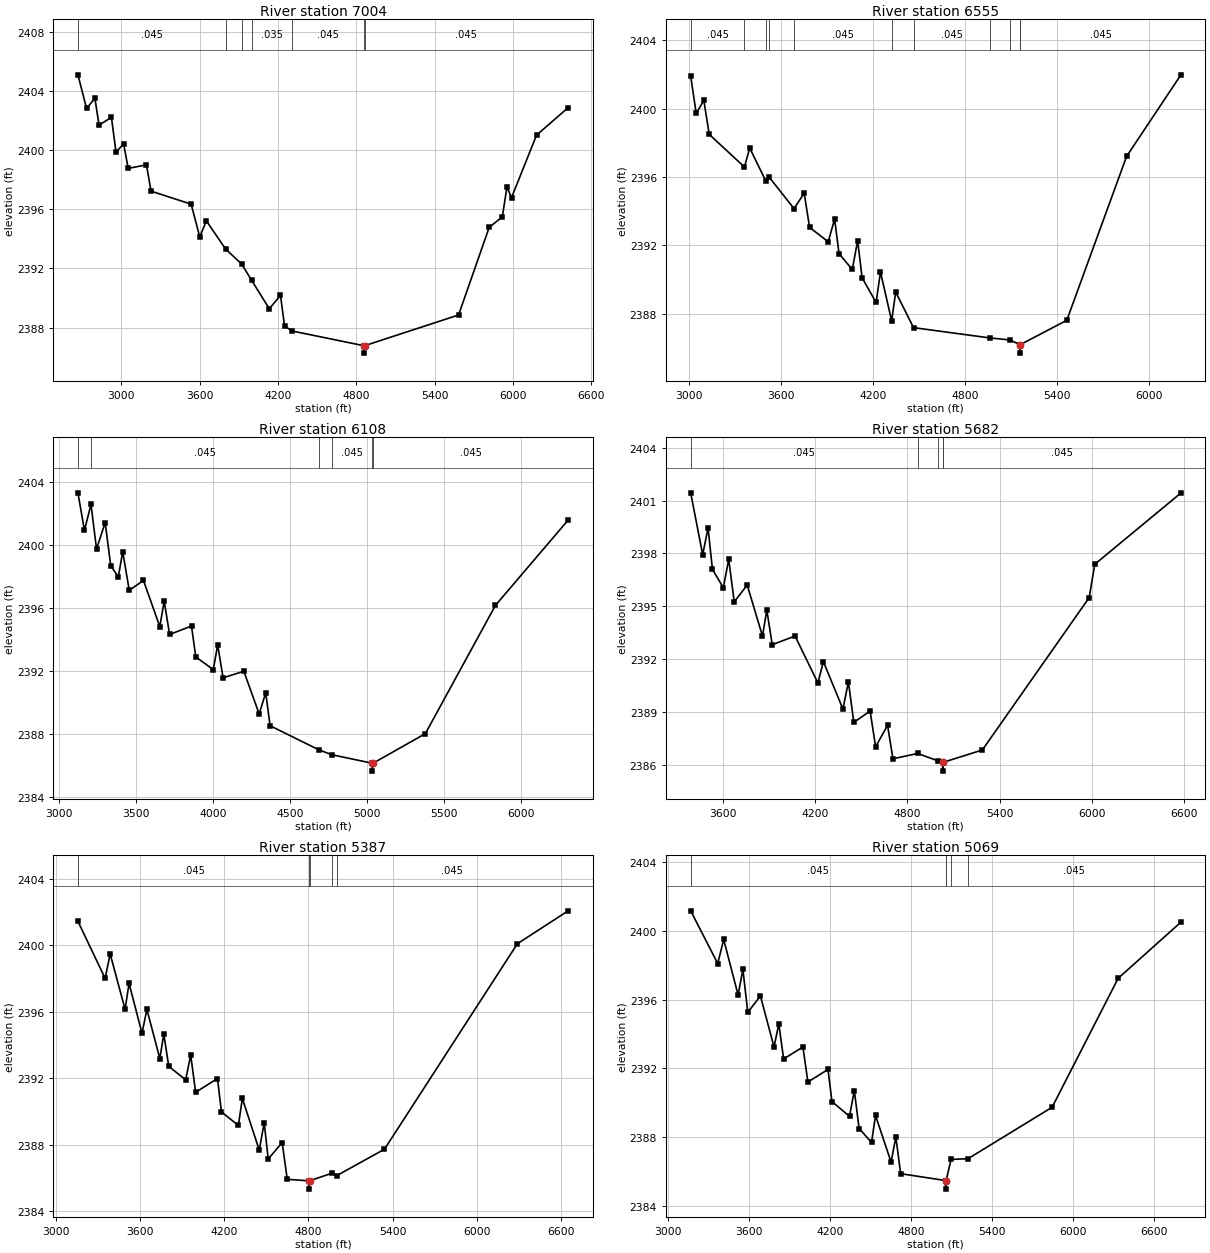
Type RM Length L Ch R = 1,7004,449,449,449
BEGIN DESCRIPTION:
Buffalo Creek Trib 09-01 13.0
END DESCRIPTION:
XS GIS Cut Line= 3
      1282605.00      6932138.00      1280605.00      6930938.00
      1279705.03      6929838.04
#Sta/Elev= 30
  2667.6 2405.10  2733.7 2402.83  2797.8 2403.51  2828.9 2401.70  2924.2 2402.22
  2959.1 2399.87  3017.5 2400.43  3052.4 2398.77  3192.4 2399.01  3227.4 2397.23
  3534.5 2396.35  3600.6 2394.13  3651.1 2395.22  3798.4 2393.31  3921.1 2392.30
  3998.0 2391.19  4133.1 2389.27  4218.6 2390.18  4249.7 2388.11  4306.1 2387.77
  4858.0 2386.77  4858.2 2386.27  4862.1 2386.77  5582.1 2388.85  5816.8 2394.78
  5917.3 2395.49  5952.5 2397.51  5987.7 2396.79  6179.3 2401.02  6421.2 2402.88
#Mann=7,-1,0
  2667.6   0.045       0  3798.4   0.035       0  3921.1   0.045       0
  3998.0   0.035       0  4306.1   0.045       0  4858.0   0.045       0
  4862.1   0.045       0
Bank Sta=4858,4862.1
Exp/Cntr=0.3,0.1

Type RM Length L Ch R = 1,6555,447,447,447
BEGIN DESCRIPTION:
Buffalo Creek Trib 09-01 12.0
END DESCRIPTION:
XS GIS Cut Line= 3
      1282405.04      6931888.03      1280855.00      6930638.00
      1280055.02      6929738.03
#Sta/Elev= 30
  3012.8 2401.89  3048.8 2399.71  3098.4 2400.48  3133.6 2398.49  3363.3 2396.58
  3397.5 2397.69  3503.9 2395.74  3524.9 2395.98  3686.4 2394.15  3752.6 2395.05
  3787.8 2393.05  3909.3 2392.21  3950.9 2393.54  3979.7 2391.52  4066.0 2390.59
  4101.2 2392.27  4130.0 2390.11  4221.2 2388.66  4250.0 2390.44  4322.7 2387.59
  4349.2 2389.27  4465.4 2387.19  4961.7 2386.59  5093.5 2386.47  5158.0 2386.20
  5158.2 2385.70  5162.1 2386.20  5464.4 2387.62  5854.1 2397.20  6208.2 2401.97
#Mann=11,-1,0
  3012.8   0.045       0  3363.3   0.035       0  3503.9   0.045       0
  3524.9   0.035       0  3686.4   0.045       0  4322.7   0.035       0
  4465.4   0.045       0  4961.7   0.035       0  5093.5   0.045       0
  5158.0   0.035       0  5162.1   0.045       0
Bank Sta=5158,5162.1
Exp/Cntr=0.3,0.1

Type RM Length L Ch R = 1,6108,426,426,426
BEGIN DESCRIPTION:
Buffalo Creek Trib 09-01 11.0
END DESCRIPTION:
XS GIS Cut Line= 3
      1282605.01      6931638.01      1281205.00      6930388.00
      1280104.98      6929687.99
#Sta/Elev= 30
  3122.5 2403.31  3164.7 2400.93  3207.3 2402.57  3243.2 2399.75  3299.3 2401.42
  3335.3 2398.69  3384.6 2397.97  3413.0 2399.58  3455.6 2397.12  3547.6 2397.75
  3653.8 2394.82  3682.2 2396.44  3717.3 2394.32  3859.4 2394.86  3887.0 2392.90
  4000.7 2392.09  4029.2 2393.66  4064.3 2391.57  4198.9 2391.99  4298.3 2389.28
  4341.0 2390.62  4369.3 2388.53  4686.1 2387.00  4770.4 2386.69  5032.7 2386.15
  5033.0 2385.65  5037.0 2386.15  5376.9 2388.03  5831.6 2396.17  6303.2 2401.58
#Mann=6,-1,0
  3122.5   0.035       0  3207.3   0.045       0  4686.1   0.035       0
  4770.4   0.045       0  5032.7   0.045       0  5037.0   0.045       0
Bank Sta=5032.7,5037
Exp/Cntr=0.3,0.1

Type RM Length L Ch R = 1,5682,295,295,295
BEGIN DESCRIPTION:
Buffalo Creek Trib 09-01 10.0
END DESCRIPTION:
XS GIS Cut Line= 3
      1282654.98      6931237.98      1281455.00      6930138.00
      1280255.00      6929138.00
#Sta/Elev= 30
  3389.8 2401.44  3467.8 2397.93  3502.9 2399.45  3531.3 2397.10  3602.2 2396.06
  3637.3 2397.67  3673.1 2395.26  3757.6 2396.21  3856.9 2393.32  3885.2 2394.79
  3920.4 2392.83  4069.0 2393.32  4217.6 2390.66  4253.3 2391.87  4380.4 2389.18
  4416.1 2390.72  4451.3 2388.42  4557.3 2389.07  4593.1 2387.04  4670.8 2388.26
  4706.0 2386.36  4866.2 2386.66  4997.1 2386.25  5029.1 2386.16  5029.4 2385.66
  5033.5 2386.16  5287.8 2386.86  5982.9 2395.50  6019.3 2397.39  6579.7 2401.43
#Mann=5,-1,0
  3389.8   0.045       0  4866.2   0.035       0  4997.1   0.045       0
  5029.1   0.045       0  5033.5   0.045       0
Bank Sta=5029.1,5033.5
Exp/Cntr=0.3,0.1

Type RM Length L Ch R = 1,5387,318,318,318
BEGIN DESCRIPTION:
Buffalo Creek Trib 09-01 8.8
END DESCRIPTION:
XS GIS Cut Line= 3
      1282823.44      6931213.59      1281856.87      6930111.37
      1280212.04      6928924.37
#Sta/Elev= 30
  3157.2 2401.44  3351.0 2398.01  3387.0 2399.48  3493.3 2396.15  3521.8 2397.71
  3613.8 2394.71  3648.9 2396.14  3741.0 2393.19  3769.4 2394.66  3804.6 2392.72
  3925.1 2391.91  3961.1 2393.40  3996.3 2391.16  4151.9 2391.99  4180.4 2389.98
  4300.9 2389.17  4329.3 2390.79  4449.9 2387.68  4485.0 2389.34  4513.5 2387.15
  4613.1 2388.14  4649.3 2385.93  4804.1 2385.84  4804.4 2385.34  4808.5 2385.84
  4969.2 2386.30  5002.0 2386.15  5342.5 2387.74  6289.6 2400.09  6651.6 2402.07
#Mann=5,-1,0
  3157.2   0.045       0  4804.1   0.035       0  4808.5   0.045       0
  4969.2   0.035       0  5002.0   0.045       0
Bank Sta=4804.1,4808.5
Exp/Cntr=0.3,0.1

Type RM Length L Ch R = 1,5069,281,281,281
BEGIN DESCRIPTION:
Buffalo Creek Trib 09-01 8.7
END DESCRIPTION:
XS GIS Cut Line= 4
      1282874.32      6931179.70      1281924.70      6929873.97
      1281466.86      6929500.91      1280298.40      6928688.07
#Sta/Elev= 30
  3168.0 2401.17  3368.2 2398.10  3412.3 2399.50  3518.9 2396.27  3554.5 2397.76
  3590.5 2395.26  3684.3 2396.21  3784.8 2393.24  3820.3 2394.59  3855.9 2392.54
  3998.6 2393.24  4035.6 2391.20  4184.3 2391.93  4213.7 2390.06  4343.5 2389.20
  4379.1 2390.70  4414.6 2388.49  4506.6 2387.68  4536.0 2389.25  4651.1 2386.54
  4686.7 2387.99  4722.2 2385.86  5054.1 2385.46  5054.4 2384.96  5058.6 2385.46
  5095.5 2386.69  5220.3 2386.73  5843.3 2389.73  6332.1 2397.24  6796.5 2400.51
#Mann=5,-1,0
  3168.0   0.045       0  5054.1   0.045       0  5058.6   0.045       0
  5095.5   0.035       0  5220.3   0.045       0
Bank Sta=5054.1,5058.6
Exp/Cntr=0.3,0.1

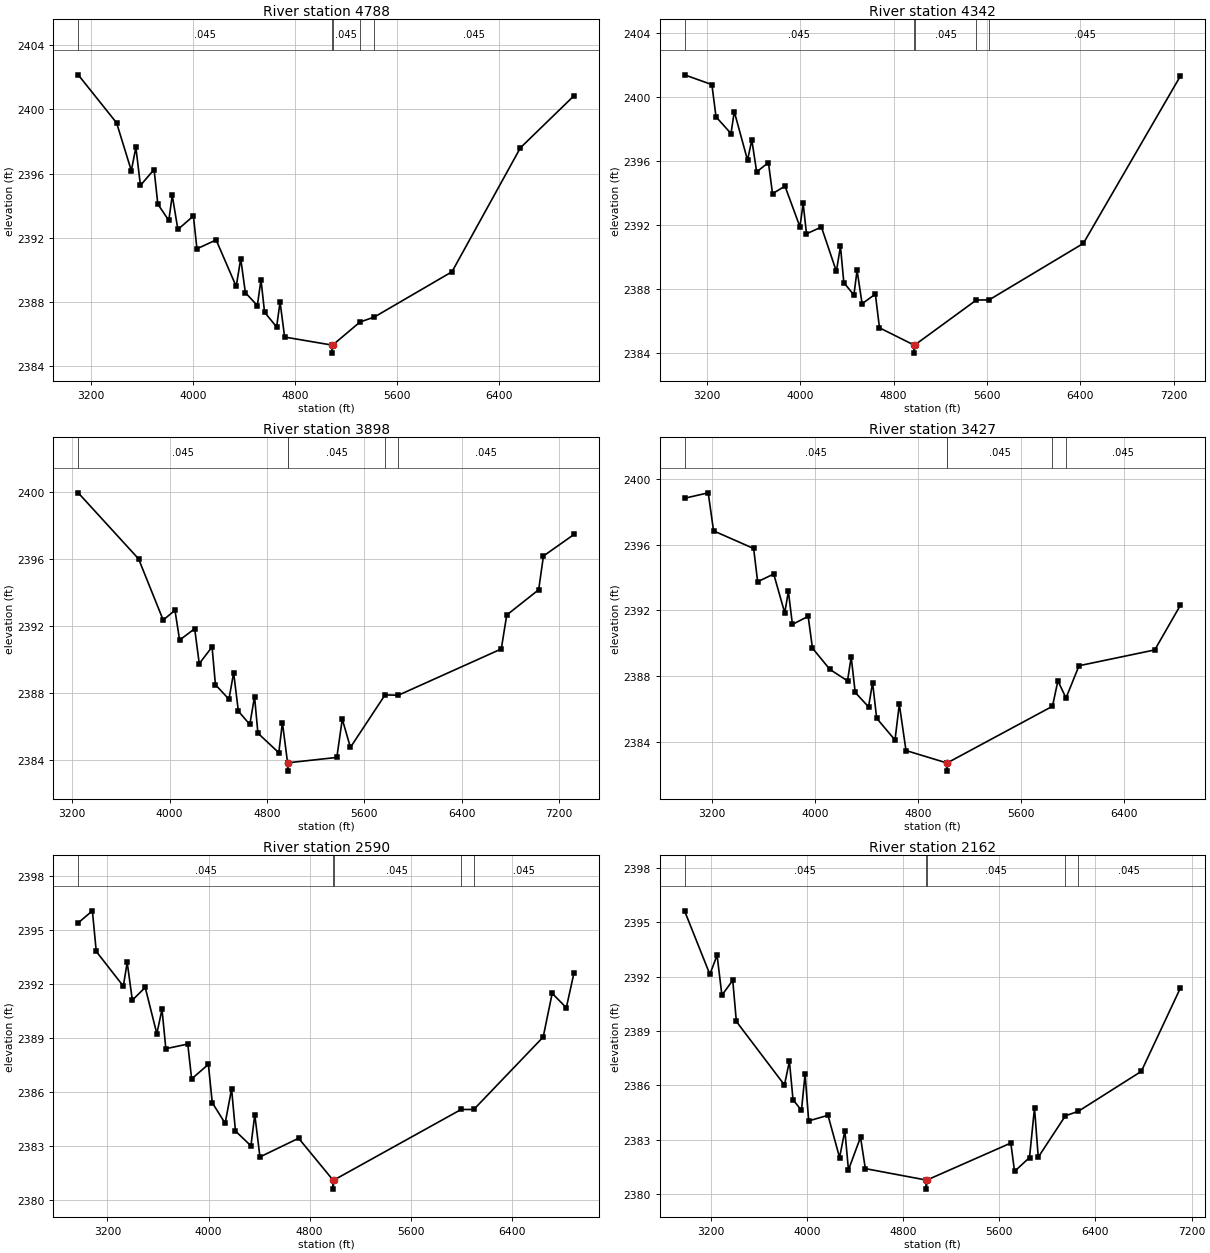
Type RM Length L Ch R = 1,4788,446,446,446
BEGIN DESCRIPTION:
Buffalo Creek Trib 09-01 9.0
END DESCRIPTION:
XS GIS Cut Line= 3
      1283054.98      6931087.97      1281955.00      6929538.00
      1280260.49      6928492.70
#Sta/Elev= 30
  3099.4 2402.14  3400.8 2399.15  3516.3 2396.18  3552.1 2397.63  3587.8 2395.26
  3694.8 2396.25  3724.3 2394.10  3810.4 2393.08  3837.5 2394.64  3881.8 2392.52
  4003.6 2393.36  4031.3 2391.32  4181.9 2391.87  4339.4 2388.98  4375.1 2390.70
  4411.4 2388.59  4505.5 2387.79  4534.0 2389.39  4562.1 2387.37  4656.7 2386.46
  4683.8 2388.01  4719.5 2385.83  5091.7 2385.33  5092.0 2384.83  5096.3 2385.33
  5310.4 2386.76  5424.7 2387.08  6033.1 2389.89  6570.0 2397.60  6991.0 2400.84
#Mann=5,-1,0
  3099.4   0.045       0  5091.7   0.045       0  5096.3   0.045       0
  5310.4   0.035       0  5424.7   0.045       0
Bank Sta=5091.7,5096.3
Exp/Cntr=0.3,0.1

Type RM Length L Ch R = 1,4342,444,444,444
BEGIN DESCRIPTION:
Buffalo Creek Trib 09-01 8.0
END DESCRIPTION:
XS GIS Cut Line= 3
      1283504.99      6930787.99      1282255.00      6929238.00
      1280242.17      6928214.33
#Sta/Elev= 30
  3008.8 2401.37  3243.1 2400.76  3278.6 2398.75  3407.0 2397.71  3435.0 2399.08
  3548.6 2396.05  3585.3 2397.31  3627.0 2395.32  3727.7 2395.90  3762.9 2393.96
  3869.5 2394.43  3998.0 2391.89  4025.2 2393.36  4054.0 2391.46  4181.9 2391.88
  4309.9 2389.12  4345.1 2390.67  4373.9 2388.42  4460.2 2387.64  4487.4 2389.18
  4530.6 2387.10  4644.2 2387.70  4679.4 2385.60  4976.1 2384.52  4976.4 2384.02
  4980.8 2384.52  5509.8 2387.33  5619.3 2387.34  6426.7 2390.86  7258.2 2401.29
#Mann=5,-1,0
  3008.8   0.045       0  4976.1   0.045       0  4980.8   0.045       0
  5509.8   0.035       0  5619.3   0.045       0
Bank Sta=4976.1,4980.8
Exp/Cntr=0.3,0.1

Type RM Length L Ch R = 1,3898,471,471,471
BEGIN DESCRIPTION:
Buffalo Creek Trib 09-01 7.0
END DESCRIPTION:
XS GIS Cut Line= 3
      1283405.00      6930538.01      1282605.00      6928988.00
      1280519.93      6927953.91
#Sta/Elev= 30
  3249.6 2399.98  3745.3 2396.03  3947.3 2392.37  4044.2 2392.95  4082.4 2391.17
  4206.1 2391.85  4243.6 2389.76  4348.8 2390.76  4376.5 2388.50  4487.5 2387.63
  4526.0 2389.22  4564.7 2386.92  4658.9 2386.12  4697.6 2387.79  4725.4 2385.60
  4897.0 2384.43  4926.4 2386.23  4969.0 2383.83  4969.3 2383.33  4973.8 2383.83
  5373.4 2384.15  5418.1 2386.44  5485.0 2384.75  5769.4 2387.89  5878.4 2387.87
  6724.0 2390.64  6768.7 2392.67  7030.9 2394.18  7070.1 2396.20  7321.3 2397.49
#Mann=5,-1,0
  3249.6   0.045       0  4969.0   0.045       0  4973.8   0.045       0
  5769.4   0.035       0  5878.4   0.045       0
Bank Sta=4969,4973.8
Exp/Cntr=0.3,0.1

Type RM Length L Ch R = 1,3427,837,837,837
BEGIN DESCRIPTION:
Buffalo Creek Trib 09-01 6.5
END DESCRIPTION:
XS GIS Cut Line= 3
      1283427.17      6930485.11      1282922.67      6928664.54
      1281091.61      6927962.81
#Sta/Elev= 30
  2984.2 2398.81  3168.0 2399.14  3209.5 2396.83  3520.8 2395.76  3551.9 2393.74
  3676.5 2394.21  3762.3 2391.85  3790.6 2393.16  3821.7 2391.15  3944.1 2391.64
  3977.4 2389.71  4112.3 2388.42  4249.6 2387.72  4278.3 2389.17  4309.4 2387.02
  4413.2 2386.14  4444.3 2387.62  4476.1 2385.45  4618.4 2384.13  4651.9 2386.30
  4703.8 2383.49  5019.4 2382.74  5019.7 2382.24  5024.2 2382.74  5841.4 2386.18
  5883.3 2387.72  5946.3 2386.68  6047.4 2388.64  6635.4 2389.60  6834.3 2392.31
#Mann=5,-1,0
  2984.2   0.045       0  5019.4   0.045       0  5024.2   0.045       0
  5841.4   0.035       0  5946.3   0.045       0
Bank Sta=5019.4,5024.2
Exp/Cntr=0.3,0.1

Type RM Length L Ch R = 1,2590,428,428,428
BEGIN DESCRIPTION:
Buffalo Creek Trib 09-01 6.0
END DESCRIPTION:
XS GIS Cut Line= 4
      1283355.01      6930038.05      1282955.00      6928038.00
      1282930.00      6927963.00      1281155.02      6927638.00
#Sta/Elev= 30
  2968.8 2395.41  3081.0 2396.08  3111.6 2393.82  3325.8 2391.89  3356.4 2393.21
  3397.2 2391.11  3499.1 2391.82  3590.9 2389.24  3631.7 2390.60  3662.3 2388.41
  3835.7 2388.67  3866.3 2386.73  3998.8 2387.54  4029.4 2385.41  4131.4 2384.26
  4182.4 2386.17  4213.0 2383.83  4335.4 2383.01  4366.0 2384.74  4406.8 2382.39
  4712.7 2383.43  4985.5 2381.10  4985.9 2380.60  4990.6 2381.10  5998.6 2385.03
  6098.7 2385.03  6648.0 2389.06  6719.2 2391.49  6831.0 2390.69  6892.0 2392.64
#Mann=5,-1,0
  2968.8   0.045       0  4985.5   0.045       0  4990.6   0.045       0
  5998.6   0.035       0  6098.7   0.045       0
Bank Sta=4985.5,4990.6
Exp/Cntr=0.3,0.1

Type RM Length L Ch R = 1,2162,415,415,415
BEGIN DESCRIPTION:
Buffalo Creek Trib 09-01 5.0
END DESCRIPTION:
XS GIS Cut Line= 5
      1283455.00      6929837.97      1283334.68      6928015.32
      1283255.00      6927838.00      1283180.00      6927763.00
      1281254.99      6927238.00
#Sta/Elev= 30
  2983.4 2395.62  3193.8 2392.12  3254.0 2393.17  3294.0 2390.97  3384.2 2391.79
  3414.3 2389.52  3814.3 2386.02  3855.3 2387.33  3885.3 2385.21  3955.5 2384.62
  3985.5 2386.62  4015.6 2384.04  4176.0 2384.35  4272.5 2382.02  4316.3 2383.50
  4346.3 2381.34  4446.5 2383.14  4486.6 2381.41  4993.0 2380.78  4993.4 2380.28
  4998.1 2380.78  5696.1 2382.82  5727.2 2381.26  5851.6 2382.02  5893.1 2384.76
  5924.2 2382.04  6149.8 2384.32  6257.3 2384.57  6781.0 2386.77  7105.8 2391.36
#Mann=5,-1,0
  2983.4   0.045       0  4993.0   0.045       0  4998.1   0.045       0
  6149.8   0.035       0  6257.3   0.045       0
Bank Sta=4993,4998.1
Exp/Cntr=0.3,0.1

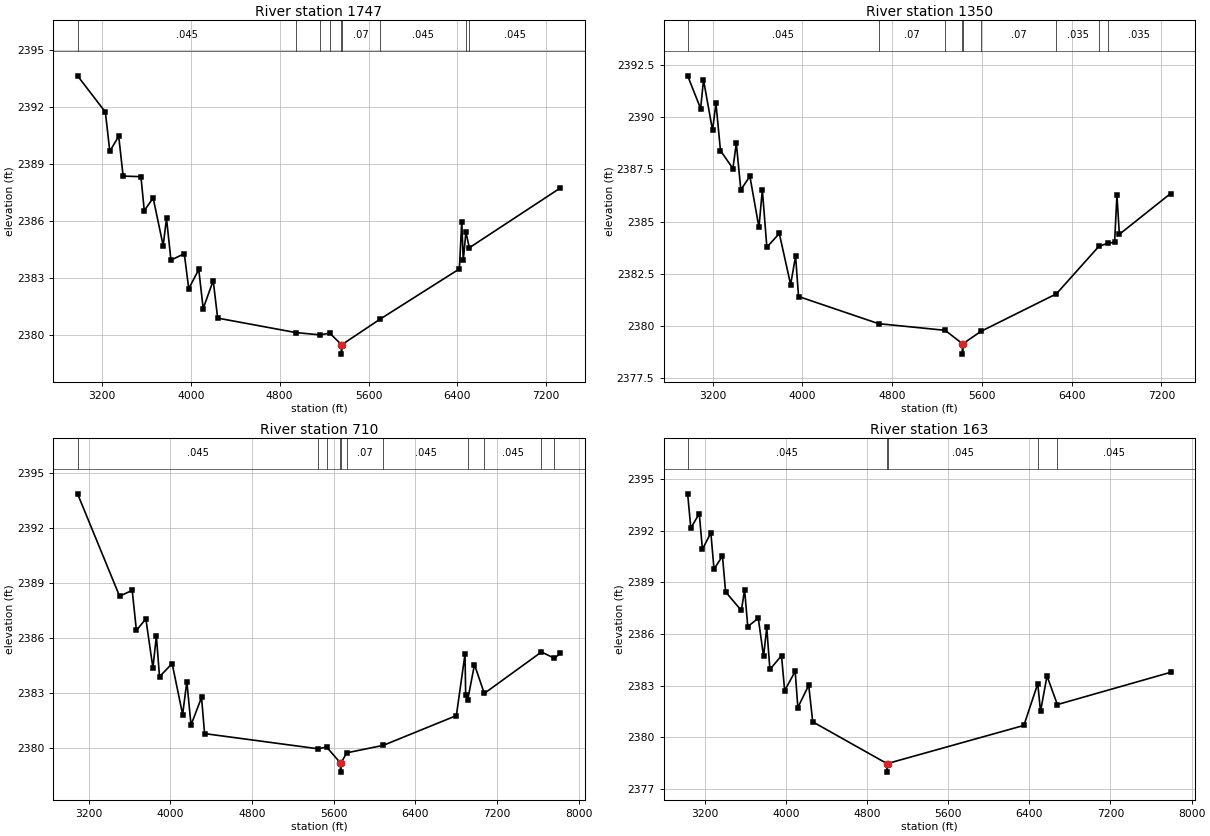
Type RM Length L Ch R = 1,1747,397,397,397
BEGIN DESCRIPTION:
Buffalo Creek Trib 09-01 4.0
END DESCRIPTION:
XS GIS Cut Line= 4
      1283555.00      6929638.02      1283622.87      6927813.93
      1283555.00      6927638.00      1281555.00      6926438.00
#Sta/Elev= 30
  2981.2 2393.62  3231.4 2391.72  3271.4 2389.66  3351.5 2390.45  3391.5 2388.36
  3551.6 2388.33  3581.6 2386.55  3661.7 2387.21  3751.8 2384.71  3781.8 2386.14
  3821.8 2383.95  3941.9 2384.29  3981.9 2382.45  4072.0 2383.46  4112.0 2381.41
  4202.1 2382.88  4242.1 2380.91  4947.3 2380.15  5163.2 2380.03  5251.3 2380.12
  5356.0 2379.52  5356.4 2379.02  5361.1 2379.52  5705.4 2380.86  6417.9 2383.49
  6439.3 2385.97  6452.9 2383.94  6476.7 2385.42  6507.5 2384.60  7327.5 2387.74
#Mann=9,-1,0
  2981.2   0.045       0  4947.3    0.07       0  5163.2   0.035       0
  5251.3    0.07       0  5356.0    0.07       0  5361.1    0.07       0
  5705.4   0.045       0  6476.7   0.035       0  6507.5   0.045       0
Bank Sta=5356,5361.1
Exp/Cntr=0.3,0.1

Type RM Length L Ch R = 1,1350,640,640,640
BEGIN DESCRIPTION:
Buffalo Creek Trib 09-01 3.0
END DESCRIPTION:
XS GIS Cut Line= 4
      1283655.00      6929488.02      1283900.65      6927616.01
      1283855.00      6927488.00      1282055.01      6926088.01
#Sta/Elev= 30
  2976.4 2391.98  3092.1 2390.41  3117.6 2391.79  3198.3 2389.37  3228.6 2390.67
  3268.9 2388.40  3379.8 2387.54  3410.1 2388.75  3450.4 2386.52  3531.1 2387.17
  3611.8 2384.72  3642.1 2386.52  3682.4 2383.77  3793.4 2384.43  3894.2 2381.98
  3938.4 2383.34  3964.8 2381.41  4677.6 2380.11  5271.6 2379.79  5425.7 2379.15
  5426.1 2378.65  5431.0 2379.15  5590.5 2379.74  6263.8 2381.54  6641.5 2383.81
  6720.7 2383.96  6782.1 2384.01  6802.9 2386.26  6824.6 2384.39  7280.7 2386.34
#Mann=9,-1,0
  2976.4   0.045       0  4677.6    0.07       0  5271.6   0.035       0
  5425.7    0.07       0  5431.0   0.035       0  5590.5    0.07       0
  6263.8   0.035       0  6641.5   0.045       0  6720.7   0.035       0
Bank Sta=5425.7,5431
Exp/Cntr=0.3,0.1

Type RM Length L Ch R = 1,710,547,547,547
BEGIN DESCRIPTION:
Buffalo Creek Trib 09-01 2.0
END DESCRIPTION:
XS GIS Cut Line= 4
      1283805.00      6929538.01      1284255.00      6927688.00
      1284341.59      6927440.49      1282338.55      6925840.64
#Sta/Elev= 30
  3092.7 2393.88  3504.4 2388.30  3627.9 2388.62  3669.0 2386.44  3761.7 2387.06
  3830.8 2384.39  3864.6 2386.13  3895.5 2383.91  4019.0 2384.63  4121.9 2381.85
  4163.0 2383.65  4204.2 2381.28  4307.1 2382.78  4336.8 2380.81  5450.9 2379.98
  5531.3 2380.08  5667.7 2379.21  5668.2 2378.71  5674.3 2379.21  5727.8 2379.76
  6087.5 2380.17  6802.9 2381.79  6887.8 2385.14  6894.2 2382.91  6913.8 2382.64
  6980.6 2384.57  7076.4 2383.00  7636.7 2385.26  7760.6 2384.92  7822.4 2385.18
#Mann=11,-1,0
  3092.7   0.045       0  5450.9    0.07       0  5531.3   0.035       0
  5667.7   0.045       0  5674.3   0.035       0  5727.8    0.07       0
  6087.5   0.045       0  6913.8   0.035       0  7076.4   0.045       0
  7636.7   0.035       0  7760.6   0.045       0
Bank Sta=5667.7,5674.3
Exp/Cntr=0.3,0.1

Type RM Length L Ch R = 1,163,0,0,0
BEGIN DESCRIPTION:
Buffalo Creek Trib 09-01 1.0
END DESCRIPTION:
XS GIS Cut Line= 4
      1284255.00      6929487.99      1284732.22      6927797.26
      1284750.45      6927391.01      1282745.06      6925743.97
#Sta/Elev= 30
  3033.3 2394.14  3064.5 2392.15  3147.6 2392.99  3178.8 2390.92  3261.9 2391.88
  3293.1 2389.77  3376.2 2390.53  3407.3 2388.45  3562.5 2387.37  3594.4 2388.57
  3625.6 2386.44  3729.5 2386.92  3781.4 2384.70  3812.6 2386.39  3843.8 2383.95
  3958.1 2384.75  3989.2 2382.72  4093.1 2383.84  4119.2 2381.74  4226.4 2383.03
  4265.6 2380.91  4996.2 2378.49  4996.7 2377.99  5002.9 2378.49  6346.4 2380.70
  6483.3 2383.12  6510.7 2381.51  6574.6 2383.57  6676.5 2381.91  7791.8 2383.78
#Mann=5,-1,0
  3033.3   0.045       0  4996.2   0.045       0  5002.9   0.045       0
  6483.3   0.035       0  6676.5   0.045       0
Bank Sta=4996.2,5002.9
Exp/Cntr=0.3,0.1

Chan Stop Cuts=-1