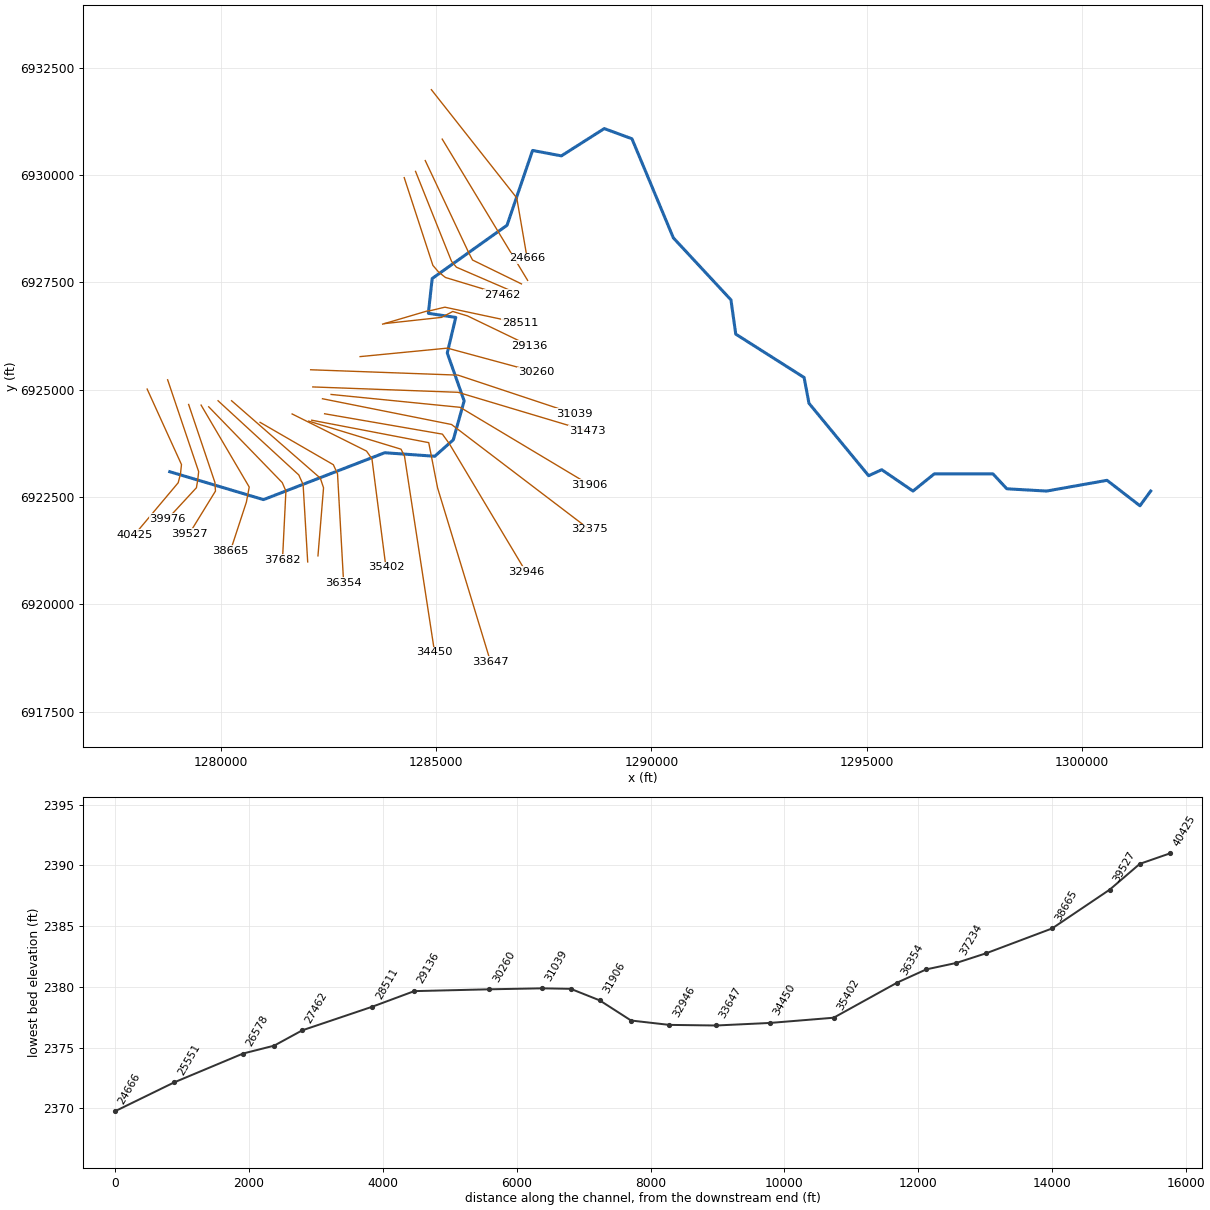
--- Buffalo Creek Trib 09.prj (project) ---

Proj Title=Buffalo Creek Trib 09 Base Level Engineering
Current Plan=p01
Default Exp/Contr=0.3,0.1
English Units
Geom File=g01
Flow File=f01
Plan File=p01
BEGIN DESCRIPTION:
Buffalo Creek Trib 09
END DESCRIPTION:

--- Buffalo Creek Trib 09.p01 (plan) ---

Plan Title=Multiple Run
Short Identifier=Multiple
Geom File=g01
Flow File=f01
Subcritical Flow
K Sum by GR= 0
Std Step Tol= 0.01
Critical Tol= 0.01
Num of Std Step Trials= 20
Max Error Tol= 0.3
Flow Tol Ratio= 0.001
Split Flow NTrial= 30
Split Flow Tol= 0.02
Split Flow Ratio= 0.02
Log Output Level= 0
Friction Slope Method= 1
Unsteady Friction Slope Method= 2
Unsteady Bridges Friction Slope Method= 1
Parabolic Critical Depth
Global Vel Dist=  1 , 1 , 1
Global Log Level= 0
CheckData=True
Encroach Param= -1, 0, 0, 0
BEGIN DESCRIPTION:
Multiple Run
END DESCRIPTION:

--- Buffalo Creek Trib 09.f01 (steady flow) ---

Flow Title=Multiple
Number of Profiles=7
Profile Names=10-year,25-year,50-year,1pct_min,100-year,1pct_plu,500-year
River Rch & RM= Buffalo Creek Tr,Reach-1,40425
     310     433     534     327     652    1300     985
River Rch & RM= Buffalo Creek Tr,Reach-1,37682
     345     484     598     366     731    1458    1107
River Rch & RM= Buffalo Creek Tr,Reach-1,33647
     501     707     878     539    1076    2147    1639
River Rch & RM= Buffalo Creek Tr,Reach-1,27462
     676     966    1210     749    1495    2984    2316
River Rch & RM= Buffalo Creek Tr,Reach-1,21371
     709    1013    1269     786    1568    3129    2428
River Rch & RM= Buffalo Creek Tr,Reach-1,18538
     774    1113    1399     869    1734    3461    2703
River Rch & RM= Buffalo Creek Tr,Reach-1,14477
     827    1193    1504     937    1870    3731    2930
River Rch & RM= Buffalo Creek Tr,Reach-1,12839
     940    1370    1739    1091    2177    4345    3461
River Rch & RM= Buffalo Creek Tr,Reach-1,10027
    1007    1474    1877    1181    2356    4702    3767
River Rch & RM= Buffalo Creek Tr,Reach-1,8293
    1174    1741    2237    1421    2836    5659    4620
Boundary for River Rch & Prof#=Buffalo Creek Tr,Reach-1,1
Up Type=0
Dn Type=3
Dn Slope=0.005
Boundary for River Rch & Prof#=Buffalo Creek Tr,Reach-1,2
Up Type=0
Dn Type=3
Dn Slope=0.005
Boundary for River Rch & Prof#=Buffalo Creek Tr,Reach-1,3
Up Type=0
Dn Type=3
Dn Slope=0.005
Boundary for River Rch & Prof#=Buffalo Creek Tr,Reach-1,4
Up Type=0
Dn Type=3
Dn Slope=0.005
Boundary for River Rch & Prof#=Buffalo Creek Tr,Reach-1,5
Up Type=0
Dn Type=3
Dn Slope=0.005
Boundary for River Rch & Prof#=Buffalo Creek Tr,Reach-1,6
Up Type=0
Dn Type=3
Dn Slope=0.005
Boundary for River Rch & Prof#=Buffalo Creek Tr,Reach-1,7
Up Type=0
Dn Type=3
Dn Slope=0.005

--- Buffalo Creek Trib 09.g01 (geometry) ---

Geom Title=Existing Conditions

River Reach=Buffalo Creek Tr,Reach-1
Reach XY= 30
      1278805.00      6923088.00      1280984.97      6922438.07
      1283801.95      6923530.24      1284965.22      6923448.30
      1285396.05      6923831.33      1285647.91      6924738.00
      1285255.24      6925853.22      1285452.95      6926682.16
      1284815.95      6926777.63      1284905.00      6927588.00
      1286644.22      6928828.32      1287238.30      6930571.62
      1287908.43      6930445.39      1288904.79      6931080.99
      1289547.54      6930844.09      1290510.09      6928535.70
      1291849.29      6927090.58      1291960.56      6926293.62
      1293549.39      6925282.41      1293662.81      6924681.81
      1295048.95      6922995.46      1295353.50      6923134.53
      1296079.96      6922637.51      1296574.99      6923038.06
      1297939.17      6923037.36      1298260.97      6922690.14
      1299184.96      6922637.39      1300589.80      6922887.50
      1301355.01      6922295.08      1301605.00      6922638.00

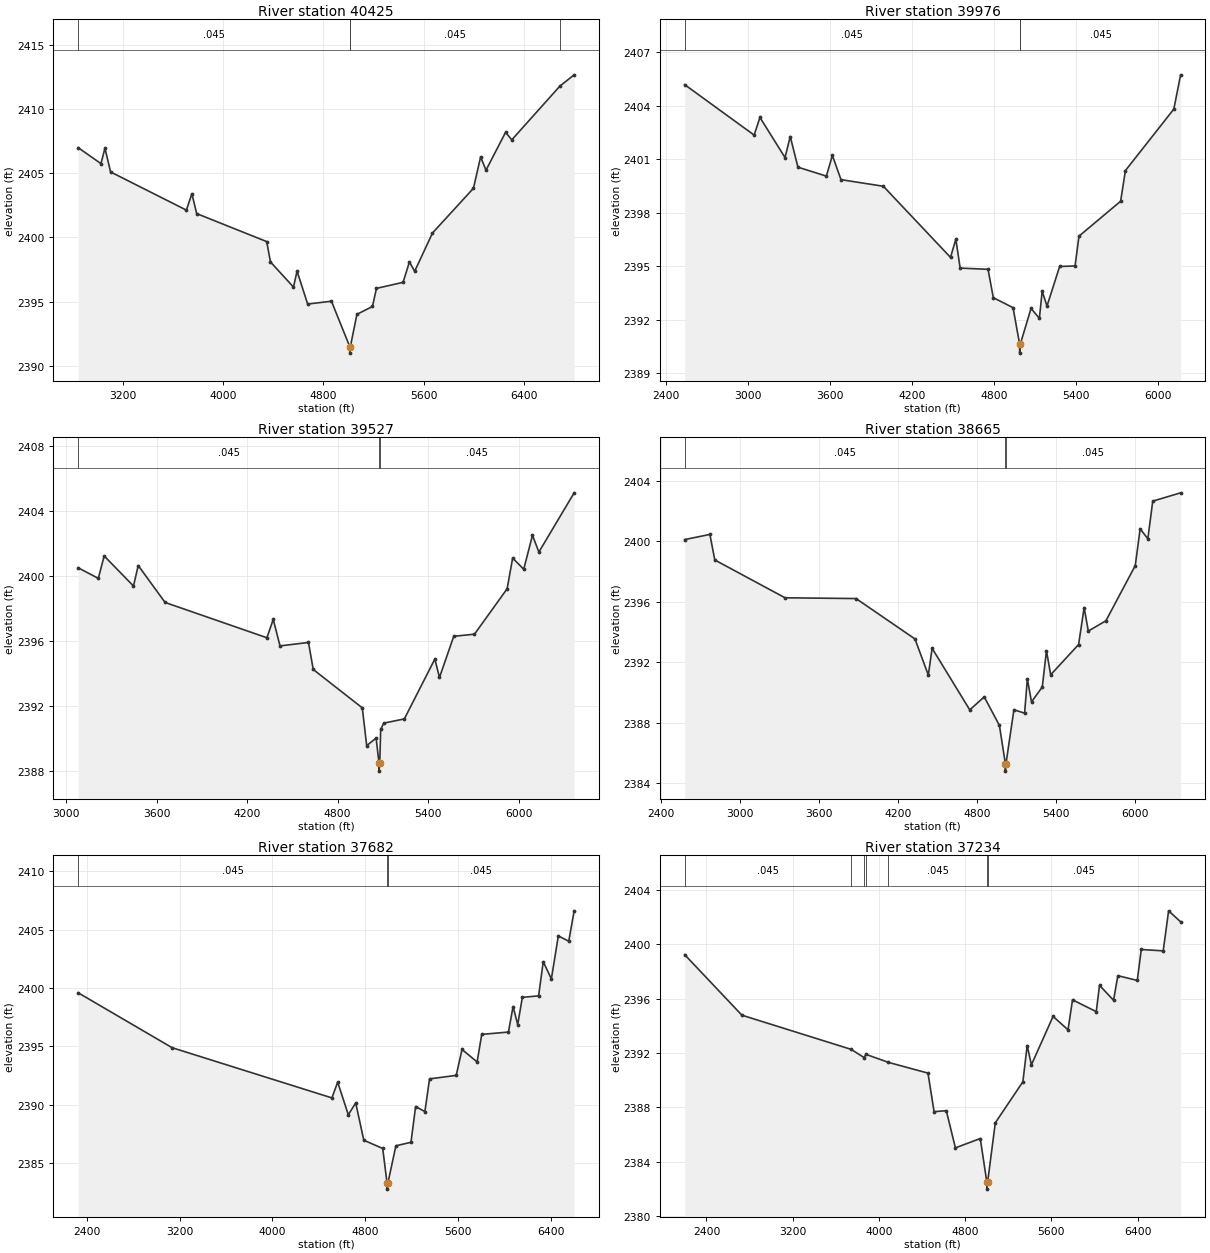
Type RM Length L Ch R = 1,40425,449,449,449
BEGIN DESCRIPTION:
Buffalo Creek Trib 09 56.0
END DESCRIPTION:
XS GIS Cut Line= 5
      1278280.00      6925012.99      1279078.04      6923254.80
      1279055.00      6923038.00      1279001.65      6922831.19
      1277980.01      6921613.01
#Sta/Elev= 30
  2846.9 2406.98  3028.1 2405.74  3060.1 2406.94  3105.0 2405.09  3709.0 2402.12
  3752.9 2403.40  3790.9 2401.85  4349.2 2399.67  4378.9 2398.09  4562.4 2396.13
  4591.0 2397.37  4675.4 2394.81  4865.0 2395.03  5011.1 2391.49  5011.4 2390.99
  5015.8 2391.49  5068.0 2394.01  5192.0 2394.62  5223.7 2396.03  5435.8 2396.50
  5486.5 2398.09  5528.2 2397.36  5670.3 2400.34  5996.6 2403.82  6053.8 2406.26
  6096.7 2405.23  6252.8 2408.18  6302.2 2407.59  6686.3 2411.78  6799.2 2412.65
#Mann=4,-1,0
  2846.9   0.045       0  5011.1   0.045       0  5015.8   0.045       0
  6686.3   0.035       0
Bank Sta=5011.1,5015.8
Exp/Cntr=0.3,0.1

Type RM Length L Ch R = 1,39976,449,449,449
BEGIN DESCRIPTION:
Buffalo Creek Trib 09 55.0
END DESCRIPTION:
XS GIS Cut Line= 5
      1278756.22      6925229.41      1279477.34      6923089.87
      1279455.00      6922888.00      1279425.26      6922714.87
      1278755.00      6921988.00
#Sta/Elev= 30
  2539.1 2405.19  3046.9 2402.36  3089.3 2403.35  3272.5 2401.10  3310.9 2402.28
  3367.0 2400.56  3574.8 2400.06  3618.9 2401.22  3681.8 2399.86  3991.4 2399.49
  4482.3 2395.50  4521.3 2396.52  4552.8 2394.90  4756.7 2394.83  4795.2 2393.24
  4939.6 2392.68  4987.5 2390.63  4987.8 2390.13  4992.4 2390.63  5071.0 2392.64
  5131.9 2392.08  5152.5 2393.60  5187.6 2392.77  5280.1 2394.99  5392.9 2395.02
  5421.3 2396.69  5725.8 2398.65  5760.9 2400.37  6114.8 2403.82  6164.4 2405.74
#Mann=3,-1,0
  2539.1   0.045       0  4987.5   0.045       0  4992.4   0.045       0
Bank Sta=4987.5,4992.4
Exp/Cntr=0.3,0.1

Type RM Length L Ch R = 1,39527,862,862,862
BEGIN DESCRIPTION:
Buffalo Creek Trib 09 54.0
END DESCRIPTION:
XS GIS Cut Line= 4
      1279244.50      6924654.33      1279855.00      6922838.00
      1279867.97      6922636.74      1279255.00      6921638.00
#Sta/Elev= 30
  3079.4 2400.51  3212.7 2399.86  3251.6 2401.24  3446.0 2399.39  3477.5 2400.65
  3655.8 2398.38  4331.0 2396.21  4373.1 2397.34  4417.8 2395.71  4606.9 2395.92
  4638.4 2394.26  4963.9 2391.90  4992.9 2389.58  5055.7 2390.04  5074.6 2388.51
  5075.0 2388.01  5079.6 2388.51  5085.8 2390.57  5105.8 2390.96  5242.7 2391.22
  5445.0 2394.90  5475.8 2393.77  5570.6 2396.30  5707.9 2396.43  5924.5 2399.22
  5961.2 2401.11  6034.6 2400.42  6092.6 2402.51  6135.2 2401.48  6369.1 2405.12
#Mann=3,-1,0
  3079.4   0.045       0  5074.6   0.045       0  5079.6   0.045       0
Bank Sta=5074.6,5079.6
Exp/Cntr=0.3,0.1

Type RM Length L Ch R = 1,38665,983,983,983
BEGIN DESCRIPTION:
Buffalo Creek Trib 09 53.5
END DESCRIPTION:
XS GIS Cut Line= 4
      1279533.85      6924639.63      1280652.49      6922731.36
      1280586.69      6922380.42      1280214.31      6921241.38
#Sta/Elev= 30
  2580.5 2400.12  2772.1 2400.46  2809.3 2398.77  3342.9 2396.27  3882.2 2396.22
  4329.8 2393.55  4431.4 2391.16  4460.2 2392.93  4746.1 2388.86  4856.1 2389.72
  4971.4 2387.83  5016.3 2385.31  5016.7 2384.81  5021.4 2385.31  5081.6 2388.87
  5162.6 2388.64  5183.6 2390.91  5215.2 2389.39  5297.0 2390.37  5328.8 2392.77
  5360.7 2391.18  5572.9 2393.18  5615.0 2395.62  5646.6 2394.07  5780.3 2394.75
  6003.4 2398.40  6040.5 2400.83  6099.0 2400.17  6136.1 2402.66  6347.9 2403.21
#Mann=3,-1,0
  2580.5   0.045       0  5016.3   0.045       0  5021.4   0.045       0
Bank Sta=5016.3,5021.4
Exp/Cntr=0.3,0.1

Type RM Length L Ch R = 1,37682,448,448,448
BEGIN DESCRIPTION:
Buffalo Creek Trib 09 53.0
END DESCRIPTION:
XS GIS Cut Line= 4
      1279711.12      6924600.01      1281420.05      6922834.66
      1281505.00      6922638.00      1281425.57      6921031.59
#Sta/Elev= 30
  2323.6 2399.58  3133.9 2394.88  4512.9 2390.58  4562.5 2391.93  4654.4 2389.14
  4718.2 2390.15  4787.9 2386.96  4951.3 2386.25  4988.8 2383.27  4989.3 2382.77
  4995.5 2383.27  5064.9 2386.48  5195.1 2386.78  5235.1 2389.84  5315.2 2389.41
  5355.3 2392.21  5585.5 2392.51  5635.6 2394.73  5765.8 2393.66  5805.8 2396.02
  6036.1 2396.22  6076.1 2398.40  6116.2 2396.86  6156.2 2399.19  6296.4 2399.32
  6336.5 2402.24  6406.6 2400.77  6466.6 2404.45  6556.7 2404.00  6603.2 2406.60
#Mann=3,-1,0
  2323.6   0.045       0  4988.8   0.045       0  4995.5   0.045       0
Bank Sta=4988.8,4995.5
Exp/Cntr=0.3,0.1

Type RM Length L Ch R = 1,37234,449,449,449
BEGIN DESCRIPTION:
Buffalo Creek Trib 09 52.0
END DESCRIPTION:
XS GIS Cut Line= 4
      1279928.08      6924741.12      1281805.47      6923011.74
      1281905.00      6922788.00      1282011.44      6920986.74
#Sta/Elev= 30
  2197.7 2399.25  2728.4 2394.79  3742.3 2392.27  3861.7 2391.67  3880.7 2391.90
  4088.8 2391.31  4455.2 2390.52  4511.9 2387.68  4625.3 2387.75  4709.8 2385.01
  4940.4 2385.70  5001.8 2382.47  5002.3 2381.97  5008.5 2382.47  5080.1 2386.86
  5335.7 2389.88  5375.8 2392.55  5414.9 2391.13  5616.2 2394.70  5754.7 2393.71
  5796.5 2395.92  6016.9 2395.05  6046.9 2396.99  6177.2 2395.89  6217.2 2397.70
  6397.5 2397.35  6434.3 2399.63  6638.0 2399.53  6688.0 2402.48  6799.5 2401.67
#Mann=7,-1,0
  2197.7   0.045       0  3742.3    0.07       0  3861.7   0.035       0
  3880.7    0.07       0  4088.8   0.045       0  5001.8   0.045       0
  5008.5   0.045       0
Bank Sta=5001.8,5008.5
Exp/Cntr=0.3,0.1

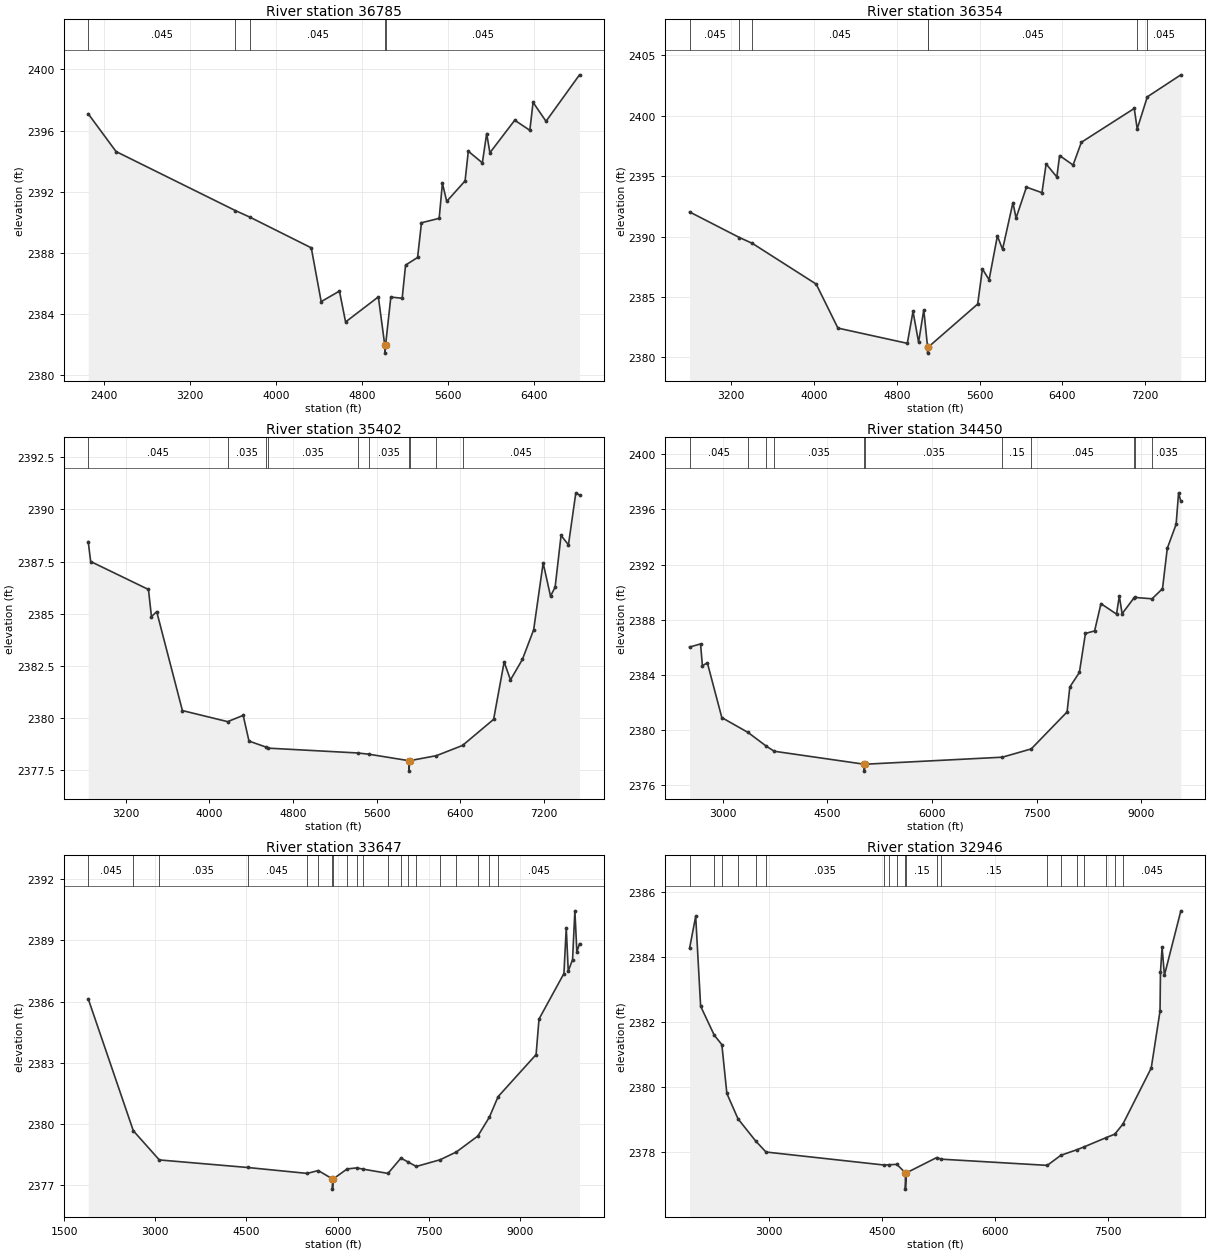
Type RM Length L Ch R = 1,36785,431,431,431
BEGIN DESCRIPTION:
Buffalo Creek Trib 09 51.0
END DESCRIPTION:
XS GIS Cut Line= 4
      1280242.80      6924741.08      1282305.00      6922938.00
      1282380.00      6922713.00      1282250.15      6921127.78
#Sta/Elev= 30
  2256.5 2397.10  2515.1 2394.63  3623.8 2390.77  3761.7 2390.33  4330.0 2388.33
  4422.0 2384.81  4591.9 2385.50  4648.9 2383.48  4953.6 2385.12  5013.5 2381.94
  5014.0 2381.44  5020.2 2381.94  5069.6 2385.11  5175.0 2385.03  5206.6 2387.20
  5318.3 2387.70  5354.4 2389.97  5518.9 2390.26  5549.0 2392.55  5589.2 2391.37
  5759.7 2392.71  5789.8 2394.65  5920.3 2393.89  5960.4 2395.81  5990.5 2394.55
  6221.3 2396.68  6361.7 2396.02  6391.8 2397.85  6512.2 2396.61  6823.5 2399.65
#Mann=5,-1,0
  2256.5   0.045       0  3623.8   0.035       0  3761.7   0.045       0
  5013.5   0.045       0  5020.2   0.045       0
Bank Sta=5013.5,5020.2
Exp/Cntr=0.3,0.1

Type RM Length L Ch R = 1,36354,952,952,952
BEGIN DESCRIPTION:
Buffalo Creek Trib 09 50.0
END DESCRIPTION:
XS GIS Cut Line= 4
      1280904.98      6924238.01      1282607.55      6923251.33
      1282705.00      6923038.00      1282846.94      6920498.51
#Sta/Elev= 30
  2798.0 2392.04  3280.3 2389.92  3404.3 2389.44  4021.0 2386.07  4231.2 2382.43
  4901.4 2381.17  4956.4 2383.81  5010.4 2381.26  5060.4 2383.94  5097.2 2380.86
  5097.7 2380.36  5103.9 2380.86  5581.2 2384.42  5626.9 2387.32  5691.4 2386.43
  5771.5 2390.05  5821.6 2388.95  5921.8 2392.81  5951.8 2391.53  6052.0 2394.09
  6202.2 2393.63  6242.3 2396.01  6345.9 2394.93  6372.5 2396.70  6502.7 2395.92
  6582.8 2397.80  7093.6 2400.60  7122.1 2398.91  7220.0 2401.56  7543.8 2403.38
#Mann=7,-1,0
  2798.0   0.045       0  3280.3   0.035       0  3404.3   0.045       0
  5097.2   0.045       0  5103.9   0.045       0  7122.1   0.035       0
  7220.0   0.045       0
Bank Sta=5097.2,5103.9
Exp/Cntr=0.3,0.1

Type RM Length L Ch R = 1,35402,952,952,952
BEGIN DESCRIPTION:
Buffalo Creek Trib 09 49.0
END DESCRIPTION:
XS GIS Cut Line= 4
      1281649.57      6924433.65      1283378.38      6923569.04
      1283505.00      6923388.00      1283830.00      6920863.02
#Sta/Elev= 30
  2841.7 2388.45  2865.0 2387.50  3418.0 2386.16  3446.4 2384.86  3496.7 2385.10
  3742.6 2380.36  4175.4 2379.83  4324.0 2380.13  4379.6 2378.90  4543.3 2378.61
  4566.0 2378.56  5418.1 2378.33  5526.7 2378.27  5909.7 2377.96  5910.2 2377.46
  5916.4 2377.96  6171.9 2378.20  6422.3 2378.69  6719.7 2379.94  6820.5 2382.69
  6881.0 2381.83  6995.0 2382.81  7102.8 2384.23  7193.6 2387.43  7264.1 2385.84
  7308.0 2386.27  7365.0 2388.75  7435.6 2388.30  7506.1 2390.79  7541.4 2390.68
#Mann=10,-1,0
  2841.7   0.045       0  4175.4   0.035       0  4543.3    0.15       0
  4566.0   0.035       0  5418.1    0.15       0  5526.7   0.035       0
  5909.7   0.035       0  5916.4   0.035       0  6171.9    0.15       0
  6422.3   0.045       0
Bank Sta=5909.7,5916.4
Exp/Cntr=0.3,0.1

Type RM Length L Ch R = 1,34450,803,803,803
BEGIN DESCRIPTION:
Buffalo Creek Trib 09 48.5
END DESCRIPTION:
XS GIS Cut Line= 4
      1282034.36      6924266.74      1284180.00      6923613.00
      1284260.65      6923455.19      1284960.28      6918885.89
#Sta/Elev= 30
  2526.0 2386.02  2683.5 2386.25  2710.0 2384.67  2780.9 2384.88  2988.4 2380.91
  3365.1 2379.83  3628.5 2378.83  3740.2 2378.47  5030.6 2377.53  5031.1 2377.03
  5038.3 2377.53  7009.7 2378.04  7423.9 2378.64  7937.9 2381.32  7977.3 2383.13
  8114.2 2384.18  8200.9 2387.01  8332.4 2387.19  8423.5 2389.17  8646.5 2388.41
  8686.5 2389.72  8727.0 2388.44  8893.2 2389.56  8908.3 2389.62  9155.6 2389.52
  9305.7 2390.25  9374.4 2393.18  9500.9 2394.92  9536.3 2397.20  9568.8 2396.58
#Mann=11,-1,0
  2526.0   0.045       0  3365.1   0.035       0  3628.5    0.15       0
  3740.2   0.035       0  5030.6   0.035       0  5038.3   0.035       0
  7009.7    0.15       0  7423.9   0.045       0  8893.2   0.035       0
  8908.3   0.045       0  9155.6   0.035       0
Bank Sta=5030.6,5038.3
Exp/Cntr=0.3,0.1

Type RM Length L Ch R = 1,33647,701,701,701
BEGIN DESCRIPTION:
Buffalo Creek Trib 09 48.0
END DESCRIPTION:
XS GIS Cut Line= 4
      1282104.97      6924288.01      1284824.72      6923765.49
      1285030.00      6922713.00      1286263.53      6918654.53
#Sta/Elev= 30
  1896.1 2386.14  2637.8 2379.68  3065.7 2378.25  4517.7 2377.88  5498.6 2377.59
  5681.3 2377.73  5914.3 2377.32  5914.8 2376.82  5927.4 2377.32  6156.6 2377.81
  6315.2 2377.86  6416.7 2377.80  6828.0 2377.59  7041.3 2378.34  7158.9 2378.15
  7294.0 2377.93  7687.0 2378.26  7953.2 2378.64  8306.7 2379.42  8497.4 2380.35
  8640.3 2381.35  9265.4 2383.41  9313.3 2385.15  9723.4 2387.38  9761.5 2389.62
  9794.4 2387.50  9865.4 2388.06  9903.5 2390.45  9936.3 2388.44  9979.7 2388.84
#Mann=20,-1,0
  1896.1   0.045       0  2637.8   0.035       0  3065.7   0.035       0
  4517.7   0.045       0  5498.6   0.045       0  5681.3   0.045       0
  5914.3   0.045       0  5927.4   0.045       0  6156.6    0.15       0
  6315.2   0.045       0  6416.7   0.035       0  6828.0    0.15       0
  7041.3   0.045       0  7158.9    0.15       0  7294.0   0.045       0
  7687.0    0.15       0  7953.2   0.035       0  8306.7   0.045       0
  8497.4   0.035       0  8640.3   0.045       0
Bank Sta=5914.3,5927.4
Exp/Cntr=0.3,0.1

Type RM Length L Ch R = 1,32946,571,571,571
BEGIN DESCRIPTION:
Buffalo Creek Trib 09 47.0
END DESCRIPTION:
XS GIS Cut Line= 4
      1282404.96      6924438.01      1285142.43      6923963.40
      1285305.00      6923738.00      1287080.00      6920763.00
#Sta/Elev= 30
  1943.4 2384.27  2024.6 2385.25  2090.2 2382.49  2270.8 2381.60  2371.8 2381.31
  2438.3 2379.81  2586.3 2379.03  2820.3 2378.35  2957.7 2378.01  4526.3 2377.61
  4594.0 2377.62  4695.0 2377.63  4807.7 2377.37  4808.2 2376.87  4821.0 2377.37
  5223.3 2377.84  5286.2 2377.79  6690.7 2377.60  6871.8 2377.91  7083.7 2378.08
  7181.5 2378.17  7470.4 2378.45  7587.6 2378.56  7695.1 2378.87  8070.8 2380.59
  8187.5 2382.34  8193.4 2383.53  8214.8 2384.30  8245.9 2383.44  8463.9 2385.42
#Mann=20,-1,0
  1943.4   0.045       0  2270.8   0.035       0  2371.8   0.045       0
  2586.3   0.035       0  2820.3    0.15       0  2957.7   0.035       0
  4526.3   0.045       0  4594.0    0.15       0  4695.0   0.045       0
  4807.7    0.07       0  4821.0    0.15       0  5223.3   0.035       0
  5286.2    0.15       0  6690.7   0.035       0  6871.8   0.035       0
  7083.7   0.035       0  7181.5    0.15       0  7470.4   0.035       0
  7587.6    0.15       0  7695.1   0.045       0
Bank Sta=4807.7,4821
Exp/Cntr=0.3,0.1

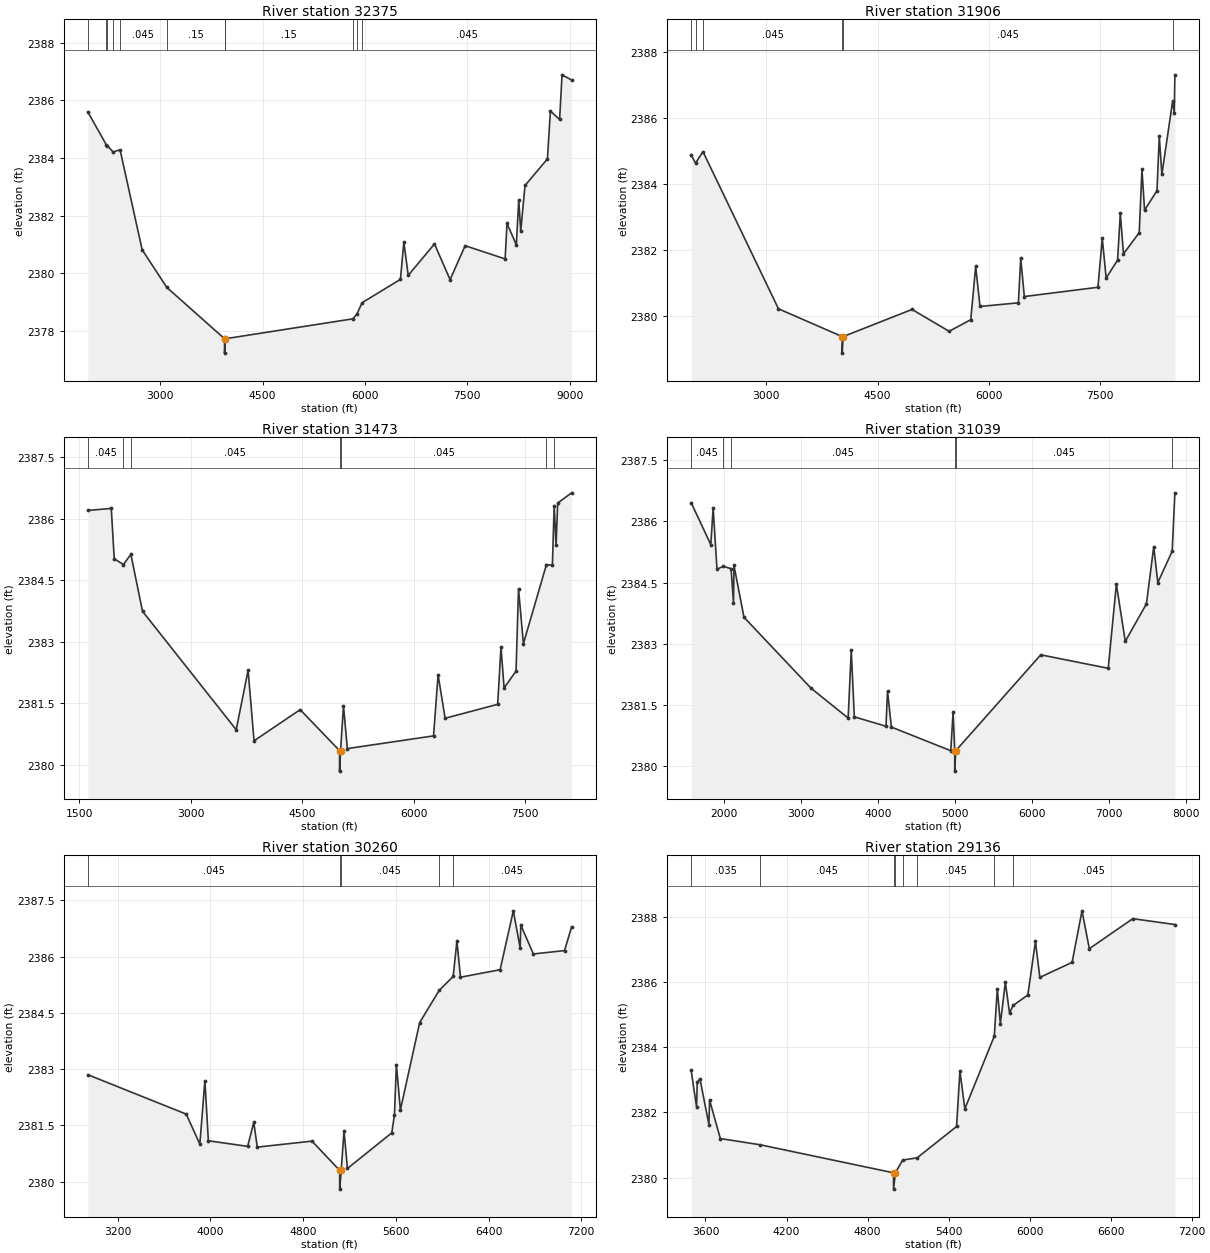
Type RM Length L Ch R = 1,32375,469,469,469
BEGIN DESCRIPTION:
Buffalo Creek Trib 09 46.0
END DESCRIPTION:
XS GIS Cut Line= 3
      1282355.02      6924788.00      1285355.00      6924188.00
      1288557.39      6921745.07
#Sta/Elev= 30
  1940.6 2385.60  2209.0 2384.47  2226.2 2384.43  2310.6 2384.21  2412.2 2384.29
  2736.0 2380.82  3097.7 2379.51  3942.9 2377.73  3943.4 2377.23  3956.3 2377.73
  5821.9 2378.42  5882.1 2378.58  5958.3 2378.98  6520.3 2379.79  6570.2 2381.08
  6634.6 2379.93  7019.2 2381.02  7247.8 2379.78  7468.2 2380.96  8054.2 2380.50
  8081.5 2381.73  8218.4 2380.99  8253.8 2382.55  8282.7 2381.47  8345.6 2383.05
  8673.7 2383.97  8717.3 2385.63  8852.4 2385.34  8887.8 2386.89  9027.8 2386.71
#Mann=11,-1,0
  1940.6   0.045       0  2209.0   0.035       0  2226.2   0.045       0
  2310.6   0.035       0  2412.2   0.045       0  3097.7    0.15       0
  3942.9    0.07       0  3956.3    0.15       0  5821.9   0.045       0
  5882.1    0.12       0  5958.3   0.045       0
Bank Sta=3942.9,3956.3
Exp/Cntr=0.3,0.1

Type RM Length L Ch R = 1,31906,433,433,433
BEGIN DESCRIPTION:
Buffalo Creek Trib 09 45.0
END DESCRIPTION:
XS GIS Cut Line= 3
      1282555.04      6924888.00      1285555.00      6924588.00
      1288555.00      6922788.00
#Sta/Elev= 30
  1989.9 2384.88  2049.1 2384.63  2148.9 2384.98  3165.7 2380.23  4023.3 2379.39
  4023.8 2378.89  4036.7 2379.39  4964.6 2380.21  5463.5 2379.55  5755.1 2379.90
  5821.2 2381.51  5879.5 2380.30  6396.5 2380.41  6427.6 2381.75  6476.2 2380.60
  7467.4 2380.88  7525.7 2382.36  7578.2 2381.16  7731.8 2381.70  7768.7 2383.11
  7811.5 2381.89  8023.3 2382.53  8060.2 2384.44  8095.2 2383.21  8262.4 2383.80
  8293.5 2385.44  8328.5 2384.29  8472.8 2386.50  8495.6 2386.16  8503.4 2387.30
#Mann=6,-1,0
  1989.9   0.045       0  2049.1   0.035       0  2148.9   0.045       0
  4023.3   0.045       0  4036.7   0.045       0  8472.8   0.035       0
Bank Sta=4023.3,4036.7
Exp/Cntr=0.3,0.1

Type RM Length L Ch R = 1,31473,434,434,434
BEGIN DESCRIPTION:
Buffalo Creek Trib 09 44.0
END DESCRIPTION:
XS GIS Cut Line= 3
      1282130.04      6925063.00      1285505.00      6924938.00
      1288505.03      6924037.99
#Sta/Elev= 30
  1616.6 2386.20  1931.8 2386.25  1971.8 2385.02  2096.1 2384.88  2195.3 2385.13
  2352.1 2383.74  3612.9 2380.85  3773.0 2382.30  3853.1 2380.58  4473.5 2381.34
  5003.7 2380.34  5004.2 2379.84  5017.1 2380.34  5056.5 2381.43  5108.7 2380.39
  6268.5 2380.70  6329.4 2382.19  6424.2 2381.13  7131.5 2381.47  7175.9 2382.87
  7217.7 2381.87  7378.6 2382.28  7411.7 2384.29  7477.8 2382.95  7787.7 2384.88
  7867.6 2384.86  7892.0 2386.32  7917.2 2385.35  7938.9 2386.38  8126.0 2386.63
#Mann=7,-1,0
  1616.6   0.045       0  2096.1   0.035       0  2195.3   0.045       0
  5003.7   0.045       0  5017.1   0.045       0  7787.7   0.035       0
  7892.0   0.045       0
Bank Sta=5003.7,5017.1
Exp/Cntr=0.3,0.1

Type RM Length L Ch R = 1,31039,779,779,779
BEGIN DESCRIPTION:
Buffalo Creek Trib 09 43.0
END DESCRIPTION:
XS GIS Cut Line= 3
      1282080.02      6925463.00      1285505.00      6925338.00
      1288204.99      6924438.00
#Sta/Elev= 30
  1576.9 2386.46  1832.1 2385.43  1862.1 2386.33  1912.1 2384.83  1995.6 2384.90
  2094.8 2384.84  2126.2 2384.01  2132.3 2384.92  2262.3 2383.65  3132.9 2381.91
  3613.2 2381.18  3653.3 2382.84  3693.3 2381.21  4103.6 2380.98  4123.6 2381.84
  4173.6 2380.96  4944.1 2380.38  4974.1 2381.33  4994.9 2380.38  4995.4 2379.88
  5008.4 2380.38  6111.0 2382.73  6985.9 2382.40  7091.3 2384.46  7207.2 2383.06
  7481.3 2383.98  7576.1 2385.38  7628.9 2384.50  7815.3 2385.27  7850.2 2386.70
#Mann=6,-1,0
  1576.9   0.045       0  1995.6   0.035       0  2094.8   0.045       0
  4994.9   0.045       0  5008.4   0.045       0  7815.3   0.035       0
Bank Sta=4994.9,5008.4
Exp/Cntr=0.3,0.1

Type RM Length L Ch R = 1,30260,1124,1124,1124
BEGIN DESCRIPTION:
Buffalo Creek Trib 09 42.9
END DESCRIPTION:
XS GIS Cut Line= 3
      1283229.74      6925769.24      1285258.66      6925966.64
      1287320.25      6925407.38
#Sta/Elev= 30
  2941.6 2382.85  3790.8 2381.80  3908.1 2381.00  3951.6 2382.69  3981.7 2381.09
  4320.6 2380.94  4373.6 2381.58  4403.7 2380.92  4875.9 2381.08  5114.6 2380.30
  5115.1 2379.80  5128.1 2380.30  5152.4 2381.36  5181.7 2380.35  5564.3 2381.30
  5587.6 2381.78  5604.2 2383.12  5638.8 2381.91  5805.2 2384.24  5973.7 2385.10
  6094.4 2385.47  6126.4 2386.41  6157.5 2385.45  6499.4 2385.65  6613.4 2387.22
  6672.5 2386.23  6677.7 2386.84  6786.8 2386.07  7055.2 2386.16  7116.2 2386.79
#Mann=5,-1,0
  2941.6   0.045       0  5114.6   0.045       0  5128.1   0.045       0
  5973.7   0.035       0  6094.4   0.045       0
Bank Sta=5114.6,5128.1
Exp/Cntr=0.3,0.1

Type RM Length L Ch R = 1,29136,625,625,625
BEGIN DESCRIPTION:
Buffalo Creek Trib 09 42.7
END DESCRIPTION:
XS GIS Cut Line= 5
      1283800.14      6926538.61      1285124.11      6926683.48
      1285383.66      6926820.63      1285722.87      6926718.44
      1287165.35      6926022.24
#Sta/Elev= 30
  3494.0 2383.29  3534.2 2382.17  3539.3 2382.93  3559.2 2383.03  3625.5 2381.63
  3630.5 2382.38  3710.1 2381.20  4004.6 2381.01  4992.3 2380.15  4992.8 2379.65
  5006.0 2380.15  5059.8 2380.54  5167.4 2380.61  5459.1 2381.57  5483.9 2383.27
  5520.5 2382.11  5738.6 2384.34  5760.7 2385.79  5783.4 2384.72  5820.3 2385.99
  5851.2 2385.05  5878.0 2385.28  5986.8 2385.60  6043.1 2387.24  6075.7 2386.14
  6314.4 2386.60  6387.8 2388.18  6442.1 2387.02  6764.1 2387.94  7075.4 2387.76
#Mann=8,-1,0
  3494.0   0.035       0  4004.6   0.045       0  4992.3   0.035       0
  5006.0   0.045       0  5059.8    0.07       0  5167.4   0.045       0
  5738.6   0.035       0  5878.0   0.045       0
Bank Sta=4992.3,5006
Exp/Cntr=0.3,0.1

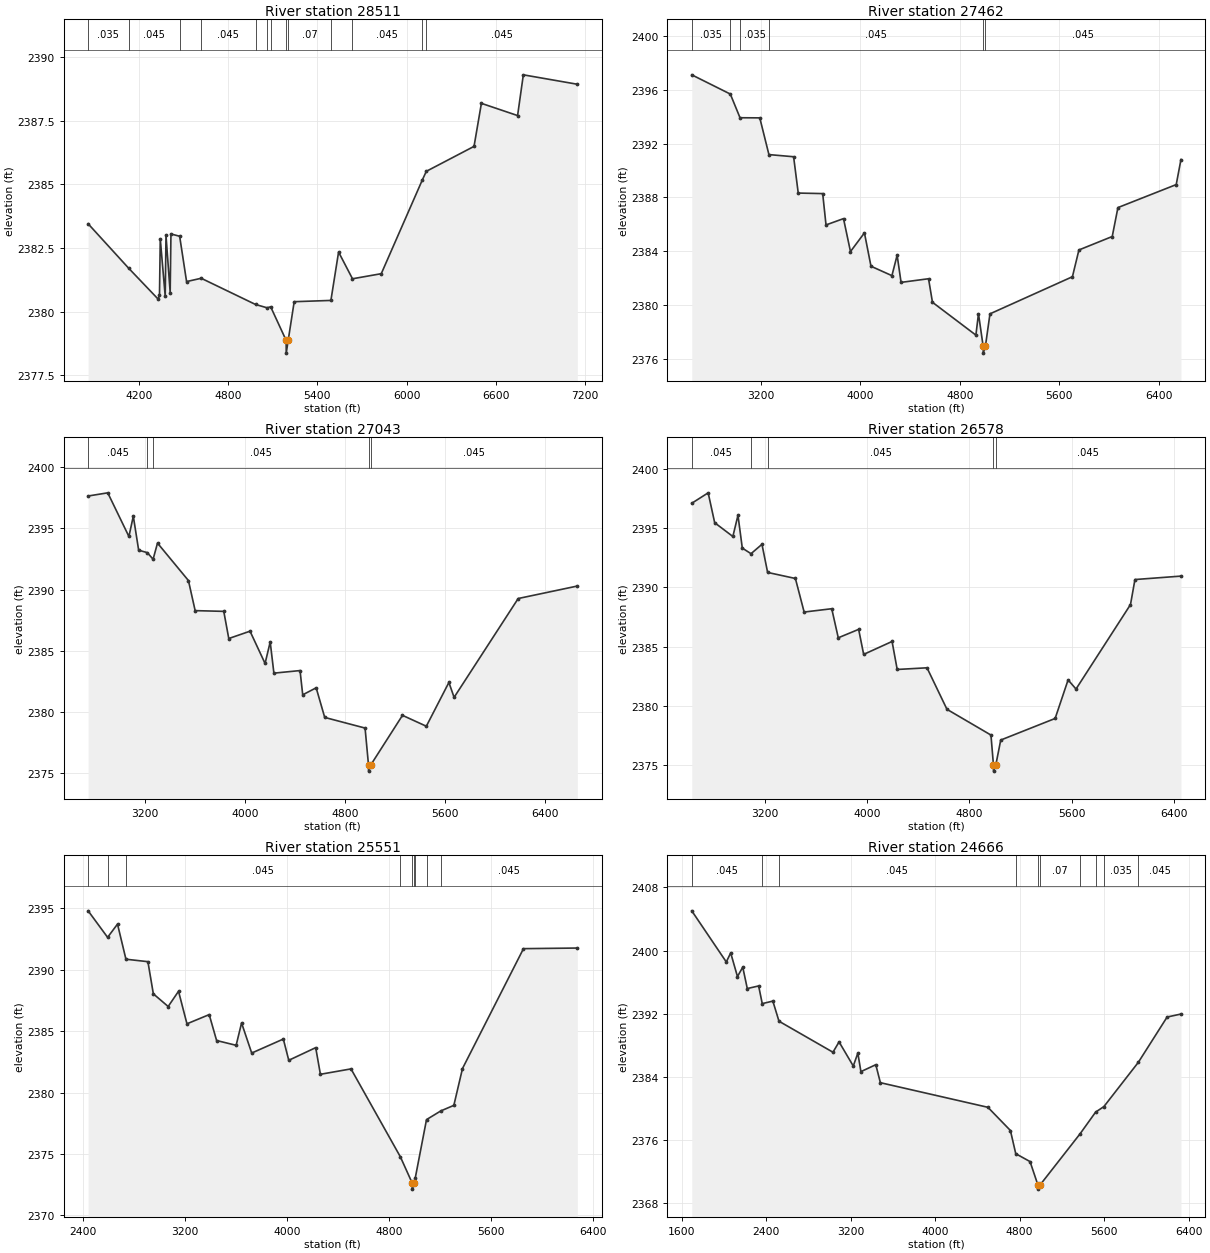
Type RM Length L Ch R = 1,28511,1049,1049,1049
BEGIN DESCRIPTION:
Buffalo Creek Trib 09 42.6
END DESCRIPTION:
XS GIS Cut Line= 5
      1283753.54      6926526.02      1284779.49      6926829.31
      1284855.00      6926838.00      1285200.42      6926920.67
      1286947.58      6926547.90
#Sta/Elev= 30
  3859.8 2383.45  4131.4 2381.71  4330.6 2380.49  4339.4 2380.65  4344.6 2382.86
  4377.9 2380.60  4383.1 2382.99  4411.2 2380.75  4416.4 2383.05  4474.9 2382.96
  4521.4 2381.18  4619.7 2381.31  4985.1 2380.28  5062.9 2380.15  5086.4 2380.19
  5190.6 2378.87  5191.1 2378.37  5204.3 2378.87  5244.6 2380.39  5491.3 2380.44
  5542.9 2382.34  5636.4 2381.29  5829.8 2381.49  6105.6 2385.17  6132.5 2385.51
  6453.2 2386.49  6502.7 2388.18  6745.9 2387.70  6784.5 2389.30  7147.3 2388.93
#Mann=13,-1,0
  3859.8   0.035       0  4131.4   0.045       0  4474.9   0.035       0
  4619.7   0.045       0  4985.1   0.035       0  5062.9   0.045       0
  5086.4    0.07       0  5190.6   0.035       0  5204.3    0.07       0
  5491.3   0.035       0  5636.4   0.045       0  6105.6   0.035       0
  6132.5   0.045       0
Bank Sta=5190.6,5204.3
Exp/Cntr=0.3,0.1

Type RM Length L Ch R = 1,27462,419,419,419
BEGIN DESCRIPTION:
Buffalo Creek Trib 09 42.0
END DESCRIPTION:
XS GIS Cut Line= 5
      1284255.00      6929937.99      1284921.48      6927893.79
      1285055.00      6927738.00      1285213.15      6927612.54
      1286530.02      6927213.00
#Sta/Elev= 30
  2644.5 2397.11  2954.5 2395.68  3032.5 2393.92  3191.4 2393.91  3264.9 2391.18
  3463.4 2391.02  3500.6 2388.32  3697.3 2388.28  3723.9 2385.95  3864.6 2386.42
  3920.6 2383.97  4032.9 2385.36  4085.5 2382.88  4253.8 2382.18  4295.8 2383.70
  4327.4 2381.68  4548.3 2381.95  4579.8 2380.20  4929.0 2377.76  4949.8 2379.35
  4987.6 2376.92  4988.1 2376.42  5005.4 2376.92  5042.2 2379.34  5705.2 2382.10
  5757.4 2384.09  6025.3 2385.09  6071.0 2387.24  6539.7 2388.95  6577.8 2390.81
#Mann=6,-1,0
  2644.5   0.035       0  2954.5   0.045       0  3032.5   0.035       0
  3264.9   0.045       0  4987.6   0.045       0  5005.4   0.045       0
Bank Sta=4987.6,5005.4
Exp/Cntr=0.3,0.1

Type RM Length L Ch R = 1,27043,465,465,465
BEGIN DESCRIPTION:
Buffalo Creek Trib 09 41.0
END DESCRIPTION:
XS GIS Cut Line= 4
      1284517.96      6930083.95      1285355.00      6927988.00
      1285468.36      6927852.12      1286830.01      6927263.00
#Sta/Elev= 30
  2743.1 2397.65  2900.3 2397.91  3069.7 2394.34  3104.9 2396.00  3147.8 2393.22
  3217.4 2393.02  3263.4 2392.48  3298.7 2393.80  3546.3 2390.74  3600.2 2388.28
  3829.4 2388.22  3869.4 2386.00  4039.6 2386.60  4160.1 2383.96  4201.2 2385.72
  4230.8 2383.17  4440.1 2383.38  4461.6 2381.40  4569.3 2381.97  4637.7 2379.55
  4960.9 2378.68  4988.4 2375.66  4988.9 2375.16  5006.2 2375.66  5260.5 2379.72
  5451.5 2378.83  5632.2 2382.41  5673.8 2381.19  6187.1 2389.27  6660.6 2390.29
#Mann=5,-1,0
  2743.1   0.045       0  3217.4   0.035       0  3263.4   0.045       0
  4988.4   0.045       0  5006.2   0.045       0
Bank Sta=4988.4,5006.2
Exp/Cntr=0.3,0.1

Type RM Length L Ch R = 1,26578,1027,1027,1027
BEGIN DESCRIPTION:
Buffalo Creek Trib 09 40.0
END DESCRIPTION:
XS GIS Cut Line= 4
      1284743.66      6930335.69      1285755.00      6928188.00
      1285843.36      6928018.79      1286979.97      6927463.02
#Sta/Elev= 30
  2626.6 2397.09  2755.0 2397.97  2806.1 2395.45  2948.4 2394.29  2988.4 2396.08
  3022.3 2393.31  3090.6 2392.84  3176.3 2393.63  3220.5 2391.26  3438.0 2390.75
  3506.4 2387.92  3722.5 2388.20  3773.6 2385.75  3933.2 2386.46  3972.5 2384.35
  4194.9 2385.44  4235.0 2383.08  4468.4 2383.22  4624.7 2379.72  4969.1 2377.55
  4988.7 2375.01  4989.2 2374.51  5006.7 2375.01  5045.6 2377.13  5471.5 2378.95
  5573.0 2382.20  5635.0 2381.43  6061.5 2388.55  6096.4 2390.66  6456.6 2390.95
#Mann=5,-1,0
  2626.6   0.045       0  3090.6   0.035       0  3220.5   0.045       0
  4988.7   0.045       0  5006.7   0.045       0
Bank Sta=4988.7,5006.7
Exp/Cntr=0.3,0.1

Type RM Length L Ch R = 1,25551,885,885,885
BEGIN DESCRIPTION:
Buffalo Creek Trib 09 39.3
END DESCRIPTION:
XS GIS Cut Line= 2
      1285138.00      6930836.04      1287123.06      6927545.89
#Sta/Elev= 30
  2437.4 2394.80  2590.4 2392.64  2668.2 2393.72  2734.4 2390.86  2907.0 2390.66
  2949.7 2388.04  3066.2 2387.01  3147.5 2388.25  3213.7 2385.60  3388.4 2386.35
  3446.6 2384.24  3600.0 2383.85  3642.7 2385.67  3722.3 2383.22  3970.7 2384.36
  4013.4 2382.63  4225.0 2383.66  4261.9 2381.49  4502.3 2381.93  4890.1 2374.77
  4982.7 2372.64  4983.2 2372.14  5000.8 2372.64  5007.3 2373.06  5095.4 2377.80
  5208.0 2378.51  5310.1 2378.96  5378.0 2381.96  5857.1 2391.72  6280.0 2391.77
#Mann=9,-1,0
  2437.4   0.045       0  2590.4   0.035       0  2734.4   0.045       0
  4890.1    0.07       0  4982.7   0.045       0  5000.8    0.07       0
  5007.3   0.035       0  5095.4    0.07       0  5208.0   0.045       0
Bank Sta=4982.7,5000.8
Exp/Cntr=0.3,0.1

Type RM Length L Ch R = 1,24666,211,211,211
BEGIN DESCRIPTION:
Buffalo Creek Trib 09 39.2
END DESCRIPTION:
XS GIS Cut Line= 3
      1284885.79      6931987.54      1286870.81      6929465.13
      1287111.94      6928062.21
#Sta/Elev= 30
  1694.3 2405.03  2021.4 2398.55  2063.0 2399.70  2127.1 2396.70  2177.3 2397.89
  2220.2 2395.18  2327.7 2395.51  2361.9 2393.27  2462.3 2393.59  2520.4 2391.04
  3031.6 2387.11  3089.4 2388.42  3224.1 2385.36  3267.4 2387.00  3296.3 2384.65
  3437.4 2385.53  3480.7 2383.25  4499.1 2380.13  4712.3 2377.19  4762.9 2374.25
  4898.4 2373.25  4973.3 2370.26  4973.8 2369.76  4991.5 2370.26  5371.5 2376.76
  5519.3 2379.52  5597.7 2380.22  5924.4 2385.84  6196.5 2391.57  6327.6 2391.95
#Mann=10,-1,0
  1694.3   0.045       0  2361.9   0.035       0  2520.4   0.045       0
  4762.9    0.07       0  4973.3    0.07       0  4991.5    0.07       0
  5371.5   0.035       0  5519.3    0.07       0  5597.7   0.035       0
  5924.4   0.045       0
Bank Sta=4973.3,4991.5
Exp/Cntr=0.3,0.1