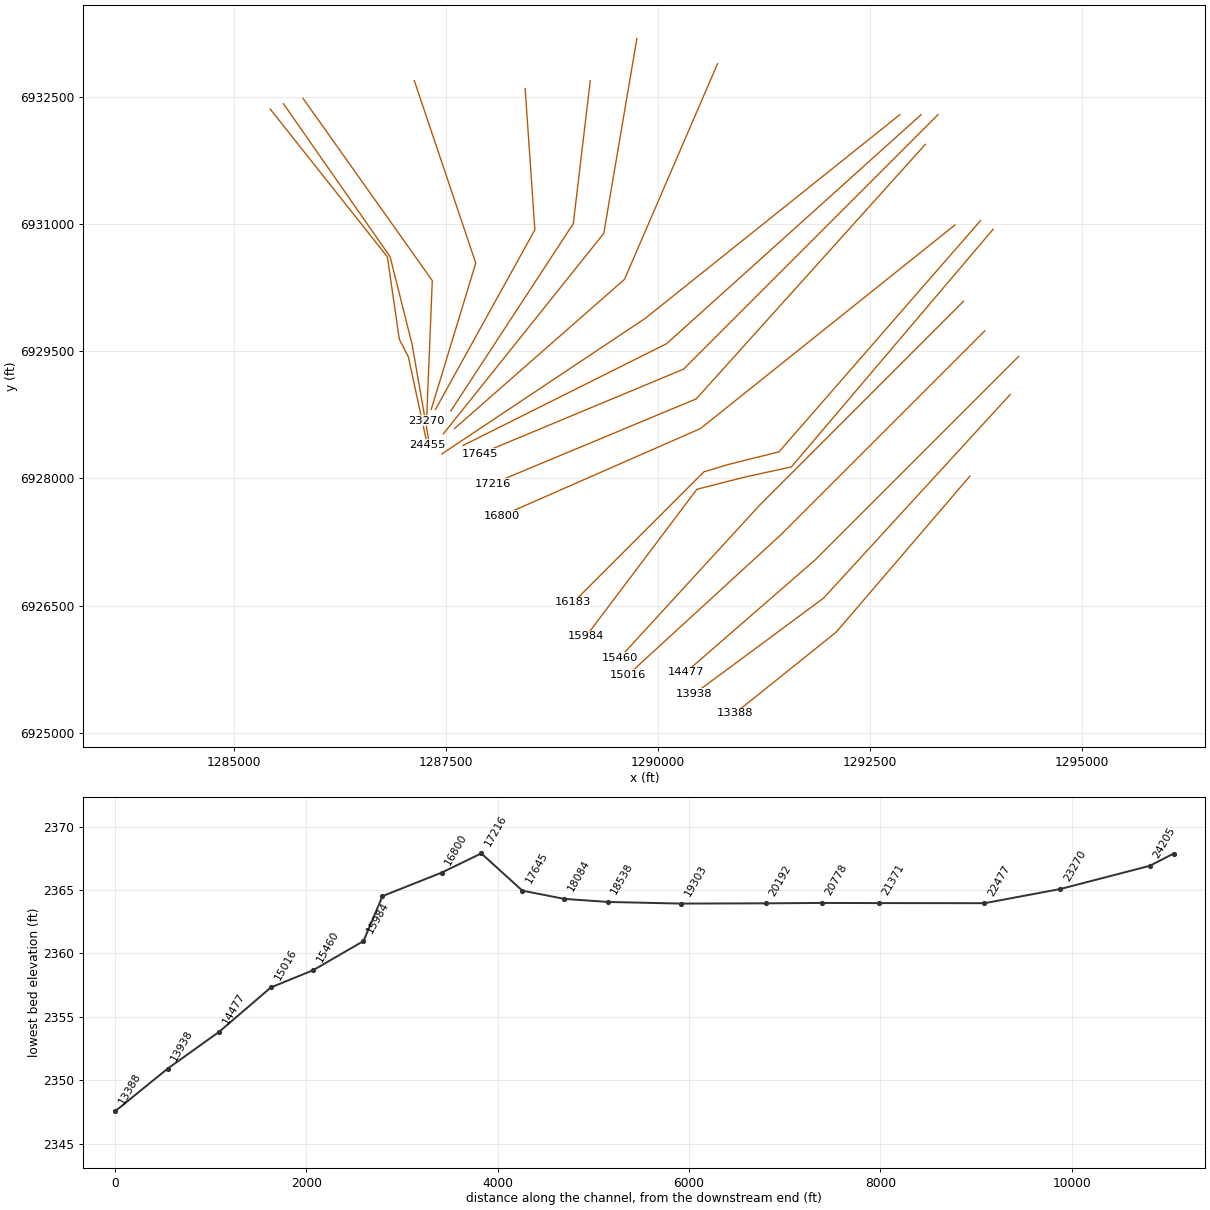
HEC-RAS study Buffalo Creek Trib 09.prj: Buffalo Creek Trib 09 Base Level Engineering

--- Buffalo Creek Trib 09.g01 (geometry) --- (continued)

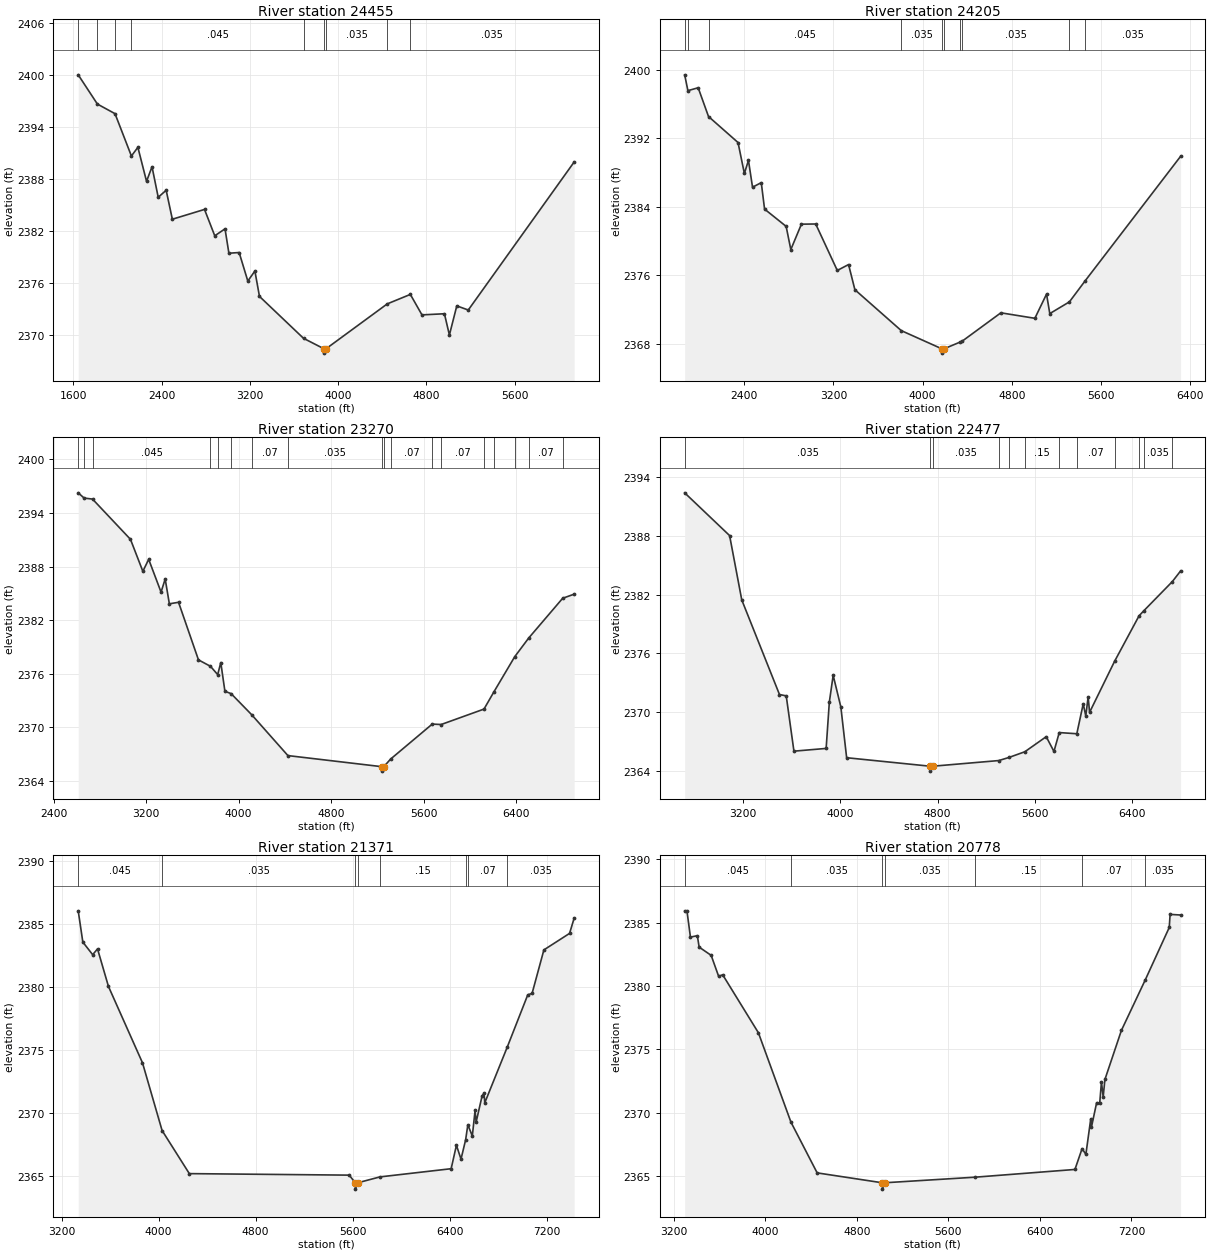
Type RM Length L Ch R = 1,24455,250,250,250
BEGIN DESCRIPTION:
Buffalo Creek Trib 09 39.4
END DESCRIPTION:
XS GIS Cut Line= 5
      1285431.61      6932354.14      1286812.72      6930613.00
      1286953.81      6929639.67      1287060.14      6929433.51
      1287283.14      6928398.73
#Sta/Elev= 30
  1642.8 2399.98  1816.6 2396.61  1976.5 2395.50  2125.1 2390.62  2183.8 2391.62
  2262.3 2387.70  2312.0 2389.38  2368.1 2385.86  2440.2 2386.67  2496.2 2383.33
  2787.9 2384.46  2880.8 2381.42  2973.8 2382.22  3009.0 2379.41  3101.9 2379.49
  3180.5 2376.20  3244.6 2377.36  3286.2 2374.43  3685.4 2369.60  3871.2 2368.39
  3871.7 2367.89  3889.4 2368.39  4444.9 2373.57  4654.1 2374.66  4759.4 2372.30
  4963.1 2372.43  5008.1 2369.98  5075.2 2373.34  5179.2 2372.86  6139.2 2389.93
#Mann=9,-1,0
  1642.8   0.035       0  1816.6   0.045       0  1976.5   0.035       0
  2125.1   0.045       0  3685.4   0.035       0  3871.2   0.035       0
  3889.4   0.035       0  4444.9   0.045       0  4654.1   0.035       0
Bank Sta=3871.2,3889.4
Exp/Cntr=0.3,0.1

Type RM Length L Ch R = 1,24205,935,935,935
BEGIN DESCRIPTION:
Buffalo Creek Trib 09 39.1
END DESCRIPTION:
XS GIS Cut Line= 5
      1285587.41      6932417.56      1286845.16      6930613.00
      1287060.14      6929754.69      1287102.90      6929588.89
      1287307.60      6928411.12
#Sta/Elev= 30
  1864.7 2399.44  1893.6 2397.59  1985.8 2397.93  2078.5 2394.57  2343.5 2391.53
  2400.5 2387.91  2437.1 2389.45  2473.6 2386.31  2552.1 2386.84  2581.7 2383.75
  2775.4 2381.73  2817.3 2379.02  2912.4 2381.99  3040.7 2382.01  3234.4 2376.58
  3335.6 2377.27  3392.3 2374.33  3808.7 2369.55  4173.8 2367.42  4174.3 2366.92
  4192.0 2367.42  4334.4 2368.20  4352.5 2368.29  4702.5 2371.63  5007.7 2370.99
  5112.5 2373.82  5141.6 2371.54  5317.7 2372.91  5460.8 2375.40  6315.8 2389.92
#Mann=10,-1,0
  1864.7   0.045       0  1893.6   0.035       0  2078.5   0.045       0
  3808.7   0.035       0  4173.8   0.035       0  4192.0   0.035       0
  4334.4    0.07       0  4352.5   0.035       0  5317.7    0.07       0
  5460.8   0.035       0
Bank Sta=4173.8,4192
Exp/Cntr=0.3,0.1

Type RM Length L Ch R = 1,23270,793,793,793
BEGIN DESCRIPTION:
Buffalo Creek Trib 09 39 0.1
END DESCRIPTION:
XS GIS Cut Line= 3
      1285817.98      6932481.06      1287342.40      6930331.53
      1287275.14      6928678.20
#Sta/Elev= 30
  2612.0 2396.26  2663.4 2395.67  2735.8 2395.56  3064.1 2391.05  3171.1 2387.47
  3221.6 2388.81  3328.6 2385.14  3364.3 2386.61  3400.4 2383.83  3479.9 2384.00
  3652.2 2377.55  3756.1 2376.83  3818.5 2375.90  3845.3 2377.25  3881.0 2374.03
  3934.6 2373.77  4113.1 2371.40  4425.9 2366.83  5237.2 2365.59  5237.7 2365.09
  5255.4 2365.59  5314.3 2366.44  5674.6 2370.36  5751.4 2370.31  6122.1 2372.04
  6205.2 2373.91  6388.1 2377.91  6508.3 2379.99  6802.6 2384.45  6901.9 2384.91
#Mann=18,-1,0
  2612.0   0.045       0  2663.4   0.035       0  2735.8   0.045       0
  3756.1   0.035       0  3818.5   0.045       0  3934.6   0.035       0
  4113.1    0.07       0  4425.9   0.035       0  5237.2   0.035       0
  5255.4   0.035       0  5314.3    0.07       0  5674.6   0.035       0
  5751.4    0.07       0  6122.1   0.035       0  6205.2    0.07       0
  6388.1   0.035       0  6508.3    0.07       0  6802.6   0.035       0
Bank Sta=5237.2,5255.4
Exp/Cntr=0.3,0.1

Type RM Length L Ch R = 1,22477,1106,1106,1106
BEGIN DESCRIPTION:
Buffalo Creek Trib 09 39.0
END DESCRIPTION:
XS GIS Cut Line= 3
      1287130.78      6932688.20      1287855.00      6930538.00
      1287330.00      6928813.01
#Sta/Elev= 30
  2723.6 2392.41  3092.5 2388.04  3192.2 2381.47  3501.9 2371.80  3557.4 2371.66
  3620.7 2366.01  3885.1 2366.29  3911.3 2371.02  3942.8 2373.76  4005.8 2370.53
  4053.4 2365.34  4740.6 2364.47  4741.1 2363.97  4758.9 2364.47  5302.6 2365.05
  5386.8 2365.37  5516.6 2365.95  5692.1 2367.49  5755.5 2365.98  5799.1 2367.91
  5943.3 2367.79  5996.0 2370.85  6016.9 2369.61  6036.3 2371.56  6048.2 2369.98
  6252.9 2375.18  6454.3 2379.84  6491.3 2380.33  6727.7 2383.34  6795.6 2384.43
#Mann=12,-1,0
  2723.6   0.035       0  4740.6   0.035       0  4758.9   0.035       0
  5302.6    0.15       0  5386.8   0.035       0  5516.6    0.15       0
  5799.1   0.035       0  5943.3    0.07       0  6252.9   0.035       0
  6454.3    0.07       0  6491.3   0.035       0  6727.7    0.07       0
Bank Sta=4740.6,4758.9
Exp/Cntr=0.3,0.1

Type RM Length L Ch R = 1,21371,593,593,593
BEGIN DESCRIPTION:
Buffalo Creek Trib 09 38.0
END DESCRIPTION:
XS GIS Cut Line= 3
      1288437.11      6932596.92      1288551.69      6930930.25
      1287380.02      6928813.04
#Sta/Elev= 30
  3336.7 2386.06  3374.8 2383.58  3455.9 2382.58  3496.0 2383.04  3586.2 2380.06
  3866.9 2374.00  4028.5 2368.63  4253.2 2365.21  5572.0 2365.09  5622.1 2364.48
  5622.6 2363.98  5641.0 2364.48  5825.2 2364.95  6412.6 2365.60  6456.1 2367.46
  6493.9 2366.36  6532.0 2367.89  6550.4 2369.09  6587.1 2368.19  6610.0 2370.22
  6618.7 2369.30  6667.9 2371.38  6684.0 2371.59  6690.0 2370.83  6874.6 2375.23
  7044.3 2379.39  7080.2 2379.51  7177.5 2382.96  7389.3 2384.27  7427.1 2385.48
#Mann=8,-1,0
  3336.7   0.045       0  4028.5   0.035       0  5622.1   0.035       0
  5641.0   0.035       0  5825.2    0.15       0  6532.0   0.035       0
  6550.4    0.07       0  6874.6   0.035       0
Bank Sta=5622.1,5641
Exp/Cntr=0.3,0.1

Type RM Length L Ch R = 1,20778,586,586,586
BEGIN DESCRIPTION:
Buffalo Creek Trib 09 37.0
END DESCRIPTION:
XS GIS Cut Line= 3
      1289205.00      6932687.97      1289004.81      6931003.16
      1287560.48      6928794.92
#Sta/Elev= 30
  3295.4 2385.92  3315.5 2385.90  3345.7 2383.85  3406.1 2383.96  3421.9 2383.06
  3527.0 2382.41  3592.2 2380.76  3627.7 2380.88  3939.9 2376.31  4224.3 2369.27
  4453.5 2365.27  5023.2 2364.49  5023.7 2363.99  5042.2 2364.49  5832.6 2364.93
  6706.9 2365.54  6769.3 2367.18  6802.5 2366.73  6845.2 2369.53  6851.2 2368.87
  6896.5 2370.80  6923.5 2370.77  6938.6 2372.43  6953.8 2371.26  6968.9 2372.63
  7113.2 2376.50  7322.8 2380.50  7531.4 2384.61  7538.8 2385.64  7630.7 2385.59
#Mann=7,-1,0
  3295.4   0.045       0  4224.3   0.035       0  5023.2   0.035       0
  5042.2   0.035       0  5832.6    0.15       0  6769.3    0.07       0
  7322.8   0.035       0
Bank Sta=5023.2,5042.2
Exp/Cntr=0.3,0.1

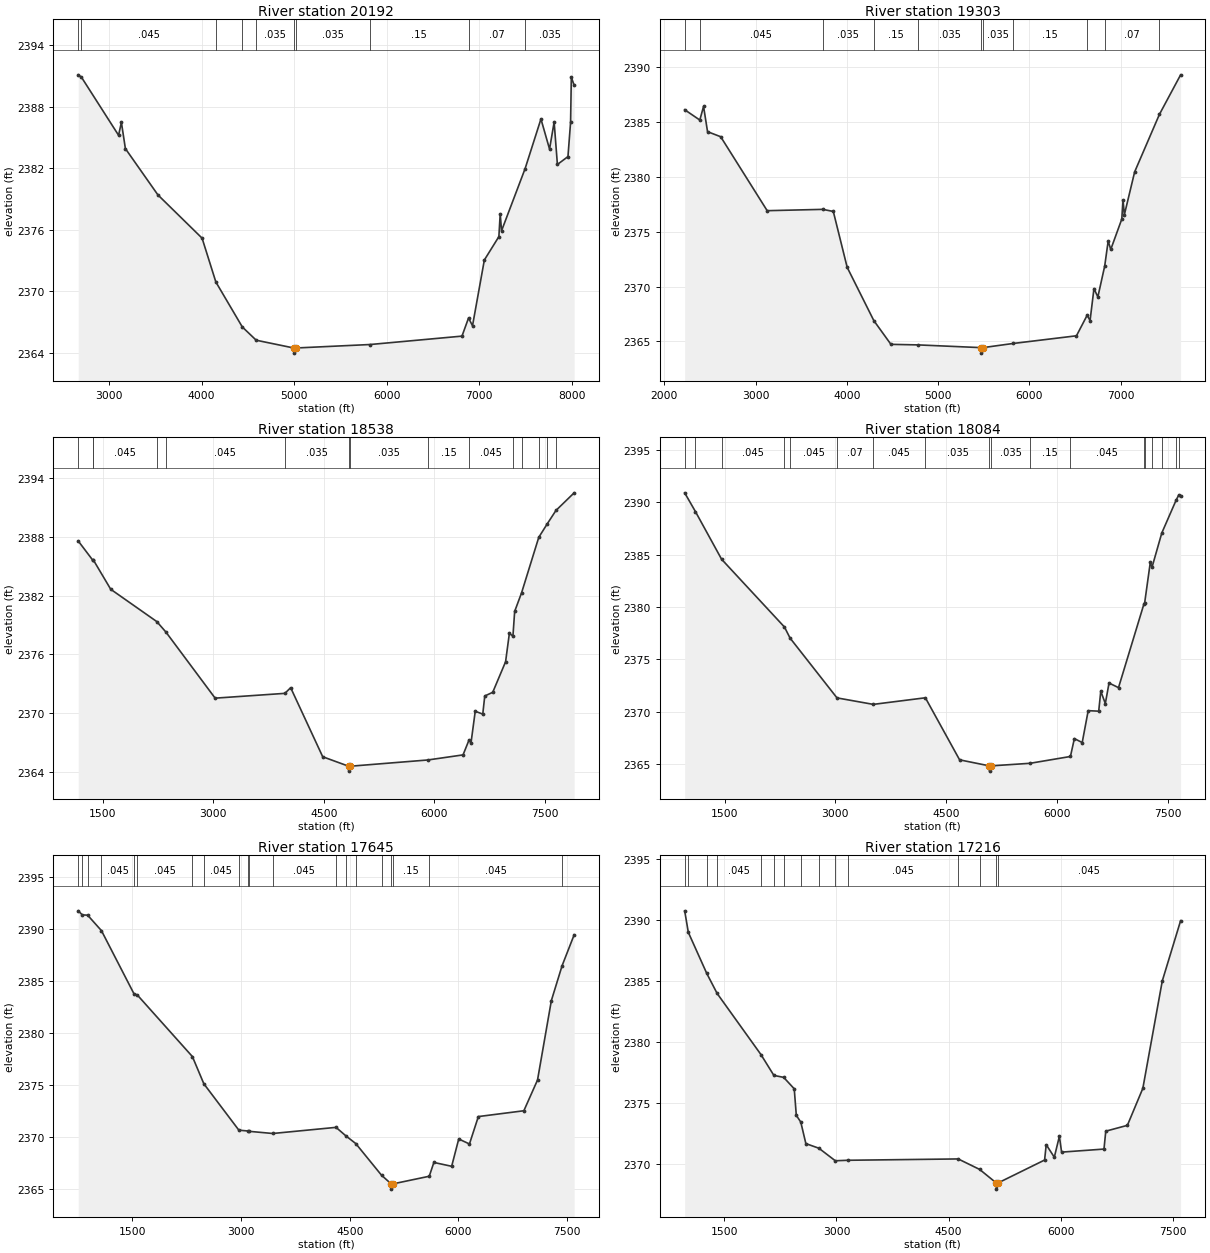
Type RM Length L Ch R = 1,20192,889,889,889
BEGIN DESCRIPTION:
Buffalo Creek Trib 09 36.0
END DESCRIPTION:
XS GIS Cut Line= 3
      1289754.99      6933187.96      1289364.19      6930888.58
      1287473.65      6928525.79
#Sta/Elev= 30
  2666.4 2391.12  2701.3 2390.89  3102.5 2385.22  3133.0 2386.48  3176.1 2383.92
  3527.6 2379.40  4004.7 2375.18  4153.7 2370.90  4439.6 2366.51  4589.5 2365.22
  4996.1 2364.46  4996.6 2363.96  5015.2 2364.46  5820.0 2364.80  6812.9 2365.62
  6883.8 2367.39  6926.6 2366.63  7054.6 2373.05  7211.5 2375.33  7225.9 2377.57
  7240.3 2375.90  7494.7 2381.96  7666.1 2386.81  7759.0 2383.87  7808.6 2386.51
  7843.8 2382.37  7957.9 2383.14  7986.3 2386.50  7994.3 2390.90  8024.8 2390.09
#Mann=10,-1,0
  2666.4   0.035       0  2701.3   0.045       0  4153.7   0.035       0
  4439.6    0.15       0  4589.5   0.035       0  4996.1   0.035       0
  5015.2   0.035       0  5820.0    0.15       0  6883.8    0.07       0
  7494.7   0.035       0
Bank Sta=4996.1,5015.2
Exp/Cntr=0.3,0.1

Type RM Length L Ch R = 1,19303,765,765,765
BEGIN DESCRIPTION:
Buffalo Creek Trib 09 35.0
END DESCRIPTION:
XS GIS Cut Line= 3
      1290705.00      6932888.00      1289608.98      6930346.91
      1287604.98      6928587.99
#Sta/Elev= 30
  2222.8 2386.12  2388.6 2385.18  2429.7 2386.42  2473.3 2384.12  2617.2 2383.66
  3126.7 2376.92  3735.9 2377.04  3851.2 2376.85  4003.1 2371.76  4295.4 2366.90
  4482.6 2364.74  4779.2 2364.69  5471.6 2364.44  5472.1 2363.94  5490.8 2364.44
  5821.3 2364.82  6515.5 2365.52  6632.4 2367.39  6664.5 2366.91  6707.2 2369.82
  6749.9 2369.06  6824.9 2371.88  6862.8 2374.15  6891.3 2373.39  7011.8 2376.15
  7026.0 2377.86  7040.2 2376.55  7153.2 2380.46  7424.6 2385.70  7656.6 2389.30
#Mann=11,-1,0
  2222.8   0.035       0  2388.6   0.045       0  3735.9   0.035       0
  4295.4    0.15       0  4779.2   0.035       0  5471.6   0.035       0
  5490.8   0.035       0  5821.3    0.15       0  6632.4   0.045       0
  6824.9    0.07       0  7424.6   0.035       0
Bank Sta=5471.6,5490.8
Exp/Cntr=0.3,0.1

Type RM Length L Ch R = 1,18538,454,454,454
BEGIN DESCRIPTION:
Buffalo Creek Trib 09 34.0
END DESCRIPTION:
XS GIS Cut Line= 3
      1292854.97      6932287.98      1289855.00      6929888.00
      1287454.98      6928287.99
#Sta/Elev= 30
  1170.4 2387.60  1368.2 2385.63  1374.6 2385.67  1611.4 2382.66  2235.7 2379.36
  2359.6 2378.29  3027.3 2371.53  3973.5 2372.02  4051.8 2372.60  4486.4 2365.54
  4838.5 2364.57  4839.0 2364.07  4857.9 2364.57  5912.4 2365.21  6389.9 2365.73
  6471.3 2367.26  6498.0 2366.97  6555.1 2370.19  6657.3 2369.90  6684.3 2371.75
  6792.5 2372.13  6966.7 2375.25  7017.8 2378.14  7066.5 2377.88  7089.9 2380.40
  7183.3 2382.29  7416.8 2387.97  7533.5 2389.37  7650.2 2390.72  7896.7 2392.52
#Mann=15,-1,0
  1170.4   0.045       0  1368.2    0.07       0  1374.6   0.045       0
  2235.7   0.035       0  2359.6   0.045       0  3973.5   0.035       0
  4838.5   0.035       0  4857.9   0.035       0  5912.4    0.15       0
  6471.3   0.045       0  7066.5   0.035       0  7183.3    0.07       0
  7416.8   0.035       0  7533.5    0.07       0  7650.2   0.045       0
Bank Sta=4838.5,4857.9
Exp/Cntr=0.3,0.1

Type RM Length L Ch R = 1,18084,439,439,439
BEGIN DESCRIPTION:
Buffalo Creek Trib 09 33.0
END DESCRIPTION:
XS GIS Cut Line= 3
      1293105.00      6932288.00      1290105.00      6929588.00
      1287704.97      6928387.98
#Sta/Elev= 30
   958.0 2390.91  1103.5 2389.12  1458.4 2384.56  2310.3 2378.08  2385.5 2377.03
  3021.6 2371.31  3513.4 2370.69  4219.3 2371.32  4682.8 2365.39  5087.8 2364.81
  5088.3 2364.31  5107.2 2364.81  5639.0 2365.06  6184.5 2365.71  6237.9 2367.42
  6344.1 2367.04  6425.2 2370.09  6567.7 2370.04  6595.7 2371.95  6657.2 2370.77
  6707.5 2372.73  6836.0 2372.29  7180.1 2380.28  7190.4 2380.40  7266.5 2384.26
  7289.2 2383.78  7422.3 2387.07  7616.6 2390.21  7654.1 2390.73  7677.4 2390.59
#Mann=18,-1,0
   958.0   0.035       0  1103.5    0.07       0  1458.4   0.045       0
  2310.3   0.035       0  2385.5   0.045       0  3021.6    0.07       0
  3513.4   0.045       0  4219.3   0.035       0  5087.8   0.035       0
  5107.2   0.035       0  5639.0    0.15       0  6184.5   0.045       0
  7180.1   0.035       0  7190.4   0.045       0  7289.2    0.07       0
  7422.3   0.035       0  7616.6    0.07       0  7654.1   0.045       0
Bank Sta=5087.8,5107.2
Exp/Cntr=0.3,0.1

Type RM Length L Ch R = 1,17645,429,429,429
BEGIN DESCRIPTION:
Buffalo Creek Trib 09 32.0
END DESCRIPTION:
XS GIS Cut Line= 3
      1293304.97      6932287.97      1290305.00      6929288.00
      1287904.99      6928288.00
#Sta/Elev= 30
   753.5 2391.77   810.2 2391.38   883.7 2391.35  1074.1 2389.86  1523.5 2383.77
  1567.9 2383.67  2328.8 2377.73  2486.8 2375.11  2970.1 2370.64  3094.9 2370.56
  3108.6 2370.53  3437.7 2370.32  4310.7 2370.91  4446.8 2370.09  4582.9 2369.35
  4938.3 2366.30  5072.5 2365.46  5073.0 2364.96  5091.9 2365.46  5596.7 2366.20
  5660.7 2367.53  5906.1 2367.16  6003.6 2369.79  6151.5 2369.31  6274.4 2371.95
  6902.2 2372.51  7090.7 2375.47  7281.9 2383.13  7430.1 2386.49  7596.1 2389.46
#Mann=20,-1,0
   753.5   0.035       0   810.2   0.045       0   883.7   0.035       0
  1074.1   0.045       0  1523.5    0.07       0  1567.9   0.045       0
  2328.8   0.035       0  2486.8   0.045       0  2970.1    0.07       0
  3094.9   0.045       0  3108.6    0.07       0  3437.7   0.045       0
  4310.7   0.035       0  4446.8   0.045       0  4582.9   0.035       0
  4938.3    0.15       0  5072.5    0.07       0  5091.9    0.15       0
  5596.7   0.045       0  7430.1   0.035       0
Bank Sta=5072.5,5091.9
Exp/Cntr=0.3,0.1

Type RM Length L Ch R = 1,17216,416,416,416
BEGIN DESCRIPTION:
Buffalo Creek Trib 09 31.0
END DESCRIPTION:
XS GIS Cut Line= 3
      1293154.98      6931937.98      1290455.00      6928938.00
      1288054.96      6927937.99
#Sta/Elev= 30
   968.8 2390.76  1017.6 2388.99  1264.2 2385.62  1403.4 2383.97  1989.6 2378.95
  2162.5 2377.24  2293.4 2377.08  2434.8 2376.14  2462.5 2373.96  2522.3 2373.41
  2590.3 2371.64  2764.5 2371.26  2984.2 2370.23  3151.5 2370.27  4628.6 2370.38
  4915.3 2369.52  5139.8 2368.40  5140.3 2367.90  5159.2 2368.40  5784.9 2370.29
  5806.5 2371.55  5914.9 2370.52  5982.6 2372.24  6012.4 2370.94  6579.5 2371.19
  6603.3 2372.66  6892.6 2373.14  7099.5 2376.18  7359.5 2385.00  7604.9 2389.95
#Mann=15,-1,0
   968.8   0.035       0  1017.6   0.045       0  1264.2    0.07       0
  1403.4   0.045       0  1989.6   0.035       0  2162.5   0.045       0
  2293.4   0.035       0  2522.3   0.045       0  2764.5    0.07       0
  2984.2   0.035       0  3151.5   0.045       0  4628.6   0.035       0
  4915.3   0.045       0  5139.8   0.045       0  5159.2   0.045       0
Bank Sta=5139.8,5159.2
Exp/Cntr=0.3,0.1

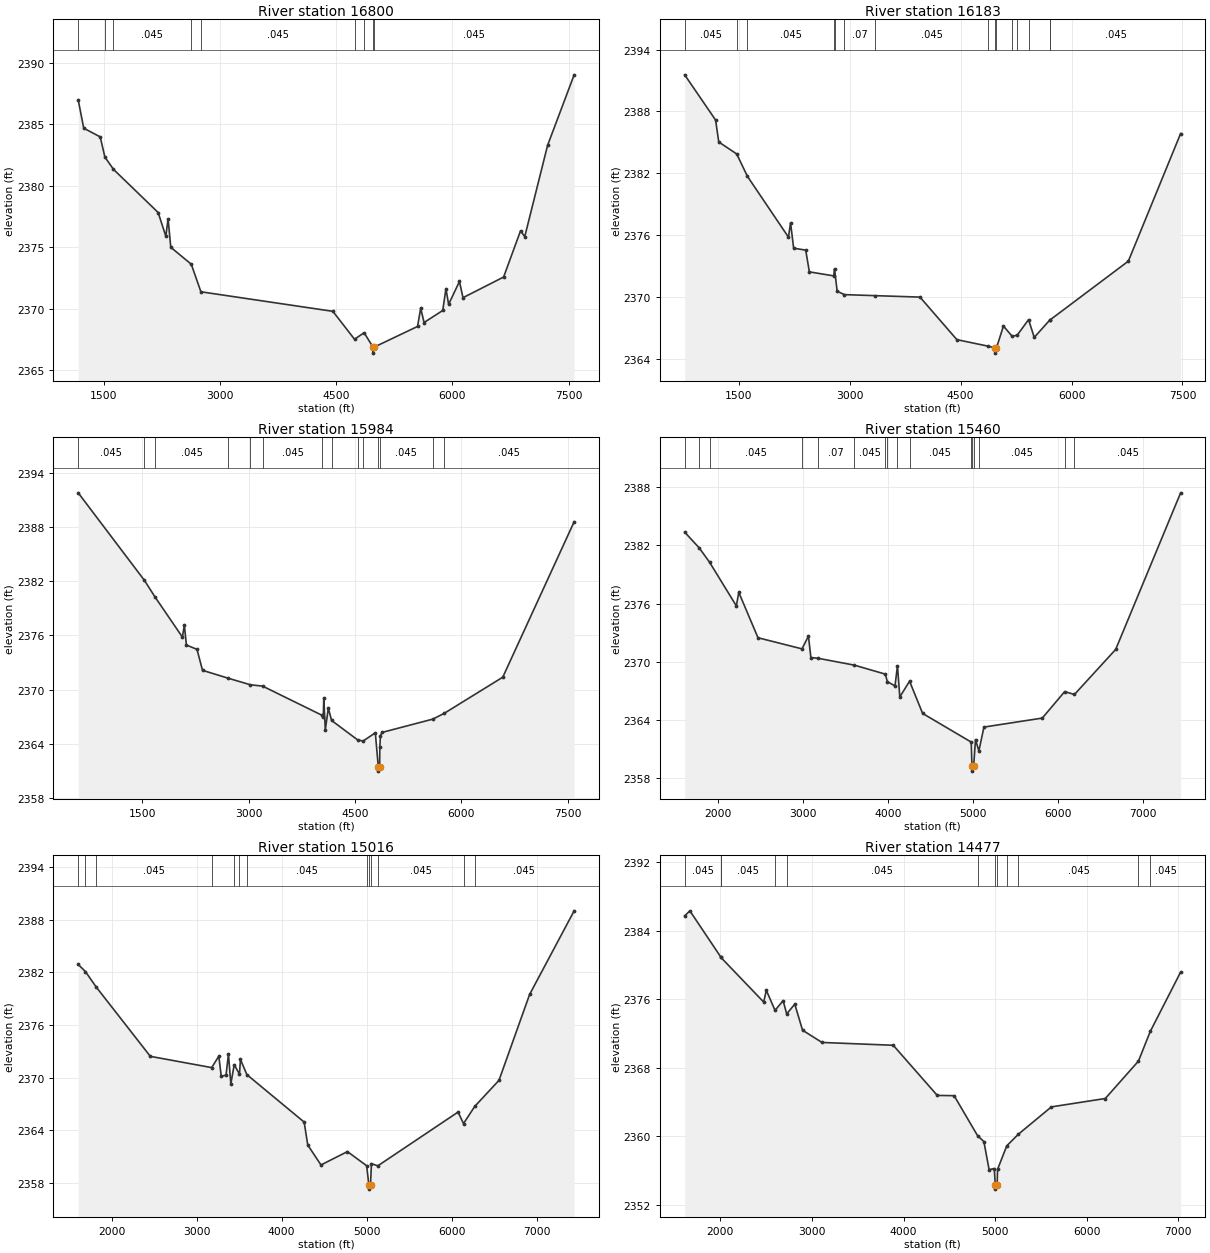
Type RM Length L Ch R = 1,16800,617,617,617
BEGIN DESCRIPTION:
Buffalo Creek Trib 09 30.0
END DESCRIPTION:
XS GIS Cut Line= 3
      1293505.02      6930988.02      1290505.00      6928588.00
      1288161.28      6927559.40
#Sta/Elev= 30
  1169.0 2386.98  1240.3 2384.68  1453.2 2383.97  1513.3 2382.33  1624.4 2381.33
  2200.7 2377.82  2300.0 2375.89  2328.8 2377.31  2364.0 2374.99  2628.7 2373.61
  2752.6 2371.37  4456.2 2369.78  4735.5 2367.51  4859.4 2368.04  4973.2 2366.88
  4973.7 2366.38  4992.6 2366.88  5548.7 2368.55  5589.7 2370.03  5633.4 2368.87
  5874.2 2369.85  5915.5 2371.62  5950.1 2370.35  6090.0 2372.21  6135.7 2370.89
  6659.9 2372.57  6878.3 2376.33  6932.9 2375.86  7227.8 2383.29  7570.4 2389.02
#Mann=9,-1,0
  1169.0   0.045       0  1513.3   0.035       0  1624.4   0.045       0
  2628.7   0.035       0  2752.6   0.045       0  4735.5   0.035       0
  4859.4   0.045       0  4973.2   0.045       0  4992.6   0.045       0
Bank Sta=4973.2,4992.6
Exp/Cntr=0.3,0.1

Type RM Length L Ch R = 1,16183,199,199,199
BEGIN DESCRIPTION:
Buffalo Creek Trib 09 29.0
END DESCRIPTION:
XS GIS Cut Line= 5
      1293805.02      6931038.02      1291430.00      6928313.00
      1290829.89      6928163.11      1290544.26      6928077.26
      1289005.00      6926538.00
#Sta/Elev= 30
   766.7 2391.55  1184.9 2387.16  1227.7 2385.03  1470.1 2383.87  1615.9 2381.69
  2170.4 2375.79  2198.9 2377.18  2240.6 2374.72  2403.9 2374.53  2453.3 2372.42
  2782.7 2372.03  2793.6 2372.72  2829.2 2370.54  2926.7 2370.21  3344.4 2370.11
  3949.5 2369.97  4448.5 2365.84  4868.0 2365.21  4964.4 2365.03  4964.9 2364.53
  4983.9 2365.03  5078.2 2367.16  5198.2 2366.15  5266.1 2366.29  5418.3 2367.78
  5495.2 2366.06  5706.6 2367.75  5712.1 2367.77  6768.0 2373.46  7475.1 2385.85
#Mann=15,-1,0
   766.7   0.045       0  1470.1   0.035       0  1615.9   0.045       0
  2782.7   0.035       0  2793.6   0.045       0  2926.7    0.07       0
  3344.4   0.045       0  4868.0   0.035       0  4964.4   0.035       0
  4983.9   0.035       0  5198.2   0.045       0  5266.1   0.035       0
  5418.3   0.045       0  5706.6   0.035       0  5712.1   0.045       0
Bank Sta=4964.4,4983.9
Exp/Cntr=0.3,0.1

Type RM Length L Ch R = 1,15984,524,524,524
BEGIN DESCRIPTION:
Buffalo Creek Trib 09 28.0
END DESCRIPTION:
XS GIS Cut Line= 5
      1293955.03      6930938.03      1291576.44      6928135.36
      1291034.54      6928017.54      1290461.85      6927871.47
      1289155.02      6926138.02
#Sta/Elev= 30
   597.3 2391.79  1530.7 2382.10  1678.6 2380.28  2066.3 2375.82  2093.9 2377.14
  2122.5 2374.94  2271.9 2374.46  2349.9 2372.14  2714.4 2371.26  3025.1 2370.54
  3197.6 2370.39  4038.3 2367.15  4052.4 2366.95  4059.9 2369.08  4081.0 2365.53
  4123.8 2367.95  4169.8 2366.59  4536.3 2364.44  4613.5 2364.31  4786.4 2365.22
  4827.9 2361.48  4828.4 2360.98  4847.4 2361.48  4849.7 2363.65  4858.3 2364.87
  4878.9 2365.26  5598.0 2366.74  5756.4 2367.37  6583.2 2371.38  7589.7 2388.59
#Mann=14,-1,0
   597.3   0.045       0  1530.7   0.035       0  1678.6   0.045       0
  2714.4   0.035       0  3025.1    0.07       0  3197.6   0.045       0
  4038.3   0.035       0  4169.8   0.045       0  4536.3   0.035       0
  4613.5   0.045       0  4827.9   0.045       0  4847.4   0.045       0
  5598.0   0.035       0  5756.4   0.045       0
Bank Sta=4827.9,4847.4
Exp/Cntr=0.3,0.1

Type RM Length L Ch R = 1,15460,444,444,444
BEGIN DESCRIPTION:
Buffalo Creek Trib 09 27.0
END DESCRIPTION:
XS GIS Cut Line= 3
      1293605.00      6930088.00      1291205.00      6927688.00
      1289555.02      6925888.03
#Sta/Elev= 30
  1610.9 2383.38  1783.9 2381.73  1903.0 2380.28  2219.0 2375.76  2247.3 2377.16
  2473.6 2372.47  2991.6 2371.32  3067.5 2372.64  3095.8 2370.42  3179.1 2370.35
  3606.5 2369.64  3972.4 2368.71  3995.6 2367.94  4085.8 2367.49  4114.8 2369.57
  4142.3 2366.35  4257.2 2367.98  4411.0 2364.65  4982.7 2361.69  4991.6 2359.19
  4992.1 2358.69  5011.4 2359.19  5033.1 2361.95  5072.8 2360.78  5132.3 2363.24
  5819.0 2364.17  6082.0 2366.90  6197.4 2366.61  6682.5 2371.26  7446.8 2387.44
#Mann=16,-1,0
  1610.9   0.045       0  1783.9   0.035       0  1903.0   0.045       0
  2991.6   0.035       0  3179.1    0.07       0  3606.5   0.045       0
  3972.4   0.035       0  3995.6   0.045       0  4114.8   0.035       0
  4257.2   0.045       0  4982.7    0.07       0  4991.6    0.07       0
  5011.4    0.07       0  5072.8   0.045       0  6082.0   0.035       0
  6197.4   0.045       0
Bank Sta=4991.6,5011.4
Exp/Cntr=0.3,0.1

Type RM Length L Ch R = 1,15016,539,539,539
BEGIN DESCRIPTION:
Buffalo Creek Trib 09 26.0
END DESCRIPTION:
XS GIS Cut Line= 3
      1293855.03      6929738.03      1291455.00      6927338.00
      1289654.99      6925687.99
#Sta/Elev= 30
  1605.8 2382.89  1691.4 2382.07  1816.6 2380.33  2454.4 2372.43  3176.4 2371.15
  3260.5 2372.45  3288.8 2370.17  3345.3 2370.29  3373.6 2372.69  3401.9 2369.29
  3441.3 2371.48  3503.6 2370.41  3515.0 2372.08  3590.4 2370.35  4264.6 2364.95
  4307.0 2362.34  4462.6 2360.07  4773.7 2361.59  5000.5 2359.98  5025.5 2357.82
  5026.0 2357.32  5045.3 2357.82  5056.4 2360.22  5131.3 2359.97  6075.7 2366.09
  6139.9 2364.78  6271.6 2366.73  6557.2 2369.70  6918.0 2379.48  7441.8 2388.99
#Mann=13,-1,0
  1605.8   0.045       0  1691.4   0.035       0  1816.6   0.045       0
  3176.4   0.035       0  3441.3   0.045       0  3503.6    0.07       0
  3590.4   0.045       0  5000.5    0.07       0  5025.5   0.045       0
  5045.3    0.07       0  5131.3   0.045       0  6139.9   0.035       0
  6271.6   0.045       0
Bank Sta=5025.5,5045.3
Exp/Cntr=0.3,0.1

Type RM Length L Ch R = 1,14477,539,539,539
BEGIN DESCRIPTION:
Buffalo Creek Trib 09 25.0
END DESCRIPTION:
XS GIS Cut Line= 3
      1294255.00      6929438.00      1291855.00      6927038.00
      1290330.02      6925713.01
#Sta/Elev= 30
  1611.0 2385.76  1667.6 2386.35  2003.5 2380.98  2005.2 2380.92  2473.7 2375.69
  2502.0 2377.07  2597.4 2374.72  2685.8 2375.85  2724.6 2374.31  2813.1 2375.44
  2897.9 2372.40  3110.1 2370.97  3887.9 2370.64  4368.7 2364.78  4552.6 2364.75
  4807.8 2360.09  4877.8 2359.38  4934.4 2356.11  4991.0 2356.23  5001.9 2354.33
  5002.4 2353.83  5022.5 2354.33  5026.5 2356.13  5127.3 2358.89  5255.3 2360.26
  5614.5 2363.44  6203.0 2364.42  6564.8 2368.79  6694.1 2372.26  7025.3 2379.19
#Mann=12,-1,0
  1611.0   0.045       0  2003.5   0.035       0  2005.2   0.045       0
  2597.4   0.035       0  2724.6   0.045       0  4807.8    0.07       0
  5001.9    0.07       0  5022.5    0.07       0  5127.3   0.035       0
  5255.3   0.045       0  6564.8   0.035       0  6694.1   0.045       0
Bank Sta=5001.9,5022.5
Exp/Cntr=0.3,0.1

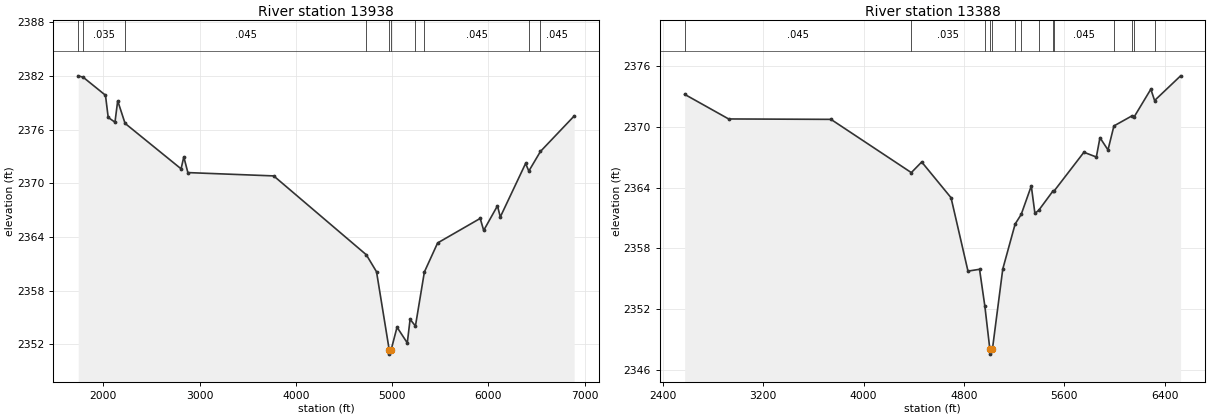
Type RM Length L Ch R = 1,13938,550,550,550
BEGIN DESCRIPTION:
Buffalo Creek Trib 09 24.0
END DESCRIPTION:
XS GIS Cut Line= 3
      1294154.98      6928987.97      1291955.00      6926588.00
      1290429.30      6925459.21
#Sta/Elev= 30
  1738.8 2382.01  1790.7 2381.85  2022.1 2379.84  2050.5 2377.36  2120.8 2376.83
  2149.1 2379.22  2225.6 2376.70  2807.7 2371.62  2836.0 2372.95  2878.3 2371.20
  3770.2 2370.83  4732.6 2362.02  4838.8 2360.12  4970.3 2351.42  4970.8 2350.92
  4991.0 2351.42  5051.9 2353.93  5158.4 2352.17  5187.6 2354.81  5243.1 2354.06
  5336.1 2360.10  5473.6 2363.34  5916.1 2366.08  5952.4 2364.74  6095.6 2367.49
  6124.9 2366.24  6387.8 2372.22  6421.4 2371.37  6542.0 2373.56  6892.4 2377.52
#Mann=10,-1,0
  1738.8   0.045       0  1790.7   0.035       0  2225.6   0.045       0
  4732.6    0.07       0  4970.3    0.07       0  4991.0    0.07       0
  5243.1   0.035       0  5336.1   0.045       0  6421.4   0.035       0
  6542.0   0.045       0
Bank Sta=4970.3,4991
Exp/Cntr=0.3,0.1

Type RM Length L Ch R = 1,13388,549,549,549
BEGIN DESCRIPTION:
Buffalo Creek Trib 09 23.0
END DESCRIPTION:
XS GIS Cut Line= 3
      1293680.38      6928026.44      1292105.00      6926188.00
      1290909.79      6925229.75
#Sta/Elev= 30
  2574.0 2373.21  2924.5 2370.78  3740.0 2370.74  4380.5 2365.48  4463.3 2366.53
  4697.1 2363.00  4832.1 2355.75  4924.3 2355.93  4966.6 2352.29  5006.3 2348.05
  5006.8 2347.55  5027.1 2348.05  5109.5 2355.96  5208.0 2360.40  5256.3 2361.35
  5336.8 2364.16  5365.6 2361.46  5395.7 2361.75  5508.8 2363.65  5519.7 2363.68
  5756.1 2367.49  5855.3 2367.02  5884.1 2368.93  5948.1 2367.72  5995.3 2370.09
  6139.9 2371.09  6157.4 2371.00  6289.6 2373.72  6319.6 2372.60  6527.0 2375.04
#Mann=14,-1,0
  2574.0   0.045       0  4380.5   0.035       0  4966.6    0.07       0
  5006.3    0.07       0  5027.1    0.07       0  5208.0   0.035       0
  5256.3    0.07       0  5395.7   0.045       0  5508.8    0.07       0
  5519.7   0.045       0  5995.3   0.035       0  6139.9   0.045       0
  6157.4   0.035       0  6319.6   0.045       0
Bank Sta=5006.3,5027.1
Exp/Cntr=0.3,0.1