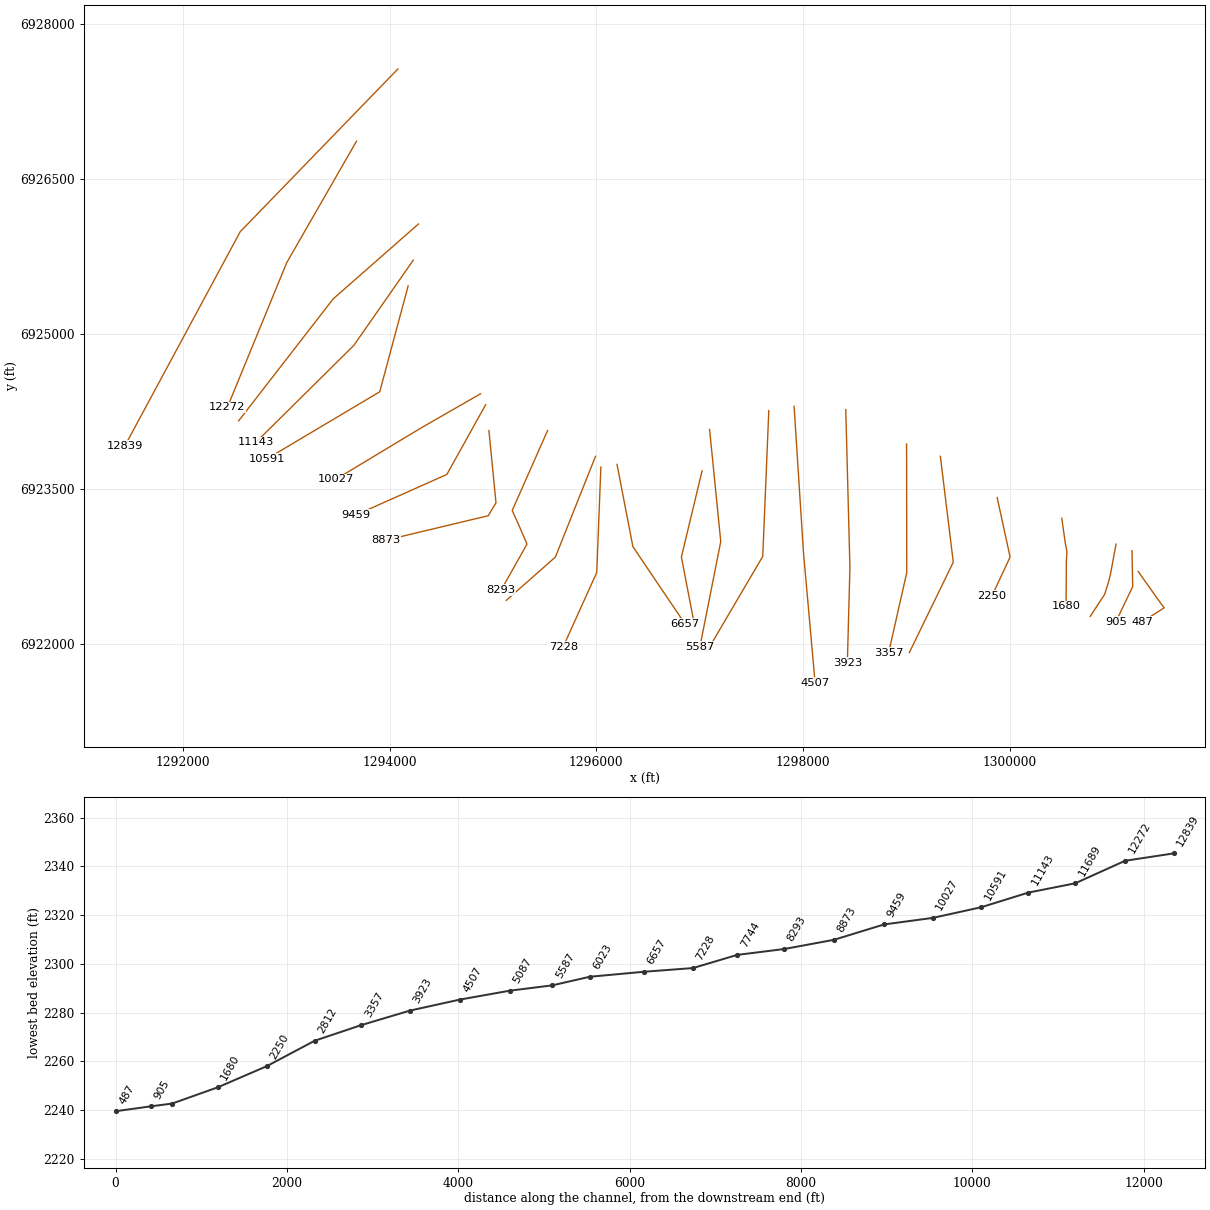
HEC-RAS study Buffalo Creek Trib 09.prj: Buffalo Creek Trib 09 Base Level Engineering

--- Buffalo Creek Trib 09.g01 (geometry) --- (continued)

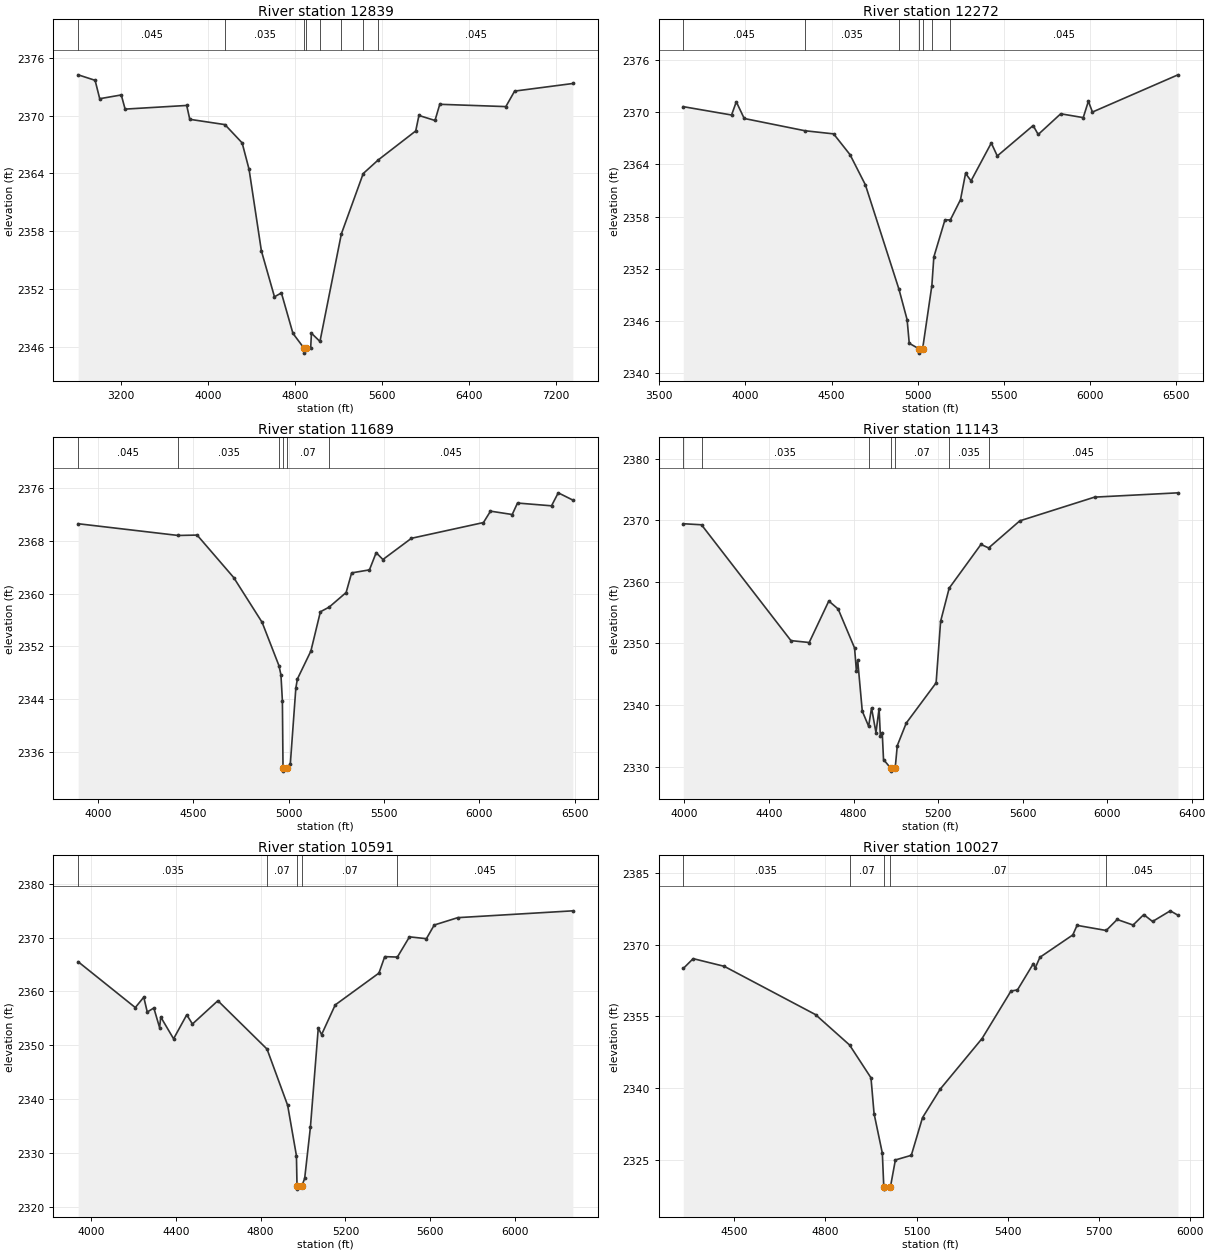
Type RM Length L Ch R = 1,12839,567,567,567
BEGIN DESCRIPTION:
Buffalo Creek Trib 09 22.0
END DESCRIPTION:
XS GIS Cut Line= 3
      1294080.00      6927563.00      1292555.00      6925988.00
      1291440.39      6923917.01
#Sta/Elev= 30
  2807.7 2374.23  2963.3 2373.66  3005.8 2371.75  3203.8 2372.14  3239.1 2370.67
  3804.8 2371.05  3833.1 2369.61  4156.1 2369.06  4314.1 2367.16  4377.6 2364.42
  4490.8 2355.95  4611.0 2351.18  4674.7 2351.58  4780.7 2347.38  4883.2 2345.83
  4883.7 2345.33  4904.6 2345.83  4943.5 2345.84  4950.5 2347.40  5028.9 2346.54
  5225.4 2357.71  5426.3 2363.98  5564.0 2365.39  5908.5 2368.40  5938.0 2370.01
  6085.6 2369.49  6129.4 2371.17  6736.3 2370.93  6817.0 2372.54  7351.9 2373.33
#Mann=8,-1,0
  2807.7   0.045       0  4156.1   0.035       0  4883.2   0.035       0
  4904.6   0.035       0  5028.9    0.07       0  5225.4   0.035       0
  5426.3    0.07       0  5564.0   0.045       0
Bank Sta=4883.2,4904.6
Exp/Cntr=0.3,0.1

Type RM Length L Ch R = 1,12272,583,583,583
BEGIN DESCRIPTION:
Buffalo Creek Trib 09 21.0
END DESCRIPTION:
XS GIS Cut Line= 3
      1293680.32      6926864.91      1293005.00      6925688.00
      1292430.36      6924286.86
#Sta/Elev= 30
  3638.8 2370.65  3919.2 2369.69  3946.6 2371.21  3992.6 2369.29  4345.2 2367.88
  4511.5 2367.52  4606.7 2365.13  4695.9 2361.66  4891.1 2349.63  4938.1 2346.15
  4950.4 2343.44  5006.5 2342.81  5007.0 2342.31  5028.1 2342.81  5081.7 2350.08
  5093.2 2353.37  5157.8 2357.64  5188.7 2357.62  5247.9 2359.95  5277.3 2362.98
  5309.1 2362.12  5426.6 2366.47  5461.4 2364.98  5669.5 2368.48  5698.9 2367.45
  5829.6 2369.83  5960.3 2369.39  5990.1 2371.27  6013.7 2370.03  6510.1 2374.31
#Mann=7,-1,0
  3638.8   0.045       0  4345.2   0.035       0  4891.1    0.07       0
  5006.5    0.07       0  5028.1    0.07       0  5081.7   0.035       0
  5188.7   0.045       0
Bank Sta=5006.5,5028.1
Exp/Cntr=0.3,0.1

Type RM Length L Ch R = 1,11689,546,546,546
BEGIN DESCRIPTION:
Buffalo Creek Trib 09 20.0
END DESCRIPTION:
XS GIS Cut Line= 3
      1294279.98      6926062.98      1293455.00      6925338.00
      1292539.86      6924156.79
#Sta/Elev= 30
  3897.0 2370.60  4421.4 2368.82  4520.4 2368.88  4712.0 2362.44  4861.0 2355.64
  4949.2 2349.07  4959.7 2347.67  4967.3 2343.75  4970.6 2333.56  4971.1 2333.06
  4992.3 2333.56  5008.8 2334.11  5037.8 2345.66  5045.9 2347.04  5116.6 2351.28
  5166.4 2357.24  5212.5 2357.95  5301.3 2360.16  5330.2 2363.14  5423.5 2363.60
  5458.8 2366.21  5494.1 2365.17  5643.5 2368.39  6021.0 2370.78  6057.9 2372.51
  6171.7 2372.00  6199.4 2373.74  6377.7 2373.32  6413.0 2375.29  6489.5 2374.19
#Mann=6,-1,0
  3897.0   0.045       0  4421.4   0.035       0  4949.2    0.07       0
  4970.6    0.07       0  4992.3    0.07       0  5212.5   0.045       0
Bank Sta=4970.6,4992.3
Exp/Cntr=0.3,0.1

Type RM Length L Ch R = 1,11143,552,552,552
BEGIN DESCRIPTION:
Buffalo Creek Trib 09 19.0
END DESCRIPTION:
XS GIS Cut Line= 3
      1294229.99      6925712.99      1293655.00      6924888.00
      1292706.36      6923948.25
#Sta/Elev= 30
  3994.4 2369.44  4080.7 2369.27  4503.9 2350.46  4590.3 2350.15  4683.1 2356.89
  4727.3 2355.59  4805.0 2349.26  4813.7 2345.48  4819.8 2347.26  4841.5 2339.00
  4871.5 2336.55  4885.3 2339.52  4906.2 2335.53  4921.0 2339.41  4927.1 2335.00
  4935.9 2335.53  4942.0 2331.14  4975.6 2329.76  4976.1 2329.26  4997.3 2329.76
  5007.1 2333.40  5049.5 2337.06  5190.9 2343.60  5212.1 2353.58  5252.6 2358.97
  5403.1 2366.08  5439.4 2365.51  5586.9 2369.91  5940.5 2373.76  6335.3 2374.46
#Mann=7,-1,0
  3994.4    0.07       0  4080.7   0.035       0  4871.5    0.07       0
  4975.6    0.07       0  4997.3    0.07       0  5252.6   0.035       0
  5439.4   0.045       0
Bank Sta=4975.6,4997.3
Exp/Cntr=0.3,0.1

Type RM Length L Ch R = 1,10591,564,564,564
BEGIN DESCRIPTION:
Buffalo Creek Trib 09 18.0
END DESCRIPTION:
XS GIS Cut Line= 3
      1294180.01      6925463.03      1293905.00      6924438.00
      1292810.56      6923786.82
#Sta/Elev= 30
  3938.7 2365.53  4208.4 2357.01  4248.4 2358.94  4264.9 2356.18  4295.9 2356.93
  4323.2 2353.26  4328.4 2355.26  4389.1 2351.20  4451.2 2355.66  4478.1 2353.95
  4598.1 2358.28  4830.1 2349.29  4927.5 2338.82  4968.9 2329.45  4971.7 2323.74
  4972.2 2323.24  4993.5 2323.74  5007.8 2325.23  5035.0 2334.81  5072.0 2353.21
  5087.6 2351.98  5151.9 2357.50  5358.3 2363.42  5385.6 2366.48  5445.3 2366.40
  5502.4 2370.16  5582.3 2369.82  5619.3 2372.36  5730.3 2373.73  6273.5 2375.00
#Mann=5,-1,0
  3938.7   0.035       0  4830.1    0.07       0  4971.7    0.07       0
  4993.5    0.07       0  5445.3   0.045       0
Bank Sta=4971.7,4993.5
Exp/Cntr=0.3,0.1

Type RM Length L Ch R = 1,10027,568,568,568
BEGIN DESCRIPTION:
Buffalo Creek Trib 09 17.0
END DESCRIPTION:
XS GIS Cut Line= 3
      1294880.03      6924418.22      1294305.00      6924088.00
      1293478.60      6923589.73
#Sta/Elev= 30
  4332.3 2365.02  4364.9 2367.08  4467.0 2365.48  4767.5 2355.38  4879.5 2349.03
  4950.1 2342.16  4960.2 2334.69  4987.5 2326.39  4992.2 2319.38  4992.7 2318.88
  5014.2 2319.38  5030.4 2324.98  5082.8 2325.95  5119.7 2333.83  5177.9 2339.79
  5315.7 2350.38  5410.9 2360.31  5432.2 2360.54  5484.6 2366.05  5490.5 2365.11
  5506.0 2367.36  5614.3 2372.04  5628.3 2374.04  5724.2 2372.97  5760.3 2375.27
  5812.7 2374.11  5847.8 2376.29  5876.8 2374.85  5935.1 2377.08  5960.4 2376.16
#Mann=5,-1,0
  4332.3   0.035       0  4879.5    0.07       0  4992.2    0.07       0
  5014.2    0.07       0  5724.2   0.045       0
Bank Sta=4992.2,5014.2
Exp/Cntr=0.3,0.1

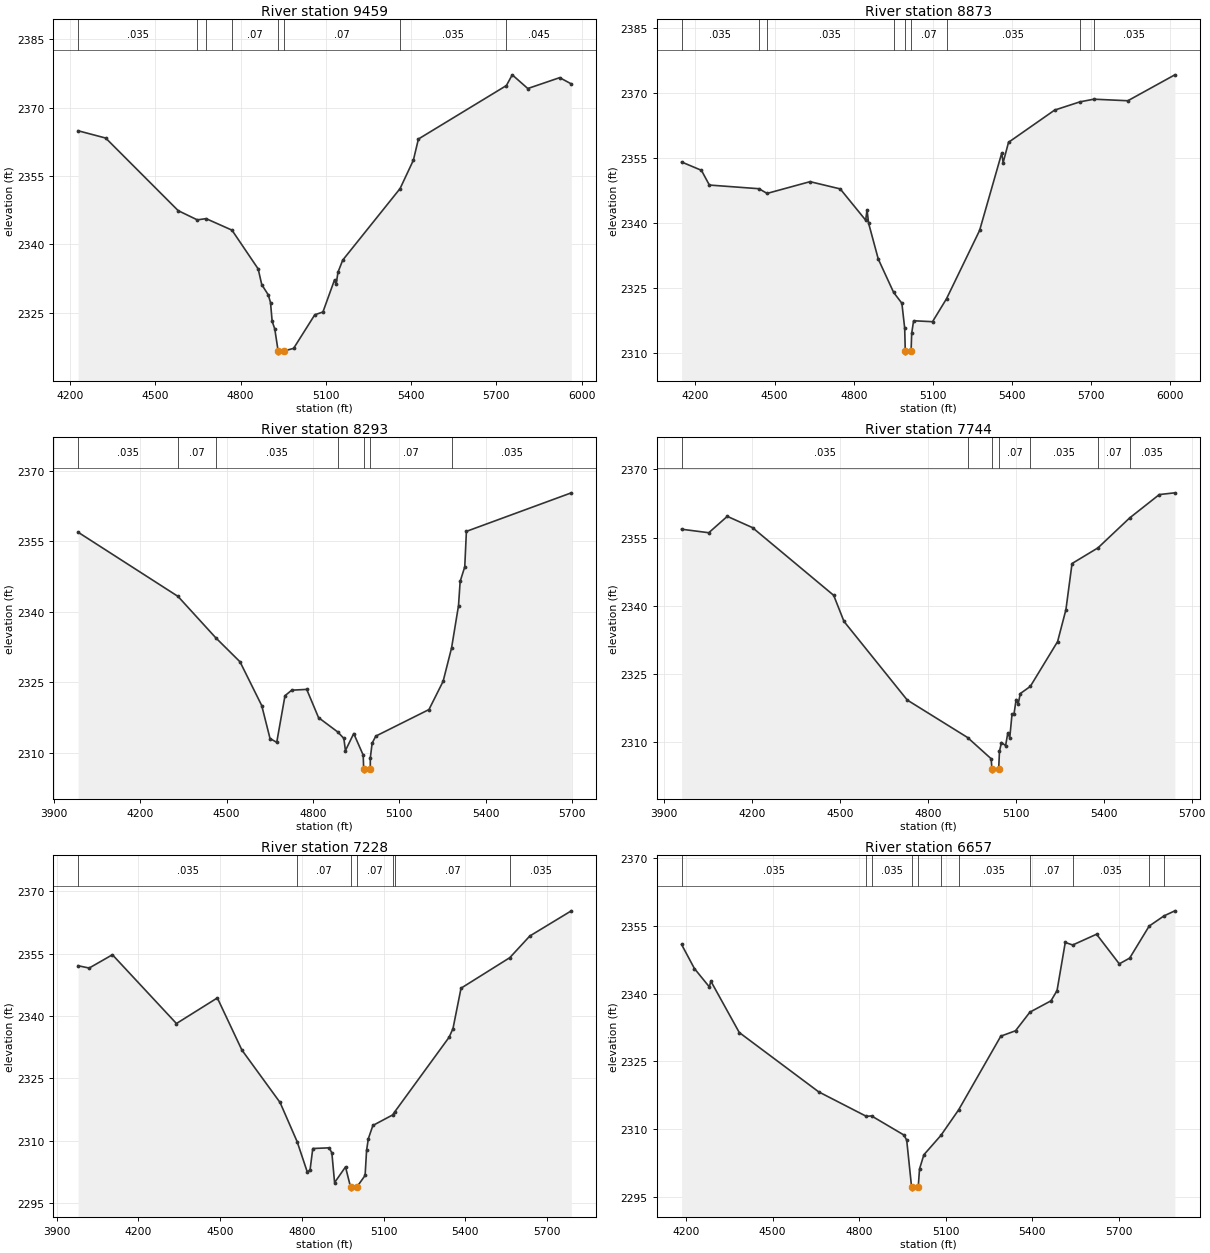
Type RM Length L Ch R = 1,9459,586,586,586
BEGIN DESCRIPTION:
Buffalo Creek Trib 09 16.0
END DESCRIPTION:
XS GIS Cut Line= 3
      1294929.98      6924312.97      1294555.00      6923638.00
      1293675.15      6923245.16
#Sta/Elev= 30
  4227.9 2364.91  4325.1 2363.31  4580.2 2347.41  4647.4 2345.39  4678.3 2345.66
  4769.4 2343.14  4861.6 2334.65  4874.2 2331.21  4897.1 2328.97  4905.1 2327.27
  4910.8 2323.18  4920.0 2321.50  4931.8 2316.70  4932.3 2316.20  4953.9 2316.70
  4986.3 2317.24  5060.8 2324.60  5089.5 2325.21  5130.5 2332.28  5135.9 2331.24
  5142.4 2333.91  5159.1 2336.57  5361.0 2352.25  5407.7 2358.45  5425.5 2363.10
  5735.1 2374.81  5755.7 2377.16  5810.4 2374.16  5922.6 2376.54  5963.6 2375.17
#Mann=8,-1,0
  4227.9   0.035       0  4647.4    0.07       0  4678.3   0.035       0
  4769.4    0.07       0  4931.8    0.07       0  4953.9    0.07       0
  5361.0   0.035       0  5735.1   0.045       0
Bank Sta=4931.8,4953.9
Exp/Cntr=0.3,0.1

Type RM Length L Ch R = 1,8873,580,580,580
BEGIN DESCRIPTION:
Buffalo Creek Trib 09 15.0
END DESCRIPTION:
XS GIS Cut Line= 4
      1294961.60      6924062.84      1295030.00      6923363.00
      1294955.00      6923238.00      1293961.57      6923000.35
#Sta/Elev= 30
  4147.4 2353.99  4222.6 2352.07  4252.7 2348.67  4440.9 2347.82  4471.6 2346.74
  4634.5 2349.45  4748.9 2347.78  4845.5 2340.56  4850.6 2342.97  4856.4 2339.90
  4893.3 2331.58  4951.6 2323.88  4982.7 2321.40  4993.4 2315.64  4995.6 2310.39
  4996.1 2309.89  5017.7 2310.39  5019.9 2314.44  5027.2 2317.36  5098.9 2317.14
  5152.0 2322.44  5277.4 2338.19  5361.5 2356.07  5366.7 2353.84  5387.1 2358.53
  5561.9 2365.96  5657.7 2367.86  5710.8 2368.48  5839.6 2368.12  6017.8 2374.10
#Mann=9,-1,0
  4147.4   0.035       0  4440.9    0.07       0  4471.6   0.035       0
  4951.6    0.07       0  4995.6    0.07       0  5017.7    0.07       0
  5152.0   0.035       0  5657.7    0.07       0  5710.8   0.035       0
Bank Sta=4995.6,5017.7
Exp/Cntr=0.3,0.1

Type RM Length L Ch R = 1,8293,549,549,549
BEGIN DESCRIPTION:
Buffalo Creek Trib 09 14.0
END DESCRIPTION:
XS GIS Cut Line= 5
      1295529.30      6924062.85      1295186.93      6923288.58
      1295255.00      6923138.00      1295330.00      6922963.00
      1295079.98      6922518.17
#Sta/Elev= 30
  3984.4 2356.95  4331.2 2343.30  4462.4 2334.49  4546.6 2329.38  4622.0 2320.07
  4650.8 2313.06  4674.1 2312.24  4702.8 2322.17  4726.1 2323.34  4778.2 2323.51
  4819.3 2317.50  4885.3 2314.48  4907.1 2313.09  4912.6 2310.49  4941.4 2314.12
  4974.3 2309.53  4975.9 2306.62  4976.4 2306.12  4998.9 2306.62  4999.0 2308.92
  5005.3 2312.06  5018.0 2313.57  5202.6 2319.22  5251.7 2325.22  5281.1 2332.33
  5305.2 2341.33  5310.9 2346.48  5326.9 2349.59  5332.6 2357.13  5696.9 2365.33
#Mann=7,-1,0
  3984.4   0.035       0  4331.2    0.07       0  4462.4   0.035       0
  4885.3    0.07       0  4975.9    0.07       0  4998.9    0.07       0
  5281.1   0.035       0
Bank Sta=4975.9,4998.9
Exp/Cntr=0.3,0.1

Type RM Length L Ch R = 1,7744,516,516,516
BEGIN DESCRIPTION:
Buffalo Creek Trib 09 13.0
END DESCRIPTION:
XS GIS Cut Line= 3
      1295992.84      6923812.85      1295605.00      6922838.00
      1295129.99      6922418.20
#Sta/Elev= 30
  3959.6 2356.87  4052.4 2356.10  4115.5 2359.70  4201.6 2357.22  4478.6 2342.34
  4513.7 2336.61  4729.5 2319.33  4935.4 2311.09  5015.9 2306.42  5018.6 2304.20
  5019.1 2303.70  5041.6 2304.20  5044.3 2308.05  5051.0 2309.99  5065.2 2309.31
  5072.8 2312.11  5079.4 2311.03  5087.0 2316.15  5093.7 2316.18  5101.2 2319.44
  5107.9 2318.41  5115.4 2320.75  5149.5 2322.32  5242.6 2332.17  5271.0 2339.18
  5291.9 2349.33  5380.5 2352.78  5488.5 2359.35  5589.7 2364.49  5642.7 2364.87
#Mann=7,-1,0
  3959.6   0.035       0  4935.4    0.07       0  5018.6    0.07       0
  5041.6    0.07       0  5149.5   0.035       0  5380.5    0.07       0
  5488.5   0.035       0
Bank Sta=5018.6,5041.6
Exp/Cntr=0.3,0.1

Type RM Length L Ch R = 1,7228,571,571,571
BEGIN DESCRIPTION:
Buffalo Creek Trib 09 12.0
END DESCRIPTION:
XS GIS Cut Line= 3
      1296044.93      6923708.71      1296005.00      6922688.00
      1295680.34      6921969.10
#Sta/Elev= 30
  3978.5 2352.07  4019.2 2351.51  4104.5 2354.71  4339.5 2338.16  4489.6 2344.32
  4579.7 2331.78  4719.8 2319.16  4782.5 2309.73  4819.8 2302.42  4829.9 2302.94
  4839.9 2308.08  4899.9 2308.25  4909.9 2307.04  4919.9 2299.88  4960.0 2303.66
  4978.5 2298.81  4979.0 2298.31  5001.5 2298.81  5031.9 2301.60  5037.4 2307.68
  5043.9 2310.47  5060.5 2313.63  5132.6 2316.15  5141.5 2316.98  5340.1 2334.85
  5354.4 2336.93  5384.0 2346.66  5563.0 2354.01  5636.4 2359.22  5788.8 2365.28
#Mann=7,-1,0
  3978.5   0.035       0  4782.5    0.07       0  4978.5    0.07       0
  5001.5    0.07       0  5132.6   0.035       0  5141.5    0.07       0
  5563.0   0.035       0
Bank Sta=4978.5,5001.5
Exp/Cntr=0.3,0.1

Type RM Length L Ch R = 1,6657,634,634,634
BEGIN DESCRIPTION:
Buffalo Creek Trib 09 11.0
END DESCRIPTION:
XS GIS Cut Line= 3
      1296201.18      6923734.71      1296355.00      6922938.00
      1296857.45      6922193.03
#Sta/Elev= 30
  4184.7 2350.86  4229.2 2345.54  4281.0 2341.48  4286.1 2342.76  4384.7 2331.40
  4660.0 2318.29  4825.2 2312.88  4843.3 2312.97  4955.4 2308.75  4965.1 2307.62
  4982.0 2297.29  4982.5 2296.79  5005.1 2297.29  5009.6 2301.25  5024.6 2304.38
  5083.6 2308.66  5145.2 2314.32  5291.4 2330.60  5342.4 2331.79  5392.3 2335.91
  5465.3 2338.41  5486.3 2340.67  5514.8 2351.31  5540.7 2350.75  5623.3 2353.13
  5702.1 2346.58  5738.1 2347.85  5805.7 2354.93  5857.1 2357.18  5894.7 2358.30
#Mann=11,-1,0
  4184.7   0.035       0  4825.2    0.07       0  4843.3   0.035       0
  4982.0   0.035       0  5005.1   0.035       0  5083.6    0.07       0
  5145.2   0.035       0  5392.3    0.07       0  5540.7   0.035       0
  5805.7    0.07       0  5857.1   0.035       0
Bank Sta=4982,5005.1
Exp/Cntr=0.3,0.1

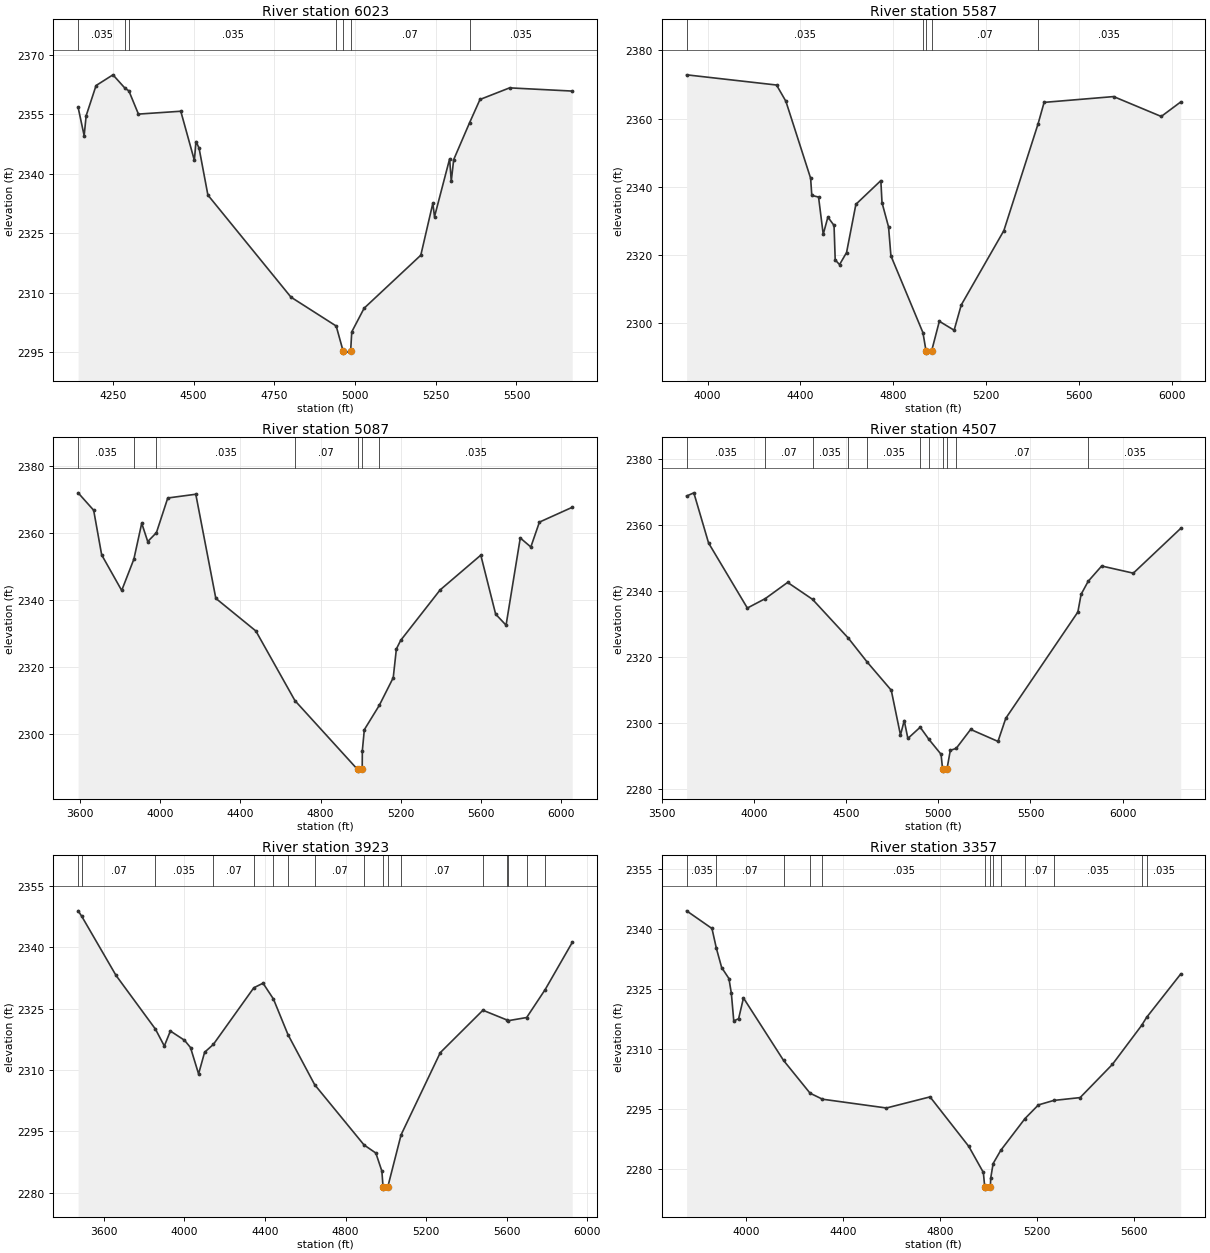
Type RM Length L Ch R = 1,6023,436,436,436
BEGIN DESCRIPTION:
Buffalo Creek Trib 09 10.0
END DESCRIPTION:
XS GIS Cut Line= 3
      1297024.10      6923672.24      1296824.21      6922838.06
      1296951.18      6922177.45
#Sta/Elev= 30
  4142.2 2356.77  4160.9 2349.62  4167.1 2354.66  4197.8 2362.28  4250.1 2364.98
  4288.2 2361.53  4299.3 2360.95  4329.0 2355.07  4460.2 2355.79  4502.2 2343.42
  4507.4 2348.14  4516.8 2346.49  4544.2 2334.63  4801.5 2308.87  4941.6 2301.58
  4963.1 2295.24  4963.6 2294.74  4986.3 2295.24  4989.8 2300.11  5028.1 2306.08
  5203.7 2319.46  5241.0 2332.59  5246.1 2329.16  5292.9 2343.76  5298.0 2338.13
  5305.5 2343.57  5354.5 2352.85  5387.0 2358.76  5478.7 2361.69  5672.7 2360.88
#Mann=7,-1,0
  4142.2   0.035       0  4288.2    0.07       0  4299.3   0.035       0
  4941.6    0.07       0  4963.1    0.07       0  4986.3    0.07       0
  5354.5   0.035       0
Bank Sta=4963.1,4986.3
Exp/Cntr=0.3,0.1

Type RM Length L Ch R = 1,5587,500,500,500
BEGIN DESCRIPTION:
Buffalo Creek Trib 09 9.0
END DESCRIPTION:
XS GIS Cut Line= 3
      1297097.01      6924073.27      1297205.00      6922988.00
      1297003.65      6921971.07
#Sta/Elev= 30
  3909.7 2372.84  4296.9 2369.85  4337.1 2365.09  4443.7 2342.50  4448.7 2337.47
  4477.8 2336.99  4497.9 2326.07  4518.0 2331.12  4544.5 2328.66  4549.5 2318.56
  4568.2 2317.18  4598.4 2320.73  4638.6 2334.87  4746.0 2341.82  4751.0 2335.36
  4779.2 2328.23  4789.3 2319.77  4927.3 2297.21  4940.9 2291.72  4941.4 2291.22
  4964.1 2291.72  4997.8 2300.56  5061.5 2297.94  5092.1 2305.34  5275.6 2327.15
  5422.8 2358.44  5448.9 2364.76  5748.2 2366.46  5953.2 2360.63  6037.0 2364.88
#Mann=5,-1,0
  3909.7   0.035       0  4927.3    0.07       0  4940.9    0.07       0
  4964.1    0.07       0  5422.8   0.035       0
Bank Sta=4940.9,4964.1
Exp/Cntr=0.3,0.1

Type RM Length L Ch R = 1,5087,580,580,580
BEGIN DESCRIPTION:
Buffalo Creek Trib 09 8.0
END DESCRIPTION:
XS GIS Cut Line= 3
      1297669.93      6924255.59      1297611.41      6922844.14
      1297076.27      6921932.80
#Sta/Elev= 30
  3588.6 2371.89  3666.3 2366.70  3706.3 2353.41  3806.4 2342.81  3867.1 2352.11
  3906.5 2362.84  3936.5 2357.38  3979.9 2360.02  4036.6 2370.35  4176.7 2371.47
  4276.8 2340.46  4476.9 2330.75  4672.2 2310.01  4985.2 2289.51  4985.7 2289.01
  5008.4 2289.51  5009.1 2295.11  5019.0 2301.35  5093.7 2308.59  5163.5 2316.83
  5179.2 2325.39  5200.6 2327.94  5397.9 2342.98  5601.1 2353.33  5675.3 2335.77
  5727.4 2332.47  5798.4 2358.45  5851.2 2355.76  5894.1 2363.17  6058.1 2367.58
#Mann=7,-1,0
  3588.6   0.035       0  3867.1    0.07       0  3979.9   0.035       0
  4672.2    0.07       0  4985.2    0.07       0  5008.4    0.07       0
  5093.7   0.035       0
Bank Sta=4985.2,5008.4
Exp/Cntr=0.3,0.1

Type RM Length L Ch R = 1,4507,584,584,584
BEGIN DESCRIPTION:
Buffalo Creek Trib 09 7.0
END DESCRIPTION:
XS GIS Cut Line= 3
      1297914.72      6924297.20      1298005.00      6922888.00
      1298117.72      6921621.60
#Sta/Elev= 30
  3632.3 2368.69  3671.6 2369.66  3751.7 2354.46  3962.2 2334.77  4059.8 2337.63
  4180.9 2342.53  4316.1 2337.41  4510.4 2325.67  4613.3 2318.39  4743.8 2309.88
  4793.9 2296.31  4814.3 2300.70  4834.0 2295.27  4900.9 2298.68  4948.7 2294.97
  5014.3 2290.48  5022.7 2285.88  5023.2 2285.38  5046.0 2285.88  5064.5 2291.68
  5096.4 2292.26  5174.9 2298.01  5323.4 2294.38  5365.7 2301.38  5757.2 2333.56
  5774.9 2338.93  5813.2 2342.86  5886.5 2347.50  6058.4 2345.33  6315.8 2358.89
#Mann=11,-1,0
  3632.3   0.035       0  4059.8    0.07       0  4316.1   0.035       0
  4510.4    0.07       0  4613.3   0.035       0  4900.9    0.07       0
  4948.7   0.035       0  5022.7   0.035       0  5046.0   0.035       0
  5096.4    0.07       0  5813.2   0.035       0
Bank Sta=5022.7,5046
Exp/Cntr=0.3,0.1

Type RM Length L Ch R = 1,3923,566,566,566
BEGIN DESCRIPTION:
Buffalo Creek Trib 09 6.0
END DESCRIPTION:
XS GIS Cut Line= 3
      1298414.72      6924265.95      1298455.00      6922738.00
      1298430.00      6921813.02
#Sta/Elev= 30
  3471.9 2348.88  3489.1 2347.61  3659.9 2333.11  3855.9 2319.96  3900.0 2315.83
  3930.0 2319.50  4000.0 2317.25  4030.0 2315.46  4070.1 2309.01  4100.1 2314.31
  4143.5 2316.23  4344.4 2330.07  4390.2 2331.19  4441.9 2327.32  4514.1 2318.62
  4646.6 2306.38  4891.8 2291.65  4950.4 2289.67  4980.4 2285.25  4986.2 2281.35
  4986.7 2280.85  5009.5 2281.35  5075.7 2294.12  5270.5 2314.22  5482.1 2324.58
  5599.4 2322.24  5606.3 2322.01  5699.4 2322.80  5791.4 2329.64  5925.7 2341.15
#Mann=17,-1,0
  3471.9   0.035       0  3489.1    0.07       0  3855.9   0.035       0
  4143.5    0.07       0  4344.4   0.035       0  4441.9    0.07       0
  4514.1   0.035       0  4646.6    0.07       0  4891.8   0.035       0
  4986.2   0.035       0  5009.5   0.035       0  5075.7    0.07       0
  5482.1   0.035       0  5599.4    0.07       0  5606.3   0.035       0
  5699.4    0.07       0  5791.4   0.035       0
Bank Sta=4986.2,5009.5
Exp/Cntr=0.3,0.1

Type RM Length L Ch R = 1,3357,545,545,545
BEGIN DESCRIPTION:
Buffalo Creek Trib 09 5.0
END DESCRIPTION:
XS GIS Cut Line= 3
      1299003.26      6923932.69      1299005.00      6922688.00
      1298830.00      6921913.00
#Sta/Elev= 30
  3755.4 2344.55  3860.1 2340.13  3878.4 2335.14  3900.1 2330.36  3930.1 2327.61
  3940.1 2323.91  3950.1 2317.00  3970.1 2317.56  3990.1 2322.75  4155.4 2307.13
  4265.0 2298.92  4316.1 2297.42  4580.1 2295.22  4760.1 2298.00  4920.1 2285.60
  4980.1 2279.09  4985.9 2275.42  4986.4 2274.92  5009.2 2275.42  5010.3 2277.59
  5020.4 2281.32  5052.0 2284.63  5152.2 2292.59  5207.3 2295.99  5270.6 2297.11
  5379.4 2297.82  5512.7 2306.13  5633.5 2315.90  5653.6 2317.87  5794.6 2328.74
#Mann=13,-1,0
  3755.4   0.035       0  3878.4    0.07       0  4155.4   0.035       0
  4265.0    0.07       0  4316.1   0.035       0  4985.9   0.035       0
  5009.2   0.035       0  5020.4    0.07       0  5052.0   0.035       0
  5152.2    0.07       0  5270.6   0.035       0  5633.5    0.07       0
  5653.6   0.035       0
Bank Sta=4985.9,5009.2
Exp/Cntr=0.3,0.1

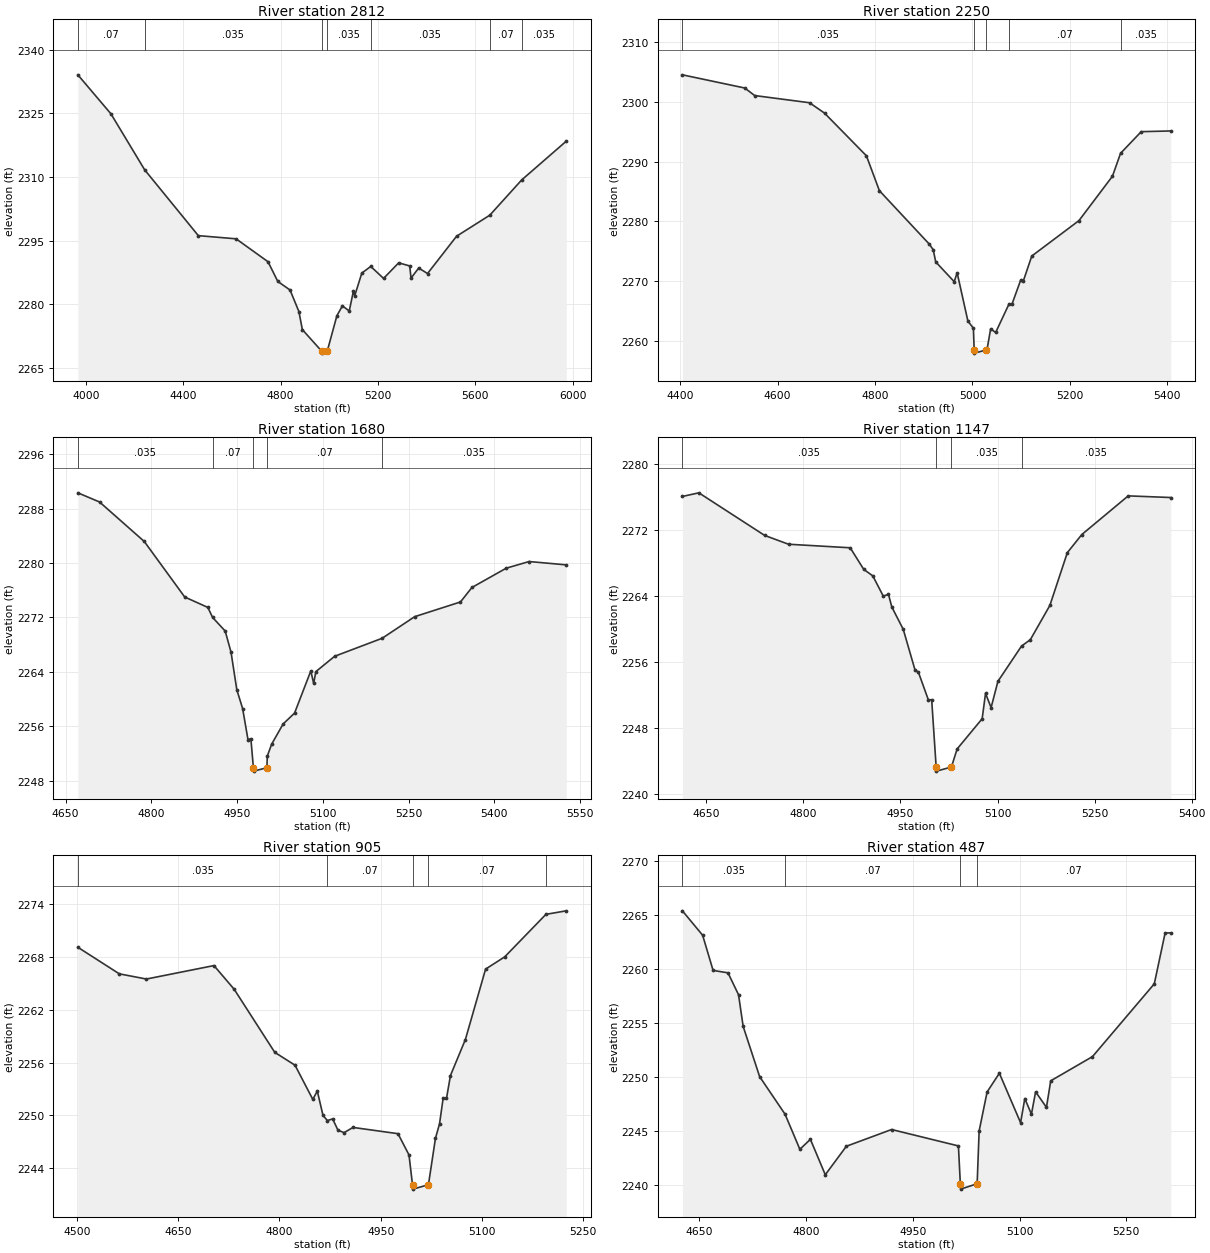
Type RM Length L Ch R = 1,2812,562,562,562
BEGIN DESCRIPTION:
Buffalo Creek Trib 09 4.0
END DESCRIPTION:
XS GIS Cut Line= 3
      1299330.00      6923813.04      1299455.00      6922788.00
      1299029.99      6921912.99
#Sta/Elev= 30
  3967.5 2334.09  4103.5 2324.89  4241.8 2311.71  4462.2 2296.19  4617.3 2295.44
  4748.3 2290.04  4788.6 2285.39  4838.9 2283.37  4875.2 2278.29  4889.3 2274.04
  4968.2 2269.00  4968.7 2268.50  4991.7 2269.00  5031.2 2277.32  5053.8 2279.64
  5081.9 2278.43  5098.9 2283.09  5104.4 2282.04  5133.5 2287.36  5170.2 2288.93
  5222.8 2286.11  5284.9 2289.78  5330.1 2289.05  5335.6 2286.18  5367.0 2288.55
  5403.3 2287.26  5522.6 2296.05  5659.0 2301.01  5789.8 2309.31  5972.9 2318.45
#Mann=7,-1,0
  3967.5    0.07       0  4241.8   0.035       0  4968.2    0.07       0
  4991.7   0.035       0  5170.2   0.035       0  5659.0    0.07       0
  5789.8   0.035       0
Bank Sta=4968.2,4991.7
Exp/Cntr=0.3,0.1

Type RM Length L Ch R = 1,2250,570,570,570
BEGIN DESCRIPTION:
Buffalo Creek Trib 09 3.0
END DESCRIPTION:
XS GIS Cut Line= 3
      1299880.01      6923412.96      1300005.00      6922838.00
      1299830.00      6922463.01
#Sta/Elev= 30
  4404.8 2304.48  4532.7 2302.28  4553.1 2301.02  4665.7 2299.82  4696.4 2298.09
  4782.4 2290.96  4809.0 2285.14  4911.3 2276.23  4919.5 2275.27  4924.6 2273.25
  4962.5 2269.95  4968.6 2271.42  4990.6 2263.38  5001.9 2262.17  5003.5 2258.52
  5004.0 2258.02  5027.0 2258.52  5030.2 2258.78  5037.3 2262.07  5047.6 2261.47
  5074.5 2266.14  5081.5 2266.29  5098.8 2270.18  5104.3 2270.05  5121.7 2274.23
  5218.6 2280.15  5287.2 2287.55  5303.9 2291.38  5346.3 2294.99  5407.0 2295.11
#Mann=5,-1,0
  4404.8   0.035       0  5003.5   0.035       0  5027.0   0.035       0
  5074.5    0.07       0  5303.9   0.035       0
Bank Sta=5003.5,5027
Exp/Cntr=0.3,0.1

Type RM Length L Ch R = 1,1680,533,533,533
BEGIN DESCRIPTION:
Buffalo Creek Trib 09 2.0
END DESCRIPTION:
XS GIS Cut Line= 5
      1300504.99      6923213.02      1300539.12      6922973.12
      1300555.00      6922888.00      1300549.53      6922798.64
      1300546.66      6922362.98
#Sta/Elev= 30
  4671.5 2290.33  4709.5 2288.98  4787.7 2283.17  4858.4 2275.00  4898.8 2273.47
  4907.2 2271.99  4929.2 2269.99  4939.4 2266.88  4949.5 2261.35  4959.7 2258.58
  4969.0 2254.03  4974.1 2254.15  4978.5 2249.88  4979.0 2249.38  5002.0 2249.88
  5002.9 2251.61  5010.4 2253.34  5030.5 2256.32  5050.5 2257.92  5078.9 2264.12
  5083.9 2262.29  5087.7 2264.02  5120.6 2266.28  5203.7 2268.93  5260.6 2272.11
  5340.6 2274.27  5360.6 2276.40  5420.6 2279.24  5460.6 2280.22  5525.6 2279.73
#Mann=5,-1,0
  4671.5   0.035       0  4907.2    0.07       0  4978.5    0.07       0
  5002.0    0.07       0  5203.7   0.035       0
Bank Sta=4978.5,5002
Exp/Cntr=0.3,0.1

Type RM Length L Ch R = 1,1147,242,242,242
BEGIN DESCRIPTION:
Buffalo Creek Trib 09 1.0
END DESCRIPTION:
XS GIS Cut Line= 5
      1301030.00      6922962.99      1300976.62      6922673.64
      1300955.00      6922588.00      1300919.33      6922475.72
      1300779.98      6922262.97
#Sta/Elev= 30
  4613.1 2276.06  4638.5 2276.50  4740.2 2271.33  4777.1 2270.26  4872.4 2269.83
  4893.3 2267.21  4907.3 2266.42  4923.5 2263.96  4931.5 2264.18  4936.7 2262.64
  4954.4 2259.92  4972.6 2254.98  4977.7 2254.74  4993.1 2251.38  4998.3 2251.38
  5005.2 2243.22  5005.7 2242.72  5028.8 2243.22  5037.6 2245.41  5076.3 2249.08
  5081.5 2252.16  5090.1 2250.43  5100.6 2253.61  5137.1 2257.90  5150.7 2258.67
  5180.9 2262.83  5207.9 2269.24  5230.3 2271.44  5302.0 2276.13  5367.8 2275.93
#Mann=4,-1,0
  4613.1   0.035       0  5005.2   0.035       0  5028.8   0.035       0
  5137.1   0.035       0
Bank Sta=5005.2,5028.8
Exp/Cntr=0.3,0.1

Type RM Length L Ch R = 1,905,418,418,418
BEGIN DESCRIPTION:
Buffalo Creek Trib 09 0.9
END DESCRIPTION:
XS GIS Cut Line= 4
      1301184.68      6922899.43      1301191.19      6922550.47
      1301105.69      6922373.35      1301030.01      6922213.02
#Sta/Elev= 30
  4501.7 2269.10  4563.1 2266.08  4603.2 2265.49  4703.2 2267.02  4733.2 2264.32
  4793.2 2257.16  4823.2 2255.70  4849.5 2251.82  4856.2 2252.76  4864.6 2250.00
  4871.1 2249.41  4878.9 2249.60  4886.8 2248.31  4895.9 2248.04  4909.0 2248.63
  4975.6 2247.92  4991.9 2245.51  4997.1 2242.12  4997.6 2241.62  5020.7 2242.12
  5031.1 2247.40  5037.1 2249.03  5042.4 2251.92  5047.4 2251.92  5053.3 2254.53
  5075.4 2258.62  5105.3 2266.62  5133.6 2268.01  5194.6 2272.84  5224.7 2273.24
#Mann=5,-1,0
  4501.7   0.035       0  4871.1    0.07       0  4997.1    0.07       0
  5020.7    0.07       0  5194.6   0.035       0
Bank Sta=4997.1,5020.7
Exp/Cntr=0.3,0.1

Type RM Length L Ch R = 1,487,0,0,0
BEGIN DESCRIPTION:
Buffalo Creek Trib 09 0.8
END DESCRIPTION:
XS GIS Cut Line= 4
      1301244.60      6922697.57      1301460.53      6922393.05
      1301495.88      6922346.04      1301282.32      6922209.31
#Sta/Elev= 30
  4626.7 2265.35  4655.1 2263.09  4669.8 2259.83  4690.7 2259.61  4705.5 2257.58
  4712.0 2254.65  4735.1 2250.00  4770.8 2246.52  4791.6 2243.27  4806.4 2244.19
  4827.3 2240.91  4856.9 2243.55  4920.4 2245.10  5014.2 2243.58  5016.9 2240.08
  5017.4 2239.58  5040.5 2240.08  5043.3 2244.97  5054.5 2248.58  5071.7 2250.31
  5101.5 2245.73  5107.4 2247.97  5116.7 2246.52  5122.6 2248.59  5137.8 2247.15
  5143.8 2249.61  5202.4 2251.85  5289.2 2258.59  5304.4 2263.30  5312.4 2263.31
#Mann=4,-1,0
  4626.7   0.035       0  4770.8    0.07       0  5016.9    0.07       0
  5040.5    0.07       0
Bank Sta=5016.9,5040.5
Exp/Cntr=0.3,0.1

Chan Stop Cuts=-1