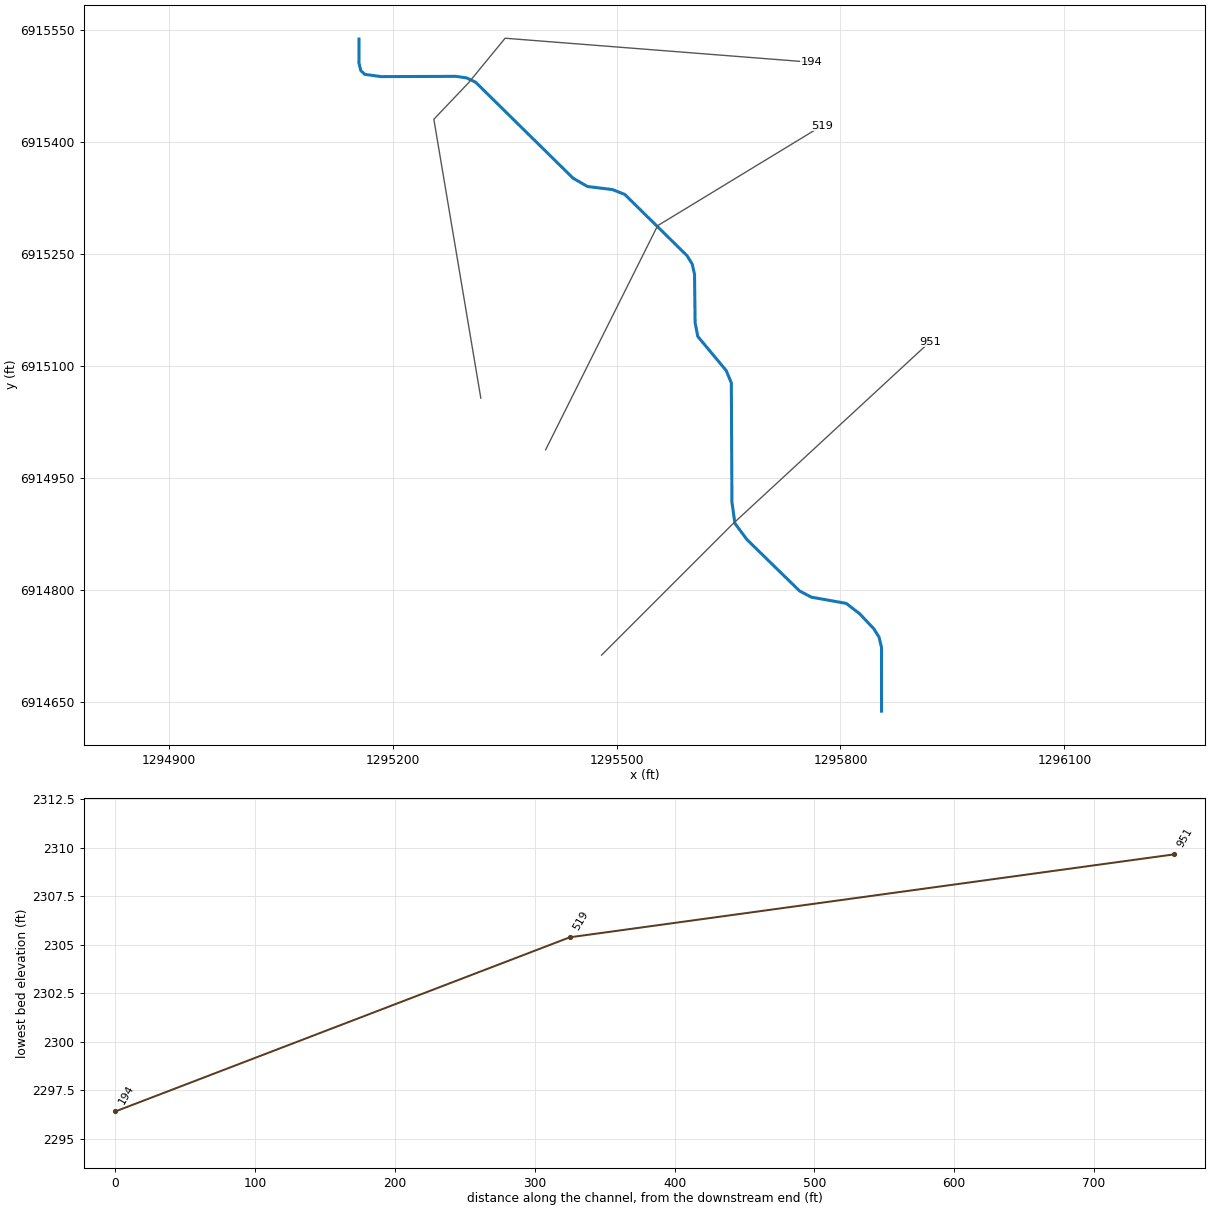
--- Buffalo Creek Trib 10.prj (project) ---

Proj Title=Buffalo Creek Trib 10 Base Level Engineering
Current Plan=p01
Default Exp/Contr=0.3,0.1
English Units
Geom File=g01
Flow File=f01
Plan File=p01
BEGIN DESCRIPTION:
Buffalo Creek Trib 10
END DESCRIPTION:

--- Buffalo Creek Trib 10.p01 (plan) ---

Plan Title=Multiple Run
Short Identifier=Multiple
Geom File=g01
Flow File=f01
Subcritical Flow
K Sum by GR= 0
Std Step Tol= 0.01
Critical Tol= 0.01
Num of Std Step Trials= 20
Max Error Tol= 0.3
Flow Tol Ratio= 0.001
Split Flow NTrial= 30
Split Flow Tol= 0.02
Split Flow Ratio= 0.02
Log Output Level= 0
Friction Slope Method= 1
Unsteady Friction Slope Method= 2
Unsteady Bridges Friction Slope Method= 1
Parabolic Critical Depth
Global Vel Dist=  1 , 1 , 1
Global Log Level= 0
CheckData=True
Encroach Param= -1, 0, 0, 0
BEGIN DESCRIPTION:
Multiple Run
END DESCRIPTION:

--- Buffalo Creek Trib 10.f01 (steady flow) ---

Flow Title=Multiple
Number of Profiles=7
Profile Names=10-year,25-year,50-year,1pct_min,100-year,1pct_plu,500-year
River Rch & RM= Buffalo Creek Tr,Reach-1,951
     159     217     264     161     321     640     477
Boundary for River Rch & Prof#=Buffalo Creek Tr,Reach-1,1
Up Type=0
Dn Type=3
Dn Slope=0.005
Boundary for River Rch & Prof#=Buffalo Creek Tr,Reach-1,2
Up Type=0
Dn Type=3
Dn Slope=0.005
Boundary for River Rch & Prof#=Buffalo Creek Tr,Reach-1,3
Up Type=0
Dn Type=3
Dn Slope=0.005
Boundary for River Rch & Prof#=Buffalo Creek Tr,Reach-1,4
Up Type=0
Dn Type=3
Dn Slope=0.005
Boundary for River Rch & Prof#=Buffalo Creek Tr,Reach-1,5
Up Type=0
Dn Type=3
Dn Slope=0.005
Boundary for River Rch & Prof#=Buffalo Creek Tr,Reach-1,6
Up Type=0
Dn Type=3
Dn Slope=0.005
Boundary for River Rch & Prof#=Buffalo Creek Tr,Reach-1,7
Up Type=0
Dn Type=3
Dn Slope=0.005

--- Buffalo Creek Trib 10.g01 (geometry) ---

Geom Title=Existing Conditions

River Reach=Buffalo Creek Tr,Reach-1
Reach XY= 30
      1295855.00      6914638.00      1295854.95      6914723.11
      1295851.72      6914736.85      1295844.71      6914748.18
      1295825.57      6914768.44      1295807.57      6914782.27
      1295761.08      6914790.54      1295745.31      6914798.77
      1295674.59      6914867.80      1295658.53      6914889.45
      1295654.57      6914917.82      1295653.78      6915077.50
      1295646.86      6915094.06      1295608.86      6915139.60
      1295605.25      6915158.10      1295604.48      6915222.79
      1295601.39      6915236.52      1295594.49      6915247.81
      1295511.07      6915329.85      1295494.37      6915336.46
      1295461.05      6915340.54      1295441.79      6915351.63
      1295311.19      6915480.19      1295299.14      6915485.94
      1295285.00      6915488.03      1295184.66      6915487.68
      1295162.71      6915490.72      1295157.37      6915495.83
      1295154.90      6915506.05      1295155.00      6915538.00

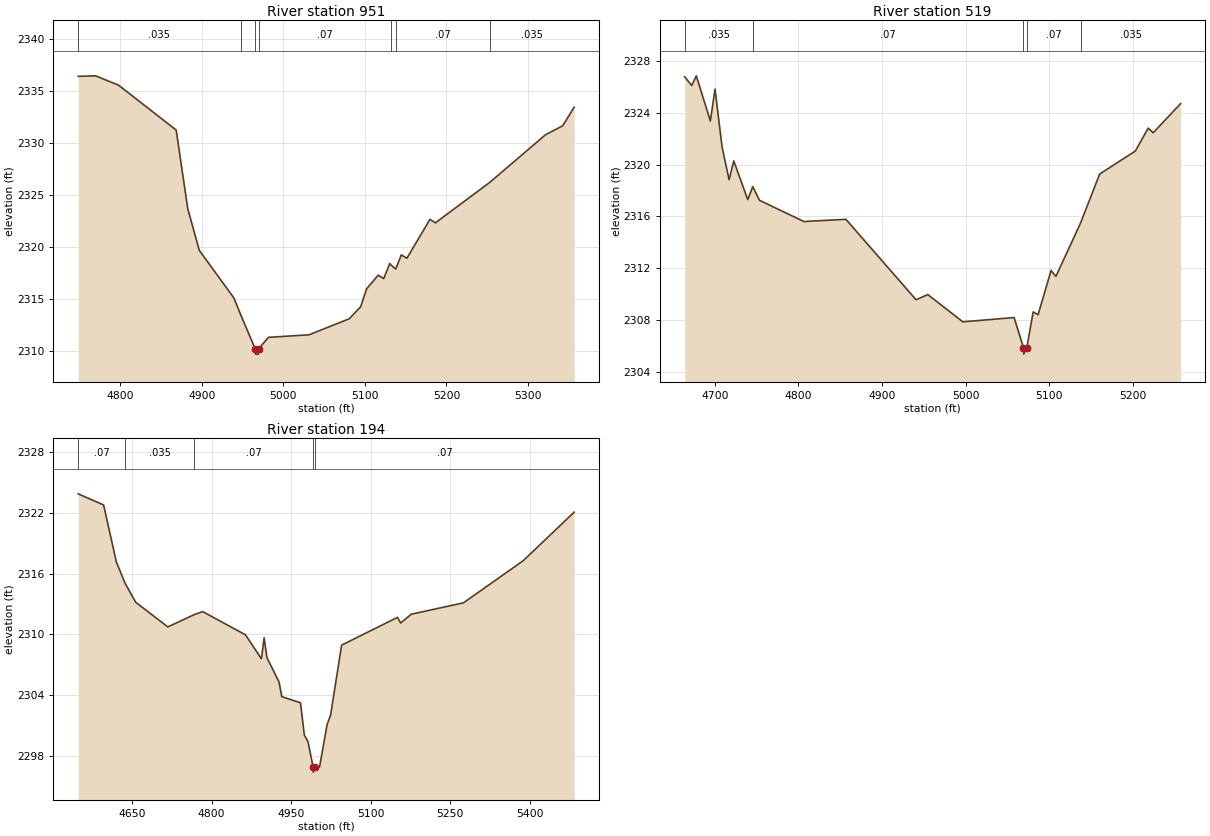
Type RM Length L Ch R = 1,951,432,432,432
BEGIN DESCRIPTION:
Buffalo Creek Trib 10 2.0
END DESCRIPTION:
XS GIS Cut Line= 3
      1295479.97      6914712.97      1295655.00      6914888.00
      1295920.11      6915132.85
#Sta/Elev= 30
  4748.3 2336.44  4769.6 2336.49  4797.8 2335.59  4868.5 2331.26  4882.7 2323.68
  4896.8 2319.67  4939.3 2315.07  4947.5 2313.48  4965.5 2310.16  4965.8 2309.66
  4969.3 2309.66  4969.5 2310.16  4981.7 2311.28  5031.3 2311.52  5080.6 2313.06
  5094.8 2314.22  5102.1 2315.96  5116.3 2317.27  5123.1 2316.94  5130.5 2318.40
  5132.2 2318.24  5137.8 2317.86  5144.7 2319.23  5151.5 2318.90  5179.8 2322.65
  5186.6 2322.32  5253.2 2326.22  5321.6 2330.81  5342.6 2331.67  5356.7 2333.46
#Mann=7,-1,0
  4748.3   0.035       0  4947.5    0.07       0  4965.5    0.07       0
  4969.5    0.07       0  5132.2   0.035       0  5137.8    0.07       0
  5253.2   0.035       0
Bank Sta=4965.5,4969.5
Exp/Cntr=0.3,0.1

Type RM Length L Ch R = 1,519,325,325,325
BEGIN DESCRIPTION:
Buffalo Creek Trib 10 1.0
END DESCRIPTION:
XS GIS Cut Line= 3
      1295405.01      6914988.02      1295555.00      6915288.00
      1295775.12      6915421.84
#Sta/Elev= 30
  4664.1 2326.77  4672.5 2326.09  4678.0 2326.84  4694.8 2323.36  4700.4 2325.82
  4708.8 2321.36  4717.2 2318.83  4722.8 2320.28  4739.5 2317.30  4745.5 2318.30
  4753.5 2317.25  4806.6 2315.61  4856.9 2315.78  4940.8 2309.58  4954.8 2309.98
  4996.7 2307.88  5058.0 2308.21  5069.2 2305.89  5069.5 2305.39  5073.2 2305.89
  5080.8 2308.64  5086.7 2308.43  5102.2 2311.84  5108.0 2311.38  5137.7 2315.53
  5160.3 2319.27  5202.9 2321.04  5218.4 2322.81  5224.3 2322.45  5257.1 2324.70
#Mann=5,-1,0
  4664.1   0.035       0  4745.5    0.07       0  5069.2    0.07       0
  5073.2    0.07       0  5137.7   0.035       0
Bank Sta=5069.2,5073.2
Exp/Cntr=0.3,0.1

Type RM Length L Ch R = 1,194,0,0,0
BEGIN DESCRIPTION:
Buffalo Creek Trib 10 0.5
END DESCRIPTION:
XS GIS Cut Line= 5
      1295318.19      6915057.13      1295255.26      6915430.58
      1295301.74      6915479.40      1295350.75      6915539.09
      1295761.14      6915506.91
#Sta/Elev= 30
  4548.4 2323.86  4596.3 2322.76  4620.3 2317.15  4636.8 2315.04  4656.8 2313.17
  4717.3 2310.74  4767.6 2311.96  4782.9 2312.25  4863.7 2309.96  4893.8 2307.60
  4898.9 2309.66  4904.2 2307.71  4927.1 2305.30  4932.2 2303.86  4967.4 2303.26
  4974.7 2300.08  4981.6 2299.42  4991.3 2296.92  4991.5 2296.42  4995.3 2296.92
  5003.4 2296.93  5017.7 2301.12  5024.2 2302.04  5045.0 2308.94  5150.4 2311.68
  5156.3 2311.12  5176.3 2311.99  5274.6 2313.11  5387.0 2317.25  5483.4 2322.05
#Mann=5,-1,0
  4548.4    0.07       0  4636.8   0.035       0  4767.6    0.07       0
  4991.3    0.07       0  4995.3    0.07       0
Bank Sta=4991.3,4995.3
Exp/Cntr=0.3,0.1

Chan Stop Cuts=-1