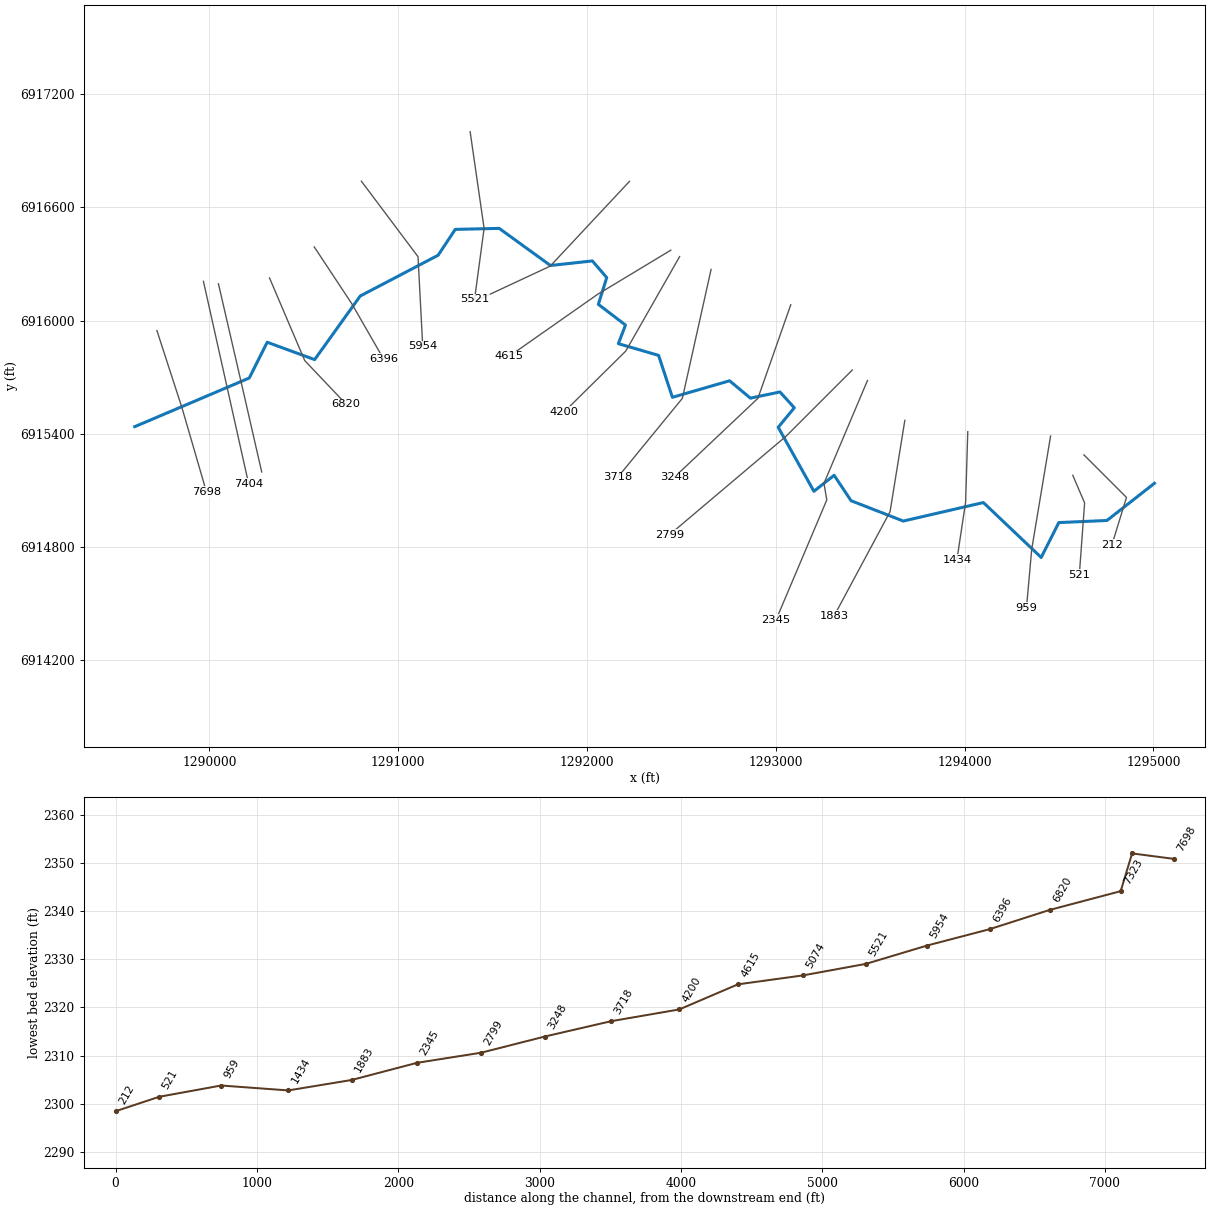
--- Buffalo Creek Trib 11.prj (project) ---

Proj Title=Buffalo Creek Trib 11 Base Level Engineering
Current Plan=p01
Default Exp/Contr=0.3,0.1
English Units
Geom File=g01
Flow File=f01
Plan File=p01
BEGIN DESCRIPTION:
Buffalo Creek Trib 11
END DESCRIPTION:

--- Buffalo Creek Trib 11.p01 (plan) ---

Plan Title=Multiple Run
Short Identifier=Multiple
Geom File=g01
Flow File=f01
Subcritical Flow
K Sum by GR= 0
Std Step Tol= 0.01
Critical Tol= 0.01
Num of Std Step Trials= 20
Max Error Tol= 0.3
Flow Tol Ratio= 0.001
Split Flow NTrial= 30
Split Flow Tol= 0.02
Split Flow Ratio= 0.02
Log Output Level= 0
Friction Slope Method= 1
Unsteady Friction Slope Method= 2
Unsteady Bridges Friction Slope Method= 1
Parabolic Critical Depth
Global Vel Dist=  1 , 1 , 1
Global Log Level= 0
CheckData=True
Encroach Param= -1, 0, 0, 0
BEGIN DESCRIPTION:
Multiple Run
END DESCRIPTION:

--- Buffalo Creek Trib 11.f01 (steady flow) ---

Flow Title=Multiple
Number of Profiles=7
Profile Names=10-year,25-year,50-year,1pct_min,100-year,1pct_plu,500-year
River Rch & RM= Buffalo Creek Tr,Reach-1,7698
     317     449     558     345     689    1375    1062
River Rch & RM= Buffalo Creek Tr,Reach-1,4615
     440     633     797     498     993    1982    1566
River Rch & RM= Buffalo Creek Tr,Reach-1,959
     446     643     810     507    1011    2017    1595
Boundary for River Rch & Prof#=Buffalo Creek Tr,Reach-1,1
Up Type=0
Dn Type=3
Dn Slope=0.005
Boundary for River Rch & Prof#=Buffalo Creek Tr,Reach-1,2
Up Type=0
Dn Type=3
Dn Slope=0.005
Boundary for River Rch & Prof#=Buffalo Creek Tr,Reach-1,3
Up Type=0
Dn Type=3
Dn Slope=0.005
Boundary for River Rch & Prof#=Buffalo Creek Tr,Reach-1,4
Up Type=0
Dn Type=3
Dn Slope=0.005
Boundary for River Rch & Prof#=Buffalo Creek Tr,Reach-1,5
Up Type=0
Dn Type=3
Dn Slope=0.005
Boundary for River Rch & Prof#=Buffalo Creek Tr,Reach-1,6
Up Type=0
Dn Type=3
Dn Slope=0.005
Boundary for River Rch & Prof#=Buffalo Creek Tr,Reach-1,7
Up Type=0
Dn Type=3
Dn Slope=0.005

--- Buffalo Creek Trib 11.g01 (geometry) ---

Geom Title=Existing Conditions

River Reach=Buffalo Creek Tr,Reach-1
Reach XY= 30
      1289605.00      6915438.00      1290211.50      6915695.73
      1290306.39      6915884.98      1290557.55      6915792.98
      1290798.94      6916129.86      1291211.45      6916345.75
      1291302.30      6916482.64      1291535.02      6916488.04
      1291806.27      6916291.47      1292028.42      6916315.57
      1292104.40      6916227.39      1292060.09      6916085.69
      1292203.78      6915975.97      1292165.96      6915877.58
      1292379.03      6915815.35      1292452.26      6915593.34
      1292755.00      6915680.90      1292865.48      6915588.95
      1293021.78      6915621.71      1293097.90      6915538.02
      1293012.61      6915434.67      1293201.64      6915095.61
      1293308.58      6915180.50      1293398.55      6915045.75
      1293675.03      6914938.04      1294099.11      6915036.04
      1294405.33      6914745.18      1294498.62      6914930.00
      1294753.58      6914941.04      1295005.00      6915138.00

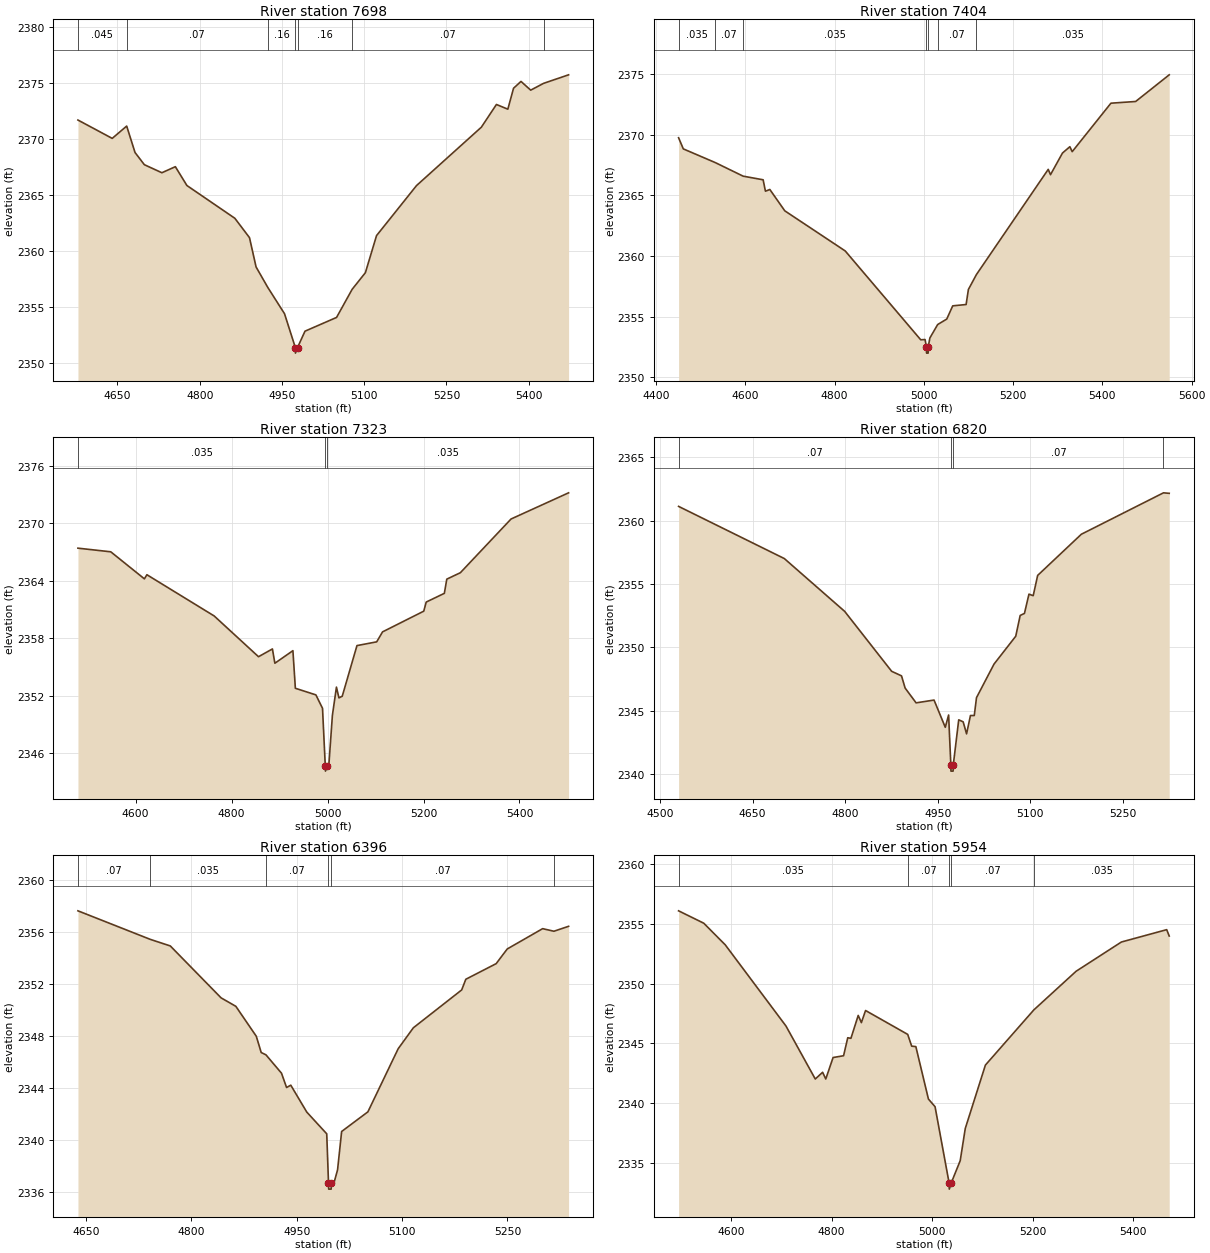
Type RM Length L Ch R = 1,7698,294,294,294
BEGIN DESCRIPTION:
Buffalo Creek Trib 11 17.0
END DESCRIPTION:
XS GIS Cut Line= 3
      1289722.21      6915947.02      1289855.00      6915538.00
      1289984.83      6915091.63
#Sta/Elev= 30
  4577.9 2371.68  4640.4 2370.04  4666.8 2371.14  4682.0 2368.78  4699.0 2367.69
  4731.0 2366.97  4755.6 2367.51  4776.6 2365.83  4864.1 2362.90  4890.8 2361.17
  4902.8 2358.55  4924.2 2356.72  4954.7 2354.37  4974.4 2351.35  4974.6 2350.85
  4978.4 2351.35  4992.0 2352.81  5049.6 2354.04  5078.0 2356.55  5102.2 2358.04
  5122.5 2361.35  5195.4 2365.82  5313.7 2371.04  5341.2 2373.07  5362.0 2372.65
  5372.4 2374.52  5386.0 2375.13  5403.7 2374.35  5427.3 2374.96  5472.8 2375.72
#Mann=7,-1,0
  4577.9   0.045       0  4666.8    0.07       0  4924.2    0.16       0
  4974.4    0.07       0  4978.4    0.16       0  5078.0    0.07       0
  5427.3   0.045       0
Bank Sta=4974.4,4978.4
Exp/Cntr=0.3,0.1

Type RM Length L Ch R = 1,7404,81,81,81
BEGIN DESCRIPTION:
Buffalo Creek Trib 11 16.2
END DESCRIPTION:
XS GIS Cut Line= 2
      1289968.64      6916207.57      1290208.23      6915134.60
#Sta/Elev= 30
  4450.3 2369.75  4460.9 2368.83  4532.5 2367.70  4595.0 2366.58  4639.8 2366.28
  4644.9 2365.34  4654.8 2365.48  4688.3 2363.72  4823.7 2360.41  4992.9 2353.08
  5002.6 2353.10  5005.7 2352.48  5006.0 2351.98  5009.5 2351.98  5009.7 2352.48
  5013.4 2353.23  5030.9 2354.34  5051.2 2354.79  5064.6 2355.88  5094.6 2355.99
  5099.7 2357.23  5117.5 2358.45  5278.6 2367.14  5283.7 2366.70  5310.6 2368.49
  5327.1 2369.01  5332.3 2368.60  5419.1 2372.60  5474.5 2372.74  5549.7 2374.94
#Mann=7,-1,0
  4450.3   0.035       0  4532.5    0.07       0  4595.0   0.035       0
  5005.7   0.035       0  5009.7   0.035       0  5030.9    0.07       0
  5117.5   0.035       0
Bank Sta=5005.7,5009.7
Exp/Cntr=0.3,0.1

Type RM Length L Ch R = 1,7323,503,503,503
BEGIN DESCRIPTION:
Buffalo Creek Trib 11 16.0
END DESCRIPTION:
XS GIS Cut Line= 3
      1290048.05      6916194.66      1290165.12      6915687.80
      1290277.21      6915198.17
#Sta/Elev= 30
  4479.8 2367.39  4548.2 2367.01  4618.3 2364.19  4623.5 2364.62  4763.7 2360.32
  4856.1 2356.07  4885.1 2356.88  4890.2 2355.39  4927.8 2356.70  4932.9 2352.78
  4975.7 2352.09  4989.5 2350.69  4995.3 2344.64  4995.6 2344.14  4999.3 2344.64
  5002.5 2344.64  5010.1 2349.96  5018.5 2352.90  5023.7 2351.78  5030.6 2351.95
  5061.3 2357.23  5102.4 2357.62  5114.6 2358.66  5200.5 2360.82  5205.6 2361.77
  5243.4 2362.68  5248.5 2364.16  5276.8 2364.83  5382.4 2370.43  5502.3 2373.16
#Mann=3,-1,0
  4479.8   0.035       0  4995.3   0.035       0  4999.3   0.035       0
Bank Sta=4995.3,4999.3
Exp/Cntr=0.3,0.1

Type RM Length L Ch R = 1,6820,424,424,424
BEGIN DESCRIPTION:
Buffalo Creek Trib 11 15.0
END DESCRIPTION:
XS GIS Cut Line= 3
      1290318.55      6916225.70      1290505.00      6915788.00
      1290724.84      6915556.38
#Sta/Elev= 30
  4530.1 2361.14  4701.5 2357.02  4799.3 2352.85  4875.4 2348.12  4891.4 2347.76
  4897.2 2346.80  4915.0 2345.63  4944.1 2345.85  4962.3 2343.70  4967.7 2344.67
  4971.3 2340.74  4971.5 2340.24  4975.0 2340.24  4975.3 2340.74  4984.1 2344.29
  4991.3 2344.13  4996.8 2343.18  5003.1 2344.63  5009.3 2344.63  5012.9 2346.04
  5041.3 2348.69  5076.5 2350.89  5083.7 2352.53  5090.6 2352.69  5097.9 2354.21
  5104.8 2354.09  5112.0 2355.69  5182.8 2358.94  5315.9 2362.21  5325.2 2362.17
#Mann=4,-1,0
  4530.1    0.07       0  4971.3    0.07       0  4975.3    0.07       0
  5315.9   0.035       0
Bank Sta=4971.3,4975.3
Exp/Cntr=0.3,0.1

Type RM Length L Ch R = 1,6396,442,442,442
BEGIN DESCRIPTION:
Buffalo Creek Trib 11 14.0
END DESCRIPTION:
XS GIS Cut Line= 3
      1290555.53      6916389.77      1290755.00      6916088.00
      1290922.74      6915795.98
#Sta/Elev= 30
  4638.5 2357.64  4741.3 2355.45  4770.0 2354.94  4842.3 2350.95  4863.3 2350.30
  4892.4 2348.00  4899.4 2346.75  4906.2 2346.57  4928.3 2345.16  4935.5 2344.06
  4941.5 2344.24  4964.3 2342.17  4992.7 2340.50  4995.2 2336.75  4995.5 2336.25
  4999.0 2336.25  4999.2 2336.75  5003.1 2336.75  5008.1 2337.73  5013.9 2340.68
  5051.3 2342.19  5094.4 2347.04  5116.0 2348.65  5184.8 2351.56  5190.7 2352.38
  5233.9 2353.58  5249.7 2354.71  5300.1 2356.27  5316.1 2356.07  5337.0 2356.45
#Mann=6,-1,0
  4638.5    0.07       0  4741.3   0.035       0  4906.2    0.07       0
  4995.2    0.07       0  4999.2    0.07       0  5316.1   0.035       0
Bank Sta=4995.2,4999.2
Exp/Cntr=0.3,0.1

Type RM Length L Ch R = 1,5954,433,433,433
BEGIN DESCRIPTION:
Buffalo Creek Trib 11 13.0
END DESCRIPTION:
XS GIS Cut Line= 3
      1290805.03      6916737.97      1291105.00      6916338.00
      1291130.00      6915863.01
#Sta/Elev= 30
  4495.8 2356.06  4545.8 2355.03  4588.5 2353.23  4709.3 2346.46  4767.6 2342.04
  4782.2 2342.60  4788.5 2342.04  4803.0 2343.83  4823.9 2343.98  4832.2 2345.48
  4838.5 2345.43  4853.0 2347.34  4859.3 2346.74  4867.6 2347.75  4951.4 2345.76
  4959.3 2344.78  4967.6 2344.74  4992.6 2340.37  5005.8 2339.73  5033.8 2333.36
  5034.1 2332.86  5037.8 2333.36  5055.8 2335.23  5065.9 2337.92  5105.9 2343.20
  5202.2 2347.80  5286.2 2351.02  5376.3 2353.46  5466.4 2354.49  5471.4 2353.96
#Mann=5,-1,0
  4495.8   0.035       0  4951.4    0.07       0  5033.8    0.07       0
  5037.8    0.07       0  5202.2   0.035       0
Bank Sta=5033.8,5037.8
Exp/Cntr=0.3,0.1

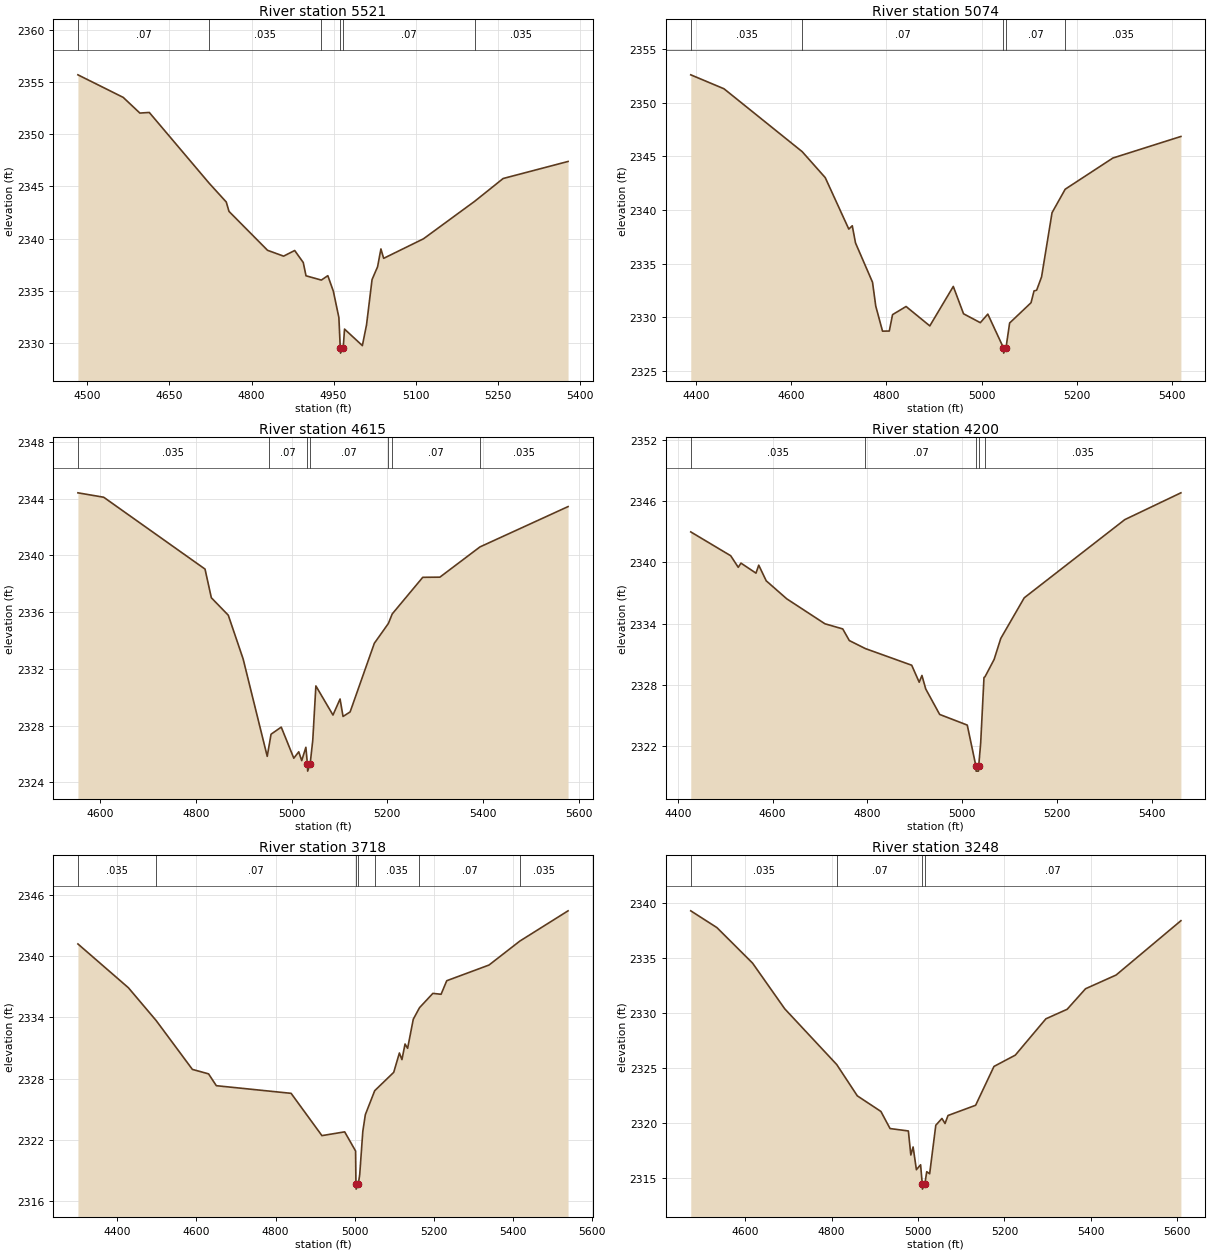
Type RM Length L Ch R = 1,5521,447,447,447
BEGIN DESCRIPTION:
Buffalo Creek Trib 11 12.0
END DESCRIPTION:
XS GIS Cut Line= 3
      1291381.06      6916999.99      1291455.00      6916488.00
      1291404.50      6916112.99
#Sta/Elev= 30
  4482.8 2355.68  4565.6 2353.52  4596.0 2352.02  4613.2 2352.08  4722.6 2345.31
  4753.9 2343.51  4758.9 2342.61  4829.3 2338.89  4858.7 2338.33  4878.9 2338.87
  4894.6 2337.72  4899.6 2336.45  4927.6 2336.04  4939.5 2336.46  4949.6 2334.97
  4959.7 2332.45  4962.2 2329.55  4962.7 2329.05  4967.6 2329.55  4970.0 2331.35
  5002.6 2329.77  5010.2 2331.75  5020.3 2336.09  5030.4 2337.31  5036.5 2339.02
  5041.5 2338.12  5114.3 2339.99  5207.9 2343.58  5259.9 2345.76  5378.5 2347.39
#Mann=6,-1,0
  4482.8    0.07       0  4722.6   0.035       0  4927.6    0.07       0
  4962.2    0.07       0  4967.6    0.07       0  5207.9   0.035       0
Bank Sta=4962.2,4967.6
Exp/Cntr=0.3,0.1

Type RM Length L Ch R = 1,5074,459,459,459
BEGIN DESCRIPTION:
Buffalo Creek Trib 11 11.0
END DESCRIPTION:
XS GIS Cut Line= 3
      1292224.81      6916736.96      1291805.00      6916288.00
      1291429.99      6916112.99
#Sta/Elev= 30
  4389.4 2352.61  4459.1 2351.31  4623.3 2345.44  4671.6 2343.02  4721.0 2338.22
  4728.3 2338.53  4735.1 2336.93  4770.8 2333.26  4777.6 2331.03  4791.8 2328.70
  4806.0 2328.71  4812.8 2330.24  4841.2 2331.00  4891.0 2329.19  4940.3 2332.87
  4961.8 2330.32  4997.0 2329.49  5012.7 2330.29  5045.5 2327.15  5046.0 2326.65
  5050.9 2327.15  5058.5 2329.46  5103.4 2331.35  5109.7 2332.45  5115.2 2332.52
  5125.5 2333.76  5147.5 2339.75  5175.1 2341.94  5275.2 2344.85  5417.9 2346.86
#Mann=5,-1,0
  4389.4   0.035       0  4623.3    0.07       0  5045.5    0.07       0
  5050.9    0.07       0  5175.1   0.035       0
Bank Sta=5045.5,5050.9
Exp/Cntr=0.3,0.1

Type RM Length L Ch R = 1,4615,415,415,415
BEGIN DESCRIPTION:
Buffalo Creek Trib 11 10.0
END DESCRIPTION:
XS GIS Cut Line= 3
      1292443.53      6916372.36      1292055.00      6916138.00
      1291588.41      6915811.01
#Sta/Elev= 30
  4553.9 2344.40  4607.7 2344.09  4819.3 2339.03  4832.5 2337.01  4867.9 2335.78
  4898.9 2332.70  4949.2 2325.84  4952.0 2326.39  4957.2 2327.40  4978.5 2327.90
  5004.7 2325.71  5015.0 2326.16  5021.2 2325.54  5029.9 2326.48  5033.1 2325.30
  5033.6 2324.80  5038.8 2325.30  5044.3 2326.98  5050.8 2330.80  5086.5 2328.75
  5101.3 2329.88  5107.5 2328.65  5122.3 2328.97  5172.8 2333.80  5202.2 2335.20
  5210.2 2335.87  5274.0 2338.45  5309.7 2338.46  5393.4 2340.59  5577.4 2343.43
#Mann=7,-1,0
  4553.9   0.035       0  4952.0    0.07       0  5033.1    0.07       0
  5038.8    0.07       0  5202.2   0.035       0  5210.2    0.07       0
  5393.4   0.035       0
Bank Sta=5033.1,5038.8
Exp/Cntr=0.3,0.1

Type RM Length L Ch R = 1,4200,482,482,482
BEGIN DESCRIPTION:
Buffalo Creek Trib 11 9.0
END DESCRIPTION:
XS GIS Cut Line= 3
      1292490.46      6916338.57      1292205.00      6915838.00
      1291879.26      6915516.40
#Sta/Elev= 30
  4427.5 2342.97  4511.8 2340.64  4527.7 2339.51  4533.4 2339.92  4565.1 2338.94
  4570.9 2339.72  4586.7 2338.19  4630.0 2336.43  4710.6 2333.99  4748.1 2333.49
  4762.0 2332.35  4795.7 2331.57  4893.6 2329.94  4909.4 2328.28  4915.2 2328.94
  4923.2 2327.62  4952.6 2325.13  5010.8 2324.09  5029.0 2320.09  5029.5 2319.59
  5034.4 2319.59  5034.9 2320.09  5039.1 2322.33  5046.1 2328.75  5048.2 2328.81
  5067.4 2330.50  5081.5 2332.56  5131.0 2336.53  5343.1 2344.17  5461.5 2346.79
#Mann=5,-1,0
  4427.5   0.035       0  4795.7    0.07       0  5029.0    0.07       0
  5034.9    0.07       0  5048.2   0.035       0
Bank Sta=5029,5034.9
Exp/Cntr=0.3,0.1

Type RM Length L Ch R = 1,3718,470,470,470
BEGIN DESCRIPTION:
Buffalo Creek Trib 11 8.0
END DESCRIPTION:
XS GIS Cut Line= 3
      1292657.10      6916270.79      1292505.00      6915588.00
      1292162.32      6915169.27
#Sta/Elev= 30
  4299.9 2341.21  4427.7 2336.91  4498.2 2333.68  4589.6 2328.90  4630.6 2328.46
  4650.2 2327.30  4839.5 2326.55  4917.5 2322.40  4975.1 2322.77  5002.7 2320.89
  5003.6 2317.65  5004.1 2317.15  5009.6 2317.65  5013.1 2318.56  5021.0 2322.82
  5027.4 2324.46  5051.1 2326.81  5099.2 2328.61  5113.6 2330.51  5120.0 2329.86
  5127.9 2331.39  5134.4 2330.97  5148.7 2333.82  5164.4 2334.95  5198.3 2336.36
  5219.1 2336.27  5233.4 2337.60  5340.4 2339.14  5418.4 2341.49  5540.5 2344.46
#Mann=7,-1,0
  4299.9   0.035       0  4498.2    0.07       0  5003.6    0.07       0
  5009.6    0.07       0  5051.1   0.035       0  5164.4    0.07       0
  5418.4   0.035       0
Bank Sta=5003.6,5009.6
Exp/Cntr=0.3,0.1

Type RM Length L Ch R = 1,3248,449,449,449
BEGIN DESCRIPTION:
Buffalo Creek Trib 11 7.0
END DESCRIPTION:
XS GIS Cut Line= 3
      1293078.99      6916083.35      1292905.00      6915588.00
      1292461.76      6915169.23
#Sta/Elev= 30
  4473.8 2339.32  4534.4 2337.79  4616.8 2334.56  4691.4 2330.39  4811.8 2325.31
  4859.4 2322.46  4914.0 2321.04  4935.2 2319.48  4977.6 2319.26  4983.3 2317.07
  4988.6 2317.80  4996.2 2315.73  5005.9 2316.18  5009.7 2314.46  5010.2 2313.96
  5015.9 2314.46  5020.1 2315.55  5026.9 2315.36  5041.1 2319.78  5055.3 2320.40
  5062.5 2319.94  5069.4 2320.67  5133.3 2321.60  5175.8 2325.14  5225.2 2326.17
  5296.0 2329.48  5345.3 2330.35  5387.8 2332.22  5458.6 2333.47  5608.6 2338.42
#Mann=4,-1,0
  4473.8   0.035       0  4811.8    0.07       0  5009.7    0.07       0
  5015.9    0.07       0
Bank Sta=5009.7,5015.9
Exp/Cntr=0.3,0.1

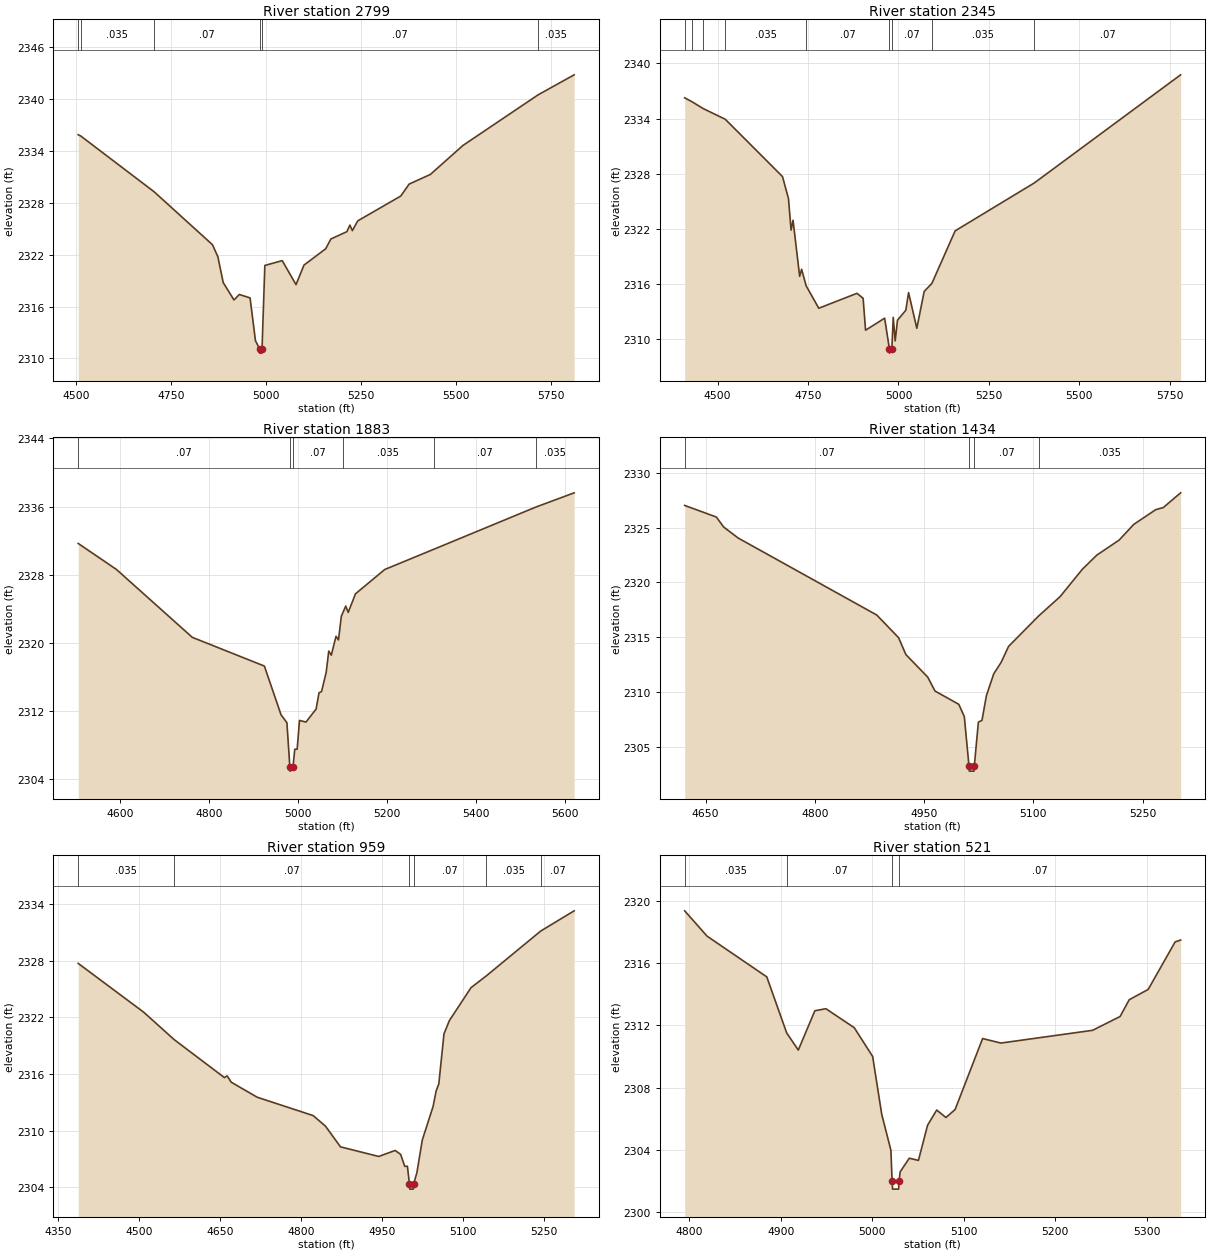
Type RM Length L Ch R = 1,2799,454,454,454
BEGIN DESCRIPTION:
Buffalo Creek Trib 11 6.0
END DESCRIPTION:
XS GIS Cut Line= 3
      1293404.98      6915737.98      1293055.00      6915388.00
      1292435.74      6914864.56
#Sta/Elev= 30
  4504.7 2335.87  4511.2 2335.73  4704.7 2329.27  4858.2 2323.15  4872.4 2321.76
  4886.5 2318.77  4914.8 2316.76  4928.9 2317.39  4957.2 2317.00  4971.4 2312.05
  4982.3 2311.11  4982.8 2310.61  4988.2 2310.61  4988.7 2311.11  4996.1 2320.75
  5041.9 2321.31  5078.2 2318.53  5099.1 2320.79  5156.3 2322.68  5169.9 2323.81
  5212.2 2324.66  5220.0 2325.42  5226.5 2324.78  5240.8 2325.91  5354.0 2328.78
  5376.0 2330.16  5432.0 2331.28  5517.7 2334.63  5715.4 2340.48  5810.5 2342.80
#Mann=6,-1,0
  4504.7    0.07       0  4511.2   0.035       0  4704.7    0.07       0
  4982.3    0.07       0  4988.7    0.07       0  5715.4   0.035       0
Bank Sta=4982.3,4988.7
Exp/Cntr=0.3,0.1

Type RM Length L Ch R = 1,2345,462,462,462
BEGIN DESCRIPTION:
Buffalo Creek Trib 11 5.0
END DESCRIPTION:
XS GIS Cut Line= 4
      1293485.22      6915682.26      1293255.00      6915138.00
      1293269.74      6915049.57      1293000.84      6914414.01
#Sta/Elev= 30
  4409.1 2336.26  4428.7 2335.85  4460.3 2335.09  4521.3 2333.93  4679.5 2327.70
  4696.0 2325.30  4703.2 2321.88  4708.6 2322.95  4726.9 2316.86  4732.3 2317.63
  4744.8 2315.83  4779.7 2313.39  4885.3 2315.01  4902.3 2314.47  4909.0 2311.00
  4961.8 2312.31  4974.8 2309.01  4975.3 2308.51  4981.8 2309.01  4985.5 2312.40
  4990.9 2309.84  4997.3 2312.09  5020.3 2313.17  5027.9 2315.09  5050.7 2311.21
  5071.0 2315.21  5092.5 2316.10  5156.6 2321.80  5375.1 2327.00  5779.8 2338.76
#Mann=9,-1,0
  4409.1    0.07       0  4428.7   0.035       0  4460.3    0.07       0
  4521.3   0.035       0  4744.8    0.07       0  4974.8    0.07       0
  4981.8    0.07       0  5092.5   0.035       0  5375.1    0.07       0
Bank Sta=4974.8,4981.8
Exp/Cntr=0.3,0.1

Type RM Length L Ch R = 1,1883,449,449,449
BEGIN DESCRIPTION:
Buffalo Creek Trib 11 4.0
END DESCRIPTION:
XS GIS Cut Line= 3
      1293683.15      6915471.34      1293605.00      6914988.00
      1293309.07      6914436.60
#Sta/Elev= 30
  4505.8 2331.67  4591.7 2328.62  4762.4 2320.65  4924.5 2317.28  4962.0 2311.56
  4975.2 2310.63  4981.8 2305.45  4982.3 2304.95  4988.8 2305.45  4992.9 2307.52
  4998.2 2307.52  5003.5 2310.90  5018.1 2310.71  5040.8 2312.23  5047.4 2314.15
  5053.1 2314.29  5063.5 2316.54  5069.3 2319.04  5075.0 2318.56  5085.6 2320.77
  5091.2 2320.35  5097.6 2323.13  5100.7 2323.50  5107.5 2324.32  5113.1 2323.58
  5129.4 2325.76  5195.2 2328.61  5306.2 2331.00  5534.7 2335.93  5621.2 2337.61
#Mann=6,-1,0
  4505.8    0.07       0  4981.8    0.07       0  4988.8    0.07       0
  5100.7   0.035       0  5306.2    0.07       0  5534.7   0.035       0
Bank Sta=4981.8,4988.8
Exp/Cntr=0.3,0.1

Type RM Length L Ch R = 1,1434,475,475,475
BEGIN DESCRIPTION:
Buffalo Creek Trib 11 3.0
END DESCRIPTION:
XS GIS Cut Line= 3
      1294016.48      6915411.49      1294005.00      6915038.00
      1293959.19      6914734.40
#Sta/Elev= 30
  4621.4 2327.03  4664.9 2325.97  4674.9 2325.06  4694.9 2324.05  4885.0 2317.03
  4915.0 2314.96  4925.0 2313.42  4955.0 2311.36  4965.0 2310.09  4997.6 2308.88
  5005.2 2307.76  5011.6 2303.28  5012.1 2302.78  5018.5 2302.78  5019.0 2303.28
  5024.5 2307.25  5029.5 2307.42  5035.5 2309.66  5045.6 2311.66  5055.7 2312.70
  5065.9 2314.16  5107.2 2316.94  5136.6 2318.70  5167.3 2321.21  5187.2 2322.50
  5217.6 2323.86  5237.8 2325.30  5268.1 2326.65  5278.2 2326.83  5302.1 2328.18
#Mann=4,-1,0
  4621.4    0.07       0  5011.6    0.07       0  5019.0    0.07       0
  5107.2   0.035       0
Bank Sta=5011.6,5019
Exp/Cntr=0.3,0.1

Type RM Length L Ch R = 1,959,438,438,438
BEGIN DESCRIPTION:
Buffalo Creek Trib 11 2.0
END DESCRIPTION:
XS GIS Cut Line= 3
      1294455.00      6915388.02      1294355.00      6914788.00
      1294327.25      6914477.43
#Sta/Elev= 30
  4386.6 2327.72  4508.3 2322.54  4564.5 2319.65  4657.8 2315.62  4662.9 2315.80
  4670.5 2315.13  4718.6 2313.54  4822.6 2311.59  4845.4 2310.47  4873.2 2308.28
  4944.2 2307.26  4974.6 2307.90  4984.8 2307.48  4992.4 2306.22  4997.4 2306.22
  5001.2 2304.30  5001.7 2303.80  5008.2 2303.80  5008.7 2304.30  5015.0 2305.56
  5025.0 2309.01  5045.1 2312.58  5050.6 2314.20  5055.6 2314.95  5065.2 2320.25
  5075.2 2321.66  5115.4 2325.15  5143.8 2326.40  5244.7 2331.15  5306.7 2333.29
#Mann=6,-1,0
  4386.6   0.035       0  4564.5    0.07       0  5001.2    0.07       0
  5008.7    0.07       0  5143.8   0.035       0  5244.7    0.07       0
Bank Sta=5001.2,5008.7
Exp/Cntr=0.3,0.1

Type RM Length L Ch R = 1,521,309,309,309
BEGIN DESCRIPTION:
Buffalo Creek Trib 11 1.0
END DESCRIPTION:
XS GIS Cut Line= 3
      1294572.48      6915180.55      1294635.25      6915034.09
      1294607.07      6914651.97
#Sta/Elev= 30
  4794.8 2319.37  4819.3 2317.74  4884.6 2315.12  4906.4 2311.51  4919.1 2310.41
  4937.2 2312.94  4949.3 2313.07  4980.3 2311.85  5000.4 2310.00  5010.4 2306.26
  5020.4 2303.96  5021.7 2301.96  5022.2 2301.46  5028.8 2301.46  5029.3 2301.96
  5030.5 2302.57  5040.5 2303.45  5050.5 2303.31  5060.5 2305.57  5070.5 2306.55
  5080.6 2306.07  5090.6 2306.58  5120.7 2311.15  5140.7 2310.86  5241.0 2311.68
  5271.1 2312.57  5281.1 2313.65  5301.8 2314.31  5331.3 2317.37  5337.3 2317.49
#Mann=4,-1,0
  4794.8   0.035       0  4906.4    0.07       0  5021.7    0.07       0
  5029.3    0.07       0
Bank Sta=5021.7,5029.3
Exp/Cntr=0.3,0.1

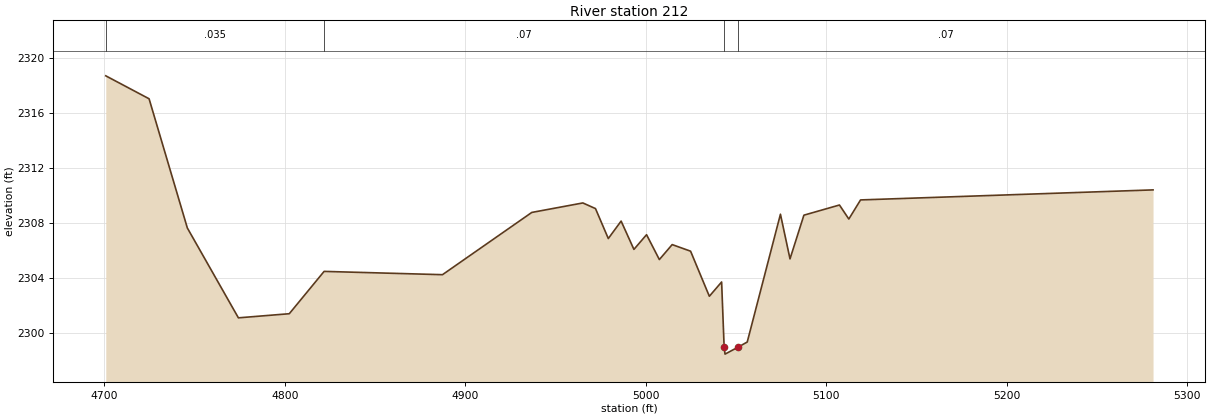
Type RM Length L Ch R = 1,212,0,0,0
BEGIN DESCRIPTION:
Buffalo Creek Trib 11 0.9
END DESCRIPTION:
XS GIS Cut Line= 3
      1294631.54      6915288.43      1294857.04      6915063.00
      1294780.01      6914813.05
#Sta/Elev= 30
  4700.8 2318.71  4724.8 2317.04  4746.0 2307.64  4774.3 2301.10  4802.5 2301.40
  4821.8 2304.48  4887.4 2304.24  4936.9 2308.77  4965.2 2309.46  4972.2 2309.05
  4979.3 2306.87  4986.4 2308.14  4993.5 2306.08  5000.5 2307.15  5007.6 2305.34
  5014.7 2306.43  5024.9 2305.95  5035.3 2302.67  5042.1 2303.71  5043.5 2298.96
  5044.0 2298.46  5051.1 2298.96  5056.3 2299.34  5074.7 2308.64  5080.0 2305.39
  5087.7 2308.57  5107.4 2309.31  5112.6 2308.29  5119.1 2309.68  5281.2 2310.41
#Mann=4,-1,0
  4700.8   0.035       0  4821.8    0.07       0  5043.5    0.07       0
  5051.1    0.07       0
Bank Sta=5043.5,5051.1
Exp/Cntr=0.3,0.1

Chan Stop Cuts=-1