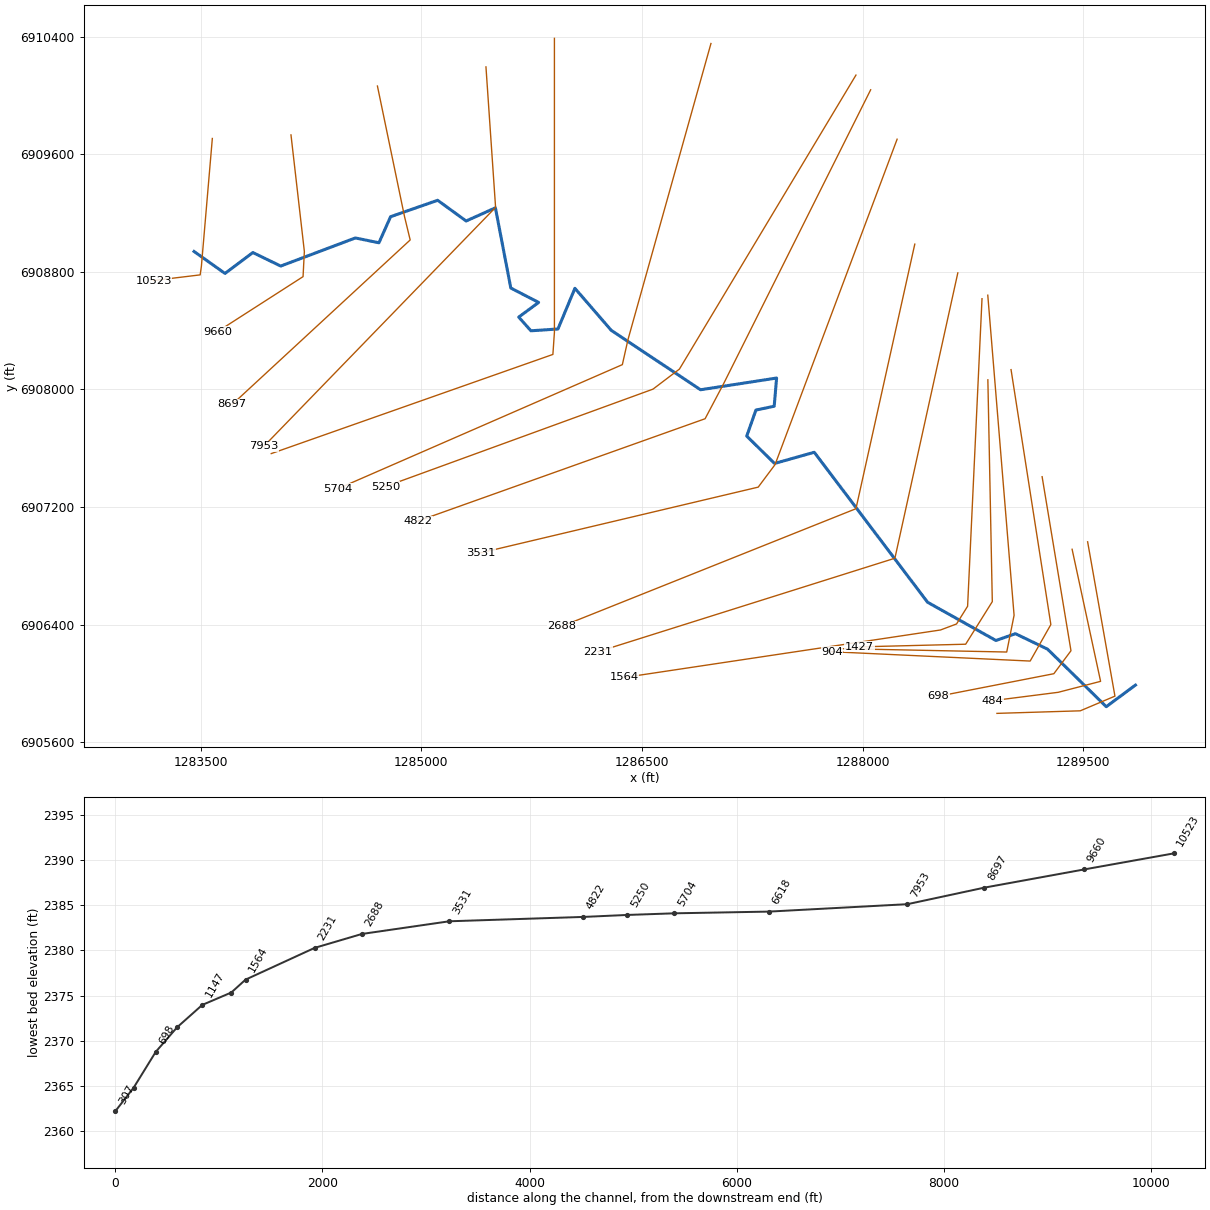
--- Buffalo Creek Trib 12.prj (project) ---

Proj Title=Buffalo Creek Trib 12 Base Level Engineering
Current Plan=p01
Default Exp/Contr=0.3,0.1
English Units
Geom File=g01
Flow File=f01
Plan File=p01
Y Axis Title=Elevation
X Axis Title(PF)=Main Channel Distance
X Axis Title(XS)=Station
BEGIN DESCRIPTION:
Buffalo Creek Trib 12
END DESCRIPTION:
DSS Export Rating Curves= 0
DSS Export Rating Curve Sorted= 0
DSS Export Volume Flow Curves= 0
DXF OffsetX= 0
DXF OffsetY= 0
DXF ScaleX= 1
DXF ScaleY= 10

--- Buffalo Creek Trib 12.p01 (plan) ---

Plan Title=Multiple Run
Short Identifier=Multiple
Geom File=g01
Flow File=f01
Subcritical Flow
K Sum by GR= 0
Std Step Tol= 0.01
Critical Tol= 0.01
Num of Std Step Trials= 20
Max Error Tol= 0.3
Flow Tol Ratio= 0.001
Split Flow NTrial= 30
Split Flow Tol= 0.02
Split Flow Ratio= 0.02
Log Output Level= 0
Friction Slope Method= 1
Unsteady Friction Slope Method= 2
Unsteady Bridges Friction Slope Method= 1
Parabolic Critical Depth
Global Vel Dist=  1 , 1 , 1
Global Log Level= 0
CheckData=True
Encroach Param= -1, 0, 0, 0
BEGIN DESCRIPTION:
Multiple Run
END DESCRIPTION:

--- Buffalo Creek Trib 12.f01 (steady flow) ---

Flow Title=Multiple
Number of Profiles=7
Profile Names=10-year,25-year,50-year,1pct_min,100-year,1pct_plu,500-year
River Rch & RM= Buffalo Creek Tr,Reach-1,10523
     239     328     400     241     482     961     710
Boundary for River Rch & Prof#=Buffalo Creek Tr,Reach-1,1
Up Type=0
Dn Type=3
Dn Slope=0.005
Boundary for River Rch & Prof#=Buffalo Creek Tr,Reach-1,2
Up Type=0
Dn Type=3
Dn Slope=0.005
Boundary for River Rch & Prof#=Buffalo Creek Tr,Reach-1,3
Up Type=0
Dn Type=3
Dn Slope=0.005
Boundary for River Rch & Prof#=Buffalo Creek Tr,Reach-1,4
Up Type=0
Dn Type=3
Dn Slope=0.005
Boundary for River Rch & Prof#=Buffalo Creek Tr,Reach-1,5
Up Type=0
Dn Type=3
Dn Slope=0.005
Boundary for River Rch & Prof#=Buffalo Creek Tr,Reach-1,6
Up Type=0
Dn Type=3
Dn Slope=0.005
Boundary for River Rch & Prof#=Buffalo Creek Tr,Reach-1,7
Up Type=0
Dn Type=3
Dn Slope=0.005

--- Buffalo Creek Trib 12.g01 (geometry) ---

Geom Title=Existing Conditions
Program Version=4.10

River Reach=Buffalo Creek Tr,Reach-1
Reach XY= 30
        1283455.        6908938.      1283665.64      6908788.56
      1283854.91      6908930.71      1284044.31      6908838.74
      1284551.67      6909029.99      1284711.99      6908997.15
      1284791.25      6909174.52      1285111.13      6909286.22
      1285304.91      6909145.29      1285503.83      6909234.88
      1285608.51      6908689.25       1285797.6      6908591.43
      1285662.48      6908491.57      1285745.15      6908398.47
      1285929.03      6908410.65      1286044.25      6908687.32
      1286291.43      6908401.47      1286898.45      6907997.25
      1287415.44       6908076.9      1287399.17      6907885.16
      1287274.78      6907858.99      1287212.48      6907681.94
      1287401.59      6907495.82      1287671.48      6907571.87
      1288441.79      6906551.63      1288906.73      6906291.35
      1289038.98      6906337.75      1289257.45      6906232.53
      1289656.65      6905841.11        1289855.        6905988.

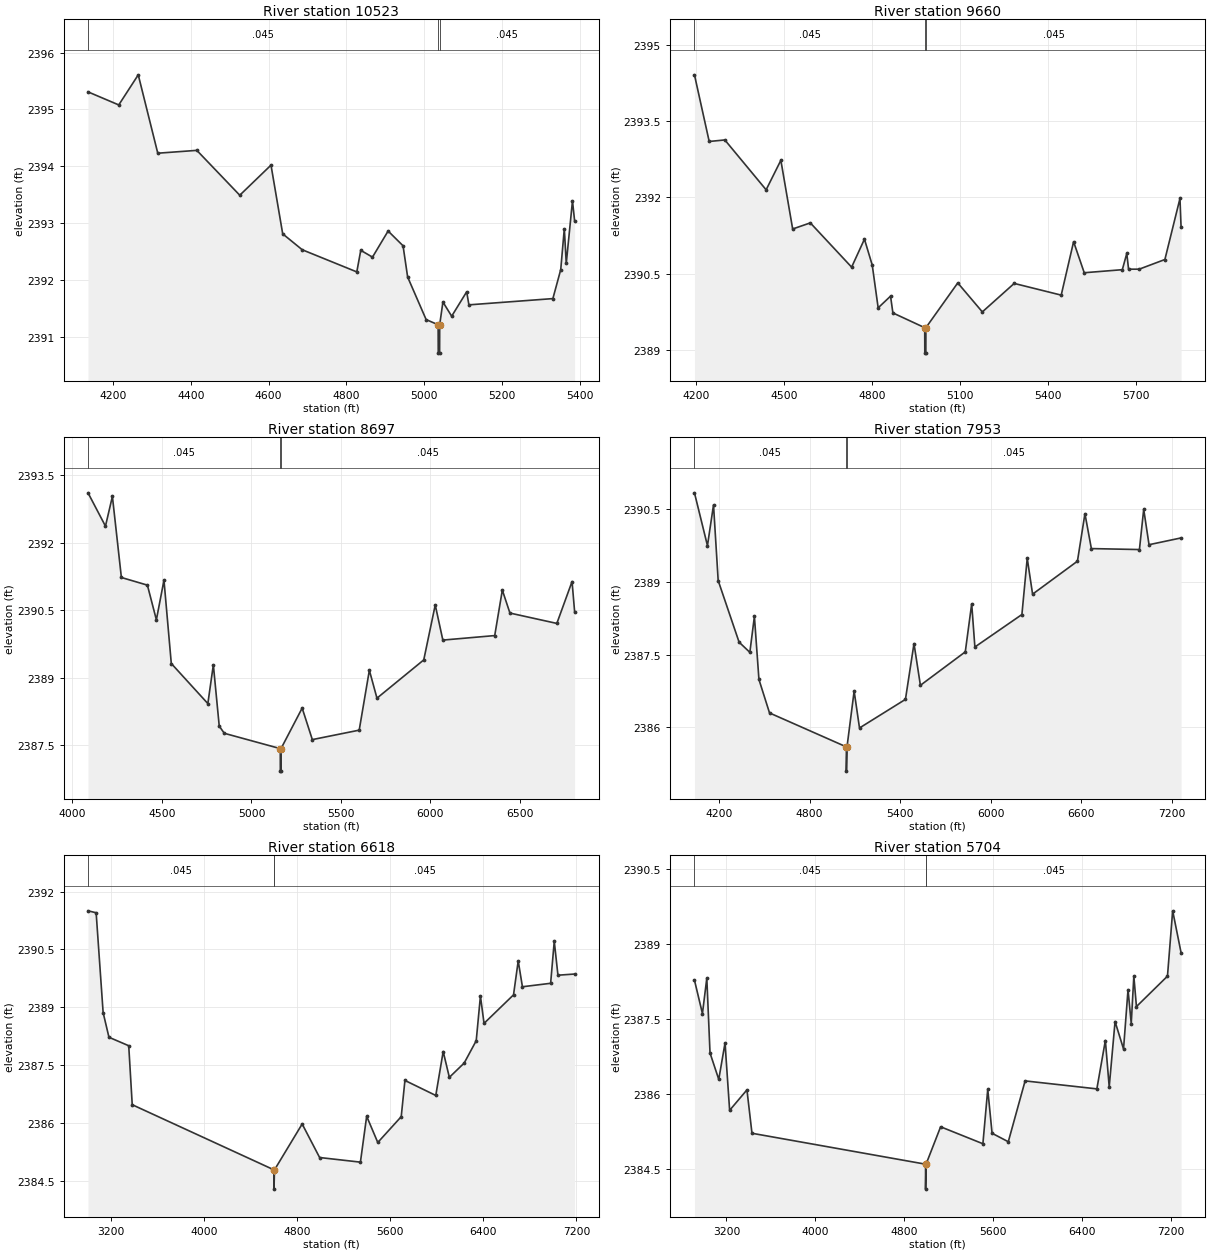
Type RM Length L Ch R = 1 ,10523   ,863,863,863
BEGIN DESCRIPTION:
Buffalo Creek Trib 12 9.0
END DESCRIPTION:
XS GIS Cut Line= 4
      1283579.32      6909706.76        1283505.        6908838.
       1283496.6      6908778.82      1283179.54       6908740.3
#Sta/Elev= 30
  4135.6 2395.31  4214.7 2395.08  4264.8 2395.61    4315 2394.23  4415.4 2394.28
  4525.8 2393.49  4606.1 2394.02  4636.2 2392.81  4686.4 2392.53  4826.7 2392.14
  4836.9 2392.52    4867  2392.4  4907.2 2392.86  4945.6  2392.6  4957.4 2392.05
    5005  2391.3  5035.8 2391.21  5036.1 2390.71  5039.6 2390.71  5039.8 2391.21
  5048.1 2391.61  5070.6 2391.36  5109.2 2391.79  5114.9 2391.56  5330.8 2391.67
    5351 2392.18  5360.2  2392.9  5365.2 2392.29  5381.2 2393.39  5386.7 2393.04
#Mann= 3 ,-1 , 0
  4135.6    .045       0  5035.8    .045       0  5039.8    .045       0
Bank Sta=5035.8,5039.8
XS Rating Curve= 0 ,0
Exp/Cntr=0.3,0.1

Type RM Length L Ch R = 1 ,9660    ,963,963,963
BEGIN DESCRIPTION:
Buffalo Creek Trib 12 8.0
END DESCRIPTION:
XS GIS Cut Line= 4
      1284114.04      6909731.07        1284205.        6908938.
       1284196.1      6908766.79      1283614.21      6908392.65
#Sta/Elev= 30
  4194.1 2394.41  4244.4  2393.1  4297.8 2393.13  4438.8 2392.15  4489.1 2392.73
  4529.4 2391.38  4589.7  2391.5  4730.7 2390.63  4774.5 2391.18  4801.1 2390.67
  4821.3 2389.83  4863.6 2390.06  4871.6 2389.73  4980.3 2389.44  4980.6 2388.94
  4984.1 2388.94  4984.3 2389.44  5093.1 2390.32    5177 2389.75  5285.8 2390.31
  5446.3 2390.08  5488.6 2391.13  5524.9 2390.52    5655 2390.58  5670.2  2390.9
  5676.3 2390.59  5712.5 2390.59  5800.3 2390.78  5851.8 2391.98  5855.6 2391.41
#Mann= 3 ,-1 , 0
  4194.1    .045       0  4980.3    .045       0  4984.3    .045       0
Bank Sta=4980.3,4984.3
XS Rating Curve= 0 ,0
Exp/Cntr=0.3,0.1

Type RM Length L Ch R = 1 ,8697    ,744,744,744
BEGIN DESCRIPTION:
Buffalo Creek Trib 12 7.5
END DESCRIPTION:
XS GIS Cut Line= 4
      1284701.71      6910063.56      1284885.78      6909176.08
       1284924.4      6909016.36      1283714.73      6907897.74
#Sta/Elev= 30
    4087 2393.11  4184.6 2392.37  4223.3 2393.03  4273.5 2391.23  4418.8 2391.06
    4469 2390.29  4511.4 2391.17  4552.3 2389.32  4756.5 2388.43  4787.2 2389.29
  4820.1 2387.93  4848.4 2387.77  5161.1 2387.43  5161.4 2386.93    5165 2386.93
  5165.2 2387.43  5283.4 2388.33  5340.1 2387.63    5602 2387.84  5658.7 2389.17
  5701.2 2388.55  5962.6  2389.4  6026.7 2390.62  6069.2 2389.84    6359 2389.94
  6401.5 2390.95    6444 2390.44    6706 2390.21    6791 2391.14  6805.3 2390.47
#Mann= 3 ,-1 , 0
    4087    .045       0  5161.1    .045       0  5165.2    .045       0
Bank Sta=5161.1,5165.2
XS Rating Curve= 0 ,0
Exp/Cntr=0.3,0.1

Type RM Length L Ch R = 1 ,7953    ,1335,1335,1335
BEGIN DESCRIPTION:
Buffalo Creek Trib 12 7.0
END DESCRIPTION:
XS GIS Cut Line= 3
      1285439.56      6910193.77        1285505.        6909238.
      1283930.02      6907613.02
#Sta/Elev= 30
  4038.3 2390.84  4124.3 2389.75  4164.4 2390.59  4195.3 2389.03  4333.7 2387.76
  4404.9 2387.55    4435 2388.29  4465.1 2386.99  4535.2  2386.3  5043.7  2385.6
    5044  2385.1    5048  2385.6  5095.2 2386.75  5130.7 2385.99  5434.8 2386.58
  5491.4 2387.73  5533.8 2386.87  5830.9 2387.56  5873.3 2388.55  5894.4 2387.66
  6205.7 2388.33  6240.9 2389.49  6276.4 2388.75  6573.3 2389.43  6622.9 2390.41
  6665.4 2389.69  6983.6 2389.67  7011.9  2390.5  7047.1 2389.77  7259.3 2389.91
#Mann= 3 ,-1 , 0
  4038.3    .045       0  5043.7    .045       0    5048    .045       0
Bank Sta=5043.7,5048
XS Rating Curve= 0 ,0
Exp/Cntr=0.3,0.1

Type RM Length L Ch R = 1 ,6618    ,914,914,914
BEGIN DESCRIPTION:
Buffalo Creek Trib 12 6.0
END DESCRIPTION:
XS GIS Cut Line= 4
        1285905.      6910388.02        1285905.        6908388.
      1285894.62      6908237.58      1283979.97      6907562.99
#Sta/Elev= 30
    3004  2391.5    3074 2391.45    3134 2388.86    3184 2388.22    3354    2388
    3384 2386.47  4601.8 2384.78  4602.1 2384.28  4606.2 2384.78    4844 2385.97
    4994  2385.1  5344.5 2384.98  5398.2 2386.17  5493.7 2385.49  5695.1 2386.16
  5726.9  2387.1    5992 2386.71  6055.6 2387.85  6108.6 2387.18  6235.8 2387.55
  6339.4 2388.13  6375.6 2389.29  6406.6 2388.58  6659.9 2389.32  6700.2  2390.2
  6736.4 2389.53  6978.7 2389.62  7009.8 2390.71  7041.6 2389.83  7184.8 2389.86
#Mann= 3 ,-1 , 0
    3004    .045       0  4601.8    .045       0  4606.2    .045       0
Bank Sta=4601.8,4606.2
XS Rating Curve= 0 ,0
Exp/Cntr=0.3,0.1

Type RM Length L Ch R = 1 ,5704    ,454,454,454
BEGIN DESCRIPTION:
Buffalo Creek Trib 12 5.0
END DESCRIPTION:
XS GIS Cut Line= 4
      1286969.17       6910352.8        1286405.        6908338.
      1286366.84      6908168.14      1284430.39      6907322.83
#Sta/Elev= 30
  2912.3 2388.28  2984.1 2387.61  3023.4 2388.32  3052.3 2386.82    3131 2386.29
  3187.3 2387.02  3228.8 2385.67  3384.6 2386.08  3429.9 2385.21  4991.9 2384.59
  4992.2 2384.09  4996.5 2384.59  5127.6 2385.34    5508    2385  5551.7 2386.09
  5590.7 2385.21  5736.6 2385.04  5887.9 2386.26  6533.7  2386.1  6610.1 2387.07
  6644.8 2386.14  6697.4 2387.45  6773.7  2386.9  6814.1 2388.09    6843 2387.41
  6866.4 2388.36  6889.8 2387.75  7169.1 2388.36  7215.9 2389.67  7291.6 2388.83
#Mann= 3 ,-1 , 0
  2912.3    .045       0  4991.9    .045       0  4996.5    .045       0
Bank Sta=4991.9,4996.5
XS Rating Curve= 0 ,0
Exp/Cntr=0.3,0.1

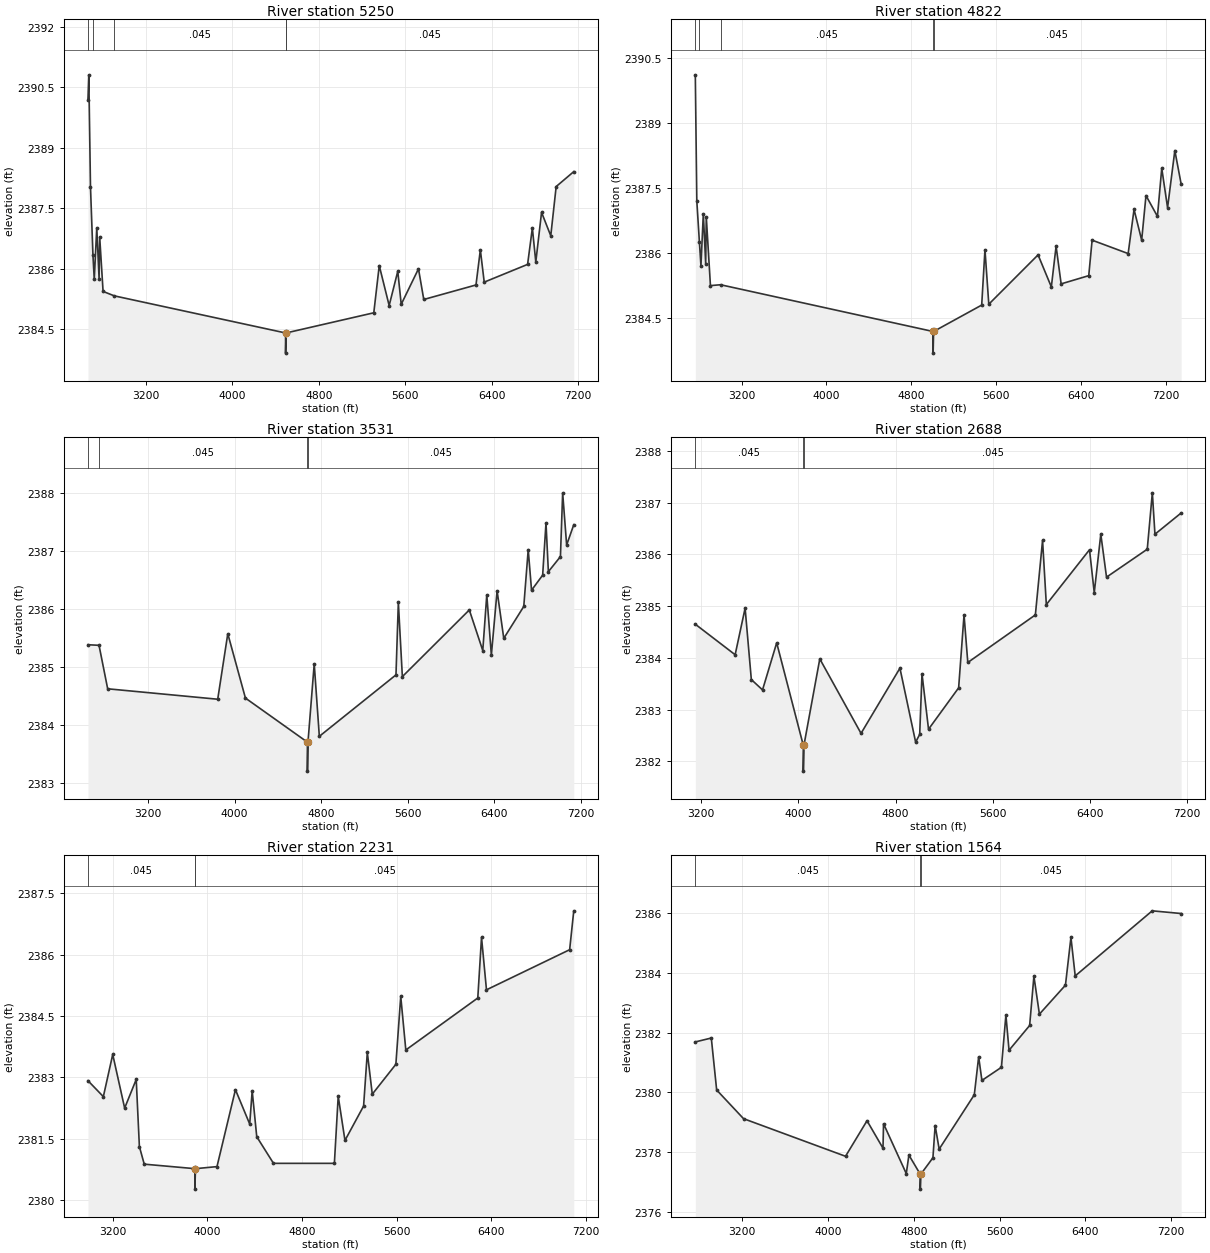
Type RM Length L Ch R = 1 ,5250    ,428,428,428
BEGIN DESCRIPTION:
Buffalo Creek Trib 12 4.0
END DESCRIPTION:
XS GIS Cut Line= 4
      1287954.98      6910137.97        1286755.        6908138.
      1286575.17      6908001.47      1284754.95      6907337.98
#Sta/Elev= 30
  2663.1 2390.19  2670.8 2390.81  2686.4 2388.04  2709.3 2386.34  2721.4 2385.74
  2744.7 2387.02  2766.1 2385.76  2771.9 2386.78    2803 2385.44  2906.5 2385.33
  4491.6 2384.41  4491.9 2383.91  4496.4 2384.41  5308.1 2384.91  5358.6 2386.08
  5450.3 2385.09  5530.1 2385.94  5561.9 2385.12  5721.7    2386  5770.6 2385.24
  6253.8  2385.6  6294.1 2386.47    6330 2385.67  6731.3 2386.11  6775.4 2387.01
  6807.3 2386.17  6860.5  2387.4  6945.7 2386.82  6995.8 2388.04  7158.6 2388.41
#Mann= 5 ,-1 , 0
  2663.1     .07       0  2709.3    .035       0  2906.5    .045       0
  4491.6    .045       0  4496.4    .045       0
Bank Sta=4491.6,4496.4
XS Rating Curve= 0 ,0
Exp/Cntr=0.3,0.1

Type RM Length L Ch R = 1 ,4822    ,1291,1291,1291
BEGIN DESCRIPTION:
Buffalo Creek Trib 12 3.0
END DESCRIPTION:
XS GIS Cut Line= 4
      1288055.01      6910038.01        1287055.        6908038.
      1286929.34      6907800.08      1284974.59       6907102.9
#Sta/Elev= 30
    2764 2390.12    2778 2387.21  2802.7 2386.25  2817.1 2385.71  2839.5 2386.91
  2861.8 2385.76  2867.4 2386.84  2906.6 2385.25    3002 2385.27  5005.8 2384.19
  5006.2 2383.69  5010.7 2384.19  5464.2  2384.8    5495 2386.08  5531.1 2384.82
  5995.7 2385.96  6120.8 2385.22  6165.6 2386.16  6213.2 2385.29  6473.5 2385.48
  6505.3  2386.3  6845.1 2385.99  6900.6 2387.01  6972.5  2386.3  7013.2 2387.33
  7121.1 2386.85  7161.9 2387.96  7216.7 2387.05  7285.2 2388.37  7344.5  2387.6
#Mann= 5 ,-1 , 0
    2764     .07       0  2802.7    .035       0    3002    .045       0
  5005.8    .045       0  5010.7    .045       0
Bank Sta=5005.8,5010.7
XS Rating Curve= 0 ,0
Exp/Cntr=0.3,0.1

Type RM Length L Ch R = 1 ,3531    ,843,843,843
BEGIN DESCRIPTION:
Buffalo Creek Trib 12 2.0
END DESCRIPTION:
XS GIS Cut Line= 4
       1288234.8      6909701.79        1287405.        6907488.
      1287290.45      6907334.81      1285405.05      6906888.01
#Sta/Elev= 30
  2644.2 2385.39  2746.6 2385.38  2826.6 2384.63  3844.3 2384.45  3937.5 2385.58
  4100.6 2384.47  4673.7 2383.71  4674.1 2383.21  4679.1 2383.71  4736.9 2385.06
  4784.1 2383.81    5493 2384.87  5514.9 2386.12    5552 2384.84  6171.3 2385.99
  6295.7 2385.29  6332.8 2386.25  6375.1 2385.21  6428.2 2386.32  6489.9  2385.5
  6674.9 2386.05    6716 2387.03  6746.8 2386.33  6849.6 2386.59  6880.4 2387.49
  6902.5 2386.65    7014 2386.91  7034.6 2388.01  7071.4 2387.11  7137.3 2387.46
#Mann= 4 ,-1 , 0
  2644.2    .035       0  2746.6    .045       0  4673.7    .045       0
  4679.1    .045       0
Bank Sta=4673.7,4679.1
XS Rating Curve= 0 ,0
Exp/Cntr=0.3,0.1

Type RM Length L Ch R = 1 ,2688    ,457,457,457
BEGIN DESCRIPTION:
Buffalo Creek Trib 12 1.0
END DESCRIPTION:
XS GIS Cut Line= 3
      1288355.01      6908988.03        1287955.        6907188.
        1285955.        6906388.
#Sta/Elev= 30
  3151.5 2384.65  3479.3 2384.06  3561.3 2384.96  3612.5 2383.58  3704.7 2383.38
  3821.2 2384.29    4040 2382.31  4040.5 2381.81  4045.5 2382.31  4175.9 2383.98
  4515.3 2382.54  4835.4  2383.8  4964.7 2382.37  4998.1 2382.52    5017 2383.69
  5070.8 2382.62  5318.5 2383.42    5363 2384.83  5393.9 2383.91    5950 2384.83
  6009.2 2386.27  6040.2 2385.03  6395.6 2386.09  6434.6 2385.26  6488.5 2386.39
  6535.6 2385.56  6870.8  2386.1  6912.6 2387.19  6934.1 2386.39  7149.5  2386.8
#Mann= 3 ,-1 , 0
  3151.5    .045       0    4040    .045       0  4045.5    .045       0
#XS Ineff= 2 , 0
       0                  4175.9       0 2383.98
Permanent Ineff=
       F       F
Bank Sta=4040,4045.5
XS Rating Curve= 0 ,0
Exp/Cntr=0.3,0.1

Type RM Length L Ch R = 1 ,2231    ,667,667,667
BEGIN DESCRIPTION:
Buffalo Creek Trib 12 0.9
END DESCRIPTION:
XS GIS Cut Line= 3
      1288647.48      6908792.27      1288219.76      6906851.07
      1286201.81      6906214.97
#Sta/Elev= 30
    2992 2382.92    3122 2382.53  3201.2 2383.56    3302 2382.25  3399.7 2382.95
  3426.4 2381.31  3467.4 2380.88  3894.7 2380.77  3895.2 2380.27  3900.2 2380.77
  4081.8 2380.82  4237.8  2382.7  4358.3 2381.86  4379.2 2382.67  4417.8 2381.55
  4559.2  2380.9  5073.5  2380.9  5105.9 2382.54    5163 2381.46  5320.3  2382.3
  5351.7 2383.61  5393.7 2382.59  5592.9 2383.32  5634.1 2384.98  5676.9 2383.67
  6284.9 2384.94  6316.4 2386.42  6358.3 2385.14  7060.8 2386.12  7095.6 2387.07
#Mann= 3 ,-1 , 0
    2992    .045       0  3894.7    .045       0  3900.2    .045       0
#XS Ineff= 2 , 0
       0                  4237.8       0  2382.7
Permanent Ineff=
       F       F
Bank Sta=3894.7,3900.2
XS Rating Curve= 0 ,0
Exp/Cntr=0.3,0.1

Type RM Length L Ch R = 1 ,1564    ,137,137,137
BEGIN DESCRIPTION:
Buffalo Creek Trib 12 0.7
END DESCRIPTION:
XS GIS Cut Line= 5
      1288811.98      6908616.79      1288714.03      6906524.33
      1288638.85      6906403.93        1288530.        6906363.
      1286378.64      6906039.71
#Sta/Elev= 30
  2763.3 2381.69  2912.3 2381.82  2962.3 2380.08  3212.6 2379.12  4163.6 2377.86
  4363.8 2379.05  4512.8 2378.13  4517.8 2378.95  4729.8 2377.28  4754.3  2377.9
  4859.9 2377.26  4860.3 2376.76  4865.4 2377.26  4978.2 2377.81  4998.9 2378.89
  5036.3  2378.1    5364 2379.92  5404.5 2381.19  5434.8  2380.4  5616.8 2380.84
  5658.5 2382.59  5687.6 2381.41  5879.8 2382.24  5919.5 2383.89  5970.8 2382.62
  6213.5 2383.59  6264.7 2385.19  6304.5  2383.9  7022.5 2386.08  7291.8 2385.99
#Mann= 3 ,-1 , 0
  2763.3    .045       0  4859.9    .045       0  4865.4    .045       0
#XS Ineff= 2 , 0
       0  4517.8 2378.95               0
Permanent Ineff=
       F       F
Bank Sta=4859.9,4865.4
XS Rating Curve= 0 ,0
Exp/Cntr=0.3,0.1

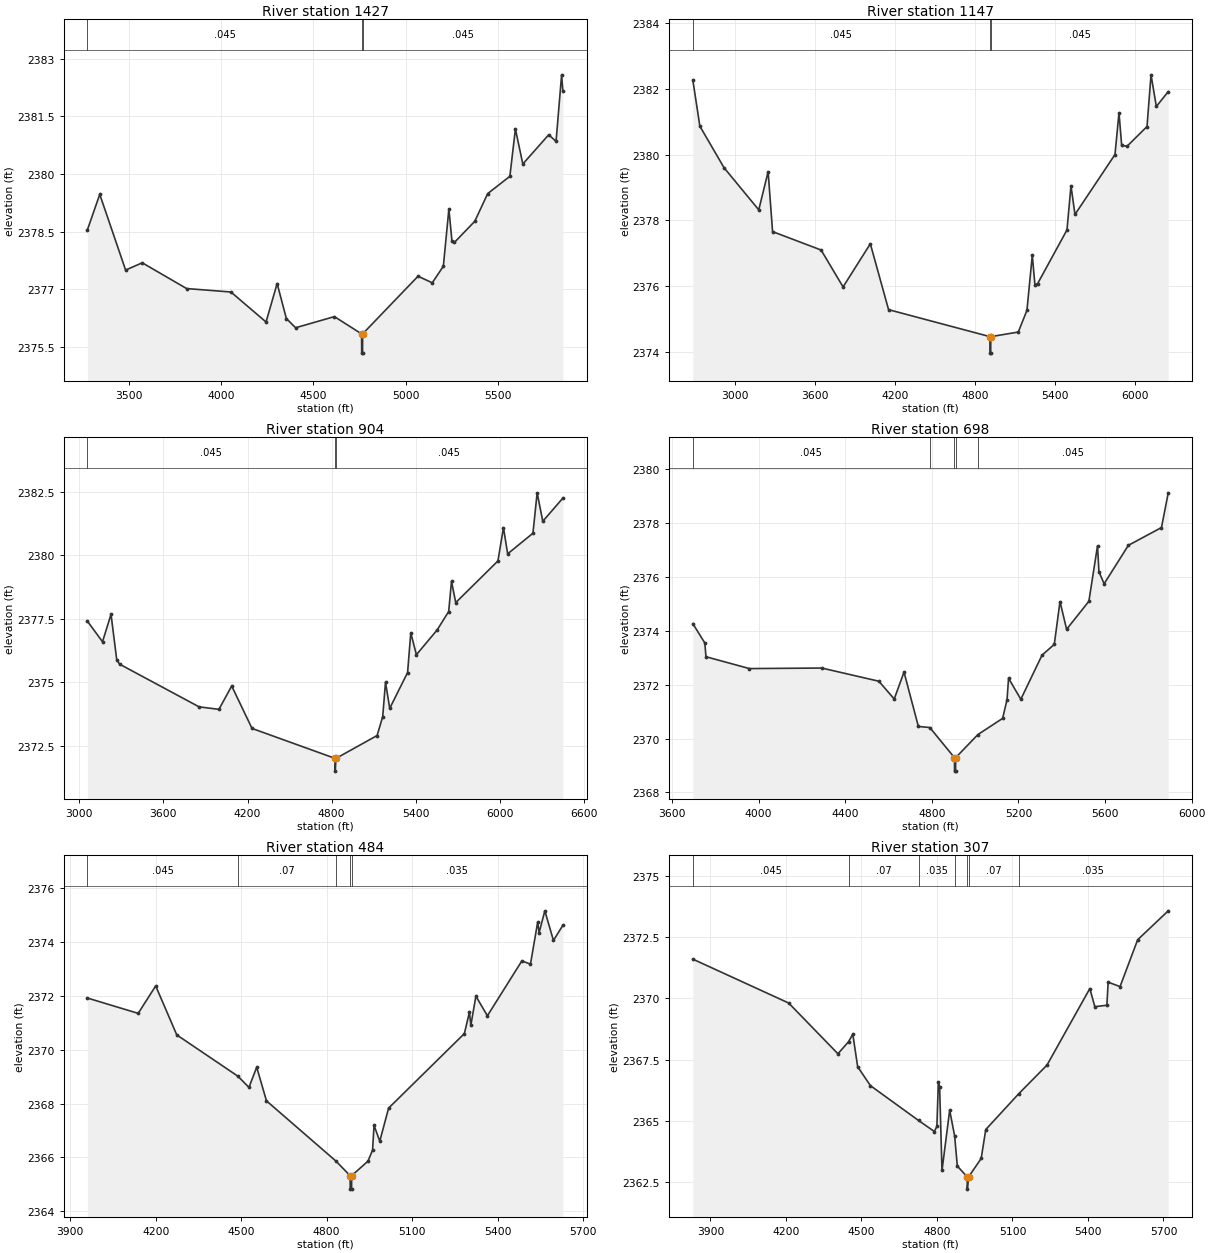
Type RM Length L Ch R = 1 ,1427    ,280,280,280
BEGIN DESCRIPTION:
Buffalo Creek Trib 12 0.45
END DESCRIPTION:
XS GIS Cut Line= 4
      1288851.77      6908064.68      1288881.95      6906555.81
      1288700.88       6906266.1      1287978.33      6906248.03
#Sta/Elev= 30
  3276.5 2378.55  3343.2 2379.47  3483.2  2377.5  3573.2 2377.69  3813.3 2377.02
  4053.3 2376.93  4243.4 2376.15  4303.4 2377.15  4353.4 2376.24  4403.4    2376
  4613.4 2376.29  4760.7 2375.84  4761.2 2375.34  4765.8 2375.34  4766.2 2375.84
  5066.1 2377.34  5143.2 2377.17  5203.2  2377.6  5233.2 2379.09  5249.7 2378.26
  5263.2 2378.22  5373.3 2378.77  5443.3 2379.49  5563.3 2379.94  5593.3 2381.17
  5633.4 2380.26  5773.4 2381.02  5813.4 2380.85  5843.4 2382.58  5850.1 2382.17
#Mann= 3 ,-1 , 0
  3276.5    .045       0  4760.7    .045       0  4766.2    .045       0
Bank Sta=4760.7,4766.2
XS Rating Curve= 0 ,0
Exp/Cntr=0.3,0.1

Type RM Length L Ch R = 1 ,1147    ,243,243,243
BEGIN DESCRIPTION:
Buffalo Creek Trib 12 0.35
END DESCRIPTION:
XS GIS Cut Line= 4
      1288851.23      6908640.61        1289030.        6906463.
        1288980.        6906213.      1287855.92      6906235.92
#Sta/Elev= 30
  2682.7 2382.26  2735.5 2380.86  2916.6  2379.6    3177 2378.32  3247.2 2379.48
  3280.5 2377.66  3644.5  2377.1  3809.1 2375.98  4013.4 2377.29  4150.2 2375.29
  4910.8 2374.47  4911.2 2373.97  4915.8 2373.97  4916.3 2374.47  5122.6 2374.61
  5187.6 2375.27  5227.6 2376.94  5247.6 2376.04  5267.6 2376.08  5487.7 2377.71
  5517.7 2379.05  5547.7 2378.18  5847.7    2380  5877.7 2381.27  5897.7 2380.28
  5937.8 2380.25  6087.8 2380.85  6117.8 2382.42  6157.8 2381.46  6246.9 2381.91
#Mann= 3 ,-1 , 0
  2682.7    .045       0  4910.8    .045       0  4916.3    .045       0
Bank Sta=4910.8,4916.3
XS Rating Curve= 0 ,0
Exp/Cntr=0.3,0.1

Type RM Length L Ch R = 1 ,904     ,206,206,206
BEGIN DESCRIPTION:
Buffalo Creek Trib 12 0.5
END DESCRIPTION:
XS GIS Cut Line= 4
      1289009.39      6908134.17      1289279.97      6906399.77
      1289139.35      6906151.51      1287792.05      6906214.98
#Sta/Elev= 30
  3058.8  2377.4  3166.3 2376.59    3227 2377.67  3267.5 2375.89  3287.7 2375.71
  3854.5 2374.03  3996.2 2373.93  4087.3 2374.85  4232.2 2373.18    4825    2372
  4825.4  2371.5  4830.5    2372  5123.9  2372.9  5163.9 2373.64  5183.9    2375
    5214 2373.97  5341.4 2375.38  5364.1 2376.94  5404.2 2376.08  5552.8 2377.06
  5634.4 2377.78  5654.5 2378.97  5684.5 2378.13  5985.5 2379.77  6024.9 2381.08
  6054.9 2380.05  6235.1 2380.86  6265.1 2382.45  6305.2 2381.33  6448.3 2382.24
#Mann= 3 ,-1 , 0
  3058.8    .045       0    4825    .045       0  4830.5    .045       0
Bank Sta=4825,4830.5
XS Rating Curve= 0 ,0
Exp/Cntr=0.3,0.1

Type RM Length L Ch R = 1 ,698     ,214,214,214
BEGIN DESCRIPTION:
Buffalo Creek Trib 12 0.25
END DESCRIPTION:
XS GIS Cut Line= 4
      1289220.59      6907405.73      1289416.77      6906221.75
      1289300.45       6906065.5      1288514.32      6905911.92
#Sta/Elev= 30
  3695.9 2374.27  3751.4 2373.55  3756.5 2373.04  3957.1  2372.6  4291.6 2372.62
  4555.2 2372.13  4626.1 2371.47  4671.4 2372.47  4737.6 2370.45  4790.4 2370.41
  4904.4 2369.29  4904.8 2368.79  4909.4 2368.79  4909.9 2369.29  5012.9 2370.15
  5126.9 2370.75  5147.3 2371.45  5154.2 2372.24  5210.9 2371.46  5308.9  2373.1
  5365.5  2373.5  5391.8 2375.09  5422.4 2374.06  5525.2  2375.1  5565.1 2377.16
  5571.7  2376.2  5595.6 2375.75  5707.7 2377.18  5860.5 2377.84  5891.8 2379.13
#Mann= 5 ,-1 , 0
  3695.9    .045       0  4790.4     .07       0  4904.4     .07       0
  4909.9     .07       0  5012.9    .045       0
Bank Sta=4904.4,4909.9
XS Rating Curve= 0 ,0
Exp/Cntr=0.3,0.1

Type RM Length L Ch R = 1 ,484     ,177,177,177
BEGIN DESCRIPTION:
Buffalo Creek Trib 12 0.3
END DESCRIPTION:
XS GIS Cut Line= 4
      1289424.52      6906912.09      1289618.18      6906013.52
        1289330.      6905938.94      1288882.31      6905881.83
#Sta/Elev= 30
  3960.5 2371.92  4138.6 2371.35    4200 2372.37    4274 2370.55  4487.9 2369.02
  4527.3  2368.6  4554.5 2369.35  4588.7  2368.1  4832.7 2365.86  4882.2 2365.32
  4882.7 2364.82  4887.3 2364.82  4887.7 2365.32    4945 2365.86    4961 2366.27
  4966.2 2367.19  4986.3  2366.6  5017.3 2367.83  5283.2  2370.6  5300.8 2371.39
  5305.9 2370.91  5323.6 2371.99  5363.9 2371.26  5484.9  2373.3  5515.1 2373.18
  5540.4 2374.74  5545.4 2374.35  5565.5 2375.16  5595.7 2374.06  5628.7 2374.62
#Mann= 5 ,-1 , 0
  3960.5    .045       0  4487.9     .07       0  4832.7    .035       0
  4882.2    .035       0  4887.7    .035       0
Bank Sta=4882.2,4887.7
XS Rating Curve= 0 ,0
Exp/Cntr=0.3,0.1

Type RM Length L Ch R = 1 ,307     ,0,0,0
BEGIN DESCRIPTION:
Buffalo Creek Trib 12 0.4
END DESCRIPTION:
XS GIS Cut Line= 4
        1289530.      6906962.99      1289715.69      6905912.89
        1289480.        6905813.      1288913.55       6905795.6
#Sta/Elev= 30
  3829.8  2371.6  4210.6 2369.81  4406.4 2367.74  4448.4 2368.23  4465.5 2368.54
  4484.8 2367.21  4535.6 2366.44  4726.7 2365.02  4789.5 2364.57  4799.6 2364.78
  4805.4 2366.59  4810.5 2366.37  4819.9 2362.98  4850.4 2365.44  4870.1 2364.39
  4880.8 2363.16  4920.1 2362.72  4920.5 2362.22  4925.6 2362.72  4975.6 2363.47
  4993.8 2364.65  5123.9  2366.1  5237.2 2367.28  5407.3  2370.4  5427.3 2369.66
  5475.1 2369.72  5480.1 2370.66  5527.4 2370.48  5597.4 2372.39  5718.9 2373.57
#Mann= 7 ,-1 , 0
  3829.8    .045       0  4448.4     .07       0  4726.7    .035       0
  4870.1     .07       0  4920.1     .07       0  4925.6     .07       0
  5123.9    .035       0
Bank Sta=4920.1,4925.6
XS Rating Curve= 0 ,0
Exp/Cntr=0.3,0.1

Chan Stop Cuts=-1
Use User Specified Reach Order=0
Composite Channel Slope=5