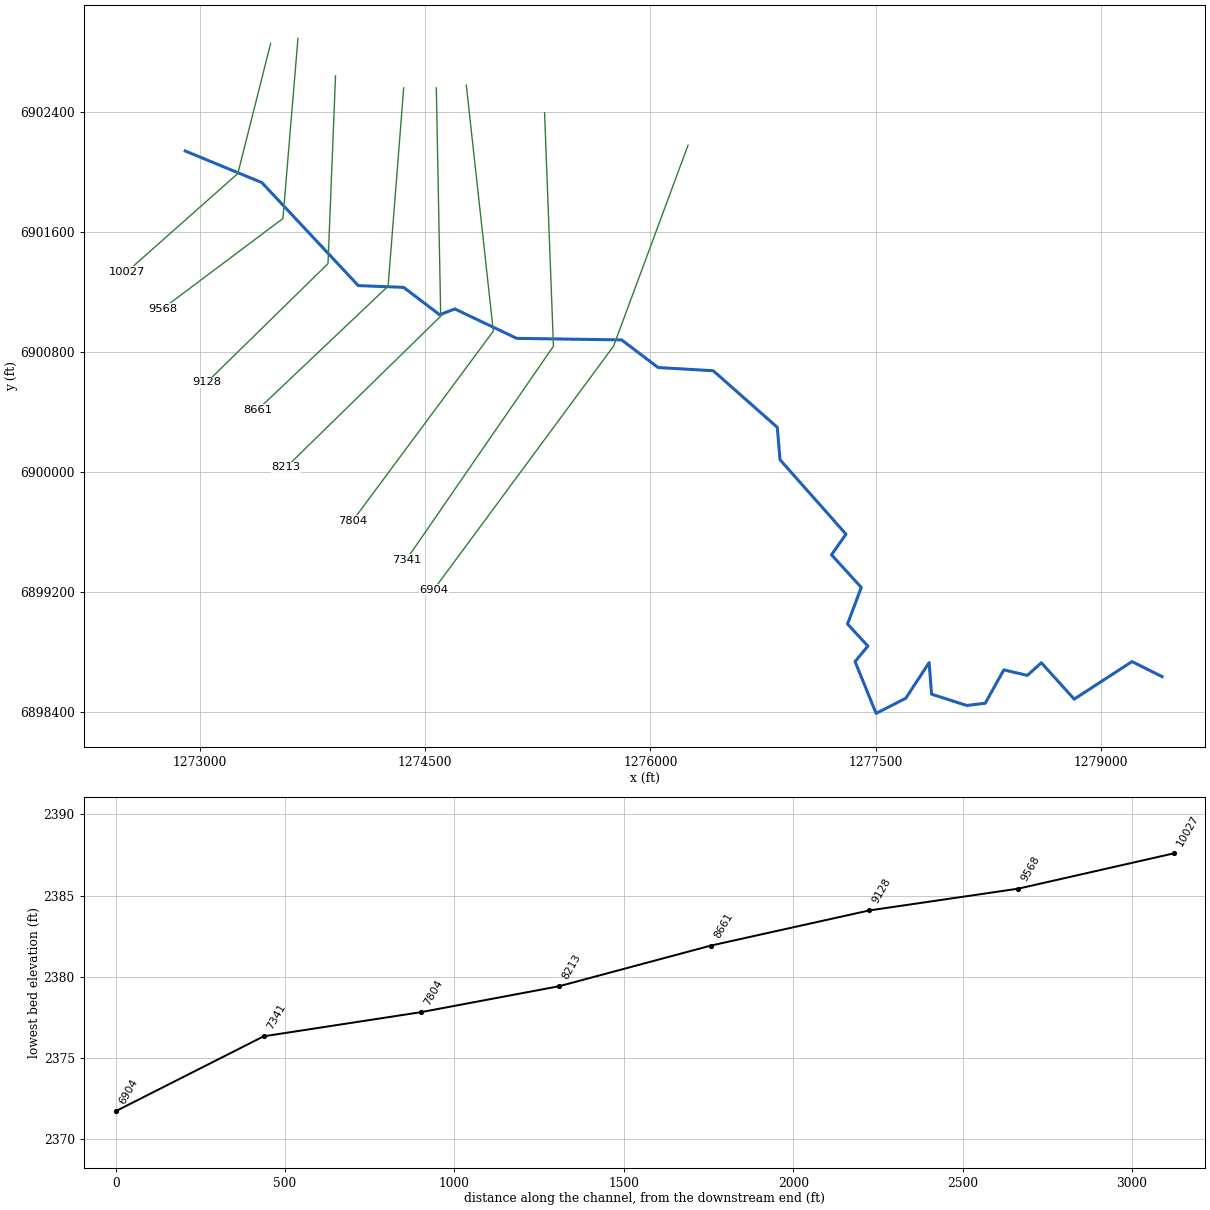
--- Buffalo Creek Trib 15.prj (project) ---

Proj Title=Buffalo Creek Trib 15 Base Level Engineering
Current Plan=p01
Default Exp/Contr=0.3,0.1
English Units
Geom File=g01
Flow File=f01
Plan File=p01
BEGIN DESCRIPTION:
Buffalo Creek Trib 15
END DESCRIPTION:

--- Buffalo Creek Trib 15.p01 (plan) ---

Plan Title=Multiple Run
Short Identifier=Multiple
Geom File=g01
Flow File=f01
Subcritical Flow
K Sum by GR= 0
Std Step Tol= 0.01
Critical Tol= 0.01
Num of Std Step Trials= 20
Max Error Tol= 0.3
Flow Tol Ratio= 0.001
Split Flow NTrial= 30
Split Flow Tol= 0.02
Split Flow Ratio= 0.02
Log Output Level= 0
Friction Slope Method= 1
Unsteady Friction Slope Method= 2
Unsteady Bridges Friction Slope Method= 1
Parabolic Critical Depth
Global Vel Dist=  1 , 1 , 1
Global Log Level= 0
CheckData=True
Encroach Param= -1, 0, 0, 0
BEGIN DESCRIPTION:
Multiple Run
END DESCRIPTION:

--- Buffalo Creek Trib 15.f01 (steady flow) ---

Flow Title=Multiple
Number of Profiles=7
Profile Names=10-year,25-year,50-year,1pct_min,100-year,1pct_plu,500-year
River Rch & RM= Buffalo Creek Tr,Reach-1,10027
     253     349     428     260     519    1035     774
Boundary for River Rch & Prof#=Buffalo Creek Tr,Reach-1,1
Up Type=0
Dn Type=3
Dn Slope=0.005
Boundary for River Rch & Prof#=Buffalo Creek Tr,Reach-1,2
Up Type=0
Dn Type=3
Dn Slope=0.005
Boundary for River Rch & Prof#=Buffalo Creek Tr,Reach-1,3
Up Type=0
Dn Type=3
Dn Slope=0.005
Boundary for River Rch & Prof#=Buffalo Creek Tr,Reach-1,4
Up Type=0
Dn Type=3
Dn Slope=0.005
Boundary for River Rch & Prof#=Buffalo Creek Tr,Reach-1,5
Up Type=0
Dn Type=3
Dn Slope=0.005
Boundary for River Rch & Prof#=Buffalo Creek Tr,Reach-1,6
Up Type=0
Dn Type=3
Dn Slope=0.005
Boundary for River Rch & Prof#=Buffalo Creek Tr,Reach-1,7
Up Type=0
Dn Type=3
Dn Slope=0.005

--- Buffalo Creek Trib 15.g01 (geometry) ---

Geom Title=Existing Conditions

River Reach=Buffalo Creek Tr,Reach-1
Reach XY= 30
      1272905.00      6902138.00      1273414.81      6901927.49
      1274056.47      6901241.55      1274358.23      6901229.76
      1274598.27      6901047.15      1274698.87      6901086.16
      1275110.85      6900890.08      1275808.32      6900879.96
      1276051.66      6900695.99      1276418.57      6900674.53
      1276844.52      6900297.85      1276862.81      6900081.81
      1277301.91      6899586.33      1277205.39      6899449.02
      1277403.35      6899231.95      1277312.10      6898988.00
      1277447.39      6898841.33      1277362.11      6898738.01
      1277502.17      6898393.06      1277699.38      6898493.62
      1277855.03      6898731.12      1277871.10      6898520.83
      1278105.10      6898445.78      1278228.34      6898460.51
      1278352.03      6898682.60      1278508.42      6898645.83
      1278601.59      6898730.20      1278820.32      6898487.95
      1279205.00      6898738.00      1279405.00      6898638.00

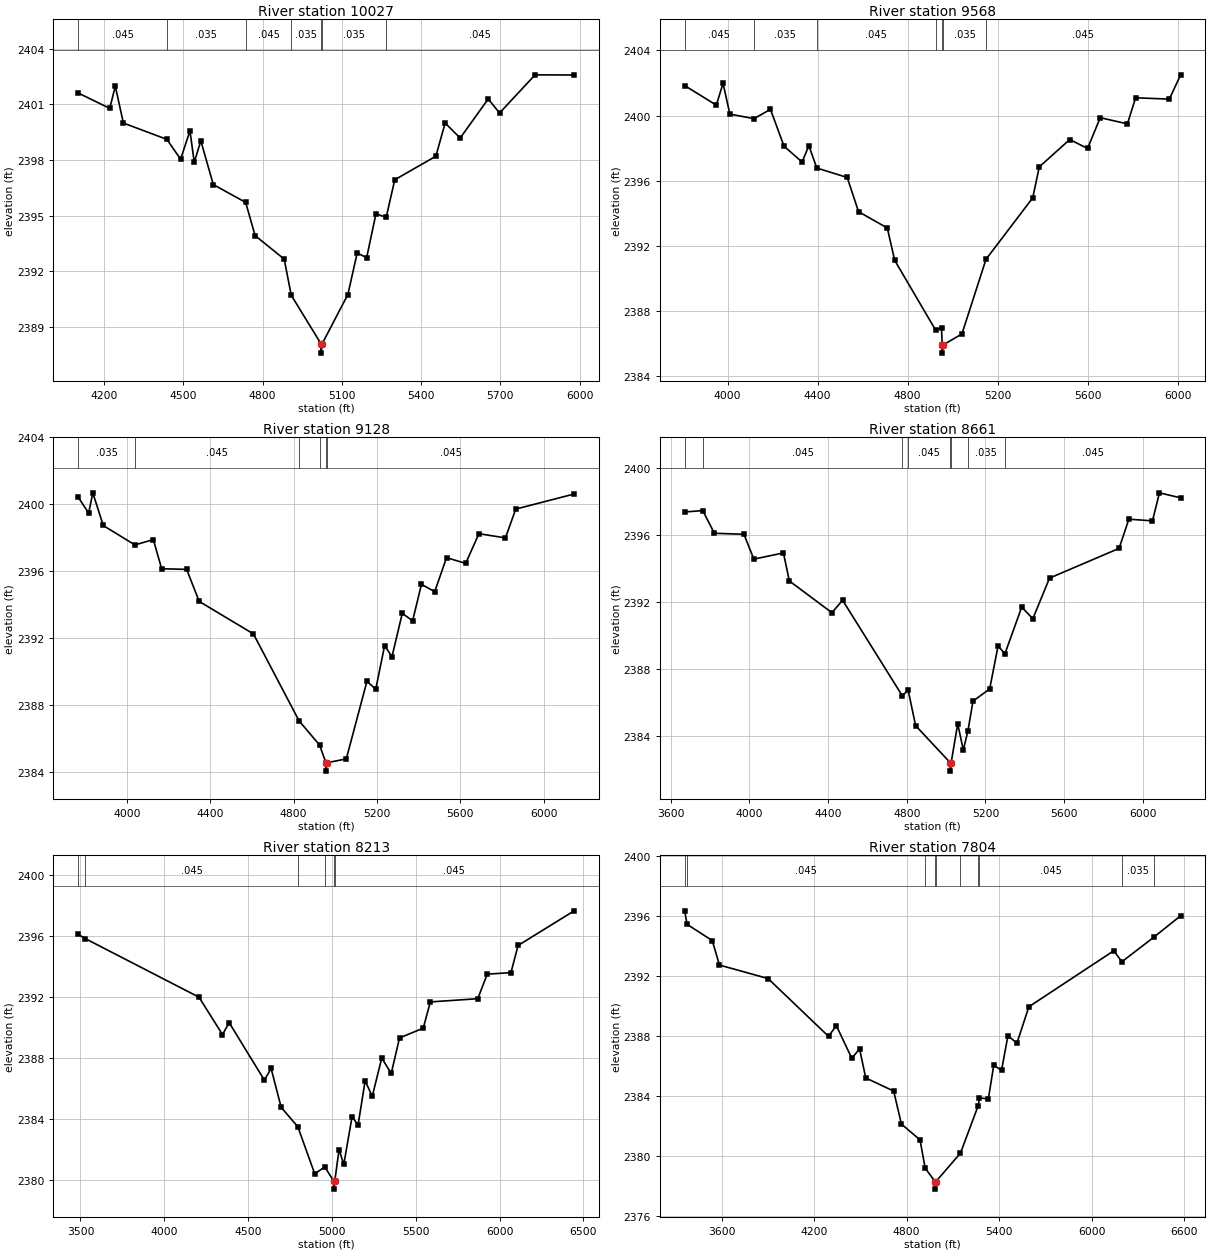
Type RM Length L Ch R = 1,10027,459,459,459
BEGIN DESCRIPTION:
Buffalo Creek Trib 15 13.0
END DESCRIPTION:
XS GIS Cut Line= 3
      1273473.17      6902853.64      1273255.00      6901988.00
      1272519.16      6901335.32
#Sta/Elev= 30
  4102.6 2401.62  4221.9 2400.79  4243.0 2401.99  4273.4 2400.00  4437.9 2399.12
  4490.0 2398.05  4525.4 2399.58  4541.6 2397.88  4566.5 2399.04  4613.7 2396.68
  4736.1 2395.72  4771.9 2393.93  4881.9 2392.66  4908.6 2390.71  5021.3 2388.09
  5021.6 2387.59  5025.3 2388.09  5122.8 2390.75  5158.0 2392.99  5193.9 2392.74
  5229.1 2395.11  5267.7 2394.91  5300.2 2396.94  5455.7 2398.21  5490.8 2400.00
  5547.7 2399.19  5653.9 2401.30  5696.6 2400.54  5831.2 2402.60  5978.9 2402.59
#Mann=7,-1,0
  4102.6   0.045       0  4437.9   0.035       0  4736.1   0.045       0
  4908.6   0.035       0  5021.3   0.035       0  5025.3   0.035       0
  5267.7   0.045       0
Bank Sta=5021.3,5025.3
Exp/Cntr=0.3,0.1

Type RM Length L Ch R = 1,9568,440,440,440
BEGIN DESCRIPTION:
Buffalo Creek Trib 15 12.0
END DESCRIPTION:
XS GIS Cut Line= 3
      1273655.00      6902888.01      1273555.00      6901688.00
      1272754.97      6901087.98
#Sta/Elev= 30
  3809.2 2401.84  3949.7 2400.64  3979.8 2401.98  4009.9 2400.09  4117.0 2399.81
  4190.5 2400.38  4250.7 2398.12  4331.0 2397.15  4361.1 2398.15  4396.5 2396.78
  4531.7 2396.20  4581.9 2394.10  4709.8 2393.10  4742.4 2391.12  4924.2 2386.84
  4950.7 2386.99  4953.6 2385.92  4953.9 2385.42  4957.8 2385.92  5041.5 2386.60
  5148.5 2391.18  5356.1 2394.95  5385.2 2396.85  5520.7 2398.53  5599.8 2397.98
  5656.1 2399.87  5776.9 2399.49  5813.4 2401.09  5963.4 2401.01  6013.4 2402.50
#Mann=7,-1,0
  3809.2   0.045       0  4117.0   0.035       0  4396.5   0.045       0
  4924.2   0.035       0  4953.6   0.035       0  4957.8   0.035       0
  5148.5   0.045       0
Bank Sta=4953.6,4957.8
Exp/Cntr=0.3,0.1

Type RM Length L Ch R = 1,9128,467,467,467
BEGIN DESCRIPTION:
Buffalo Creek Trib 15 11.0
END DESCRIPTION:
XS GIS Cut Line= 3
      1273905.00      6902638.03      1273855.00      6901388.00
      1273048.95      6900597.81
#Sta/Elev= 30
  3766.1 2400.43  3816.2 2399.48  3836.2 2400.69  3886.2 2398.74  4038.2 2397.58
  4126.4 2397.90  4166.5 2396.16  4286.5 2396.12  4346.6 2394.21  4606.8 2392.27
  4826.0 2387.08  4924.1 2385.64  4955.0 2384.58  4955.2 2384.08  4959.2 2384.58
  5052.5 2384.81  5151.5 2389.44  5193.9 2388.97  5236.4 2391.57  5271.7 2390.91
  5321.2 2393.50  5370.7 2393.05  5413.1 2395.23  5476.8 2394.79  5533.4 2396.82
  5625.3 2396.48  5689.0 2398.25  5816.1 2398.00  5865.7 2399.72  6145.9 2400.62
#Mann=6,-1,0
  3766.1   0.035       0  4038.2   0.045       0  4826.0   0.035       0
  4924.1   0.045       0  4955.0   0.045       0  4959.2   0.045       0
Bank Sta=4955,4959.2
Exp/Cntr=0.3,0.1

Type RM Length L Ch R = 1,8661,448,448,448
BEGIN DESCRIPTION:
Buffalo Creek Trib 15 10.0
END DESCRIPTION:
XS GIS Cut Line= 3
      1274358.59      6902558.56      1274255.00      6901238.00
      1273386.38      6900414.43
#Sta/Elev= 30
  3670.6 2397.36  3762.6 2397.44  3821.6 2396.09  3972.1 2396.03  4022.2 2394.55
  4172.7 2394.92  4202.8 2393.25  4419.1 2391.36  4473.6 2392.10  4777.6 2386.40
  4806.5 2386.76  4844.8 2384.63  5021.1 2382.42  5021.4 2381.92  5025.5 2382.42
  5058.9 2384.74  5087.2 2383.18  5110.5 2384.30  5136.6 2386.09  5221.5 2386.82
  5264.0 2389.38  5298.8 2388.91  5384.2 2391.69  5440.8 2391.00  5525.7 2393.42
  5879.3 2395.19  5929.0 2396.93  6049.2 2396.83  6084.4 2398.50  6192.2 2398.20
#Mann=8,-1,0
  3670.6   0.035       0  3762.6   0.045       0  4777.6   0.035       0
  4806.5   0.045       0  5021.1   0.045       0  5025.5   0.045       0
  5110.5   0.035       0  5298.8   0.045       0
Bank Sta=5021.1,5025.5
Exp/Cntr=0.3,0.1

Type RM Length L Ch R = 1,8213,409,409,409
BEGIN DESCRIPTION:
Buffalo Creek Trib 15 9.0
END DESCRIPTION:
XS GIS Cut Line= 3
      1274575.60      6902558.47      1274605.00      6901038.00
      1273577.35      6900032.49
#Sta/Elev= 30
  3486.6 2396.12  3528.6 2395.84  4207.2 2392.00  4347.2 2389.55  4387.2 2390.33
  4597.3 2386.56  4637.3 2387.33  4697.3 2384.78  4796.6 2383.51  4897.3 2380.43
  4957.9 2380.87  5012.2 2379.92  5012.5 2379.42  5016.7 2379.92  5042.7 2382.01
  5071.0 2381.04  5120.4 2384.18  5155.9 2383.61  5198.3 2386.52  5240.7 2385.50
  5297.3 2388.01  5353.9 2387.00  5403.3 2389.33  5544.8 2389.97  5587.2 2391.69
  5870.1 2391.90  5926.7 2393.51  6068.1 2393.61  6110.6 2395.39  6445.1 2397.66
#Mann=6,-1,0
  3486.6   0.035       0  3528.6   0.045       0  4796.6    0.07       0
  4957.9   0.045       0  5012.2   0.045       0  5016.7   0.045       0
Bank Sta=5012.2,5016.7
Exp/Cntr=0.3,0.1

Type RM Length L Ch R = 1,7804,463,463,463
BEGIN DESCRIPTION:
Buffalo Creek Trib 15 8.0
END DESCRIPTION:
XS GIS Cut Line= 3
      1274775.25      6902575.93      1274955.00      6900938.00
      1274020.04      6899676.57
#Sta/Elev= 30
  3360.2 2396.35  3375.6 2395.45  3539.2 2394.37  3585.8 2392.74  3901.4 2391.84
  4293.7 2387.99  4344.0 2388.71  4444.6 2386.53  4494.9 2387.16  4535.1 2385.22
  4716.2 2384.35  4766.5 2382.15  4887.2 2381.10  4920.5 2379.22  4985.5 2378.32
  4985.9 2377.82  4990.1 2378.32  5149.8 2380.22  5265.0 2383.38  5272.5 2383.90
  5330.4 2383.82  5365.9 2386.08  5416.0 2385.72  5457.6 2388.03  5516.1 2387.54
  5593.3 2389.96  6144.2 2393.69  6197.1 2392.96  6402.5 2394.58  6578.1 2396.02
#Mann=10,-1,0
  3360.2   0.035       0  3375.6   0.045       0  4920.5    0.07       0
  4985.5    0.07       0  4990.1    0.07       0  5149.8   0.045       0
  5265.0   0.035       0  5272.5   0.045       0  6197.1   0.035       0
  6402.5   0.045       0
Bank Sta=4985.5,4990.1
Exp/Cntr=0.3,0.1

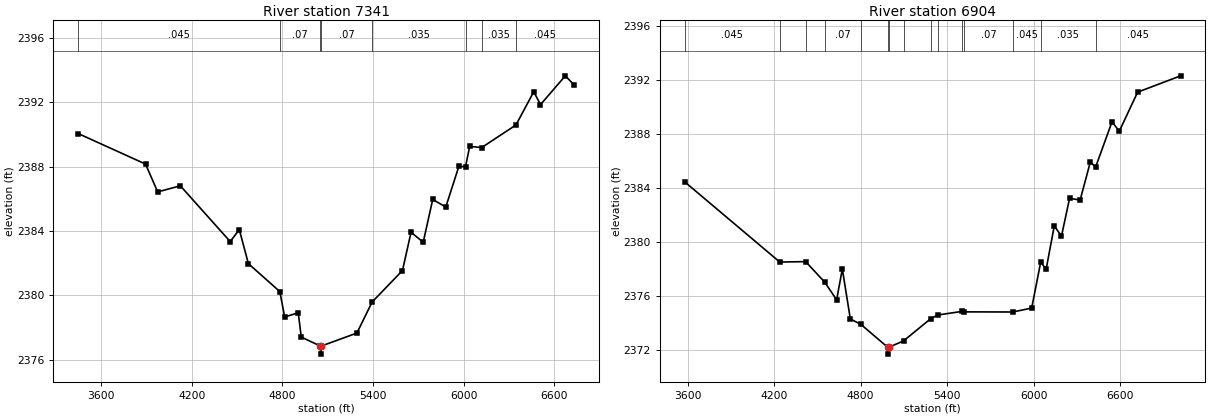
Type RM Length L Ch R = 1,7341,437,437,437
BEGIN DESCRIPTION:
Buffalo Creek Trib 15 7.0
END DESCRIPTION:
XS GIS Cut Line= 3
      1275296.09      6902393.59      1275355.00      6900838.00
      1274375.96      6899416.18
#Sta/Elev= 30
  3447.9 2390.06  3893.8 2388.16  3973.9 2386.43  4124.0 2386.81  4454.2 2383.34
  4514.3 2384.09  4574.3 2381.97  4782.6 2380.23  4814.5 2378.65  4904.5 2378.91
  4924.5 2377.40  5051.7 2376.84  5052.0 2376.34  5056.3 2376.84  5292.7 2377.65
  5393.4 2379.58  5594.4 2381.54  5651.2 2383.92  5731.7 2383.30  5794.6 2385.96
  5881.1 2385.49  5967.7 2388.02  6011.8 2388.00  6039.4 2389.26  6119.0 2389.19
  6345.5 2390.59  6463.5 2392.66  6508.1 2391.86  6672.5 2393.65  6730.9 2393.08
#Mann=8,-1,0
  3447.9   0.045       0  4782.6    0.07       0  5051.7    0.07       0
  5056.3    0.07       0  5393.4   0.035       0  6011.8   0.045       0
  6119.0   0.035       0  6345.5   0.045       0
Bank Sta=5051.7,5056.3
Exp/Cntr=0.3,0.1

Type RM Length L Ch R = 1,6904,0,0,0
BEGIN DESCRIPTION:
Buffalo Creek Trib 15 6.0
END DESCRIPTION:
XS GIS Cut Line= 3
      1276250.95      6902176.59      1275755.00      6900838.00
      1274559.14      6899217.73
#Sta/Elev= 30
  3578.7 2384.49  4238.5 2378.55  4418.3 2378.58  4550.4 2377.06  4633.0 2375.75
  4672.7 2378.03  4728.2 2374.33  4800.5 2373.94  4988.7 2372.23  4989.0 2371.73
  4993.4 2372.23  5097.5 2372.71  5285.4 2374.35  5336.2 2374.63  5500.5 2374.89
  5516.5 2374.86  5855.1 2374.85  5986.6 2375.14  6049.2 2378.55  6086.8 2378.01
  6143.2 2381.22  6193.3 2380.47  6249.6 2383.27  6322.8 2383.14  6393.7 2385.97
  6429.8 2385.57  6544.1 2388.94  6594.2 2388.23  6721.5 2391.13  7020.0 2392.34
#Mann=15,-1,0
  3578.7   0.045       0  4238.5    0.07       0  4418.3   0.035       0
  4550.4    0.07       0  4800.5   0.045       0  4988.7   0.045       0
  4993.4   0.045       0  5097.5    0.07       0  5285.4   0.035       0
  5336.2    0.07       0  5500.5   0.035       0  5516.5    0.07       0
  5855.1   0.045       0  6049.2   0.035       0  6429.8   0.045       0
Bank Sta=4988.7,4993.4
Exp/Cntr=0.3,0.1

Chan Stop Cuts=-1