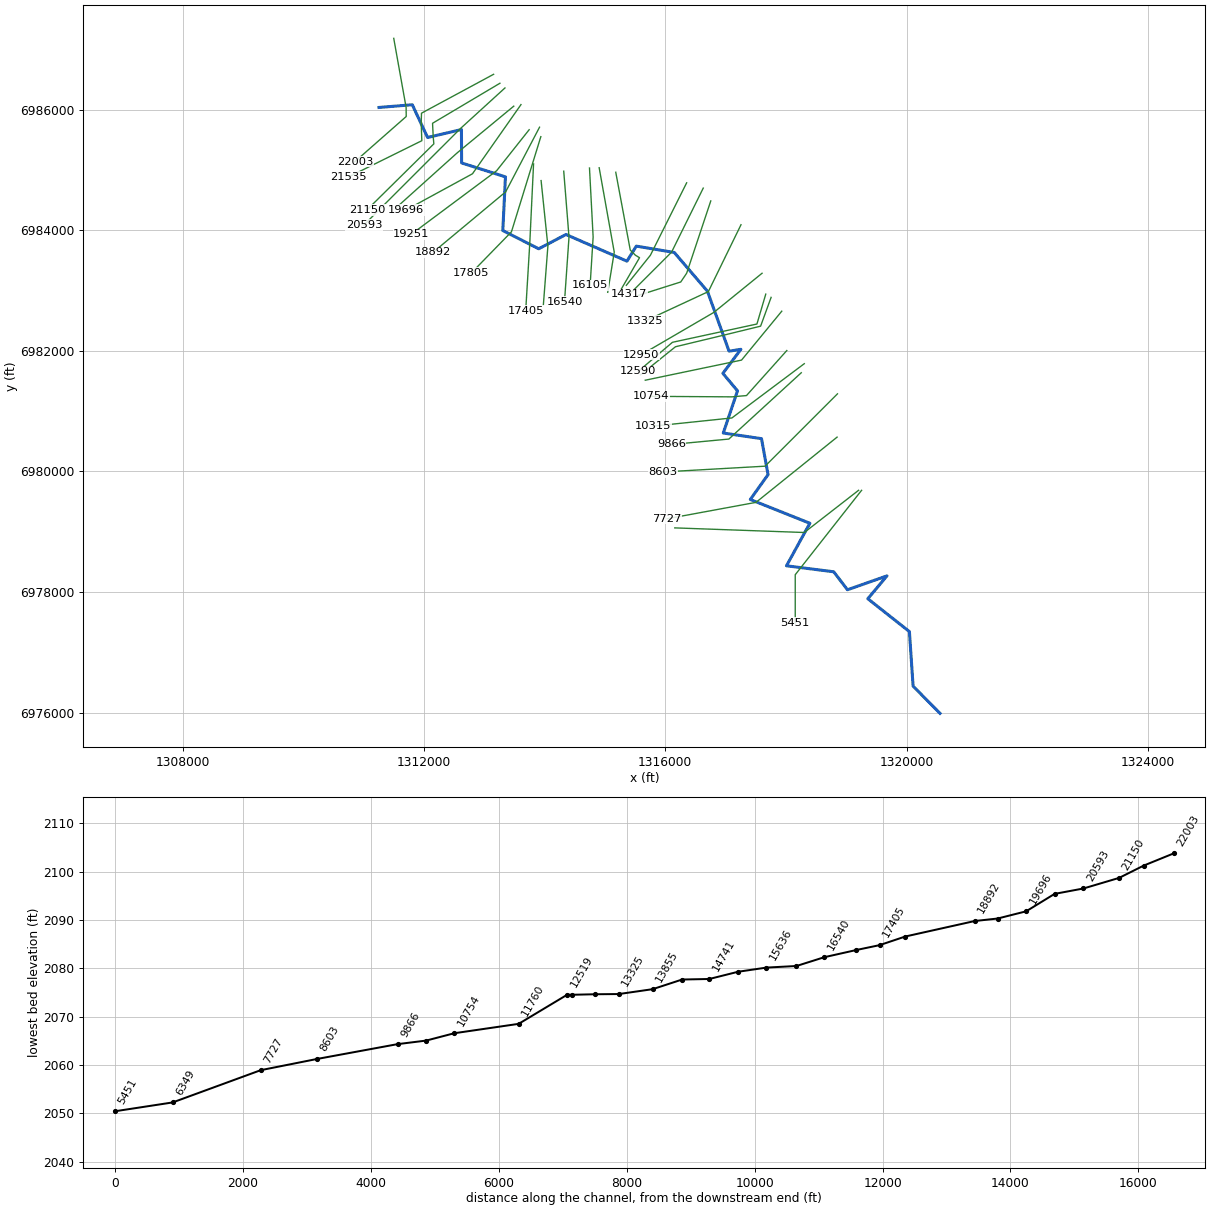
--- Deep Creek.prj (project) ---

Proj Title=Deep Creek Base Level Engineering
Current Plan=p01
Default Exp/Contr=0.3,0.1
English Units
Geom File=g01
Flow File=f01
Plan File=p01
BEGIN DESCRIPTION:
Deep Creek
END DESCRIPTION:

--- Deep Creek.p01 (plan) ---

Plan Title=Multiple Run
Short Identifier=Multiple
Geom File=g01
Flow File=f01
Subcritical Flow
K Sum by GR= 0
Std Step Tol= 0.01
Critical Tol= 0.01
Num of Std Step Trials= 20
Max Error Tol= 0.3
Flow Tol Ratio= 0.001
Split Flow NTrial= 30
Split Flow Tol= 0.02
Split Flow Ratio= 0.02
Log Output Level= 0
Friction Slope Method= 1
Unsteady Friction Slope Method= 2
Unsteady Bridges Friction Slope Method= 1
Parabolic Critical Depth
Global Vel Dist=  1 , 1 , 1
Global Log Level= 0
CheckData=True
Encroach Param= -1, 0, 0, 0
BEGIN DESCRIPTION:
Multiple Run
END DESCRIPTION:

--- Deep Creek.f01 (steady flow) ---

Flow Title=Multiple
Number of Profiles=7
Profile Names=10-year,25-year,50-year,1pct_min,100-year,1pct_plu,500-year
River Rch & RM= Deep Creek,Reach-1,22003
     401     579     731     458     915    1825    1452
River Rch & RM= Deep Creek,Reach-1,17805
     489     711     901     567    1132    2258    1808
River Rch & RM= Deep Creek,Reach-1,14317
     574     839    1068     674    1345    2683    2163
River Rch & RM= Deep Creek,Reach-1,10754
     626     915    1164     734    1464    2920    2348
River Rch & RM= Deep Creek,Reach-1,3888
     691    1012    1290     815    1625    3243    2616
Boundary for River Rch & Prof#=Deep Creek,Reach-1,1
Up Type=0
Dn Type=3
Dn Slope=0.005
Boundary for River Rch & Prof#=Deep Creek,Reach-1,2
Up Type=0
Dn Type=3
Dn Slope=0.005
Boundary for River Rch & Prof#=Deep Creek,Reach-1,3
Up Type=0
Dn Type=3
Dn Slope=0.005
Boundary for River Rch & Prof#=Deep Creek,Reach-1,4
Up Type=0
Dn Type=3
Dn Slope=0.005
Boundary for River Rch & Prof#=Deep Creek,Reach-1,5
Up Type=0
Dn Type=3
Dn Slope=0.005
Boundary for River Rch & Prof#=Deep Creek,Reach-1,6
Up Type=0
Dn Type=3
Dn Slope=0.005
Boundary for River Rch & Prof#=Deep Creek,Reach-1,7
Up Type=0
Dn Type=3
Dn Slope=0.005

--- Deep Creek.g01 (geometry) ---

Geom Title=Existing Conditions

River Reach=Deep Creek,Reach-1
Reach XY= 30
      1311255.00      6986038.00      1311807.55      6986083.02
      1312060.65      6985539.97      1312622.14      6985671.55
      1312624.78      6985117.91      1313351.48      6984886.72
      1313307.57      6983996.51      1313902.81      6983694.05
      1314355.10      6983930.67      1315365.71      6983488.70
      1315520.75      6983737.95      1316149.53      6983632.74
      1316699.17      6982990.84      1317058.06      6981995.54
      1317253.61      6982026.52      1316955.86      6981627.66
      1317197.78      6981337.71      1316962.29      6980637.91
      1317595.87      6980544.78      1317704.14      6979948.31
      1317409.99      6979535.45      1318397.24      6979141.42
      1318010.06      6978435.71      1318793.47      6978336.50
      1319020.22      6978038.13      1319675.69      6978268.74
      1319357.99      6977889.46      1320047.66      6977344.38
      1320108.52      6976439.48      1320555.00      6975988.00

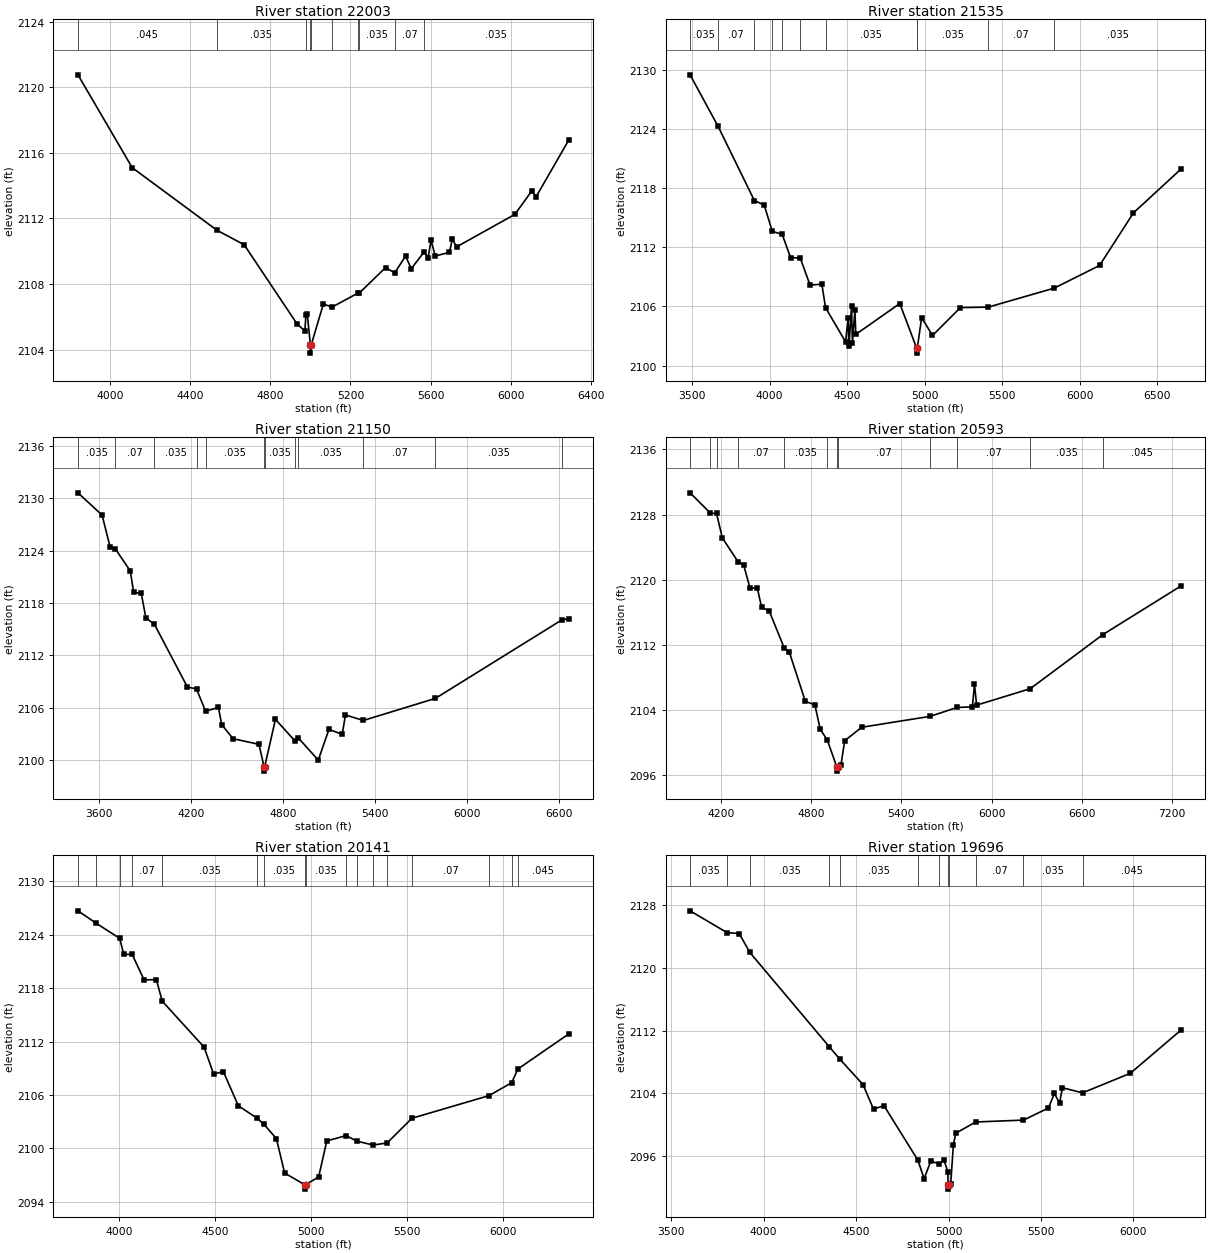
Type RM Length L Ch R = 1,22003,468,468,468
BEGIN DESCRIPTION:
Deep Creek 32.0
END DESCRIPTION:
XS GIS Cut Line= 4
      1311499.75      6987184.51      1311705.00      6986038.00
      1311706.74      6985888.05      1310855.01      6985138.01
#Sta/Elev= 30
  3840.0 2120.76  4110.7 2115.10  4532.8 2111.29  4669.5 2110.40  4933.6 2105.57
  4972.8 2105.14  4977.6 2106.11  4984.4 2106.17  5000.2 2104.29  5000.4 2103.79
  5004.2 2104.29  5064.7 2106.78  5108.8 2106.60  5235.9 2107.44  5242.6 2107.43
  5375.5 2109.01  5420.9 2108.68  5475.1 2109.71  5503.5 2108.94  5567.1 2109.95
  5588.0 2109.62  5602.3 2110.67  5623.4 2109.71  5694.3 2109.94  5708.5 2110.74
  5730.0 2110.27  6020.6 2112.25  6105.1 2113.68  6126.9 2113.33  6289.6 2116.78
#Mann=10,-1,0
  3840.0   0.045       0  4532.8   0.035       0  4977.6    0.07       0
  5000.2    0.07       0  5004.2    0.07       0  5108.8   0.035       0
  5235.9    0.07       0  5242.6   0.035       0  5420.9    0.07       0
  5567.1   0.035       0
Bank Sta=5000.2,5004.2
Exp/Cntr=0.3,0.1

Type RM Length L Ch R = 1,21535,385,385,385
BEGIN DESCRIPTION:
Deep Creek 31.0
END DESCRIPTION:
XS GIS Cut Line= 5
      1313154.99      6986587.99      1311959.89      6985943.14
      1311955.00      6985788.00      1311965.10      6985486.54
      1310754.96      6984887.98
#Sta/Elev= 30
  3486.8 2129.50  3666.8 2124.29  3901.4 2116.75  3965.2 2116.28  4016.6 2113.62
  4080.6 2113.32  4134.6 2110.97  4197.6 2110.90  4260.3 2108.17  4336.5 2108.27
  4360.2 2105.88  4489.7 2102.41  4505.9 2104.87  4511.6 2102.00  4527.8 2106.02
  4533.5 2102.33  4549.7 2105.61  4555.4 2103.17  4839.0 2106.30  4948.0 2101.77
  4948.2 2101.27  4952.0 2101.77  4980.0 2104.88  5050.0 2103.06  5230.1 2105.89
  5410.3 2105.94  5834.5 2107.86  6127.3 2110.16  6346.0 2115.50  6651.7 2119.93
#Mann=11,-1,0
  3486.8   0.035       0  3666.8    0.07       0  3901.4   0.035       0
  4016.6    0.07       0  4080.6   0.035       0  4197.6    0.07       0
  4360.2   0.035       0  4948.0   0.035       0  4952.0   0.035       0
  5410.3    0.07       0  5834.5   0.035       0
Bank Sta=4948,4952
Exp/Cntr=0.3,0.1

Type RM Length L Ch R = 1,21150,557,557,557
BEGIN DESCRIPTION:
Deep Creek 30.0
END DESCRIPTION:
XS GIS Cut Line= 5
      1313260.21      6986439.70      1312143.05      6985775.61
      1312155.00      6985538.00      1312164.75      6985434.46
      1311055.00      6984338.00
#Sta/Elev= 30
  3462.3 2130.63  3619.6 2128.08  3671.5 2124.46  3705.6 2124.22  3804.0 2121.66
  3825.4 2119.22  3875.5 2119.09  3905.3 2116.29  3960.8 2115.56  4176.1 2108.37
  4235.8 2108.14  4294.9 2105.58  4378.6 2106.03  4400.0 2104.05  4474.1 2102.44
  4643.3 2101.79  4676.2 2099.22  4676.5 2098.72  4680.2 2099.22  4750.7 2104.66
  4880.5 2102.13  4899.7 2102.53  5030.0 2099.98  5099.6 2103.51  5186.1 2102.93
  5207.2 2105.16  5324.1 2104.53  5794.1 2107.06  6617.3 2116.04  6663.9 2116.22
#Mann=12,-1,0
  3462.3   0.035       0  3705.6    0.07       0  3960.8   0.035       0
  4235.8    0.07       0  4294.9   0.035       0  4676.2   0.035       0
  4680.2   0.035       0  4880.5    0.07       0  4899.7   0.035       0
  5324.1    0.07       0  5794.1   0.035       0  6617.3   0.045       0
Bank Sta=4676.2,4680.2
Exp/Cntr=0.3,0.1

Type RM Length L Ch R = 1,20593,452,452,452
BEGIN DESCRIPTION:
Deep Creek 29.0
END DESCRIPTION:
XS GIS Cut Line= 3
      1313343.49      6986361.54      1312605.00      6985688.00
      1311004.97      6984087.97
#Sta/Elev= 30
  3995.9 2130.66  4131.2 2128.16  4171.8 2128.13  4210.0 2125.14  4316.4 2122.16
  4351.2 2121.86  4393.8 2119.00  4443.1 2118.95  4471.5 2116.60  4521.5 2116.19
  4621.6 2111.63  4655.9 2111.11  4762.0 2105.08  4825.5 2104.66  4860.6 2101.68
  4907.9 2100.34  4971.5 2097.03  4971.9 2096.53  4976.8 2097.03  4999.0 2097.31
  5023.7 2100.26  5136.8 2101.91  5592.3 2103.25  5770.4 2104.34  5872.2 2104.41
  5886.4 2107.16  5900.5 2104.62  6257.1 2106.64  6740.3 2113.28  7258.2 2119.23
#Mann=12,-1,0
  3995.9   0.035       0  4131.2    0.07       0  4171.8   0.035       0
  4316.4    0.07       0  4621.6   0.035       0  4907.9    0.07       0
  4971.5    0.07       0  4976.8    0.07       0  5592.3   0.035       0
  5770.4    0.07       0  6257.1   0.035       0  6740.3   0.045       0
Bank Sta=4971.5,4976.8
Exp/Cntr=0.3,0.1

Type RM Length L Ch R = 1,20141,445,445,445
BEGIN DESCRIPTION:
Deep Creek 28.0
END DESCRIPTION:
XS GIS Cut Line= 3
      1313489.31      6986059.45      1312555.00      6985288.00
      1311555.00      6984388.00
#Sta/Elev= 30
  3787.3 2126.70  3879.0 2125.35  4004.4 2123.61  4026.3 2121.80  4069.6 2121.81
  4131.9 2118.93  4195.7 2118.97  4226.2 2116.55  4444.6 2111.37  4494.1 2108.35
  4544.9 2108.62  4622.9 2104.78  4719.3 2103.40  4757.0 2102.69  4821.1 2101.09
  4864.1 2097.22  4968.2 2095.91  4968.7 2095.41  4973.6 2095.91  5041.2 2096.78
  5083.8 2100.83  5185.0 2101.43  5239.2 2100.81  5324.8 2100.37  5397.8 2100.60
  5527.6 2103.38  5928.6 2105.92  6047.1 2107.38  6079.6 2108.92  6344.3 2112.86
#Mann=17,-1,0
  3787.3   0.035       0  3879.0    0.07       0  4004.4   0.035       0
  4069.6    0.07       0  4226.2   0.035       0  4719.3    0.07       0
  4757.0   0.035       0  4968.2   0.035       0  4973.6   0.035       0
  5185.0    0.07       0  5239.2   0.035       0  5324.8    0.07       0
  5397.8   0.035       0  5527.6    0.07       0  5928.6   0.045       0
  6047.1    0.07       0  6079.6   0.045       0
Bank Sta=4968.2,4973.6
Exp/Cntr=0.3,0.1

Type RM Length L Ch R = 1,19696,445,445,445
BEGIN DESCRIPTION:
Deep Creek 27.0
END DESCRIPTION:
XS GIS Cut Line= 3
      1313609.12      6986085.50      1312805.00      6984938.00
      1311705.00      6984338.00
#Sta/Elev= 30
  3602.4 2127.24  3801.9 2124.47  3868.2 2124.35  3925.2 2121.95  4354.8 2109.94
  4411.2 2108.38  4537.7 2105.11  4594.3 2101.99  4651.0 2102.43  4834.3 2095.49
  4868.0 2093.13  4903.8 2095.35  4950.5 2095.04  4975.3 2095.49  4996.2 2094.04
  4997.7 2092.30  4998.2 2091.80  5003.4 2092.30  5011.7 2092.42  5026.4 2097.45
  5039.2 2098.92  5147.1 2100.35  5405.3 2100.59  5540.4 2102.13  5572.7 2103.99
  5600.2 2102.75  5616.3 2104.71  5724.7 2104.06  5983.2 2106.55  6256.6 2112.04
#Mann=12,-1,0
  3602.4   0.035       0  3801.9    0.07       0  3925.2   0.035       0
  4354.8    0.07       0  4411.2   0.035       0  4834.3    0.07       0
  4950.5   0.035       0  4997.7   0.035       0  5003.4   0.035       0
  5147.1    0.07       0  5405.3   0.035       0  5724.7   0.045       0
Bank Sta=4997.7,5003.4
Exp/Cntr=0.3,0.1

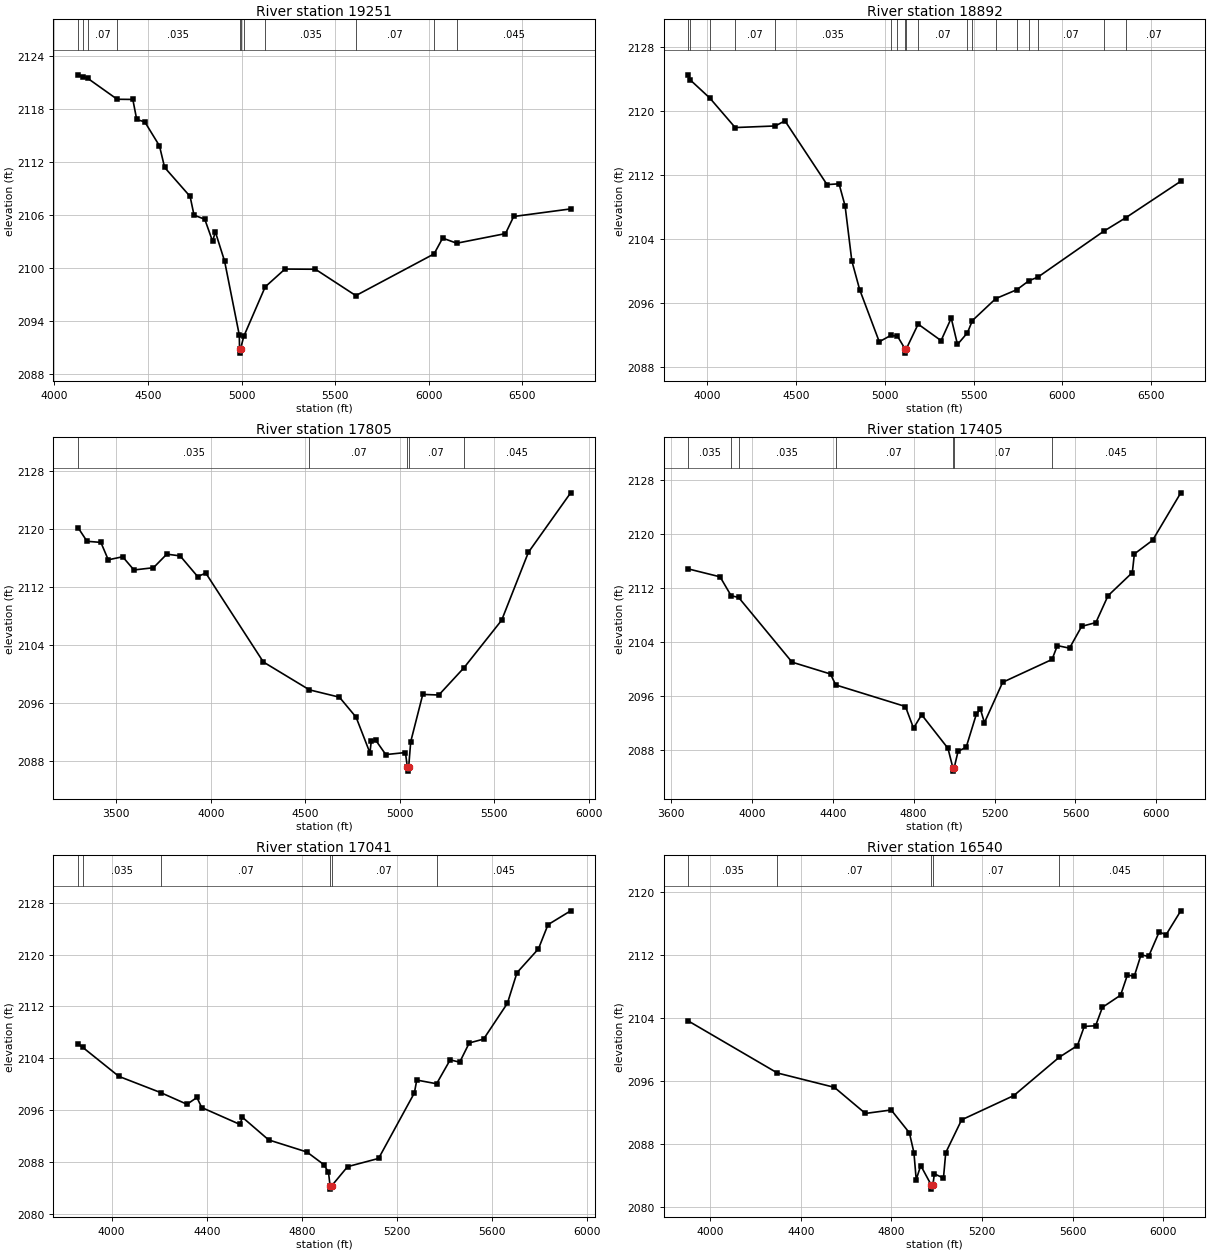
Type RM Length L Ch R = 1,19251,359,359,359
BEGIN DESCRIPTION:
Deep Creek 26.0
END DESCRIPTION:
XS GIS Cut Line= 3
      1313744.54      6985668.84      1313205.00      6984988.00
      1311791.41      6983934.46
#Sta/Elev= 30
  4126.4 2121.86  4152.6 2121.62  4177.6 2121.47  4335.4 2119.09  4419.0 2119.07
  4439.8 2116.80  4483.1 2116.52  4561.3 2113.81  4588.9 2111.36  4725.1 2108.07
  4745.9 2105.96  4803.6 2105.48  4845.3 2102.98  4859.7 2104.07  4909.4 2100.73
  4987.9 2092.35  4989.1 2090.81  4989.5 2090.31  4994.8 2090.81  5011.6 2092.20
  5126.2 2097.82  5231.8 2099.84  5394.4 2099.82  5610.4 2096.83  6028.4 2101.56
  6074.2 2103.35  6149.3 2102.77  6409.9 2103.86  6453.7 2105.80  6758.1 2106.66
#Mann=11,-1,0
  4126.4    0.07       0  4152.6   0.035       0  4177.6    0.07       0
  4335.4   0.035       0  4989.1   0.035       0  4994.8   0.035       0
  5011.6    0.07       0  5126.2   0.035       0  5610.4    0.07       0
  6028.4   0.035       0  6149.3   0.045       0
Bank Sta=4989.1,4994.8
Exp/Cntr=0.3,0.1

Type RM Length L Ch R = 1,18892,1087,1087,1087
BEGIN DESCRIPTION:
Deep Creek 25.0
END DESCRIPTION:
XS GIS Cut Line= 3
      1313916.40      6985710.48      1313355.00      6984638.00
      1312154.98      6983637.99
#Sta/Elev= 30
  3894.0 2124.52  3903.8 2123.92  4015.9 2121.62  4158.6 2117.94  4384.6 2118.14
  4438.6 2118.78  4675.6 2110.82  4743.2 2110.92  4777.2 2108.16  4815.1 2101.30
  4859.2 2097.72  4969.5 2091.21  5034.4 2092.00  5072.1 2091.90  5115.3 2090.29
  5115.8 2089.79  5121.0 2090.29  5188.4 2093.41  5317.4 2091.35  5374.6 2094.16
  5409.8 2090.87  5465.5 2092.32  5494.0 2093.86  5625.0 2096.59  5744.2 2097.71
  5812.3 2098.83  5862.1 2099.27  6232.2 2104.99  6358.0 2106.70  6666.6 2111.24
#Mann=18,-1,0
  3894.0   0.035       0  3903.8    0.07       0  4015.9   0.035       0
  4158.6    0.07       0  4384.6   0.035       0  5034.4    0.07       0
  5072.1   0.035       0  5115.3   0.035       0  5121.0   0.035       0
  5188.4    0.07       0  5465.5   0.035       0  5494.0    0.07       0
  5625.0   0.035       0  5744.2    0.07       0  5812.3   0.035       0
  5862.1    0.07       0  6232.2   0.035       0  6358.0    0.07       0
Bank Sta=5115.3,5121
Exp/Cntr=0.3,0.1

Type RM Length L Ch R = 1,17805,400,400,400
BEGIN DESCRIPTION:
Deep Creek 24.5
END DESCRIPTION:
XS GIS Cut Line= 3
      1313937.86      6985553.39      1313450.97      6983975.50
      1312785.09      6983291.63
#Sta/Elev= 30
  3298.0 2120.13  3345.5 2118.25  3418.8 2118.10  3457.8 2115.70  3533.9 2116.12
  3593.7 2114.30  3696.9 2114.61  3767.4 2116.48  3838.0 2116.24  3930.7 2113.39
  3973.8 2113.87  4278.2 2101.62  4521.9 2097.78  4680.5 2096.77  4768.8 2094.01
  4842.0 2089.10  4849.0 2090.71  4873.4 2090.81  4925.8 2088.86  5029.6 2089.14
  5040.4 2087.08  5040.9 2086.58  5046.7 2087.08  5057.7 2090.63  5121.5 2097.15
  5206.4 2097.07  5339.3 2100.82  5538.7 2107.37  5680.2 2116.73  5903.8 2124.93
#Mann=5,-1,0
  3298.0   0.035       0  4521.9    0.07       0  5040.4    0.07       0
  5046.7    0.07       0  5339.3   0.045       0
Bank Sta=5040.4,5046.7
Exp/Cntr=0.3,0.1

Type RM Length L Ch R = 1,17405,364,364,364
BEGIN DESCRIPTION:
Deep Creek 24.0
END DESCRIPTION:
XS GIS Cut Line= 3
      1313817.46      6985101.11      1313755.00      6983788.00
      1313687.26      6982668.84
#Sta/Elev= 30
  3685.1 2114.85  3842.8 2113.67  3897.6 2110.86  3934.4 2110.61  4198.8 2100.99
  4389.0 2099.23  4414.4 2097.61  4759.4 2094.40  4799.5 2091.18  4839.5 2093.18
  4969.7 2088.19  4993.9 2085.30  4994.4 2084.80  5000.4 2085.30  5019.7 2087.75
  5059.8 2088.35  5109.9 2093.25  5129.9 2094.02  5150.0 2092.00  5240.1 2098.00
  5484.2 2101.39  5510.6 2103.45  5570.7 2103.07  5630.8 2106.31  5701.0 2106.87
  5761.1 2110.86  5881.3 2114.30  5891.3 2117.07  5981.5 2119.10  6120.9 2126.15
#Mann=7,-1,0
  3685.1   0.035       0  3897.6    0.07       0  3934.4   0.035       0
  4414.4    0.07       0  4993.9    0.07       0  5000.4    0.07       0
  5484.2   0.045       0
Bank Sta=4993.9,5000.4
Exp/Cntr=0.3,0.1

Type RM Length L Ch R = 1,17041,501,501,501
BEGIN DESCRIPTION:
Deep Creek 23.0
END DESCRIPTION:
XS GIS Cut Line= 3
      1313942.47      6984825.06      1314055.00      6983738.00
      1313980.00      6982762.95
#Sta/Elev= 30
  3858.9 2106.21  3879.0 2105.67  4030.5 2101.20  4207.9 2098.67  4316.9 2096.89
  4358.6 2097.94  4378.7 2096.39  4539.6 2093.78  4549.6 2094.89  4660.2 2091.39
  4821.1 2089.52  4891.5 2087.59  4911.6 2086.41  4918.4 2084.29  4918.9 2083.79
  4924.9 2084.29  4991.9 2087.26  5122.3 2088.53  5272.7 2098.64  5282.7 2100.63
  5366.1 2100.06  5423.2 2103.75  5463.3 2103.39  5503.4 2106.36  5563.6 2106.95
  5663.9 2112.49  5704.0 2117.21  5794.3 2120.89  5834.4 2124.62  5929.7 2126.76
#Mann=6,-1,0
  3858.9    0.07       0  3879.0   0.035       0  4207.9    0.07       0
  4918.4    0.07       0  4924.9    0.07       0  5366.1   0.045       0
Bank Sta=4918.4,4924.9
Exp/Cntr=0.3,0.1

Type RM Length L Ch R = 1,16540,435,435,435
BEGIN DESCRIPTION:
Deep Creek 22.0
END DESCRIPTION:
XS GIS Cut Line= 3
      1314317.47      6984981.35      1314405.00      6983888.00
      1314330.00      6982812.96
#Sta/Elev= 30
  3903.3 2103.64  4297.1 2097.03  4548.7 2095.21  4685.5 2091.90  4799.5 2092.34
  4879.8 2089.44  4899.8 2086.94  4909.9 2083.51  4929.9 2085.29  4976.7 2082.80
  4977.2 2082.30  4983.4 2082.80  4990.1 2084.24  5030.2 2083.70  5040.2 2086.92
  5110.4 2091.09  5341.0 2094.17  5540.8 2099.02  5621.7 2100.51  5651.7 2102.94
  5701.8 2103.02  5731.9 2105.36  5812.1 2106.90  5842.2 2109.46  5872.3 2109.29
  5902.3 2112.02  5935.7 2111.81  5982.5 2114.93  6012.6 2114.55  6077.8 2117.60
#Mann=5,-1,0
  3903.3   0.035       0  4297.1    0.07       0  4976.7    0.07       0
  4983.4    0.07       0  5540.8   0.045       0
Bank Sta=4976.7,4983.4
Exp/Cntr=0.3,0.1

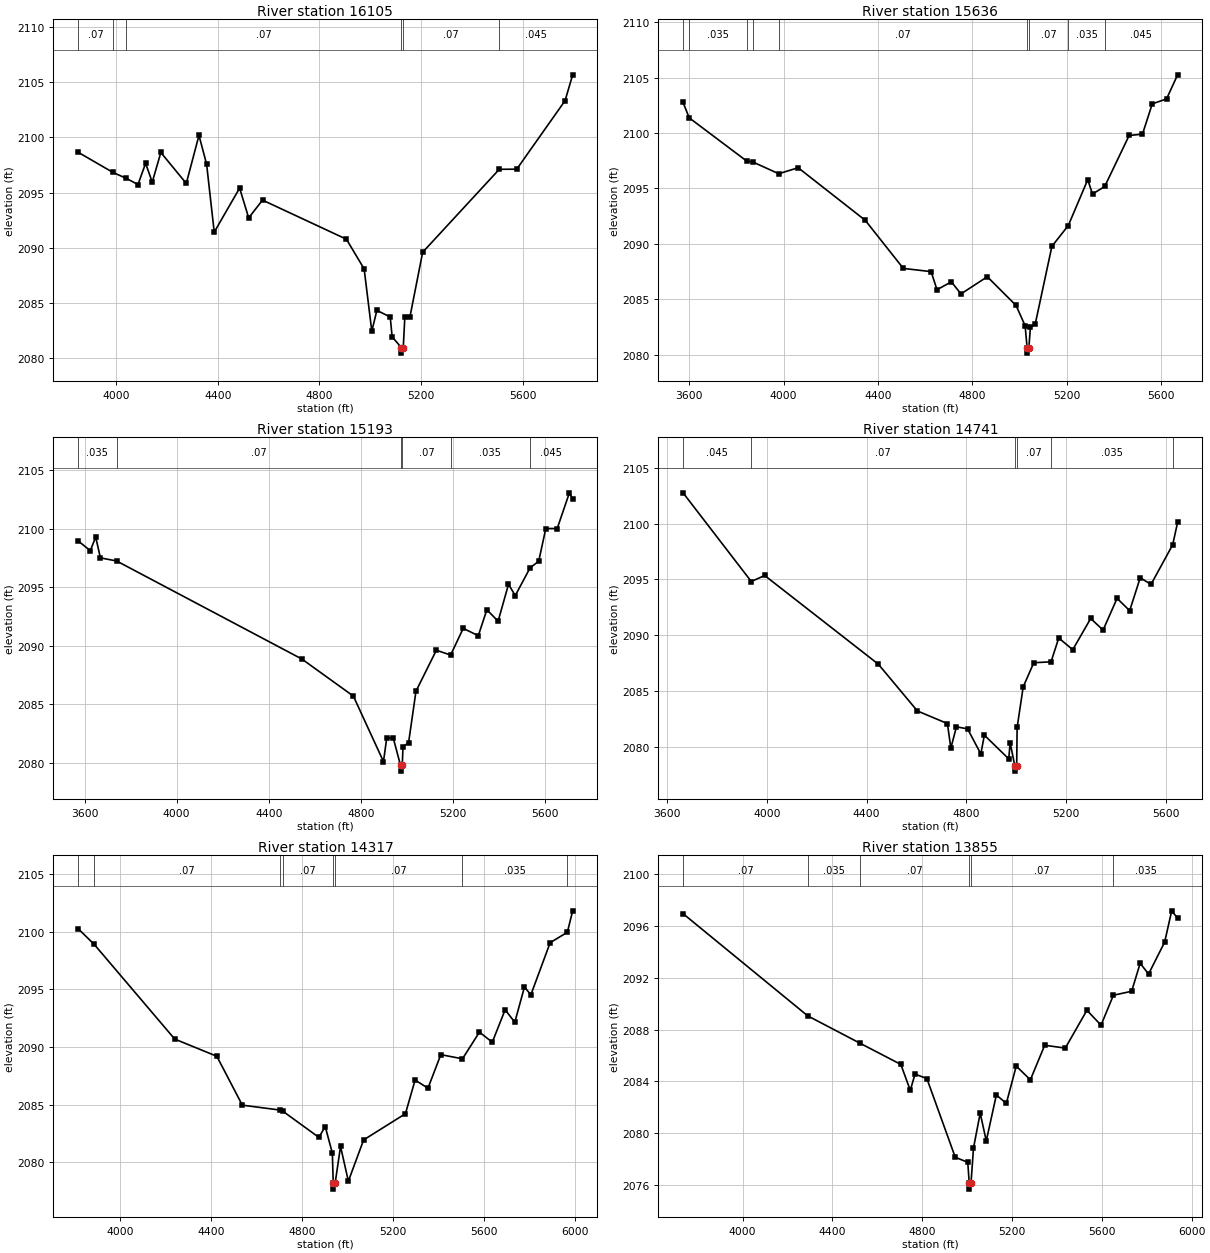
Type RM Length L Ch R = 1,16105,469,469,469
BEGIN DESCRIPTION:
Deep Creek 21.0
END DESCRIPTION:
XS GIS Cut Line= 3
      1314744.55      6985033.47      1314805.00      6983888.00
      1314755.00      6983088.02
#Sta/Elev= 30
  3849.0 2098.66  3986.7 2096.83  4036.8 2096.32  4084.8 2095.74  4114.8 2097.66
  4141.0 2095.96  4174.9 2098.64  4275.1 2095.84  4325.1 2100.19  4355.2 2097.58
  4385.2 2091.43  4485.3 2095.42  4521.0 2092.72  4575.5 2094.33  4906.1 2090.79
  4976.0 2088.10  5006.1 2082.46  5026.1 2084.35  5078.7 2083.75  5086.2 2081.96
  5122.5 2080.98  5123.0 2080.48  5130.1 2080.98  5136.3 2083.76  5156.4 2083.76
  5206.5 2089.61  5508.4 2097.12  5577.2 2097.13  5767.6 2103.33  5797.6 2105.67
#Mann=6,-1,0
  3849.0    0.07       0  3986.7   0.035       0  4036.8    0.07       0
  5122.5    0.07       0  5130.1    0.07       0  5508.4   0.045       0
Bank Sta=5122.5,5130.1
Exp/Cntr=0.3,0.1

Type RM Length L Ch R = 1,15636,443,443,443
BEGIN DESCRIPTION:
Deep Creek 20.0
END DESCRIPTION:
XS GIS Cut Line= 3
      1314905.01      6985037.97      1315155.00      6983638.00
      1315046.80      6982971.94
#Sta/Elev= 30
  3573.8 2102.76  3599.9 2101.37  3844.4 2097.46  3868.6 2097.40  3979.4 2096.33
  4061.9 2096.87  4346.3 2092.13  4507.8 2087.79  4625.6 2087.50  4650.5 2085.87
  4711.5 2086.58  4752.1 2085.49  4863.9 2087.04  4985.8 2084.45  5024.2 2082.62
  5032.6 2080.65  5033.1 2080.15  5040.2 2080.65  5046.6 2082.47  5066.8 2082.74
  5137.7 2089.78  5207.3 2091.66  5289.7 2095.79  5310.0 2094.50  5361.7 2095.18
  5465.3 2099.78  5521.8 2099.90  5563.3 2102.63  5624.0 2103.08  5670.7 2105.25
#Mann=9,-1,0
  3573.8    0.07       0  3599.9   0.035       0  3844.4    0.07       0
  3868.6   0.035       0  3979.4    0.07       0  5032.6    0.07       0
  5040.2    0.07       0  5207.3   0.035       0  5361.7   0.045       0
Bank Sta=5032.6,5040.2
Exp/Cntr=0.3,0.1

Type RM Length L Ch R = 1,15193,452,452,452
BEGIN DESCRIPTION:
Deep Creek 19.0
END DESCRIPTION:
XS GIS Cut Line= 5
      1315179.99      6984963.04      1315420.28      6983673.56
      1315505.00      6983588.00      1315573.93      6983545.95
      1315254.99      6982997.01
#Sta/Elev= 30
  3572.2 2098.96  3625.0 2098.13  3648.5 2099.29  3668.9 2097.51  3738.9 2097.25
  4543.7 2088.87  4767.5 2085.70  4898.2 2080.11  4912.4 2082.11  4940.6 2082.13
  4972.2 2079.79  4972.7 2079.29  4979.8 2079.79  4983.1 2081.39  5007.2 2081.71
  5039.4 2086.12  5127.9 2089.62  5189.9 2089.21  5244.6 2091.49  5310.0 2090.86
  5347.2 2093.08  5396.1 2092.10  5441.2 2095.25  5470.6 2094.29  5535.2 2096.67
  5572.4 2097.22  5603.1 2100.02  5652.7 2100.02  5705.7 2103.07  5719.9 2102.55
#Mann=6,-1,0
  3572.2   0.035       0  3738.9    0.07       0  4972.2    0.07       0
  4979.8    0.07       0  5189.9   0.035       0  5535.2   0.045       0
Bank Sta=4972.2,4979.8
Exp/Cntr=0.3,0.1

Type RM Length L Ch R = 1,14741,424,424,424
BEGIN DESCRIPTION:
Deep Creek 18.0
END DESCRIPTION:
XS GIS Cut Line= 3
      1316355.01      6984788.02      1315755.00      6983588.00
      1315354.99      6983087.98
#Sta/Elev= 30
  3664.3 2102.77  3937.8 2094.81  3991.4 2095.35  4446.9 2087.39  4603.5 2083.19
  4723.7 2082.06  4737.6 2079.86  4760.0 2081.77  4804.7 2081.58  4857.8 2079.33
  4871.8 2081.02  4969.6 2078.89  4975.2 2080.34  4993.7 2078.29  4994.2 2077.79
  5001.4 2078.29  5003.2 2081.71  5027.6 2085.36  5070.0 2087.52  5139.1 2087.60
  5170.0 2089.74  5226.1 2088.69  5298.1 2091.49  5347.7 2090.45  5403.8 2093.30
  5454.2 2092.19  5496.6 2095.15  5539.8 2094.55  5626.7 2098.11  5646.3 2100.11
#Mann=6,-1,0
  3664.3   0.045       0  3937.8    0.07       0  4993.7    0.07       0
  5001.4    0.07       0  5139.1   0.035       0  5626.7   0.045       0
Bank Sta=4993.7,5001.4
Exp/Cntr=0.3,0.1

Type RM Length L Ch R = 1,14317,462,462,462
BEGIN DESCRIPTION:
Deep Creek 17.0
END DESCRIPTION:
XS GIS Cut Line= 3
      1316629.98      6984700.12      1316105.00      6983638.00
      1315405.02      6982938.02
#Sta/Elev= 30
  3815.4 2100.26  3886.1 2098.90  4240.1 2090.69  4425.2 2089.20  4537.4 2084.96
  4701.7 2084.54  4714.5 2084.45  4874.0 2082.17  4902.0 2083.11  4933.3 2080.80
  4937.2 2078.18  4937.7 2077.68  4945.4 2078.18  4969.3 2081.38  5003.7 2078.37
  5070.9 2081.95  5254.7 2084.22  5297.2 2087.14  5353.7 2086.43  5410.3 2089.34
  5505.5 2088.98  5580.0 2091.29  5636.6 2090.42  5693.1 2093.23  5735.6 2092.15
  5778.0 2095.20  5806.3 2094.53  5891.1 2099.05  5966.7 2099.95  5990.1 2101.81
#Mann=8,-1,0
  3815.4   0.045       0  3886.1    0.07       0  4701.7   0.035       0
  4714.5    0.07       0  4937.2    0.07       0  4945.4    0.07       0
  5505.5   0.035       0  5966.7   0.045       0
Bank Sta=4937.2,4945.4
Exp/Cntr=0.3,0.1

Type RM Length L Ch R = 1,13855,530,530,530
BEGIN DESCRIPTION:
Deep Creek 16.0
END DESCRIPTION:
XS GIS Cut Line= 4
      1316755.00      6984487.99      1316355.00      6983288.00
      1316257.09      6983143.26      1315530.02      6982913.01
#Sta/Elev= 30
  3735.1 2096.95  4290.2 2089.06  4521.6 2086.96  4704.9 2085.31  4747.0 2083.31
  4768.1 2084.56  4820.8 2084.22  4947.3 2078.14  5003.0 2077.75  5009.4 2076.18
  5009.9 2075.68  5017.6 2076.18  5028.5 2078.85  5058.4 2081.55  5085.4 2079.40
  5130.3 2082.95  5174.7 2082.30  5218.9 2085.18  5281.8 2084.12  5345.6 2086.79
  5437.3 2086.57  5533.6 2089.49  5596.5 2088.34  5651.4 2090.65  5732.9 2090.96
  5770.7 2093.12  5808.2 2092.29  5879.7 2094.75  5911.2 2097.17  5937.4 2096.60
#Mann=6,-1,0
  3735.1    0.07       0  4290.2   0.035       0  4521.6    0.07       0
  5009.4    0.07       0  5017.6    0.07       0  5651.4   0.035       0
Bank Sta=5009.4,5017.6
Exp/Cntr=0.3,0.1

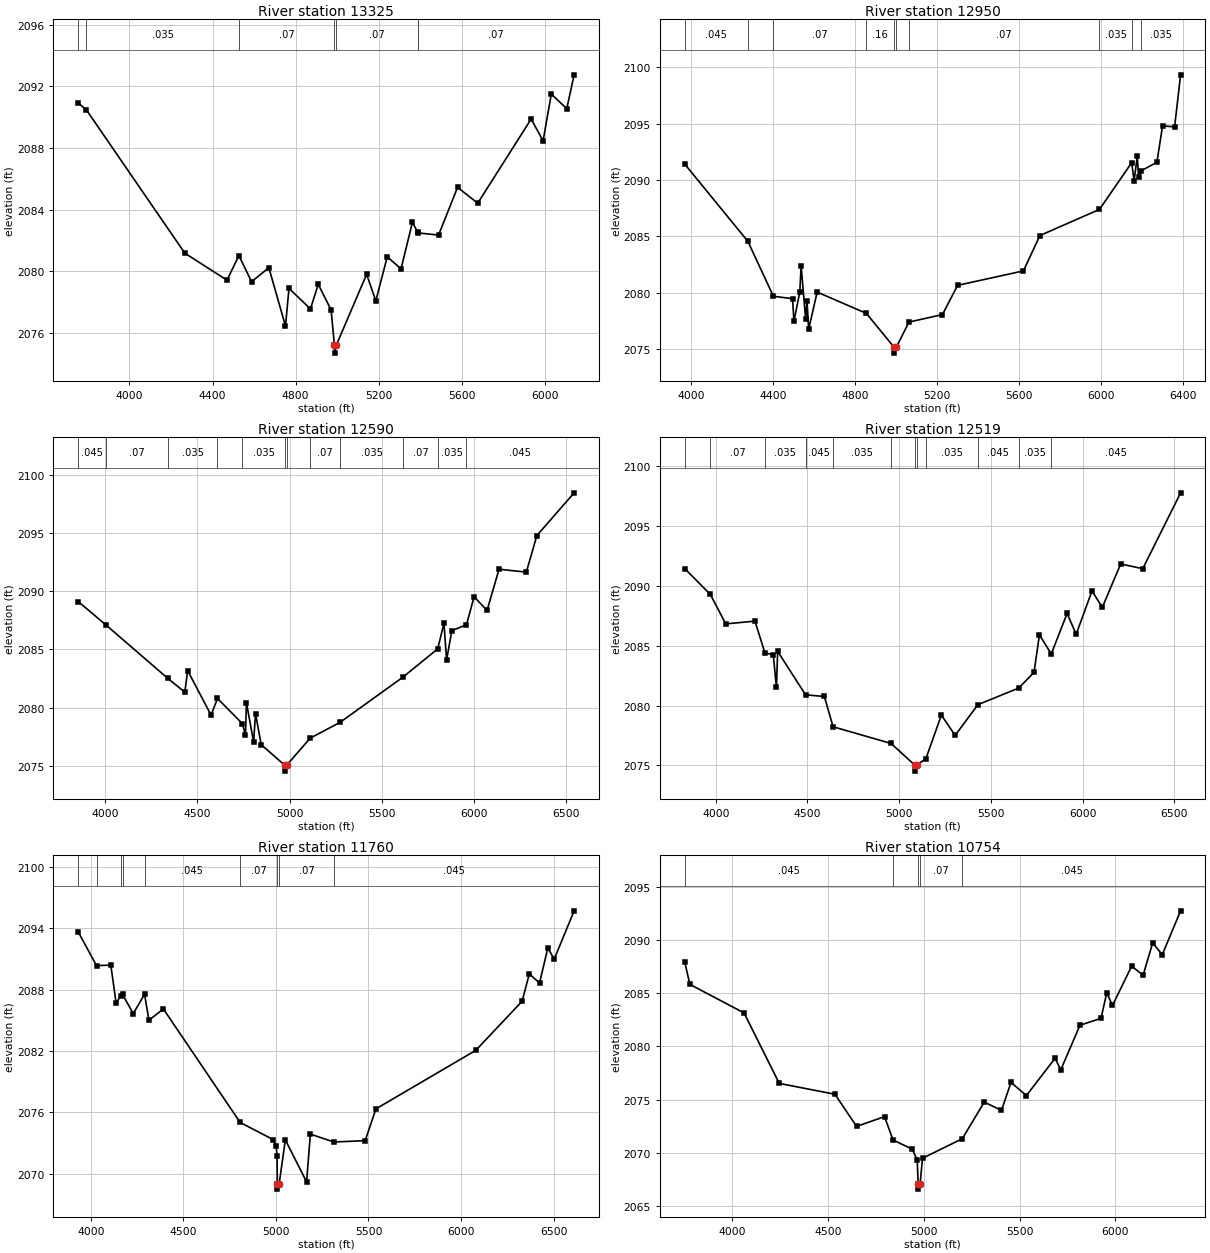
Type RM Length L Ch R = 1,13325,375,375,375
BEGIN DESCRIPTION:
Deep Creek 15.5
END DESCRIPTION:
XS GIS Cut Line= 3
      1317255.86      6984092.68      1316714.89      6982983.70
      1315669.50      6982497.06
#Sta/Elev= 30
  3753.4 2090.92  3792.4 2090.48  4266.7 2081.16  4469.5 2079.41  4526.8 2081.01
  4587.7 2079.31  4671.0 2080.22  4751.0 2076.43  4767.9 2078.88  4871.2 2077.54
  4908.7 2079.14  4970.7 2077.47  4986.6 2075.17  4987.1 2074.67  4995.1 2075.17
  5141.6 2079.79  5185.7 2078.06  5240.9 2080.93  5307.1 2080.14  5362.2 2083.18
  5387.8 2082.51  5389.7 2082.48  5487.8 2082.34  5579.3 2085.44  5676.3 2084.41
  5933.5 2089.88  5990.9 2088.46  6030.5 2091.50  6104.7 2090.55  6140.4 2092.75
#Mann=7,-1,0
  3753.4    0.07       0  3792.4   0.035       0  4526.8    0.07       0
  4986.6    0.07       0  4995.1    0.07       0  5387.8   0.035       0
  5389.7    0.07       0
Bank Sta=4986.6,4995.1
Exp/Cntr=0.3,0.1

Type RM Length L Ch R = 1,12950,360,360,360
BEGIN DESCRIPTION:
Deep Creek 15.0
END DESCRIPTION:
XS GIS Cut Line= 3
      1317605.02      6983288.02      1316805.00      6982638.00
      1315604.96      6981937.98
#Sta/Elev= 30
  3969.2 2091.42  4277.4 2084.56  4402.1 2079.68  4495.8 2079.46  4502.2 2077.44
  4531.0 2080.07  4537.4 2082.39  4559.7 2077.62  4566.1 2079.29  4574.1 2076.75
  4615.7 2080.05  4855.9 2078.16  4992.1 2075.13  4992.6 2074.63  5001.5 2075.13
  5063.7 2077.39  5227.0 2078.05  5301.0 2080.65  5622.3 2081.93  5702.5 2085.07
  5993.3 2087.39  6150.6 2091.54  6162.3 2089.93  6178.0 2092.14  6183.8 2090.24
  6197.3 2090.83  6273.5 2091.57  6301.2 2094.81  6359.9 2094.72  6389.3 2099.34
#Mann=10,-1,0
  3969.2   0.045       0  4277.4   0.035       0  4402.1    0.07       0
  4855.9    0.16       0  4992.1    0.07       0  5001.5    0.16       0
  5063.7    0.07       0  5993.3   0.035       0  6150.6    0.07       0
  6197.3   0.035       0
Bank Sta=4992.1,5001.5
Exp/Cntr=0.3,0.1

Type RM Length L Ch R = 1,12590,71,71,71
BEGIN DESCRIPTION:
Deep Creek 14.5
END DESCRIPTION:
XS GIS Cut Line= 4
      1317666.48      6982941.99      1317519.91      6982445.95
      1316119.72      6982142.88      1315554.94      6981662.66
#Sta/Elev= 30
  3853.3 2089.13  4006.0 2087.08  4340.1 2082.50  4431.8 2081.32  4447.2 2083.18
  4574.3 2079.34  4608.8 2080.78  4744.3 2078.61  4761.0 2077.60  4766.1 2080.43
  4805.0 2077.03  4815.5 2079.47  4846.2 2076.80  4974.4 2075.02  4974.9 2074.52
  4984.0 2075.02  5112.3 2077.36  5275.2 2078.73  5615.9 2082.62  5804.0 2085.05
  5838.0 2087.25  5852.3 2084.10  5880.8 2086.62  5960.2 2087.13  6001.7 2089.54
  6071.9 2088.36  6136.8 2091.91  6285.0 2091.66  6342.1 2094.81  6544.5 2098.49
#Mann=12,-1,0
  3853.3   0.045       0  4006.0    0.07       0  4340.1   0.035       0
  4608.8    0.07       0  4744.3   0.035       0  4974.4   0.035       0
  4984.0   0.035       0  5112.3    0.07       0  5275.2   0.035       0
  5615.9    0.07       0  5804.0   0.035       0  5960.2   0.045       0
Bank Sta=4974.4,4984
Exp/Cntr=0.3,0.1

Type RM Length L Ch R = 1,12519,759,759,759
BEGIN DESCRIPTION:
Deep Creek 14.0
END DESCRIPTION:
XS GIS Cut Line= 5
      1317755.01      6982888.02      1317581.03      6982410.36
      1316937.87      6982253.56      1316169.64      6982069.10
      1315590.32      6981602.77
#Sta/Elev= 30
  3830.5 2091.44  3970.4 2089.28  4054.5 2086.82  4213.7 2087.05  4267.6 2084.42
  4313.7 2084.23  4330.7 2081.52  4337.5 2084.53  4489.4 2080.90  4592.1 2080.76
  4639.8 2078.23  4955.9 2076.84  5085.2 2075.03  5085.7 2074.53  5094.9 2075.03
  5145.8 2075.57  5230.1 2079.21  5305.1 2077.51  5429.4 2080.08  5651.6 2081.46
  5735.2 2082.77  5764.8 2085.91  5829.3 2084.31  5915.6 2087.69  5965.1 2085.95
  6051.5 2089.58  6107.5 2088.19  6207.7 2091.82  6328.3 2091.43  6534.6 2097.76
#Mann=12,-1,0
  3830.5   0.045       0  3970.4    0.07       0  4267.6   0.035       0
  4489.4   0.045       0  4639.8   0.035       0  4955.9    0.07       0
  5085.2    0.07       0  5094.9    0.07       0  5145.8   0.035       0
  5429.4   0.045       0  5651.6   0.035       0  5829.3   0.045       0
Bank Sta=5085.2,5094.9
Exp/Cntr=0.3,0.1

Type RM Length L Ch R = 1,11760,1006,1006,1006
BEGIN DESCRIPTION:
Deep Creek 13.5
END DESCRIPTION:
XS GIS Cut Line= 3
      1317932.08      6982659.09      1317264.89      6981847.64
      1315669.49      6981514.14
#Sta/Elev= 30
  3931.1 2093.66  4030.2 2090.36  4107.4 2090.41  4136.1 2086.68  4160.9 2087.41
  4170.6 2087.54  4228.7 2085.67  4289.6 2087.56  4313.3 2085.02  4391.5 2086.12
  4806.4 2075.02  4984.1 2073.35  5000.6 2072.76  5005.7 2071.76  5007.3 2069.00
  5007.8 2068.50  5017.1 2069.00  5050.5 2073.32  5165.4 2069.21  5185.8 2073.88
  5312.9 2073.11  5482.1 2073.24  5540.1 2076.35  6079.6 2082.07  6330.0 2086.87
  6369.3 2089.56  6424.3 2088.65  6469.2 2092.08  6503.7 2091.00  6611.5 2095.72
#Mann=9,-1,0
  3931.1   0.045       0  4030.2   0.035       0  4160.9   0.045       0
  4170.6   0.035       0  4289.6   0.045       0  4806.4    0.07       0
  5007.3    0.07       0  5017.1    0.07       0  5312.9   0.045       0
Bank Sta=5007.3,5017.1
Exp/Cntr=0.3,0.1

Type RM Length L Ch R = 1,10754,439,439,439
BEGIN DESCRIPTION:
Deep Creek 13.0
END DESCRIPTION:
XS GIS Cut Line= 4
      1318015.32      6982005.97      1317346.90      6981259.42
      1317105.00      6981238.00      1315759.13      6981246.40
#Sta/Elev= 30
  3750.2 2087.99  3777.1 2085.85  4060.5 2083.16  4244.4 2076.52  4535.2 2075.50
  4648.1 2072.47  4794.3 2073.39  4838.2 2071.20  4939.2 2070.32  4965.0 2069.30
  4969.9 2067.06  4970.4 2066.56  4980.1 2067.06  4992.6 2069.47  5200.5 2071.31
  5315.1 2074.76  5405.1 2073.98  5455.1 2076.62  5535.1 2075.37  5685.1 2078.89
  5715.1 2077.80  5815.1 2082.00  5925.1 2082.65  5955.1 2085.05  5985.1 2083.87
  6085.1 2087.56  6145.1 2086.72  6195.1 2089.76  6245.1 2088.65  6341.0 2092.78
#Mann=5,-1,0
  3750.2   0.045       0  4838.2    0.07       0  4969.9    0.07       0
  4980.1    0.07       0  5200.5   0.045       0
Bank Sta=4969.9,4980.1
Exp/Cntr=0.3,0.1

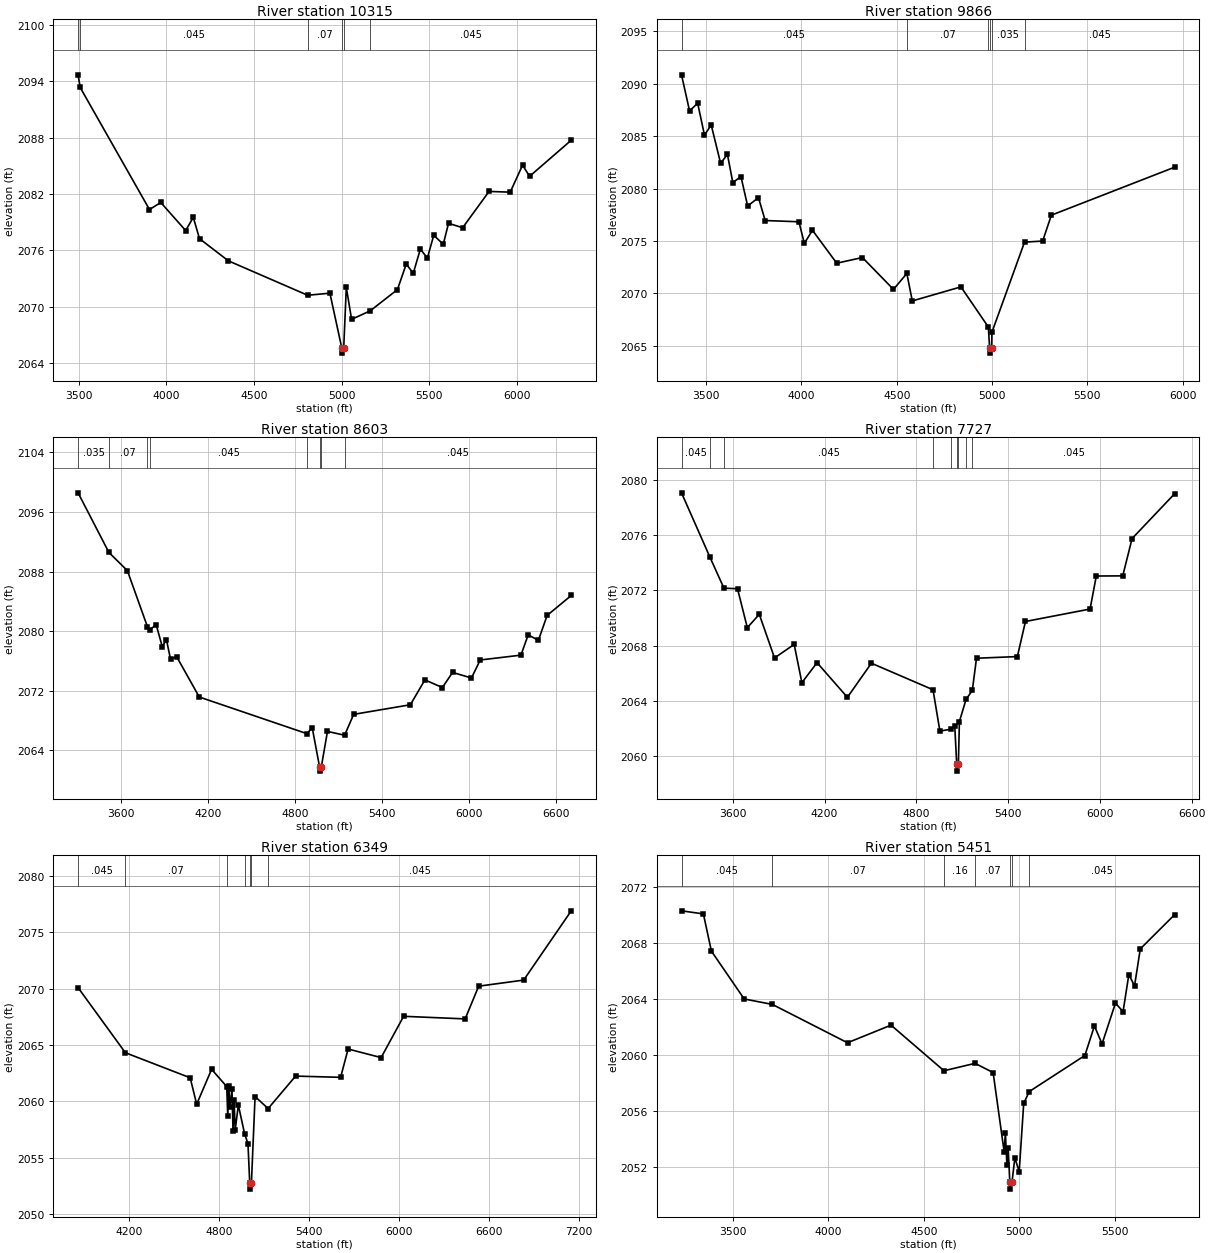
Type RM Length L Ch R = 1,10315,449,449,449
BEGIN DESCRIPTION:
Deep Creek 12.0
END DESCRIPTION:
XS GIS Cut Line= 3
      1318305.01      6981788.01      1317105.00      6980888.00
      1315798.70      6980751.74
#Sta/Elev= 30
  3495.9 2094.71  3508.0 2093.36  3903.2 2080.35  3967.8 2081.10  4109.5 2078.11
  4153.2 2079.51  4188.6 2077.24  4353.2 2074.88  4805.6 2071.21  4932.4 2071.43
  5000.8 2065.54  5001.3 2065.04  5011.1 2065.54  5026.1 2072.04  5056.2 2068.64
  5162.5 2069.55  5317.6 2071.81  5367.9 2074.53  5408.1 2073.56  5448.4 2076.13
  5488.6 2075.18  5524.9 2077.61  5579.1 2076.64  5609.2 2078.88  5689.7 2078.41
  5840.5 2082.28  5961.1 2082.20  6031.5 2085.08  6071.7 2083.89  6309.3 2087.74
#Mann=6,-1,0
  3495.9   0.035       0  3508.0   0.045       0  4805.6    0.07       0
  5000.8    0.07       0  5011.1    0.07       0  5162.5   0.045       0
Bank Sta=5000.8,5011.1
Exp/Cntr=0.3,0.1

Type RM Length L Ch R = 1,9866,1263,1263,1263
BEGIN DESCRIPTION:
Deep Creek 11.0
END DESCRIPTION:
XS GIS Cut Line= 3
      1318254.97      6981637.97      1317055.00      6980538.00
      1316101.20      6980447.79
#Sta/Elev= 30
  3371.7 2090.85  3413.9 2087.41  3456.4 2088.14  3492.2 2085.09  3527.4 2086.07
  3576.7 2082.41  3612.5 2083.26  3640.8 2080.57  3683.4 2081.15  3718.5 2078.33
  3775.2 2079.14  3810.4 2076.95  3987.4 2076.83  4015.7 2074.77  4058.3 2076.02
  4185.6 2072.88  4320.3 2073.42  4483.1 2070.38  4553.2 2071.90  4581.8 2069.28
  4836.8 2070.62  4980.6 2066.79  4987.2 2064.80  4987.7 2064.30  4997.8 2064.80
  4999.5 2066.30  5170.3 2074.89  5265.4 2074.99  5310.9 2077.46  5957.6 2082.04
#Mann=6,-1,0
  3371.7   0.045       0  4553.2    0.07       0  4980.6   0.035       0
  4987.2   0.035       0  4997.8   0.035       0  5170.3   0.045       0
Bank Sta=4987.2,4997.8
Exp/Cntr=0.3,0.1

Type RM Length L Ch R = 1,8603,876,876,876
BEGIN DESCRIPTION:
Deep Creek 10.0
END DESCRIPTION:
XS GIS Cut Line= 3
      1318854.99      6981287.99      1317655.00      6980088.00
      1315959.05      6979992.12
#Sta/Elev= 30
  3307.5 2098.58  3519.9 2090.57  3646.9 2088.14  3784.8 2080.62  3804.6 2080.22
  3844.9 2080.90  3887.3 2077.92  3915.6 2078.88  3943.9 2076.26  3986.3 2076.58
  4141.9 2071.17  4883.0 2066.25  4919.7 2067.05  4970.9 2061.72  4971.4 2061.22
  4981.7 2061.72  5024.6 2066.55  5142.8 2066.04  5204.9 2068.84  5595.5 2070.13
  5695.6 2073.47  5815.8 2072.44  5885.9 2074.47  6016.2 2073.72  6076.3 2076.14
  6356.7 2076.79  6406.8 2079.52  6476.9 2078.77  6537.0 2082.12  6703.2 2084.80
#Mann=8,-1,0
  3307.5   0.035       0  3519.9    0.07       0  3784.8   0.035       0
  3804.6   0.045       0  4883.0    0.07       0  4970.9    0.07       0
  4981.7    0.07       0  5142.8   0.045       0
Bank Sta=4970.9,4981.7
Exp/Cntr=0.3,0.1

Type RM Length L Ch R = 1,7727,1378,1378,1378
BEGIN DESCRIPTION:
Deep Creek 9.0
END DESCRIPTION:
XS GIS Cut Line= 3
      1318848.68      6980569.86      1317505.00      6979488.00
      1316031.02      6979215.73
#Sta/Elev= 30
  3265.1 2079.05  3451.9 2074.37  3542.5 2072.15  3631.3 2072.11  3695.3 2069.29
  3773.6 2070.26  3873.2 2067.10  4001.6 2068.08  4052.0 2065.31  4151.2 2066.76
  4349.5 2064.25  4506.3 2066.72  4909.2 2064.80  4954.2 2061.81  5025.1 2061.94
  5051.2 2062.21  5064.2 2059.41  5064.7 2058.91  5075.1 2059.41  5081.7 2062.50
  5125.3 2064.10  5166.1 2064.75  5193.6 2067.08  5460.6 2067.20  5513.5 2069.74
  5935.9 2070.64  5976.6 2073.03  6149.5 2073.04  6210.5 2075.74  6489.1 2078.99
#Mann=9,-1,0
  3265.1   0.045       0  3451.9   0.035       0  3542.5   0.045       0
  4909.2    0.07       0  5025.1    0.16       0  5064.2    0.07       0
  5075.1    0.16       0  5125.3    0.07       0  5166.1   0.045       0
Bank Sta=5064.2,5075.1
Exp/Cntr=0.3,0.1

Type RM Length L Ch R = 1,6349,898,898,898
BEGIN DESCRIPTION:
Deep Creek 8.0
END DESCRIPTION:
XS GIS Cut Line= 3
      1319204.99      6979687.99      1318305.00      6978988.00
      1316158.03      6979064.61
#Sta/Elev= 30
  3859.8 2070.09  4175.3 2064.32  4607.2 2062.10  4650.7 2059.76  4750.2 2062.85
  4851.1 2061.32  4857.9 2058.67  4864.2 2061.33  4872.4 2059.47  4885.9 2061.10
  4893.2 2057.34  4899.5 2060.16  4907.7 2057.51  4928.5 2059.68  4970.4 2057.12
  4992.7 2056.26  5004.4 2052.73  5004.9 2052.23  5015.5 2052.73  5040.0 2060.44
  5126.9 2059.37  5310.2 2062.25  5610.4 2062.14  5660.4 2064.65  5880.5 2063.89
  6030.6 2067.55  6440.9 2067.32  6530.9 2070.22  6831.1 2070.76  7148.3 2076.90
#Mann=7,-1,0
  3859.8   0.045       0  4175.3    0.07       0  4851.1    0.16       0
  4970.4    0.07       0  5004.4    0.07       0  5015.5    0.07       0
  5126.9   0.045       0
Bank Sta=5004.4,5015.5
Exp/Cntr=0.3,0.1

Type RM Length L Ch R = 1,5451,456,456,456
BEGIN DESCRIPTION:
Deep Creek 7.0
END DESCRIPTION:
XS GIS Cut Line= 3
      1319255.02      6979688.02      1318155.00      6978288.00
      1318155.00      6977487.97
#Sta/Elev= 30
  3232.5 2070.30  3347.0 2070.08  3388.9 2067.42  3560.6 2064.00  3708.1 2063.61
  4101.1 2060.87  4328.8 2062.13  4605.9 2058.87  4768.4 2059.40  4863.0 2058.74
  4920.8 2053.07  4927.1 2054.44  4935.2 2052.12  4941.6 2053.37  4950.3 2050.91
  4950.8 2050.41  4961.8 2050.91  4976.8 2052.65  4999.4 2051.65  5023.0 2056.53
  5051.6 2057.38  5343.0 2059.96  5393.0 2062.07  5433.0 2060.79  5503.0 2063.70
  5543.0 2063.10  5573.0 2065.74  5603.0 2064.94  5633.0 2067.58  5813.0 2070.03
#Mann=7,-1,0
  3232.5   0.045       0  3708.1    0.07       0  4605.9    0.16       0
  4768.4    0.07       0  4950.3    0.07       0  4961.8    0.07       0
  5051.6   0.045       0
Bank Sta=4950.3,4961.8
Exp/Cntr=0.3,0.1