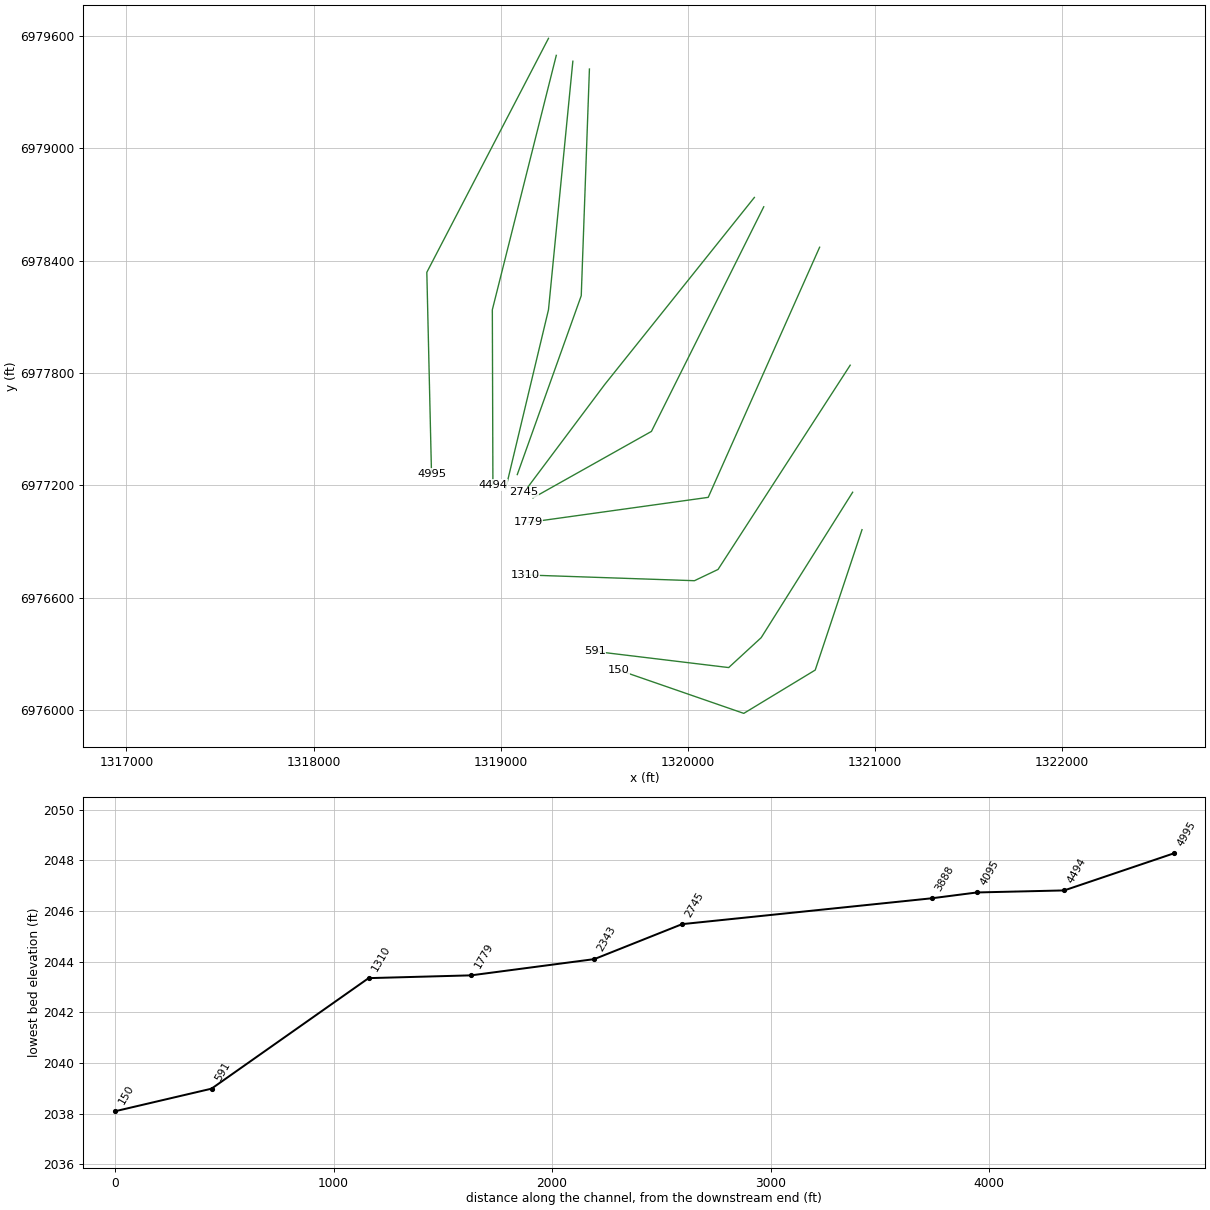
HEC-RAS study Deep Creek.prj: Deep Creek Base Level Engineering

--- Deep Creek.g01 (geometry) --- (continued)

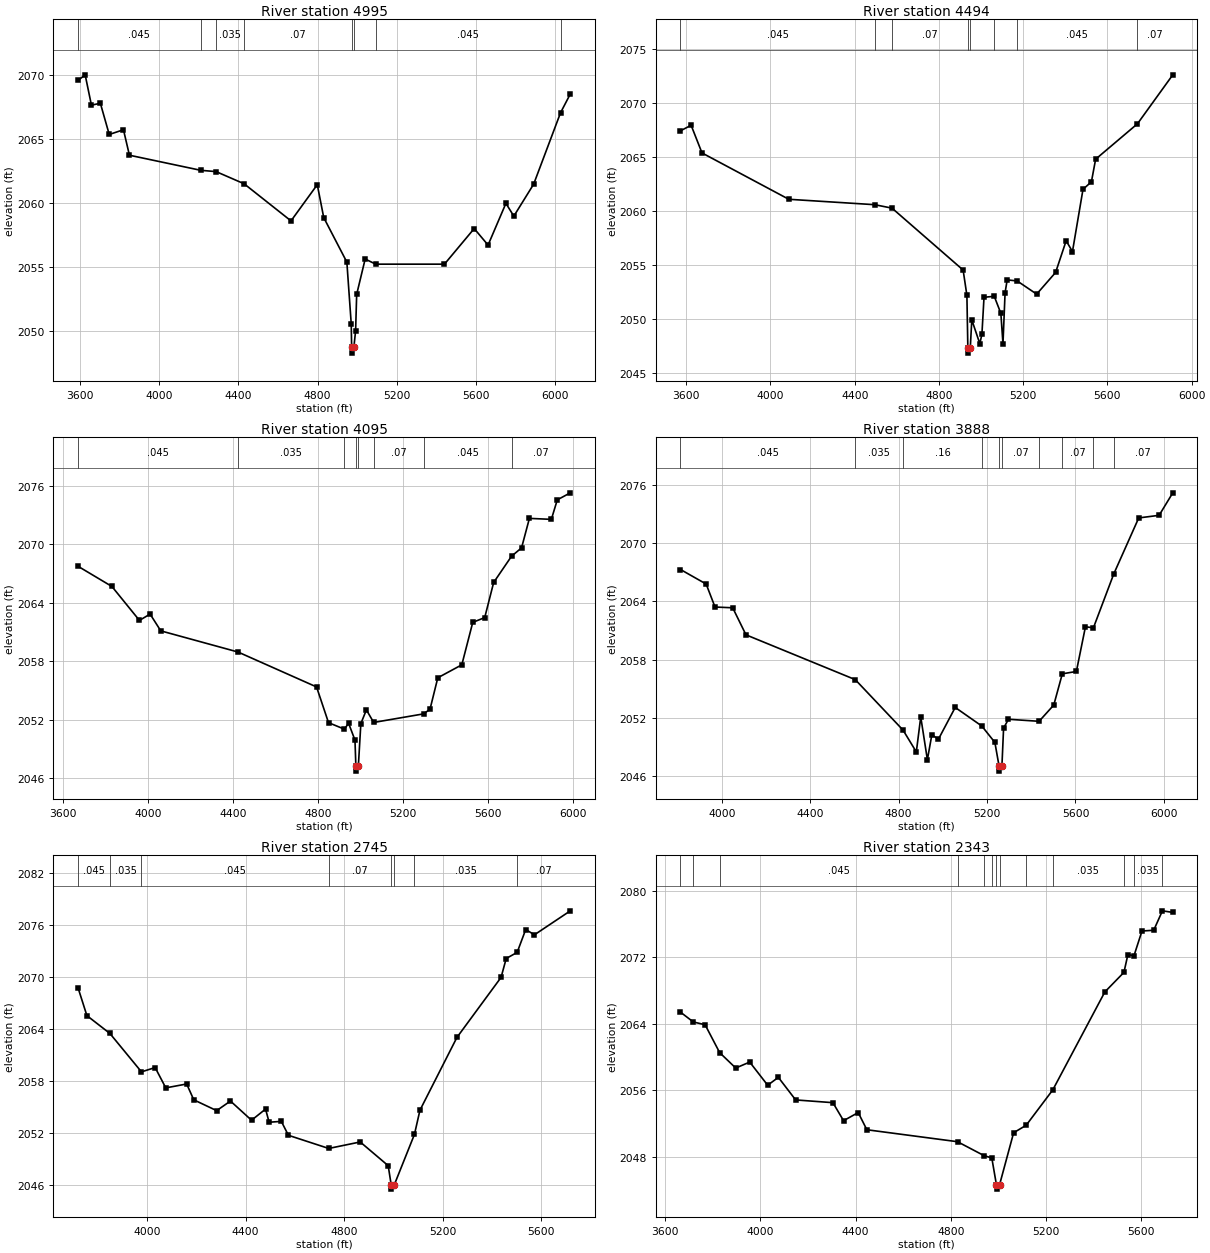
Type RM Length L Ch R = 1,4995,501,501,501
BEGIN DESCRIPTION:
Deep Creek 6.0
END DESCRIPTION:
XS GIS Cut Line= 3
      1319255.01      6979588.01      1318605.00      6978338.00
      1318630.00      6977263.00
#Sta/Elev= 30
  3591.1 2069.57  3627.1 2070.01  3658.7 2067.64  3703.8 2067.79  3748.5 2065.35
  3820.4 2065.72  3850.4 2063.73  4210.7 2062.55  4287.7 2062.45  4429.0 2061.50
  4665.8 2058.60  4798.4 2061.43  4830.9 2058.86  4947.6 2055.38  4969.7 2050.56
  4971.7 2048.77  4972.2 2048.27  4983.3 2048.77  4991.8 2050.02  4997.2 2052.86
  5040.0 2055.62  5093.4 2055.22  5440.1 2055.22  5590.2 2058.00  5660.2 2056.71
  5750.2 2059.97  5790.2 2058.97  5890.3 2061.47  6025.7 2067.04  6075.3 2068.52
#Mann=8,-1,0
  3591.1   0.045       0  4210.7    0.07       0  4287.7   0.035       0
  4429.0    0.07       0  4971.7    0.07       0  4983.3    0.07       0
  5093.4   0.045       0  6025.7    0.07       0
Bank Sta=4971.7,4983.3
Exp/Cntr=0.3,0.1

Type RM Length L Ch R = 1,4494,399,399,399
BEGIN DESCRIPTION:
Deep Creek 5.0
END DESCRIPTION:
XS GIS Cut Line= 3
      1319296.63      6979496.97      1318955.00      6978138.00
      1318958.09      6977201.56
#Sta/Elev= 30
  3572.7 2067.39  3623.2 2067.90  3674.8 2065.34  4087.1 2061.05  4494.7 2060.55
  4577.2 2060.23  4914.8 2054.50  4932.7 2052.16  4937.2 2047.31  4937.7 2046.81
  4948.8 2047.31  4956.0 2049.89  4994.0 2047.69  5004.0 2048.55  5014.0 2051.98
  5062.6 2052.07  5094.0 2050.49  5104.0 2047.67  5114.0 2052.40  5124.0 2053.59
  5171.6 2053.49  5264.0 2052.27  5354.0 2054.28  5404.0 2057.21  5434.0 2056.21
  5484.0 2061.97  5524.0 2062.67  5544.0 2064.76  5742.7 2068.04  5910.4 2072.57
#Mann=8,-1,0
  3572.7   0.045       0  4494.7   0.035       0  4577.2    0.07       0
  4937.2    0.07       0  4948.8    0.07       0  5062.6    0.07       0
  5171.6   0.045       0  5742.7    0.07       0
Bank Sta=4937.2,4948.8
Exp/Cntr=0.3,0.1

Type RM Length L Ch R = 1,4095,207,207,207
BEGIN DESCRIPTION:
Deep Creek 4.0
END DESCRIPTION:
XS GIS Cut Line= 3
      1319385.17      6979465.71      1319255.00      6978138.00
      1319026.25      6977181.14
#Sta/Elev= 30
  3670.8 2067.73  3830.3 2065.66  3959.9 2062.18  4010.1 2062.83  4060.4 2061.11
  4424.1 2058.94  4793.9 2055.36  4850.1 2051.70  4925.1 2051.03  4944.6 2051.64
  4974.7 2049.91  4979.0 2047.23  4979.5 2046.73  4990.6 2047.23  5002.4 2051.60
  5028.5 2053.01  5062.8 2051.72  5298.1 2052.60  5328.1 2053.08  5364.7 2056.30
  5477.8 2057.63  5529.3 2061.98  5585.6 2062.47  5627.7 2066.07  5711.9 2068.76
  5759.1 2069.62  5796.0 2072.64  5899.4 2072.54  5927.3 2074.54  5988.7 2075.26
#Mann=8,-1,0
  3670.8   0.045       0  4424.1   0.035       0  4925.1    0.16       0
  4979.0    0.07       0  4990.6    0.16       0  5062.8    0.07       0
  5298.1   0.045       0  5711.9    0.07       0
Bank Sta=4979,4990.6
Exp/Cntr=0.3,0.1

Type RM Length L Ch R = 1,3888,1143,1143,1143
BEGIN DESCRIPTION:
Deep Creek 3.0
END DESCRIPTION:
XS GIS Cut Line= 3
      1319473.71      6979424.02      1319430.00      6978213.00
      1319088.29      6977257.36
#Sta/Elev= 30
  3813.5 2067.30  3929.6 2065.80  3969.6 2063.43  4049.7 2063.35  4109.7 2060.56
  4603.9 2055.94  4820.2 2050.73  4880.2 2048.48  4900.2 2052.09  4930.2 2047.68
  4950.3 2050.24  4980.3 2049.80  5056.1 2053.07  5176.5 2051.15  5235.5 2049.46
  5254.6 2047.00  5255.1 2046.50  5267.3 2047.00  5274.9 2050.94  5297.0 2051.85
  5435.5 2051.64  5501.9 2053.32  5540.5 2056.54  5604.1 2056.78  5645.1 2061.39
  5681.3 2061.29  5773.0 2066.83  5886.1 2072.62  5978.4 2072.89  6040.2 2075.21
#Mann=10,-1,0
  3813.5   0.045       0  4603.9   0.035       0  4820.2    0.16       0
  5176.5    0.07       0  5254.6    0.07       0  5267.3    0.07       0
  5435.5   0.035       0  5540.5    0.07       0  5681.3   0.045       0
  5773.0    0.07       0
Bank Sta=5254.6,5267.3
Exp/Cntr=0.3,0.1

Type RM Length L Ch R = 1,2745,402,402,402
BEGIN DESCRIPTION:
Deep Creek 2.0
END DESCRIPTION:
XS GIS Cut Line= 3
      1320355.00      6978738.00      1319555.00      6977738.00
      1319124.73      6977163.61
#Sta/Elev= 30
  3719.6 2068.75  3755.6 2065.53  3848.9 2063.47  3977.1 2059.03  4032.6 2059.53
  4075.8 2057.18  4160.6 2057.63  4189.4 2055.80  4282.3 2054.55  4338.3 2055.66
  4423.9 2053.44  4480.8 2054.73  4495.2 2053.21  4544.8 2053.31  4573.6 2051.70
  4737.2 2050.18  4865.0 2050.93  4978.6 2048.19  4990.7 2045.98  4991.2 2045.48
  5003.4 2045.98  5085.1 2051.80  5107.5 2054.60  5257.6 2063.01  5436.8 2069.95
  5457.6 2072.13  5502.1 2072.84  5536.8 2075.48  5572.2 2074.87  5717.9 2077.64
#Mann=8,-1,0
  3719.6   0.045       0  3848.9   0.035       0  3977.1   0.045       0
  4737.2    0.07       0  4990.7    0.07       0  5003.4    0.07       0
  5085.1   0.035       0  5502.1    0.07       0
Bank Sta=4990.7,5003.4
Exp/Cntr=0.3,0.1

Type RM Length L Ch R = 1,2343,564,564,564
BEGIN DESCRIPTION:
Deep Creek 1.0
END DESCRIPTION:
XS GIS Cut Line= 3
      1320405.00      6978688.00      1319805.00      6977488.00
      1319172.17      6977132.69
#Sta/Elev= 30
  3664.7 2065.41  3718.4 2064.23  3768.1 2063.89  3829.3 2060.53  3896.7 2058.68
  3955.4 2059.40  4030.9 2056.61  4075.6 2057.56  4148.3 2054.84  4304.8 2054.51
  4349.5 2052.34  4411.0 2053.32  4447.3 2051.25  4828.0 2049.81  4939.0 2048.14
  4972.1 2047.85  4991.6 2044.60  4992.1 2044.10  5004.4 2044.60  5063.7 2050.89
  5116.4 2051.79  5228.2 2056.05  5446.7 2067.84  5526.9 2070.20  5543.6 2072.35
  5569.0 2072.19  5602.7 2075.18  5652.0 2075.27  5688.5 2077.61  5732.1 2077.42
#Mann=13,-1,0
  3664.7   0.045       0  3718.4   0.035       0  3829.3   0.045       0
  4828.0   0.035       0  4939.0    0.07       0  4972.1    0.16       0
  4991.6    0.07       0  5004.4    0.16       0  5116.4    0.07       0
  5228.2   0.035       0  5526.9    0.07       0  5569.0   0.035       0
  5688.5    0.07       0
Bank Sta=4991.6,5004.4
Exp/Cntr=0.3,0.1

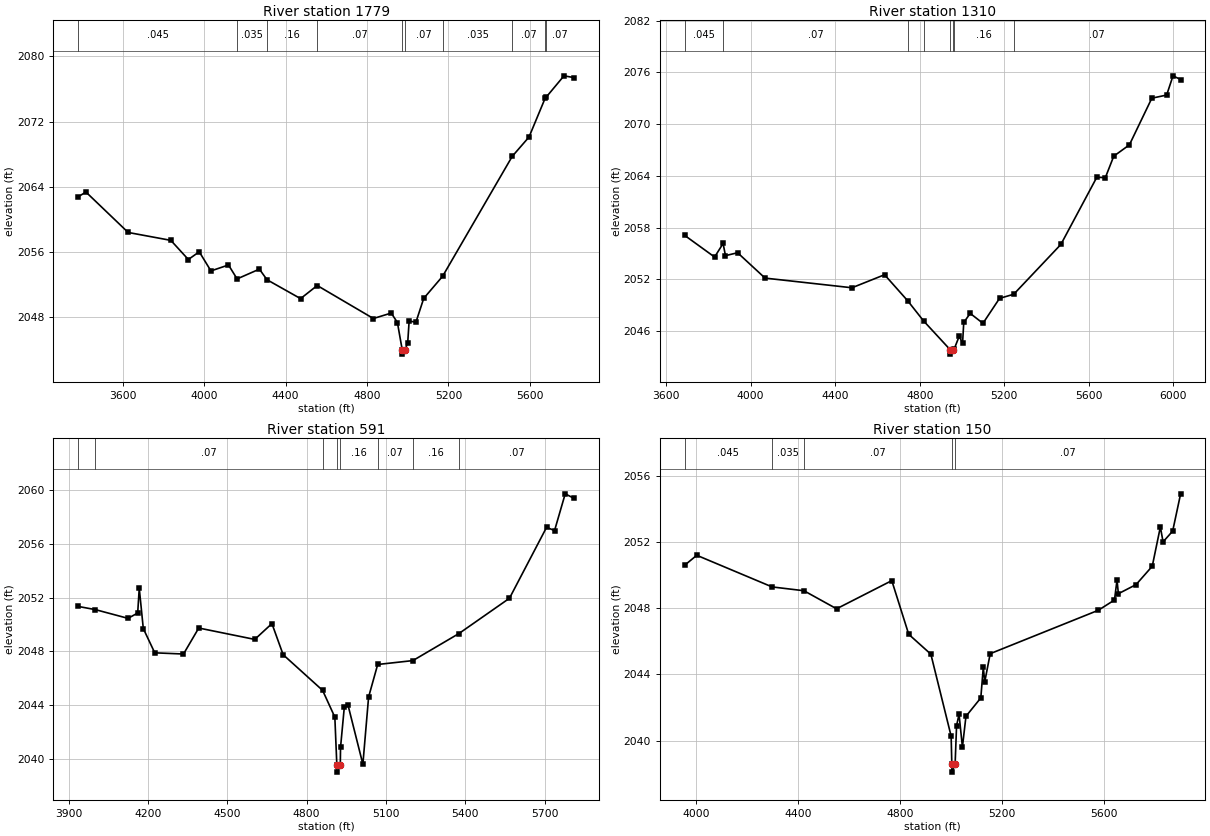
Type RM Length L Ch R = 1,1779,469,469,469
BEGIN DESCRIPTION:
Deep Creek 0.9
END DESCRIPTION:
XS GIS Cut Line= 3
      1320703.51      6978471.95      1320108.30      6977135.65
      1319145.48      6977001.44
#Sta/Elev= 30
  3382.2 2062.77  3420.1 2063.35  3627.4 2058.39  3837.0 2057.42  3922.9 2055.07
  3976.4 2056.02  4033.9 2053.67  4120.0 2054.40  4162.3 2052.69  4271.7 2053.89
  4309.1 2052.59  4474.0 2050.27  4555.7 2051.88  4831.5 2047.83  4919.1 2048.50
  4949.4 2047.34  4973.2 2043.96  4973.7 2043.46  4986.2 2043.96  4999.9 2044.82
  5007.0 2047.53  5040.2 2047.37  5078.6 2050.30  5171.5 2053.02  5513.2 2067.73
  5595.6 2070.10  5675.4 2074.90  5679.8 2074.99  5767.2 2077.61  5817.2 2077.39
#Mann=10,-1,0
  3382.2   0.045       0  4162.3   0.035       0  4309.1    0.16       0
  4555.7    0.07       0  4973.2    0.07       0  4986.2    0.07       0
  5171.5   0.035       0  5513.2    0.07       0  5675.4   0.035       0
  5679.8    0.07       0
Bank Sta=4973.2,4986.2
Exp/Cntr=0.3,0.1

Type RM Length L Ch R = 1,1310,719,719,719
BEGIN DESCRIPTION:
Deep Creek 0.8
END DESCRIPTION:
XS GIS Cut Line= 4
      1320866.90      6977841.72      1320160.82      6976750.51
      1320034.83      6976690.41      1319128.97      6976721.30
#Sta/Elev= 30
  3688.2 2057.11  3829.7 2054.60  3869.9 2056.17  3881.1 2054.76  3938.5 2055.10
  4068.4 2052.16  4479.4 2051.04  4633.6 2052.55  4742.4 2049.55  4818.1 2047.20
  4944.4 2043.85  4944.9 2043.35  4957.4 2043.85  4962.6 2043.92  4986.4 2045.41
  5002.6 2044.64  5008.2 2047.02  5038.7 2048.07  5099.0 2046.92  5177.4 2049.81
  5244.6 2050.29  5467.5 2056.06  5637.6 2063.85  5677.7 2063.79  5717.7 2066.29
  5791.6 2067.60  5897.8 2073.01  5967.8 2073.37  5997.9 2075.60  6033.9 2075.17
#Mann=8,-1,0
  3688.2   0.045       0  3869.9    0.07       0  4742.4    0.16       0
  4818.1    0.07       0  4944.4    0.07       0  4957.4    0.07       0
  4962.6    0.16       0  5244.6    0.07       0
Bank Sta=4944.4,4957.4
Exp/Cntr=0.3,0.1

Type RM Length L Ch R = 1,591,441,441,441
BEGIN DESCRIPTION:
Deep Creek 0.6
END DESCRIPTION:
XS GIS Cut Line= 4
      1320880.01      6977163.01      1320391.31      6976386.03
      1320217.70      6976226.31      1319501.41      6976312.85
#Sta/Elev= 30
  3936.5 2051.35  4001.8 2051.11  4124.9 2050.46  4161.4 2050.86  4167.3 2052.71
  4182.6 2049.70  4225.9 2047.89  4334.6 2047.80  4392.3 2049.74  4604.0 2048.89
  4669.0 2050.07  4711.4 2047.75  4860.6 2045.09  4906.9 2043.09  4914.5 2039.49
  4915.0 2038.99  4927.5 2039.49  4928.4 2040.83  4942.6 2043.82  4956.8 2043.98
  5012.9 2039.58  5034.5 2044.59  5068.9 2047.02  5202.0 2047.31  5376.3 2049.33
  5567.2 2051.96  5707.5 2057.25  5737.7 2057.01  5778.0 2059.75  5811.8 2059.41
#Mann=8,-1,0
  3936.5   0.045       0  4001.8    0.07       0  4860.6    0.16       0
  4914.5    0.07       0  4927.5    0.16       0  5068.9    0.07       0
  5202.0    0.16       0  5376.3    0.07       0
Bank Sta=4914.5,4927.5
Exp/Cntr=0.3,0.1

Type RM Length L Ch R = 1,150,0,0,0
BEGIN DESCRIPTION:
Deep Creek 0.5
END DESCRIPTION:
XS GIS Cut Line= 4
      1320930.00      6976962.99      1320680.00      6976213.00
      1320298.31      6975981.58      1319629.96      6976213.01
#Sta/Elev= 30
  3955.8 2050.59  4003.2 2051.19  4298.6 2049.28  4423.3 2049.05  4551.3 2047.96
  4767.7 2049.66  4834.1 2046.42  4920.9 2045.22  5000.4 2040.27  5003.0 2038.60
  5003.5 2038.10  5016.0 2038.60  5021.7 2040.91  5031.4 2041.59  5044.6 2039.61
  5058.5 2041.47  5116.7 2042.58  5126.4 2044.42  5132.2 2043.56  5153.5 2045.25
  5577.2 2047.87  5640.7 2048.49  5650.7 2049.70  5656.0 2048.87  5725.3 2049.42
  5788.8 2050.53  5820.6 2052.90  5831.2 2052.00  5868.8 2052.65  5900.0 2054.90
#Mann=5,-1,0
  3955.8   0.045       0  4298.6   0.035       0  4423.3    0.07       0
  5003.0    0.07       0  5016.0    0.07       0
Bank Sta=5003,5016
Exp/Cntr=0.3,0.1

Chan Stop Cuts=-1