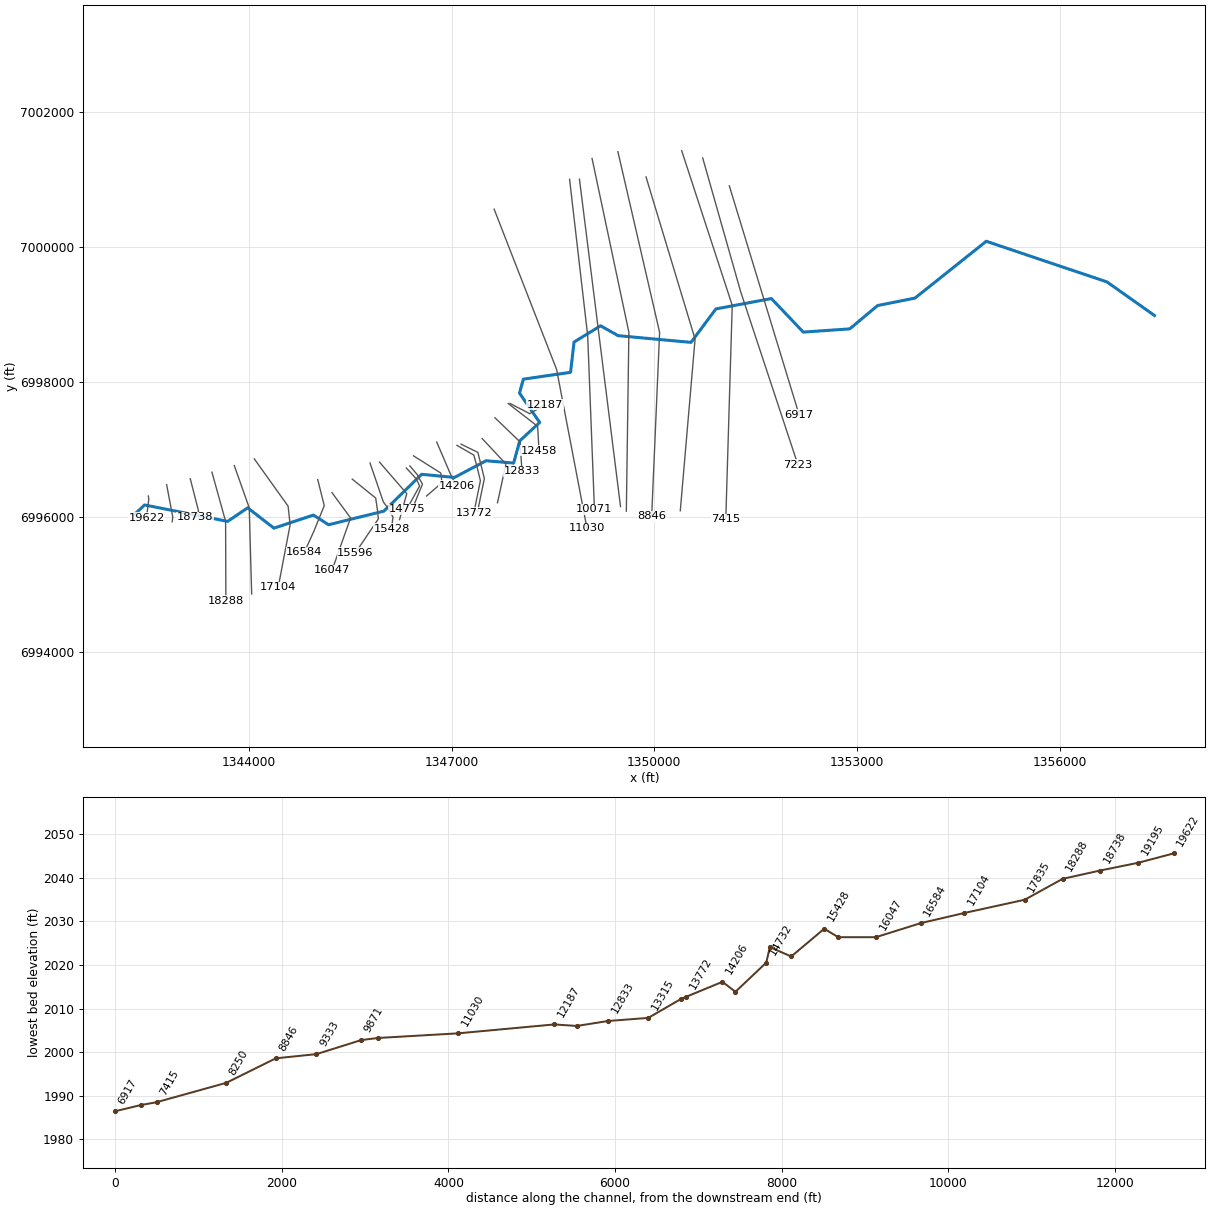
--- Hackberry Creek.prj (project) ---

Proj Title=Hackberry Creek Base Level Engineering
Current Plan=p01
Default Exp/Contr=0.3,0.1
English Units
Geom File=g01
Flow File=f01
Plan File=p01
BEGIN DESCRIPTION:
Hackberry Creek
END DESCRIPTION:

--- Hackberry Creek.p01 (plan) ---

Plan Title=Multiple Run
Short Identifier=Multiple
Geom File=g01
Flow File=f01
Subcritical Flow
K Sum by GR= 0
Std Step Tol= 0.01
Critical Tol= 0.01
Num of Std Step Trials= 20
Max Error Tol= 0.3
Flow Tol Ratio= 0.001
Split Flow NTrial= 30
Split Flow Tol= 0.02
Split Flow Ratio= 0.02
Log Output Level= 0
Friction Slope Method= 1
Unsteady Friction Slope Method= 2
Unsteady Bridges Friction Slope Method= 1
Parabolic Critical Depth
Global Vel Dist=  1 , 1 , 1
Global Log Level= 0
CheckData=True
Encroach Param= -1, 0, 0, 0
BEGIN DESCRIPTION:
Multiple Run
END DESCRIPTION:

--- Hackberry Creek.f01 (steady flow) ---

Flow Title=Multiple
Number of Profiles=7
Profile Names=10-year,25-year,50-year,1pct_min,100-year,1pct_plu,500-year
River Rch & RM= Hackberry Creek,Reach-1,19622
     157     213     259     157     313     624     461
River Rch & RM= Hackberry Creek,Reach-1,18288
     334     476     596     371     741    1478    1157
River Rch & RM= Hackberry Creek,Reach-1,14206
     568     833    1062     672    1341    2676    2166
River Rch & RM= Hackberry Creek,Reach-1,11030
     766    1136    1460     930    1856    3704    3042
River Rch & RM= Hackberry Creek,Reach-1,7415
     771    1141    1464     930    1857    3704    3030
Boundary for River Rch & Prof#=Hackberry Creek,Reach-1,1
Up Type=0
Dn Type=3
Dn Slope=0.005
Boundary for River Rch & Prof#=Hackberry Creek,Reach-1,2
Up Type=0
Dn Type=3
Dn Slope=0.005
Boundary for River Rch & Prof#=Hackberry Creek,Reach-1,3
Up Type=0
Dn Type=3
Dn Slope=0.005
Boundary for River Rch & Prof#=Hackberry Creek,Reach-1,4
Up Type=0
Dn Type=3
Dn Slope=0.005
Boundary for River Rch & Prof#=Hackberry Creek,Reach-1,5
Up Type=0
Dn Type=3
Dn Slope=0.005
Boundary for River Rch & Prof#=Hackberry Creek,Reach-1,6
Up Type=0
Dn Type=3
Dn Slope=0.005
Boundary for River Rch & Prof#=Hackberry Creek,Reach-1,7
Up Type=0
Dn Type=3
Dn Slope=0.005

--- Hackberry Creek.g01 (geometry) ---

Geom Title=Existing Conditions

River Reach=Hackberry Creek,Reach-1
Reach XY= 30
      1342305.00      6996038.00      1342455.08      6996180.70
      1343684.87      6995937.60      1343982.16      6996138.18
      1344370.06      6995837.27      1344955.10      6996030.68
      1345180.03      6995887.50      1345999.15      6996090.06
      1346556.47      6996634.47      1347043.16      6996588.59
      1347510.93      6996835.76      1347918.73      6996801.16
      1348008.51      6997129.52      1348304.51      6997403.22
      1348005.00      6997838.00      1348062.85      6998044.19
      1348761.70      6998145.47      1348813.13      6998594.08
      1349206.63      6998834.88      1349465.62      6998688.60
      1350544.57      6998589.03      1350913.28      6999084.93
      1351734.65      6999238.41      1352206.46      6998741.54
      1352894.56      6998789.05      1353306.50      6999134.39
      1353861.17      6999245.86      1354915.50      7000086.80
      1356703.50      6999484.38      1357405.00      6998988.00

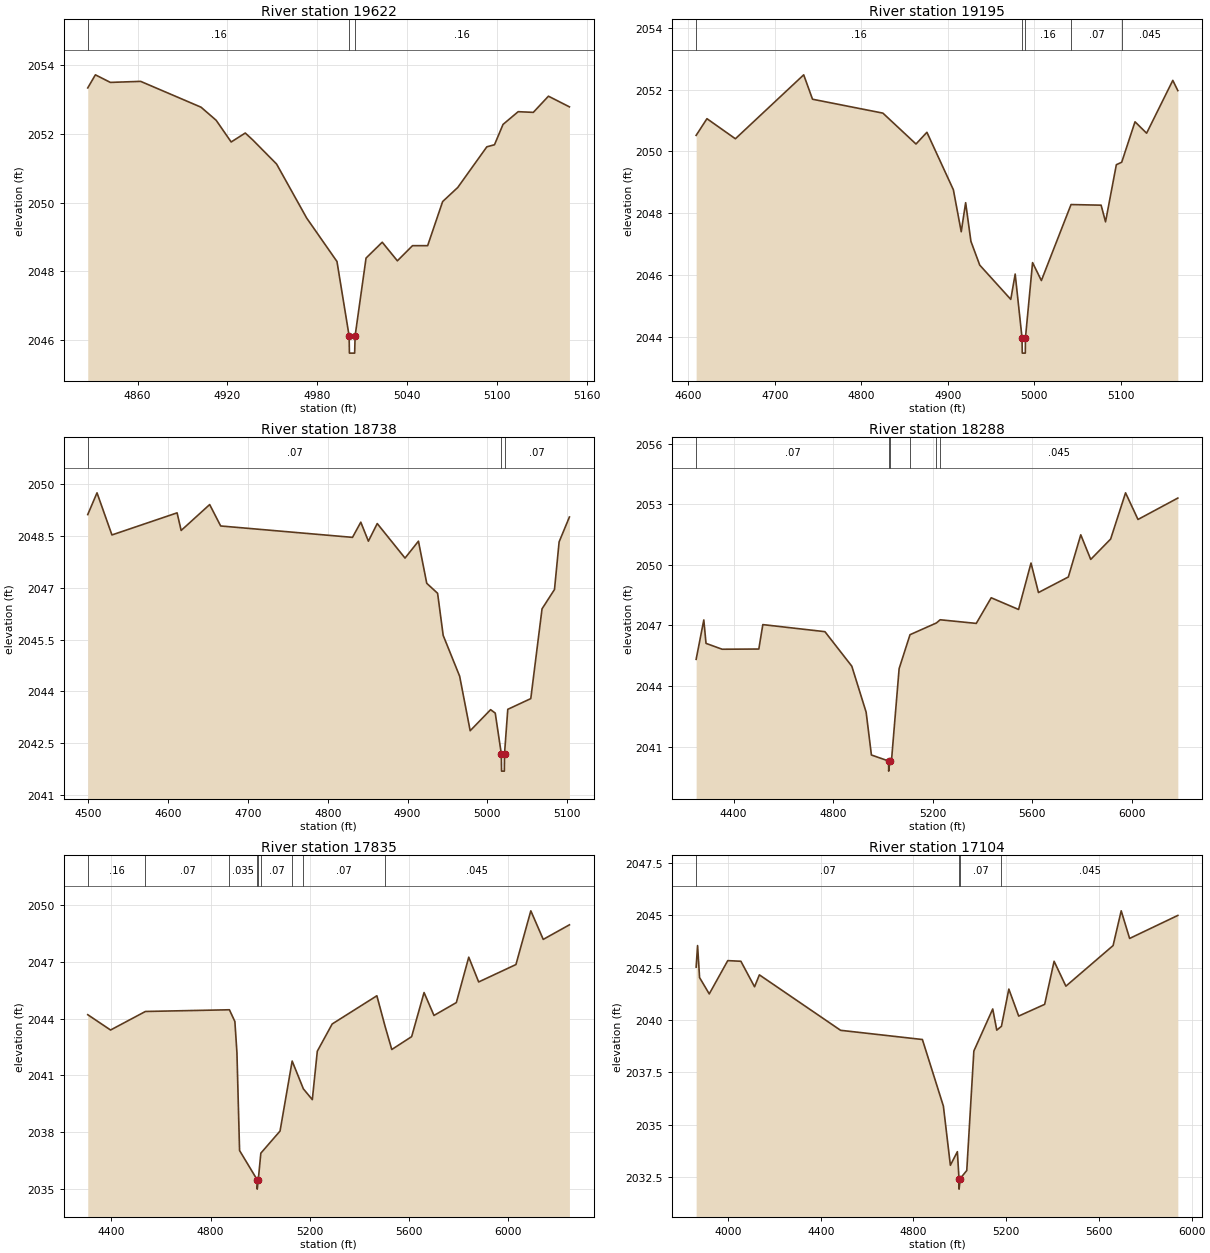
Type RM Length L Ch R = 1,19622,427,427,427
BEGIN DESCRIPTION:
Hackberry Creek 17.0
END DESCRIPTION:
XS GIS Cut Line= 3
      1342511.67      6996313.03      1342517.50      6996264.45
      1342483.71      6995994.08
#Sta/Elev= 30
  4826.8 2053.33  4831.9 2053.71  4841.9 2053.49  4862.1 2053.52  4902.4 2052.77
  4912.5 2052.39  4922.5 2051.76  4931.9 2052.02  4936.9 2051.82  4952.8 2051.12
  4972.9 2049.55  4993.1 2048.29  5001.2 2046.13  5001.4 2045.63  5004.9 2045.63
  5005.2 2046.13  5012.5 2048.39  5023.3 2048.85  5033.4 2048.31  5043.5 2048.75
  5053.6 2048.75  5063.6 2050.03  5073.7 2050.44  5093.1 2051.62  5098.2 2051.68
  5103.9 2052.27  5114.0 2052.64  5124.1 2052.62  5134.2 2053.09  5148.2 2052.78
#Mann=3,-1,0
  4826.8    0.16       0  5001.2    0.07       0  5005.2    0.16       0
Bank Sta=5001.2,5005.2
Exp/Cntr=0.3,0.1

Type RM Length L Ch R = 1,19195,457,457,457
BEGIN DESCRIPTION:
Hackberry Creek 16.0
END DESCRIPTION:
XS GIS Cut Line= 3
      1342782.05      6996480.25      1342872.78      6996002.55
      1342864.20      6995932.21
#Sta/Elev= 30
  4608.9 2050.52  4621.4 2051.06  4654.3 2050.41  4733.3 2052.48  4743.5 2051.69
  4824.9 2051.24  4863.2 2050.24  4875.8 2050.62  4906.4 2048.76  4915.5 2047.40
  4920.6 2048.34  4926.7 2047.09  4936.9 2046.32  4972.8 2045.21  4977.9 2046.03
  4985.8 2043.97  4986.1 2043.47  4989.6 2043.47  4989.8 2043.97  4998.0 2046.40
  5008.2 2045.82  5042.5 2048.28  5077.3 2048.26  5082.4 2047.72  5094.9 2049.57
  5101.1 2049.65  5116.5 2050.96  5129.9 2050.59  5160.2 2052.30  5166.0 2051.97
#Mann=5,-1,0
  4608.9    0.16       0  4985.8    0.07       0  4989.8    0.16       0
  5042.5    0.07       0  5101.1   0.045       0
Bank Sta=4985.8,4989.8
Exp/Cntr=0.3,0.1

Type RM Length L Ch R = 1,18738,450,450,450
BEGIN DESCRIPTION:
Hackberry Creek 15.0
END DESCRIPTION:
XS GIS Cut Line= 3
      1343131.69      6996569.27      1343255.00      6996088.00
      1343200.90      6995996.28
#Sta/Elev= 30
  4499.4 2049.12  4511.0 2049.75  4529.7 2048.53  4611.3 2049.17  4616.4 2048.66
  4652.1 2049.41  4665.9 2048.79  4831.0 2048.46  4841.4 2048.90  4850.9 2048.35
  4862.0 2048.86  4896.8 2047.86  4913.6 2048.35  4924.0 2047.13  4937.6 2046.84
  4944.6 2045.62  4965.2 2044.44  4978.4 2042.86  5004.0 2043.47  5009.8 2043.37
  5017.4 2042.19  5017.7 2041.69  5021.2 2041.69  5021.4 2042.19  5025.5 2043.48
  5054.3 2043.79  5068.4 2046.39  5084.0 2046.95  5089.8 2048.33  5102.7 2049.05
#Mann=3,-1,0
  4499.4    0.07       0  5017.4    0.07       0  5021.4    0.07       0
Bank Sta=5017.4,5021.4
Exp/Cntr=0.3,0.1

Type RM Length L Ch R = 1,18288,453,453,453
BEGIN DESCRIPTION:
Hackberry Creek 14.0
END DESCRIPTION:
XS GIS Cut Line= 3
      1343452.76      6996666.27      1343655.00      6995938.00
      1343658.83      6994758.03
#Sta/Elev= 30
  4249.3 2045.32  4280.1 2047.27  4289.0 2046.11  4353.8 2045.82  4501.2 2045.83
  4517.3 2047.04  4766.9 2046.69  4874.9 2044.98  4932.5 2042.70  4953.7 2040.58
  5022.8 2040.28  5023.1 2039.78  5027.5 2040.28  5035.1 2040.41  5065.1 2044.86
  5108.8 2046.54  5214.6 2047.12  5230.0 2047.28  5375.1 2047.10  5435.1 2048.37
  5545.1 2047.79  5595.1 2050.09  5625.1 2048.63  5745.1 2049.40  5795.1 2051.49
  5835.1 2050.27  5915.1 2051.28  5975.1 2053.57  6025.1 2052.25  6185.1 2053.31
#Mann=6,-1,0
  4249.3    0.07       0  5022.8    0.07       0  5027.5    0.07       0
  5108.8   0.035       0  5214.6    0.07       0  5230.0   0.045       0
Bank Sta=5022.8,5027.5
Exp/Cntr=0.3,0.1

Type RM Length L Ch R = 1,17835,731,731,731
BEGIN DESCRIPTION:
Hackberry Creek 13.0
END DESCRIPTION:
XS GIS Cut Line= 3
      1343783.25      6996764.68      1344005.00      6996138.00
      1344040.77      6994862.55
#Sta/Elev= 30
  4304.8 2044.21  4396.7 2043.40  4537.1 2044.38  4875.6 2044.47  4897.6 2043.85
  4905.9 2042.20  4916.5 2037.03  4987.2 2035.49  4987.6 2034.99  4991.9 2035.49
  5002.2 2036.89  5079.6 2038.06  5128.4 2041.76  5173.6 2040.29  5209.6 2039.72
  5229.7 2042.28  5289.7 2043.72  5469.7 2045.21  5502.9 2043.59  5529.8 2042.37
  5609.8 2043.05  5659.8 2045.38  5699.8 2044.17  5789.9 2044.85  5839.9 2047.25
  5879.9 2045.94  6030.0 2046.86  6090.0 2049.70  6140.0 2048.19  6245.5 2048.96
#Mann=9,-1,0
  4304.8    0.16       0  4537.1    0.07       0  4875.6   0.035       0
  4987.2   0.035       0  4991.9   0.035       0  5002.2    0.07       0
  5128.4   0.035       0  5173.6    0.07       0  5502.9   0.045       0
Bank Sta=4987.2,4991.9
Exp/Cntr=0.3,0.1

Type RM Length L Ch R = 1,17104,520,520,520
BEGIN DESCRIPTION:
Hackberry Creek 12.0
END DESCRIPTION:
XS GIS Cut Line= 4
      1344079.98      6996863.02      1344580.00      6996163.00
      1344610.23      6995887.52      1344434.15      6994963.75
#Sta/Elev= 30
  3862.6 2042.53  3868.8 2043.56  3877.4 2042.03  3919.2 2041.25  3999.0 2042.84
  4055.6 2042.81  4114.6 2041.59  4135.4 2042.16  4485.7 2039.51  4838.6 2039.07
  4929.1 2035.89  4959.3 2033.06  4989.5 2033.71  4996.5 2032.42  4996.9 2031.92
  5001.3 2032.42  5030.0 2032.81  5060.6 2038.52  5142.0 2040.53  5159.4 2039.52
  5179.5 2039.70  5211.5 2041.48  5254.0 2040.19  5366.0 2040.75  5406.7 2042.81
  5457.6 2041.62  5661.2 2043.56  5696.2 2045.22  5732.5 2043.90  5940.4 2045.00
#Mann=4,-1,0
  3862.6    0.07       0  4996.5    0.07       0  5001.3    0.07       0
  5179.5   0.045       0
Bank Sta=4996.5,5001.3
Exp/Cntr=0.3,0.1

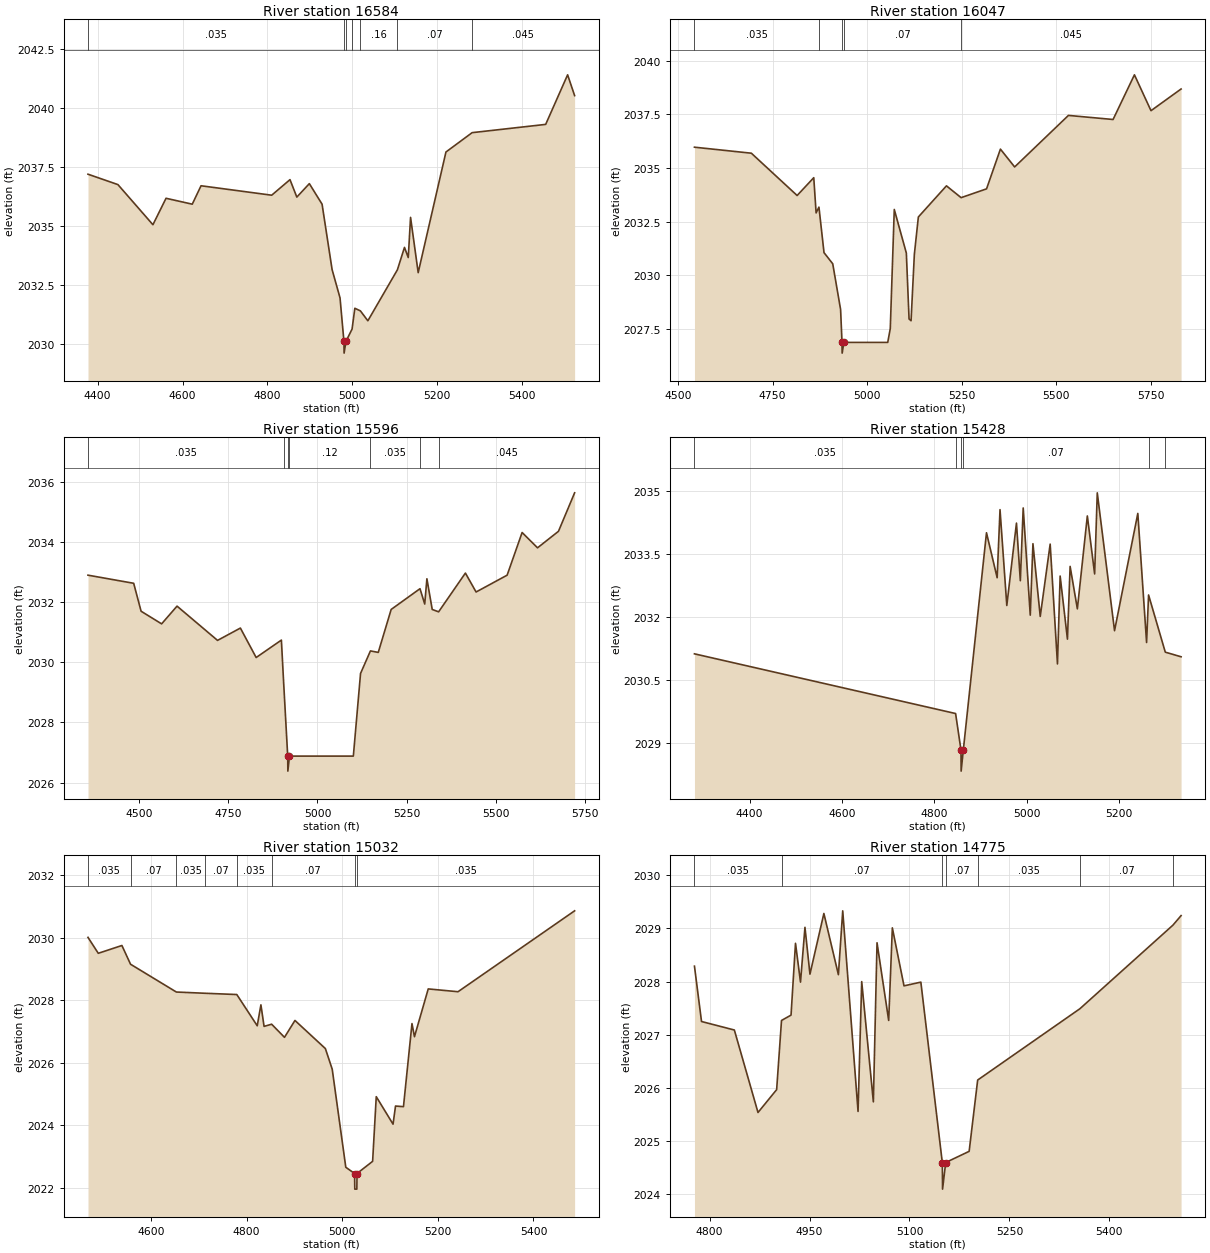
Type RM Length L Ch R = 1,16584,537,537,537
BEGIN DESCRIPTION:
Hackberry Creek 11.5
END DESCRIPTION:
XS GIS Cut Line= 4
      1345018.78      6996556.37      1345115.43      6996170.59
      1344961.50      6995790.74      1344821.35      6995481.91
#Sta/Elev= 30
  4377.3 2037.18  4447.8 2036.74  4530.3 2035.04  4561.2 2036.16  4623.0 2035.91
  4643.7 2036.69  4810.2 2036.29  4853.3 2036.95  4869.4 2036.21  4898.9 2036.78
  4928.9 2035.91  4952.5 2033.14  4971.2 2031.94  4980.4 2030.10  4980.8 2029.60
  4985.2 2030.10  4999.6 2030.62  5006.1 2031.50  5019.2 2031.39  5036.8 2030.97
  5106.4 2033.13  5123.1 2034.08  5132.0 2033.65  5137.4 2035.35  5155.4 2033.01
  5220.8 2038.12  5282.5 2038.94  5455.8 2039.29  5507.5 2041.39  5524.0 2040.51
#Mann=7,-1,0
  4377.3   0.035       0  4980.4    0.07       0  4985.2   0.035       0
  4999.6    0.07       0  5019.2    0.16       0  5106.4    0.07       0
  5282.5   0.045       0
Bank Sta=4980.4,4985.2
Exp/Cntr=0.3,0.1

Type RM Length L Ch R = 1,16047,451,451,451
BEGIN DESCRIPTION:
Hackberry Creek 11.0
END DESCRIPTION:
XS GIS Cut Line= 3
      1345230.03      6996362.96      1345505.00      6995988.00
      1345230.01      6995213.02
#Sta/Elev= 30
  4543.3 2035.97  4693.8 2035.69  4814.9 2033.72  4858.9 2034.55  4865.1 2032.91
  4872.6 2033.18  4886.0 2031.06  4909.1 2030.54  4929.9 2028.41  4933.6 2026.88
  4934.0 2026.38  4938.6 2026.88  5054.6 2026.88  5061.3 2027.52  5071.9 2033.07
  5103.8 2031.04  5111.0 2027.97  5116.3 2027.89  5125.0 2030.98  5135.6 2032.72
  5209.9 2034.17  5248.7 2033.62  5316.0 2034.03  5352.7 2035.88  5390.3 2035.05
  5532.6 2037.45  5650.7 2037.26  5707.2 2039.34  5751.0 2037.67  5830.6 2038.68
#Mann=5,-1,0
  4543.3   0.035       0  4872.6    0.07       0  4933.6    0.07       0
  4938.6    0.07       0  5248.7   0.045       0
Bank Sta=4933.6,4938.6
Exp/Cntr=0.3,0.1

Type RM Length L Ch R = 1,15596,168,168,168
BEGIN DESCRIPTION:
Hackberry Creek 10.0
END DESCRIPTION:
XS GIS Cut Line= 5
      1345529.98      6996563.02      1345877.19      6996282.69
      1345905.00      6996088.00      1345916.77      6995975.35
      1345577.16      6995471.86
#Sta/Elev= 30
  4357.0 2032.90  4485.0 2032.63  4505.8 2031.70  4563.3 2031.28  4606.5 2031.87
  4720.0 2030.73  4784.0 2031.14  4828.2 2030.16  4898.9 2030.74  4904.9 2029.39
  4916.6 2026.88  4917.0 2026.38  4921.6 2026.88  5100.5 2026.88  5120.7 2029.63
  5148.4 2030.38  5170.3 2030.33  5206.5 2031.76  5287.3 2032.45  5300.5 2031.94
  5306.6 2032.78  5321.5 2031.76  5339.4 2031.68  5414.5 2032.97  5444.4 2032.34
  5531.4 2032.90  5573.4 2034.32  5616.6 2033.81  5675.3 2034.36  5720.5 2035.64
#Mann=7,-1,0
  4357.0   0.035       0  4904.9    0.12       0  4916.6    0.07       0
  4921.6    0.12       0  5148.4   0.035       0  5287.3    0.07       0
  5339.4   0.045       0
Bank Sta=4916.6,4921.6
Exp/Cntr=0.3,0.1

Type RM Length L Ch R = 1,15428,396,396,396
BEGIN DESCRIPTION:
Hackberry Creek 09.9
END DESCRIPTION:
XS GIS Cut Line= 5
      1345792.72      6996802.77      1345990.64      6996224.63
      1346054.47      6996137.36      1346132.57      6996001.98
      1346111.73      6995824.89
#Sta/Elev= 30
  4280.8 2031.12  4846.3 2029.70  4858.0 2028.83  4858.3 2028.33  4863.0 2028.83
  4913.2 2034.00  4936.3 2032.93  4942.5 2034.55  4957.2 2032.27  4978.1 2034.23
  4986.5 2032.86  4992.7 2034.59  5008.0 2032.04  5013.8 2033.74  5029.6 2032.01
  5051.1 2033.73  5066.9 2030.88  5072.7 2032.97  5088.5 2031.47  5094.3 2033.20
  5110.0 2032.19  5131.6 2034.40  5147.4 2033.02  5153.1 2034.95  5190.5 2031.67
  5240.9 2034.46  5259.9 2031.39  5264.2 2032.52  5300.4 2031.16  5334.6 2031.05
#Mann=6,-1,0
  4280.8   0.035       0  4846.3    0.07       0  4858.0    0.07       0
  4863.0    0.07       0  5264.2   0.045       0  5300.4   0.035       0
Bank Sta=4858,4863
Exp/Cntr=0.3,0.1

Type RM Length L Ch R = 1,15032,257,257,257
BEGIN DESCRIPTION:
Hackberry Creek 9.85
END DESCRIPTION:
XS GIS Cut Line= 3
      1345932.70      6996815.59      1346336.65      6996348.94
      1346230.00      6995963.00
#Sta/Elev= 30
  4468.5 2030.01  4490.0 2029.50  4539.4 2029.75  4557.5 2029.15  4653.3 2028.26
  4714.1 2028.22  4779.7 2028.18  4822.4 2027.18  4830.1 2027.85  4836.7 2027.16
  4852.5 2027.23  4879.4 2026.81  4901.3 2027.35  4964.9 2026.45  4979.2 2025.79
  5007.6 2022.65  5026.0 2022.45  5026.4 2021.95  5030.7 2021.95  5031.1 2022.45
  5063.7 2022.84  5071.3 2024.91  5106.4 2024.03  5111.6 2024.61  5128.2 2024.59
  5146.0 2027.25  5151.2 2026.83  5180.0 2028.36  5242.3 2028.27  5486.1 2030.86
#Mann=8,-1,0
  4468.5   0.035       0  4557.5    0.07       0  4653.3   0.035       0
  4714.1    0.07       0  4779.7   0.035       0  4852.5    0.07       0
  5026.0    0.07       0  5031.1   0.035       0
Bank Sta=5026,5031.1
Exp/Cntr=0.3,0.1

Type RM Length L Ch R = 1,14775,43,43,43
BEGIN DESCRIPTION:
Hackberry Creek 09.8
END DESCRIPTION:
XS GIS Cut Line= 5
      1346330.00      6996727.75      1346420.06      6996631.18
      1346480.32      6996563.33      1346527.12      6996461.09
      1346334.96      6996115.57
#Sta/Elev= 30
  4777.2 2028.29  4787.8 2027.25  4837.1 2027.09  4872.6 2025.54  4900.6 2025.97
  4907.9 2027.27  4922.2 2027.37  4928.9 2028.72  4936.4 2027.99  4943.1 2029.02
  4950.6 2028.14  4971.5 2029.28  4993.3 2028.13  4999.8 2029.33  5022.8 2025.56
  5028.3 2028.00  5045.8 2025.74  5051.3 2028.73  5068.8 2027.27  5074.3 2029.01
  5091.8 2027.92  5117.1 2027.99  5149.3 2024.60  5149.7 2024.10  5154.4 2024.60
  5189.6 2024.81  5202.4 2026.15  5355.9 2027.49  5495.5 2029.06  5507.8 2029.24
#Mann=7,-1,0
  4777.2   0.035       0  4907.9    0.07       0  5149.3    0.07       0
  5154.4    0.07       0  5202.4   0.035       0  5355.9    0.07       0
  5495.5   0.035       0
Bank Sta=5149.3,5154.4
Exp/Cntr=0.3,0.1

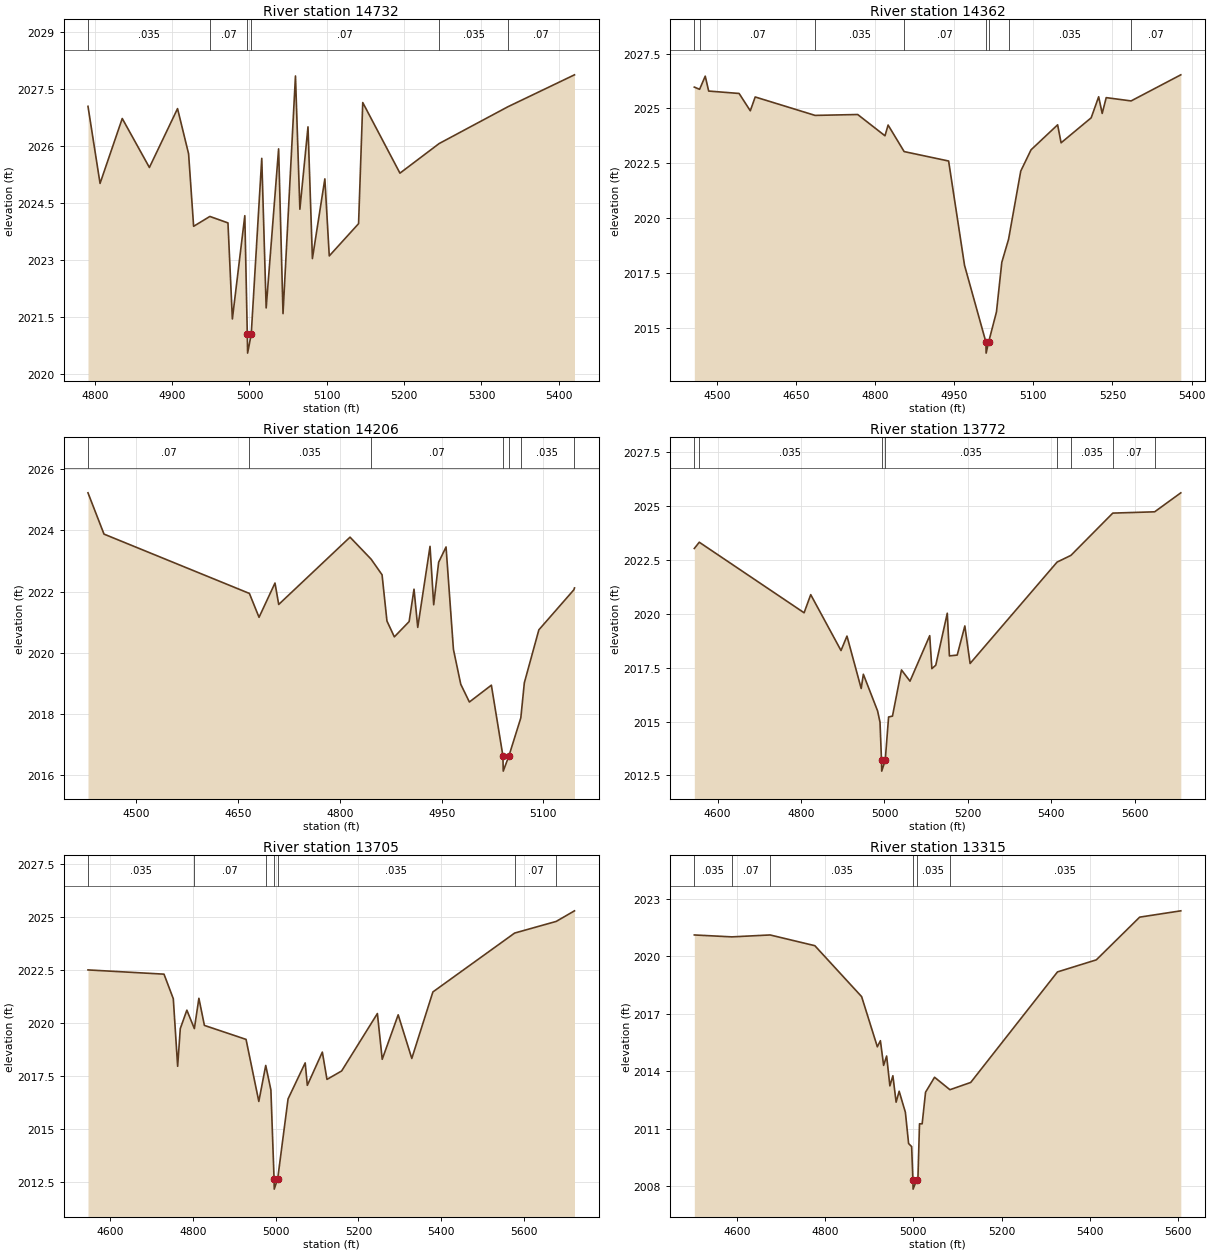
Type RM Length L Ch R = 1,14732,370,370,370
BEGIN DESCRIPTION:
Hackberry Creek 09.5
END DESCRIPTION:
XS GIS Cut Line= 4
      1346383.11      6996758.75      1346492.96      6996627.77
      1346569.00      6996488.36      1346455.66      6996211.30
#Sta/Elev= 30
  4791.2 2027.04  4806.8 2025.01  4835.5 2026.72  4870.6 2025.43  4907.0 2026.98
  4921.3 2025.79  4927.8 2023.88  4948.8 2024.14  4972.2 2023.97  4977.9 2021.44
  4994.0 2024.16  4997.2 2021.04  4997.6 2020.54  5002.3 2021.04  5015.9 2025.67
  5021.6 2021.73  5037.7 2025.92  5043.4 2021.58  5059.5 2027.84  5065.2 2024.33
  5075.7 2026.50  5081.4 2023.03  5097.5 2025.13  5103.2 2023.10  5141.1 2023.95
  5146.5 2027.14  5194.6 2025.28  5245.3 2026.06  5334.3 2027.03  5420.3 2027.87
#Mann=6,-1,0
  4791.2   0.035       0  4948.8    0.07       0  4997.2    0.07       0
  5002.3    0.07       0  5245.3   0.035       0  5334.3    0.07       0
Bank Sta=4997.2,5002.3
Exp/Cntr=0.3,0.1

Type RM Length L Ch R = 1,14362,156,156,156
BEGIN DESCRIPTION:
Hackberry Creek 09.7
END DESCRIPTION:
XS GIS Cut Line= 4
      1346437.45      6996907.85      1346840.27      6996653.61
      1346858.45      6996511.84      1346630.03      6996313.02
#Sta/Elev= 30
  4457.4 2025.97  4467.4 2025.87  4478.1 2026.47  4484.6 2025.79  4542.3 2025.68
  4563.5 2024.89  4572.8 2025.52  4686.3 2024.68  4767.1 2024.72  4818.8 2023.75
  4824.7 2024.24  4855.1 2023.03  4939.4 2022.60  4969.6 2017.84  5010.1 2014.34
  5010.5 2013.84  5015.2 2014.34  5030.1 2015.72  5040.2 2017.98  5053.0 2019.03
  5076.1 2022.14  5095.6 2023.11  5146.0 2024.25  5152.6 2023.43  5209.6 2024.57
  5223.8 2025.53  5230.5 2024.77  5238.1 2025.49  5285.3 2025.34  5379.5 2026.53
#Mann=8,-1,0
  4457.4   0.035       0  4467.4    0.07       0  4686.3   0.035       0
  4855.1    0.07       0  5010.1    0.07       0  5015.2    0.07       0
  5053.0   0.035       0  5285.3    0.07       0
Bank Sta=5010.1,5015.2
Exp/Cntr=0.3,0.1

Type RM Length L Ch R = 1,14206,434,434,434
BEGIN DESCRIPTION:
Hackberry Creek 9.0
END DESCRIPTION:
XS GIS Cut Line= 3
      1346779.99      6997113.02      1347005.00      6996588.00
      1347080.01      6996462.98
#Sta/Elev= 30
  4428.8 2025.23  4452.4 2023.88  4666.7 2021.94  4680.9 2021.16  4704.4 2022.28
  4709.9 2021.58  4815.0 2023.78  4846.1 2023.06  4862.2 2022.55  4869.4 2021.04
  4880.3 2020.52  4902.1 2021.02  4909.3 2022.08  4914.8 2020.83  4932.9 2023.48
  4938.3 2021.57  4945.6 2022.96  4956.5 2023.46  4967.4 2020.11  4978.2 2018.97
  4990.9 2018.39  5023.3 2018.94  5040.3 2016.63  5040.8 2016.13  5049.2 2016.63
  5066.7 2017.87  5071.9 2019.02  5093.3 2020.75  5144.9 2022.06  5145.8 2022.12
#Mann=7,-1,0
  4428.8    0.07       0  4666.7   0.035       0  4846.1    0.07       0
  5040.3    0.07       0  5049.2    0.07       0  5066.7   0.035       0
  5144.9    0.07       0
Bank Sta=5040.3,5049.2
Exp/Cntr=0.3,0.1

Type RM Length L Ch R = 1,13772,67,67,67
BEGIN DESCRIPTION:
Hackberry Creek 8.0
END DESCRIPTION:
XS GIS Cut Line= 5
      1347079.99      6997063.00      1347329.09      6996920.18
      1347374.67      6996757.42      1347426.75      6996539.32
      1347330.01      6996063.04
#Sta/Elev= 30
  4544.1 2023.02  4556.0 2023.31  4807.3 2020.04  4823.2 2020.88  4895.8 2018.29
  4910.1 2018.96  4944.2 2016.53  4949.4 2017.19  4983.5 2015.49  4989.3 2014.97
  4992.9 2013.20  4993.4 2012.70  5001.8 2013.20  5009.9 2015.21  5019.2 2015.25
  5040.8 2017.39  5061.2 2016.87  5108.5 2018.98  5113.6 2017.45  5123.0 2017.61
  5150.6 2020.02  5155.7 2018.04  5174.4 2018.08  5192.7 2019.43  5205.3 2017.69
  5413.9 2022.39  5447.0 2022.70  5547.4 2024.66  5647.8 2024.72  5710.5 2025.60
#Mann=8,-1,0
  4544.1    0.07       0  4556.0   0.035       0  4992.9   0.035       0
  5001.8   0.035       0  5413.9    0.07       0  5447.0   0.035       0
  5547.4    0.07       0  5647.8   0.035       0
Bank Sta=4992.9,5001.8
Exp/Cntr=0.3,0.1

Type RM Length L Ch R = 1,13705,390,390,390
BEGIN DESCRIPTION:
Hackberry Creek 7.5
END DESCRIPTION:
XS GIS Cut Line= 4
      1347140.32      6997081.64      1347389.86      6996959.24
      1347485.34      6996571.87      1347384.69      6996082.62
#Sta/Elev= 30
  4545.9 2022.50  4729.7 2022.30  4752.2 2021.14  4762.7 2017.95  4769.1 2019.73
  4785.0 2020.60  4803.1 2019.73  4814.1 2021.16  4827.4 2019.88  4928.1 2019.22
  4959.0 2016.29  4975.7 2017.99  4988.2 2016.83  4995.8 2012.65  4996.3 2012.15
  5004.7 2012.65  5029.7 2016.41  5071.1 2018.11  5076.3 2017.05  5112.6 2018.62
  5123.8 2017.33  5159.3 2017.73  5245.7 2020.44  5257.4 2018.28  5296.0 2020.38
  5328.9 2018.32  5379.9 2021.46  5577.6 2024.24  5678.1 2024.79  5722.3 2025.29
#Mann=7,-1,0
  4545.9   0.035       0  4803.1    0.07       0  4975.7   0.035       0
  4995.8   0.035       0  5004.7   0.035       0  5577.6    0.07       0
  5678.1   0.035       0
Bank Sta=4995.8,5004.7
Exp/Cntr=0.3,0.1

Type RM Length L Ch R = 1,13315,482,482,482
BEGIN DESCRIPTION:
Hackberry Creek 7.0
END DESCRIPTION:
XS GIS Cut Line= 3
      1347454.17      6997163.03      1347805.00      6996788.00
      1347679.99      6996212.98
#Sta/Elev= 30
  4503.9 2021.11  4589.0 2021.01  4675.5 2021.11  4776.9 2020.55  4882.9 2017.89
  4918.5 2015.27  4925.4 2015.59  4932.7 2014.30  4939.5 2014.79  4946.9 2013.23
  4953.7 2013.76  4961.0 2012.38  4967.9 2012.95  4982.0 2011.85  4989.3 2010.22
  4996.2 2010.06  4999.0 2008.34  4999.5 2007.84  5008.0 2008.34  5010.4 2008.39
  5014.0 2011.25  5020.0 2011.25  5027.7 2012.90  5048.1 2013.68  5082.9 2013.03
  5130.0 2013.41  5326.5 2019.18  5414.5 2019.81  5512.7 2022.04  5605.9 2022.37
#Mann=6,-1,0
  4503.9   0.035       0  4589.0    0.07       0  4675.5   0.035       0
  4999.0    0.07       0  5008.0   0.035       0  5082.9   0.035       0
Bank Sta=4999,5008
Exp/Cntr=0.3,0.1

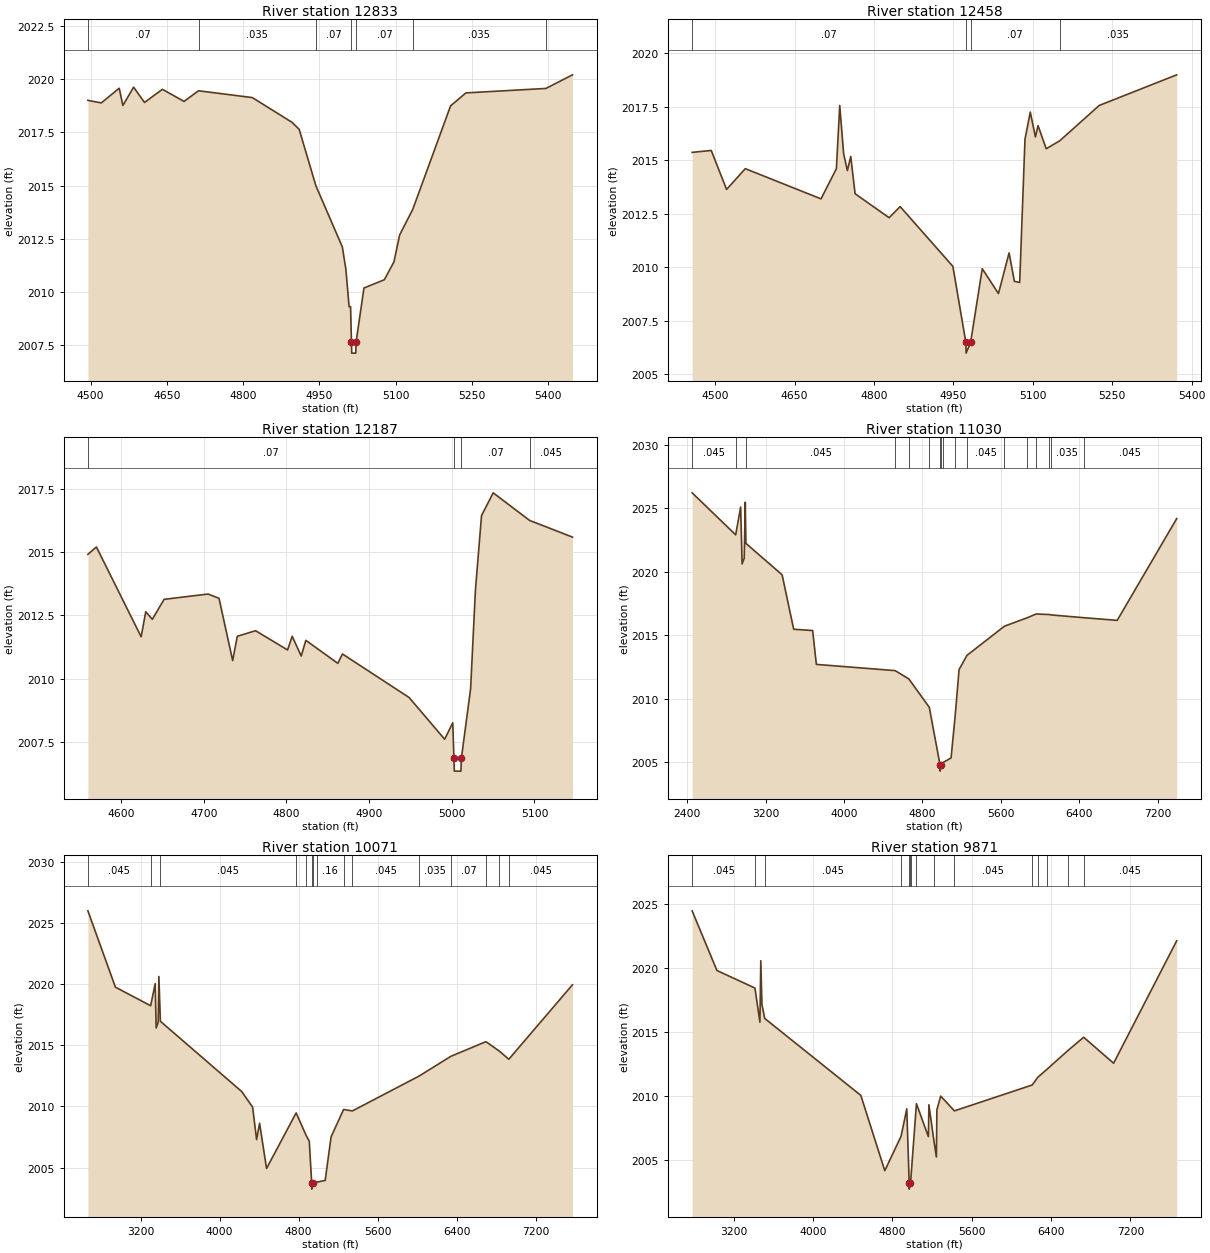
Type RM Length L Ch R = 1,12833,375,375,375
BEGIN DESCRIPTION:
Hackberry Creek 6.8
END DESCRIPTION:
XS GIS Cut Line= 3
      1347642.07      6997472.35      1348014.25      6997114.22
      1348042.34      6996678.83
#Sta/Elev= 30
  4494.8 2019.01  4521.2 2018.89  4556.4 2019.58  4563.6 2018.77  4584.7 2019.63
  4606.1 2018.91  4641.3 2019.53  4683.8 2018.96  4712.3 2019.46  4818.1 2019.14
  4896.0 2017.98  4910.2 2017.65  4943.0 2015.00  4995.1 2012.12  5002.0 2011.08
  5008.4 2009.31  5011.3 2009.31  5013.0 2007.63  5013.5 2007.13  5021.5 2007.13
  5022.0 2007.63  5037.6 2010.19  5077.7 2010.58  5096.6 2011.42  5107.7 2012.68
  5133.6 2013.89  5207.9 2018.75  5238.0 2019.36  5395.4 2019.57  5447.6 2020.21
#Mann=7,-1,0
  4494.8    0.07       0  4712.3   0.035       0  4943.0    0.07       0
  5013.0    0.07       0  5022.0    0.07       0  5133.6   0.035       0
  5395.4    0.07       0
Bank Sta=5013,5022
Exp/Cntr=0.3,0.1

Type RM Length L Ch R = 1,12458,271,271,271
BEGIN DESCRIPTION:
Hackberry Creek 6.6
END DESCRIPTION:
XS GIS Cut Line= 3
      1347838.72      6997683.03      1348274.09      6997345.97
      1348295.10      6996981.88
#Sta/Elev= 30
  4456.5 2015.36  4492.6 2015.45  4521.6 2013.63  4556.9 2014.60  4700.0 2013.19
  4729.0 2014.60  4735.3 2017.55  4742.7 2015.29  4749.8 2014.51  4756.1 2015.17
  4764.3 2013.43  4828.6 2012.31  4849.4 2012.83  4949.0 2010.04  4973.5 2006.49
  4974.0 2005.99  4982.5 2006.49  5004.5 2009.93  5035.1 2008.77  5055.2 2010.67
  5065.2 2009.34  5075.2 2009.29  5085.2 2015.97  5095.2 2017.24  5104.9 2016.08
  5109.9 2016.61  5125.3 2015.53  5150.8 2015.90  5225.4 2017.55  5371.8 2018.98
#Mann=4,-1,0
  4456.5    0.07       0  4973.5    0.07       0  4982.5    0.07       0
  5150.8   0.035       0
Bank Sta=4973.5,4982.5
Exp/Cntr=0.3,0.1

Type RM Length L Ch R = 1,12187,1157,1157,1157
BEGIN DESCRIPTION:
Hackberry Creek 6.5
END DESCRIPTION:
XS GIS Cut Line= 3
      1347865.85      6997684.20      1348157.55      6997533.14
      1348380.03      6997663.02
#Sta/Elev= 30
  4559.9 2014.91  4570.2 2015.20  4624.3 2011.65  4629.9 2012.64  4637.8 2012.34
  4652.1 2013.13  4705.3 2013.34  4718.5 2013.17  4735.0 2010.71  4740.6 2011.67
  4762.7 2011.89  4801.4 2011.13  4807.0 2011.67  4817.9 2010.89  4823.5 2011.51
  4862.2 2010.60  4867.8 2010.97  4948.4 2009.25  4991.4 2007.60  5001.2 2008.25
  5002.6 2006.84  5003.1 2006.34  5011.1 2006.34  5011.6 2006.84  5022.8 2009.60
  5028.6 2013.49  5036.0 2016.44  5050.1 2017.34  5094.1 2016.25  5146.0 2015.59
#Mann=4,-1,0
  4559.9    0.07       0  5002.6    0.07       0  5011.6    0.07       0
  5094.1   0.045       0
Bank Sta=5002.6,5011.6
Exp/Cntr=0.3,0.1

Type RM Length L Ch R = 1,11030,959,959,959
BEGIN DESCRIPTION:
Hackberry Creek 6.0
END DESCRIPTION:
XS GIS Cut Line= 3
      1347629.99      7000563.03      1348555.00      6998188.00
      1349004.10      6995838.13
#Sta/Elev= 30
  2451.4 2026.22  2895.6 2022.91  2946.2 2025.10  2961.2 2020.62  2982.6 2021.07
  2993.4 2025.48  2999.5 2022.24  3369.0 2019.76  3487.0 2015.47  3680.2 2015.37
  3718.3 2012.70  4521.5 2012.21  4661.8 2011.55  4869.6 2009.32  4979.2 2004.79
  4979.7 2004.29  4991.3 2004.79  5007.7 2004.96  5091.8 2005.33  5134.1 2008.69
  5173.3 2012.29  5253.8 2013.41  5635.7 2015.71  5866.6 2016.37  5958.9 2016.67
  6094.5 2016.63  6111.2 2016.60  6445.3 2016.38  6785.9 2016.17  7392.6 2024.19
#Mann=17,-1,0
  2451.4   0.045       0  2895.6   0.035       0  2999.5   0.045       0
  4521.5   0.035       0  4661.8   0.045       0  4869.6    0.07       0
  4979.2    0.07       0  4991.3    0.07       0  5007.7    0.16       0
  5134.1    0.07       0  5253.8   0.045       0  5635.7   0.035       0
  5866.6    0.07       0  5958.9   0.035       0  6094.5    0.07       0
  6111.2   0.035       0  6445.3   0.045       0
Bank Sta=4979.2,4991.3
Exp/Cntr=0.3,0.1

Type RM Length L Ch R = 1,10071,200,200,200
BEGIN DESCRIPTION:
Hackberry Creek 5.0
END DESCRIPTION:
XS GIS Cut Line= 3
      1348747.16      7001004.80      1349015.19      6998687.55
      1349115.21      6996115.90
#Sta/Elev= 30
  2667.3 2026.01  2945.9 2019.76  3302.9 2018.24  3348.6 2020.05  3358.7 2016.42
  3378.8 2016.88  3386.1 2020.63  3401.1 2016.97  4224.4 2011.22  4335.1 2009.94
  4375.4 2007.28  4405.6 2008.62  4476.1 2004.92  4775.8 2009.47  4874.0 2007.68
  4908.9 2007.15  4933.1 2003.73  4933.6 2003.23  4945.2 2003.73  4983.2 2003.80
  5069.6 2003.94  5129.6 2007.51  5256.4 2009.75  5344.8 2009.63  6019.9 2012.48
  6341.9 2014.10  6697.0 2015.30  6831.0 2014.54  6928.9 2013.86  7573.6 2019.96
#Mann=15,-1,0
  2667.3   0.045       0  3302.9   0.035       0  3401.1   0.045       0
  4775.8   0.035       0  4874.0    0.07       0  4933.1    0.07       0
  4945.2    0.07       0  4983.2    0.16       0  5256.4    0.07       0
  5344.8   0.045       0  6019.9   0.035       0  6341.9    0.07       0
  6697.0   0.035       0  6831.0    0.07       0  6928.9   0.045       0
Bank Sta=4933.1,4945.2
Exp/Cntr=0.3,0.1

Type RM Length L Ch R = 1,9871,538,538,538
BEGIN DESCRIPTION:
Hackberry Creek 4.7
END DESCRIPTION:
XS GIS Cut Line= 2
      1348893.37      7001006.36      1349501.38      6996156.12
#Sta/Elev= 30
  2779.6 2024.48  3029.9 2019.82  3413.2 2018.45  3463.3 2015.79  3472.2 2020.58
  3483.4 2017.19  3511.5 2016.08  4481.2 2010.07  4723.1 2004.19  4887.5 2006.88
  4944.8 2009.02  4969.0 2003.25  4969.5 2002.75  4981.1 2003.25  4985.7 2003.53
  5042.3 2009.42  5162.9 2006.85  5168.0 2009.34  5214.4 2006.75  5243.4 2005.26
  5248.5 2008.95  5287.4 2010.01  5425.4 2008.86  6209.6 2010.88  6267.6 2011.49
  6355.0 2012.08  6573.1 2013.59  6729.4 2014.61  7031.0 2012.58  7667.8 2022.14
#Mann=15,-1,0
  2779.6   0.045       0  3413.2   0.035       0  3511.5   0.045       0
  4887.5   0.035       0  4969.0    0.07       0  4981.1   0.035       0
  4985.7    0.07       0  5042.3    0.16       0  5214.4    0.07       0
  5425.4   0.045       0  6209.6   0.035       0  6267.6    0.07       0
  6355.0   0.045       0  6573.1   0.035       0  6729.4   0.045       0
Bank Sta=4969,4981.1
Exp/Cntr=0.3,0.1

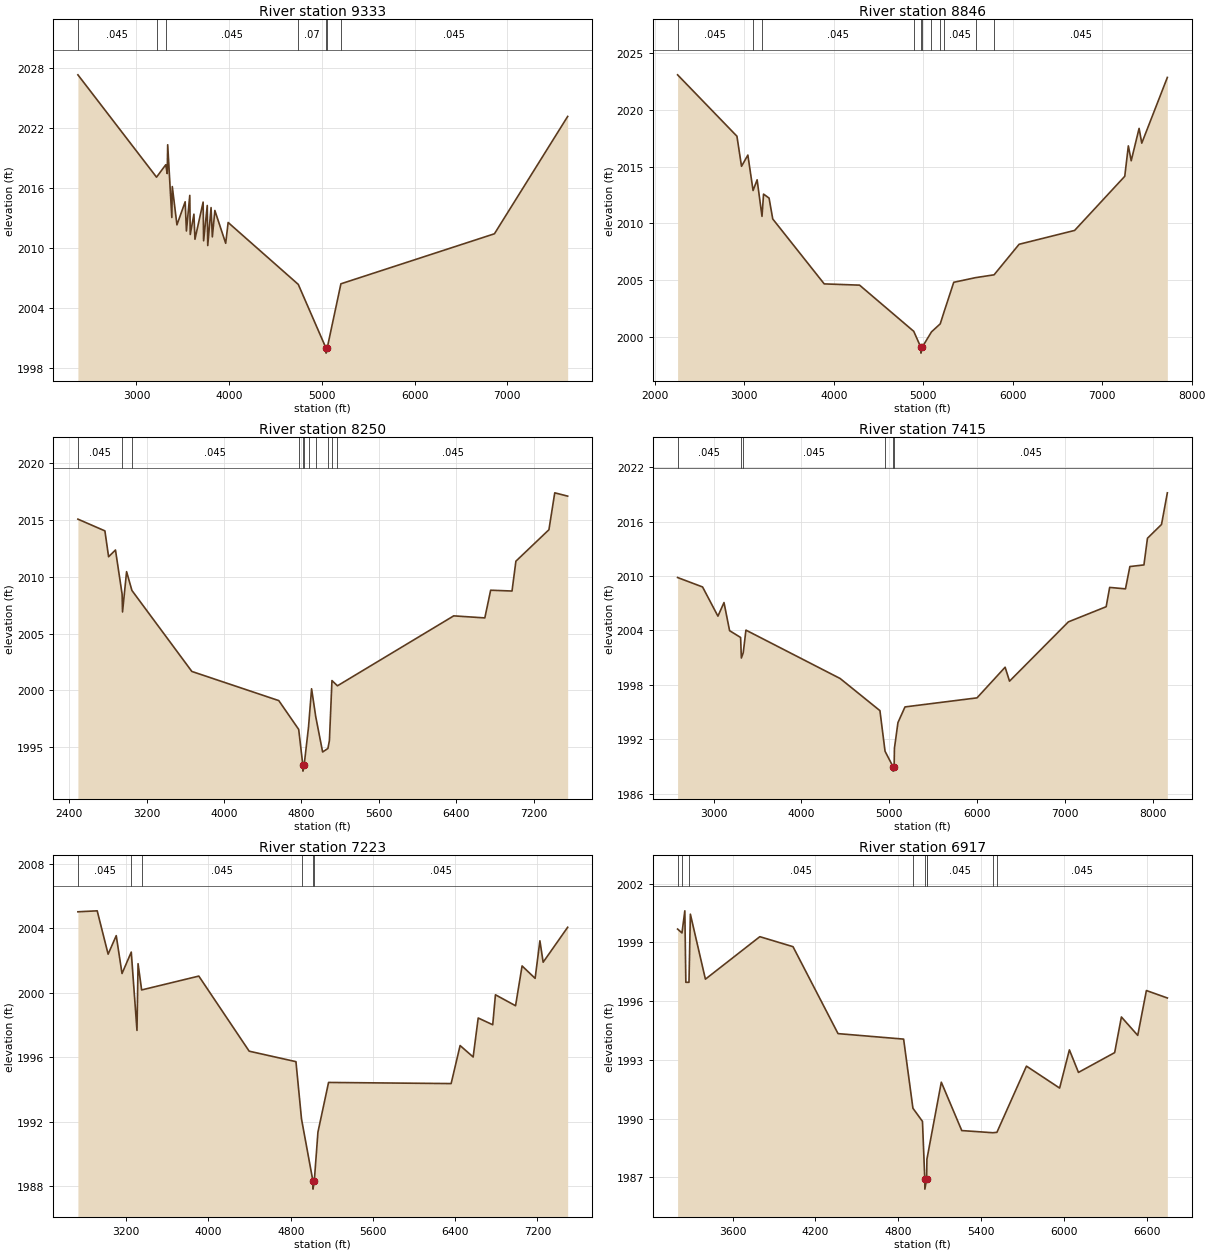
Type RM Length L Ch R = 1,9333,487,487,487
BEGIN DESCRIPTION:
Hackberry Creek 4.0
END DESCRIPTION:
XS GIS Cut Line= 3
      1349079.99      7001313.03      1349625.05      6998738.59
      1349587.44      6996088.16
#Sta/Elev= 30
  2368.5 2027.34  3216.5 2017.11  3316.0 2018.35  3331.7 2017.47  3336.9 2020.35
  3381.4 2013.08  3386.5 2016.17  3436.7 2012.34  3525.4 2014.65  3538.9 2011.73
  3575.1 2015.29  3580.2 2011.38  3619.7 2013.41  3630.9 2010.90  3719.1 2014.62
  3724.2 2010.75  3763.7 2014.28  3768.8 2010.27  3804.7 2014.07  3818.5 2011.14
  3845.6 2013.78  3962.4 2010.50  3988.7 2012.58  4745.3 2006.39  5044.2 2000.02
  5044.7 1999.52  5056.9 2000.02  5205.1 2006.45  6860.8 2011.45  7650.7 2023.18
#Mann=7,-1,0
  2368.5   0.045       0  3216.5   0.035       0  3316.0   0.045       0
  4745.3    0.07       0  5044.2    0.07       0  5056.9    0.07       0
  5205.1   0.045       0
Bank Sta=5044.2,5056.9
Exp/Cntr=0.3,0.1

Type RM Length L Ch R = 1,8846,596,596,596
BEGIN DESCRIPTION:
Hackberry Creek 3.0
END DESCRIPTION:
XS GIS Cut Line= 3
      1349462.43      7001414.53      1350080.00      6998738.05
      1349962.47      6996012.38
#Sta/Elev= 30
  2253.2 2023.08  2916.7 2017.67  2968.0 2015.02  3038.9 2016.01  3097.1 2012.89
  3142.5 2013.83  3196.9 2010.61  3214.3 2012.57  3275.9 2012.22  3317.0 2010.38
  3892.4 2004.66  4287.6 2004.55  4893.3 2000.48  4973.2 1999.06  4973.7 1998.56
  4985.9 1999.06  5091.3 2000.43  5189.4 2001.14  5227.7 2002.09  5340.4 2004.80
  5583.8 2005.21  5791.2 2005.46  6071.0 2008.15  6691.6 2009.37  7252.1 2014.14
  7292.2 2016.82  7324.2 2015.51  7412.3 2018.36  7442.3 2017.06  7728.2 2022.85
#Mann=11,-1,0
  2253.2   0.045       0  3097.1   0.035       0  3196.9   0.045       0
  4893.3   0.035       0  4973.2   0.035       0  4985.9   0.035       0
  5091.3   0.045       0  5189.4    0.07       0  5227.7   0.045       0
  5583.8   0.035       0  5791.2   0.045       0
Bank Sta=4973.2,4985.9
Exp/Cntr=0.3,0.1

Type RM Length L Ch R = 1,8250,835,835,835
BEGIN DESCRIPTION:
Hackberry Creek 2.0
END DESCRIPTION:
XS GIS Cut Line= 3
      1349879.10      7001039.52      1350605.00      6998638.00
      1350386.05      6996095.03
#Sta/Elev= 30
  2490.4 2015.04  2769.4 2014.01  2807.6 2011.74  2878.7 2012.33  2947.2 2008.46
  2951.6 2006.89  2993.4 2010.43  3048.6 2008.78  3667.9 2001.67  4566.4 1999.11
  4772.1 1996.58  4815.2 1993.42  4815.7 1992.92  4828.0 1993.42  4873.5 1996.78
  4905.2 2000.15  4948.2 1997.70  5019.3 1994.60  5074.0 1994.91  5089.6 1995.61
  5115.8 2000.87  5172.5 2000.41  6374.3 2006.55  6695.5 2006.37  6755.7 2008.80
  6976.5 2008.73  7016.7 2011.35  7357.9 2014.11  7418.1 2017.35  7551.6 2017.06
#Mann=11,-1,0
  2490.4   0.045       0  2947.2   0.035       0  3048.6   0.045       0
  4772.1    0.07       0  4815.2    0.07       0  4828.0    0.07       0
  4873.5    0.16       0  4948.2    0.07       0  5074.0   0.045       0
  5115.8    0.07       0  5172.5   0.045       0
Bank Sta=4815.2,4828
Exp/Cntr=0.3,0.1

Type RM Length L Ch R = 1,7415,192,192,192
BEGIN DESCRIPTION:
Hackberry Creek 1.0
END DESCRIPTION:
XS GIS Cut Line= 3
      1350406.87      7001428.42      1351155.00      6999138.00
      1351059.70      6995971.54
#Sta/Elev= 30
  2590.9 2009.83  2875.4 2008.79  3050.4 2005.57  3119.4 2007.07  3183.2 2003.97
  3308.7 2003.22  3317.2 2000.95  3338.8 2001.54  3369.2 2004.03  4442.8 1998.69
  4895.2 1995.15  4953.6 1990.67  5043.8 1988.98  5044.3 1988.48  5057.0 1988.98
  5060.4 1991.00  5100.4 1993.83  5180.5 1995.56  6000.9 1996.56  6321.0 1999.94
  6371.0 1998.40  7041.3 2004.94  7471.5 2006.61  7511.5 2008.74  7691.6 2008.58
  7741.6 2011.04  7901.7 2011.22  7941.7 2014.16  8101.8 2015.68  8168.3 2019.17
#Mann=6,-1,0
  2590.9   0.045       0  3308.7   0.035       0  3338.8   0.045       0
  4953.6    0.07       0  5043.8    0.07       0  5057.0   0.045       0
Bank Sta=5043.8,5057
Exp/Cntr=0.3,0.1

Type RM Length L Ch R = 1,7223,306,306,306
BEGIN DESCRIPTION:
Hackberry Creek 0.5
END DESCRIPTION:
XS GIS Cut Line= 3
      1350717.99      7001320.87      1351279.82      6999340.42
      1352129.09      6996771.57
#Sta/Elev= 30
  2729.9 2005.02  2917.6 2005.08  3023.9 2002.39  3102.8 2003.54  3159.1 2001.19
  3249.0 2002.52  3304.6 1997.66  3315.0 2001.80  3349.9 2000.17  3906.0 2001.03
  4396.0 1996.37  4850.9 1995.72  4905.1 1992.16  5016.2 1988.31  5016.7 1987.81
  5029.4 1988.31  5064.9 1991.35  5168.2 1994.43  6360.4 1994.36  6447.8 1996.72
  6574.7 1996.01  6623.7 1998.43  6765.1 1998.01  6791.5 1999.87  6987.2 1999.19
  7050.6 2001.66  7177.5 2000.89  7224.0 2003.22  7255.6 2001.89  7494.1 2004.06
#Mann=6,-1,0
  2729.9   0.045       0  3249.0   0.035       0  3349.9   0.045       0
  4905.1    0.07       0  5016.2    0.07       0  5029.4   0.045       0
Bank Sta=5016.2,5029.4
Exp/Cntr=0.3,0.1

Type RM Length L Ch R = 1,6917,730,730,730
BEGIN DESCRIPTION:
Hackberry Creek 0.4
END DESCRIPTION:
XS GIS Cut Line= 2
      1351111.92      7000908.18      1352146.53      6997512.71
#Sta/Elev= 30
  3201.4 1999.68  3233.2 1999.48  3253.9 2000.61  3261.3 1996.96  3284.0 1996.96
  3294.1 2000.44  3403.1 1997.12  3797.5 1999.29  4037.9 1998.78  4364.3 1994.34
  4839.6 1994.06  4907.1 1990.53  4976.2 1989.86  4993.1 1986.90  4993.6 1986.40
  5006.3 1986.90  5008.5 1987.93  5112.8 1991.86  5261.0 1989.39  5485.9 1989.28
  5515.7 1989.30  5729.9 1992.68  5970.2 1991.56  6041.1 1993.51  6106.8 1992.36
  6369.1 1993.37  6418.0 1995.19  6536.4 1994.25  6599.1 1996.54  6751.0 1996.16
#Mann=9,-1,0
  3201.4   0.045       0  3233.2   0.035       0  3284.0   0.045       0
  4907.1   0.035       0  4993.1   0.035       0  5006.3   0.035       0
  5008.5   0.045       0  5485.9    0.07       0  5515.7   0.045       0
Bank Sta=4993.1,5006.3
Exp/Cntr=0.3,0.1