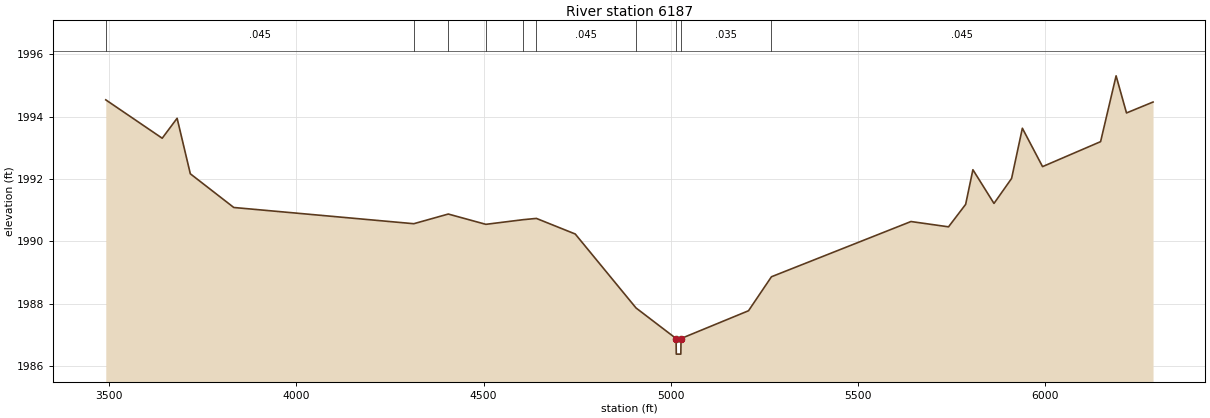
HEC-RAS study Hackberry Creek.prj: Hackberry Creek Base Level Engineering

--- Hackberry Creek.g01 (geometry) --- (continued)

Type RM Length L Ch R = 1,6187,0,0,0
BEGIN DESCRIPTION:
Hackberry Creek 0.1
END DESCRIPTION:
XS GIS Cut Line= 4
      1351619.26      7000221.97      1351980.00      6999413.00
      1352210.13      6998509.84      1352457.39      6997562.45
#Sta/Elev= 30
  3490.9 1994.54  3641.6 1993.31  3681.4 1993.95  3716.7 1992.17  3832.8 1991.09
  4313.5 1990.57  4405.6 1990.88  4505.9 1990.55  4606.2 1990.70  4640.9 1990.74
  4744.7 1990.24  4907.0 1987.87  5014.0 1986.89  5014.5 1986.39  5026.7 1986.39
  5027.2 1986.89  5207.4 1987.78  5268.7 1988.87  5641.3 1990.64  5741.6 1990.47
  5787.3 1991.19  5806.7 1992.30  5863.0 1991.22  5910.0 1992.02  5938.8 1993.63
  5992.7 1992.40  6147.7 1993.20  6189.1 1995.31  6216.9 1994.12  6287.8 1994.47
#Mann=10,-1,0
  3490.9   0.045       0  4313.5    0.07       0  4405.6   0.035       0
  4505.9   0.045       0  4606.2    0.07       0  4640.9   0.045       0
  4907.0   0.035       0  5014.0   0.035       0  5027.2   0.035       0
  5268.7   0.045       0
Bank Sta=5014,5027.2
Exp/Cntr=0.3,0.1

Chan Stop Cuts=-1