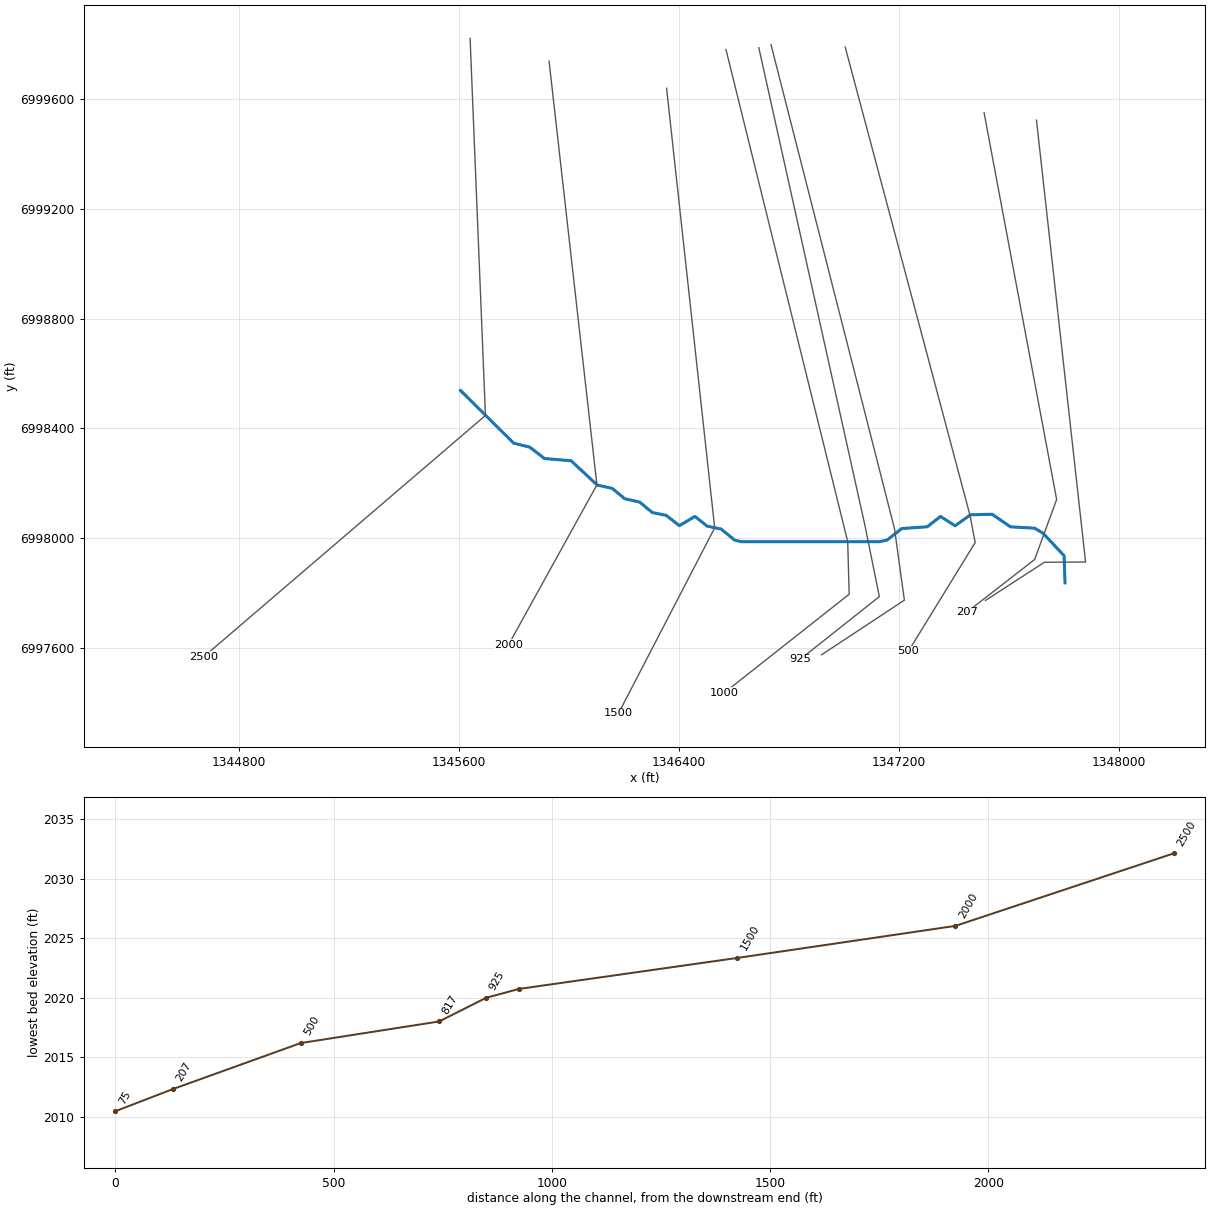
--- Hackberry Creek Trib 01-01.prj (project) ---

Proj Title=Hackberry Creek Trib 01-01 Base Level Engineering
Current Plan=p01
Default Exp/Contr=0.3,0.1
English Units
Geom File=g01
Flow File=f01
Plan File=p01
BEGIN DESCRIPTION:
Hackberry Creek Trib 01-01
END DESCRIPTION:

--- Hackberry Creek Trib 01-01.p01 (plan) ---

Plan Title=Multiple Run
Short Identifier=Multiple
Geom File=g01
Flow File=f01
Subcritical Flow
K Sum by GR= 0
Std Step Tol= 0.01
Critical Tol= 0.01
Num of Std Step Trials= 20
Max Error Tol= 0.3
Flow Tol Ratio= 0.001
Split Flow NTrial= 30
Split Flow Tol= 0.02
Split Flow Ratio= 0.02
Log Output Level= 0
Friction Slope Method= 1
Unsteady Friction Slope Method= 2
Unsteady Bridges Friction Slope Method= 1
Parabolic Critical Depth
Global Vel Dist=  1 , 1 , 1
Global Log Level= 0
CheckData=True
Encroach Param= -1, 0, 0, 0
BEGIN DESCRIPTION:
Multiple Run
END DESCRIPTION:

--- Hackberry Creek Trib 01-01.f01 (steady flow) ---

Flow Title=Multiple
Number of Profiles=7
Profile Names=10-year,25-year,50-year,1pct_min,100-year,1pct_plu,500-year
River Rch & RM= Hackberry Creek ,Reach-1,2500
     162     222     270     164     327     653     486
River Rch & RM= Hackberry Creek ,Reach-1,500
     197     272     335     205     409     815     617
Boundary for River Rch & Prof#=Hackberry Creek ,Reach-1,1
Up Type=0
Dn Type=3
Dn Slope=0.005
Boundary for River Rch & Prof#=Hackberry Creek ,Reach-1,2
Up Type=0
Dn Type=3
Dn Slope=0.005
Boundary for River Rch & Prof#=Hackberry Creek ,Reach-1,3
Up Type=0
Dn Type=3
Dn Slope=0.005
Boundary for River Rch & Prof#=Hackberry Creek ,Reach-1,4
Up Type=0
Dn Type=3
Dn Slope=0.005
Boundary for River Rch & Prof#=Hackberry Creek ,Reach-1,5
Up Type=0
Dn Type=3
Dn Slope=0.005
Boundary for River Rch & Prof#=Hackberry Creek ,Reach-1,6
Up Type=0
Dn Type=3
Dn Slope=0.005
Boundary for River Rch & Prof#=Hackberry Creek ,Reach-1,7
Up Type=0
Dn Type=3
Dn Slope=0.005

--- Hackberry Creek Trib 01-01.g01 (geometry) ---

Geom Title=Existing Conditions

River Reach=Hackberry Creek ,Reach-1
Reach XY= 30
      1345605.00      6998538.00      1345798.94      6998346.14
      1345857.17      6998331.86      1345910.97      6998290.33
      1346007.42      6998282.46      1346102.71      6998193.85
      1346157.19      6998181.90      1346202.80      6998144.08
      1346257.20      6998131.92      1346302.81      6998094.05
      1346353.37      6998083.59      1346401.77      6998046.24
      1346458.23      6998079.76      1346502.70      6998044.37
      1346553.25      6998033.84      1346602.65      6997993.71
      1346625.03      6997988.06      1347130.08      6997987.80
      1347157.34      6997993.74      1347210.98      6998035.65
      1347303.50      6998042.08      1347351.78      6998079.72
      1347404.90      6998045.80      1347460.89      6998085.64
      1347539.72      6998087.61      1347606.60      6998041.86
      1347694.53      6998036.84      1347725.20      6998018.39
      1347801.63      6997936.61      1347805.00      6997838.00

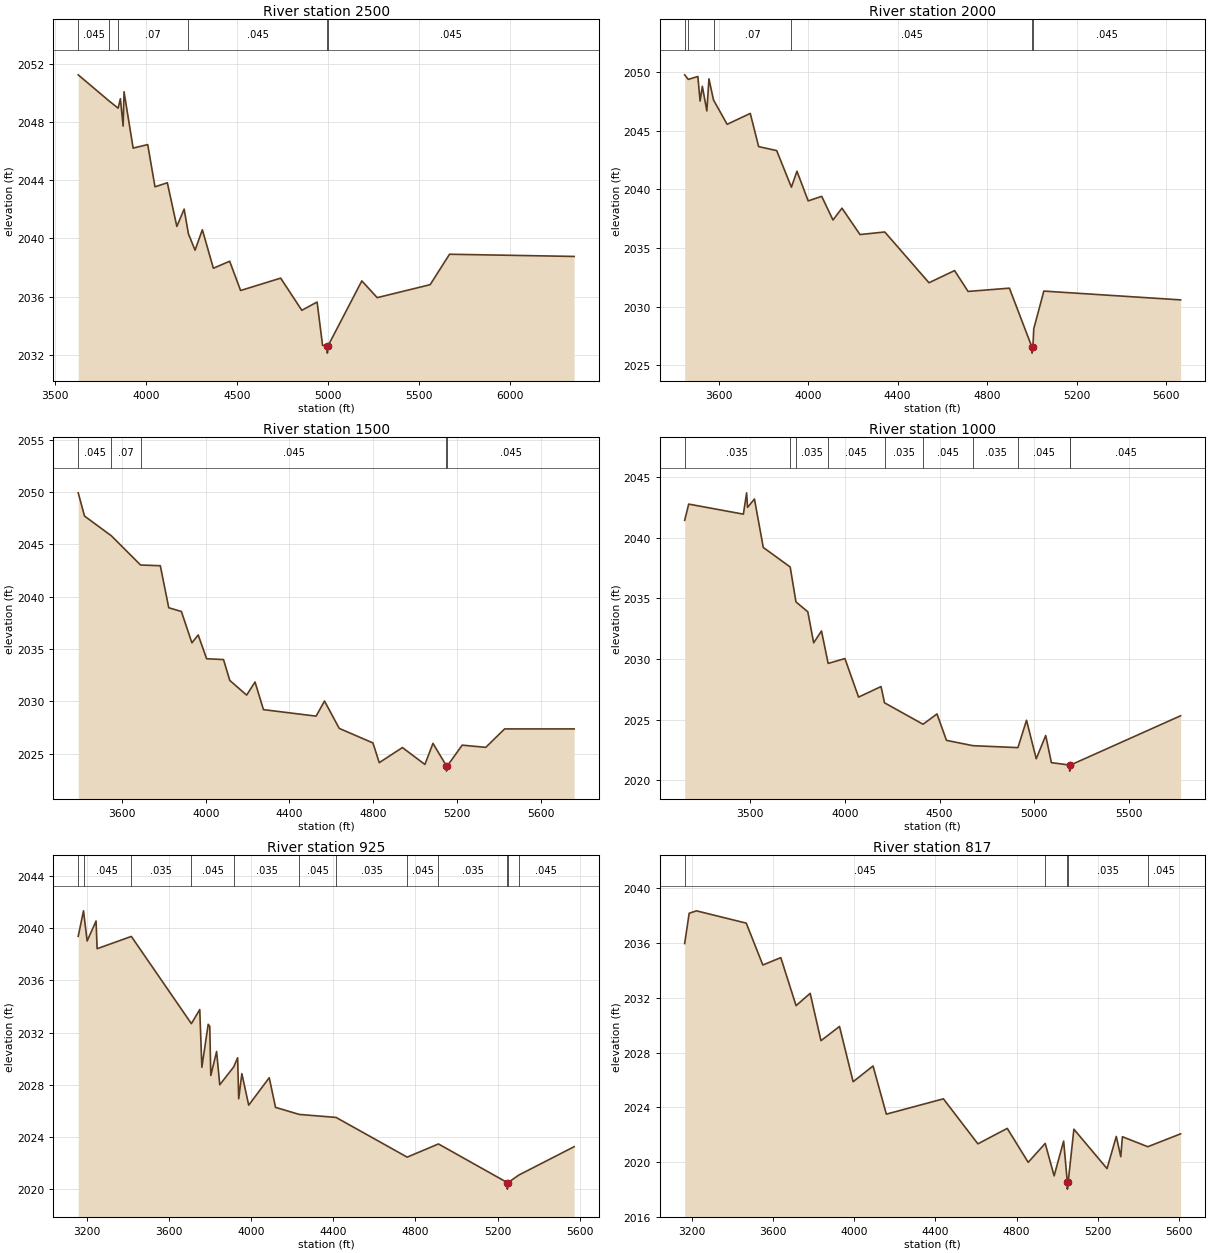
Type RM Length L Ch R = 1,2500,500,500,500
BEGIN DESCRIPTION:
Hackberry Creek Trib 01-01 5.0
END DESCRIPTION:
XS GIS Cut Line= 3
      1345639.96      6999819.57      1345695.85      6998447.11
      1344669.37      6997567.97
#Sta/Elev= 30
  3626.4 2051.23  3794.8 2049.45  3845.8 2048.94  3858.2 2049.59  3873.2 2047.71
  3878.2 2050.07  3928.2 2046.20  4008.3 2046.44  4048.3 2043.54  4116.1 2043.82
  4168.4 2040.82  4208.5 2042.01  4231.9 2040.32  4268.5 2039.19  4308.5 2040.59
  4369.1 2037.95  4458.7 2038.43  4518.7 2036.42  4738.9 2037.27  4855.1 2035.06
  4939.1 2035.63  4969.1 2032.65  4995.1 2032.62  4995.3 2032.12  4999.1 2032.62
  5184.8 2037.08  5269.3 2035.93  5560.2 2036.82  5666.7 2038.91  6351.5 2038.76
#Mann=6,-1,0
  3626.4   0.045       0  3794.8   0.035       0  3845.8    0.07       0
  4231.9   0.045       0  4995.1   0.045       0  4999.1   0.045       0
Bank Sta=4995.1,4999.1
Exp/Cntr=0.3,0.1

Type RM Length L Ch R = 1,2000,500,500,500
BEGIN DESCRIPTION:
Hackberry Creek Trib 01-01 4.0
END DESCRIPTION:
XS GIS Cut Line= 3
      1345927.36      6999736.51      1346101.47      6998194.61
      1345780.02      6997613.03
#Sta/Elev= 30
  3448.3 2049.77  3464.3 2049.38  3507.2 2049.63  3517.2 2047.53  3527.3 2048.79
  3547.4 2046.69  3556.7 2049.43  3577.1 2047.63  3638.0 2045.55  3741.4 2046.48
  3778.9 2043.65  3859.4 2043.31  3925.2 2040.19  3950.0 2041.55  4000.3 2039.02
  4060.7 2039.41  4111.0 2037.39  4151.2 2038.40  4231.8 2036.15  4342.5 2036.37
  4540.0 2032.04  4654.4 2033.08  4714.7 2031.30  4899.4 2031.58  5000.4 2026.54
  5000.7 2026.04  5004.4 2026.54  5008.2 2028.11  5053.3 2031.33  5664.5 2030.58
#Mann=6,-1,0
  3448.3   0.045       0  3464.3   0.035       0  3577.1    0.07       0
  3925.2   0.045       0  5000.4   0.045       0  5004.4   0.045       0
Bank Sta=5000.4,5004.4
Exp/Cntr=0.3,0.1

Type RM Length L Ch R = 1,1500,500,500,500
BEGIN DESCRIPTION:
Hackberry Creek Trib 01-01 3.0
END DESCRIPTION:
XS GIS Cut Line= 3
      1346355.00      6999638.03      1346530.05      6998038.08
      1346180.02      6997363.04
#Sta/Elev= 30
  3390.5 2049.92  3420.7 2047.70  3548.8 2045.82  3688.4 2043.03  3782.9 2042.96
  3823.1 2038.95  3883.5 2038.59  3933.8 2035.60  3963.9 2036.35  4004.2 2034.08
  4084.9 2034.00  4114.8 2032.01  4195.3 2030.61  4235.5 2031.86  4275.8 2029.22
  4527.3 2028.60  4567.5 2030.04  4637.9 2027.43  4798.9 2026.04  4829.1 2024.16
  4939.7 2025.60  5047.2 2023.99  5085.8 2026.00  5150.2 2023.85  5150.4 2023.35
  5154.2 2023.85  5225.4 2025.83  5338.0 2025.62  5428.1 2027.38  5760.4 2027.38
#Mann=5,-1,0
  3390.5   0.045       0  3548.8    0.07       0  3688.4   0.045       0
  5150.2   0.045       0  5154.2   0.045       0
Bank Sta=5150.2,5154.2
Exp/Cntr=0.3,0.1

Type RM Length L Ch R = 1,1000,75,75,75
BEGIN DESCRIPTION:
Hackberry Creek Trib 01-01 2.0
END DESCRIPTION:
XS GIS Cut Line= 4
      1346571.17      6999778.59      1347014.16      6997987.98
      1347019.43      6997796.57      1346563.88      6997437.23
#Sta/Elev= 30
  3155.4 2041.45  3176.6 2042.79  3465.1 2041.96  3482.1 2043.72  3487.2 2042.52
  3523.5 2043.21  3570.1 2039.21  3712.0 2037.60  3742.5 2034.72  3805.0 2033.90
  3835.9 2031.34  3877.1 2032.32  3912.3 2029.64  4000.7 2030.04  4072.8 2026.86
  4191.4 2027.73  4209.6 2026.39  4412.9 2024.62  4486.5 2025.47  4536.4 2023.29
  4676.6 2022.85  4913.5 2022.69  4958.8 2024.95  5010.0 2021.77  5060.0 2023.69
  5090.0 2021.45  5186.3 2021.25  5186.5 2020.75  5190.3 2021.25  5771.7 2025.32
#Mann=10,-1,0
  3155.4   0.035       0  3712.0   0.045       0  3742.5   0.035       0
  3912.3   0.045       0  4209.6   0.035       0  4412.9   0.045       0
  4676.6   0.035       0  4913.5   0.045       0  5186.3   0.045       0
  5190.3   0.045       0
Bank Sta=5186.3,5190.3
Exp/Cntr=0.3,0.1

Type RM Length L Ch R = 1,925,108,108,108
BEGIN DESCRIPTION:
Hackberry Creek Trib 01-01 1.5
END DESCRIPTION:
XS GIS Cut Line= 4
      1346690.63      6999785.46      1347076.05      6998050.60
      1347129.22      6997788.02      1346840.54      6997559.10
#Sta/Elev= 30
  3158.7 2039.37  3184.5 2041.32  3202.1 2039.01  3245.6 2040.54  3250.7 2038.42
  3417.3 2039.36  3709.5 2032.68  3750.2 2033.76  3760.5 2029.34  3791.2 2032.63
  3798.8 2032.48  3804.0 2028.71  3832.2 2030.55  3847.5 2028.00  3915.5 2029.37
  3934.6 2030.07  3939.7 2026.93  3955.1 2028.85  3988.4 2026.44  4088.3 2028.54
  4119.0 2026.27  4234.6 2025.73  4413.6 2025.50  4759.7 2022.46  4911.8 2023.47
  5246.9 2020.51  5247.2 2020.01  5250.9 2020.51  5302.1 2021.08  5572.2 2023.26
#Mann=12,-1,0
  3158.7   0.035       0  3184.5   0.045       0  3417.3   0.035       0
  3709.5   0.045       0  3915.5   0.035       0  4234.6   0.045       0
  4413.6   0.035       0  4759.7   0.045       0  4911.8   0.035       0
  5246.9   0.035       0  5250.9   0.035       0  5302.1   0.045       0
Bank Sta=5246.9,5250.9
Exp/Cntr=0.3,0.1

Type RM Length L Ch R = 1,817,317,317,317
BEGIN DESCRIPTION:
Hackberry Creek Trib 01-01 1.3
END DESCRIPTION:
XS GIS Cut Line= 4
      1346735.05      6999796.50      1347184.56      6998034.33
      1347220.37      6997775.00      1346919.17      6997576.35
#Sta/Elev= 30
  3166.3 2035.97  3188.4 2038.18  3224.1 2038.36  3469.4 2037.46  3551.1 2034.40
  3639.5 2034.94  3714.6 2031.43  3784.0 2032.33  3837.2 2028.87  3928.4 2029.91
  3995.5 2025.87  4093.6 2027.02  4159.0 2023.50  4439.9 2024.62  4609.6 2021.33
  4754.1 2022.46  4857.3 2019.98  4940.9 2021.36  4984.9 2018.99  5031.7 2021.53
  5049.9 2018.52  5050.1 2018.02  5053.9 2018.52  5082.1 2022.40  5245.3 2019.52
  5290.8 2021.87  5313.0 2020.39  5321.0 2021.85  5446.0 2021.12  5607.5 2022.06
#Mann=5,-1,0
  3166.3   0.045       0  4940.9   0.035       0  5049.9   0.035       0
  5053.9   0.035       0  5446.0   0.045       0
Bank Sta=5049.9,5053.9
Exp/Cntr=0.3,0.1

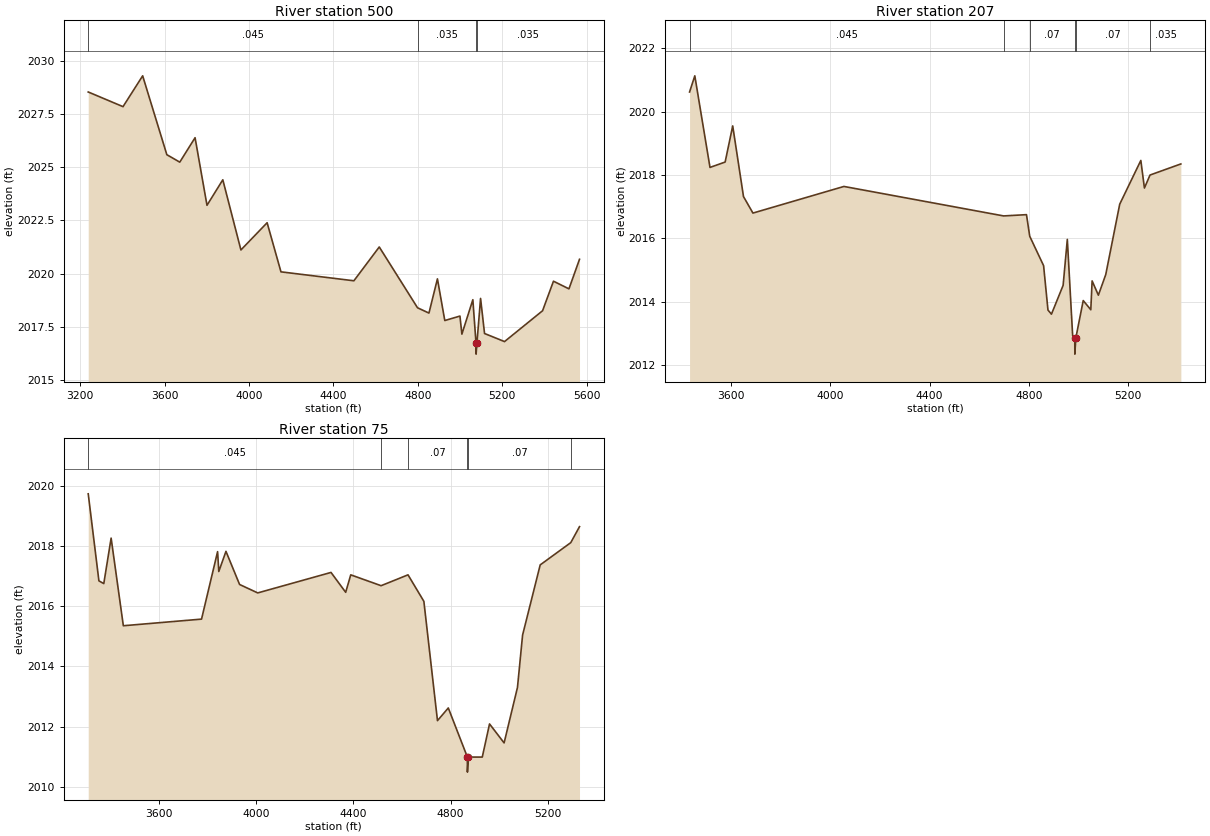
Type RM Length L Ch R = 1,500,293,293,293
BEGIN DESCRIPTION:
Hackberry Creek Trib 01-01 1.0
END DESCRIPTION:
XS GIS Cut Line= 4
      1347005.19      6999787.30      1347458.83      6998084.91
      1347478.02      6997984.63      1347234.76      6997588.80
#Sta/Elev= 30
  3238.2 2028.54  3403.1 2027.85  3496.2 2029.30  3610.8 2025.59  3672.1 2025.24
  3744.6 2026.39  3801.1 2023.21  3876.1 2024.41  3961.9 2021.11  4086.1 2022.39
  4151.7 2020.08  4497.3 2019.66  4617.6 2021.25  4799.0 2018.39  4853.1 2018.14
  4893.3 2019.75  4928.2 2017.79  5000.0 2018.00  5009.2 2017.15  5061.2 2018.77
  5076.3 2016.71  5076.6 2016.21  5080.3 2016.71  5097.8 2018.83  5116.6 2017.18
  5211.3 2016.80  5391.6 2018.25  5443.3 2019.64  5516.7 2019.28  5566.7 2020.67
#Mann=4,-1,0
  3238.2   0.045       0  4799.0   0.035       0  5076.3   0.035       0
  5080.3   0.035       0
Bank Sta=5076.3,5080.3
Exp/Cntr=0.3,0.1

Type RM Length L Ch R = 1,207,132,132,132
BEGIN DESCRIPTION:
Hackberry Creek Trib 01-01 0.9
END DESCRIPTION:
XS GIS Cut Line= 4
      1347510.41      6999548.76      1347774.46      6998141.49
      1347694.30      6997922.88      1347447.07      6997730.87
#Sta/Elev= 30
  3433.9 2020.62  3455.0 2021.13  3516.1 2018.24  3577.1 2018.41  3607.6 2019.55
  3651.0 2017.32  3689.0 2016.80  4055.3 2017.64  4698.1 2016.71  4790.2 2016.75
  4803.2 2016.07  4859.1 2015.14  4876.7 2013.74  4890.7 2013.61  4937.7 2014.52
  4954.6 2015.97  4976.0 2012.94  4984.6 2012.85  4984.9 2012.35  4988.6 2012.85
  5018.6 2014.04  5049.1 2013.75  5054.4 2014.66  5079.6 2014.21  5109.3 2014.86
  5165.5 2017.08  5250.5 2018.46  5265.0 2017.59  5287.5 2018.00  5411.6 2018.35
#Mann=6,-1,0
  3433.9   0.045       0  4698.1   0.035       0  4803.2    0.07       0
  4984.6    0.07       0  4988.6    0.07       0  5287.5   0.035       0
Bank Sta=4984.6,4988.6
Exp/Cntr=0.3,0.1

Type RM Length L Ch R = 1,75,0,0,0
BEGIN DESCRIPTION:
Hackberry Creek Trib 01-01 0.8
END DESCRIPTION:
XS GIS Cut Line= 4
      1347701.09      6999521.72      1347879.75      6997913.78
      1347730.00      6997913.00      1347515.53      6997774.12
#Sta/Elev= 30
  3308.0 2019.73  3352.0 2016.84  3372.1 2016.75  3402.3 2018.26  3452.6 2015.35
  3774.6 2015.57  3840.7 2017.81  3845.7 2017.15  3875.2 2017.82  3931.3 2016.72
  4006.0 2016.44  4307.8 2017.12  4368.2 2016.46  4389.1 2017.04  4514.1 2016.68
  4624.9 2017.04  4690.2 2016.16  4746.2 2012.20  4790.8 2012.62  4869.3 2010.99
  4869.5 2010.49  4873.3 2010.99  4930.7 2010.99  4960.6 2012.09  5020.6 2011.46
  5075.6 2013.30  5096.7 2015.04  5169.2 2017.37  5295.2 2018.11  5331.1 2018.64
#Mann=6,-1,0
  3308.0   0.045       0  4514.1   0.035       0  4624.9    0.07       0
  4869.3    0.07       0  4873.3    0.07       0  5295.2   0.035       0
Bank Sta=4869.3,4873.3
Exp/Cntr=0.3,0.1

Chan Stop Cuts=-1