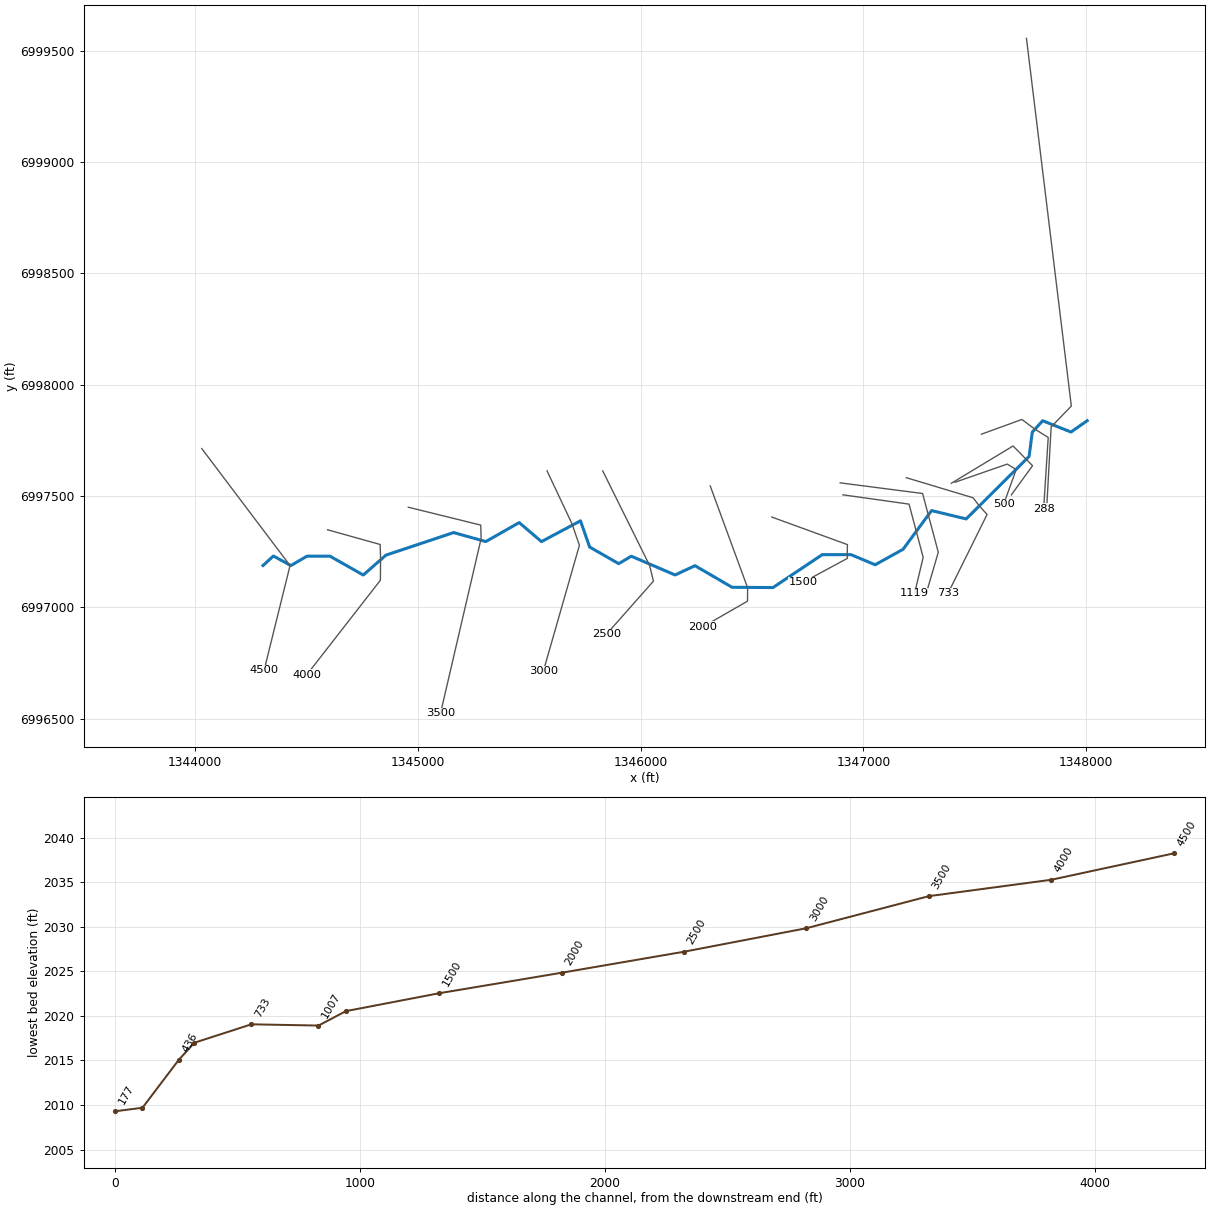
--- Hackberry Creek Trib 01.prj (project) ---

Proj Title=Hackberry Creek Trib 01 Base Level Engineering
Current Plan=p01
Default Exp/Contr=0.3,0.1
English Units
Geom File=g01
Flow File=f01
Plan File=p01
BEGIN DESCRIPTION:
Hackberry Creek Trib 01
END DESCRIPTION:

--- Hackberry Creek Trib 01.p01 (plan) ---

Plan Title=Multiple Run
Short Identifier=Multiple
Geom File=g01
Flow File=f01
Subcritical Flow
K Sum by GR= 0
Std Step Tol= 0.01
Critical Tol= 0.01
Num of Std Step Trials= 20
Max Error Tol= 0.3
Flow Tol Ratio= 0.001
Split Flow NTrial= 30
Split Flow Tol= 0.02
Split Flow Ratio= 0.02
Log Output Level= 0
Friction Slope Method= 1
Unsteady Friction Slope Method= 2
Unsteady Bridges Friction Slope Method= 1
Parabolic Critical Depth
Global Vel Dist=  1 , 1 , 1
Global Log Level= 0
CheckData=True
Encroach Param= -1, 0, 0, 0
BEGIN DESCRIPTION:
Multiple Run
END DESCRIPTION:

--- Hackberry Creek Trib 01.f01 (steady flow) ---

Flow Title=Multiple
Number of Profiles=7
Profile Names=10-year,25-year,50-year,1pct_min,100-year,1pct_plu,500-year
River Rch & RM= Hackberry Creek ,Reach-1,4500
     159     216     262     159     316     631     466
River Rch & RM= Hackberry Creek ,Reach-1,177
     293     414     515     319     636    1269     982
Boundary for River Rch & Prof#=Hackberry Creek ,Reach-1,1
Up Type=0
Dn Type=3
Dn Slope=0.005
Boundary for River Rch & Prof#=Hackberry Creek ,Reach-1,2
Up Type=0
Dn Type=3
Dn Slope=0.005
Boundary for River Rch & Prof#=Hackberry Creek ,Reach-1,3
Up Type=0
Dn Type=3
Dn Slope=0.005
Boundary for River Rch & Prof#=Hackberry Creek ,Reach-1,4
Up Type=0
Dn Type=3
Dn Slope=0.005
Boundary for River Rch & Prof#=Hackberry Creek ,Reach-1,5
Up Type=0
Dn Type=3
Dn Slope=0.005
Boundary for River Rch & Prof#=Hackberry Creek ,Reach-1,6
Up Type=0
Dn Type=3
Dn Slope=0.005
Boundary for River Rch & Prof#=Hackberry Creek ,Reach-1,7
Up Type=0
Dn Type=3
Dn Slope=0.005

--- Hackberry Creek Trib 01.g01 (geometry) ---

Geom Title=Existing Conditions

River Reach=Hackberry Creek ,Reach-1
Reach XY= 30
      1344305.00      6997188.00      1344351.56      6997230.73
      1344430.01      6997187.73      1344501.77      6997229.69
      1344604.91      6997230.25      1344755.08      6997145.30
      1344856.50      6997234.36      1345160.98      6997335.83
      1345305.01      6997295.53      1345455.09      6997380.69
      1345554.91      6997295.31      1345730.30      6997388.62
      1345771.31      6997270.90      1345901.76      6997196.24
      1345958.22      6997229.72      1346155.01      6997145.59
      1346244.30      6997187.20      1346410.93      6997090.24
      1346594.56      6997089.05      1346815.50      6997236.81
      1346944.50      6997236.77      1347053.28      6997191.34
      1347178.52      6997260.99      1347306.28      6997434.63
      1347461.74      6997397.13      1347744.15      6997677.77
      1347758.39      6997786.59      1347805.00      6997838.00
      1347932.16      6997787.29      1348005.00      6997838.00

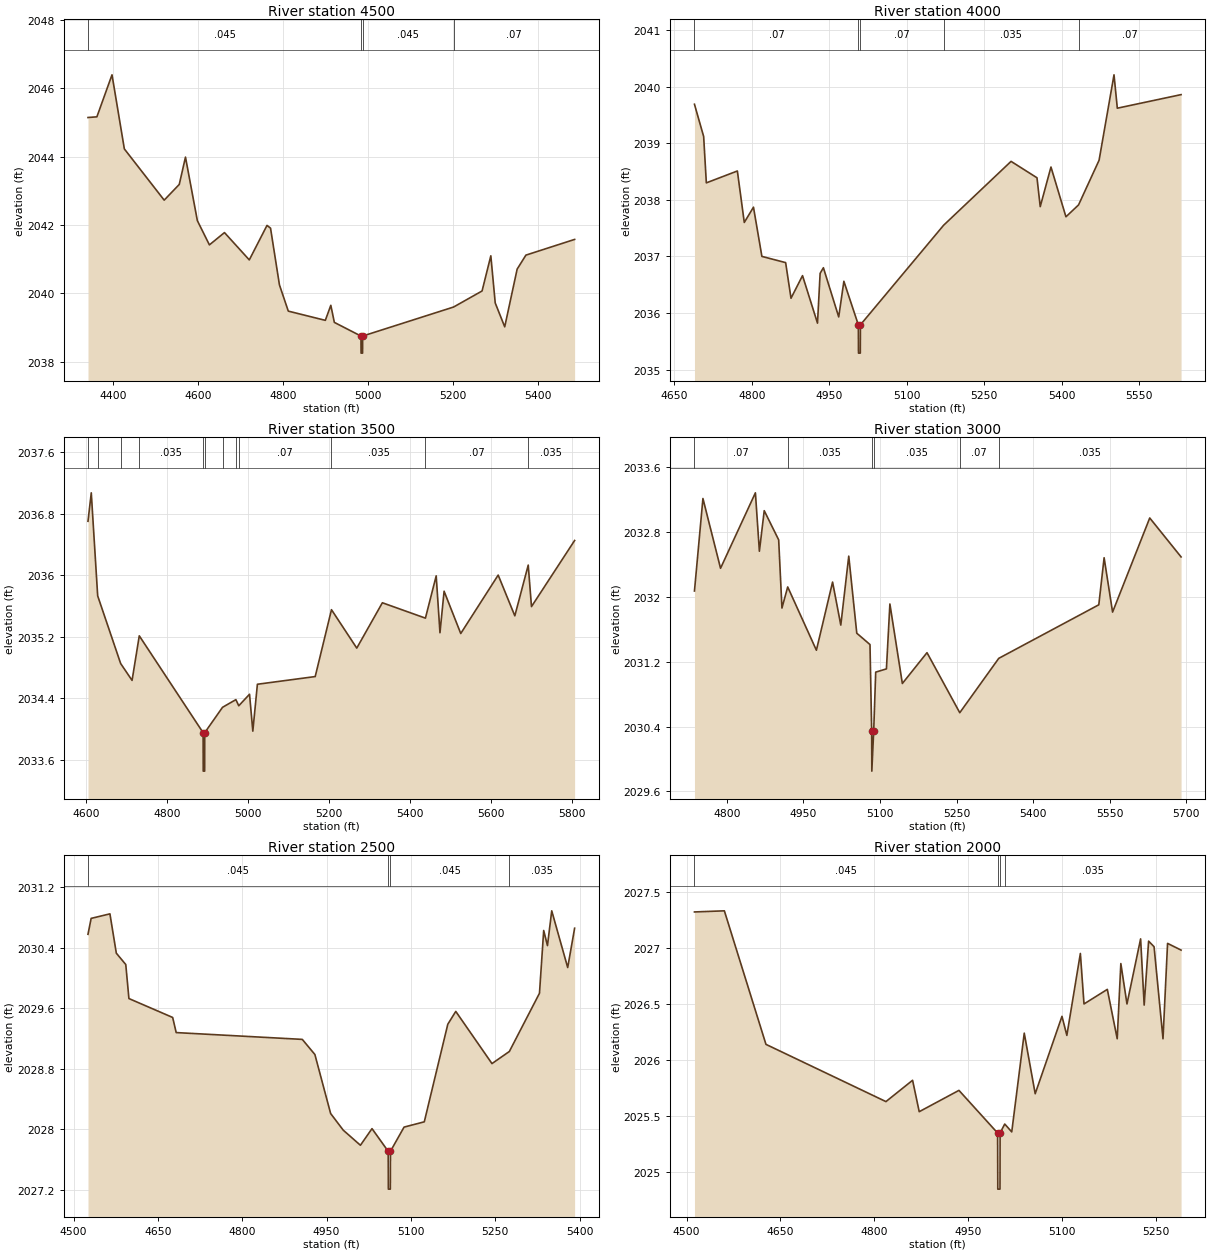
Type RM Length L Ch R = 1,4500,500,500,500
BEGIN DESCRIPTION:
Hackberry Creek Trib 01 9.0
END DESCRIPTION:
XS GIS Cut Line= 3
      1344029.97      6997713.03      1344426.34      6997187.81
      1344309.68      6996716.95
#Sta/Elev= 30
  4342.0 2045.15  4362.9 2045.17  4398.4 2046.40  4427.4 2044.23  4521.0 2042.73
  4556.4 2043.19  4571.0 2043.99  4598.9 2042.13  4627.2 2041.42  4662.6 2041.78
  4720.9 2040.98  4762.5 2041.99  4770.8 2041.91  4791.7 2040.25  4812.5 2039.48
  4899.5 2039.21  4912.4 2039.65  4920.7 2039.15  4983.2 2038.75  4983.5 2038.25
  4987.0 2038.25  4987.2 2038.75  5200.8 2039.60  5267.7 2040.07  5288.3 2041.10
  5298.6 2039.72  5320.9 2039.02  5350.1 2040.71  5370.7 2041.12  5485.1 2041.58
#Mann=4,-1,0
  4342.0   0.045       0  4983.2   0.045       0  4987.2   0.045       0
  5200.8    0.07       0
Bank Sta=4983.2,4987.2
Exp/Cntr=0.3,0.1

Type RM Length L Ch R = 1,4000,500,500,500
BEGIN DESCRIPTION:
Hackberry Creek Trib 01 8.0
END DESCRIPTION:
XS GIS Cut Line= 5
      1344594.95      6997348.40      1344830.87      6997282.42
      1344832.74      6997216.22      1344831.91      6997121.84
      1344502.04      6996698.21
#Sta/Elev= 30
  4688.8 2039.69  4706.6 2039.12  4711.8 2038.30  4771.9 2038.51  4785.3 2037.60
  4803.1 2037.87  4819.4 2037.00  4865.4 2036.89  4875.8 2036.26  4898.1 2036.66
  4927.1 2035.82  4932.2 2036.70  4938.5 2036.80  4968.2 2035.93  4978.2 2036.56
  5006.2 2035.79  5006.5 2035.29  5010.0 2035.29  5010.2 2035.79  5171.3 2037.55
  5302.0 2038.68  5352.2 2038.39  5358.5 2037.88  5379.3 2038.58  5408.3 2037.70
  5432.7 2037.91  5472.5 2038.70  5501.4 2040.21  5507.8 2039.62  5631.3 2039.86
#Mann=5,-1,0
  4688.8    0.07       0  5006.2    0.07       0  5010.2    0.07       0
  5171.3   0.035       0  5432.7    0.07       0
Bank Sta=5006.2,5010.2
Exp/Cntr=0.3,0.1

Type RM Length L Ch R = 1,3500,500,500,500
BEGIN DESCRIPTION:
Hackberry Creek Trib 01 7.0
END DESCRIPTION:
XS GIS Cut Line= 4
      1344957.14      6997449.74      1345282.51      6997369.42
      1345284.14      6997308.78      1345101.65      6996524.22
#Sta/Elev= 30
  4604.2 2036.70  4612.3 2037.07  4628.1 2035.73  4684.8 2034.85  4713.0 2034.63
  4730.8 2035.21  4888.4 2033.95  4888.7 2033.45  4892.2 2033.45  4892.4 2033.95
  4936.3 2034.28  4969.3 2034.38  4976.4 2034.30  5003.0 2034.45  5011.1 2033.97
  5022.4 2034.58  5165.1 2034.68  5205.3 2035.55  5267.7 2035.05  5330.9 2035.64
  5437.2 2035.44  5463.8 2035.99  5473.1 2035.25  5483.3 2035.79  5524.4 2035.24
  5616.8 2036.00  5657.9 2035.47  5691.0 2036.13  5699.0 2035.59  5805.5 2036.45
#Mann=12,-1,0
  4604.2    0.07       0  4628.1   0.035       0  4684.8    0.07       0
  4730.8   0.035       0  4888.4    0.07       0  4892.4   0.035       0
  4936.3    0.07       0  4969.3   0.035       0  4976.4    0.07       0
  5205.3   0.035       0  5437.2    0.07       0  5691.0   0.035       0
Bank Sta=4888.4,4892.4
Exp/Cntr=0.3,0.1

Type RM Length L Ch R = 1,3000,500,500,500
BEGIN DESCRIPTION:
Hackberry Creek Trib 01 6.0
END DESCRIPTION:
XS GIS Cut Line= 4
      1345580.00      6997613.01      1345692.34      6997374.76
      1345725.36      6997278.61      1345563.34      6996713.02
#Sta/Elev= 30
  4736.6 2032.07  4753.2 2033.21  4787.7 2032.35  4856.0 2033.28  4863.8 2032.56
  4873.3 2033.06  4901.6 2032.70  4908.0 2031.86  4919.3 2032.12  4975.5 2031.34
  5007.2 2032.18  5023.3 2031.65  5038.9 2032.50  5054.6 2031.55  5080.5 2031.41
  5083.8 2030.35  5084.1 2029.85  5087.8 2030.35  5091.7 2031.07  5112.7 2031.11
  5119.5 2031.91  5143.9 2030.93  5192.2 2031.31  5256.4 2030.57  5332.8 2031.24
  5528.8 2031.90  5539.2 2032.48  5555.8 2031.81  5628.6 2032.97  5690.0 2032.49
#Mann=6,-1,0
  4736.6    0.07       0  4919.3   0.035       0  5083.8   0.035       0
  5087.8   0.035       0  5256.4    0.07       0  5332.8   0.035       0
Bank Sta=5083.8,5087.8
Exp/Cntr=0.3,0.1

Type RM Length L Ch R = 1,2500,500,500,500
BEGIN DESCRIPTION:
Hackberry Creek Trib 01 5.0
END DESCRIPTION:
XS GIS Cut Line= 5
      1345830.01      6997612.98      1345996.55      6997276.84
      1346040.62      6997187.90      1346057.59      6997117.53
      1345846.22      6996878.85
#Sta/Elev= 30
  4525.6 2030.58  4531.2 2030.79  4564.6 2030.85  4576.0 2030.33  4592.8 2030.18
  4598.4 2029.73  4676.2 2029.48  4682.5 2029.28  4906.8 2029.19  4929.2 2028.99
  4957.2 2028.21  4979.6 2027.99  5010.2 2027.79  5030.8 2028.01  5059.6 2027.71
  5059.9 2027.21  5063.4 2027.21  5063.6 2027.71  5087.8 2028.03  5123.8 2028.10
  5165.6 2029.39  5179.8 2029.56  5244.2 2028.87  5275.1 2029.03  5328.7 2029.80
  5336.2 2030.63  5342.9 2030.43  5350.5 2030.89  5378.9 2030.14  5391.2 2030.66
#Mann=4,-1,0
  4525.6   0.045       0  5059.6   0.045       0  5063.6   0.045       0
  5275.1   0.035       0
Bank Sta=5059.6,5063.6
Exp/Cntr=0.3,0.1

Type RM Length L Ch R = 1,2000,500,500,500
BEGIN DESCRIPTION:
Hackberry Creek Trib 01 4.0
END DESCRIPTION:
XS GIS Cut Line= 4
      1346312.60      6997545.32      1346480.54      6997087.77
      1346480.00      6997028.00      1346279.98      6996912.99
#Sta/Elev= 30
  4512.6 2027.32  4560.4 2027.33  4626.9 2026.14  4818.7 2025.63  4861.3 2025.82
  4871.9 2025.54  4935.4 2025.73  4997.2 2025.35  4997.5 2024.85  5001.0 2024.85
  5001.2 2025.35  5008.6 2025.43  5019.8 2025.36  5039.8 2026.24  5057.3 2025.70
  5100.1 2026.39  5107.9 2026.22  5129.5 2026.95  5135.3 2026.50  5172.6 2026.63
  5188.4 2026.19  5194.2 2026.86  5204.0 2026.50  5225.8 2027.08  5231.5 2026.49
  5238.6 2027.06  5247.3 2027.01  5261.6 2026.19  5268.9 2027.04  5290.5 2026.98
#Mann=4,-1,0
  4512.6   0.045       0  4997.2   0.045       0  5001.2   0.045       0
  5008.6   0.035       0
Bank Sta=4997.2,5001.2
Exp/Cntr=0.3,0.1

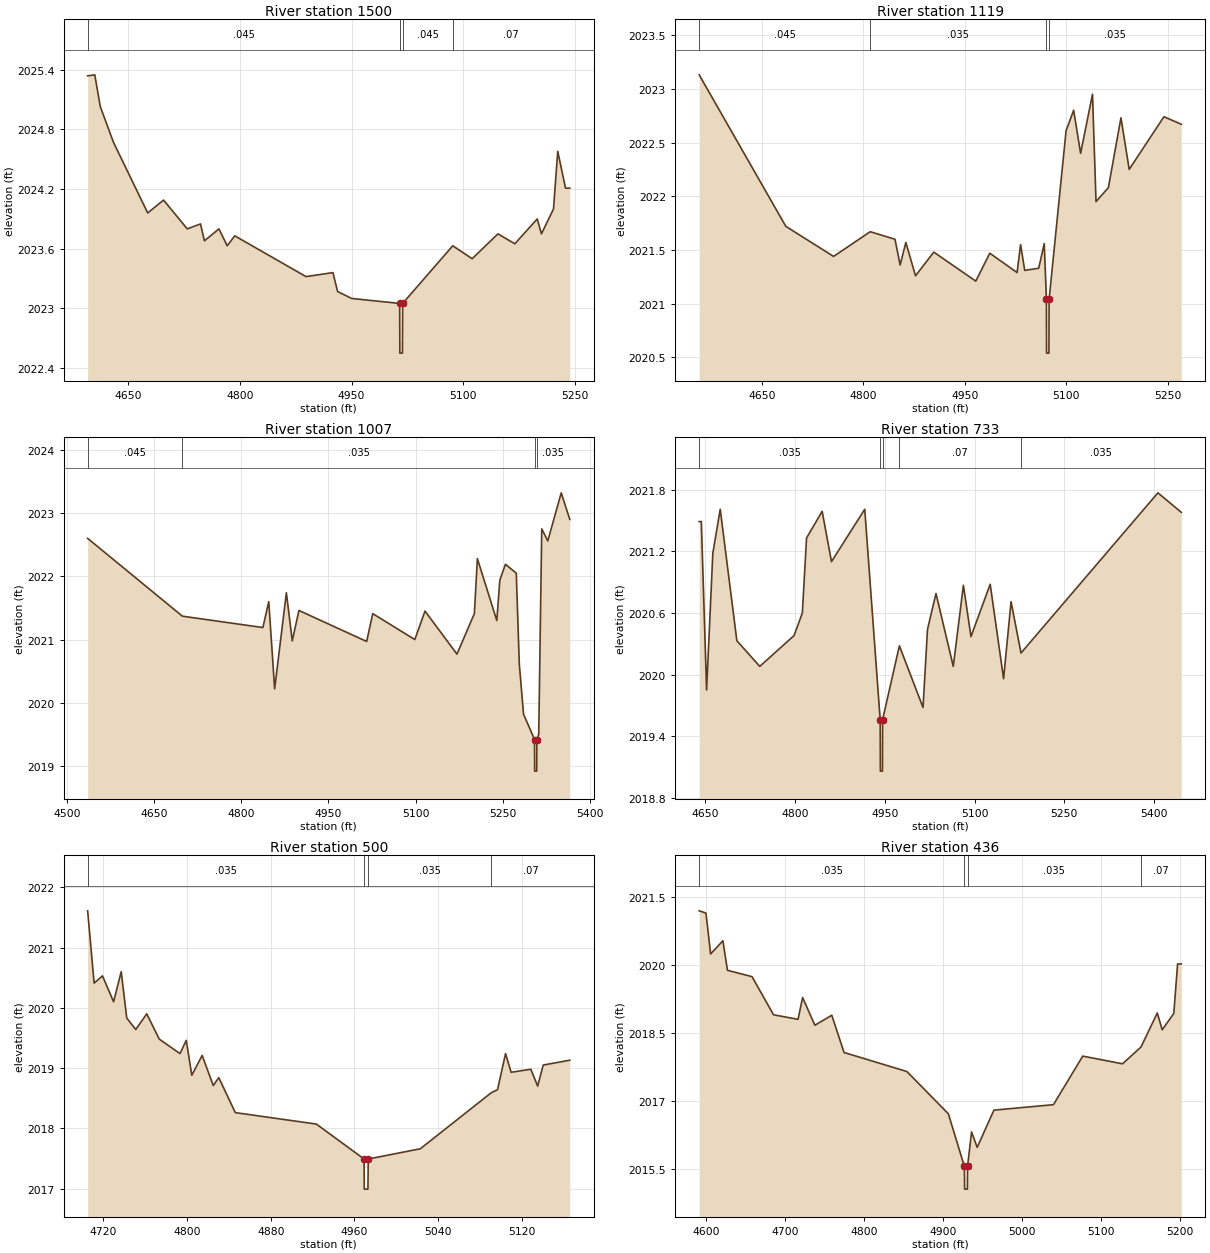
Type RM Length L Ch R = 1,1500,381,381,381
BEGIN DESCRIPTION:
Hackberry Creek Trib 01 3.0
END DESCRIPTION:
XS GIS Cut Line= 5
      1346589.07      6997405.56      1346928.53      6997281.91
      1346927.73      6997238.29      1346928.28      6997220.03
      1346730.00      6997113.00
#Sta/Elev= 30
  4595.1 2025.34  4604.7 2025.35  4612.1 2025.03  4629.9 2024.67  4675.9 2023.96
  4697.2 2024.09  4729.1 2023.80  4746.9 2023.85  4752.2 2023.68  4771.7 2023.80
  4782.8 2023.63  4793.0 2023.73  4888.8 2023.32  4925.0 2023.36  4931.3 2023.17
  4950.2 2023.10  5014.8 2023.05  5015.0 2022.55  5018.5 2022.55  5018.8 2023.05
  5086.2 2023.63  5112.3 2023.50  5147.0 2023.75  5169.7 2023.65  5199.8 2023.90
  5205.5 2023.75  5221.7 2024.00  5227.4 2024.58  5237.9 2024.21  5243.6 2024.21
#Mann=4,-1,0
  4595.1   0.045       0  5014.8   0.045       0  5018.8   0.045       0
  5086.2    0.07       0
Bank Sta=5014.8,5018.8
Exp/Cntr=0.3,0.1

Type RM Length L Ch R = 1,1119,112,112,112
BEGIN DESCRIPTION:
Hackberry Creek Trib 01 2.0
END DESCRIPTION:
XS GIS Cut Line= 4
      1346908.08      6997505.39      1347205.18      6997463.58
      1347268.62      6997224.68      1347230.01      6997063.03
#Sta/Elev= 30
  4557.0 2023.13  4685.2 2021.72  4755.9 2021.44  4810.1 2021.67  4846.7 2021.60
  4854.4 2021.36  4862.8 2021.57  4877.1 2021.26  4904.2 2021.48  4966.3 2021.21
  4987.0 2021.47  5027.4 2021.29  5032.6 2021.55  5038.7 2021.31  5059.4 2021.33
  5067.6 2021.56  5070.8 2021.04  5071.0 2020.54  5074.5 2020.54  5074.8 2021.04
  5099.9 2022.61  5111.1 2022.80  5121.4 2022.40  5139.0 2022.95  5144.2 2021.95
  5162.5 2022.08  5181.1 2022.73  5193.3 2022.25  5244.7 2022.74  5270.4 2022.67
#Mann=4,-1,0
  4557.0   0.045       0  4810.1   0.035       0  5070.8   0.035       0
  5074.8   0.035       0
Bank Sta=5070.8,5074.8
Exp/Cntr=0.3,0.1

Type RM Length L Ch R = 1,1007,274,274,274
BEGIN DESCRIPTION:
Hackberry Creek Trib 01 1.5
END DESCRIPTION:
XS GIS Cut Line= 4
      1346896.04      6997559.10      1347265.94      6997511.33
      1347336.47      6997247.65      1347285.04      6997071.73
#Sta/Elev= 30
  4535.8 2022.60  4698.7 2021.37  4837.2 2021.19  4847.3 2021.60  4857.4 2020.22
  4877.6 2021.74  4887.7 2020.98  4899.2 2021.46  5015.7 2020.97  5026.1 2021.41
  5098.5 2021.00  5116.0 2021.45  5171.0 2020.77  5200.9 2021.41  5206.1 2022.28
  5239.5 2021.30  5244.7 2021.94  5254.3 2022.19  5273.0 2022.05  5278.2 2020.61
  5285.5 2019.82  5304.4 2019.42  5304.6 2018.92  5308.1 2018.92  5308.4 2019.42
  5311.6 2019.50  5316.8 2022.75  5327.2 2022.56  5350.3 2023.32  5365.0 2022.90
#Mann=4,-1,0
  4535.8   0.045       0  4698.7   0.035       0  5304.4   0.035       0
  5308.4   0.035       0
Bank Sta=5304.4,5308.4
Exp/Cntr=0.3,0.1

Type RM Length L Ch R = 1,733,233,233,233
BEGIN DESCRIPTION:
Hackberry Creek Trib 01 1.1
END DESCRIPTION:
XS GIS Cut Line= 5
      1347193.13      6997582.19      1347492.61      6997492.13
      1347521.67      6997454.47      1347555.55      6997417.26
      1347380.00      6997062.99
#Sta/Elev= 30
  4639.7 2021.49  4643.3 2021.49  4652.1 2019.85  4662.5 2021.18  4674.9 2021.61
  4702.7 2020.33  4741.0 2020.08  4798.3 2020.38  4812.2 2020.60  4819.2 2021.33
  4845.3 2021.59  4860.9 2021.10  4916.5 2021.61  4942.3 2019.56  4942.6 2019.06
  4946.1 2019.06  4946.3 2019.56  4974.4 2020.28  5013.9 2019.68  5021.4 2020.44
  5035.6 2020.79  5064.5 2020.08  5081.4 2020.87  5094.1 2020.37  5126.2 2020.88
  5148.6 2019.96  5161.1 2020.71  5177.7 2020.21  5406.6 2021.77  5445.7 2021.58
#Mann=5,-1,0
  4639.7   0.035       0  4942.3    0.07       0  4946.3   0.035       0
  4974.4    0.07       0  5177.7   0.035       0
Bank Sta=4942.3,4946.3
Exp/Cntr=0.3,0.1

Type RM Length L Ch R = 1,500,64,64,64
BEGIN DESCRIPTION:
Hackberry Creek Trib 01 1.0
END DESCRIPTION:
XS GIS Cut Line= 4
      1347411.59      6997561.82      1347645.98      6997643.28
      1347686.22      6997619.08      1347630.00      6997463.00
#Sta/Elev= 30
  4704.9 2021.61  4711.1 2020.41  4719.1 2020.53  4729.7 2020.10  4737.0 2020.60
  4742.3 2019.83  4750.9 2019.64  4761.4 2019.90  4773.4 2019.48  4793.2 2019.24
  4799.2 2019.46  4804.5 2018.88  4814.4 2019.21  4825.0 2018.71  4830.3 2018.84
  4846.1 2018.26  4923.6 2018.07  4969.2 2017.49  4969.4 2016.99  4972.9 2016.99
  4973.2 2017.49  5023.0 2017.66  5090.8 2018.59  5096.8 2018.64  5104.5 2019.24
  5109.8 2018.93  5128.7 2018.98  5135.2 2018.70  5140.5 2019.05  5165.9 2019.13
#Mann=4,-1,0
  4704.9   0.035       0  4969.2   0.035       0  4973.2   0.035       0
  5090.8    0.07       0
Bank Sta=4969.2,4973.2
Exp/Cntr=0.3,0.1

Type RM Length L Ch R = 1,436,148,148,148
BEGIN DESCRIPTION:
Hackberry Creek Trib 01 0.7
END DESCRIPTION:
XS GIS Cut Line= 4
      1347394.90      6997557.15      1347672.25      6997724.59
      1347759.58      6997636.06      1347664.47      6997505.20
#Sta/Elev= 30
  4591.2 2021.19  4599.8 2021.14  4605.7 2020.24  4621.2 2020.53  4627.0 2019.88
  4658.1 2019.74  4685.3 2018.90  4716.3 2018.80  4722.1 2019.28  4737.6 2018.67
  4759.0 2018.89  4774.5 2018.07  4854.1 2017.65  4906.5 2016.72  4926.8 2015.56
  4927.1 2015.06  4930.6 2015.06  4930.8 2015.56  4935.9 2016.32  4943.0 2015.98
  4964.2 2016.80  5039.5 2016.92  5076.6 2017.99  5126.9 2017.82  5150.3 2018.19
  5170.9 2018.94  5177.1 2018.57  5191.8 2018.93  5196.6 2020.02  5201.3 2020.02
#Mann=4,-1,0
  4591.2   0.035       0  4926.8   0.035       0  4930.8   0.035       0
  5150.3    0.07       0
Bank Sta=4926.8,4930.8
Exp/Cntr=0.3,0.1

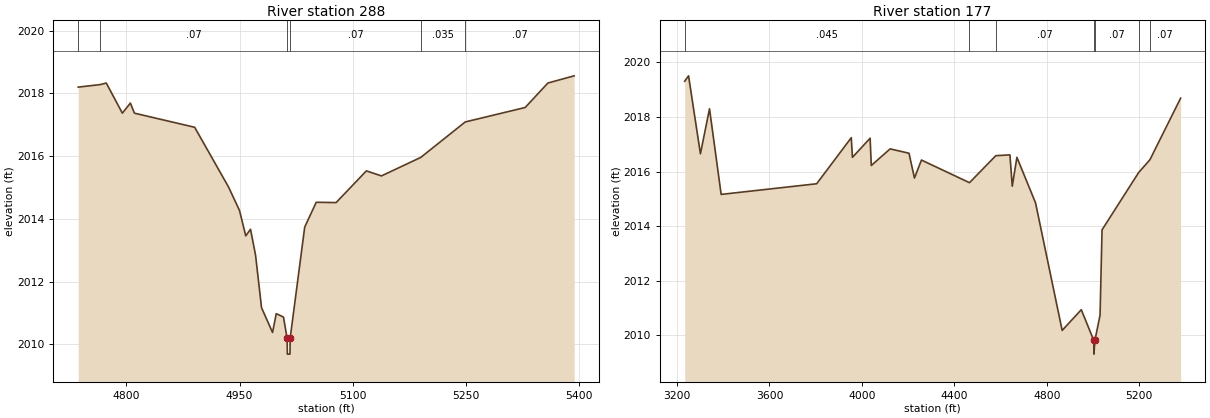
Type RM Length L Ch R = 1,288,111,111,111
BEGIN DESCRIPTION:
Hackberry Creek Trib 01 0.9
END DESCRIPTION:
XS GIS Cut Line= 5
      1347530.03      6997777.51      1347711.80      6997843.69
      1347767.97      6997801.48      1347830.00      6997763.00
      1347809.45      6997443.26
#Sta/Elev= 30
  4736.3 2018.20  4765.3 2018.28  4773.5 2018.33  4794.8 2017.37  4805.4 2017.69
  4810.8 2017.37  4890.6 2016.92  4935.4 2015.02  4950.0 2014.27  4958.3 2013.46
  4964.6 2013.67  4971.3 2012.84  4979.2 2011.17  4993.8 2010.38  4998.7 2010.98
  5008.3 2010.87  5013.1 2010.19  5013.4 2009.69  5016.9 2009.69  5017.1 2010.19
  5036.4 2013.74  5051.7 2014.53  5078.0 2014.52  5118.1 2015.53  5138.1 2015.37
  5190.2 2015.96  5249.1 2017.09  5328.5 2017.55  5358.6 2018.33  5393.4 2018.56
#Mann=6,-1,0
  4736.3   0.035       0  4765.3    0.07       0  5013.1    0.07       0
  5017.1    0.07       0  5190.2   0.035       0  5249.1    0.07       0
Bank Sta=5013.1,5017.1
Exp/Cntr=0.3,0.1

Type RM Length L Ch R = 1,177,0,0,0
BEGIN DESCRIPTION:
Hackberry Creek Trib 01 0.3
END DESCRIPTION:
XS GIS Cut Line= 4
      1347732.24      6999554.65      1347933.71      6997903.94
      1347843.13      6997810.03      1347823.81      6997458.59
#Sta/Elev= 30
  3233.4 2019.31  3250.2 2019.51  3301.5 2016.65  3340.8 2018.30  3391.2 2015.16
  3804.3 2015.55  3954.1 2017.24  3959.1 2016.52  4035.6 2017.22  4040.7 2016.22
  4122.2 2016.83  4203.8 2016.67  4227.4 2015.76  4257.6 2016.42  4465.5 2015.59
  4579.3 2016.58  4640.4 2016.61  4650.5 2015.46  4670.6 2016.52  4751.2 2014.85
  4866.4 2010.17  4949.1 2010.93  5003.3 2009.80  5003.7 2009.30  5008.0 2009.80
  5030.3 2010.73  5038.9 2013.86  5197.1 2015.96  5245.9 2016.43  5378.8 2018.69
#Mann=7,-1,0
  3233.4   0.045       0  4465.5   0.035       0  4579.3    0.07       0
  5003.3    0.07       0  5008.0    0.07       0  5197.1   0.035       0
  5245.9    0.07       0
Bank Sta=5003.3,5008
Exp/Cntr=0.3,0.1

Chan Stop Cuts=-1