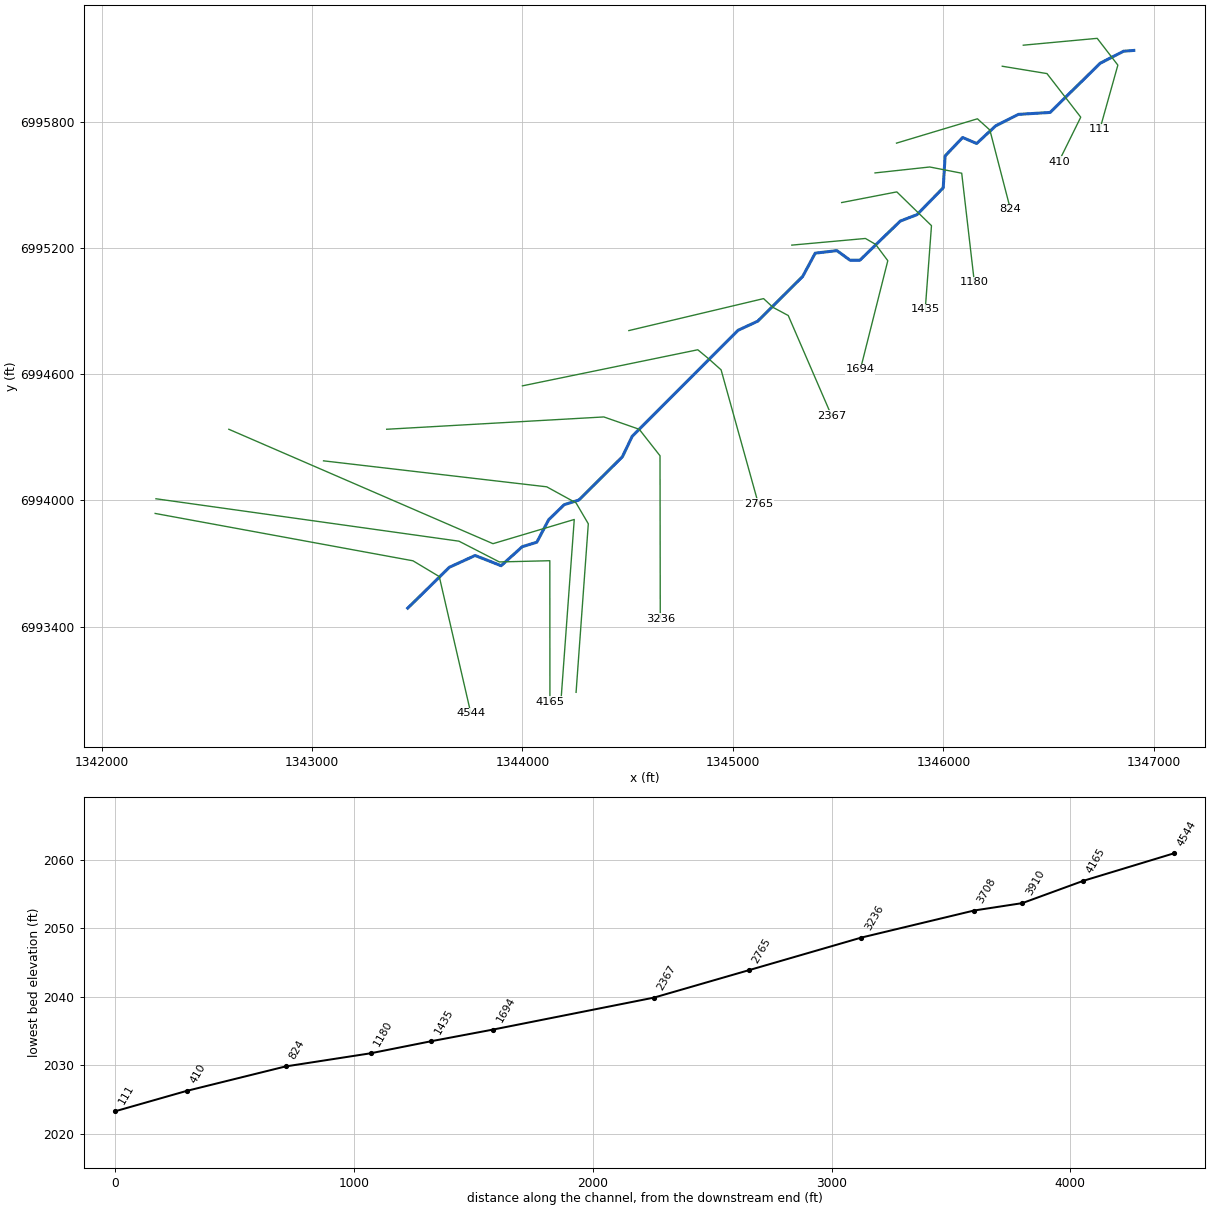
--- Hackberry Creek Trib 02-01.prj (project) ---

Proj Title=Hackberry Creek Trib 02-01 Base Level Engineering
Current Plan=p01
Default Exp/Contr=0.3,0.1
English Units
Geom File=g01
Flow File=f01
Plan File=p01
BEGIN DESCRIPTION:
Hackberry Creek Trib 02-01
END DESCRIPTION:

--- Hackberry Creek Trib 02-01.p01 (plan) ---

Plan Title=Multiple Run
Short Identifier=Multiple
Geom File=g01
Flow File=f01
Subcritical Flow
K Sum by GR= 0
Std Step Tol= 0.01
Critical Tol= 0.01
Num of Std Step Trials= 20
Max Error Tol= 0.3
Flow Tol Ratio= 0.001
Split Flow NTrial= 30
Split Flow Tol= 0.02
Split Flow Ratio= 0.02
Log Output Level= 0
Friction Slope Method= 1
Unsteady Friction Slope Method= 2
Unsteady Bridges Friction Slope Method= 1
Parabolic Critical Depth
Global Vel Dist=  1 , 1 , 1
Global Log Level= 0
CheckData=True
Encroach Param= -1, 0, 0, 0
BEGIN DESCRIPTION:
Multiple Run
END DESCRIPTION:

--- Hackberry Creek Trib 02-01.f01 (steady flow) ---

Flow Title=Multiple
Number of Profiles=7
Profile Names=10-year,25-year,50-year,1pct_min,100-year,1pct_plu,500-year
River Rch & RM= Hackberry Creek ,Reach-1,4544
     193     266     325     198     396     790     593
Boundary for River Rch & Prof#=Hackberry Creek ,Reach-1,1
Up Type=0
Dn Type=3
Dn Slope=0.005
Boundary for River Rch & Prof#=Hackberry Creek ,Reach-1,2
Up Type=0
Dn Type=3
Dn Slope=0.005
Boundary for River Rch & Prof#=Hackberry Creek ,Reach-1,3
Up Type=0
Dn Type=3
Dn Slope=0.005
Boundary for River Rch & Prof#=Hackberry Creek ,Reach-1,4
Up Type=0
Dn Type=3
Dn Slope=0.005
Boundary for River Rch & Prof#=Hackberry Creek ,Reach-1,5
Up Type=0
Dn Type=3
Dn Slope=0.005
Boundary for River Rch & Prof#=Hackberry Creek ,Reach-1,6
Up Type=0
Dn Type=3
Dn Slope=0.005
Boundary for River Rch & Prof#=Hackberry Creek ,Reach-1,7
Up Type=0
Dn Type=3
Dn Slope=0.005

--- Hackberry Creek Trib 02-01.g01 (geometry) ---

Geom Title=Existing Conditions

River Reach=Hackberry Creek ,Reach-1
Reach XY= 30
      1343455.00      6993488.00      1343652.70      6993682.17
      1343775.18      6993738.29      1343898.96      6993689.63
      1343998.98      6993779.81      1344068.56      6993801.49
      1344124.78      6993908.12      1344198.93      6993979.85
      1344268.21      6994001.63      1344475.38      6994207.84
      1344521.65      6994304.67      1345024.84      6994808.38
      1345118.21      6994851.63      1345331.98      6995064.54
      1345391.35      6995174.81      1345494.45      6995186.88
      1345556.75      6995141.34      1345603.37      6995141.13
      1345795.32      6995327.22      1345875.09      6995357.79
      1345999.53      6995485.55      1346008.54      6995636.56
      1346091.64      6995724.36      1346158.33      6995696.02
      1346248.94      6995779.82      1346356.56      6995834.24
      1346507.45      6995843.47      1346745.31      6996077.25
      1346856.49      6996134.40      1346905.00      6996138.00

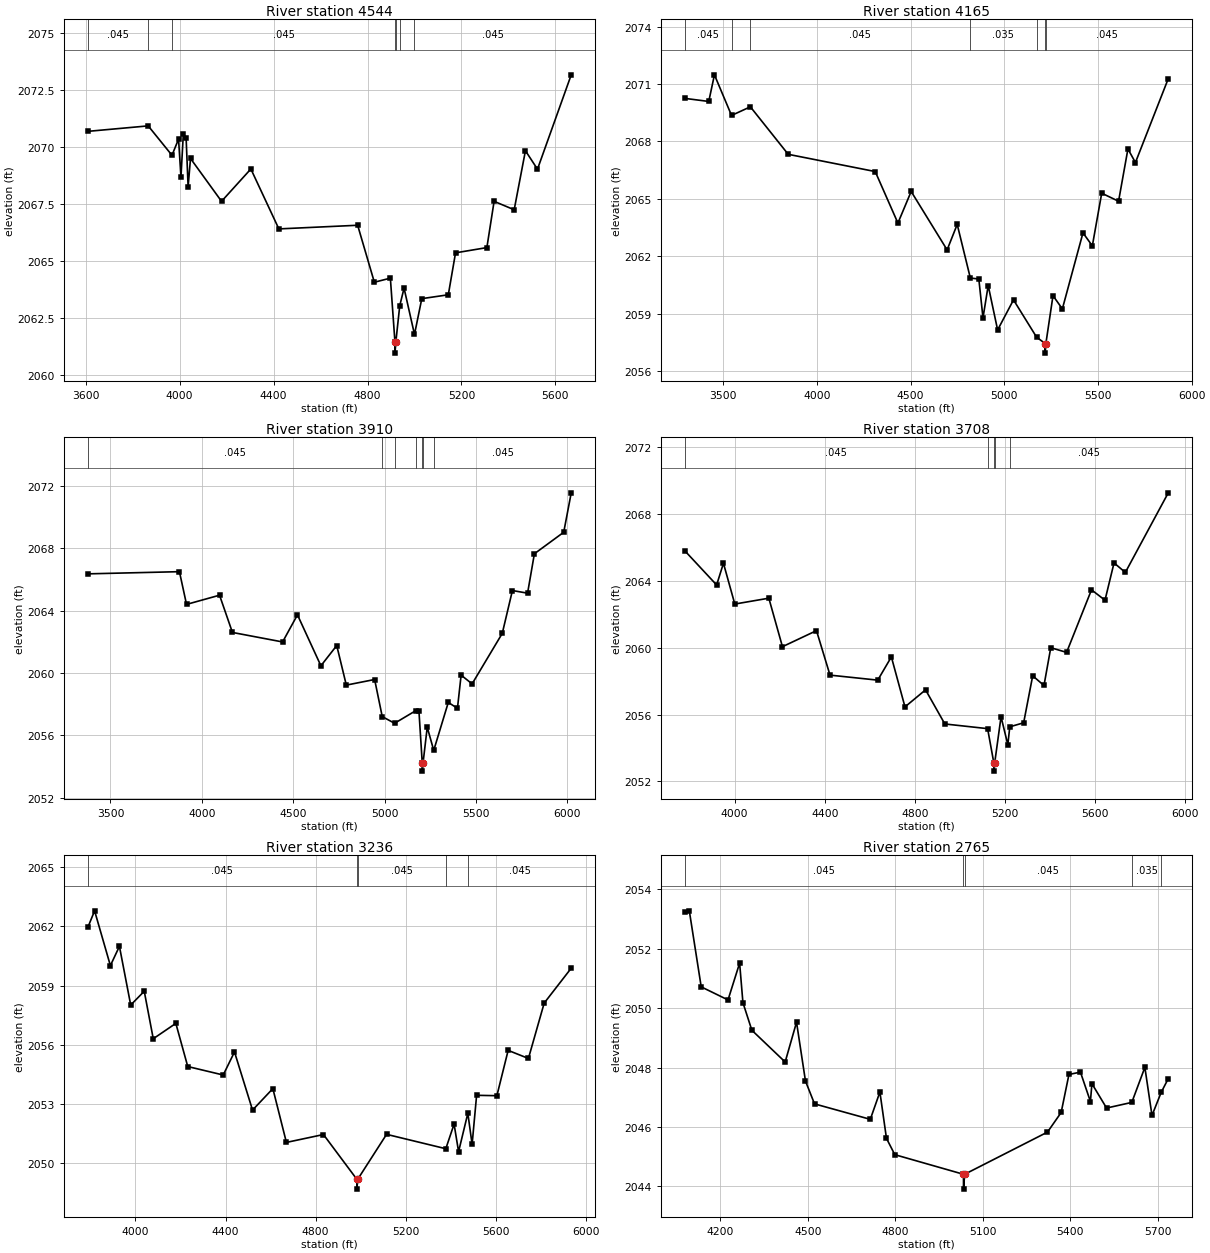
Type RM Length L Ch R = 1,4544,379,379,379
BEGIN DESCRIPTION:
Hackberry Creek Trib 02-01 4.0
END DESCRIPTION:
XS GIS Cut Line= 4
      1342255.02      6993938.00      1343480.00      6993713.00
      1343605.00      6993638.00      1343754.99      6992988.02
#Sta/Elev= 30
  3609.0 2070.69  3866.0 2070.93  3967.3 2069.64  3995.3 2070.35  4005.5 2068.68
  4015.7 2070.59  4027.5 2070.40  4036.0 2068.26  4046.2 2069.50  4178.3 2067.62
  4303.2 2069.04  4422.4 2066.41  4757.9 2066.57  4829.0 2064.07  4897.2 2064.25
  4916.6 2061.46  4916.9 2060.96  4920.6 2061.46  4937.1 2063.04  4955.5 2063.81
  4999.9 2061.78  5031.0 2063.35  5143.9 2063.52  5174.7 2065.36  5308.1 2065.59
  5338.9 2067.62  5424.4 2067.25  5472.3 2069.84  5523.6 2069.03  5667.3 2073.17
#Mann=7,-1,0
  3609.0   0.045       0  3866.0   0.035       0  3967.3   0.045       0
  4916.6   0.045       0  4920.6   0.045       0  4937.1   0.035       0
  4999.9   0.045       0
Bank Sta=4916.6,4920.6
Exp/Cntr=0.3,0.1

Type RM Length L Ch R = 1,4165,255,255,255
BEGIN DESCRIPTION:
Hackberry Creek Trib 02-01 3.5
END DESCRIPTION:
XS GIS Cut Line= 5
      1342258.74      6994007.78      1343698.40      6993806.27
      1343890.46      6993707.53      1344130.26      6993713.43
      1344130.74      6993042.66
#Sta/Elev= 30
  3294.8 2070.25  3422.3 2070.09  3452.6 2071.48  3543.9 2069.36  3644.4 2069.81
  3846.4 2067.33  4310.9 2066.43  4432.0 2063.74  4502.7 2065.39  4694.6 2062.34
  4748.5 2063.67  4818.6 2060.87  4863.9 2060.82  4886.1 2058.79  4913.9 2060.48
  4964.2 2058.16  5049.0 2059.73  5171.8 2057.79  5217.8 2057.45  5218.0 2056.95
  5221.8 2057.45  5259.8 2059.95  5309.8 2059.26  5419.8 2063.23  5469.8 2062.55
  5519.8 2065.30  5609.8 2064.88  5659.8 2067.61  5699.8 2066.90  5875.1 2071.28
#Mann=7,-1,0
  3294.8   0.045       0  3543.9   0.035       0  3644.4   0.045       0
  4818.6   0.035       0  5171.8   0.045       0  5217.8   0.035       0
  5221.8   0.045       0
Bank Sta=5217.8,5221.8
Exp/Cntr=0.3,0.1

Type RM Length L Ch R = 1,3910,202,202,202
BEGIN DESCRIPTION:
Hackberry Creek Trib 02-01 3.0
END DESCRIPTION:
XS GIS Cut Line= 4
      1342605.03      6994337.99      1343860.08      6993794.34
      1344246.36      6993909.35      1344182.35      6993036.98
#Sta/Elev= 30
  3376.3 2066.36  3877.6 2066.50  3916.4 2064.40  4097.1 2064.99  4167.6 2062.60
  4442.2 2061.99  4523.5 2063.73  4651.8 2060.46  4738.5 2061.76  4790.9 2059.22
  4945.9 2059.58  4987.5 2057.20  5055.1 2056.77  5171.0 2057.58  5188.5 2057.53
  5206.6 2054.20  5206.9 2053.70  5210.6 2054.20  5233.8 2056.52  5269.3 2055.03
  5349.0 2058.11  5399.1 2057.73  5419.2 2059.86  5479.3 2059.30  5644.4 2062.54
  5699.9 2065.29  5782.9 2065.12  5820.2 2067.65  5980.7 2069.03  6021.8 2071.56
#Mann=7,-1,0
  3376.3   0.045       0  4987.5   0.035       0  5055.1   0.045       0
  5171.0   0.035       0  5206.6   0.035       0  5210.6   0.035       0
  5269.3   0.045       0
Bank Sta=5206.6,5210.6
Exp/Cntr=0.3,0.1

Type RM Length L Ch R = 1,3708,472,472,472
BEGIN DESCRIPTION:
Hackberry Creek Trib 02-01 2.0
END DESCRIPTION:
XS GIS Cut Line= 5
      1343055.01      6994188.00      1344115.63      6994064.53
      1344255.00      6993988.00      1344313.12      6993888.75
      1344255.00      6993088.05
#Sta/Elev= 30
  3779.1 2065.79  3920.0 2063.75  3950.2 2065.05  4000.6 2062.61  4151.6 2062.96
  4212.0 2060.06  4363.0 2061.02  4423.0 2058.36  4634.8 2058.06  4695.2 2059.45
  4755.6 2056.46  4846.9 2057.48  4932.4 2055.44  5122.2 2055.16  5149.7 2053.12
  5150.0 2052.62  5153.7 2053.12  5181.8 2055.87  5211.9 2054.20  5220.6 2055.27
  5282.1 2055.51  5322.2 2058.32  5372.3 2057.74  5402.4 2060.00  5472.6 2059.72
  5583.1 2063.46  5643.0 2062.84  5683.1 2065.07  5733.2 2064.50  5923.7 2069.26
#Mann=5,-1,0
  3779.1   0.045       0  5122.2   0.035       0  5149.7   0.045       0
  5153.7   0.035       0  5220.6   0.045       0
Bank Sta=5149.7,5153.7
Exp/Cntr=0.3,0.1

Type RM Length L Ch R = 1,3236,471,471,471
BEGIN DESCRIPTION:
Hackberry Creek Trib 02-01 1.0
END DESCRIPTION:
XS GIS Cut Line= 5
      1343355.03      6994338.00      1344386.90      6994396.56
      1344555.00      6994338.00      1344653.83      6994212.10
      1344655.00      6993438.00
#Sta/Elev= 30
  3788.7 2061.95  3818.7 2062.79  3888.8 2060.01  3928.9 2060.99  3979.0 2058.01
  4039.1 2058.71  4079.1 2056.30  4179.3 2057.08  4232.2 2054.89  4389.6 2054.46
  4439.7 2055.63  4519.8 2052.68  4610.0 2053.77  4670.1 2051.04  4834.6 2051.44
  4982.7 2049.17  4983.0 2048.67  4986.7 2049.17  5114.7 2051.45  5377.7 2050.72
  5414.4 2051.97  5434.4 2050.57  5475.5 2052.52  5494.4 2050.94  5514.4 2053.43
  5604.4 2053.41  5654.4 2055.71  5744.4 2055.30  5814.4 2058.11  5934.4 2059.88
#Mann=5,-1,0
  3788.7   0.045       0  4982.7   0.045       0  4986.7   0.045       0
  5377.7   0.035       0  5475.5   0.045       0
Bank Sta=4982.7,4986.7
Exp/Cntr=0.3,0.1

Type RM Length L Ch R = 1,2765,398,398,398
BEGIN DESCRIPTION:
Hackberry Creek Trib 02-01 0.9
END DESCRIPTION:
XS GIS Cut Line= 5
      1344000.10      6994544.35      1344833.39      6994715.78
      1344884.34      6994673.53      1344944.07      6994620.30
      1345121.08      6993984.21
#Sta/Elev= 30
  4078.7 2053.24  4093.9 2053.28  4134.7 2050.72  4226.6 2050.28  4266.4 2051.52
  4277.7 2050.19  4308.3 2049.26  4422.5 2048.19  4461.5 2049.53  4492.1 2047.55
  4523.2 2046.78  4714.4 2046.26  4747.3 2047.18  4769.8 2045.62  4798.4 2045.07
  5033.8 2044.41  5034.0 2043.91  5037.8 2044.41  5321.8 2045.83  5368.7 2046.49
  5395.4 2047.77  5434.8 2047.85  5469.0 2046.86  5474.2 2047.46  5524.4 2046.64
  5610.9 2046.83  5655.7 2048.01  5680.1 2046.39  5711.7 2047.17  5735.9 2047.63
#Mann=5,-1,0
  4078.7   0.045       0  5033.8   0.045       0  5037.8   0.045       0
  5610.9   0.035       0  5711.7   0.045       0
Bank Sta=5033.8,5037.8
Exp/Cntr=0.3,0.1

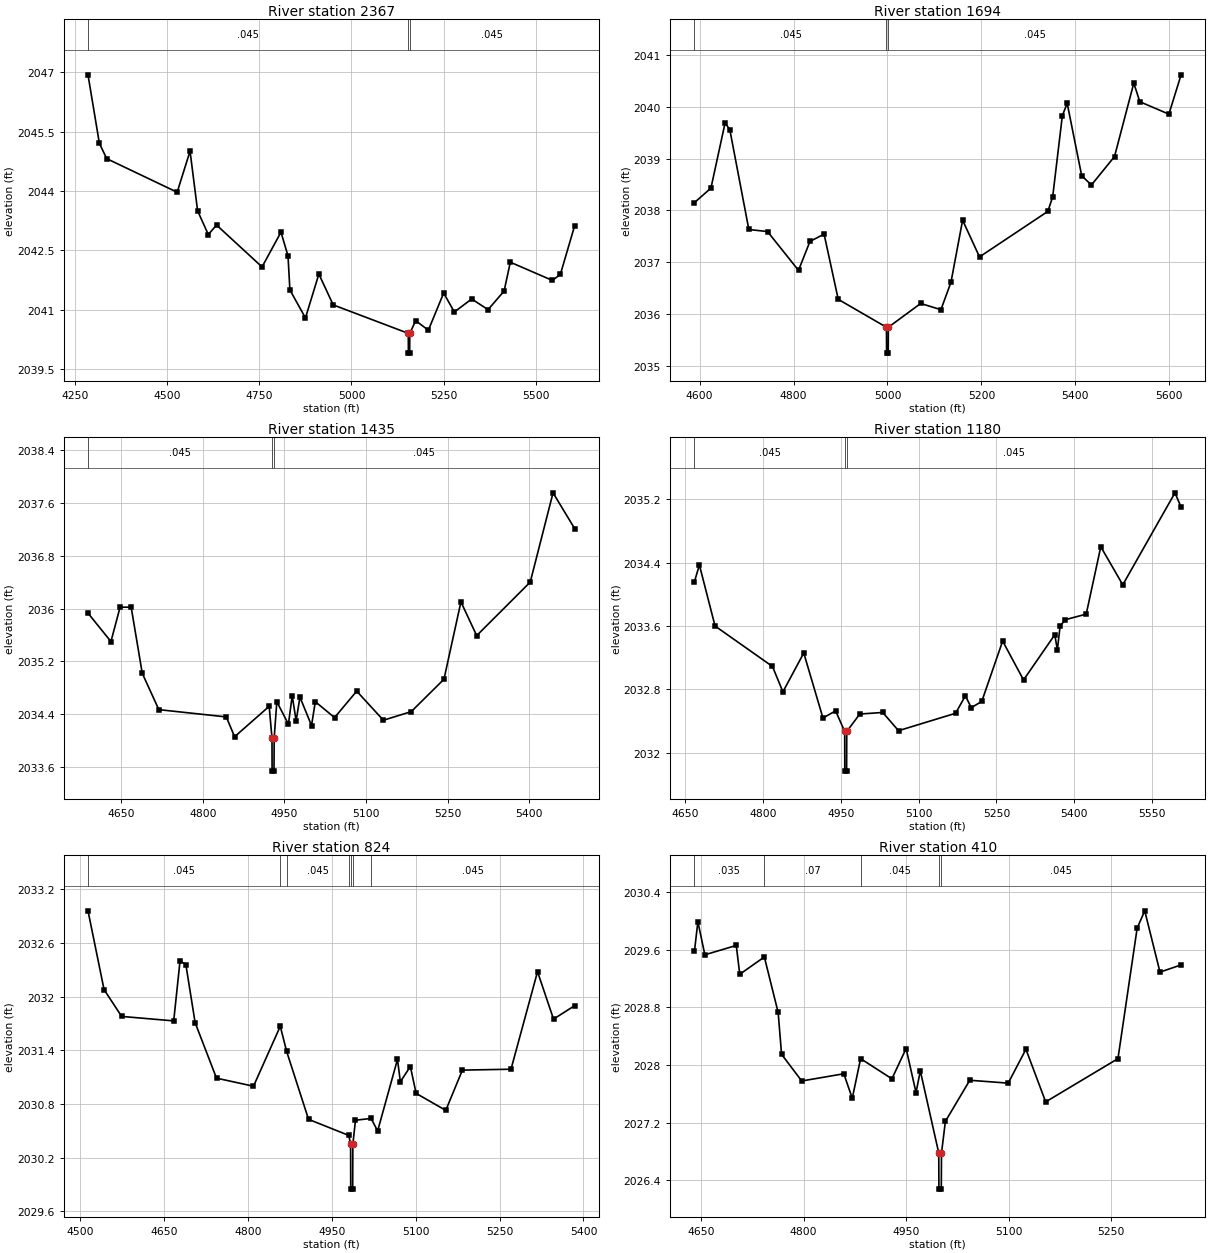
Type RM Length L Ch R = 1,2367,673,673,673
BEGIN DESCRIPTION:
Hackberry Creek Trib 02-01 0.8
END DESCRIPTION:
XS GIS Cut Line= 5
      1344505.70      6994806.93      1345145.89      6994958.84
      1345190.72      6994917.24      1345263.08      6994878.54
      1345469.03      6994402.47
#Sta/Elev= 30
  4285.4 2046.94  4316.2 2045.21  4336.1 2044.82  4527.2 2043.97  4562.2 2045.01
  4582.7 2043.50  4611.7 2042.90  4634.1 2043.14  4757.5 2042.08  4808.8 2042.96
  4827.9 2042.36  4833.0 2041.50  4875.2 2040.79  4911.6 2041.90  4950.5 2041.12
  5154.2 2040.40  5154.4 2039.90  5157.9 2039.90  5158.2 2040.40  5174.2 2040.72
  5208.6 2040.48  5250.1 2041.42  5279.1 2040.94  5326.1 2041.27  5370.5 2041.00
  5414.0 2041.47  5430.9 2042.20  5544.8 2041.74  5566.6 2041.89  5605.3 2043.12
#Mann=3,-1,0
  4285.4   0.045       0  5154.2   0.045       0  5158.2   0.045       0
Bank Sta=5154.2,5158.2
Exp/Cntr=0.3,0.1

Type RM Length L Ch R = 1,1694,259,259,259
BEGIN DESCRIPTION:
Hackberry Creek Trib 02-01 0.7
END DESCRIPTION:
XS GIS Cut Line= 5
      1345280.02      6995213.00      1345630.00      6995244.62
      1345678.15      6995216.66      1345736.17      6995138.96
      1345606.04      6994622.77
#Sta/Elev= 30
  4588.9 2038.15  4624.0 2038.43  4654.1 2039.69  4664.2 2039.56  4704.7 2037.63
  4744.5 2037.59  4810.5 2036.84  4834.9 2037.40  4865.0 2037.54  4895.1 2036.28
  4997.8 2035.74  4998.1 2035.24  5001.6 2035.24  5001.8 2035.74  5070.7 2036.20
  5113.8 2036.08  5135.2 2036.61  5160.0 2037.81  5196.0 2037.10  5341.5 2037.98
  5351.8 2038.26  5372.4 2039.83  5382.7 2040.07  5413.6 2038.67  5434.3 2038.49
  5483.5 2039.04  5524.6 2040.46  5537.4 2040.10  5599.3 2039.86  5625.3 2040.62
#Mann=3,-1,0
  4588.9   0.045       0  4997.8   0.045       0  5001.8   0.045       0
Bank Sta=4997.8,5001.8
Exp/Cntr=0.3,0.1

Type RM Length L Ch R = 1,1435,255,255,255
BEGIN DESCRIPTION:
Hackberry Creek Trib 02-01 0.55
END DESCRIPTION:
XS GIS Cut Line= 4
      1345517.06      6995415.28      1345778.98      6995465.98
      1345943.75      6995305.44      1345914.18      6994908.36
#Sta/Elev= 30
  4588.6 2035.93  4630.8 2035.50  4647.6 2036.02  4668.0 2036.02  4688.4 2035.02
  4718.9 2034.47  4843.0 2034.36  4858.2 2034.06  4921.8 2034.52  4927.0 2034.04
  4927.2 2033.54  4930.7 2033.54  4931.0 2034.04  4935.9 2034.59  4957.2 2034.25
  4964.2 2034.68  4971.4 2034.30  4978.4 2034.66  4999.7 2034.23  5006.7 2034.59
  5042.1 2034.35  5082.8 2034.75  5131.9 2034.31  5183.1 2034.44  5243.3 2034.93
  5274.5 2036.10  5303.5 2035.59  5402.0 2036.40  5443.9 2037.75  5483.6 2037.21
#Mann=3,-1,0
  4588.6   0.045       0  4927.0   0.045       0  4931.0   0.045       0
Bank Sta=4927,4931
Exp/Cntr=0.3,0.1

Type RM Length L Ch R = 1,1180,356,356,356
BEGIN DESCRIPTION:
Hackberry Creek Trib 02-01 0.45
END DESCRIPTION:
XS GIS Cut Line= 4
      1345675.51      6995556.09      1345935.30      6995584.27
      1346087.39      6995554.70      1346147.49      6995036.32
#Sta/Elev= 30
  4667.8 2034.16  4677.3 2034.37  4707.5 2033.60  4818.2 2033.09  4838.3 2032.77
  4878.5 2033.26  4915.5 2032.44  4939.9 2032.53  4957.4 2032.27  4957.6 2031.77
  4961.1 2031.77  4961.4 2032.27  4986.5 2032.49  5030.7 2032.51  5061.2 2032.28
  5171.3 2032.50  5190.0 2032.72  5201.5 2032.57  5221.7 2032.65  5261.9 2033.41
  5302.2 2032.92  5362.4 2033.49  5367.4 2033.30  5372.7 2033.60  5382.7 2033.68
  5423.0 2033.75  5451.1 2034.60  5493.5 2034.12  5594.1 2035.28  5605.9 2035.10
#Mann=3,-1,0
  4667.8   0.045       0  4957.4   0.045       0  4961.4   0.045       0
Bank Sta=4957.4,4961.4
Exp/Cntr=0.3,0.1

Type RM Length L Ch R = 1,824,414,414,414
BEGIN DESCRIPTION:
Hackberry Creek Trib 02-01 0.6
END DESCRIPTION:
XS GIS Cut Line= 4
      1345777.48      6995697.63      1346162.11      6995813.24
      1346221.28      6995759.79      1346318.77      6995383.79
#Sta/Elev= 30
  4514.4 2032.96  4543.1 2032.08  4574.5 2031.78  4667.6 2031.73  4678.9 2032.40
  4689.3 2032.36  4705.9 2031.71  4744.1 2031.09  4810.2 2031.00  4858.1 2031.67
  4869.4 2031.39  4908.6 2030.63  4980.6 2030.45  4983.8 2030.35  4984.0 2029.85
  4987.5 2029.85  4987.8 2030.35  4992.5 2030.62  5020.4 2030.64  5032.1 2030.50
  5067.6 2031.30  5072.7 2031.05  5090.6 2031.22  5100.9 2030.92  5153.9 2030.73
  5183.6 2031.18  5270.5 2031.19  5317.9 2032.28  5346.5 2031.75  5384.2 2031.90
#Mann=7,-1,0
  4514.4   0.045       0  4858.1   0.035       0  4869.4   0.045       0
  4980.6    0.07       0  4983.8    0.07       0  4987.8    0.07       0
  5020.4   0.045       0
Bank Sta=4983.8,4987.8
Exp/Cntr=0.3,0.1

Type RM Length L Ch R = 1,410,299,299,299
BEGIN DESCRIPTION:
Hackberry Creek Trib 02-01 0.5
END DESCRIPTION:
XS GIS Cut Line= 4
      1346280.03      6996062.99      1346492.54      6996028.10
      1346653.00      6995820.90      1346548.95      6995610.32
#Sta/Elev= 30
  4640.2 2029.58  4645.2 2029.99  4655.4 2029.53  4701.4 2029.66  4706.5 2029.26
  4742.5 2029.50  4762.7 2028.73  4767.7 2028.15  4797.2 2027.78  4858.8 2027.88
  4871.2 2027.54  4883.4 2028.09  4929.2 2027.81  4950.0 2028.23  4964.5 2027.62
  4970.8 2027.92  4997.8 2026.78  4998.0 2026.28  5001.5 2026.28  5001.8 2026.78
  5007.5 2027.22  5043.2 2027.79  5099.4 2027.75  5125.4 2028.22  5154.3 2027.49
  5260.1 2028.09  5288.2 2029.90  5299.3 2030.14  5321.6 2029.29  5352.5 2029.39
#Mann=5,-1,0
  4640.2   0.035       0  4742.5    0.07       0  4883.4   0.045       0
  4997.8   0.045       0  5001.8   0.045       0
Bank Sta=4997.8,5001.8
Exp/Cntr=0.3,0.1

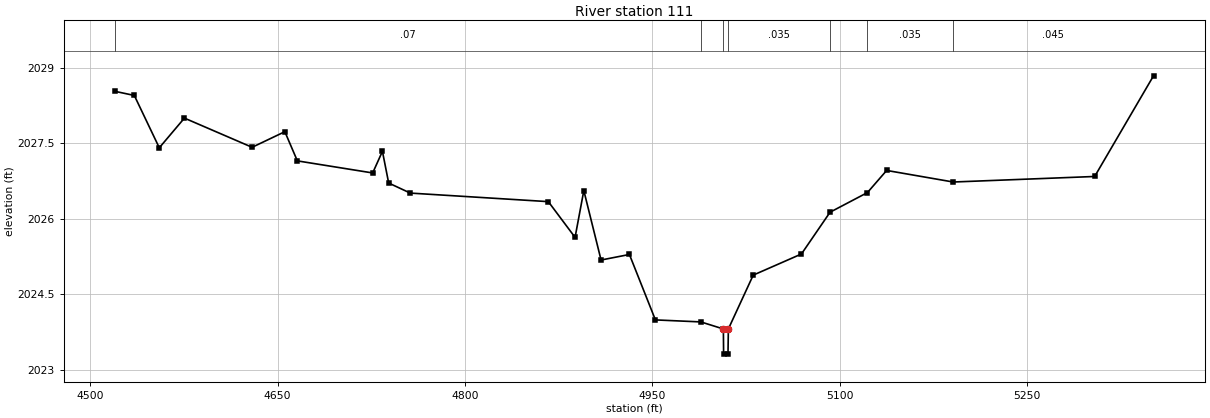
Type RM Length L Ch R = 1,111,0,0,0
BEGIN DESCRIPTION:
Hackberry Creek Trib 02-01 0.4
END DESCRIPTION:
XS GIS Cut Line= 4
      1346380.00      6996163.00      1346731.21      6996195.58
      1346829.36      6996068.34      1346743.68      6995762.63
#Sta/Elev= 30
  4520.2 2028.53  4535.3 2028.45  4555.3 2027.41  4575.4 2028.00  4629.6 2027.42
  4655.8 2027.73  4665.8 2027.15  4726.1 2026.91  4733.9 2027.34  4738.9 2026.71
  4756.2 2026.51  4866.7 2026.34  4888.1 2025.63  4895.1 2026.56  4908.9 2025.18
  4931.6 2025.29  4952.4 2023.99  4988.8 2023.95  5006.8 2023.81  5007.0 2023.31
  5010.5 2023.31  5010.8 2023.81  5030.7 2024.88  5069.3 2025.30  5092.2 2026.13
  5122.1 2026.52  5137.5 2026.96  5190.8 2026.73  5304.0 2026.84  5351.1 2028.84
#Mann=7,-1,0
  4520.2    0.07       0  4988.8   0.035       0  5006.8   0.035       0
  5010.8   0.035       0  5092.2    0.07       0  5122.1   0.035       0
  5190.8   0.045       0
Bank Sta=5006.8,5010.8
Exp/Cntr=0.3,0.1

Chan Stop Cuts=-1