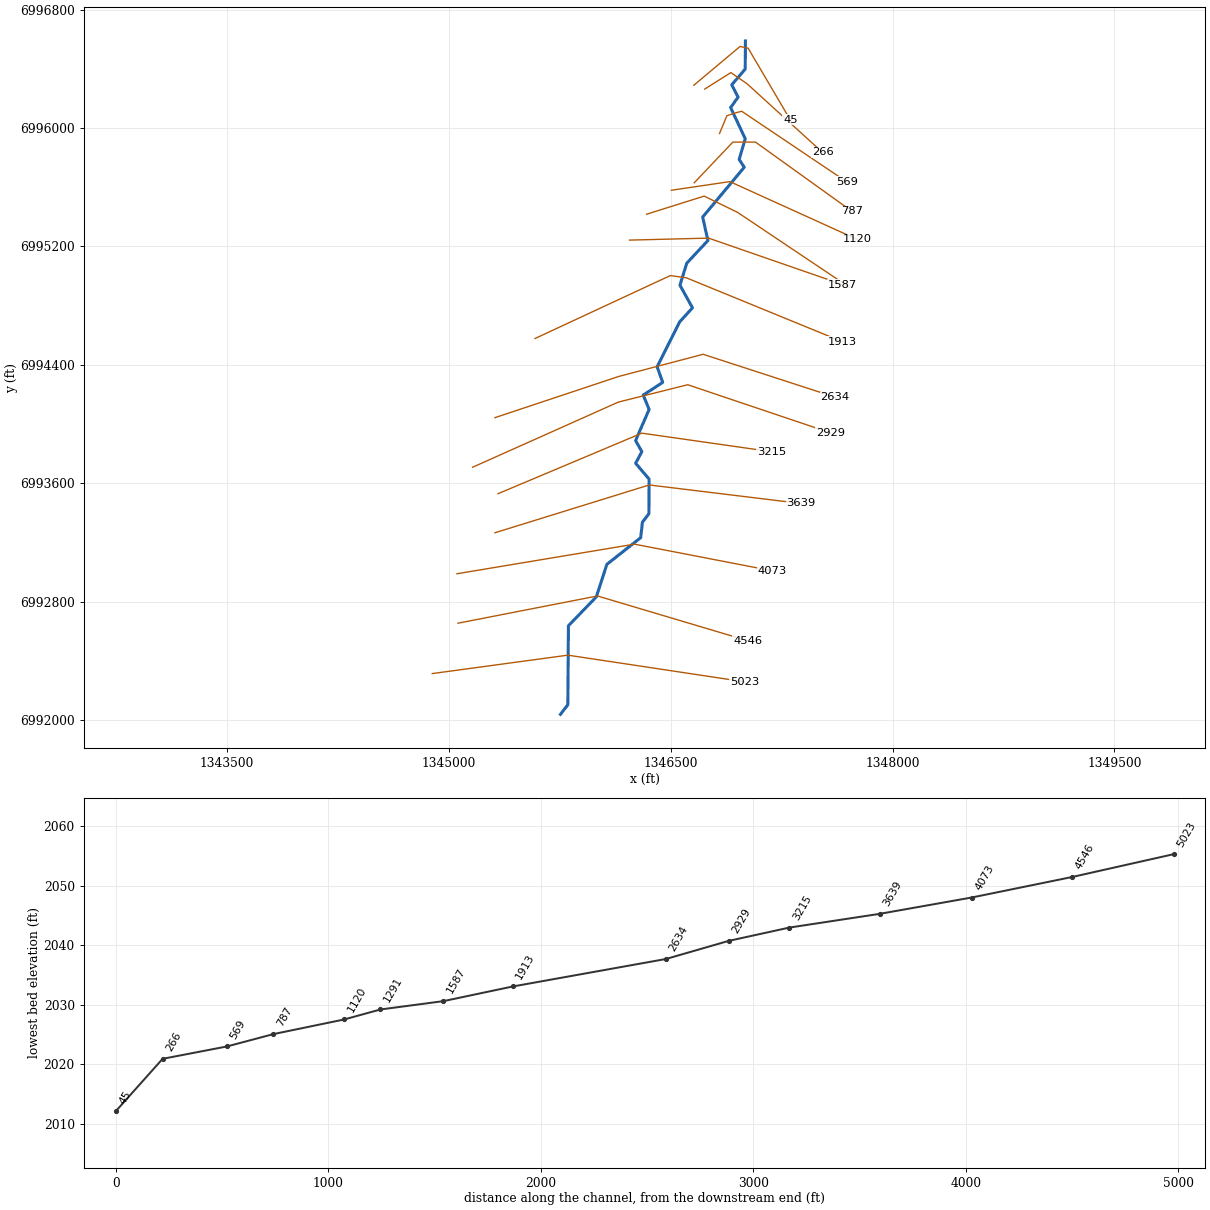
--- Hackberry Creek Trib 02.prj (project) ---

Proj Title=Hackberry Creek Trib 02 Base Level Engineering
Current Plan=p01
Default Exp/Contr=0.3,0.1
English Units
Geom File=g01
Flow File=f01
Plan File=p01
BEGIN DESCRIPTION:
Hackberry Creek Trib 02
END DESCRIPTION:

--- Hackberry Creek Trib 02.p01 (plan) ---

Plan Title=Multiple Run
Short Identifier=Multiple
Geom File=g01
Flow File=f01
Subcritical Flow
K Sum by GR= 0
Std Step Tol= 0.01
Critical Tol= 0.01
Num of Std Step Trials= 20
Max Error Tol= 0.3
Flow Tol Ratio= 0.001
Split Flow NTrial= 30
Split Flow Tol= 0.02
Split Flow Ratio= 0.02
Log Output Level= 0
Friction Slope Method= 1
Unsteady Friction Slope Method= 2
Unsteady Bridges Friction Slope Method= 1
Parabolic Critical Depth
Global Vel Dist=  1 , 1 , 1
Global Log Level= 0
CheckData=True
Encroach Param= -1, 0, 0, 0
BEGIN DESCRIPTION:
Multiple Run
END DESCRIPTION:

--- Hackberry Creek Trib 02.f01 (steady flow) ---

Flow Title=Multiple
Number of Profiles=7
Profile Names=10-year,25-year,50-year,1pct_min,100-year,1pct_plu,500-year
River Rch & RM= Hackberry Creek ,Reach-1,5023
     208     289     356     218     435     868     658
River Rch & RM= Hackberry Creek ,Reach-1,266
     344     491     616     384     765    1527    1199
Boundary for River Rch & Prof#=Hackberry Creek ,Reach-1,1
Up Type=0
Dn Type=3
Dn Slope=0.005
Boundary for River Rch & Prof#=Hackberry Creek ,Reach-1,2
Up Type=0
Dn Type=3
Dn Slope=0.005
Boundary for River Rch & Prof#=Hackberry Creek ,Reach-1,3
Up Type=0
Dn Type=3
Dn Slope=0.005
Boundary for River Rch & Prof#=Hackberry Creek ,Reach-1,4
Up Type=0
Dn Type=3
Dn Slope=0.005
Boundary for River Rch & Prof#=Hackberry Creek ,Reach-1,5
Up Type=0
Dn Type=3
Dn Slope=0.005
Boundary for River Rch & Prof#=Hackberry Creek ,Reach-1,6
Up Type=0
Dn Type=3
Dn Slope=0.005
Boundary for River Rch & Prof#=Hackberry Creek ,Reach-1,7
Up Type=0
Dn Type=3
Dn Slope=0.005

--- Hackberry Creek Trib 02.g01 (geometry) ---

Geom Title=Existing Conditions

River Reach=Hackberry Creek ,Reach-1
Reach XY= 30
      1345755.00      6992038.00      1345804.64      6992103.15
      1345808.54      6992636.54      1345997.14      6992831.83
      1346068.47      6993051.57      1346297.14      6993231.83
      1346308.86      6993336.40      1346352.74      6993393.94
      1346353.94      6993627.57      1346262.83      6993734.60
      1346305.22      6993813.00      1346262.59      6993887.99
      1346354.18      6994098.71      1346314.03      6994195.01
      1346445.96      6994280.99      1346408.37      6994386.26
      1346560.86      6994690.30      1346647.22      6994784.60
      1346562.53      6994937.99      1346608.61      6995086.50
      1346751.54      6995239.50      1346716.10      6995398.06
      1346997.01      6995734.66      1346962.81      6995787.90
      1347003.89      6995927.45      1346905.00      6996138.00
      1346955.46      6996208.25      1346912.81      6996291.40
      1347003.95      6996398.43      1347005.00      6996588.00

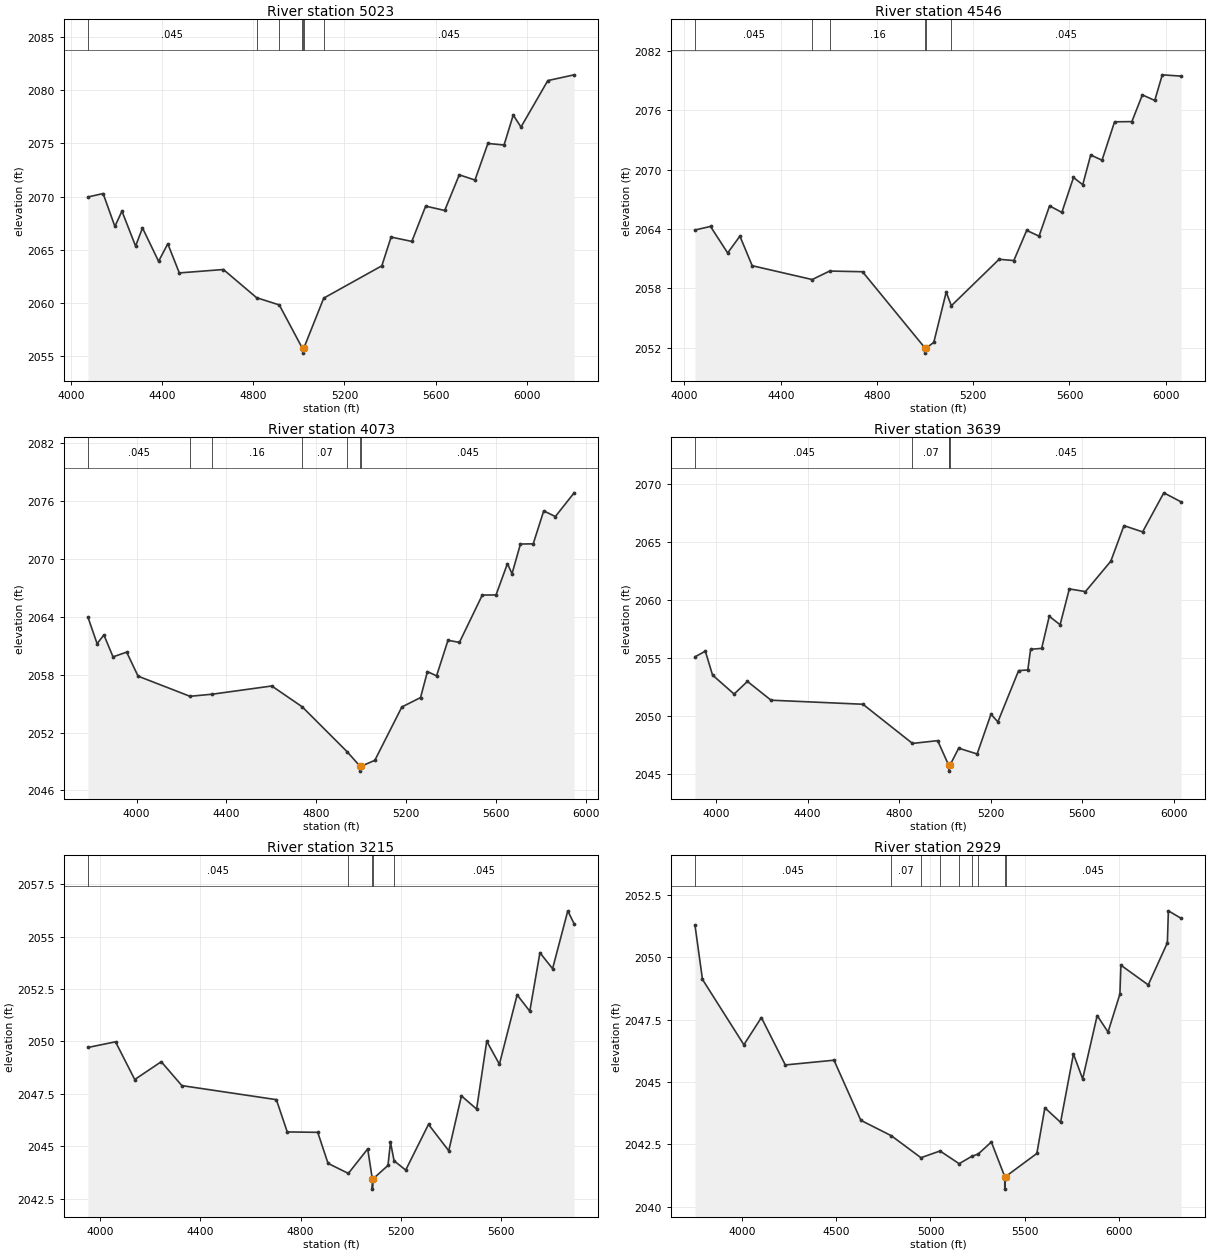
Type RM Length L Ch R = 1,5023,477,477,477
BEGIN DESCRIPTION:
Hackberry Creek Trib 02 7.0
END DESCRIPTION:
XS GIS Cut Line= 3
      1344887.98      6992313.56      1345805.00      6992438.00
      1346999.09      6992258.01
#Sta/Elev= 30
  4074.6 2069.96  4141.0 2070.28  4192.7 2067.19  4223.6 2068.63  4283.5 2065.34
  4313.8 2067.05  4384.4 2063.91  4424.8 2065.56  4475.3 2062.82  4668.7 2063.14
  4814.5 2060.49  4914.0 2059.81  5013.7 2055.80  5018.2 2055.78  5018.5 2055.28
  5022.2 2055.78  5109.0 2060.45  5364.0 2063.49  5404.5 2066.19  5495.6 2065.78
  5556.2 2069.10  5639.8 2068.69  5703.7 2072.04  5772.6 2071.55  5829.3 2074.99
  5900.1 2074.84  5940.5 2077.66  5974.4 2076.53  6092.2 2080.90  6207.6 2081.44
#Mann=7,-1,0
  4074.6   0.045       0  4814.5    0.07       0  4914.0   0.035       0
  5013.7    0.07       0  5018.2   0.035       0  5022.2    0.07       0
  5109.0   0.045       0
Bank Sta=5018.2,5022.2
Exp/Cntr=0.3,0.1

Type RM Length L Ch R = 1,4546,473,473,473
BEGIN DESCRIPTION:
Hackberry Creek Trib 02 6.0
END DESCRIPTION:
XS GIS Cut Line= 3
      1345061.62      6992653.84      1346005.00      6992838.00
      1347019.97      6992535.77
#Sta/Elev= 30
  4043.7 2063.90  4108.3 2064.26  4179.6 2061.58  4230.5 2063.28  4281.5 2060.29
  4530.8 2058.89  4603.5 2059.75  4740.0 2059.68  5000.3 2051.95  5000.6 2051.45
  5004.3 2051.95  5036.2 2052.54  5087.8 2057.62  5109.1 2056.24  5307.7 2060.94
  5368.8 2060.81  5422.2 2063.86  5473.6 2063.28  5517.2 2066.34  5568.3 2065.68
  5616.7 2069.21  5655.1 2068.48  5688.2 2071.48  5735.3 2070.96  5787.4 2074.84
  5859.3 2074.86  5902.9 2077.56  5954.4 2077.00  5985.7 2079.59  6063.9 2079.46
#Mann=6,-1,0
  4043.7   0.045       0  4530.8    0.07       0  4603.5    0.16       0
  5000.3    0.07       0  5004.3    0.16       0  5109.1   0.045       0
Bank Sta=5000.3,5004.3
Exp/Cntr=0.3,0.1

Type RM Length L Ch R = 1,4073,434,434,434
BEGIN DESCRIPTION:
Hackberry Creek Trib 02 5.0
END DESCRIPTION:
XS GIS Cut Line= 3
      1345054.96      6992987.99      1346255.00      6993188.00
      1347186.58      6993008.01
#Sta/Elev= 30
  3783.1 2063.96  3823.7 2061.22  3854.1 2062.12  3894.7 2059.85  3955.5 2060.34
  4006.2 2057.85  4237.6 2055.76  4337.5 2055.98  4601.8 2056.83  4737.3 2054.67
  4937.1 2050.02  4995.2 2048.50  4995.4 2048.00  4999.2 2048.50  5060.8 2049.12
  5181.1 2054.65  5264.5 2055.63  5295.1 2058.32  5335.8 2057.88  5386.7 2061.57
  5437.6 2061.35  5539.5 2066.26  5600.6 2066.27  5651.5 2069.52  5671.9 2068.47
  5709.4 2071.55  5766.3 2071.57  5813.1 2074.99  5864.9 2074.40  5948.5 2076.86
#Mann=7,-1,0
  3783.1   0.045       0  4237.6    0.07       0  4337.5    0.16       0
  4737.3    0.07       0  4937.1   0.045       0  4995.2   0.045       0
  4999.2   0.045       0
Bank Sta=4995.2,4999.2
Exp/Cntr=0.3,0.1

Type RM Length L Ch R = 1,3639,424,424,424
BEGIN DESCRIPTION:
Hackberry Creek Trib 02 4.0
END DESCRIPTION:
XS GIS Cut Line= 3
      1345311.59      6993264.94      1346355.00      6993588.00
      1347380.03      6993463.00
#Sta/Elev= 30
  3907.3 2055.11  3952.7 2055.60  3984.1 2053.54  4078.4 2051.90  4136.7 2052.99
  4239.7 2051.37  4641.5 2051.02  4858.0 2047.64  4968.2 2047.88  5016.0 2045.77
  5017.7 2045.75  5018.0 2045.25  5021.7 2045.75  5060.0 2047.23  5140.6 2046.73
  5201.1 2050.16  5231.3 2049.50  5321.9 2053.92  5362.2 2053.98  5374.3 2055.76
  5422.7 2055.84  5455.9 2058.61  5503.3 2057.88  5543.6 2060.97  5614.1 2060.74
  5724.9 2063.36  5782.3 2066.43  5863.9 2065.89  5956.6 2069.26  6032.2 2068.48
#Mann=5,-1,0
  3907.3   0.045       0  4858.0    0.07       0  5016.0   0.045       0
  5017.7    0.07       0  5021.7   0.045       0
Bank Sta=5017.7,5021.7
Exp/Cntr=0.3,0.1

Type RM Length L Ch R = 1,3215,286,286,286
BEGIN DESCRIPTION:
Hackberry Creek Trib 02 3.0
END DESCRIPTION:
XS GIS Cut Line= 3
      1345332.44      6993528.83      1346305.00      6993938.00
      1347179.99      6993813.00
#Sta/Elev= 30
  3951.6 2049.71  4061.5 2049.98  4138.1 2048.18  4243.9 2049.03  4326.0 2047.89
  4703.0 2047.22  4746.4 2045.68  4868.0 2045.66  4909.1 2044.18  4990.1 2043.70
  5067.3 2044.87  5085.5 2043.45  5085.8 2042.95  5089.5 2043.45  5148.1 2044.08
  5158.2 2045.19  5172.5 2044.30  5218.9 2043.86  5309.8 2046.04  5390.6 2044.78
  5441.1 2047.40  5501.7 2046.77  5542.1 2050.01  5592.6 2048.91  5663.3 2052.22
  5713.8 2051.44  5754.2 2054.23  5804.7 2053.47  5865.4 2056.23  5890.6 2055.61
#Mann=5,-1,0
  3951.6   0.045       0  4990.1    0.07       0  5085.5    0.07       0
  5089.5    0.07       0  5172.5   0.045       0
Bank Sta=5085.5,5089.5
Exp/Cntr=0.3,0.1

Type RM Length L Ch R = 1,2929,295,295,295
BEGIN DESCRIPTION:
Hackberry Creek Trib 02 0.85
END DESCRIPTION:
XS GIS Cut Line= 4
      1345161.06      6993707.88      1346146.28      6994147.97
      1346615.03      6994265.16      1347580.38      6993940.19
#Sta/Elev= 30
  3749.7 2051.30  3789.6 2049.12  4009.4 2046.50  4102.3 2047.59  4229.3 2045.69
  4487.8 2045.88  4630.2 2043.47  4792.4 2042.85  4949.5 2041.97  5050.8 2042.24
  5152.2 2041.73  5218.1 2042.02  5253.6 2042.12  5323.2 2042.60  5394.3 2041.21
  5394.5 2040.71  5398.3 2041.21  5564.6 2042.14  5607.3 2043.97  5690.6 2043.39
  5758.9 2046.13  5807.8 2045.13  5884.9 2047.67  5942.6 2047.01  6005.6 2048.53
  6010.9 2049.69  6156.0 2048.90  6257.6 2050.59  6262.9 2051.87  6330.5 2051.57
#Mann=9,-1,0
  3749.7   0.045       0  4792.4    0.07       0  4949.5   0.045       0
  5050.8    0.07       0  5152.2   0.045       0  5218.1   0.035       0
  5253.6   0.045       0  5394.3   0.045       0  5398.3   0.045       0
Bank Sta=5394.3,5398.3
Exp/Cntr=0.3,0.1

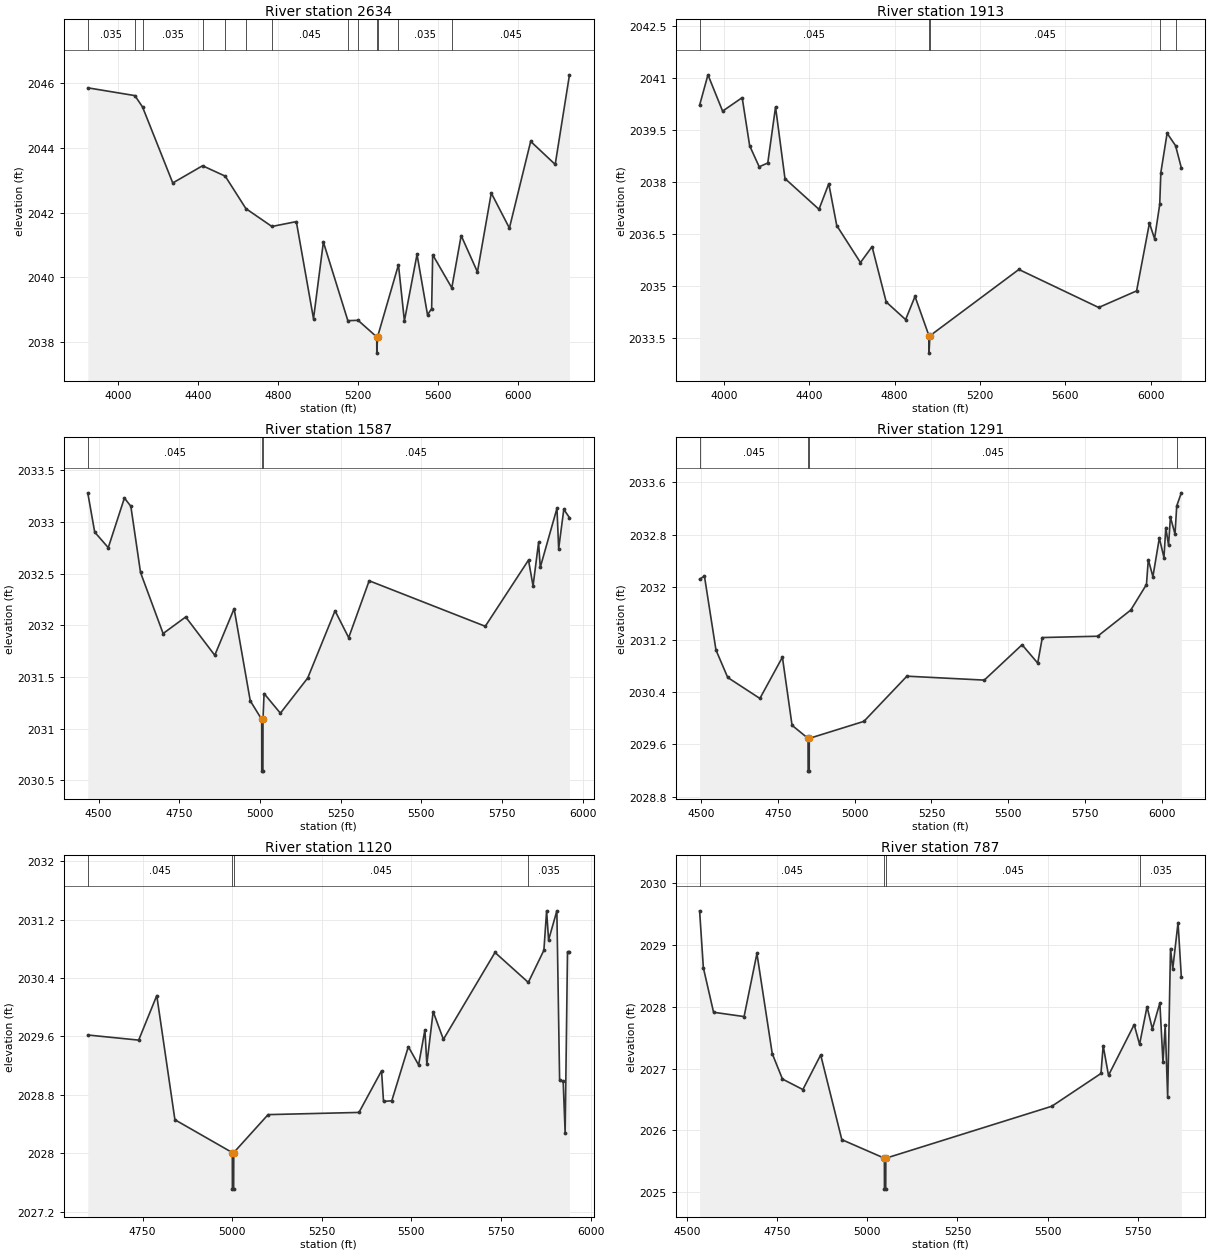
Type RM Length L Ch R = 1,2634,721,721,721
BEGIN DESCRIPTION:
Hackberry Creek Trib 02 2.0
END DESCRIPTION:
XS GIS Cut Line= 4
      1345311.57      6994042.71      1346148.88      6994321.15
      1346719.19      6994470.89      1347610.09      6994181.66
#Sta/Elev= 30
  3847.5 2045.84  4083.2 2045.60  4121.4 2045.25  4272.6 2042.91  4421.6 2043.44
  4534.9 2043.12  4638.3 2042.12  4768.2 2041.57  4890.4 2041.72  4976.3 2038.73
  5025.7 2041.09  5148.0 2038.67  5199.1 2038.68  5292.5 2038.17  5292.8 2037.67
  5296.5 2038.17  5401.1 2040.39  5430.8 2038.66  5493.9 2040.71  5546.4 2038.85
  5567.0 2039.04  5572.2 2040.70  5667.8 2039.68  5714.6 2041.29  5796.0 2040.17
  5865.2 2042.60  5955.8 2041.52  6062.2 2044.19  6184.8 2043.48  6256.2 2046.24
#Mann=13,-1,0
  3847.5   0.035       0  4083.2   0.045       0  4121.4   0.035       0
  4421.6   0.045       0  4534.9    0.07       0  4638.3   0.035       0
  4768.2   0.045       0  5148.0   0.035       0  5199.1   0.045       0
  5292.5   0.045       0  5296.5   0.045       0  5401.1   0.035       0
  5667.8   0.045       0
Bank Sta=5292.5,5296.5
Exp/Cntr=0.3,0.1

Type RM Length L Ch R = 1,1913,326,326,326
BEGIN DESCRIPTION:
Hackberry Creek Trib 02 1.0
END DESCRIPTION:
XS GIS Cut Line= 4
      1345582.45      6994577.45      1346497.29      6995002.75
      1346605.00      6994988.00      1347658.84      6994556.61
#Sta/Elev= 30
  3887.0 2040.22  3926.1 2041.10  3994.8 2040.05  4086.4 2040.44  4121.4 2039.05
  4166.1 2038.44  4206.3 2038.55  4242.7 2040.17  4286.8 2038.10  4446.2 2037.21
  4492.0 2037.95  4529.4 2036.74  4640.4 2035.67  4694.8 2036.13  4761.0 2034.53
  4851.9 2034.02  4895.9 2034.69  4961.4 2033.55  4961.7 2033.05  4965.4 2033.55
  5382.4 2035.47  5756.2 2034.37  5933.8 2034.85  5993.9 2036.81  6017.9 2036.36
  6042.1 2037.35  6047.3 2038.27  6076.7 2039.41  6116.4 2039.05  6143.3 2038.41
#Mann=5,-1,0
  3887.0   0.045       0  4961.4   0.045       0  4965.4   0.045       0
  6042.1   0.035       0  6116.4   0.045       0
Bank Sta=4961.4,4965.4
Exp/Cntr=0.3,0.1

Type RM Length L Ch R = 1,1587,296,296,296
BEGIN DESCRIPTION:
Hackberry Creek Trib 02 0.9
END DESCRIPTION:
XS GIS Cut Line= 3
      1346221.46      6995242.38      1346755.98      6995255.85
      1347661.66      6994942.01
#Sta/Elev= 30
  4466.3 2033.28  4487.9 2032.90  4529.9 2032.75  4579.9 2033.23  4599.9 2033.15
  4629.9 2032.51  4699.9 2031.92  4769.9 2032.08  4860.0 2031.71  4920.0 2032.16
  4970.0 2031.27  5005.5 2031.09  5005.7 2030.59  5009.2 2030.59  5009.5 2031.09
  5012.8 2031.34  5063.4 2031.15  5148.1 2031.49  5232.8 2032.14  5275.1 2031.88
  5338.6 2032.43  5698.5 2031.99  5832.5 2032.63  5846.6 2032.38  5863.7 2032.80
  5869.0 2032.56  5920.7 2033.13  5926.0 2032.74  5941.9 2033.12  5959.5 2033.04
#Mann=3,-1,0
  4466.3   0.045       0  5005.5   0.045       0  5009.5   0.045       0
Bank Sta=5005.5,5009.5
Exp/Cntr=0.3,0.1

Type RM Length L Ch R = 1,1291,171,171,171
BEGIN DESCRIPTION:
Hackberry Creek Trib 02 0.95
END DESCRIPTION:
XS GIS Cut Line= 4
      1346337.66      6995417.49      1346726.26      6995539.67
      1346952.27      6995429.65      1347709.02      6994922.84
#Sta/Elev= 30
  4494.8 2032.12  4510.5 2032.17  4548.1 2031.04  4586.4 2030.62  4691.2 2030.30
  4764.6 2030.93  4796.0 2029.89  4848.1 2029.69  4848.4 2029.19  4851.9 2029.19
  4852.1 2029.69  5030.1 2029.95  5170.2 2030.64  5422.3 2030.58  5545.4 2031.12
  5596.4 2030.84  5611.4 2031.23  5791.6 2031.25  5899.6 2031.65  5950.7 2032.04
  5956.7 2032.42  5971.7 2032.16  5992.7 2032.75  6007.7 2032.45  6013.7 2032.91
  6022.7 2032.64  6028.7 2033.07  6043.7 2032.81  6049.3 2033.24  6064.3 2033.44
#Mann=4,-1,0
  4494.8   0.045       0  4848.1   0.045       0  4852.1   0.045       0
  6049.3   0.035       0
Bank Sta=4848.1,4852.1
Exp/Cntr=0.3,0.1

Type RM Length L Ch R = 1,1120,333,333,333
BEGIN DESCRIPTION:
Hackberry Creek Trib 02 0.8
END DESCRIPTION:
XS GIS Cut Line= 3
      1346504.42      6995579.28      1346899.73      6995637.67
      1347760.00      6995247.54
#Sta/Elev= 30
  4596.9 2029.62  4739.0 2029.55  4789.5 2030.16  4840.1 2028.46  5000.3 2028.01
  5000.5 2027.51  5004.0 2027.51  5004.3 2028.01  5100.1 2028.53  5353.7 2028.56
  5416.7 2029.13  5422.2 2028.71  5445.3 2028.72  5491.5 2029.46  5520.1 2029.21
  5537.7 2029.69  5543.1 2029.22  5560.7 2029.94  5589.3 2029.56  5733.3 2030.75
  5826.2 2030.34  5869.7 2030.78  5877.3 2031.32  5882.8 2030.92  5905.9 2031.32
  5913.6 2029.00  5923.5 2028.99  5929.0 2028.28  5935.6 2030.76  5941.1 2030.76
#Mann=4,-1,0
  4596.9   0.045       0  5000.3   0.045       0  5004.3   0.045       0
  5826.2   0.035       0
Bank Sta=5000.3,5004.3
Exp/Cntr=0.3,0.1

Type RM Length L Ch R = 1,787,218,218,218
BEGIN DESCRIPTION:
Hackberry Creek Trib 02 0.7
END DESCRIPTION:
XS GIS Cut Line= 4
      1346658.96      6995629.50      1346920.25      6995904.76
      1347072.92      6995904.76      1347725.79      6995436.54
#Sta/Elev= 30
  4535.1 2029.55  4545.5 2028.63  4573.8 2027.91  4658.4 2027.84  4694.0 2028.86
  4736.5 2027.24  4764.8 2026.83  4821.4 2026.66  4870.8 2027.22  4929.4 2025.85
  5047.4 2025.55  5047.6 2025.05  5051.1 2025.05  5051.4 2025.55  5511.6 2026.39
  5647.9 2026.92  5654.0 2027.37  5668.8 2026.89  5740.0 2027.71  5754.9 2027.39
  5775.6 2028.00  5790.4 2027.64  5811.2 2028.06  5819.8 2027.10  5826.0 2027.70
  5832.8 2026.54  5840.7 2028.94  5846.9 2028.61  5861.6 2029.36  5870.7 2028.48
#Mann=4,-1,0
  4535.1   0.045       0  5047.4   0.045       0  5051.4   0.045       0
  5754.9   0.035       0
Bank Sta=5047.4,5051.4
Exp/Cntr=0.3,0.1

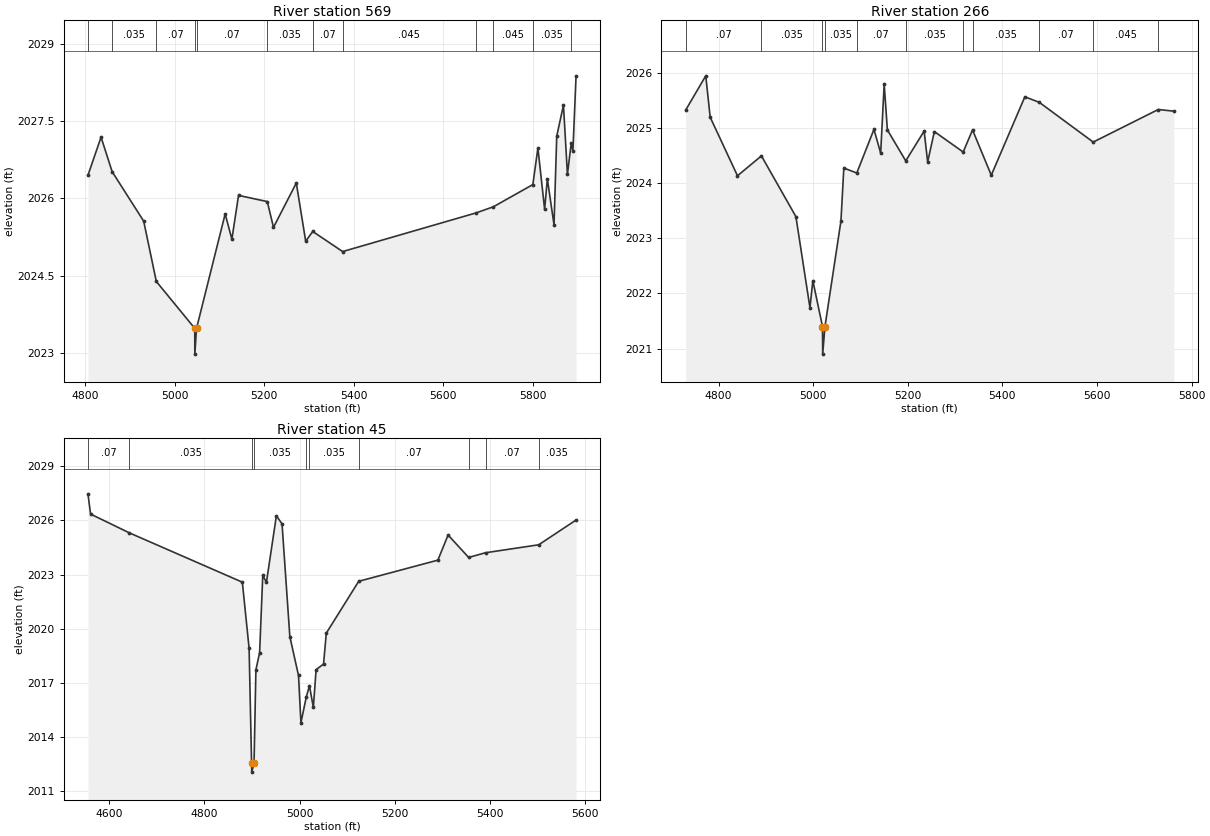
Type RM Length L Ch R = 1,569,303,303,303
BEGIN DESCRIPTION:
Hackberry Creek Trib 02 0.6
END DESCRIPTION:
XS GIS Cut Line= 5
      1346829.99      6995962.96      1346880.00      6996083.28
      1346945.00      6996103.91      1346980.00      6996113.00
      1347690.89      6995635.53
#Sta/Elev= 30
  4805.7 2026.45  4835.0 2027.19  4859.8 2026.52  4930.3 2025.56  4958.5 2024.39
  5044.4 2023.48  5044.6 2022.98  5048.4 2023.48  5112.4 2025.70  5127.4 2025.21
  5142.3 2026.06  5206.5 2025.94  5220.4 2025.44  5271.4 2026.30  5292.4 2025.17
  5308.1 2025.36  5375.0 2024.97  5673.1 2025.72  5712.1 2025.84  5800.1 2026.27
  5811.4 2026.98  5826.4 2025.79  5832.5 2026.38  5847.4 2025.49  5853.5 2027.21
  5868.5 2027.81  5877.4 2026.47  5885.8 2027.07  5889.6 2026.92  5896.7 2028.38
#Mann=12,-1,0
  4805.7    0.07       0  4859.8   0.035       0  4958.5    0.07       0
  5044.4    0.07       0  5048.4    0.07       0  5206.5   0.035       0
  5308.1    0.07       0  5375.0   0.045       0  5673.1   0.035       0
  5712.1   0.045       0  5800.1   0.035       0  5885.8   0.045       0
Bank Sta=5044.4,5048.4
Exp/Cntr=0.3,0.1

Type RM Length L Ch R = 1,266,221,221,221
BEGIN DESCRIPTION:
Hackberry Creek Trib 02 0.5
END DESCRIPTION:
XS GIS Cut Line= 4
      1346730.01      6996263.01      1346906.98      6996374.29
      1347016.82      6996298.25      1347526.83      6995834.61
#Sta/Elev= 30
  4730.4 2025.32  4772.8 2025.94  4782.2 2025.19  4839.9 2024.13  4890.5 2024.49
  4963.4 2023.39  4993.1 2021.74  4999.2 2022.23  5019.6 2021.40  5020.0 2020.90
  5024.8 2021.40  5058.6 2023.31  5064.7 2024.27  5092.1 2024.18  5128.4 2024.97
  5142.6 2024.54  5150.0 2025.79  5156.8 2024.96  5195.6 2024.40  5234.5 2024.94
  5241.9 2024.38  5256.1 2024.93  5317.0 2024.56  5336.8 2024.96  5376.4 2024.14
  5447.4 2025.56  5477.9 2025.46  5591.9 2024.74  5729.4 2025.33  5762.3 2025.30
#Mann=11,-1,0
  4730.4    0.07       0  4890.5   0.035       0  5019.6   0.035       0
  5024.8   0.035       0  5092.1    0.07       0  5195.6   0.035       0
  5317.0    0.07       0  5336.8   0.035       0  5477.9    0.07       0
  5591.9   0.045       0  5729.4   0.035       0
Bank Sta=5019.6,5024.8
Exp/Cntr=0.3,0.1

Type RM Length L Ch R = 1,45,0,0,0
BEGIN DESCRIPTION:
Hackberry Creek Trib 02 0.4
END DESCRIPTION:
XS GIS Cut Line= 4
      1346656.34      6996288.95      1346969.00      6996550.83
      1347023.54      6996539.15      1347308.39      6996054.71
#Sta/Elev= 30
  4555.3 2027.47  4560.8 2026.35  4642.3 2025.31  4879.7 2022.58  4893.9 2018.92
  4899.1 2012.57  4899.5 2012.07  4904.3 2012.57  4908.2 2017.73  4916.0 2018.68
  4922.6 2022.96  4930.3 2022.57  4951.2 2026.25  4963.1 2025.81  4979.5 2019.57
  4997.7 2017.42  5002.8 2014.80  5014.1 2016.23  5020.7 2016.85  5028.9 2015.65
  5034.7 2017.74  5050.3 2018.05  5056.1 2019.76  5124.2 2022.63  5290.5 2023.80
  5312.0 2025.19  5355.2 2023.95  5390.7 2024.21  5502.4 2024.65  5580.9 2026.02
#Mann=10,-1,0
  4555.3    0.07       0  4642.3   0.035       0  4899.1   0.035       0
  4904.3   0.035       0  5014.1    0.07       0  5020.7   0.035       0
  5124.2    0.07       0  5355.2   0.035       0  5390.7    0.07       0
  5502.4   0.035       0
Bank Sta=4899.1,4904.3
Exp/Cntr=0.3,0.1

Chan Stop Cuts=-1