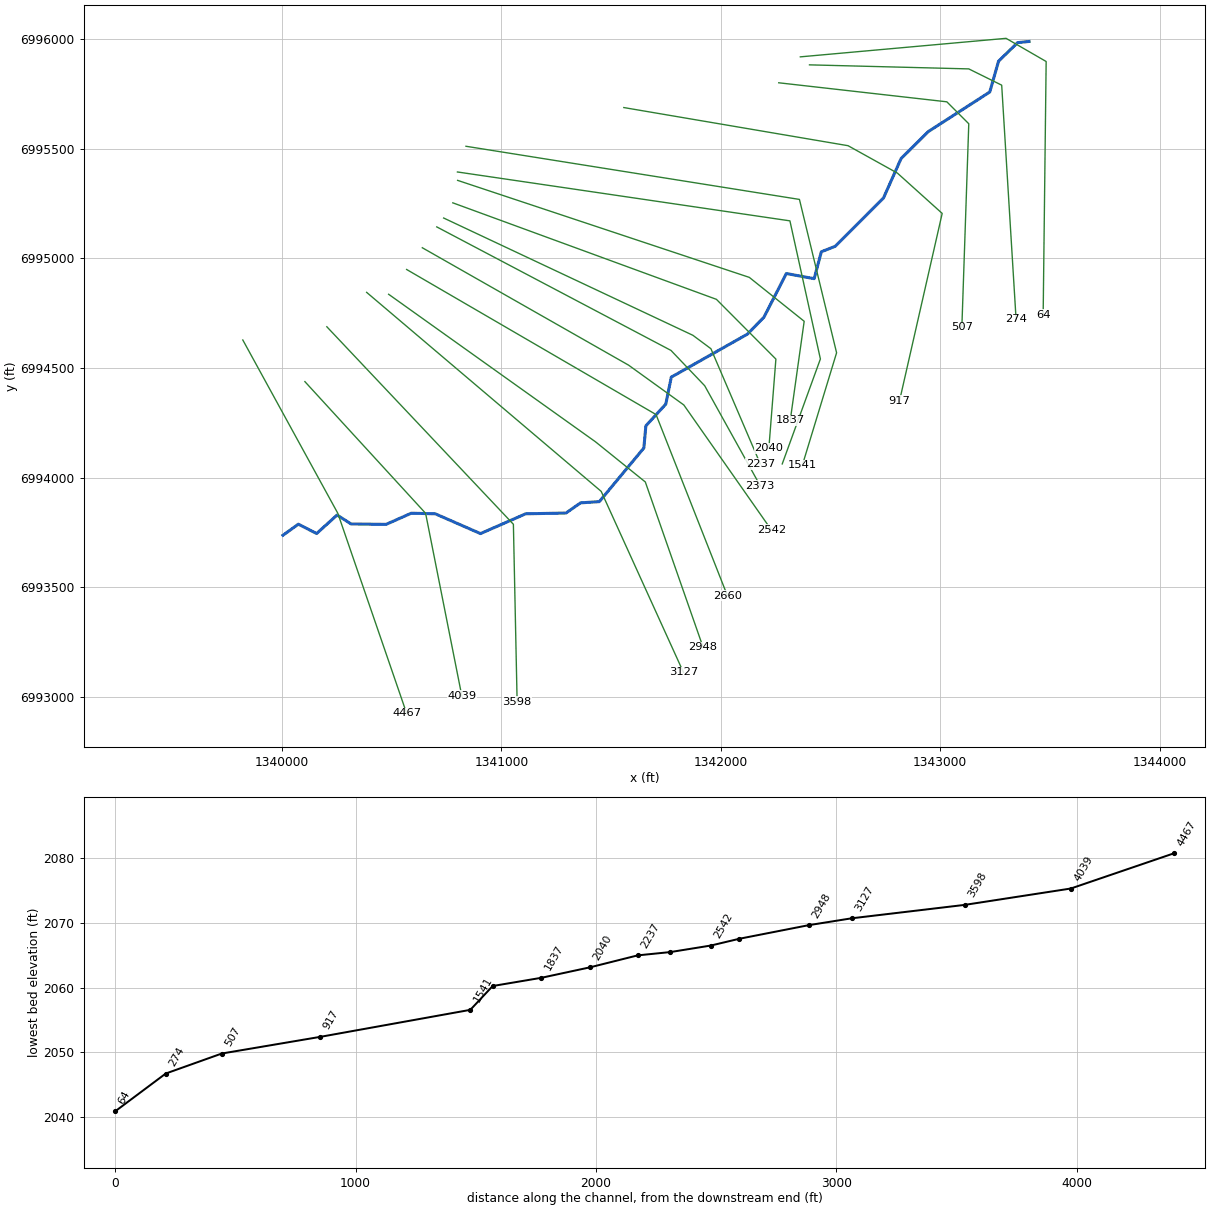
--- Hackberry Creek Trib 03.prj (project) ---

Proj Title=Hackberry Creek Trib 03 Base Level Engineering
Current Plan=p01
Default Exp/Contr=0.3,0.1
English Units
Geom File=g01
Flow File=f01
Plan File=p01
BEGIN DESCRIPTION:
Hackberry Creek Trib 03
END DESCRIPTION:

--- Hackberry Creek Trib 03.p01 (plan) ---

Plan Title=Multiple Run
Short Identifier=Multiple
Geom File=g01
Flow File=f01
Subcritical Flow
K Sum by GR= 0
Std Step Tol= 0.01
Critical Tol= 0.01
Num of Std Step Trials= 20
Max Error Tol= 0.3
Flow Tol Ratio= 0.001
Split Flow NTrial= 30
Split Flow Tol= 0.02
Split Flow Ratio= 0.02
Log Output Level= 0
Friction Slope Method= 1
Unsteady Friction Slope Method= 2
Unsteady Bridges Friction Slope Method= 1
Parabolic Critical Depth
Global Vel Dist=  1 , 1 , 1
Global Log Level= 0
CheckData=True
Encroach Param= -1, 0, 0, 0
BEGIN DESCRIPTION:
Multiple Run
END DESCRIPTION:

--- Hackberry Creek Trib 03.f01 (steady flow) ---

Flow Title=Multiple
Number of Profiles=7
Profile Names=10-year,25-year,50-year,1pct_min,100-year,1pct_plu,500-year
River Rch & RM= Hackberry Creek ,Reach-1,4467
     175     240     293     178     355     709     529
Boundary for River Rch & Prof#=Hackberry Creek ,Reach-1,1
Up Type=0
Dn Type=3
Dn Slope=0.005
Boundary for River Rch & Prof#=Hackberry Creek ,Reach-1,2
Up Type=0
Dn Type=3
Dn Slope=0.005
Boundary for River Rch & Prof#=Hackberry Creek ,Reach-1,3
Up Type=0
Dn Type=3
Dn Slope=0.005
Boundary for River Rch & Prof#=Hackberry Creek ,Reach-1,4
Up Type=0
Dn Type=3
Dn Slope=0.005
Boundary for River Rch & Prof#=Hackberry Creek ,Reach-1,5
Up Type=0
Dn Type=3
Dn Slope=0.005
Boundary for River Rch & Prof#=Hackberry Creek ,Reach-1,6
Up Type=0
Dn Type=3
Dn Slope=0.005
Boundary for River Rch & Prof#=Hackberry Creek ,Reach-1,7
Up Type=0
Dn Type=3
Dn Slope=0.005

--- Hackberry Creek Trib 03.g01 (geometry) ---

Geom Title=Existing Conditions

River Reach=Hackberry Creek ,Reach-1
Reach XY= 30
      1340005.00      6993738.00      1340075.25      6993788.46
      1340158.41      6993745.83      1340251.58      6993830.18
      1340315.43      6993789.39      1340475.15      6993787.64
      1340589.84      6993838.47      1340699.06      6993835.75
      1340905.00      6993745.56      1341110.94      6993835.74
      1341294.50      6993839.22      1341361.06      6993885.61
      1341446.65      6993891.19      1341649.46      6994135.58
      1341658.63      6994236.50      1341749.46      6994335.58
      1341774.47      6994458.54      1342121.71      6994654.63
      1342196.87      6994731.93      1342298.67      6994930.62
      1342425.51      6994907.11      1342458.17      6995029.65
      1342521.45      6995054.74      1342741.38      6995274.79
      1342821.64      6995454.68      1342945.52      6995577.37
      1343225.57      6995757.59      1343265.50      6995897.81
      1343352.46      6995982.70      1343405.00      6995988.00

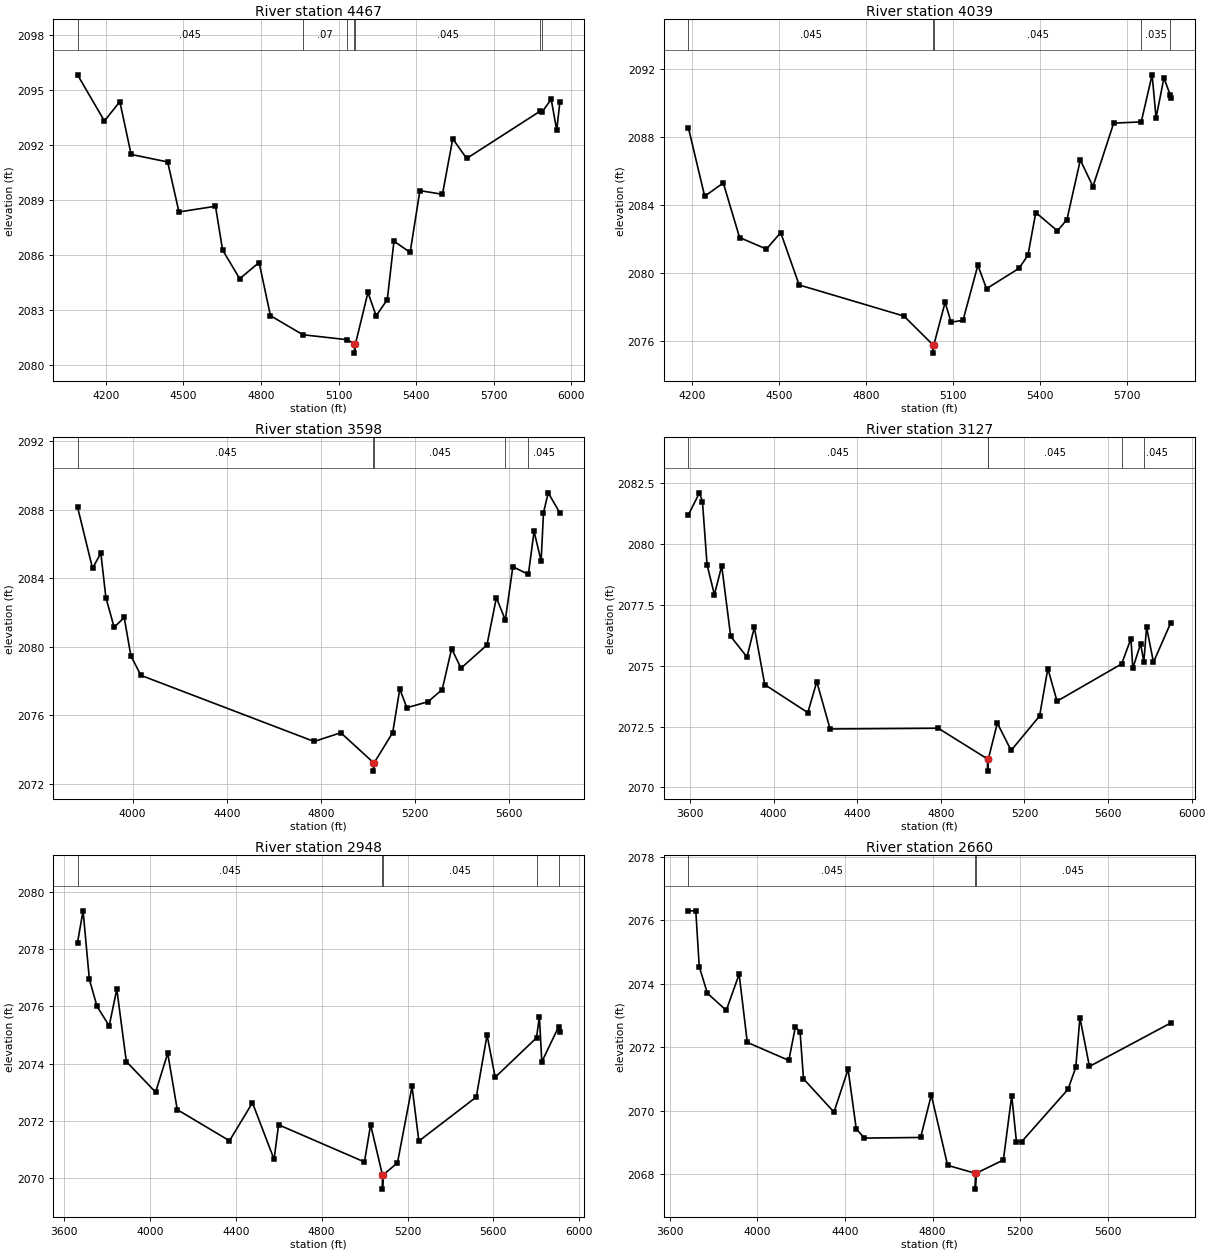
Type RM Length L Ch R = 1,4467,428,428,428
BEGIN DESCRIPTION:
Hackberry Creek Trib 03 8.0
END DESCRIPTION:
XS GIS Cut Line= 3
      1339822.05      6994627.76      1340255.00      6993838.00
      1340568.57      6992926.37
#Sta/Elev= 30
  4091.1 2095.81  4195.0 2093.30  4254.7 2094.35  4298.3 2091.48  4439.6 2091.07
  4483.2 2088.35  4624.4 2088.66  4651.9 2086.28  4718.0 2084.72  4793.1 2085.60
  4836.8 2082.71  4962.2 2081.67  5133.3 2081.40  5161.5 2081.17  5161.8 2080.67
  5165.5 2081.17  5213.8 2083.97  5245.5 2082.70  5288.5 2083.58  5314.4 2086.76
  5376.9 2086.15  5414.7 2089.51  5501.8 2089.31  5541.6 2092.33  5595.5 2091.26
  5879.1 2093.83  5887.9 2093.81  5922.3 2094.48  5943.5 2092.80  5955.8 2094.32
#Mann=7,-1,0
  4091.1   0.045       0  4962.2    0.07       0  5133.3   0.045       0
  5161.5    0.07       0  5165.5   0.045       0  5879.1   0.035       0
  5887.9   0.045       0
Bank Sta=5161.5,5165.5
Exp/Cntr=0.3,0.1

Type RM Length L Ch R = 1,4039,441,441,441
BEGIN DESCRIPTION:
Hackberry Creek Trib 03 7.0
END DESCRIPTION:
XS GIS Cut Line= 3
      1340105.00      6994438.00      1340655.00      6993838.00
      1340820.15      6993005.26
#Sta/Elev= 30
  4186.7 2088.53  4243.1 2084.49  4307.2 2085.27  4363.4 2082.06  4455.9 2081.38
  4505.2 2082.35  4568.7 2079.27  4930.0 2077.44  5029.3 2075.76  5029.6 2075.26
  5033.3 2075.76  5072.0 2078.25  5092.4 2077.08  5133.7 2077.19  5184.9 2080.43
  5214.7 2079.05  5326.9 2080.25  5357.5 2081.02  5384.6 2083.53  5459.4 2082.45
  5492.0 2083.12  5538.1 2086.62  5581.7 2085.06  5653.1 2088.79  5748.1 2088.86
  5785.6 2091.63  5799.2 2089.10  5826.4 2091.45  5847.4 2090.47  5849.6 2090.26
#Mann=5,-1,0
  4186.7   0.045       0  5029.3   0.045       0  5033.3   0.045       0
  5748.1   0.035       0  5847.4   0.045       0
Bank Sta=5029.3,5033.3
Exp/Cntr=0.3,0.1

Type RM Length L Ch R = 1,3598,471,471,471
BEGIN DESCRIPTION:
Hackberry Creek Trib 03 6.0
END DESCRIPTION:
XS GIS Cut Line= 3
      1340204.98      6994688.02      1341055.00      6993788.00
      1341072.03      6992978.45
#Sta/Elev= 30
  3766.6 2088.15  3830.3 2084.57  3865.5 2085.47  3887.0 2082.86  3922.2 2081.13
  3964.7 2081.71  3993.0 2079.47  4035.5 2078.33  4770.9 2074.47  4884.2 2074.98
  5022.6 2073.24  5022.8 2072.74  5026.6 2073.24  5104.6 2074.99  5134.6 2077.53
  5164.6 2076.44  5254.6 2076.79  5314.6 2077.50  5354.7 2079.88  5394.7 2078.75
  5504.7 2080.10  5544.7 2082.86  5582.6 2081.56  5614.7 2084.67  5680.5 2084.22
  5704.7 2086.73  5734.7 2085.00  5744.7 2087.82  5764.7 2088.98  5814.3 2087.81
#Mann=5,-1,0
  3766.6   0.045       0  5022.6   0.045       0  5026.6   0.045       0
  5582.6   0.035       0  5680.5   0.045       0
Bank Sta=5022.6,5026.6
Exp/Cntr=0.3,0.1

Type RM Length L Ch R = 1,3127,179,179,179
BEGIN DESCRIPTION:
Hackberry Creek Trib 03 5.0
END DESCRIPTION:
XS GIS Cut Line= 3
      1340386.25      6994844.82      1341455.00      6993938.00
      1341830.02      6993112.96
#Sta/Elev= 30
  3591.7 2081.18  3645.0 2082.09  3659.3 2081.73  3681.3 2079.14  3716.4 2077.91
  3751.5 2079.09  3794.4 2076.20  3872.4 2075.35  3907.5 2076.57  3957.3 2074.22
  4163.5 2073.07  4206.3 2074.34  4270.0 2072.40  4787.4 2072.43  5023.2 2071.17
  5023.4 2070.67  5027.2 2071.17  5070.2 2072.64  5136.1 2071.52  5272.3 2072.93
  5311.9 2074.88  5355.8 2073.54  5665.1 2075.07  5709.5 2076.11  5718.3 2074.89
  5755.7 2075.89  5771.3 2075.16  5784.2 2076.58  5817.2 2075.14  5899.6 2076.75
#Mann=5,-1,0
  3591.7   0.045       0  5023.2   0.045       0  5027.2   0.045       0
  5665.1   0.035       0  5771.3   0.045       0
Bank Sta=5023.2,5027.2
Exp/Cntr=0.3,0.1

Type RM Length L Ch R = 1,2948,288,288,288
BEGIN DESCRIPTION:
Hackberry Creek Trib 03 4.1
END DESCRIPTION:
XS GIS Cut Line= 4
      1340486.50      6994836.04      1341429.54      6994163.49
      1341656.16      6993980.73      1341919.31      6993227.82
#Sta/Elev= 30
  3662.7 2078.23  3688.4 2079.34  3717.9 2076.94  3753.5 2076.00  3810.1 2075.32
  3845.7 2076.60  3890.0 2074.07  4026.4 2073.00  4082.9 2074.36  4127.2 2072.39
  4370.6 2071.30  4477.5 2072.63  4578.3 2070.65  4599.2 2071.86  4999.2 2070.56
  5028.0 2071.86  5082.9 2070.11  5083.2 2069.61  5086.9 2070.11  5153.1 2070.53
  5220.9 2073.20  5252.7 2071.29  5520.3 2072.83  5570.5 2075.00  5608.2 2073.52
  5800.8 2074.90  5814.2 2075.64  5825.5 2074.06  5903.5 2075.28  5909.7 2075.10
#Mann=5,-1,0
  3662.7   0.045       0  5082.9   0.045       0  5086.9   0.045       0
  5800.8   0.035       0  5903.5   0.045       0
Bank Sta=5082.9,5086.9
Exp/Cntr=0.3,0.1

Type RM Length L Ch R = 1,2660,118,118,118
BEGIN DESCRIPTION:
Hackberry Creek Trib 03 4.0
END DESCRIPTION:
XS GIS Cut Line= 3
      1340568.55      6994948.98      1341705.00      6994288.00
      1342030.00      6993462.99
#Sta/Elev= 30
  3685.3 2076.30  3719.4 2076.30  3735.1 2074.54  3772.3 2073.70  3858.4 2073.16
  3917.2 2074.30  3954.4 2072.15  4143.9 2071.58  4173.7 2072.63  4195.2 2072.49
  4210.9 2071.00  4350.0 2069.95  4414.5 2071.30  4451.7 2069.42  4489.0 2069.13
  4745.5 2069.15  4794.3 2070.49  4868.8 2068.27  4995.1 2068.02  4995.3 2067.52
  4999.1 2068.02  5123.2 2068.44  5161.2 2070.47  5182.7 2069.02  5207.1 2069.02
  5418.3 2070.67  5453.5 2071.36  5472.5 2072.93  5515.9 2071.39  5886.7 2072.76
#Mann=3,-1,0
  3685.3   0.045       0  4995.1   0.045       0  4999.1   0.045       0
Bank Sta=4995.1,4999.1
Exp/Cntr=0.3,0.1

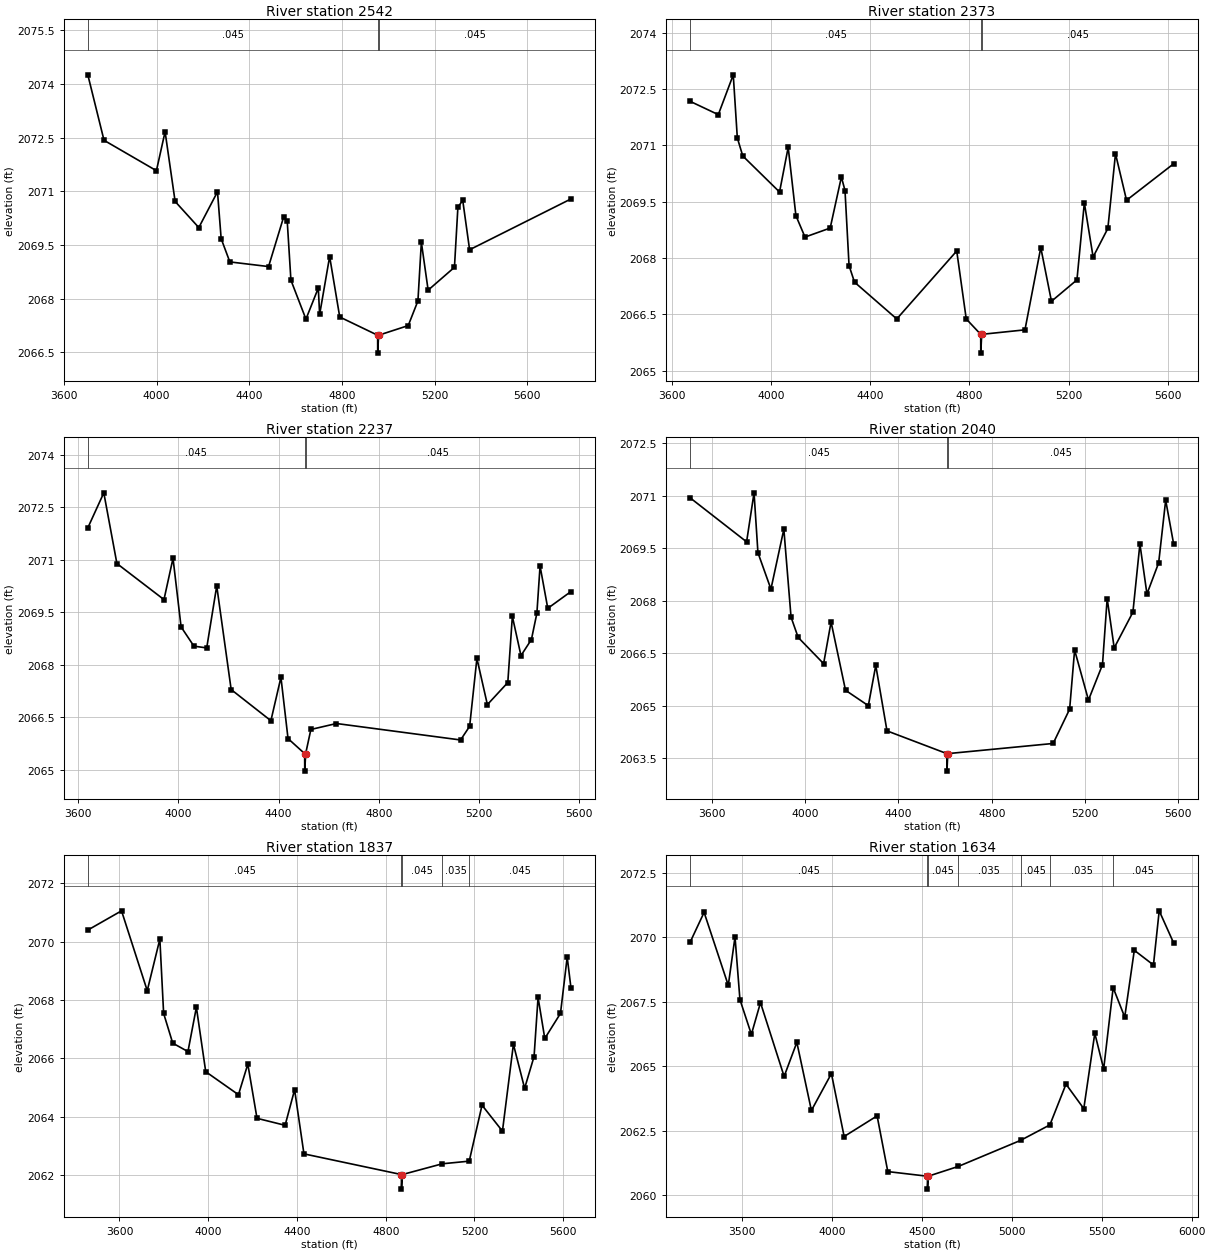
Type RM Length L Ch R = 1,2542,169,169,169
BEGIN DESCRIPTION:
Hackberry Creek Trib 03 3.2
END DESCRIPTION:
XS GIS Cut Line= 4
      1340640.02      6995048.03      1341580.00      6994513.00
      1341831.60      6994331.62      1342229.97      6993763.04
#Sta/Elev= 30
  3702.7 2074.26  3772.6 2072.43  3998.9 2071.58  4036.3 2072.67  4079.6 2070.72
  4181.9 2069.99  4262.6 2070.99  4278.4 2069.68  4315.9 2069.03  4483.1 2068.90
  4548.4 2070.29  4563.8 2070.16  4579.6 2068.52  4644.5 2067.43  4697.8 2068.30
  4703.6 2067.56  4746.8 2069.18  4790.4 2067.49  4954.1 2066.98  4954.3 2066.48
  4958.1 2066.98  5086.1 2067.25  5128.0 2067.94  5142.8 2069.58  5172.1 2068.24
  5285.7 2068.88  5300.6 2070.56  5321.5 2070.75  5351.1 2069.37  5788.7 2070.79
#Mann=3,-1,0
  3702.7   0.045       0  4954.1   0.045       0  4958.1   0.045       0
Bank Sta=4954.1,4958.1
Exp/Cntr=0.3,0.1

Type RM Length L Ch R = 1,2373,136,136,136
BEGIN DESCRIPTION:
Hackberry Creek Trib 03 3.1
END DESCRIPTION:
XS GIS Cut Line= 4
      1340705.84      6995143.04      1341773.12      6994580.17
      1341926.63      6994419.34      1342180.00      6993963.00
#Sta/Elev= 30
  3673.3 2072.17  3785.8 2071.82  3846.2 2072.88  3862.6 2071.20  3884.6 2070.72
  4033.1 2069.76  4068.0 2070.95  4099.2 2069.13  4135.9 2068.56  4237.6 2068.80
  4282.8 2070.16  4297.4 2069.80  4313.8 2067.80  4335.8 2067.36  4506.4 2066.38
  4748.6 2068.19  4787.0 2066.38  4845.4 2065.97  4845.7 2065.47  4849.4 2065.97
  5024.1 2066.09  5088.0 2068.28  5131.1 2066.85  5234.0 2067.42  5263.9 2069.47
  5299.3 2068.03  5358.8 2068.79  5389.7 2070.78  5434.3 2069.54  5624.2 2070.51
#Mann=3,-1,0
  3673.3   0.045       0  4845.4   0.045       0  4849.4   0.045       0
Bank Sta=4845.4,4849.4
Exp/Cntr=0.3,0.1

Type RM Length L Ch R = 1,2237,197,197,197
BEGIN DESCRIPTION:
Hackberry Creek Trib 03 3.0
END DESCRIPTION:
XS GIS Cut Line= 4
      1340737.29      6995183.51      1341872.90      6994649.11
      1341955.00      6994588.00      1342180.00      6994063.00
#Sta/Elev= 30
  3638.3 2071.91  3702.1 2072.91  3754.4 2070.89  3942.3 2069.86  3978.4 2071.04
  4010.6 2069.08  4061.8 2068.53  4112.9 2068.48  4152.9 2070.25  4210.5 2067.29
  4369.1 2066.40  4409.2 2067.64  4437.5 2065.89  4503.9 2065.46  4504.2 2064.96
  4507.9 2065.46  4528.7 2066.15  4630.9 2066.32  5126.3 2065.85  5162.5 2066.24
  5191.5 2068.18  5233.3 2066.86  5314.8 2067.49  5333.0 2069.38  5367.4 2068.26
  5409.1 2068.72  5430.9 2069.47  5443.6 2070.82  5474.4 2069.61  5566.9 2070.09
#Mann=3,-1,0
  3638.3   0.045       0  4503.9   0.045       0  4507.9   0.045       0
Bank Sta=4503.9,4507.9
Exp/Cntr=0.3,0.1

Type RM Length L Ch R = 1,2040,203,203,203
BEGIN DESCRIPTION:
Hackberry Creek Trib 03 2.2
END DESCRIPTION:
XS GIS Cut Line= 4
      1340778.98      6995252.69      1341980.00      6994813.00
      1342251.10      6994540.71      1342219.04      6994134.28
#Sta/Elev= 30
  3508.5 2070.93  3749.2 2069.68  3781.1 2071.08  3797.8 2069.37  3853.5 2068.33
  3908.9 2070.04  3939.7 2067.53  3970.2 2066.95  4079.3 2066.20  4111.3 2067.39
  4173.2 2065.44  4271.0 2065.00  4302.9 2066.15  4351.0 2064.28  4607.7 2063.63
  4607.9 2063.13  4611.7 2063.63  5063.2 2063.92  5133.9 2064.90  5155.2 2066.59
  5214.6 2065.16  5274.7 2066.17  5294.8 2068.06  5324.9 2066.65  5405.1 2067.67
  5435.1 2069.62  5465.3 2068.19  5515.5 2069.08  5545.6 2070.87  5579.4 2069.63
#Mann=3,-1,0
  3508.5   0.045       0  4607.7   0.045       0  4611.7   0.045       0
Bank Sta=4607.7,4611.7
Exp/Cntr=0.3,0.1

Type RM Length L Ch R = 1,1837,203,203,203
BEGIN DESCRIPTION:
Hackberry Creek Trib 03 2.1
END DESCRIPTION:
XS GIS Cut Line= 4
      1340800.85      6995355.05      1342130.00      6994913.00
      1342380.00      6994713.00      1342316.45      6994261.24
#Sta/Elev= 30
  3457.6 2070.40  3609.5 2071.06  3725.4 2068.32  3782.2 2070.09  3799.2 2067.54
  3840.2 2066.52  3908.8 2066.23  3946.8 2067.75  3988.9 2065.54  4136.4 2064.75
  4178.6 2065.80  4220.0 2063.94  4346.6 2063.70  4389.4 2064.92  4431.5 2062.72
  4870.7 2062.01  4871.0 2061.51  4874.7 2062.01  5055.2 2062.38  5176.3 2062.47
  5234.0 2064.39  5326.0 2063.50  5375.4 2066.48  5425.9 2064.97  5468.5 2066.06
  5486.5 2068.09  5516.8 2066.68  5587.5 2067.54  5617.8 2069.47  5634.7 2068.42
#Mann=5,-1,0
  3457.6   0.045       0  4870.7   0.045       0  4874.7   0.045       0
  5055.2   0.035       0  5176.3   0.045       0
Bank Sta=4870.7,4874.7
Exp/Cntr=0.3,0.1

Type RM Length L Ch R = 1,1634,93,93,93
BEGIN DESCRIPTION:
Hackberry Creek Trib 03 2.0
END DESCRIPTION:
XS GIS Cut Line= 4
      1340799.98      6995393.31      1342314.99      6995170.59
      1342453.88      6994541.25      1342279.99      6994062.96
#Sta/Elev= 30
  3214.8 2069.84  3290.7 2070.97  3425.1 2068.14  3462.5 2070.02  3489.8 2067.59
  3553.4 2066.24  3604.0 2067.47  3735.4 2064.61  3806.1 2065.93  3887.0 2063.29
  3998.2 2064.72  4068.9 2062.28  4252.1 2063.08  4311.5 2060.92  4531.8 2060.74
  4532.1 2060.24  4535.8 2060.74  4703.2 2061.12  5049.3 2062.13  5212.2 2062.73
  5301.7 2064.31  5400.6 2063.36  5461.8 2066.28  5511.1 2064.90  5563.8 2068.05
  5628.1 2066.91  5681.3 2069.50  5787.7 2068.93  5819.7 2071.03  5899.5 2069.79
#Mann=7,-1,0
  3214.8   0.045       0  4531.8   0.035       0  4535.8   0.045       0
  4703.2   0.035       0  5049.3   0.045       0  5212.2   0.035       0
  5563.8   0.045       0
Bank Sta=4531.8,4535.8
Exp/Cntr=0.3,0.1

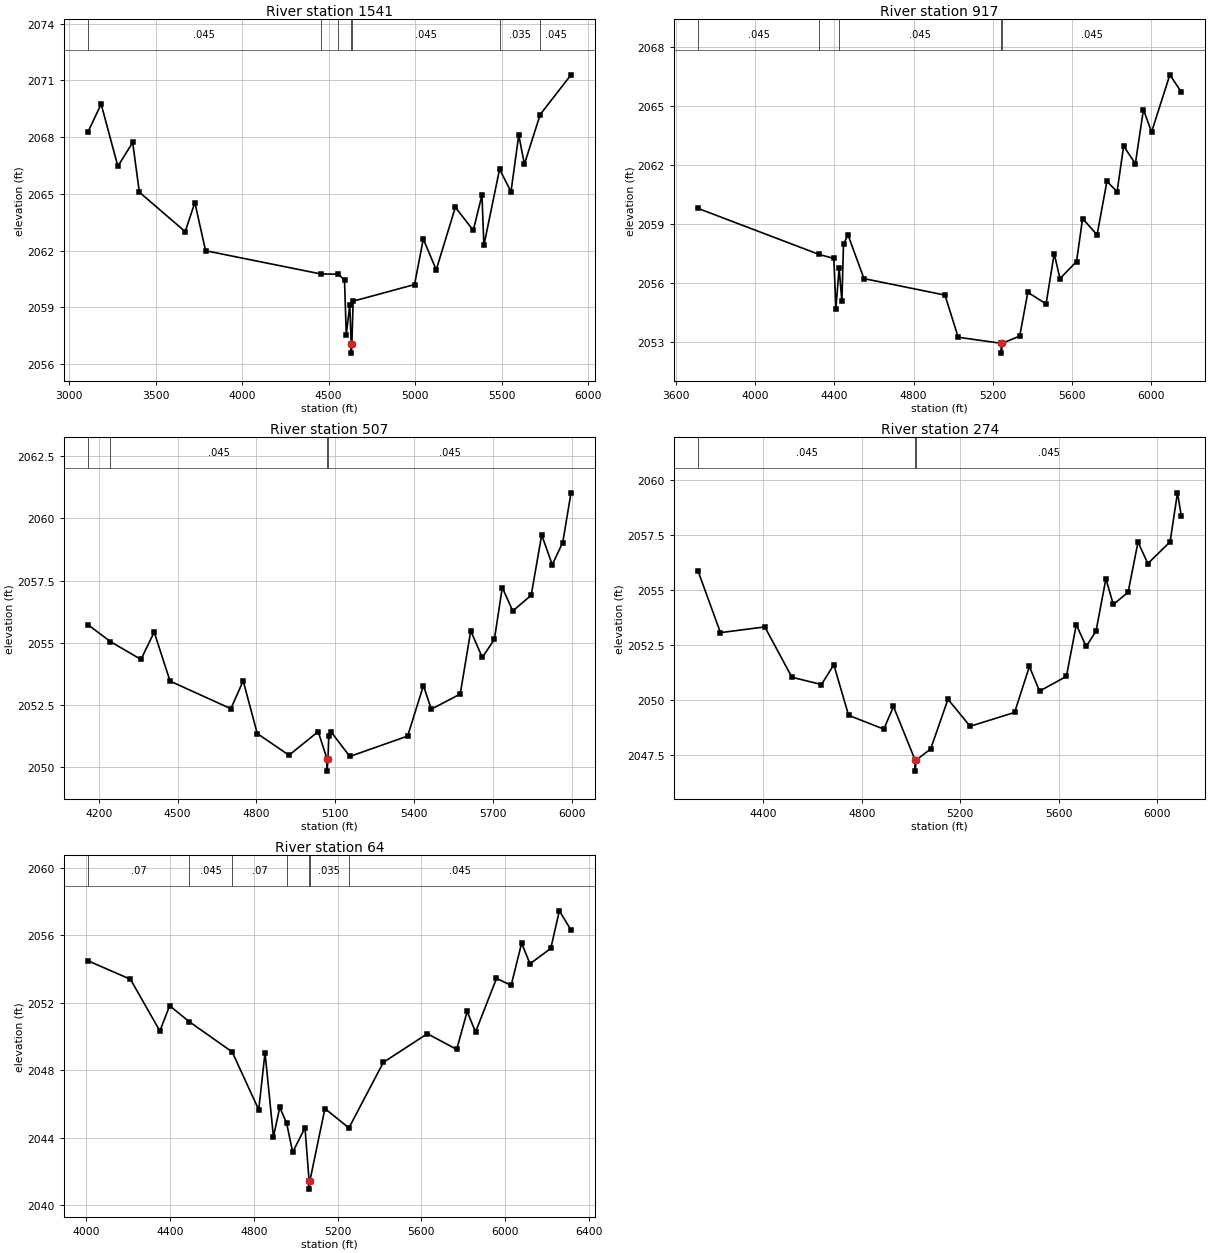
Type RM Length L Ch R = 1,1541,624,624,624
BEGIN DESCRIPTION:
Hackberry Creek Trib 03 1.5
END DESCRIPTION:
XS GIS Cut Line= 4
      1340838.96      6995510.43      1342358.39      6995268.25
      1342527.66      6994569.46      1342371.25      6994055.86
#Sta/Elev= 30
  3107.3 2068.26  3184.3 2069.75  3281.0 2066.46  3366.6 2067.72  3405.3 2065.09
  3670.4 2063.00  3726.2 2064.54  3788.3 2061.99  4455.1 2060.76  4555.9 2060.75
  4591.8 2060.43  4602.0 2057.54  4622.2 2059.14  4630.4 2057.07  4630.6 2056.57
  4634.4 2057.07  4641.7 2059.32  4996.8 2060.20  5047.4 2062.61  5122.3 2060.98
  5232.7 2064.29  5336.5 2063.07  5386.7 2064.94  5397.8 2062.27  5488.6 2066.31
  5554.6 2065.11  5599.4 2068.11  5632.2 2066.57  5723.6 2069.20  5901.8 2071.30
#Mann=7,-1,0
  3107.3   0.045       0  4455.1   0.035       0  4555.9   0.045       0
  4630.4   0.045       0  4634.4   0.045       0  5488.6   0.035       0
  5723.6   0.045       0
Bank Sta=4630.4,4634.4
Exp/Cntr=0.3,0.1

Type RM Length L Ch R = 1,917,410,410,410
BEGIN DESCRIPTION:
Hackberry Creek Trib 03 1.0
END DESCRIPTION:
XS GIS Cut Line= 5
      1341558.17      6995686.82      1342580.00      6995513.00
      1342805.00      6995388.00      1343008.85      6995204.50
      1342814.72      6994351.69
#Sta/Elev= 30
  3710.7 2059.79  4322.9 2057.44  4397.3 2057.24  4407.4 2054.67  4423.9 2056.75
  4437.8 2055.05  4446.0 2057.95  4468.3 2058.45  4549.4 2056.21  4958.8 2055.37
  5025.9 2053.22  5243.6 2052.91  5243.9 2052.41  5247.6 2052.91  5336.8 2053.28
  5377.8 2055.51  5470.1 2054.92  5511.2 2057.48  5540.4 2056.21  5624.0 2057.08
  5654.8 2059.27  5727.9 2058.44  5777.8 2061.17  5829.1 2060.64  5862.2 2062.97
  5921.4 2062.07  5962.4 2064.83  6003.4 2063.68  6095.8 2066.60  6153.5 2065.73
#Mann=5,-1,0
  3710.7   0.045       0  4322.9   0.035       0  4423.9   0.045       0
  5243.6   0.045       0  5247.6   0.045       0
Bank Sta=5243.6,5247.6
Exp/Cntr=0.3,0.1

Type RM Length L Ch R = 1,507,233,233,233
BEGIN DESCRIPTION:
Hackberry Creek Trib 03 0.9
END DESCRIPTION:
XS GIS Cut Line= 4
      1342264.02      6995799.73      1343030.00      6995713.00
      1343130.00      6995613.00      1343098.48      6994686.44
#Sta/Elev= 30
  4158.4 2055.73  4244.4 2055.05  4360.7 2054.33  4411.0 2055.43  4471.4 2053.46
  4702.8 2052.35  4749.8 2053.47  4803.5 2051.35  4924.2 2050.48  5035.3 2051.43
  5068.7 2050.34  5068.9 2049.84  5072.7 2050.34  5075.7 2051.27  5085.7 2051.40
  5155.7 2050.43  5375.9 2051.25  5435.9 2053.28  5465.9 2052.33  5576.0 2052.94
  5616.0 2055.48  5660.0 2054.41  5706.1 2055.14  5736.1 2057.22  5776.1 2056.28
  5846.1 2056.91  5886.2 2059.34  5926.2 2058.14  5966.2 2059.03  5997.8 2061.03
#Mann=4,-1,0
  4158.4    0.07       0  4244.4   0.045       0  5068.7   0.045       0
  5072.7   0.045       0
Bank Sta=5068.7,5072.7
Exp/Cntr=0.3,0.1

Type RM Length L Ch R = 1,274,210,210,210
BEGIN DESCRIPTION:
Hackberry Creek Trib 03 0.8
END DESCRIPTION:
XS GIS Cut Line= 4
      1342404.12      6995881.40      1343130.00      6995863.00
      1343280.00      6995788.83      1343345.53      6994722.69
#Sta/Elev= 30
  4135.2 2055.86  4226.1 2053.06  4406.2 2053.32  4516.2 2051.03  4636.2 2050.70
  4686.3 2051.60  4746.3 2049.30  4889.3 2048.67  4928.6 2049.70  5016.4 2047.26
  5016.6 2046.76  5020.4 2047.26  5079.6 2047.77  5149.7 2050.03  5239.9 2048.80
  5420.2 2049.43  5480.3 2051.52  5521.5 2050.40  5630.6 2051.07  5670.7 2053.42
  5710.8 2052.43  5750.8 2053.13  5790.9 2055.51  5821.0 2054.34  5881.1 2054.90
  5921.2 2057.18  5961.2 2056.20  6051.4 2057.19  6081.5 2059.42  6096.8 2058.38
#Mann=3,-1,0
  4135.2   0.045       0  5016.4   0.045       0  5020.4   0.045       0
Bank Sta=5016.4,5020.4
Exp/Cntr=0.3,0.1

Type RM Length L Ch R = 1,64,0,0,0
BEGIN DESCRIPTION:
Hackberry Creek Trib 03 0.6
END DESCRIPTION:
XS GIS Cut Line= 4
      1342362.43      6995917.86      1343299.92      6996002.24
      1343482.56      6995896.68      1343468.91      6994742.19
#Sta/Elev= 30
  4007.6 2054.50  4211.0 2053.40  4351.6 2050.33  4398.2 2051.83  4491.2 2050.89
  4696.7 2049.09  4823.5 2045.66  4853.6 2049.05  4893.7 2044.05  4923.9 2045.80
  4956.8 2044.86  4985.5 2043.14  5044.3 2044.59  5063.9 2041.45  5064.1 2040.95
  5067.9 2041.45  5139.5 2045.73  5254.0 2044.58  5418.5 2048.47  5628.5 2050.17
  5768.5 2049.24  5818.6 2051.49  5858.6 2050.27  5958.6 2053.45  6028.6 2053.04
  6078.6 2055.54  6118.6 2054.32  6217.8 2055.23  6258.6 2057.46  6314.4 2056.32
#Mann=7,-1,0
  4007.6    0.07       0  4491.2   0.045       0  4696.7    0.07       0
  4956.8   0.035       0  5063.9   0.035       0  5067.9   0.035       0
  5254.0   0.045       0
Bank Sta=5063.9,5067.9
Exp/Cntr=0.3,0.1

Chan Stop Cuts=-1