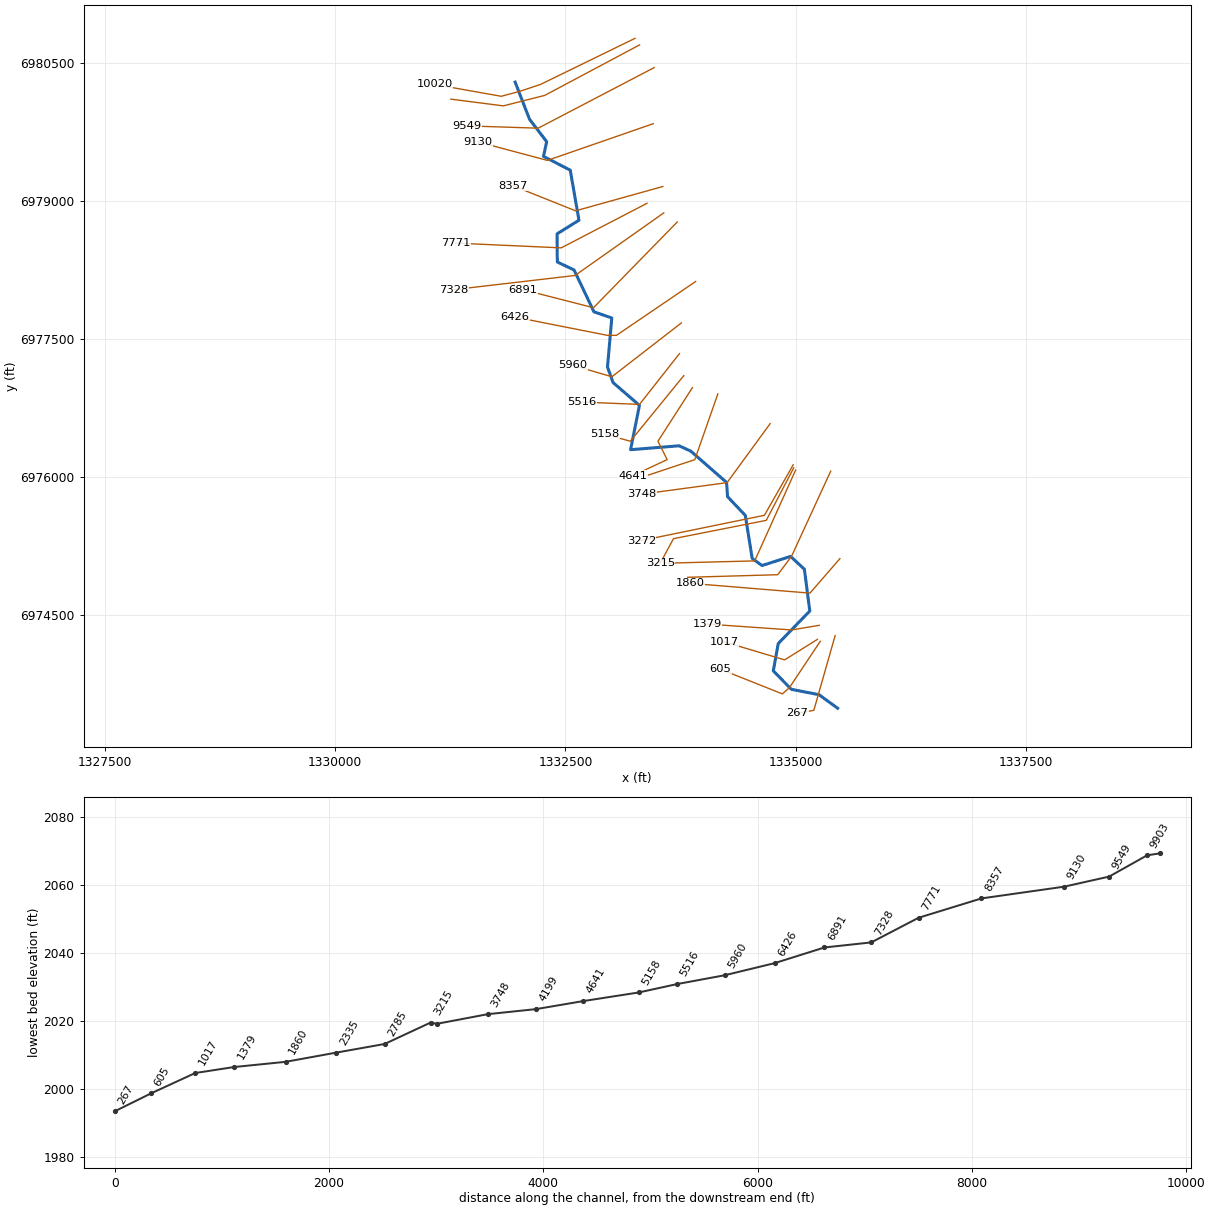
--- Spring Creek Trib 01.prj (project) ---

Proj Title=Spring Creek Trib 01 Base Level Engineering
Current Plan=p01
Default Exp/Contr=0.3,0.1
English Units
Geom File=g01
Flow File=f01
Plan File=p01
BEGIN DESCRIPTION:
Spring Creek Trib 01
END DESCRIPTION:

--- Spring Creek Trib 01.p01 (plan) ---

Plan Title=Multiple Run
Short Identifier=Multiple
Geom File=g01
Flow File=f01
Subcritical Flow
K Sum by GR= 0
Std Step Tol= 0.01
Critical Tol= 0.01
Num of Std Step Trials= 20
Max Error Tol= 0.3
Flow Tol Ratio= 0.001
Split Flow NTrial= 30
Split Flow Tol= 0.02
Split Flow Ratio= 0.02
Log Output Level= 0
Friction Slope Method= 1
Unsteady Friction Slope Method= 2
Unsteady Bridges Friction Slope Method= 1
Parabolic Critical Depth
Global Vel Dist=  1 , 1 , 1
Global Log Level= 0
CheckData=True
Encroach Param= -1, 0, 0, 0
BEGIN DESCRIPTION:
Multiple Run
END DESCRIPTION:

--- Spring Creek Trib 01.f01 (steady flow) ---

Flow Title=Multiple
Number of Profiles=7
Profile Names=10-year,25-year,50-year,1pct_min,100-year,1pct_plu,500-year
River Rch & RM= Spring Creek Tri,Reach-1,10020
     348     497     623     388     773    1543    1209
Boundary for River Rch & Prof#=Spring Creek Tri,Reach-1,1
Up Type=0
Dn Type=3
Dn Slope=0.005
Boundary for River Rch & Prof#=Spring Creek Tri,Reach-1,2
Up Type=0
Dn Type=3
Dn Slope=0.005
Boundary for River Rch & Prof#=Spring Creek Tri,Reach-1,3
Up Type=0
Dn Type=3
Dn Slope=0.005
Boundary for River Rch & Prof#=Spring Creek Tri,Reach-1,4
Up Type=0
Dn Type=3
Dn Slope=0.005
Boundary for River Rch & Prof#=Spring Creek Tri,Reach-1,5
Up Type=0
Dn Type=3
Dn Slope=0.005
Boundary for River Rch & Prof#=Spring Creek Tri,Reach-1,6
Up Type=0
Dn Type=3
Dn Slope=0.005
Boundary for River Rch & Prof#=Spring Creek Tri,Reach-1,7
Up Type=0
Dn Type=3
Dn Slope=0.005

--- Spring Creek Trib 01.g01 (geometry) ---

Geom Title=Existing Conditions

River Reach=Spring Creek Tri,Reach-1
Reach XY= 30
      1331955.00      6980288.00      1332110.52      6979885.57
      1332296.96      6979641.32      1332262.62      6979481.50
      1332552.95      6979332.16      1332647.66      6978787.90
      1332409.97      6978640.58      1332412.68      6978334.30
      1332594.37      6978248.05      1332810.25      6977793.44
      1333003.61      6977726.42      1332957.26      6977193.94
      1333018.26      6977024.35      1333303.95      6976777.57
      1333207.81      6976295.95      1333734.83      6976338.30
      1333861.34      6976279.98      1334249.53      6975940.45
      1334260.47      6975785.55      1334452.94      6975582.15
      1334527.86      6975114.42      1334634.79      6975037.63
      1334944.56      6975136.96      1335094.24      6974997.68
      1335152.94      6974543.85      1334810.47      6974190.45
      1334756.96      6973893.89      1334952.57      6973693.52
      1335253.53      6973634.46      1335455.00      6973488.00

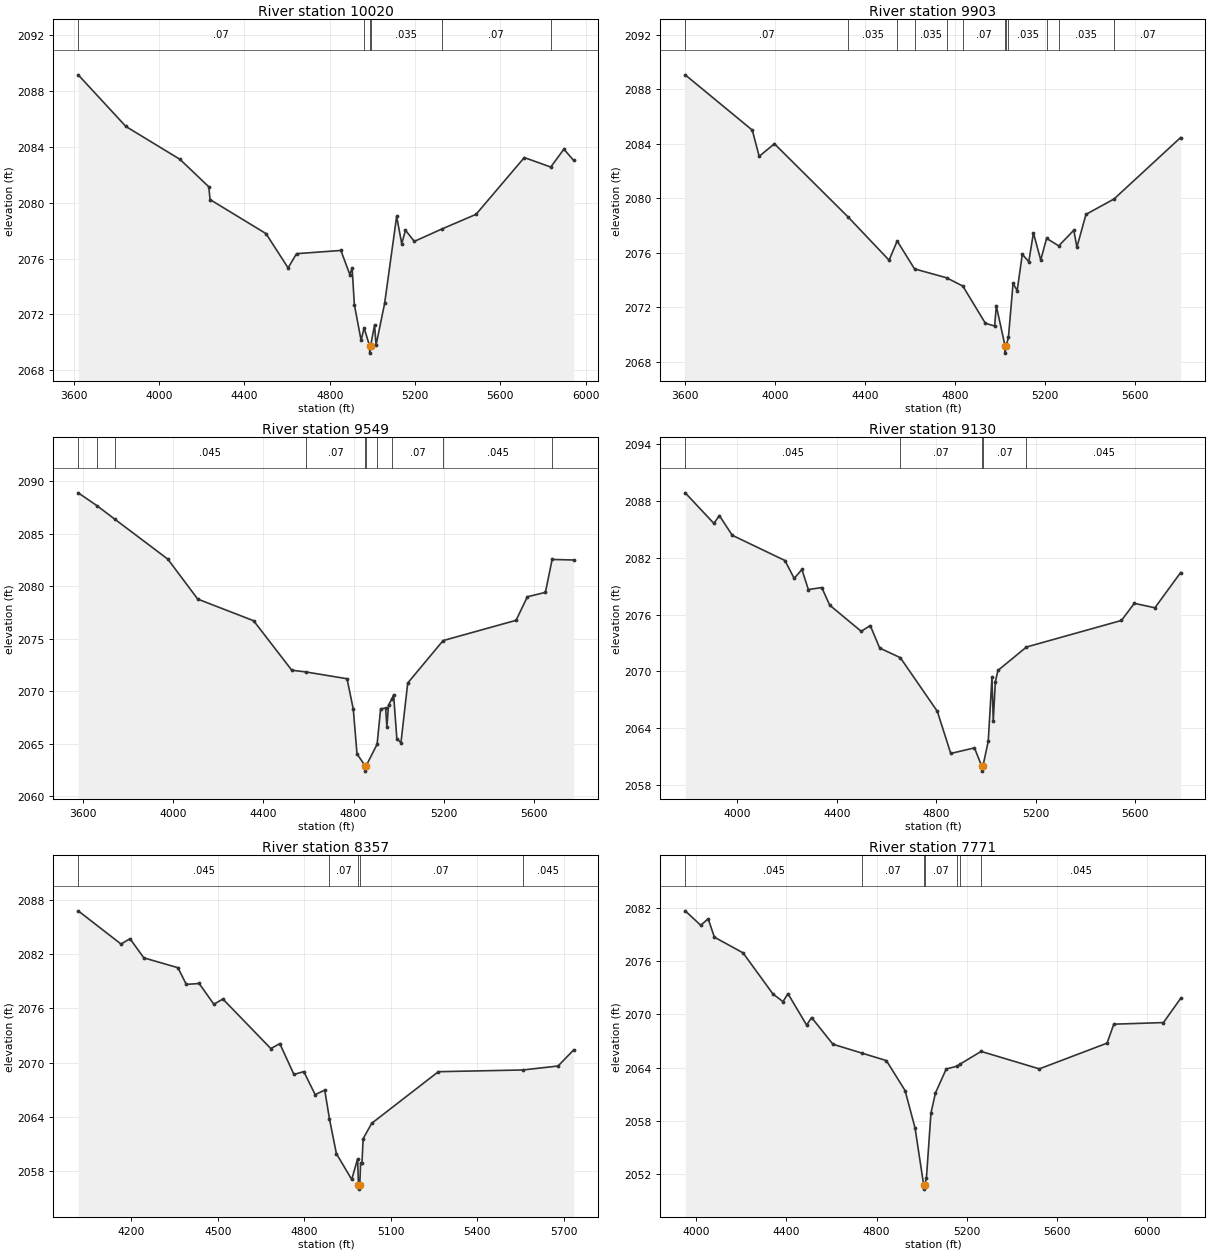
Type RM Length L Ch R = 1,10020,117,117,117
BEGIN DESCRIPTION:
Spring Creek Trib 01 20.0
END DESCRIPTION:
XS GIS Cut Line= 5
      1333255.85      6980763.80      1332230.00      6980263.00
      1332005.00      6980188.00      1331803.95      6980134.41
      1331079.99      6980263.00
#Sta/Elev= 30
  3621.2 2089.17  3844.7 2085.47  4098.4 2083.11  4233.6 2081.14  4239.1 2080.23
  4501.3 2077.79  4605.1 2075.33  4644.6 2076.35  4852.4 2076.58  4894.5 2074.85
  4905.1 2075.34  4915.6 2072.70  4947.2 2070.14  4961.4 2071.03  4987.3 2069.72
  4987.5 2069.22  4991.5 2069.72  5010.3 2071.24  5017.4 2069.80  5057.5 2072.79
  5113.8 2079.02  5137.7 2077.06  5155.2 2078.03  5196.6 2077.23  5324.4 2078.11
  5486.0 2079.17  5712.1 2083.24  5836.1 2082.56  5897.6 2083.84  5943.3 2083.04
#Mann=6,-1,0
  3621.2    0.07       0  4961.4   0.035       0  4987.3   0.035       0
  4991.5   0.035       0  5324.4    0.07       0  5836.1   0.045       0
Bank Sta=4987.3,4991.5
Exp/Cntr=0.3,0.1

Type RM Length L Ch R = 1,9903,354,354,354
BEGIN DESCRIPTION:
Spring Creek Trib 01 19.5
END DESCRIPTION:
XS GIS Cut Line= 4
      1333305.31      6980692.33      1332276.22      6980143.93
      1331826.41      6980030.24      1331257.23      6980103.31
#Sta/Elev= 30
  3601.1 2089.07  3899.6 2085.01  3930.1 2083.09  3998.0 2084.01  4324.5 2078.66
  4508.0 2075.47  4544.1 2076.88  4621.2 2074.83  4763.6 2074.18  4836.1 2073.57
  4936.4 2070.84  4977.5 2070.64  4985.1 2072.11  5024.2 2069.15  5024.5 2068.65
  5028.4 2069.15  5038.9 2069.80  5059.5 2073.77  5077.9 2073.24  5100.6 2075.90
  5129.5 2075.36  5150.1 2077.47  5182.6 2075.48  5208.7 2077.07  5262.8 2076.52
  5329.8 2077.67  5343.5 2076.42  5383.8 2078.83  5508.7 2079.96  5805.0 2084.47
#Mann=12,-1,0
  3601.1    0.07       0  4324.5   0.035       0  4544.1    0.07       0
  4621.2   0.035       0  4763.6    0.16       0  4836.1    0.07       0
  5024.2    0.07       0  5028.4    0.07       0  5038.9   0.035       0
  5208.7   0.045       0  5262.8   0.035       0  5508.7    0.07       0
Bank Sta=5024.2,5028.4
Exp/Cntr=0.3,0.1

Type RM Length L Ch R = 1,9549,419,419,419
BEGIN DESCRIPTION:
Spring Creek Trib 01 19.0
END DESCRIPTION:
XS GIS Cut Line= 3
      1333464.13      6980446.07      1332205.00      6979788.00
      1331430.03      6979813.00
#Sta/Elev= 30
  3579.5 2088.88  3663.3 2087.65  3743.1 2086.35  3976.9 2082.57  4109.4 2078.77
  4357.1 2076.71  4526.3 2072.00  4588.2 2071.84  4771.2 2071.19  4798.9 2068.30
  4815.4 2064.04  4851.4 2062.90  4851.7 2062.40  4855.7 2062.90  4904.5 2064.96
  4920.1 2068.32  4942.2 2068.41  4947.9 2066.62  4955.1 2068.68  4969.1 2069.25
  4977.7 2069.65  4992.0 2065.50  5010.2 2065.10  5040.2 2070.78  5196.9 2074.82
  5520.5 2076.75  5570.5 2078.99  5650.6 2079.41  5680.3 2082.54  5775.6 2082.49
#Mann=10,-1,0
  3579.5   0.045       0  3663.3   0.035       0  3743.1   0.045       0
  4588.2    0.07       0  4851.4    0.07       0  4855.7    0.07       0
  4904.5    0.16       0  4969.1    0.07       0  5196.9   0.045       0
  5680.3    0.07       0
Bank Sta=4851.4,4855.7
Exp/Cntr=0.3,0.1

Type RM Length L Ch R = 1,9130,773,773,773
BEGIN DESCRIPTION:
Spring Creek Trib 01 18.0
END DESCRIPTION:
XS GIS Cut Line= 3
      1333453.79      6979836.72      1332305.00      6979438.00
      1331555.03      6979637.99
#Sta/Elev= 30
  3790.0 2088.88  3905.2 2085.65  3927.5 2086.47  3979.2 2084.39  4191.0 2081.72
  4228.2 2079.83  4259.3 2080.77  4285.1 2078.65  4339.2 2078.86  4370.9 2077.00
  4497.7 2074.23  4534.1 2074.84  4572.0 2072.46  4655.1 2071.44  4803.7 2065.77
  4857.8 2061.31  4953.1 2061.90  4982.7 2059.94  4983.0 2059.44  4987.0 2059.94
  5008.6 2062.62  5023.5 2069.36  5028.7 2064.72  5037.1 2068.88  5047.4 2070.09
  5162.3 2072.57  5544.2 2075.38  5595.9 2077.19  5678.7 2076.72  5782.2 2080.45
#Mann=5,-1,0
  3790.0   0.045       0  4655.1    0.07       0  4982.7    0.07       0
  4987.0    0.07       0  5162.3   0.045       0
Bank Sta=4982.7,4987
Exp/Cntr=0.3,0.1

Type RM Length L Ch R = 1,8357,586,586,586
BEGIN DESCRIPTION:
Spring Creek Trib 01 17.0
END DESCRIPTION:
XS GIS Cut Line= 3
      1333557.94      6979154.42      1332610.67      6978890.28
      1331929.98      6979163.01
#Sta/Elev= 30
  4016.6 2086.81  4165.0 2083.13  4196.1 2083.72  4244.1 2081.60  4362.2 2080.51
  4391.2 2078.66  4435.8 2078.76  4486.8 2076.46  4518.0 2077.04  4684.1 2071.55
  4715.2 2072.10  4764.2 2068.68  4798.3 2069.00  4837.8 2066.45  4870.9 2066.95
  4887.4 2063.74  4911.3 2059.91  4964.4 2057.05  4984.9 2059.34  4987.8 2056.48
  4988.1 2055.98  4992.4 2056.48  4995.2 2058.90  5000.0 2058.90  5004.0 2061.57
  5033.6 2063.27  5264.7 2068.99  5557.0 2069.18  5679.5 2069.62  5733.3 2071.40
#Mann=5,-1,0
  4016.6   0.045       0  4887.4    0.07       0  4987.8    0.07       0
  4992.4    0.07       0  5557.0   0.045       0
Bank Sta=4987.8,4992.4
Exp/Cntr=0.3,0.1

Type RM Length L Ch R = 1,7771,443,443,443
BEGIN DESCRIPTION:
Spring Creek Trib 01 16.0
END DESCRIPTION:
XS GIS Cut Line= 3
      1333386.09      6978972.15      1332455.00      6978488.00
      1331309.01      6978539.78
#Sta/Elev= 30
  3951.1 2081.68  4020.0 2080.05  4052.9 2080.78  4080.6 2078.71  4207.6 2076.94
  4340.3 2072.30  4384.5 2071.44  4406.6 2072.34  4489.4 2068.80  4511.5 2069.65
  4606.0 2066.64  4736.7 2065.62  4843.2 2064.79  4926.0 2061.41  4970.2 2057.19
  5008.2 2050.80  5008.5 2050.30  5012.9 2050.80  5020.6 2051.54  5040.6 2058.87
  5060.6 2061.14  5108.5 2063.85  5156.1 2064.16  5167.4 2064.36  5263.0 2065.83
  5521.1 2063.86  5821.4 2066.76  5851.4 2068.90  6071.6 2069.08  6147.7 2071.81
#Mann=7,-1,0
  3951.1   0.045       0  4736.7    0.07       0  5008.2    0.07       0
  5012.9    0.07       0  5156.1   0.045       0  5167.4    0.07       0
  5263.0   0.045       0
Bank Sta=5008.2,5012.9
Exp/Cntr=0.3,0.1

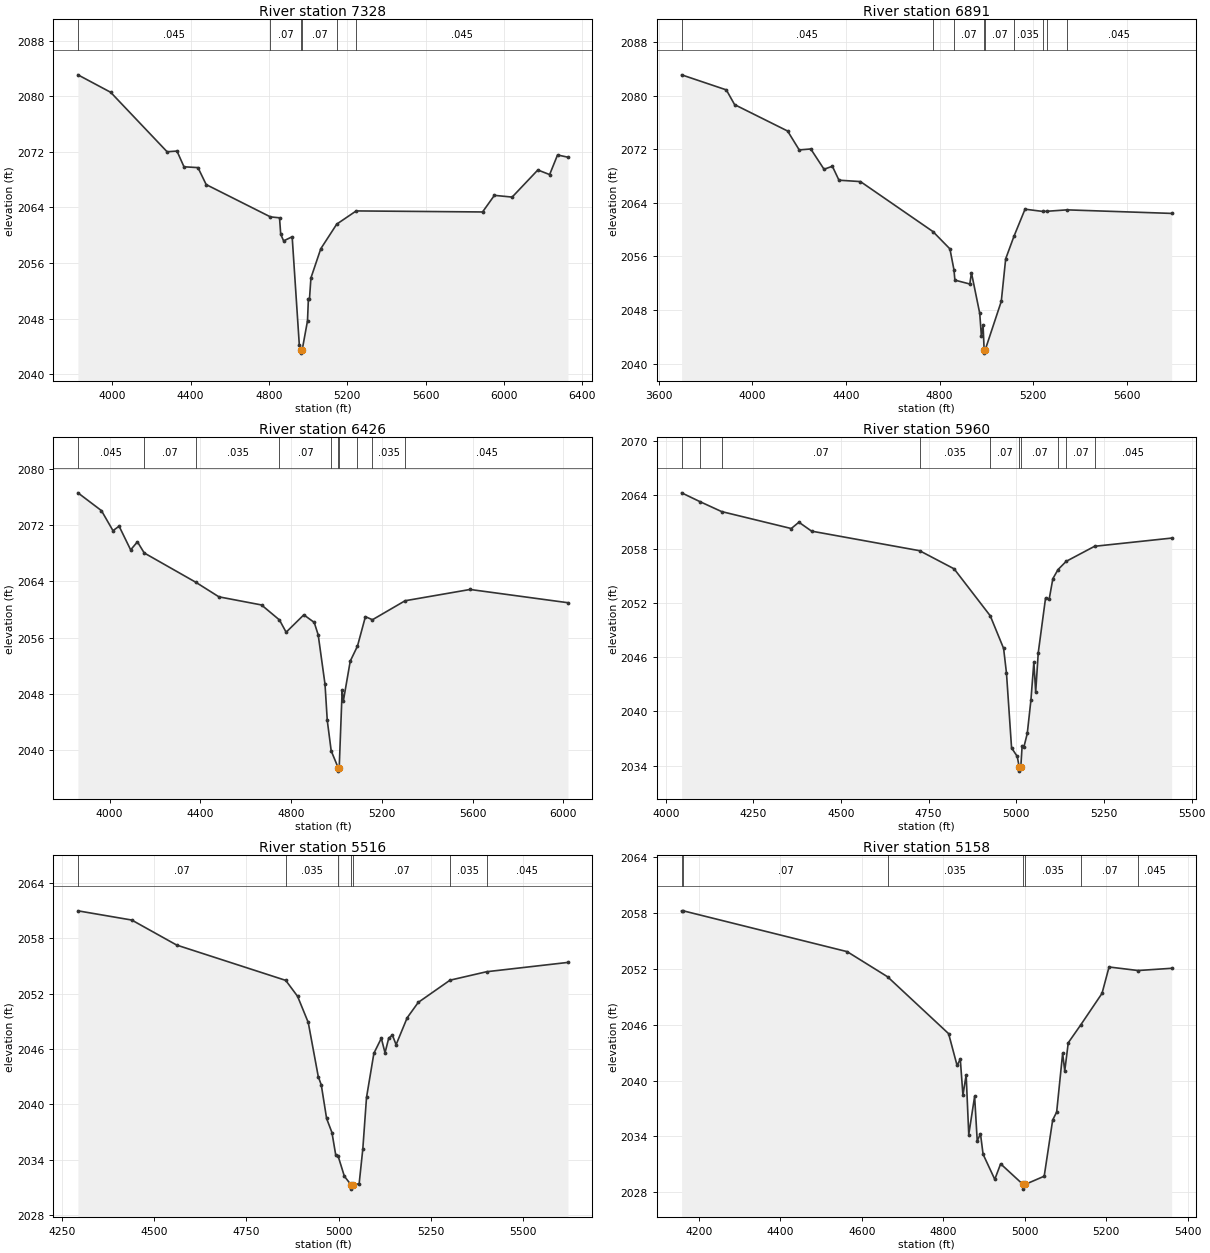
Type RM Length L Ch R = 1,7328,437,437,437
BEGIN DESCRIPTION:
Spring Creek Trib 01 15.0
END DESCRIPTION:
XS GIS Cut Line= 3
      1333568.33      6978867.95      1332605.00      6978188.00
      1331292.26      6978034.62
#Sta/Elev= 30
  3825.4 2083.08  3992.4 2080.57  4280.6 2072.01  4331.0 2072.11  4366.7 2069.85
  4438.1 2069.73  4480.0 2067.29  4808.0 2062.64  4854.3 2062.51  4860.4 2060.14
  4875.2 2059.19  4918.8 2059.78  4955.3 2044.21  4965.5 2043.54  4965.8 2043.04
  4970.2 2043.54  4997.1 2047.69  5001.5 2050.77  5007.0 2050.77  5014.6 2053.86
  5064.9 2058.06  5146.3 2061.60  5245.7 2063.50  5890.5 2063.35  5950.9 2065.74
  6041.5 2065.49  6172.6 2069.39  6232.8 2068.73  6273.1 2071.55  6326.2 2071.23
#Mann=6,-1,0
  3825.4   0.045       0  4808.0    0.07       0  4965.5    0.07       0
  4970.2    0.07       0  5146.3   0.035       0  5245.7   0.045       0
Bank Sta=4965.5,4970.2
Exp/Cntr=0.3,0.1

Type RM Length L Ch R = 1,6891,465,465,465
BEGIN DESCRIPTION:
Spring Creek Trib 01 14.0
END DESCRIPTION:
XS GIS Cut Line= 3
      1333714.13      6978768.97      1332805.00      6977838.00
      1332038.57      6978034.25
#Sta/Elev= 30
  3698.6 2083.10  3889.6 2080.85  3924.9 2078.65  4151.2 2074.71  4200.8 2071.89
  4250.2 2072.03  4306.8 2069.00  4342.3 2069.45  4370.5 2067.37  4462.4 2067.16
  4771.8 2059.70  4844.3 2057.11  4861.6 2053.98  4865.5 2052.45  4929.2 2051.87
  4936.2 2053.55  4971.6 2047.49  4978.6 2044.12  4985.8 2045.73  4990.4 2042.05
  4990.8 2041.55  4995.1 2042.05  5063.6 2049.28  5082.4 2055.63  5117.5 2058.97
  5165.0 2063.04  5239.9 2062.71  5259.1 2062.73  5344.3 2062.94  5791.0 2062.41
#Mann=9,-1,0
  3698.6   0.045       0  4771.8   0.035       0  4861.6    0.07       0
  4990.4    0.07       0  4995.1    0.07       0  5117.5   0.035       0
  5239.9   0.045       0  5259.1   0.035       0  5344.3   0.045       0
Bank Sta=4990.4,4995.1
Exp/Cntr=0.3,0.1

Type RM Length L Ch R = 1,6426,466,466,466
BEGIN DESCRIPTION:
Spring Creek Trib 01 13.0
END DESCRIPTION:
XS GIS Cut Line= 4
      1333913.82      6978122.59      1333055.00      6977538.00
      1332955.00      6977538.00      1331953.80      6977736.01
#Sta/Elev= 30
  3860.7 2076.65  3964.4 2074.11  4015.2 2071.25  4042.2 2071.89  4093.1 2068.51
  4123.0 2069.66  4152.9 2068.07  4380.1 2063.89  4482.1 2061.81  4669.8 2060.65
  4748.9 2058.51  4778.3 2056.76  4856.2 2059.24  4902.1 2058.16  4919.6 2056.38
  4949.6 2049.35  4959.6 2044.17  4976.9 2039.83  5007.4 2037.44  5007.7 2036.94
  5012.2 2037.44  5025.2 2048.48  5030.3 2046.92  5060.8 2052.63  5092.7 2054.78
  5127.7 2058.98  5158.7 2058.54  5302.5 2061.25  5589.0 2062.86  6020.2 2060.97
#Mann=10,-1,0
  3860.7   0.045       0  4152.9    0.07       0  4380.1   0.035       0
  4748.9    0.07       0  4976.9   0.035       0  5007.4   0.035       0
  5012.2   0.035       0  5092.7    0.07       0  5158.7   0.035       0
  5302.5   0.045       0
Bank Sta=5007.4,5012.2
Exp/Cntr=0.3,0.1

Type RM Length L Ch R = 1,5960,444,444,444
BEGIN DESCRIPTION:
Spring Creek Trib 01 12.0
END DESCRIPTION:
XS GIS Cut Line= 3
      1333759.32      6977672.94      1333005.00      6977088.00
      1332580.04      6977212.99
#Sta/Elev= 30
  4045.4 2064.25  4097.3 2063.28  4159.5 2062.17  4358.1 2060.29  4379.9 2060.99
  4416.1 2060.00  4724.1 2057.83  4822.5 2055.82  4925.6 2050.61  4963.7 2046.99
  4971.9 2044.25  4986.4 2035.96  5002.6 2035.01  5008.0 2033.88  5008.3 2033.38
  5012.8 2033.88  5016.6 2036.21  5021.8 2036.09  5031.2 2037.56  5041.6 2041.25
  5050.0 2045.48  5055.2 2042.15  5062.5 2046.51  5083.3 2052.57  5093.8 2052.48
  5104.2 2054.73  5119.0 2055.74  5142.2 2056.65  5223.2 2058.32  5442.9 2059.23
#Mann=10,-1,0
  4045.4    0.07       0  4097.3   0.035       0  4159.5    0.07       0
  4724.1   0.035       0  4925.6    0.07       0  5008.0    0.07       0
  5012.8    0.07       0  5119.0   0.035       0  5142.2    0.07       0
  5223.2   0.045       0
Bank Sta=5008,5012.8
Exp/Cntr=0.3,0.1

Type RM Length L Ch R = 1,5516,358,358,358
BEGIN DESCRIPTION:
Spring Creek Trib 01 11.0
END DESCRIPTION:
XS GIS Cut Line= 3
      1333738.48      6977339.61      1333305.00      6976788.00
      1332679.96      6976813.00
#Sta/Elev= 30
  4294.1 2061.00  4439.9 2060.00  4561.8 2057.28  4856.9 2053.45  4889.0 2051.72
  4917.9 2048.88  4945.1 2042.99  4953.2 2042.10  4967.6 2038.46  4982.1 2036.93
  4992.5 2034.45  4998.6 2034.40  5015.7 2032.19  5033.2 2031.29  5033.6 2030.79
  5038.1 2031.29  5055.7 2031.36  5065.7 2035.16  5075.7 2040.74  5095.7 2045.54
  5115.8 2047.17  5125.8 2045.59  5135.8 2047.17  5145.8 2047.51  5155.8 2046.47
  5185.8 2049.39  5215.8 2051.06  5301.8 2053.47  5401.0 2054.39  5621.2 2055.40
#Mann=7,-1,0
  4294.1    0.07       0  4856.9   0.035       0  4998.6    0.07       0
  5033.2    0.07       0  5038.1    0.07       0  5301.8   0.035       0
  5401.0   0.045       0
Bank Sta=5033.2,5038.1
Exp/Cntr=0.3,0.1

Type RM Length L Ch R = 1,5158,517,517,517
BEGIN DESCRIPTION:
Spring Creek Trib 01 10.0
END DESCRIPTION:
XS GIS Cut Line= 3
      1333785.37      6977100.04      1333205.00      6976388.00
      1332930.05      6976462.99
#Sta/Elev= 30
  4157.2 2058.25  4161.2 2058.25  4563.8 2053.86  4663.0 2051.16  4813.0 2045.04
  4833.8 2041.62  4841.7 2042.30  4848.2 2038.42  4856.1 2040.61  4862.5 2034.19
  4876.9 2038.29  4883.3 2033.51  4891.3 2034.27  4897.7 2032.07  4926.4 2029.37
  4940.8 2031.04  4995.8 2028.82  4996.2 2028.32  5000.7 2028.82  5047.8 2029.71
  5068.6 2035.75  5078.4 2036.61  5093.1 2042.92  5098.3 2041.04  5106.9 2044.06
  5137.5 2045.98  5189.8 2049.37  5207.1 2052.21  5278.4 2051.83  5360.8 2052.07
#Mann=7,-1,0
  4157.2   0.035       0  4161.2    0.07       0  4663.0   0.035       0
  4995.8   0.035       0  5000.7   0.035       0  5137.5    0.07       0
  5278.4   0.045       0
Bank Sta=4995.8,5000.7
Exp/Cntr=0.3,0.1

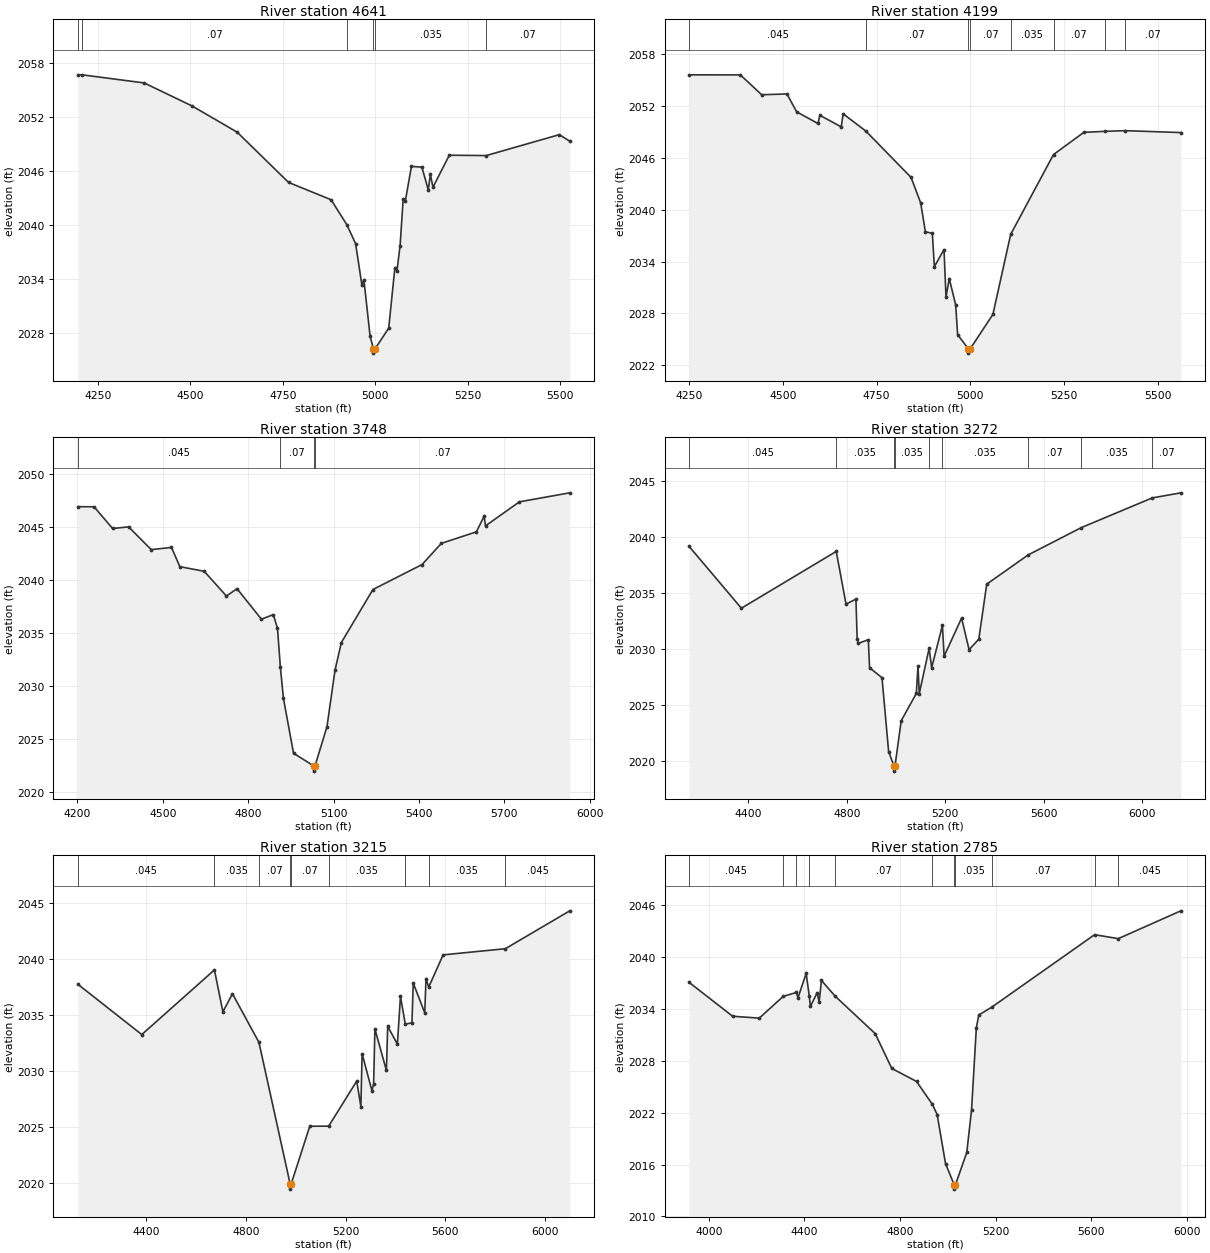
Type RM Length L Ch R = 1,4641,442,442,442
BEGIN DESCRIPTION:
Spring Creek Trib 01 9.0
END DESCRIPTION:
XS GIS Cut Line= 5
      1333879.09      6976969.81      1333505.00      6976388.00
      1333555.00      6976288.00      1333605.00      6976188.00
      1333230.02      6976013.01
#Sta/Elev= 30
  4196.4 2056.66  4207.6 2056.67  4375.3 2055.77  4505.4 2053.20  4626.5 2050.31
  4765.6 2044.73  4880.5 2042.81  4923.2 2040.03  4946.8 2037.93  4963.6 2033.38
  4969.2 2033.93  4985.9 2027.68  4994.7 2026.29  4995.0 2025.79  4999.6 2026.29
  5036.2 2028.56  5053.0 2035.29  5058.6 2034.93  5067.0 2037.72  5075.4 2042.92
  5081.0 2042.65  5097.7 2046.51  5125.9 2046.43  5143.2 2043.90  5148.8 2045.64
  5155.8 2044.20  5200.0 2047.75  5299.6 2047.71  5497.2 2050.03  5525.5 2049.31
#Mann=6,-1,0
  4196.4   0.035       0  4207.6    0.07       0  4923.2   0.035       0
  4994.7   0.035       0  4999.6   0.035       0  5299.6    0.07       0
Bank Sta=4994.7,4999.6
Exp/Cntr=0.3,0.1

Type RM Length L Ch R = 1,4199,451,451,451
BEGIN DESCRIPTION:
Spring Creek Trib 01 8.0
END DESCRIPTION:
XS GIS Cut Line= 3
      1334155.13      6976902.08      1333905.00      6976188.00
      1333380.02      6976013.01
#Sta/Elev= 30
  4250.6 2055.57  4387.2 2055.56  4444.0 2053.27  4511.3 2053.36  4537.0 2051.30
  4593.8 2049.95  4599.1 2050.89  4655.8 2049.56  4661.1 2051.06  4721.5 2049.07
  4841.9 2043.72  4867.6 2040.77  4880.1 2037.44  4898.7 2037.26  4904.0 2033.41
  4929.7 2035.39  4935.0 2029.88  4943.6 2032.04  4960.7 2029.01  4966.0 2025.55
  4994.5 2023.92  4994.9 2023.42  4999.5 2023.92  5059.9 2027.89  5107.3 2037.14
  5221.4 2046.36  5302.4 2048.93  5358.5 2049.04  5412.2 2049.12  5560.6 2048.90
#Mann=8,-1,0
  4250.6   0.045       0  4721.5    0.07       0  4994.5    0.07       0
  4999.5    0.07       0  5107.3   0.035       0  5221.4    0.07       0
  5358.5   0.035       0  5412.2    0.07       0
Bank Sta=4994.5,4999.5
Exp/Cntr=0.3,0.1

Type RM Length L Ch R = 1,3748,476,476,476
BEGIN DESCRIPTION:
Spring Creek Trib 01 7.0
END DESCRIPTION:
XS GIS Cut Line= 3
      1334722.87      6976579.22      1334255.00      6975938.00
      1333329.97      6975813.00
#Sta/Elev= 30
  4202.2 2046.93  4258.7 2046.92  4323.6 2044.87  4380.0 2045.02  4459.5 2042.87
  4530.6 2043.08  4559.9 2041.26  4645.7 2040.82  4723.6 2038.48  4760.8 2039.18
  4846.5 2036.29  4888.2 2036.73  4902.9 2035.43  4913.0 2031.76  4923.8 2028.80
  4959.3 2023.62  5029.8 2022.43  5030.1 2021.93  5034.8 2022.43  5076.7 2026.13
  5104.9 2031.46  5127.1 2034.08  5238.1 2039.10  5410.7 2041.46  5478.3 2043.46
  5601.4 2044.55  5628.7 2046.03  5633.7 2045.12  5752.8 2047.39  5929.4 2048.24
#Mann=4,-1,0
  4202.2   0.045       0  4913.0    0.07       0  5029.8    0.07       0
  5034.8    0.07       0
Bank Sta=5029.8,5034.8
Exp/Cntr=0.3,0.1

Type RM Length L Ch R = 1,3272,57,57,57
BEGIN DESCRIPTION:
Spring Creek Trib 01 6.0
END DESCRIPTION:
XS GIS Cut Line= 3
      1334972.87      6976131.31      1334660.29      6975583.29
      1333323.27      6975308.87
#Sta/Elev= 30
  4160.0 2039.15  4372.2 2033.63  4757.2 2038.70  4796.9 2034.00  4837.1 2034.44
  4842.2 2030.87  4847.3 2030.50  4887.4 2030.82  4892.5 2028.32  4942.9 2027.43
  4969.8 2020.84  4990.8 2019.59  4991.2 2019.09  4995.9 2019.59  5020.9 2023.59
  5082.1 2026.02  5089.0 2028.47  5094.1 2026.00  5134.3 2030.06  5144.5 2028.31
  5188.2 2032.10  5194.9 2029.34  5265.9 2032.75  5296.5 2029.93  5335.8 2030.87
  5368.0 2035.78  5536.3 2038.39  5751.3 2040.82  6038.9 2043.47  6155.8 2043.93
#Mann=9,-1,0
  4160.0   0.045       0  4757.2   0.035       0  4990.8   0.035       0
  4995.9   0.035       0  5134.3    0.07       0  5188.2   0.035       0
  5536.3    0.07       0  5751.3   0.035       0  6038.9    0.07       0
Bank Sta=4990.8,4995.9
Exp/Cntr=0.3,0.1

Type RM Length L Ch R = 1,3215,430,430,430
BEGIN DESCRIPTION:
Spring Creek Trib 01 6.1
END DESCRIPTION:
XS GIS Cut Line= 4
      1334978.79      6976099.16      1334680.65      6975528.48
      1333673.31      6975329.38      1333529.99      6975062.98
#Sta/Elev= 30
  4126.2 2037.74  4382.1 2033.26  4673.7 2039.03  4707.6 2035.29  4746.1 2036.90
  4852.2 2032.57  4977.1 2019.97  4977.5 2019.47  4982.2 2019.97  5056.2 2025.08
  5132.1 2025.09  5244.7 2029.11  5261.3 2026.84  5266.3 2031.55  5305.9 2028.23
  5312.5 2028.87  5317.6 2033.76  5363.8 2030.06  5368.9 2033.99  5407.8 2032.41
  5420.2 2036.67  5439.6 2034.19  5466.3 2034.31  5471.4 2037.86  5517.6 2035.20
  5522.7 2038.26  5533.6 2037.50  5591.3 2040.37  5841.1 2040.92  6099.4 2044.30
#Mann=9,-1,0
  4126.2   0.045       0  4673.7   0.035       0  4852.2    0.07       0
  4977.1    0.07       0  4982.2    0.07       0  5132.1   0.035       0
  5439.6    0.07       0  5533.6   0.035       0  5841.1   0.045       0
Bank Sta=4977.1,4982.2
Exp/Cntr=0.3,0.1

Type RM Length L Ch R = 1,2785,450,450,450
BEGIN DESCRIPTION:
Spring Creek Trib 01 5.0
END DESCRIPTION:
XS GIS Cut Line= 3
      1334998.90      6976073.99      1334555.00      6975088.00
      1333580.03      6975063.00
#Sta/Elev= 30
  3918.0 2037.09  4100.0 2033.17  4211.4 2032.95  4311.8 2035.47  4366.6 2035.92
  4373.4 2035.30  4407.5 2038.13  4420.5 2035.55  4425.2 2034.31  4453.8 2035.90
  4461.9 2034.80  4471.5 2037.32  4529.2 2035.48  4696.3 2031.16  4765.7 2027.13
  4869.3 2025.62  4935.8 2022.96  4955.4 2021.79  4990.5 2016.12  5026.7 2013.66
  5027.1 2013.16  5031.9 2013.66  5079.3 2017.40  5099.3 2022.32  5119.3 2031.80
  5129.4 2033.31  5183.7 2034.22  5614.0 2042.61  5713.0 2042.15  5974.6 2045.37
#Mann=11,-1,0
  3918.0   0.045       0  4311.8   0.035       0  4366.6   0.045       0
  4420.5   0.035       0  4529.2    0.07       0  4935.8   0.035       0
  5026.7   0.035       0  5031.9   0.035       0  5183.7    0.07       0
  5614.0   0.035       0  5713.0   0.045       0
Bank Sta=5026.7,5031.9
Exp/Cntr=0.3,0.1

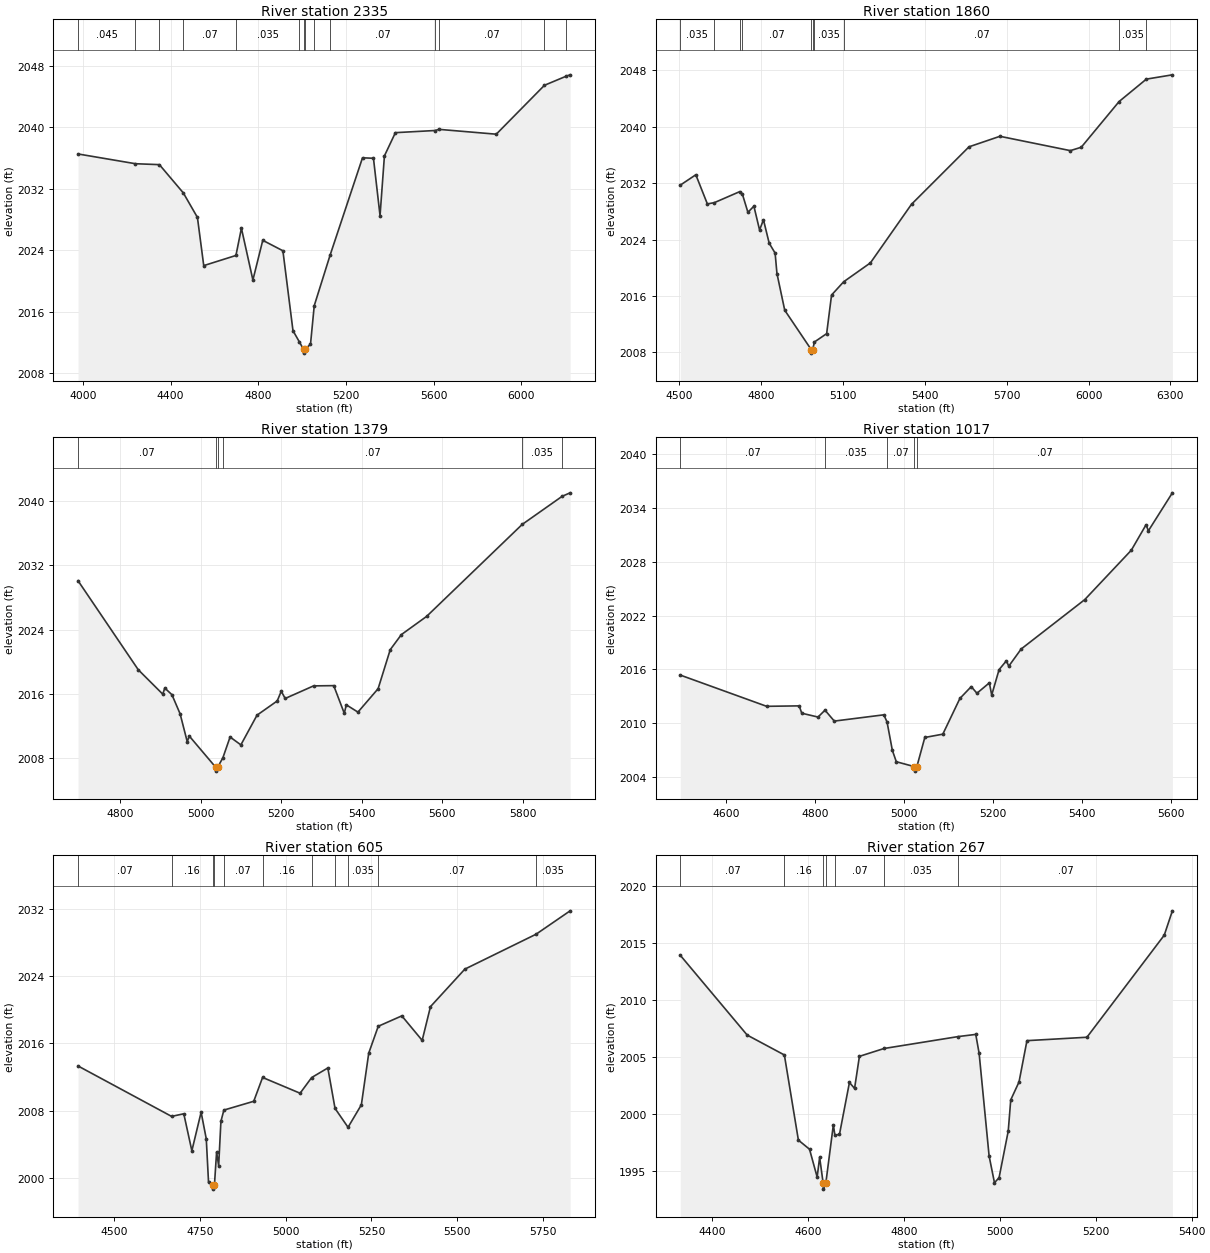
Type RM Length L Ch R = 1,2335,475,475,475
BEGIN DESCRIPTION:
Spring Creek Trib 01 4.0
END DESCRIPTION:
XS GIS Cut Line= 4
      1335380.01      6976063.02      1334955.00      6975138.00
      1334805.00      6974938.00      1333828.09      6974909.97
#Sta/Elev= 30
  3978.0 2036.53  4240.2 2035.26  4349.3 2035.14  4458.3 2031.47  4522.8 2028.28
  4551.6 2022.01  4698.5 2023.33  4723.5 2026.87  4775.9 2020.14  4820.9 2025.30
  4912.8 2023.94  4958.8 2013.55  4987.5 2012.11  5006.9 2011.13  5007.3 2010.63
  5012.1 2011.13  5038.7 2011.77  5055.8 2016.80  5128.6 2023.41  5276.0 2036.03
  5326.0 2035.97  5356.0 2028.51  5376.0 2036.28  5426.1 2039.30  5607.8 2039.58
  5624.4 2039.73  5886.3 2039.10  6106.2 2045.46  6205.2 2046.64  6223.3 2046.82
#Mann=14,-1,0
  3978.0   0.045       0  4240.2    0.07       0  4349.3   0.035       0
  4458.3    0.07       0  4698.5   0.035       0  4987.5    0.07       0
  5006.9    0.07       0  5012.1    0.07       0  5055.8   0.035       0
  5128.6    0.07       0  5607.8   0.035       0  5624.4    0.07       0
  6106.2   0.035       0  6205.2    0.07       0
Bank Sta=5006.9,5012.1
Exp/Cntr=0.3,0.1

Type RM Length L Ch R = 1,1860,481,481,481
BEGIN DESCRIPTION:
Spring Creek Trib 01 3.0
END DESCRIPTION:
XS GIS Cut Line= 3
      1335480.01      6975113.01      1335155.00      6974738.00
      1333852.22      6974844.81
#Sta/Elev= 30
  4503.8 2031.71  4560.8 2033.18  4603.1 2029.05  4628.7 2029.23  4721.6 2030.79
  4731.4 2030.44  4751.7 2027.86  4773.6 2028.73  4794.4 2025.36  4808.7 2026.80
  4829.6 2023.49  4851.4 2022.08  4858.1 2019.19  4886.6 2013.99  4983.7 2008.41
  4984.1 2007.91  4989.0 2008.41  4995.5 2009.49  5040.2 2010.67  5058.2 2016.14
  5102.6 2018.02  5200.7 2020.70  5351.2 2029.00  5561.9 2037.14  5675.2 2038.63
  5933.2 2036.60  5973.3 2037.08  6112.1 2043.56  6211.8 2046.73  6307.2 2047.34
#Mann=10,-1,0
  4503.8   0.035       0  4628.7    0.07       0  4721.6   0.035       0
  4731.4    0.07       0  4983.7   0.035       0  4989.0    0.07       0
  4995.5   0.035       0  5102.6    0.07       0  6112.1   0.035       0
  6211.8    0.07       0
Bank Sta=4983.7,4989
Exp/Cntr=0.3,0.1

Type RM Length L Ch R = 1,1379,362,362,362
BEGIN DESCRIPTION:
Spring Creek Trib 01 2.0
END DESCRIPTION:
XS GIS Cut Line= 3
      1335255.04      6974388.01      1334955.00      6974338.00
      1334039.41      6974402.06
#Sta/Elev= 30
  4695.8 2030.10  4845.4 2019.01  4906.2 2015.97  4911.3 2016.73  4929.0 2015.90
  4949.3 2013.52  4967.0 2010.05  4972.1 2010.75  5037.4 2006.88  5037.8 2006.38
  5042.7 2006.88  5055.5 2008.04  5073.4 2010.63  5100.2 2009.65  5140.3 2013.35
  5190.4 2015.12  5200.5 2016.33  5210.2 2015.43  5280.7 2017.00  5330.8 2017.03
  5357.0 2013.58  5362.0 2014.64  5390.9 2013.73  5441.0 2016.65  5471.1 2021.51
  5498.8 2023.39  5561.3 2025.65  5798.7 2037.11  5898.1 2040.62  5917.8 2041.05
#Mann=6,-1,0
  4695.8    0.07       0  5037.4    0.07       0  5042.7    0.07       0
  5055.5    0.07       0  5798.7   0.035       0  5898.1   0.045       0
Bank Sta=5037.4,5042.7
Exp/Cntr=0.3,0.1

Type RM Length L Ch R = 1,1017,412,412,412
BEGIN DESCRIPTION:
Spring Creek Trib 01 1.5
END DESCRIPTION:
XS GIS Cut Line= 3
      1335235.51      6974235.46      1334880.00      6974013.00
      1334221.66      6974209.42
#Sta/Elev= 30
  4497.0 2015.35  4691.2 2011.86  4764.3 2011.91  4770.2 2011.09  4806.7 2010.66
  4822.4 2011.43  4843.3 2010.21  4954.7 2010.91  4961.9 2010.11  4973.8 2006.95
  4982.7 2005.67  5023.5 2005.12  5024.0 2004.62  5028.9 2005.12  5046.8 2008.38
  5087.3 2008.75  5125.7 2012.74  5151.2 2014.06  5164.0 2013.32  5191.9 2014.48
  5197.2 2013.12  5213.8 2015.96  5230.3 2016.95  5235.5 2016.34  5263.4 2018.26
  5406.4 2023.78  5511.1 2029.30  5544.2 2032.14  5549.5 2031.47  5603.4 2035.71
#Mann=5,-1,0
  4497.0    0.07       0  4822.4   0.035       0  4961.9    0.07       0
  5023.5    0.07       0  5028.9    0.07       0
Bank Sta=5023.5,5028.9
Exp/Cntr=0.3,0.1

Type RM Length L Ch R = 1,605,338,338,338
BEGIN DESCRIPTION:
Spring Creek Trib 01 1.0
END DESCRIPTION:
XS GIS Cut Line= 4
      1335266.75      6974214.60      1334931.48      6973710.88
      1334855.32      6973643.46      1334180.03      6973912.99
#Sta/Elev= 30
  4394.9 2013.32  4667.5 2007.31  4703.1 2007.62  4726.6 2003.21  4753.6 2007.81
  4768.6 2004.63  4775.2 1999.44  4787.0 1999.14  4787.4 1998.64  4792.4 1999.14
  4798.7 2003.06  4804.7 2001.44  4811.3 2006.72  4819.9 2008.06  4906.9 2009.11
  4932.7 2011.95  5042.0 2010.07  5075.7 2011.94  5122.8 2013.08  5143.8 2008.26
  5181.7 2006.01  5220.5 2008.69  5242.0 2014.85  5269.7 2018.05  5338.4 2019.29
  5397.7 2016.37  5421.9 2020.39  5522.0 2024.86  5729.5 2029.02  5828.8 2031.81
#Mann=11,-1,0
  4394.9    0.07       0  4667.5    0.16       0  4787.0    0.07       0
  4792.4    0.16       0  4819.9    0.07       0  4932.7    0.16       0
  5075.7    0.07       0  5143.8    0.16       0  5181.7   0.035       0
  5269.7    0.07       0  5729.5   0.035       0
Bank Sta=4787,4792.4
Exp/Cntr=0.3,0.1

Type RM Length L Ch R = 1,267,0,0,0
BEGIN DESCRIPTION:
Spring Creek Trib 01 0.5
END DESCRIPTION:
XS GIS Cut Line= 3
      1335428.22      6974277.09      1335196.99      6973465.38
      1335018.39      6973431.95
#Sta/Elev= 30
  4334.1 2013.95  4473.6 2006.93  4551.1 2005.18  4580.3 1997.69  4603.5 1996.89
  4619.4 1994.44  4624.6 1996.18  4632.0 1993.88  4632.4 1993.38  4637.4 1993.88
  4653.2 1999.04  4656.3 1998.13  4665.9 1998.19  4686.7 2002.76  4697.4 2002.24
  4707.5 2005.06  4758.8 2005.75  4913.6 2006.80  4950.0 2006.99  4957.0 2005.33
  4977.8 1996.30  4989.0 1993.94  4998.6 1994.39  5017.7 1998.49  5022.9 2001.23
  5040.2 2002.81  5056.7 2006.44  5181.7 2006.74  5342.9 2015.72  5359.8 2017.86
#Mann=7,-1,0
  4334.1    0.07       0  4551.1    0.16       0  4632.0    0.07       0
  4637.4    0.16       0  4656.3    0.07       0  4758.8   0.035       0
  4913.6    0.07       0
Bank Sta=4632,4637.4
Exp/Cntr=0.3,0.1

Chan Stop Cuts=-1