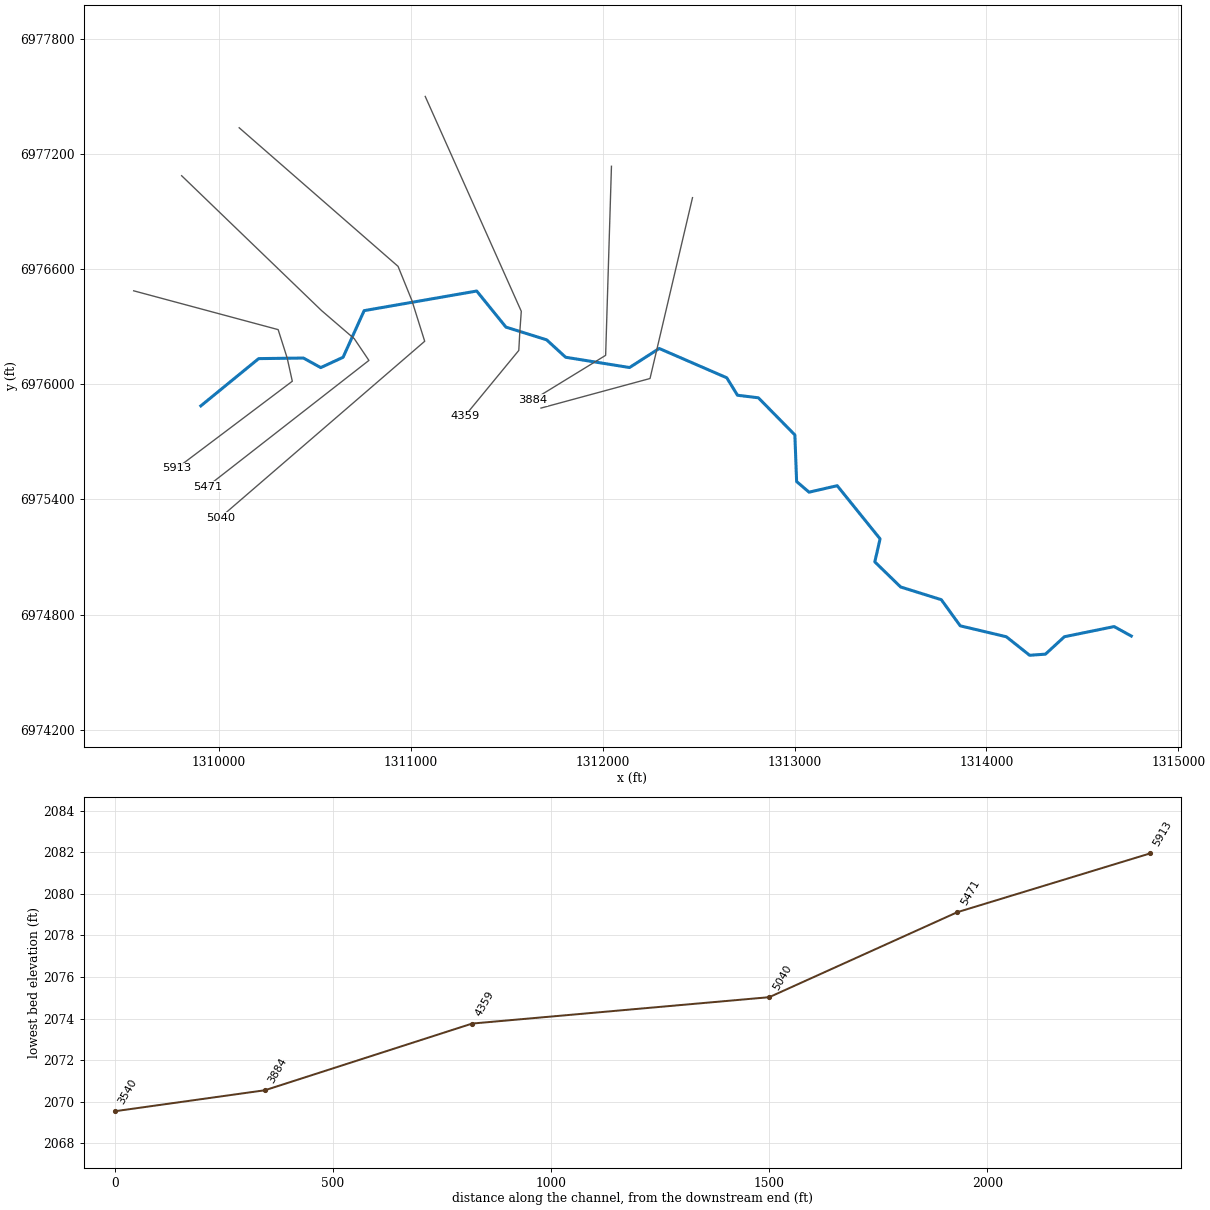
--- Spring Creek Trib 03.prj (project) ---

Proj Title=Spring Creek Trib 03 Base Level Engineering
Current Plan=p01
Default Exp/Contr=0.3,0.1
English Units
Geom File=g01
Flow File=f01
Plan File=p01
BEGIN DESCRIPTION:
Spring Creek Trib 03
END DESCRIPTION:

--- Spring Creek Trib 03.p01 (plan) ---

Plan Title=Multiple Run
Short Identifier=Multiple
Geom File=g01
Flow File=f01
Subcritical Flow
K Sum by GR= 0
Std Step Tol= 0.01
Critical Tol= 0.01
Num of Std Step Trials= 20
Max Error Tol= 0.3
Flow Tol Ratio= 0.001
Split Flow NTrial= 30
Split Flow Tol= 0.02
Split Flow Ratio= 0.02
Log Output Level= 0
Friction Slope Method= 1
Unsteady Friction Slope Method= 2
Unsteady Bridges Friction Slope Method= 1
Parabolic Critical Depth
Global Vel Dist=  1 , 1 , 1
Global Log Level= 0
CheckData=True
Encroach Param= -1, 0, 0, 0
BEGIN DESCRIPTION:
Multiple Run
END DESCRIPTION:

--- Spring Creek Trib 03.f01 (steady flow) ---

Flow Title=Multiple
Number of Profiles=7
Profile Names=10-year,25-year,50-year,1pct_min,100-year,1pct_plu,500-year
River Rch & RM= Spring Creek Tri,Reach-1,5913
     348     501     633     397     793    1581    1260
River Rch & RM= Spring Creek Tri,Reach-1,3884
     497     730     933     592    1182    2358    1922
Boundary for River Rch & Prof#=Spring Creek Tri,Reach-1,1
Up Type=0
Dn Type=3
Dn Slope=0.005
Boundary for River Rch & Prof#=Spring Creek Tri,Reach-1,2
Up Type=0
Dn Type=3
Dn Slope=0.005
Boundary for River Rch & Prof#=Spring Creek Tri,Reach-1,3
Up Type=0
Dn Type=3
Dn Slope=0.005
Boundary for River Rch & Prof#=Spring Creek Tri,Reach-1,4
Up Type=0
Dn Type=3
Dn Slope=0.005
Boundary for River Rch & Prof#=Spring Creek Tri,Reach-1,5
Up Type=0
Dn Type=3
Dn Slope=0.005
Boundary for River Rch & Prof#=Spring Creek Tri,Reach-1,6
Up Type=0
Dn Type=3
Dn Slope=0.005
Boundary for River Rch & Prof#=Spring Creek Tri,Reach-1,7
Up Type=0
Dn Type=3
Dn Slope=0.005

--- Spring Creek Trib 03.g01 (geometry) ---

Geom Title=Existing Conditions

River Reach=Spring Creek Tri,Reach-1
Reach XY= 30
      1309905.00      6975888.00      1310206.47      6976134.45
      1310439.79      6976137.46      1310530.01      6976087.58
      1310646.54      6976141.50      1310756.22      6976384.56
      1311342.99      6976486.83      1311495.32      6976298.76
      1311707.42      6976232.46      1311806.47      6976141.55
      1312139.66      6976087.96      1312294.30      6976187.30
      1312646.51      6976034.47      1312702.34      6975943.46
      1312811.17      6975930.14      1313001.46      6975736.54
      1313010.51      6975493.51      1313075.32      6975438.09
      1313222.08      6975471.86      1313445.59      6975194.66
      1313418.13      6975074.79      1313552.70      6974943.83
      1313764.81      6974877.49      1313863.34      6974741.16
      1314103.50      6974684.38      1314225.06      6974587.79
      1314307.42      6974593.41      1314406.47      6974684.45
      1314665.63      6974737.32      1314755.00      6974688.00

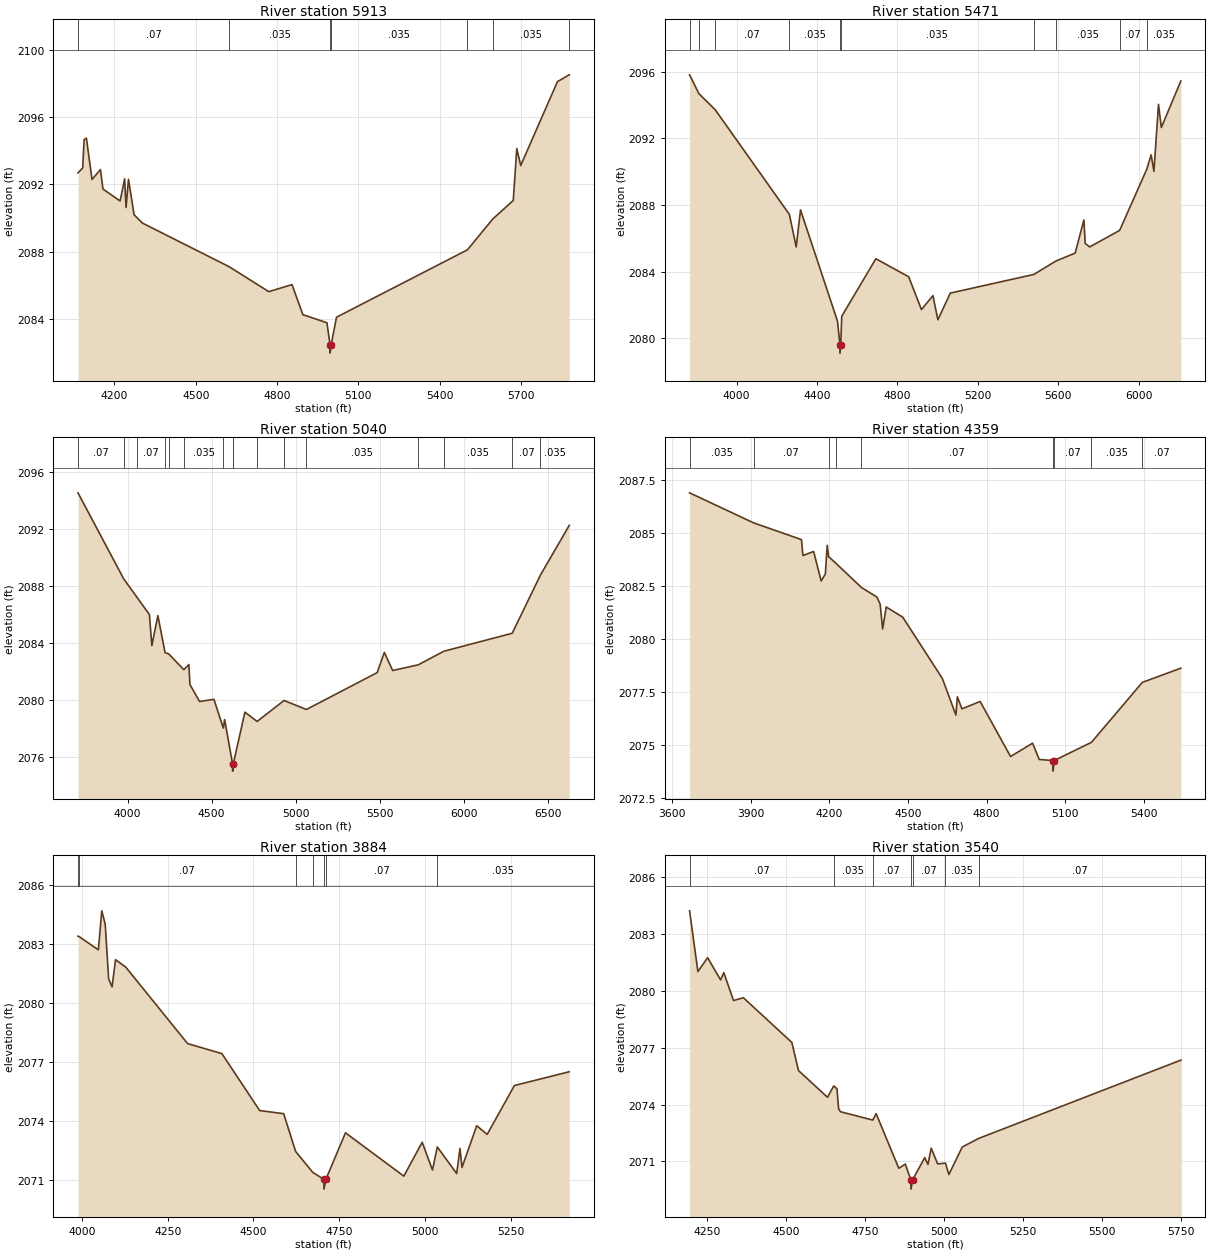
Type RM Length L Ch R = 1,5913,442,442,442
BEGIN DESCRIPTION:
Spring Creek Trib 03 4.0
END DESCRIPTION:
XS GIS Cut Line= 5
      1309554.95      6976488.01      1310308.02      6976285.62
      1310355.00      6976138.00      1310381.80      6976016.53
      1309779.97      6975562.98
#Sta/Elev= 30
  4065.4 2092.68  4082.8 2092.98  4088.0 2094.66  4096.5 2094.75  4117.2 2092.29
  4148.3 2092.88  4157.6 2091.72  4220.8 2091.01  4237.6 2092.33  4242.7 2090.62
  4251.8 2092.30  4272.4 2090.19  4303.6 2089.69  4622.7 2087.10  4769.6 2085.61
  4855.1 2086.03  4895.2 2084.24  4984.0 2083.76  4995.5 2082.45  4995.7 2081.95
  4999.5 2082.45  5019.4 2084.09  5502.3 2088.10  5595.5 2089.93  5671.5 2091.04
  5684.5 2094.13  5699.0 2093.12  5834.4 2098.11  5877.5 2098.52  5878.1 2098.52
#Mann=7,-1,0
  4065.4    0.07       0  4622.7   0.035       0  4995.5   0.035       0
  4999.5   0.035       0  5502.3    0.07       0  5595.5   0.035       0
  5877.5    0.07       0
Bank Sta=4995.5,4999.5
Exp/Cntr=0.3,0.1

Type RM Length L Ch R = 1,5471,431,431,431
BEGIN DESCRIPTION:
Spring Creek Trib 03 3.0
END DESCRIPTION:
XS GIS Cut Line= 5
      1309805.00      6977088.00      1310533.71      6976385.45
      1310705.00      6976238.00      1310781.11      6976125.03
      1309938.52      6975467.56
#Sta/Elev= 30
  3766.2 2095.81  3812.6 2094.68  3893.5 2093.72  4262.5 2087.44  4296.5 2085.49
  4317.9 2087.71  4501.8 2081.04  4514.0 2079.62  4514.2 2079.12  4518.0 2079.62
  4522.9 2081.33  4692.7 2084.78  4855.8 2083.70  4919.4 2081.73  4976.4 2082.57
  5001.1 2081.12  5062.9 2082.72  5478.6 2083.84  5587.6 2084.64  5683.9 2085.12
  5727.3 2087.11  5733.7 2085.70  5756.3 2085.49  5905.0 2086.48  6039.7 2090.14
  6061.7 2091.01  6075.6 2090.02  6098.2 2094.04  6112.4 2092.65  6209.4 2095.44
#Mann=10,-1,0
  3766.2    0.07       0  3812.6   0.035       0  3893.5    0.07       0
  4262.5   0.035       0  4514.0   0.035       0  4518.0   0.035       0
  5478.6    0.07       0  5587.6   0.035       0  5905.0    0.07       0
  6039.7   0.035       0
Bank Sta=4514,4518
Exp/Cntr=0.3,0.1

Type RM Length L Ch R = 1,5040,681,681,681
BEGIN DESCRIPTION:
Spring Creek Trib 03 2.0
END DESCRIPTION:
XS GIS Cut Line= 5
      1310104.99      6977338.01      1310933.02      6976615.48
      1311005.00      6976438.00      1311071.91      6976224.86
      1310006.49      6975305.81
#Sta/Elev= 30
  3705.4 2094.53  3976.9 2088.51  4055.6 2087.22  4130.2 2086.00  4144.5 2083.82
  4180.5 2085.93  4223.4 2083.32  4244.4 2083.25  4334.6 2082.14  4364.7 2082.50
  4371.3 2081.09  4428.3 2079.91  4513.7 2080.06  4569.5 2078.05  4577.3 2078.64
  4624.7 2075.53  4625.0 2075.03  4628.7 2075.53  4697.9 2079.16  4770.5 2078.51
  4930.5 2079.98  5063.4 2079.35  5484.1 2081.93  5526.9 2083.35  5576.3 2082.08
  5729.0 2082.48  5880.6 2083.43  6287.2 2084.69  6455.1 2088.77  6626.3 2092.25
#Mann=16,-1,0
  3705.4    0.07       0  3976.9   0.035       0  4055.6    0.07       0
  4223.4   0.035       0  4244.4    0.07       0  4334.6   0.035       0
  4569.5    0.07       0  4624.7    0.07       0  4628.7    0.07       0
  4770.5   0.035       0  4930.5    0.07       0  5063.4   0.035       0
  5729.0    0.07       0  5880.6   0.035       0  6287.2    0.07       0
  6455.1   0.035       0
Bank Sta=4624.7,4628.7
Exp/Cntr=0.3,0.1

Type RM Length L Ch R = 1,4359,475,475,475
BEGIN DESCRIPTION:
Spring Creek Trib 03 1.8
END DESCRIPTION:
XS GIS Cut Line= 5
      1311074.74      6977501.35      1311575.38      6976381.11
      1311567.64      6976272.87      1311562.36      6976177.12
      1311279.71      6975833.32
#Sta/Elev= 30
  3665.8 2086.90  3910.8 2085.48  4093.3 2084.69  4098.7 2083.94  4139.7 2084.13
  4168.4 2082.74  4184.3 2083.06  4191.6 2084.42  4196.8 2083.89  4226.0 2083.56
  4322.3 2082.43  4381.4 2081.98  4393.7 2081.64  4403.3 2080.47  4416.9 2081.51
  4480.0 2081.03  4631.2 2078.14  4683.1 2076.41  4688.6 2077.27  4706.3 2076.70
  4775.7 2077.05  4891.8 2074.45  4976.1 2075.08  5001.3 2074.31  5054.0 2074.26
  5054.3 2073.76  5058.6 2074.26  5200.9 2075.12  5395.2 2077.95  5542.3 2078.62
#Mann=9,-1,0
  3665.8   0.035       0  3910.8    0.07       0  4196.8   0.035       0
  4226.0    0.16       0  4322.3    0.07       0  5054.0    0.07       0
  5058.6    0.07       0  5200.9   0.035       0  5395.2    0.07       0
Bank Sta=5054,5058.6
Exp/Cntr=0.3,0.1

Type RM Length L Ch R = 1,3884,344,344,344
BEGIN DESCRIPTION:
Spring Creek Trib 03 1.5
END DESCRIPTION:
XS GIS Cut Line= 3
      1312045.40      6977137.34      1312015.07      6976151.53
      1311635.04      6975918.62
#Sta/Elev= 30
  3988.4 2083.39  3991.0 2083.38  4047.8 2082.70  4057.8 2084.68  4067.8 2084.00
  4077.8 2081.22  4087.8 2080.82  4097.8 2082.20  4127.8 2081.82  4307.9 2077.94
  4407.9 2077.43  4518.0 2074.54  4588.0 2074.38  4622.9 2072.46  4672.9 2071.40
  4705.0 2071.05  4705.5 2070.55  4711.1 2071.05  4768.1 2073.41  4938.2 2071.21
  4991.7 2072.93  5021.7 2071.52  5035.8 2072.69  5092.3 2071.34  5101.9 2072.62
  5107.7 2071.65  5150.7 2073.77  5181.2 2073.33  5260.5 2075.81  5420.4 2076.51
#Mann=7,-1,0
  3988.4   0.045       0  3991.0    0.07       0  4622.9   0.035       0
  4672.9    0.07       0  4705.0    0.07       0  4711.1    0.07       0
  5035.8   0.035       0
Bank Sta=4705,4711.1
Exp/Cntr=0.3,0.1

Type RM Length L Ch R = 1,3540,0,0,0
BEGIN DESCRIPTION:
Spring Creek Trib 03 1
END DESCRIPTION:
XS GIS Cut Line= 3
      1312467.86      6976973.74      1312246.40      6976030.75
      1311678.09      6975876.57
#Sta/Elev= 30
  4193.3 2084.21  4219.7 2081.01  4250.6 2081.74  4291.6 2080.57  4301.9 2080.95
  4332.7 2079.48  4363.8 2079.63  4517.6 2077.27  4538.6 2075.79  4630.6 2074.38
  4650.3 2074.98  4660.7 2074.83  4665.8 2073.78  4671.7 2073.62  4774.1 2073.18
  4784.7 2073.52  4856.6 2070.64  4877.2 2070.86  4894.6 2070.04  4895.1 2069.54
  4900.7 2070.04  4938.8 2071.20  4949.1 2070.84  4959.3 2071.70  4979.9 2070.87
  5004.5 2070.91  5015.4 2070.31  5057.8 2071.76  5109.4 2072.21  5750.8 2076.34
#Mann=7,-1,0
  4193.3    0.07       0  4650.3   0.035       0  4774.1    0.07       0
  4894.6    0.07       0  4900.7    0.07       0  5004.5   0.035       0
  5109.4    0.07       0
Bank Sta=4894.6,4900.7
Exp/Cntr=0.3,0.1

Chan Stop Cuts=-1