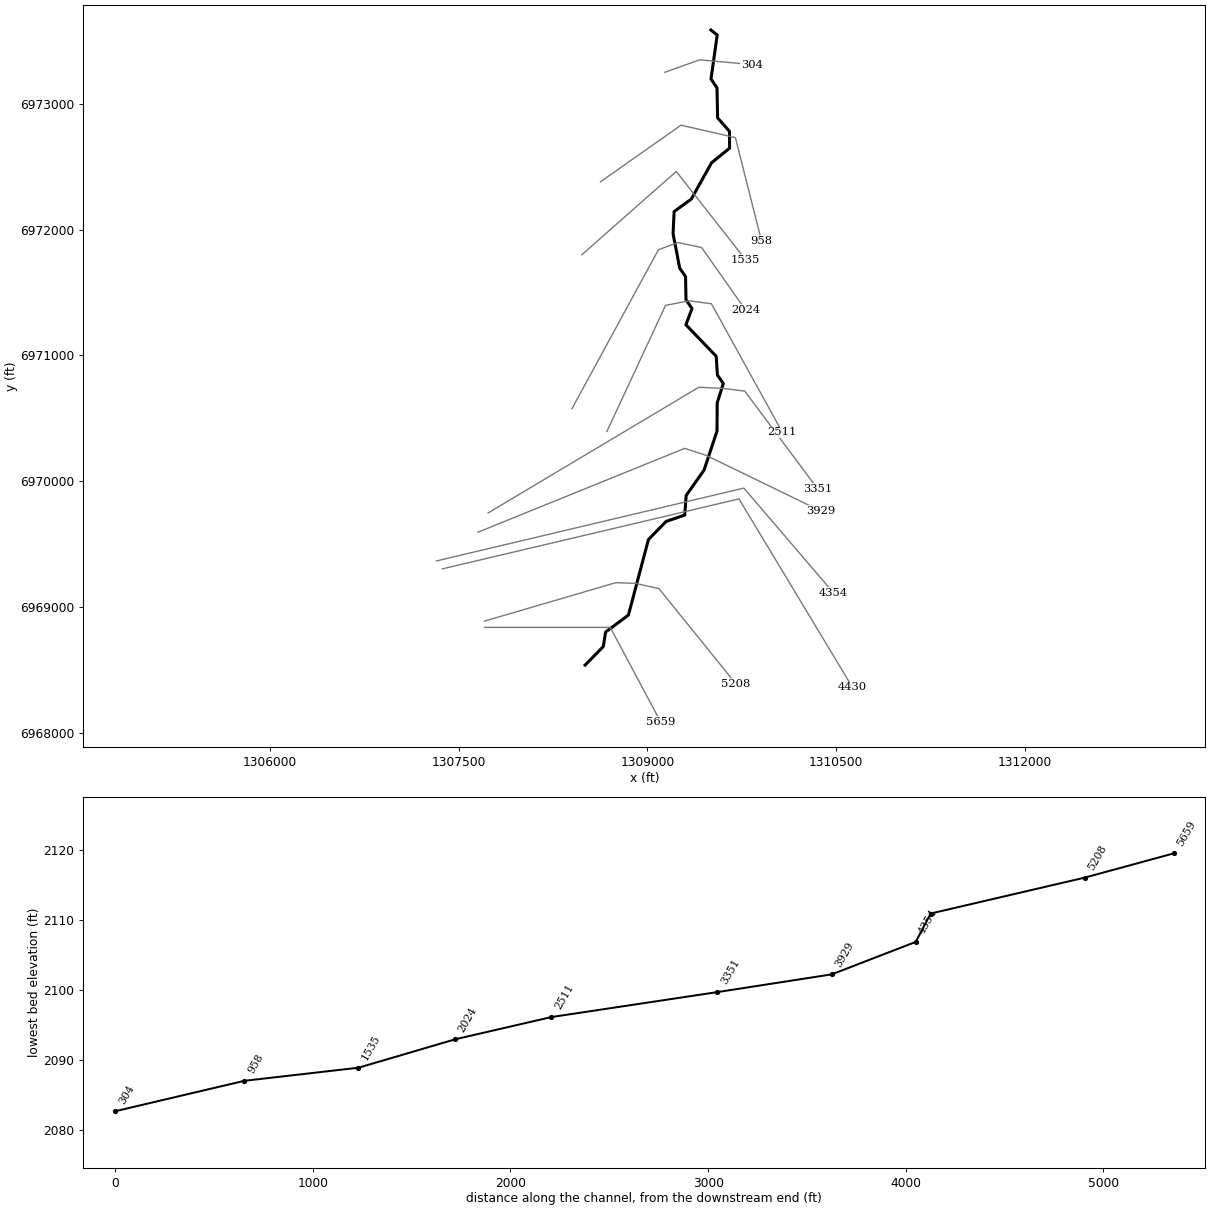
--- Spring Creek Trib 04.prj (project) ---

Proj Title=Spring Creek Trib 04 Base Level Engineering
Current Plan=p01
Default Exp/Contr=0.3,0.1
English Units
Geom File=g01
Flow File=f01
Plan File=p01
Y Axis Title=Elevation
X Axis Title(PF)=Main Channel Distance
X Axis Title(XS)=Station
BEGIN DESCRIPTION:
Spring Creek Trib 04
END DESCRIPTION:
DSS Export Rating Curves= 0
DSS Export Rating Curve Sorted= 0
DSS Export Volume Flow Curves= 0
DXF OffsetX= 0
DXF OffsetY= 0
DXF ScaleX= 1
DXF ScaleY= 10

--- Spring Creek Trib 04.p01 (plan) ---

Plan Title=Multiple Run
Short Identifier=Multiple
Geom File=g01
Flow File=f01
Subcritical Flow
K Sum by GR= 0
Std Step Tol= 0.01
Critical Tol= 0.01
Num of Std Step Trials= 20
Max Error Tol= 0.3
Flow Tol Ratio= 0.001
Split Flow NTrial= 30
Split Flow Tol= 0.02
Split Flow Ratio= 0.02
Log Output Level= 0
Friction Slope Method= 1
Unsteady Friction Slope Method= 2
Unsteady Bridges Friction Slope Method= 1
Parabolic Critical Depth
Global Vel Dist=  1 , 1 , 1
Global Log Level= 0
CheckData=True
Encroach Param= -1, 0, 0, 0
BEGIN DESCRIPTION:
Multiple Run
END DESCRIPTION:

--- Spring Creek Trib 04.f01 (steady flow) ---

Flow Title=Multiple
Number of Profiles=7
Profile Names=10-year,25-year,50-year,1pct_min,100-year,1pct_plu,500-year
River Rch & RM= Spring Creek Tri,Reach-1,5659
     421     615     784     497     991    1978    1605
Boundary for River Rch & Prof#=Spring Creek Tri,Reach-1,1
Up Type=0
Dn Type=3
Dn Slope=0.005
Boundary for River Rch & Prof#=Spring Creek Tri,Reach-1,2
Up Type=0
Dn Type=3
Dn Slope=0.005
Boundary for River Rch & Prof#=Spring Creek Tri,Reach-1,3
Up Type=0
Dn Type=3
Dn Slope=0.005
Boundary for River Rch & Prof#=Spring Creek Tri,Reach-1,4
Up Type=0
Dn Type=3
Dn Slope=0.005
Boundary for River Rch & Prof#=Spring Creek Tri,Reach-1,5
Up Type=0
Dn Type=3
Dn Slope=0.005
Boundary for River Rch & Prof#=Spring Creek Tri,Reach-1,6
Up Type=0
Dn Type=3
Dn Slope=0.005
Boundary for River Rch & Prof#=Spring Creek Tri,Reach-1,7
Up Type=0
Dn Type=3
Dn Slope=0.005

--- Spring Creek Trib 04.g01 (geometry) ---

Geom Title=Existing Conditions
Program Version=4.10

River Reach=Spring Creek Tri,Reach-1
Reach XY= 30
        1308505.        6968538.      1308649.48      6968685.57
      1308668.39      6968801.33      1308849.27      6968935.45
      1309008.61       6969536.5      1309148.83      6969680.14
      1309297.32      6969731.48      1309308.55      6969886.53
      1309451.17      6970089.58      1309553.78       6970398.5
      1309555.52      6970622.78       1309603.9      6970777.45
      1309557.27      6970843.94      1309547.18      6970994.19
      1309306.62      6971244.03       1309354.9       6971372.6
      1309307.29      6971443.93      1309303.78      6971627.49
      1309257.26      6971693.94      1309204.64      6971967.85
       1309212.8      6972144.21      1309349.41      6972243.61
      1309510.62      6972532.38      1309653.97      6972648.43
      1309652.94      6972782.14      1309558.55      6972889.47
      1309553.78       6973127.5      1309506.21      6973198.51
      1309555.46      6973548.45        1309505.        6973588.

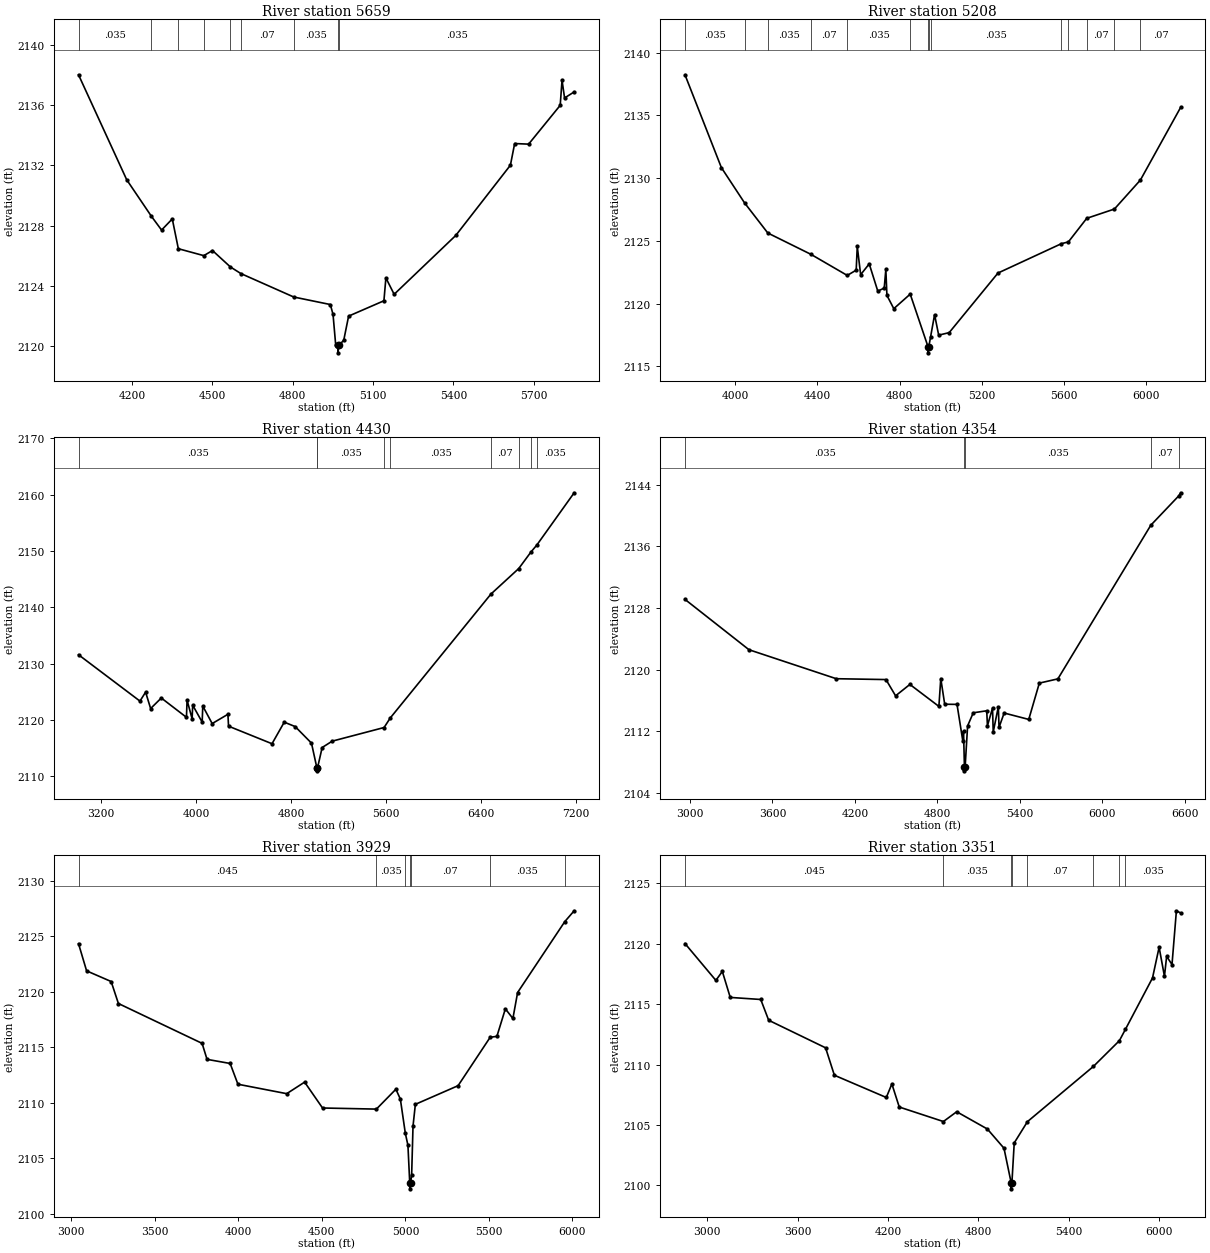
Type RM Length L Ch R = 1 ,5659    ,451,451,451
BEGIN DESCRIPTION:
Spring Creek Trib 04 4.0
END DESCRIPTION:
XS GIS Cut Line= 3
      1307705.01        6968838.        1308705.        6968838.
        1309105.      6968087.99
#Sta/Elev= 30
  4000.7 2138.02  4180.7 2131.04    4273 2128.61  4310.7  2127.7  4350.7 2128.44
  4373.3 2126.46  4468.4    2126  4500.7 2126.34  4567.5 2125.25  4606.6 2124.81
  4804.1 2123.25  4940.7 2122.75  4950.7 2122.09  4960.7 2120.05  4968.6 2120.04
  4968.9 2119.54  4972.7 2120.04  4990.7 2120.38  5008.8 2121.98  5140.6    2123
    5148 2124.52  5178.8 2123.43  5408.7 2127.34  5612.7 2132.01  5628.6 2133.45
  5680.7 2133.41  5798.6 2135.99  5805.4 2137.65  5814.9 2136.48  5850.7 2136.88
#Mann= 9 ,-1 , 0
  4000.7    .035       0    4273     .07       0  4373.3    .035       0
  4468.4     .07       0  4567.5    .035       0  4606.6     .07       0
  4804.1    .035       0  4968.6    .035       0  4972.7    .035       0
Bank Sta=4968.6,4972.7
XS Rating Curve= 0 ,0
Exp/Cntr=0.3,0.1

Type RM Length L Ch R = 1 ,5208    ,778,778,778
BEGIN DESCRIPTION:
Spring Creek Trib 04 3.0
END DESCRIPTION:
XS GIS Cut Line= 5
      1307704.98      6968887.99      1308749.86      6969193.61
        1308905.        6969188.      1309092.74      6969145.87
      1309705.01      6968387.99
#Sta/Elev= 30
  3756.5 2138.23  3933.6 2130.83  4046.3 2128.02  4159.3 2125.62  4369.1 2123.92
  4545.7 2122.24  4589.2 2122.66  4594.4 2124.55  4610.9  2122.3  4652.6 2123.16
  4694.2 2120.99  4725.5 2121.23  4733.4 2122.72  4738.6 2120.65  4772.1 2119.59
  4851.9 2120.75  4938.3 2116.57  4938.6 2116.07  4942.5 2116.57  4951.2 2117.36
  4970.4 2119.11  4990.4 2117.48  5041.4 2117.68  5278.8 2122.43  5587.3 2124.77
  5621.2 2124.91  5710.4 2126.79    5845 2127.53  5971.4 2129.84  6167.1 2135.63
#Mann= 14 ,-1 , 0
  3756.5    .035       0  4046.3     .07       0  4159.3    .035       0
  4369.1     .07       0  4545.7    .035       0  4851.9     .07       0
  4938.3    .035       0  4942.5     .07       0  4951.2    .035       0
  5587.3     .07       0  5621.2    .035       0  5710.4     .07       0
    5845    .035       0  5971.4     .07       0
Bank Sta=4938.3,4942.5
XS Rating Curve= 0 ,0
Exp/Cntr=0.3,0.1

Type RM Length L Ch R = 1 ,4430    ,76,76,76
BEGIN DESCRIPTION:
Spring Creek Trib 04 1.7
END DESCRIPTION:
XS GIS Cut Line= 3
      1307370.57      6969303.43      1309728.39      6969859.68
      1310629.99      6968363.01
#Sta/Elev= 30
  3012.3 2131.56  3529.2 2123.33  3576.7 2124.92    3619 2122.01  3708.8 2123.88
  3920.4 2120.45  3925.6  2123.5  3967.9 2120.19    3973  2122.6  4052.6  2119.6
  4057.7 2122.45  4136.8 2119.34  4269.3 2120.99  4274.4 2118.88  4640.2 2115.76
    4743 2119.59  4834.9 2118.81  4972.2 2115.87  5017.9 2111.45  5018.3 2110.95
  5022.8 2111.45    5062 2115.09  5146.6 2116.22    5583 2118.64  5635.1 2120.34
  6481.9 2142.33  6715.7 2146.86  6819.1 2149.81  6867.2 2151.01  7182.1 2160.31
#Mann= 9 ,-1 , 0
  3012.3    .035       0  5017.9    .035       0  5022.8    .035       0
    5583     .07       0  5635.1    .035       0  6481.9     .07       0
  6715.7    .035       0  6819.1     .07       0  6867.2    .035       0
Bank Sta=5017.9,5022.8
XS Rating Curve= 0 ,0
Exp/Cntr=0.3,0.1

Type RM Length L Ch R = 1 ,4354    ,425,425,425
BEGIN DESCRIPTION:
Spring Creek Trib 04 2.0
END DESCRIPTION:
XS GIS Cut Line= 3
      1307323.37      6969366.38      1309767.28      6969945.62
      1310479.99      6969113.01
#Sta/Elev= 30
  2963.8 2129.13  3429.6  2122.6  4065.1 2118.84  4426.7 2118.73  4496.7 2116.62
  4600.8  2118.1  4811.9 2115.25  4825.6 2118.86  4854.2 2115.53  4943.8 2115.51
    4986 2110.77  4991.1 2112.06  4997.9 2107.39  4998.2 2106.89  5002.8 2107.39
  5020.9 2112.72    5062 2114.42  5160.1 2114.68  5165.2 2112.74  5202.3 2115.03
  5207.4 2111.94  5244.5  2115.2  5249.7 2112.53  5286.8 2114.39    5466 2113.56
  5542.9 2118.27  5677.9 2118.82  6354.3 2138.75  6558.3 2142.57  6571.4 2142.96
#Mann= 5 ,-1 , 0
  2963.8    .035       0  4997.9    .035       0  5002.8    .035       0
  6354.3     .07       0  6558.3    .035       0
Bank Sta=4997.9,5002.8
XS Rating Curve= 0 ,0
Exp/Cntr=0.3,0.1

Type RM Length L Ch R = 1 ,3929    ,578,578,578
BEGIN DESCRIPTION:
Spring Creek Trib 04 1.5
END DESCRIPTION:
XS GIS Cut Line= 4
      1307653.99      6969595.26      1309296.73      6970261.32
      1309467.02      6970206.09      1310380.02      6969762.99
#Sta/Elev= 30
  3043.5 2124.33  3091.9 2121.88  3238.8 2120.92  3282.2 2118.94  3783.2 2115.35
  3812.7 2113.91    3951 2113.54  3997.6 2111.67  4289.6 2110.82  4396.8 2111.86
    4504 2109.53  4826.3 2109.43    4943 2111.22  4969.8 2110.33  4999.3 2107.27
  5015.1 2106.17    5026 2102.75  5026.4 2102.25  5030.9 2102.75  5037.4 2103.53
  5045.5  2107.9  5059.6 2109.86  5315.3 2111.54  5507.4  2115.9  5547.5 2115.98
  5598.2 2118.46  5643.3 2117.59  5671.5 2119.93  5953.7 2126.31    6010 2127.29
#Mann= 7 ,-1 , 0
  3043.5    .045       0  4826.3    .035       0  4999.3     .07       0
    5026     .07       0  5030.9     .07       0  5507.4    .035       0
  5953.7     .07       0
Bank Sta=5026,5030.9
XS Rating Curve= 0 ,0
Exp/Cntr=0.3,0.1

Type RM Length L Ch R = 1 ,3351    ,840,840,840
BEGIN DESCRIPTION:
Spring Creek Trib 04 1.0
END DESCRIPTION:
XS GIS Cut Line= 5
      1307733.82      6969748.03      1309409.58      6970747.43
        1309605.        6970738.      1309774.16      6970717.05
        1310355.        6969938.
#Sta/Elev= 30
  2852.4 2120.02  3057.4 2116.97  3100.3 2117.71  3152.8 2115.56  3355.2 2115.39
  3407.8 2113.67  3785.4 2111.39  3843.8 2109.12  4188.3 2107.28  4225.3  2108.4
  4274.3 2106.49  4567.1 2105.29  4655.5  2106.1    4859 2104.67  4969.2 2103.08
  5016.9 2100.22  5017.3 2099.72  5021.8 2100.22  5037.2 2103.52  5124.9 2105.28
  5562.6 2109.85    5735 2111.98  5775.5 2112.93  5954.8 2117.17  5998.6 2119.71
    6034 2117.31  6048.6 2118.96  6084.1 2118.28  6113.3 2122.73  6141.4 2122.55
#Mann= 8 ,-1 , 0
  2852.4    .045       0  4567.1    .035       0  5016.9    .035       0
  5021.8    .035       0  5124.9     .07       0  5562.6    .035       0
    5735     .07       0  5775.5    .035       0
Bank Sta=5016.9,5021.8
XS Rating Curve= 0 ,0
Exp/Cntr=0.3,0.1

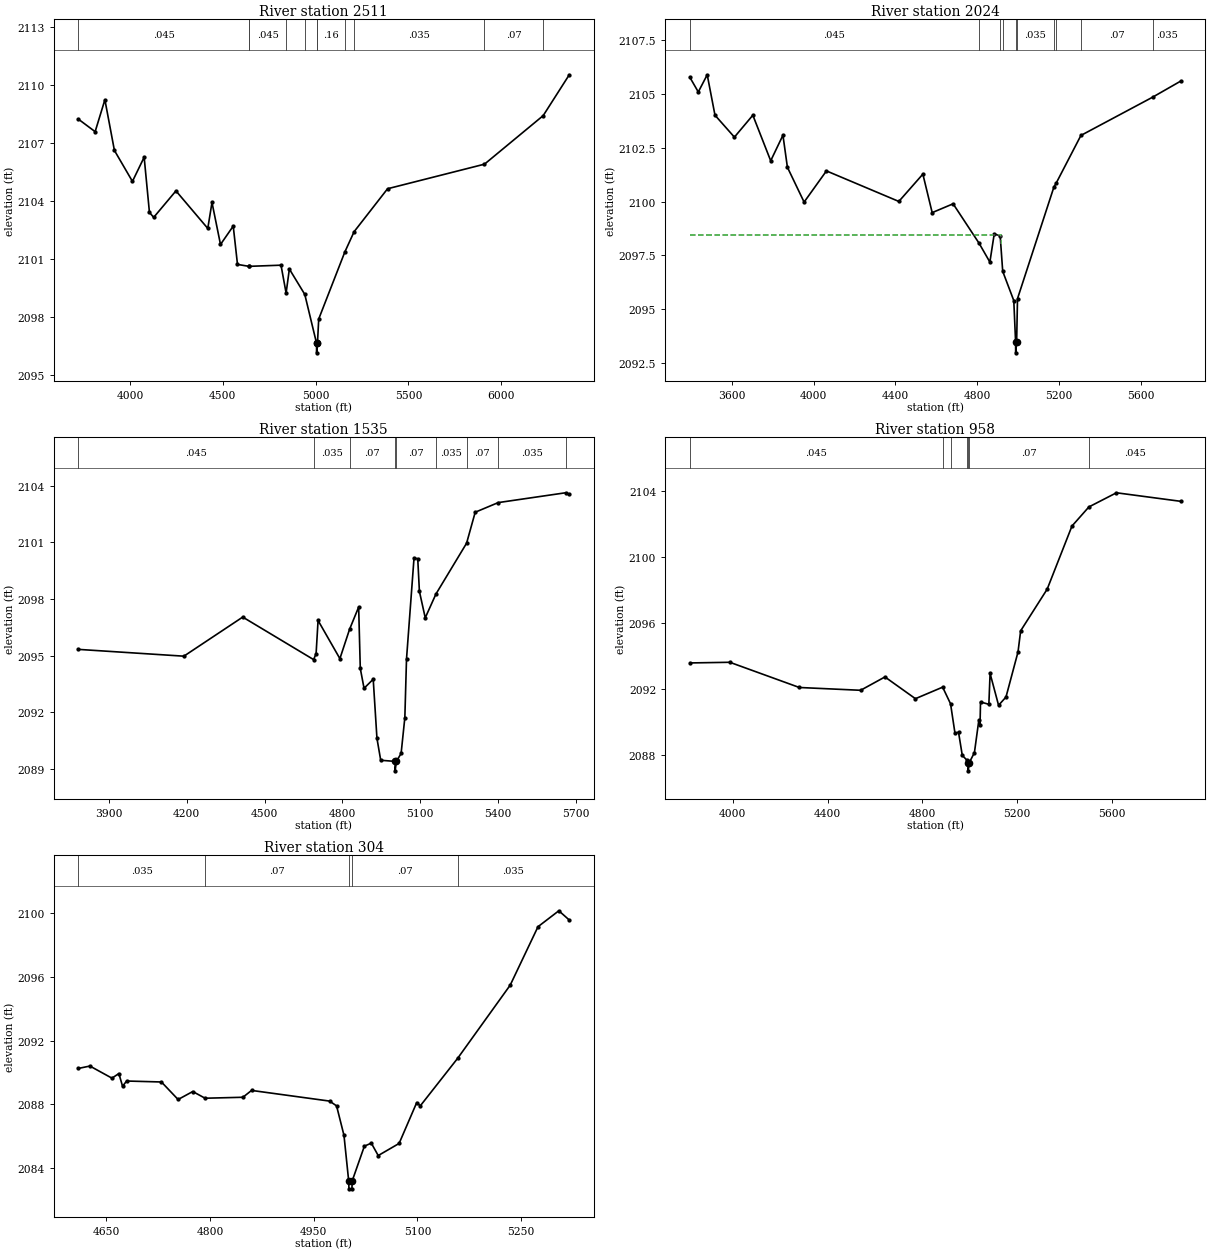
Type RM Length L Ch R = 1 ,2511    ,487,487,487
BEGIN DESCRIPTION:
Spring Creek Trib 04 0.9
END DESCRIPTION:
XS GIS Cut Line= 5
      1308678.33      6970395.65      1309144.82      6971398.47
      1309330.52      6971434.61      1309509.41      6971411.49
      1310073.68      6970388.12
#Sta/Elev= 30
    3722 2108.23  3812.8 2107.58  3865.3 2109.23  3916.6 2106.61  4013.7 2105.01
  4076.8 2106.26  4105.2 2103.41  4128.1 2103.15    4248 2104.52  4419.4 2102.58
  4442.1 2103.92  4487.9 2101.75  4556.5  2102.7  4579.4 2100.72  4641.2 2100.62
  4641.4 2100.62  4813.8 2100.68  4841.2 2099.24  4858.8 2100.48  4941.8 2099.17
  5005.1 2096.65  5005.5 2096.15  5010.1 2096.65  5016.9  2097.9  5157.4 2101.36
  5207.4 2102.41  5387.6 2104.63  5909.5  2105.9  6225.8 2108.41  6366.2 2110.52
#Mann= 11 ,-1 , 0
    3722    .045       0  4641.2    .035       0  4641.4    .045       0
  4841.2     .07       0  4941.8     .16       0  5005.1     .07       0
  5010.1     .16       0  5157.4     .07       0  5207.4    .035       0
  5909.5     .07       0  6225.8    .035       0
Bank Sta=5005.1,5010.1
XS Rating Curve= 0 ,0
Exp/Cntr=0.3,0.1

Type RM Length L Ch R = 1 ,2024    ,489,489,489
BEGIN DESCRIPTION:
Spring Creek Trib 04 0.8
END DESCRIPTION:
XS GIS Cut Line= 5
      1308400.45      6970576.56       1309088.4      6971841.18
      1309244.15      6971897.65      1309431.28      6971858.54
      1309779.99      6971363.01
#Sta/Elev= 30
  3394.7 2105.78  3435.9  2105.1  3479.6  2105.9  3517.6 2104.02  3612.6    2103
  3702.8 2104.02  3790.2  2101.9  3850.1 2103.09  3871.9  2101.6  3953.6 2099.98
  4062.9 2101.43  4417.2 2100.01  4534.7 2101.28  4580.3 2099.49  4682.7  2099.9
  4809.5 2098.07  4862.6 2097.19  4883.9  2098.5    4913 2098.41  4925.4 2096.76
  4979.6  2095.4  4988.5 2093.47  4988.8 2092.97  4993.5 2093.47  4997.8 2095.49
  5175.9 2100.68  5186.4 2100.85  5308.1 2103.08  5659.2 2104.86  5797.1 2105.61
#Mann= 10 ,-1 , 0
  3394.7    .045       0  4809.5    .035       0    4913     .07       0
  4925.4    .035       0  4988.5    .035       0  4993.5    .035       0
  5175.9     .07       0  5186.4    .035       0  5308.1     .07       0
  5659.2    .035       0
#XS Ineff= 2 , 0
       0  4915.8 2098.47               0
Permanent Ineff=
       F       F
Bank Sta=4988.5,4993.5
XS Rating Curve= 0 ,0
Exp/Cntr=0.3,0.1

Type RM Length L Ch R = 1 ,1535    ,577,577,577
BEGIN DESCRIPTION:
Spring Creek Trib 04 0.7
END DESCRIPTION:
XS GIS Cut Line= 3
      1308478.58      6971800.51        1309230.        6972463.
      1309780.01      6971762.99
#Sta/Elev= 30
  3782.4 2095.34  4189.3 2094.98  4416.1 2097.05  4689.1  2094.8  4698.8 2095.11
  4706.4 2096.87  4790.5 2094.85  4827.7  2096.4  4862.8 2097.58  4869.1 2094.33
  4883.6 2093.28  4918.9 2093.76  4933.3 2090.63  4947.8 2089.47  5003.1 2089.41
  5003.4 2088.91  5008.1 2089.41  5026.4 2089.83  5040.8 2091.73  5047.2 2094.83
  5076.1 2100.17  5090.5 2100.14  5096.9 2098.41  5119.4 2097.01  5160.6 2098.27
  5278.7 2100.96  5311.9  2102.6  5400.5 2103.11    5660 2103.63  5674.4 2103.54
#Mann= 9 ,-1 , 0
  3782.4    .045       0  4689.1    .035       0  4827.7     .07       0
  5003.1     .07       0  5008.1     .07       0  5160.6    .035       0
  5278.7     .07       0  5400.5    .035       0    5660    .045       0
Bank Sta=5003.1,5008.1
XS Rating Curve= 0 ,0
Exp/Cntr=0.3,0.1

Type RM Length L Ch R = 1 ,958     ,654,654,654
BEGIN DESCRIPTION:
Spring Creek Trib 04 0.6
END DESCRIPTION:
XS GIS Cut Line= 4
      1308627.18      6972380.44      1309267.38      6972831.29
      1309700.16      6972732.11      1309907.37      6971912.31
#Sta/Elev= 30
  3818.8 2093.59  3987.4 2093.63  4280.9  2092.1  4539.6 2091.93  4642.2 2092.74
  4770.9 2091.42  4885.8 2092.12  4919.2 2091.11  4937.9 2089.32  4952.8 2089.39
  4968.7 2087.98  4988.1 2087.69  4993.2 2087.54  4993.6 2087.04  4998.3 2087.54
    5020 2088.15  5038.6 2090.12  5043.7 2089.85  5045.7 2091.22  5080.9 2091.08
  5086.1 2092.95  5121.9 2091.02  5153.2 2091.52    5204 2094.26  5215.1 2095.54
  5327.1 2098.07  5431.7  2101.9  5503.1 2103.06  5619.5 2103.92  5891.4  2103.4
#Mann= 7 ,-1 , 0
  3818.8    .045       0  4885.8     .07       0  4919.2    .035       0
  4988.1     .07       0  4993.2     .07       0  4998.3     .07       0
  5503.1    .045       0
Bank Sta=4993.2,4998.3
XS Rating Curve= 0 ,0
Exp/Cntr=0.3,0.1

Type RM Length L Ch R = 1 ,304     ,0,0,0
BEGIN DESCRIPTION:
Spring Creek Trib 04 0.5
END DESCRIPTION:
XS GIS Cut Line= 3
      1309139.16      6973251.63      1309416.06      6973350.79
      1309830.02        6973313.
#Sta/Elev= 30
  4609.7 2090.25  4626.5  2090.4  4658.4 2089.64  4668.4 2089.93  4673.7 2089.13
  4679.6 2089.46  4729.9  2089.4    4754  2088.3  4775.2  2088.8    4793 2088.38
  4847.7 2088.44  4860.2 2088.87    4973  2088.2  4983.1  2087.9  4993.8 2086.05
  5000.6 2083.19    5001 2082.69  5005.3 2082.69  5005.7 2083.19  5023.3 2085.37
  5033.3 2085.56  5043.3 2084.78  5073.5 2085.54    5099 2088.11  5104.1  2087.9
  5158.2 2090.89  5234.1 2095.48  5274.3 2099.15  5304.4 2100.15  5319.5 2099.57
#Mann= 5 ,-1 , 0
  4609.7    .035       0    4793     .07       0  5000.6     .07       0
  5005.7     .07       0  5158.2    .035       0
Bank Sta=5000.6,5005.7
XS Rating Curve= 0 ,0
Exp/Cntr=0.3,0.1

Chan Stop Cuts=-1
Use User Specified Reach Order=0
Composite Channel Slope=5