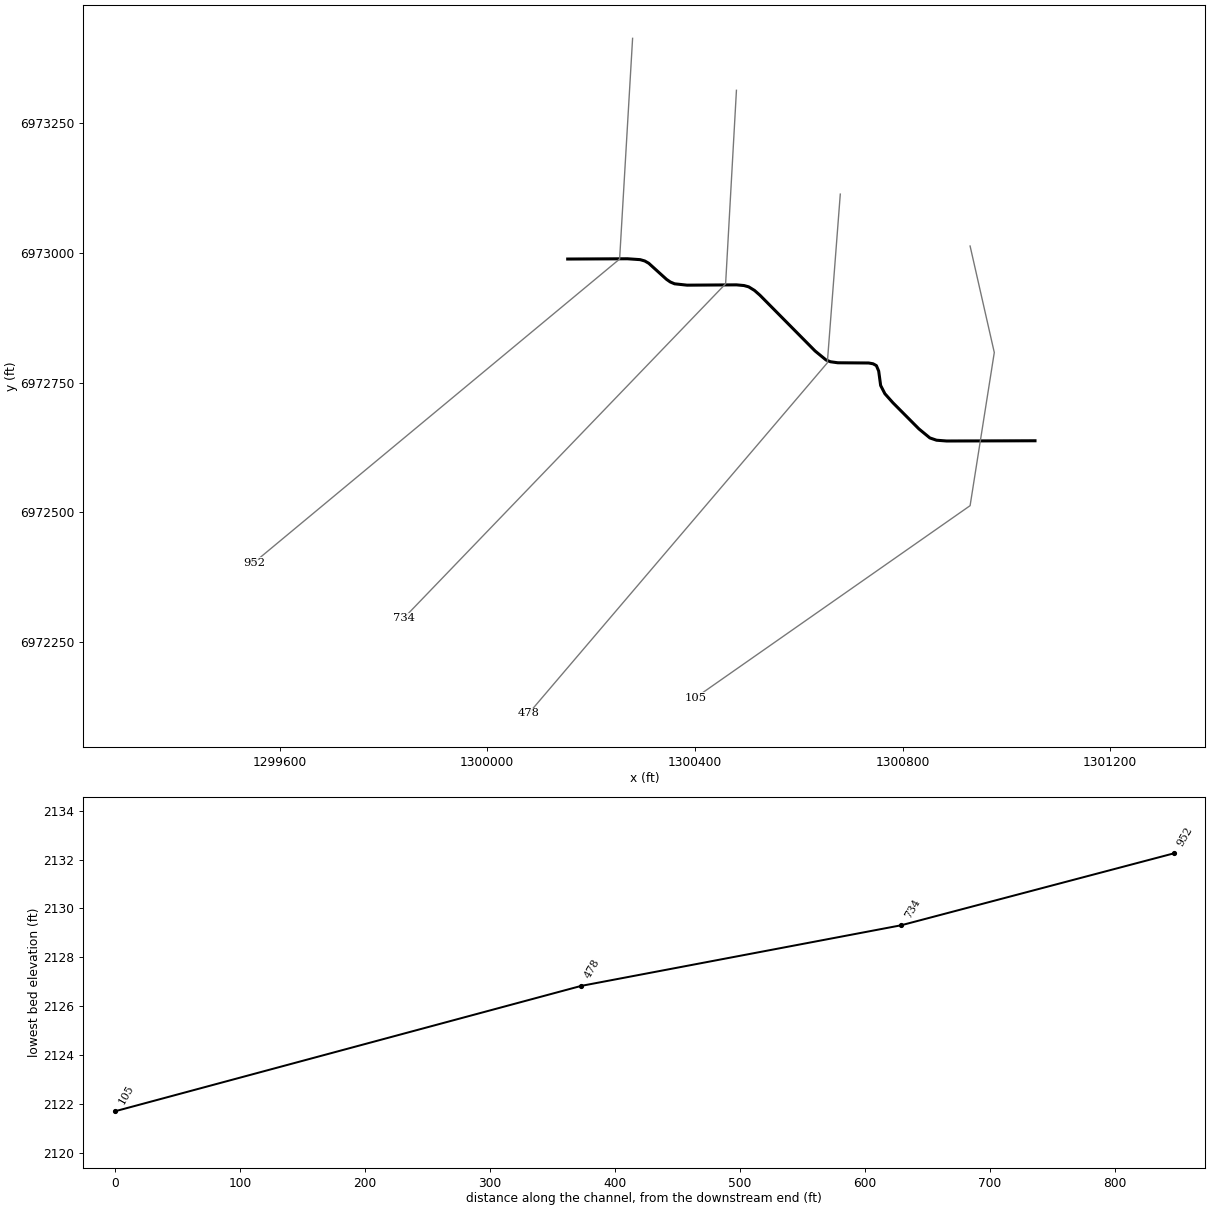
--- Spring Creek Trib 05.prj (project) ---

Proj Title=Spring Creek Trib 05 Base Level Engineering
Current Plan=p01
Default Exp/Contr=0.3,0.1
English Units
Geom File=g01
Flow File=f01
Plan File=p01
BEGIN DESCRIPTION:
Spring Creek Trib 05
END DESCRIPTION:

--- Spring Creek Trib 05.p01 (plan) ---

Plan Title=Multiple Run
Short Identifier=Multiple
Geom File=g01
Flow File=f01
Subcritical Flow
K Sum by GR= 0
Std Step Tol= 0.01
Critical Tol= 0.01
Num of Std Step Trials= 20
Max Error Tol= 0.3
Flow Tol Ratio= 0.001
Split Flow NTrial= 30
Split Flow Tol= 0.02
Split Flow Ratio= 0.02
Log Output Level= 0
Friction Slope Method= 1
Unsteady Friction Slope Method= 2
Unsteady Bridges Friction Slope Method= 1
Parabolic Critical Depth
Global Vel Dist=  1 , 1 , 1
Global Log Level= 0
CheckData=True
Encroach Param= -1, 0, 0, 0
BEGIN DESCRIPTION:
Multiple Run
END DESCRIPTION:

--- Spring Creek Trib 05.f01 (steady flow) ---

Flow Title=Multiple
Number of Profiles=7
Profile Names=10-year,25-year,50-year,1pct_min,100-year,1pct_plu,500-year
River Rch & RM= Spring Creek Tri,Reach-1,952
     228     325     406     254     507    1011     797
River Rch & RM= Spring Creek Tri,Reach-1,105
    1023    1548    2017    1302    2598    5183    4370
Boundary for River Rch & Prof#=Spring Creek Tri,Reach-1,1
Up Type=0
Dn Type=3
Dn Slope=0.005
Boundary for River Rch & Prof#=Spring Creek Tri,Reach-1,2
Up Type=0
Dn Type=3
Dn Slope=0.005
Boundary for River Rch & Prof#=Spring Creek Tri,Reach-1,3
Up Type=0
Dn Type=3
Dn Slope=0.005
Boundary for River Rch & Prof#=Spring Creek Tri,Reach-1,4
Up Type=0
Dn Type=3
Dn Slope=0.005
Boundary for River Rch & Prof#=Spring Creek Tri,Reach-1,5
Up Type=0
Dn Type=3
Dn Slope=0.005
Boundary for River Rch & Prof#=Spring Creek Tri,Reach-1,6
Up Type=0
Dn Type=3
Dn Slope=0.005
Boundary for River Rch & Prof#=Spring Creek Tri,Reach-1,7
Up Type=0
Dn Type=3
Dn Slope=0.005

--- Spring Creek Trib 05.g01 (geometry) ---

Geom Title=Existing Conditions

River Reach=Spring Creek Tri,Reach-1
Reach XY= 30
      1300155.00      6972988.00      1300270.21      6972988.51
      1300294.52      6972986.83      1300303.45      6972984.25
      1300311.06      6972979.87      1300345.35      6972948.85
      1300352.67      6972943.75      1300360.94      6972940.27
      1300384.87      6972937.68      1300480.11      6972938.27
      1300494.56      6972936.94      1300503.53      6972934.46
      1300514.80      6972927.52      1300525.16      6972918.39
      1300631.49      6972810.89      1300652.63      6972793.55
      1300660.98      6972790.19      1300675.21      6972788.20
      1300734.74      6972787.78      1300743.12      6972786.26
      1300749.53      6972782.74      1300753.95      6972772.21
      1300757.72      6972744.51      1300765.89      6972728.60
      1300781.32      6972711.24      1300831.42      6972660.84
      1300852.53      6972643.45      1300865.42      6972639.04
      1300884.81      6972637.55      1301055.00      6972638.00

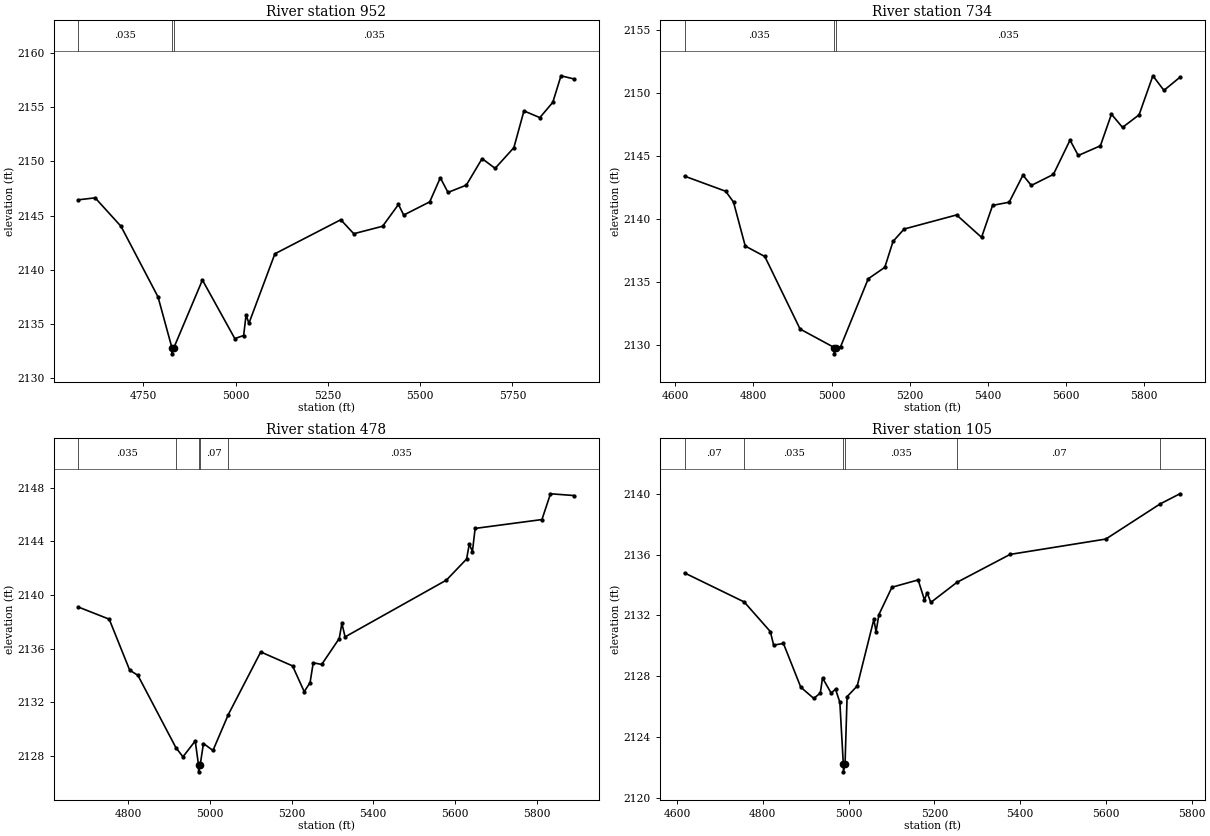
Type RM Length L Ch R = 1,952,218,218,218
BEGIN DESCRIPTION:
Spring Creek Trib 05 2.0
END DESCRIPTION:
XS GIS Cut Line= 3
      1300280.00      6973413.05      1300255.00      6972988.00
      1299550.52      6972403.14
#Sta/Elev= 30
  4574.7 2146.46  4619.8 2146.64  4689.9 2144.01  4790.1 2137.50  4828.2 2132.75
  4828.4 2132.25  4832.2 2132.75  4910.3 2139.06  4998.0 2133.66  5022.0 2133.94
  5028.5 2135.83  5036.3 2135.07  5106.6 2141.48  5285.0 2144.62  5320.2 2143.33
  5398.3 2144.02  5441.3 2146.03  5455.4 2145.05  5525.9 2146.27  5554.6 2148.49
  5575.4 2147.14  5624.9 2147.81  5667.8 2150.26  5703.0 2149.36  5753.8 2151.27
  5781.1 2154.66  5824.1 2154.04  5859.2 2155.45  5881.4 2157.90  5916.1 2157.61
#Mann=3,-1,0
  4574.7   0.035       0  4828.2   0.035       0  4832.2   0.035       0
Bank Sta=4828.2,4832.2
Exp/Cntr=0.3,0.1

Type RM Length L Ch R = 1,734,256,256,256
BEGIN DESCRIPTION:
Spring Creek Trib 05 1.5
END DESCRIPTION:
XS GIS Cut Line= 3
      1300480.00      6973313.01      1300459.15      6972940.31
      1299839.18      6972296.18
#Sta/Elev= 30
  4624.0 2143.42  4729.2 2142.22  4749.2 2141.36  4779.2 2137.87  4829.3 2137.04
  4919.5 2131.28  5007.0 2129.81  5007.2 2129.31  5011.0 2129.81  5023.1 2129.87
  5093.9 2135.27  5136.3 2136.18  5157.4 2138.24  5185.7 2139.22  5320.0 2140.34
  5383.8 2138.56  5412.1 2141.10  5454.5 2141.35  5489.8 2143.50  5511.1 2142.68
  5567.7 2143.56  5610.2 2146.28  5631.3 2145.06  5687.9 2145.83  5716.2 2148.34
  5744.5 2147.29  5786.9 2148.29  5822.2 2151.39  5850.5 2150.23  5891.3 2151.27
#Mann=3,-1,0
  4624.0   0.035       0  5007.0   0.035       0  5011.0   0.035       0
Bank Sta=5007,5011
Exp/Cntr=0.3,0.1

Type RM Length L Ch R = 1,478,373,373,373
BEGIN DESCRIPTION:
Spring Creek Trib 05 1.0
END DESCRIPTION:
XS GIS Cut Line= 3
      1300680.00      6973113.00      1300655.00      6972788.00
      1300079.98      6972112.97
#Sta/Elev= 30
  4678.3 2139.10  4753.5 2138.20  4803.7 2134.40  4823.7 2134.02  4916.8 2128.63
  4934.1 2127.95  4964.1 2129.13  4972.2 2127.33  4972.4 2126.83  4976.2 2127.33
  4984.2 2128.94  5007.5 2128.42  5045.2 2131.10  5124.5 2135.76  5202.4 2134.72
  5231.0 2132.80  5245.3 2133.48  5253.0 2134.95  5273.8 2134.83  5316.7 2136.76
  5323.2 2137.89  5331.0 2136.88  5579.1 2141.11  5628.5 2142.68  5635.1 2143.79
  5642.8 2143.24  5649.4 2144.96  5813.0 2145.62  5833.9 2147.54  5891.0 2147.41
#Mann=5,-1,0
  4678.3   0.035       0  4916.8    0.07       0  4972.2    0.07       0
  4976.2    0.07       0  5045.2   0.035       0
Bank Sta=4972.2,4976.2
Exp/Cntr=0.3,0.1

Type RM Length L Ch R = 1,105,0,0,0
BEGIN DESCRIPTION:
Spring Creek Trib 05 0.5
END DESCRIPTION:
XS GIS Cut Line= 4
      1300929.99      6973013.03      1300976.60      6972807.97
      1300930.00      6972513.00      1300400.45      6972142.69
#Sta/Elev= 30
  4617.5 2134.79  4756.6 2132.88  4817.5 2130.93  4825.2 2130.04  4848.0 2130.15
  4888.5 2127.27  4918.9 2126.53  4934.1 2126.89  4939.2 2127.88  4959.4 2126.88
  4969.5 2127.14  4979.6 2126.28  4987.7 2122.20  4988.0 2121.70  4991.7 2122.20
  4996.5 2126.65  5020.1 2127.35  5058.9 2131.73  5064.0 2130.92  5070.7 2132.05
  5101.1 2133.85  5162.2 2134.33  5177.0 2133.01  5183.1 2133.49  5191.8 2132.85
  5252.6 2134.17  5376.7 2136.01  5599.9 2137.02  5726.4 2139.33  5772.6 2140.00
#Mann=6,-1,0
  4617.5    0.07       0  4756.6   0.035       0  4987.7   0.035       0
  4991.7   0.035       0  5252.6    0.07       0  5726.4   0.035       0
Bank Sta=4987.7,4991.7
Exp/Cntr=0.3,0.1

Chan Stop Cuts=-1