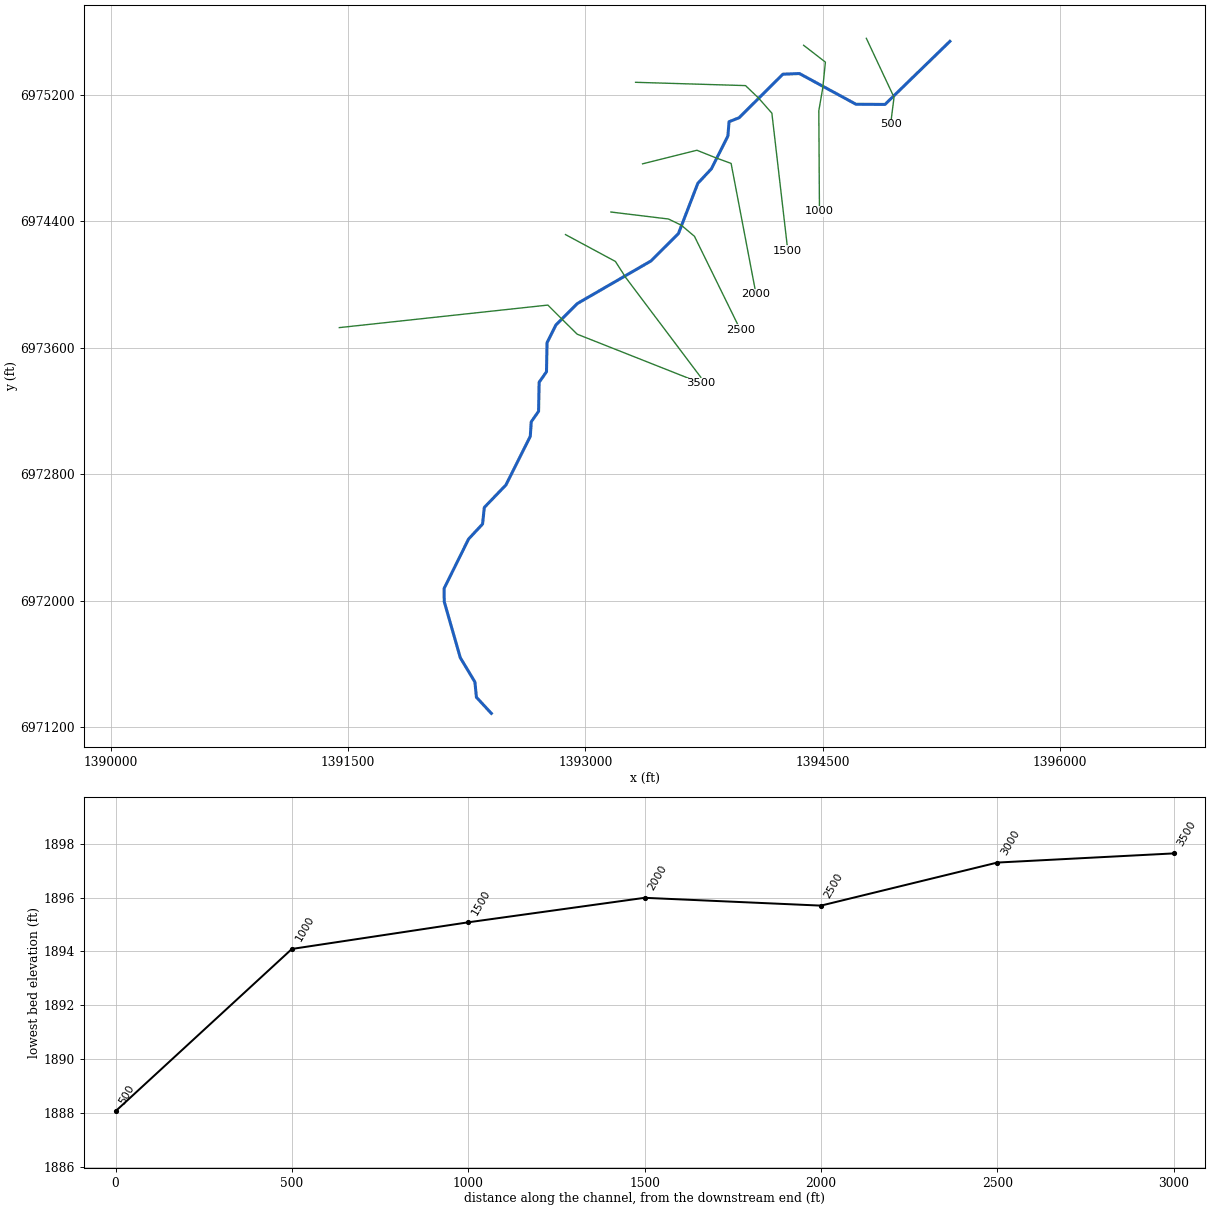
--- UCFB HW Trib 01.prj (project) ---

Proj Title=UCFB HW Trib 01 Base Level Engineering
Current Plan=p01
Default Exp/Contr=0.3,0.1
English Units
Geom File=g01
Flow File=f01
Plan File=p01
BEGIN DESCRIPTION:
UCFB HW Trib 01
END DESCRIPTION:

--- UCFB HW Trib 01.p01 (plan) ---

Plan Title=Multiple Run
Short Identifier=Multiple
Geom File=g01
Flow File=f01
Subcritical Flow
K Sum by GR= 0
Std Step Tol= 0.01
Critical Tol= 0.01
Num of Std Step Trials= 20
Max Error Tol= 0.3
Flow Tol Ratio= 0.001
Split Flow NTrial= 30
Split Flow Tol= 0.02
Split Flow Ratio= 0.02
Log Output Level= 0
Friction Slope Method= 1
Unsteady Friction Slope Method= 2
Unsteady Bridges Friction Slope Method= 1
Parabolic Critical Depth
Global Vel Dist=  1 , 1 , 1
Global Log Level= 0
CheckData=True
Encroach Param= -1, 0, 0, 0
BEGIN DESCRIPTION:
Multiple Run
END DESCRIPTION:

--- UCFB HW Trib 01.f01 (steady flow) ---

Flow Title=Multiple
Number of Profiles=7
Profile Names=10-year,25-year,50-year,1pct_min,100-year,1pct_plu,500-year
River Rch & RM= UCFB HW Trib 01,Reach-1,3500
     253     354     437     268     536    1069     814
Boundary for River Rch & Prof#=UCFB HW Trib 01,Reach-1,1
Up Type=0
Dn Type=3
Dn Slope=0.005
Boundary for River Rch & Prof#=UCFB HW Trib 01,Reach-1,2
Up Type=0
Dn Type=3
Dn Slope=0.005
Boundary for River Rch & Prof#=UCFB HW Trib 01,Reach-1,3
Up Type=0
Dn Type=3
Dn Slope=0.005
Boundary for River Rch & Prof#=UCFB HW Trib 01,Reach-1,4
Up Type=0
Dn Type=3
Dn Slope=0.005
Boundary for River Rch & Prof#=UCFB HW Trib 01,Reach-1,5
Up Type=0
Dn Type=3
Dn Slope=0.005
Boundary for River Rch & Prof#=UCFB HW Trib 01,Reach-1,6
Up Type=0
Dn Type=3
Dn Slope=0.005
Boundary for River Rch & Prof#=UCFB HW Trib 01,Reach-1,7
Up Type=0
Dn Type=3
Dn Slope=0.005

--- UCFB HW Trib 01.g01 (geometry) ---

Geom Title=Existing Conditions

River Reach=UCFB HW Trib 01,Reach-1
Reach XY= 30
      1392405.00      6971288.00      1392310.48      6971390.02
      1392301.16      6971486.41      1392208.83      6971639.58
      1392107.17      6971993.98      1392106.09      6972077.46
      1392260.85      6972390.29      1392349.46      6972485.58
      1392360.52      6972590.43      1392496.86      6972731.94
      1392651.17      6973039.58      1392657.36      6973132.02
      1392703.78      6973198.50      1392707.26      6973382.06
      1392753.78      6973448.51      1392757.24      6973632.07
      1392813.14      6973744.06      1392948.95      6973879.84
      1393414.33      6974149.06      1393588.29      6974322.68
      1393710.84      6974640.29      1393796.84      6974731.95
      1393901.14      6974939.66      1393908.16      6975029.66
      1393971.45      6975054.74      1394248.83      6975330.24
      1394353.41      6975334.33      1394710.93      6975140.24
      1394894.57      6975139.05      1395305.00      6975538.00

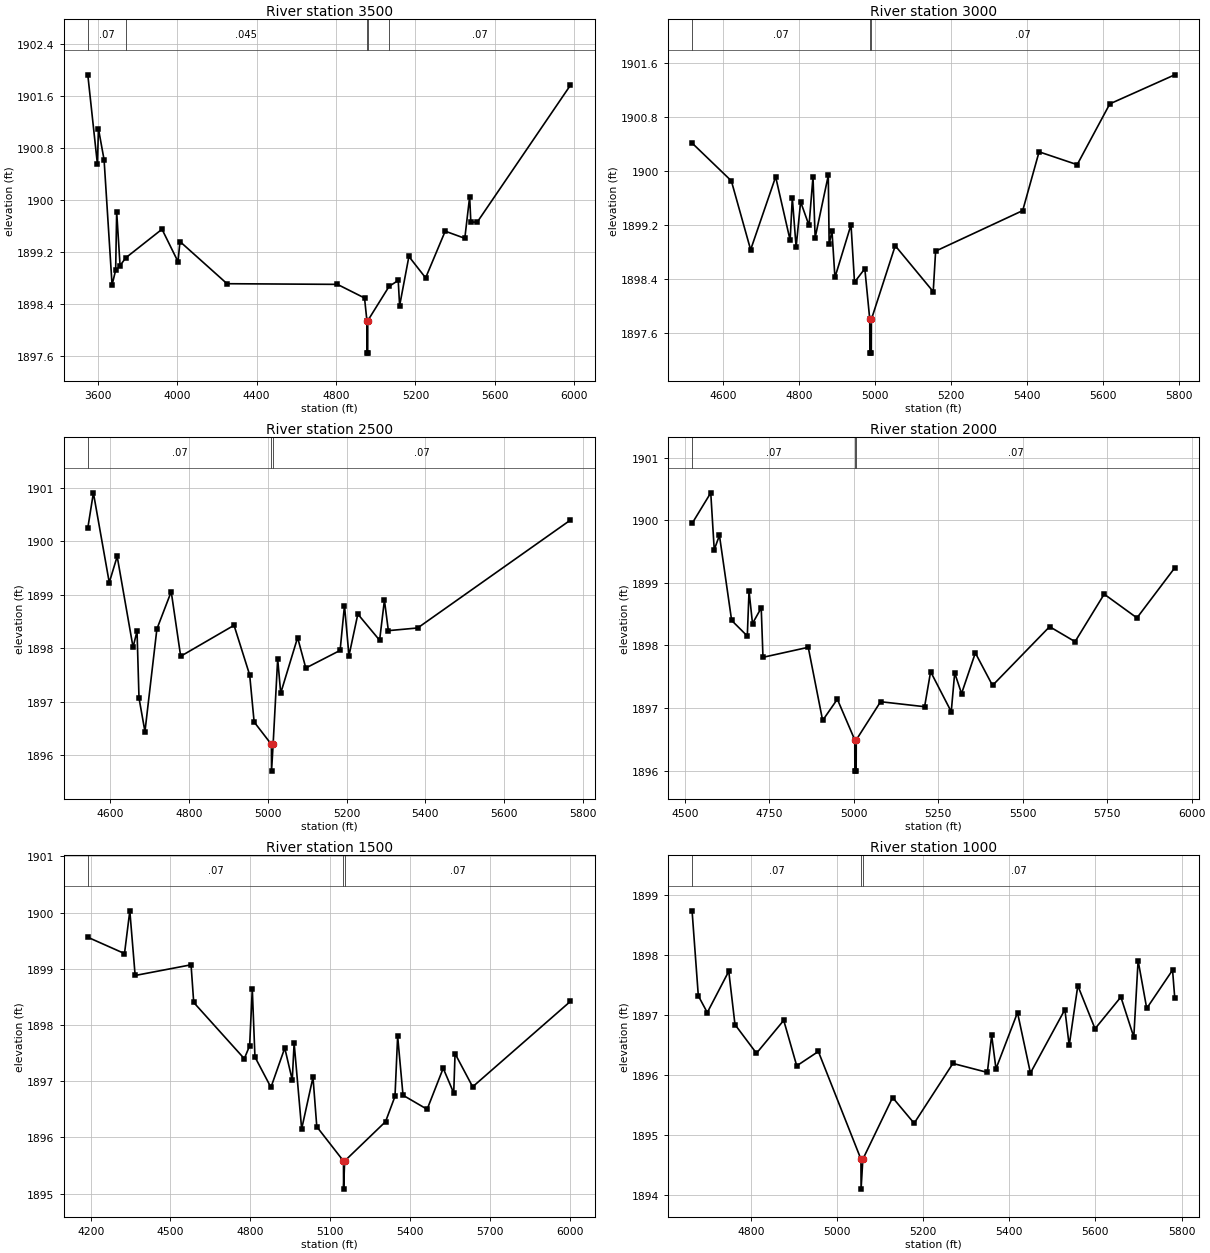
Type RM Length L Ch R = 1,3500,500,500,500
BEGIN DESCRIPTION:
UCFB HW Trib 01 7.0
END DESCRIPTION:
XS GIS Cut Line= 5
      1391443.47      6973727.60      1392762.45      6973870.13
      1392849.60      6973782.99      1392948.07      6973685.93
      1393731.43      6973376.02
#Sta/Elev= 30
  3550.1 1901.93  3598.6 1900.55  3603.7 1901.10  3632.1 1900.62  3672.3 1898.69
  3690.4 1898.92  3695.5 1899.82  3712.6 1898.99  3741.6 1899.11  3923.8 1899.55
  4004.3 1899.05  4014.3 1899.36  4251.3 1898.71  4807.1 1898.70  4943.7 1898.49
  4955.7 1898.14  4956.0 1897.64  4959.7 1897.64  4960.0 1898.14  5067.7 1898.67
  5113.4 1898.76  5120.4 1898.37  5167.2 1899.13  5251.4 1898.80  5350.0 1899.52
  5448.7 1899.41  5473.1 1900.05  5479.1 1899.66  5511.4 1899.66  5980.7 1901.77
#Mann=5,-1,0
  3550.1    0.07       0  3741.6   0.045       0  4955.7   0.045       0
  4960.0   0.045       0  5067.7    0.07       0
Bank Sta=4955.7,4960
Exp/Cntr=0.3,0.1

Type RM Length L Ch R = 1,3000,500,500,500
BEGIN DESCRIPTION:
UCFB HW Trib 01 6.0
END DESCRIPTION:
XS GIS Cut Line= 5
      1392874.06      6974315.82      1393189.53      6974146.17
      1393255.75      6974043.11      1393333.24      6973940.16
      1393729.98      6973413.03
#Sta/Elev= 30
  4519.3 1900.41  4622.6 1899.85  4673.3 1898.83  4739.1 1899.91  4777.2 1898.97
  4782.9 1899.60  4792.9 1898.87  4804.8 1899.54  4826.9 1899.19  4837.3 1899.91
  4843.0 1899.01  4877.5 1899.93  4879.8 1898.91  4887.2 1899.11  4895.0 1898.42
  4937.3 1899.20  4946.5 1898.35  4973.6 1898.55  4986.6 1897.80  4986.9 1897.30
  4990.6 1897.30  4990.9 1897.80  5053.6 1898.89  5153.5 1898.21  5159.8 1898.81
  5388.8 1899.41  5431.9 1900.28  5532.1 1900.09  5617.9 1900.99  5788.6 1901.42
#Mann=3,-1,0
  4519.3    0.07       0  4986.6    0.07       0  4990.9    0.07       0
Bank Sta=4986.6,4990.9
Exp/Cntr=0.3,0.1

Type RM Length L Ch R = 1,2500,500,500,500
BEGIN DESCRIPTION:
UCFB HW Trib 01 5.0
END DESCRIPTION:
XS GIS Cut Line= 5
      1393160.93      6974458.67      1393525.47      6974414.40
      1393606.45      6974375.19      1393689.53      6974305.03
      1393980.01      6973712.99
#Sta/Elev= 30
  4542.8 1900.25  4557.0 1900.91  4597.3 1899.23  4617.4 1899.72  4657.7 1898.02
  4667.8 1898.32  4672.8 1897.07  4687.9 1896.44  4718.2 1898.36  4754.6 1899.06
  4778.6 1897.85  4914.1 1898.43  4953.8 1897.50  4965.1 1896.62  5009.0 1896.20
  5009.3 1895.70  5013.3 1896.20  5024.9 1897.80  5032.6 1897.16  5075.5 1898.20
  5096.3 1897.63  5183.4 1897.96  5194.5 1898.80  5205.9 1897.86  5228.4 1898.64
  5283.7 1898.15  5295.9 1898.90  5305.9 1898.33  5380.3 1898.38  5768.2 1900.40
#Mann=3,-1,0
  4542.8    0.07       0  5009.0    0.07       0  5013.3    0.07       0
Bank Sta=5009,5013.3
Exp/Cntr=0.3,0.1

Type RM Length L Ch R = 1,2000,500,500,500
BEGIN DESCRIPTION:
UCFB HW Trib 01 4.0
END DESCRIPTION:
XS GIS Cut Line= 5
      1393361.40      6974763.36      1393705.16      6974849.30
      1393820.68      6974802.98      1393921.31      6974765.97
      1394079.19      6973938.21
#Sta/Elev= 30
  4521.2 1899.95  4576.5 1900.44  4586.8 1899.53  4602.2 1899.76  4638.3 1898.40
  4684.7 1898.15  4689.8 1898.87  4700.1 1898.35  4725.9 1898.60  4731.1 1897.81
  4865.1 1897.97  4907.7 1896.80  4951.2 1897.14  5002.8 1896.49  5003.1 1895.99
  5006.9 1895.99  5007.2 1896.49  5079.2 1897.10  5209.5 1897.02  5227.3 1897.58
  5288.4 1896.94  5298.6 1897.56  5318.9 1897.23  5359.7 1897.88  5410.6 1897.36
  5579.6 1898.30  5654.9 1898.06  5741.1 1898.82  5838.1 1898.44  5949.9 1899.24
#Mann=3,-1,0
  4521.2    0.07       0  5002.8    0.07       0  5007.2    0.07       0
Bank Sta=5002.8,5007.2
Exp/Cntr=0.3,0.1

Type RM Length L Ch R = 1,1500,500,500,500
BEGIN DESCRIPTION:
UCFB HW Trib 01 3.0
END DESCRIPTION:
XS GIS Cut Line= 5
      1393317.14      6975278.99      1394012.45      6975258.15
      1394095.61      6975178.62      1394179.12      6975083.67
      1394280.00      6974213.04
#Sta/Elev= 30
  4189.3 1899.56  4327.2 1899.27  4347.2 1900.03  4367.2 1898.88  4577.3 1899.07
  4587.3 1898.40  4777.4 1897.40  4797.4 1897.63  4807.4 1898.64  4817.4 1897.43
  4877.5 1896.89  4929.4 1897.59  4957.6 1897.02  4964.6 1897.68  4992.9 1896.15
  5035.5 1897.07  5049.8 1896.19  5150.1 1895.58  5150.4 1895.08  5154.5 1895.58
  5308.1 1896.28  5343.6 1896.73  5353.6 1897.80  5373.8 1896.75  5464.4 1896.50
  5524.8 1897.23  5564.3 1896.79  5569.3 1897.49  5635.5 1896.90  6002.9 1898.42
#Mann=3,-1,0
  4189.3    0.07       0  5150.1    0.07       0  5154.5    0.07       0
Bank Sta=5150.1,5154.5
Exp/Cntr=0.3,0.1

Type RM Length L Ch R = 1,1000,500,500,500
BEGIN DESCRIPTION:
UCFB HW Trib 01 2.0
END DESCRIPTION:
XS GIS Cut Line= 5
      1394379.97      6975513.02      1394517.66      6975406.59
      1394501.26      6975245.05      1394475.99      6975099.30
      1394480.00      6974463.03
#Sta/Elev= 30
  4663.6 1898.74  4678.1 1897.32  4698.9 1897.04  4748.8 1897.73  4763.2 1896.84
  4813.1 1896.36  4876.4 1896.91  4906.6 1896.15  4956.8 1896.39  5055.7 1894.59
  5056.0 1894.09  5060.1 1894.59  5129.2 1895.62  5179.2 1895.19  5269.2 1896.19
  5349.2 1896.04  5359.2 1896.66  5369.2 1896.10  5419.2 1897.04  5449.2 1896.03
  5529.2 1897.09  5539.2 1896.49  5559.2 1897.49  5599.2 1896.77  5659.2 1897.30
  5689.2 1896.63  5699.2 1897.91  5719.2 1897.11  5779.2 1897.75  5784.2 1897.29
#Mann=3,-1,0
  4663.6    0.07       0  5055.7    0.07       0  5060.1    0.07       0
Bank Sta=5055.7,5060.1
Exp/Cntr=0.3,0.1

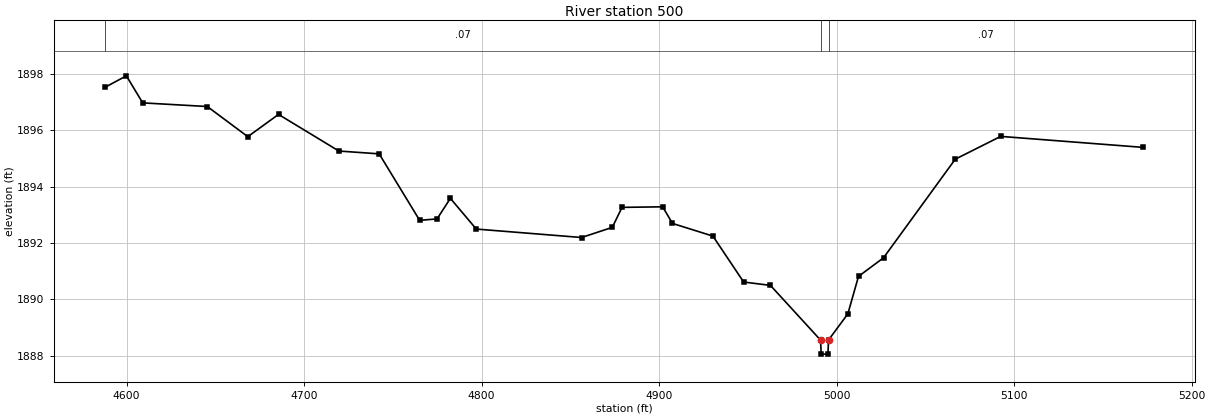
Type RM Length L Ch R = 1,500,0,0,0
BEGIN DESCRIPTION:
UCFB HW Trib 01 1.0
END DESCRIPTION:
XS GIS Cut Line= 3
      1394776.55      6975557.05      1394951.67      6975184.23
      1394930.00      6975012.99
#Sta/Elev= 30
  4588.1 1897.54  4599.9 1897.94  4609.1 1896.98  4645.5 1896.85  4668.3 1895.78
  4685.6 1896.57  4719.6 1895.27  4742.3 1895.17  4765.1 1892.81  4774.9 1892.86
  4782.4 1893.59  4797.0 1892.50  4856.3 1892.20  4873.6 1892.56  4879.1 1893.27
  4902.0 1893.29  4907.5 1892.70  4930.3 1892.25  4947.6 1890.62  4962.7 1890.50
  4990.9 1888.56  4991.3 1888.06  4995.1 1888.06  4995.4 1888.56  5006.3 1889.49
  5012.3 1890.82  5026.4 1891.48  5066.8 1894.98  5092.4 1895.79  5172.6 1895.40
#Mann=3,-1,0
  4588.1    0.07       0  4990.9    0.07       0  4995.4    0.07       0
Bank Sta=4990.9,4995.4
Exp/Cntr=0.3,0.1

Chan Stop Cuts=-1