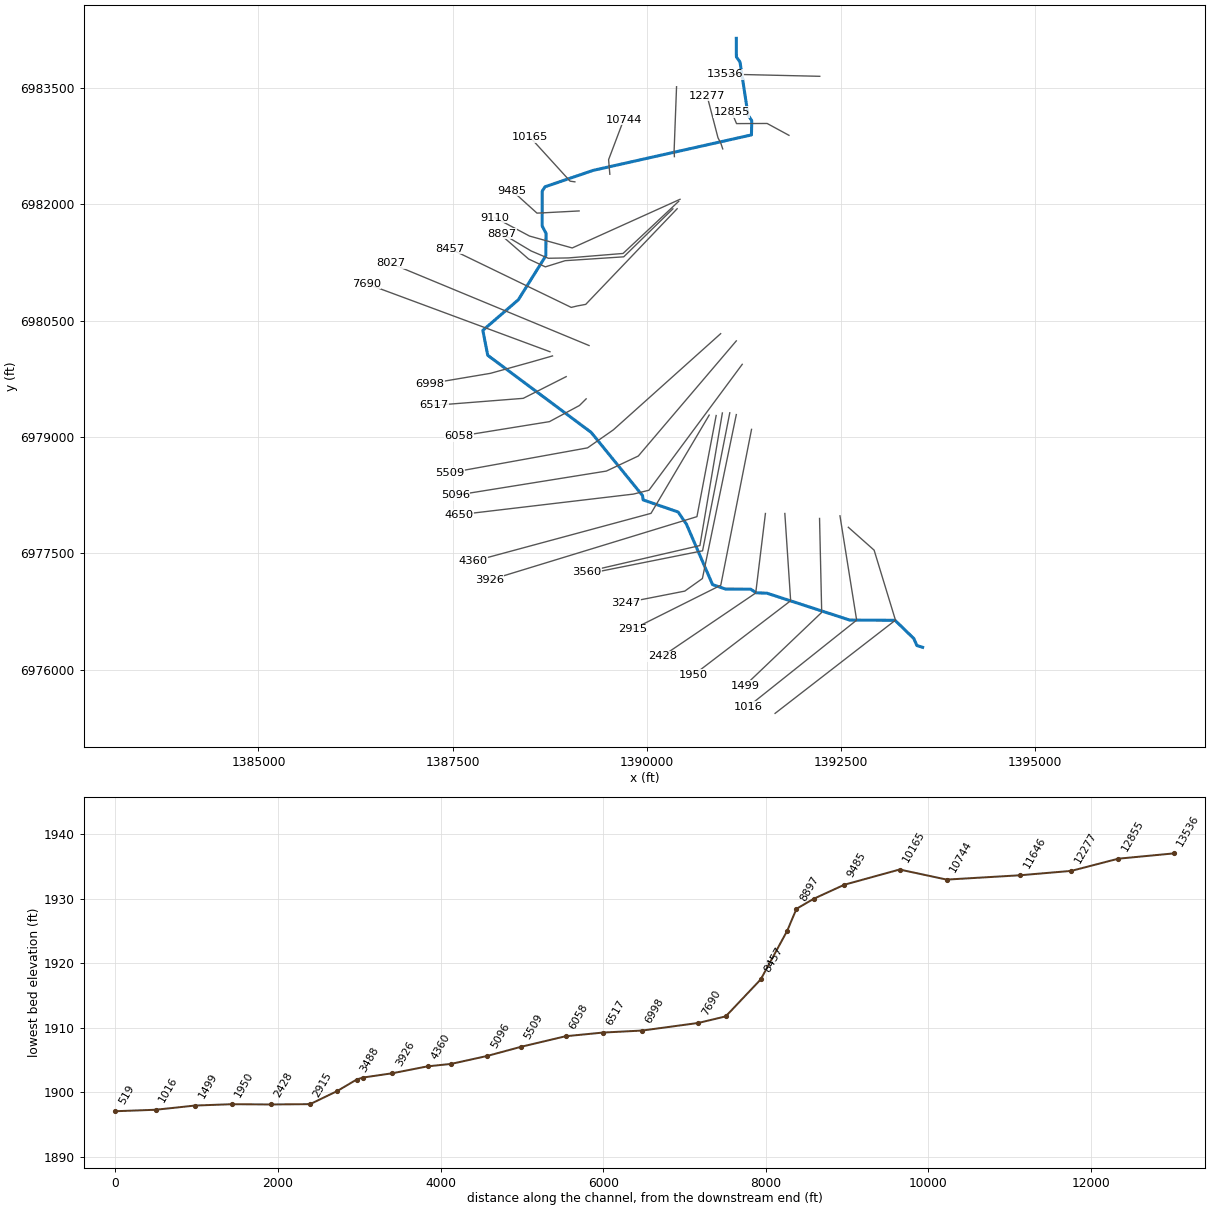
--- UCFB HW Trib 02.prj (project) ---

Proj Title=UCFB HW Trib 02 Base Level Engineering
Current Plan=p01
Default Exp/Contr=0.3,0.1
English Units
Geom File=g01
Flow File=f01
Plan File=p01
BEGIN DESCRIPTION:
UCFB HW Trib 02
END DESCRIPTION:

--- UCFB HW Trib 02.p01 (plan) ---

Plan Title=Multiple Run
Short Identifier=Multiple
Geom File=g01
Flow File=f01
Subcritical Flow
K Sum by GR= 0
Std Step Tol= 0.01
Critical Tol= 0.01
Num of Std Step Trials= 20
Max Error Tol= 0.3
Flow Tol Ratio= 0.001
Split Flow NTrial= 30
Split Flow Tol= 0.02
Split Flow Ratio= 0.02
Log Output Level= 0
Friction Slope Method= 1
Unsteady Friction Slope Method= 2
Unsteady Bridges Friction Slope Method= 1
Parabolic Critical Depth
Global Vel Dist=  1 , 1 , 1
Global Log Level= 0
CheckData=True
Encroach Param= -1, 0, 0, 0
BEGIN DESCRIPTION:
Multiple Run
END DESCRIPTION:

--- UCFB HW Trib 02.f01 (steady flow) ---

Flow Title=Multiple
Number of Profiles=7
Profile Names=10-year,25-year,50-year,1pct_min,100-year,1pct_plu,500-year
River Rch & RM= UCFB HW Trib 02,Reach-1,13536
     304     427     528     325     648    1292     987
River Rch & RM= UCFB HW Trib 02,Reach-1,8783
     352     499     621     384     766    1528    1180
River Rch & RM= UCFB HW Trib 02,Reach-1,4360
     486     699     880     549    1096    2187    1724
Boundary for River Rch & Prof#=UCFB HW Trib 02,Reach-1,1
Up Type=0
Dn Type=3
Dn Slope=0.005
Boundary for River Rch & Prof#=UCFB HW Trib 02,Reach-1,2
Up Type=0
Dn Type=3
Dn Slope=0.005
Boundary for River Rch & Prof#=UCFB HW Trib 02,Reach-1,3
Up Type=0
Dn Type=3
Dn Slope=0.005
Boundary for River Rch & Prof#=UCFB HW Trib 02,Reach-1,4
Up Type=0
Dn Type=3
Dn Slope=0.005
Boundary for River Rch & Prof#=UCFB HW Trib 02,Reach-1,5
Up Type=0
Dn Type=3
Dn Slope=0.005
Boundary for River Rch & Prof#=UCFB HW Trib 02,Reach-1,6
Up Type=0
Dn Type=3
Dn Slope=0.005
Boundary for River Rch & Prof#=UCFB HW Trib 02,Reach-1,7
Up Type=0
Dn Type=3
Dn Slope=0.005

--- UCFB HW Trib 02.g01 (geometry) ---

Geom Title=Existing Conditions

River Reach=UCFB HW Trib 02,Reach-1
Reach XY= 30
      1391155.00      6984138.00      1391156.22      6983898.50
      1391202.74      6983832.06      1391306.22      6983148.51
      1391353.78      6983077.49      1391350.00      6982893.01
      1389310.94      6982435.73      1388691.27      6982224.77
      1388654.91      6982168.13      1388654.64      6981717.85
      1388704.48      6981622.78      1388700.81      6981334.21
      1388346.61      6980767.32      1387890.00      6980373.63
      1387952.90      6980052.14      1389285.18      6979058.82
      1389946.76      6978244.01      1389955.00      6978188.00
      1390405.70      6978031.82      1390512.60      6977874.94
      1390848.95      6977096.14      1391015.50      6977039.22
      1391339.78      6977037.48      1391410.94      6976990.27
      1391549.06      6976985.73      1392615.50      6976639.22
      1393199.15      6976635.94      1393441.37      6976401.20
      1393481.02      6976310.82      1393555.00      6976288.00

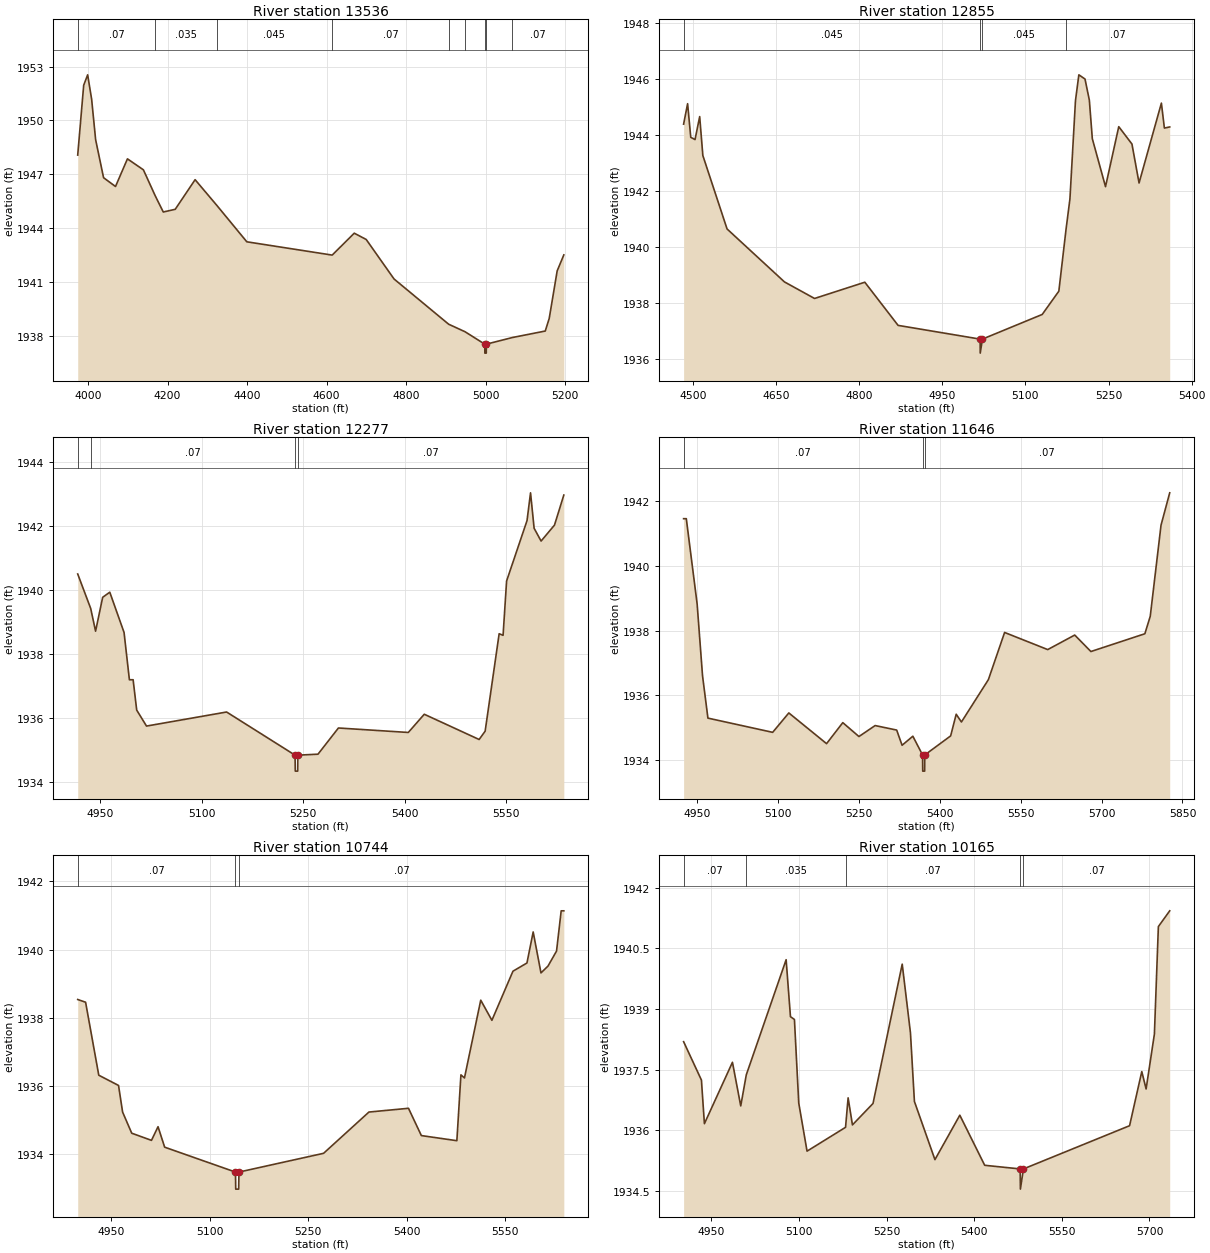
Type RM Length L Ch R = 1,13536,681,681,681
BEGIN DESCRIPTION:
UCFB HW Trib 02 17.4
END DESCRIPTION:
XS GIS Cut Line= 2
      1392230.01      6983648.57      1391008.34      6983676.88
#Sta/Elev= 30
  3974.3 1948.07  3989.3 1951.96  3999.3 1952.54  4009.3 1951.18  4019.3 1948.93
  4039.3 1946.81  4069.3 1946.32  4099.3 1947.86  4139.4 1947.25  4169.2 1945.80
  4189.4 1944.90  4219.4 1945.05  4269.4 1946.70  4323.2 1945.29  4399.4 1943.24
  4614.0 1942.50  4669.5 1943.72  4699.5 1943.37  4769.5 1941.17  4906.8 1938.65
  4948.1 1938.23  4997.6 1937.54  4997.8 1937.04  5001.3 1937.04  5001.6 1937.54
  5067.2 1937.91  5149.6 1938.27  5159.6 1938.97  5179.6 1941.62  5196.3 1942.51
#Mann=9,-1,0
  3974.3    0.07       0  4169.2   0.035       0  4323.2   0.045       0
  4614.0    0.07       0  4906.8   0.045       0  4948.1   0.035       0
  4997.6   0.035       0  5001.6   0.035       0  5067.2    0.07       0
Bank Sta=4997.6,5001.6
Exp/Cntr=0.3,0.1

Type RM Length L Ch R = 1,12855,578,578,578
BEGIN DESCRIPTION:
UCFB HW Trib 02 17.2
END DESCRIPTION:
XS GIS Cut Line= 4
      1391833.11      6982887.83      1391551.85      6983040.61
      1391157.76      6983038.87      1391095.12      6983189.07
#Sta/Elev= 30
  4483.5 1944.39  4490.7 1945.12  4496.4 1943.92  4504.1 1943.84  4512.5 1944.66
  4518.2 1943.27  4561.9 1940.65  4665.5 1938.76  4719.7 1938.17  4810.4 1938.75
  4870.4 1937.21  5018.4 1936.72  5018.6 1936.22  5022.5 1936.72  5130.4 1937.60
  5160.4 1938.43  5173.4 1940.64  5180.4 1941.72  5190.4 1945.23  5196.5 1946.15
  5207.6 1946.00  5215.4 1945.25  5220.8 1943.87  5244.6 1942.16  5268.5 1944.30
  5292.3 1943.68  5305.1 1942.29  5345.4 1945.14  5350.8 1944.25  5360.4 1944.29
#Mann=4,-1,0
  4483.5   0.045       0  5018.4   0.045       0  5022.5   0.045       0
  5173.4    0.07       0
Bank Sta=5018.4,5022.5
Exp/Cntr=0.3,0.1

Type RM Length L Ch R = 1,12277,631,631,631
BEGIN DESCRIPTION:
UCFB HW Trib 02 17.0
END DESCRIPTION:
XS GIS Cut Line= 4
      1390980.00      6982713.00      1390955.00      6982788.00
      1390919.04      6982855.83      1390777.60      6983400.53
#Sta/Elev= 30
  4916.8 1940.50  4936.0 1939.42  4943.2 1938.71  4953.7 1939.77  4964.2 1939.93
  4985.3 1938.67  4993.2 1937.19  4998.7 1937.19  5004.0 1936.24  5018.5 1935.74
  5136.9 1936.18  5238.1 1934.83  5238.4 1934.33  5242.0 1934.33  5242.2 1934.83
  5272.0 1934.86  5302.2 1935.68  5405.5 1935.54  5429.1 1936.11  5510.2 1935.32
  5519.1 1935.58  5539.8 1938.63  5545.6 1938.58  5550.8 1940.28  5581.0 1942.17
  5586.2 1943.04  5591.5 1941.93  5601.8 1941.53  5621.6 1942.03  5635.4 1942.97
#Mann=4,-1,0
  4916.8   0.045       0  4936.0    0.07       0  5238.1    0.07       0
  5242.2    0.07       0
Bank Sta=5238.1,5242.2
Exp/Cntr=0.3,0.1

Type RM Length L Ch R = 1,11646,902,902,902
BEGIN DESCRIPTION:
UCFB HW Trib 02 16.5
END DESCRIPTION:
XS GIS Cut Line= 3
      1390357.44      6982612.97      1390354.12      6982695.02
      1390385.19      6983514.11
#Sta/Elev= 30
  4924.5 1941.46  4929.5 1941.46  4949.6 1938.82  4959.6 1936.60  4969.6 1935.29
  5089.7 1934.85  5119.7 1935.45  5189.7 1934.50  5219.8 1935.15  5249.8 1934.72
  5279.8 1935.06  5319.8 1934.92  5329.8 1934.45  5349.8 1934.73  5367.8 1934.15
  5368.1 1933.65  5371.7 1933.65  5371.9 1934.15  5419.9 1934.74  5430.2 1935.41
  5439.9 1935.17  5489.9 1936.48  5520.0 1937.94  5600.0 1937.41  5650.1 1937.86
  5680.1 1937.35  5780.2 1937.90  5790.2 1938.44  5810.2 1941.26  5826.3 1942.26
#Mann=3,-1,0
  4924.5    0.07       0  5367.8    0.07       0  5371.9    0.07       0
Bank Sta=5367.8,5371.9
Exp/Cntr=0.3,0.1

Type RM Length L Ch R = 1,10744,579,579,579
BEGIN DESCRIPTION:
UCFB HW Trib 02 16.2
END DESCRIPTION:
XS GIS Cut Line= 3
      1389525.88      6982386.00      1389509.96      6982573.64
      1389705.01      6983090.54
#Sta/Elev= 30
  4898.6 1938.54  4910.6 1938.46  4930.7 1936.32  4960.8 1936.02  4967.0 1935.24
  4980.9 1934.62  5011.0 1934.41  5021.0 1934.81  5031.1 1934.21  5139.0 1933.48
  5139.4 1932.98  5143.9 1932.98  5144.3 1933.48  5273.3 1934.03  5342.4 1935.24
  5402.7 1935.35  5422.3 1934.55  5476.4 1934.40  5482.6 1936.33  5488.0 1936.24
  5512.8 1938.52  5529.8 1937.93  5561.9 1939.37  5583.2 1939.61  5592.7 1940.52
  5604.6 1939.32  5615.3 1939.52  5628.3 1939.96  5635.4 1941.14  5639.4 1941.14
#Mann=3,-1,0
  4898.6    0.07       0  5139.0    0.07       0  5144.3    0.07       0
Bank Sta=5139,5144.3
Exp/Cntr=0.3,0.1

Type RM Length L Ch R = 1,10165,680,680,680
BEGIN DESCRIPTION:
UCFB HW Trib 02 16.1
END DESCRIPTION:
XS GIS Cut Line= 3
      1389075.61      6982288.21      1389014.17      6982296.66
      1388496.01      6982866.33
#Sta/Elev= 30
  4902.6 1938.19  4933.1 1937.24  4938.2 1936.16  4986.2 1937.68  5000.4 1936.60
  5009.9 1937.37  5078.1 1940.22  5085.5 1938.81  5092.3 1938.74  5099.7 1936.67
  5113.9 1935.48  5179.8 1936.07  5184.2 1936.80  5191.6 1936.13  5226.8 1936.66
  5276.8 1940.11  5290.9 1938.41  5297.7 1936.71  5332.8 1935.27  5375.4 1936.37
  5418.0 1935.13  5478.7 1935.04  5479.1 1934.54  5484.3 1935.04  5666.0 1936.11
  5686.9 1937.45  5694.3 1937.02  5708.5 1938.38  5715.3 1941.04  5734.7 1941.43
#Mann=5,-1,0
  4902.6    0.07       0  5009.9   0.035       0  5179.8    0.07       0
  5478.7    0.07       0  5484.3    0.07       0
Bank Sta=5478.7,5484.3
Exp/Cntr=0.3,0.1

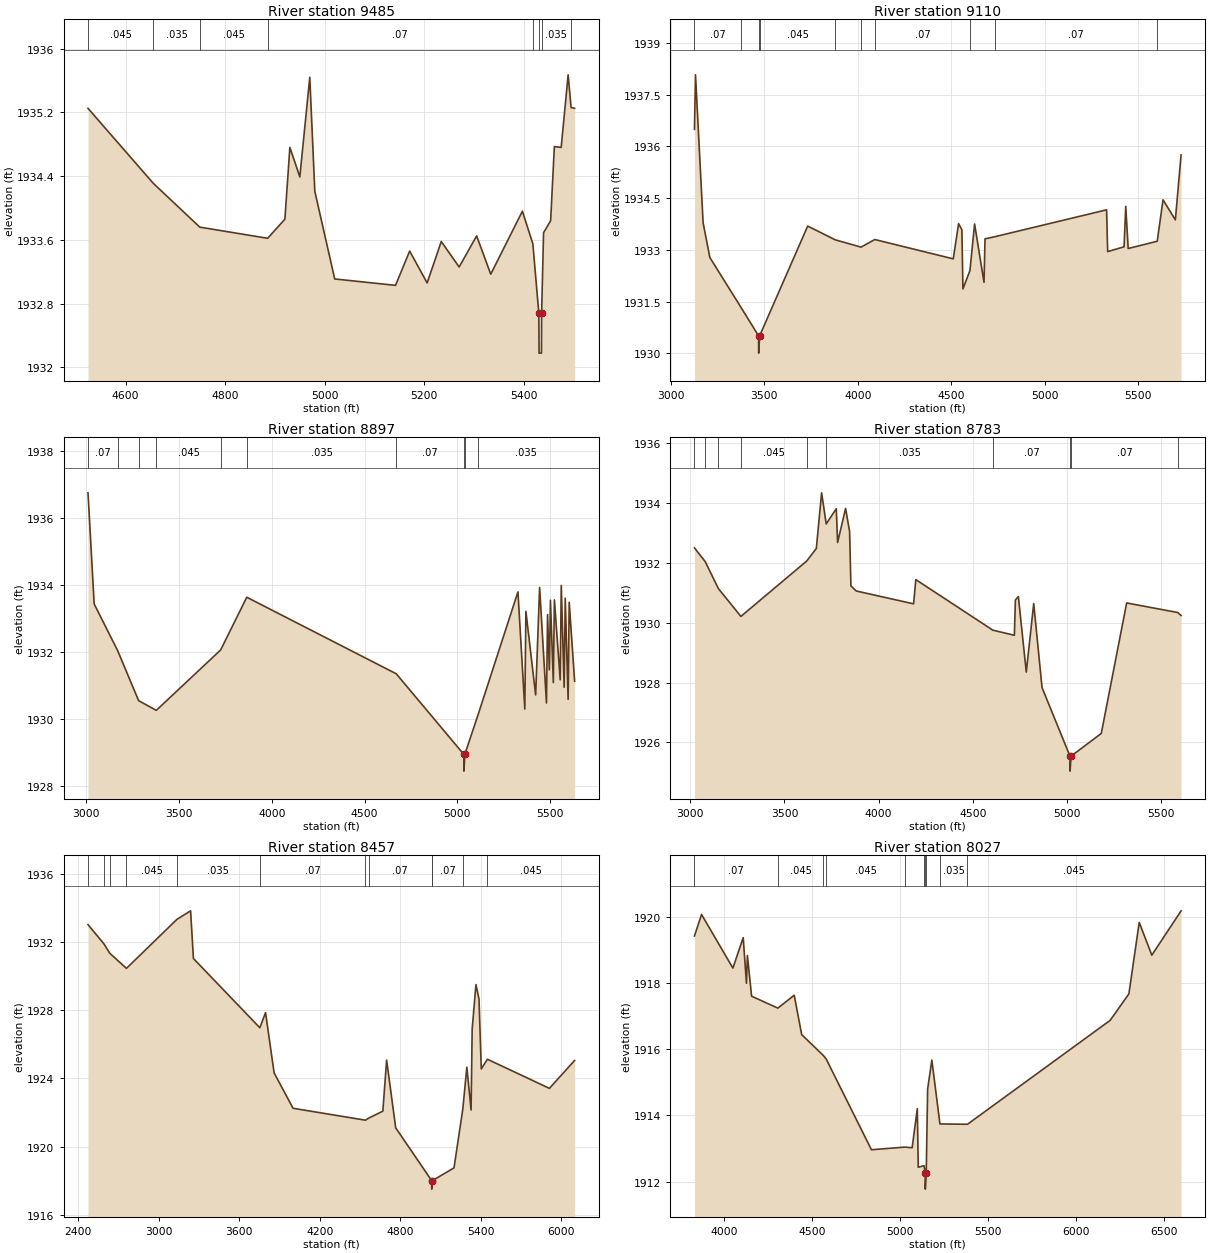
Type RM Length L Ch R = 1,9485,375,375,375
BEGIN DESCRIPTION:
UCFB HW Trib 02 16.0
END DESCRIPTION:
XS GIS Cut Line= 4
      1389130.02      6981913.00      1388655.00      6981888.00
      1388587.51      6981884.85      1388264.94      6982175.89
#Sta/Elev= 30
  4524.3 1935.25  4655.4 1934.31  4748.9 1933.76  4885.3 1933.62  4919.9 1933.86
  4929.9 1934.76  4949.9 1934.39  4969.9 1935.64  4980.0 1934.21  5020.0 1933.11
  5142.2 1933.03  5170.6 1933.46  5205.7 1933.06  5234.1 1933.58  5270.0 1933.26
  5305.1 1933.65  5333.5 1933.17  5397.1 1933.96  5418.1 1933.55  5430.1 1932.68
  5430.6 1932.18  5435.3 1932.18  5435.7 1932.68  5439.6 1933.69  5453.8 1933.84
  5461.3 1934.77  5475.0 1934.76  5489.0 1935.67  5494.9 1935.26  5502.0 1935.25
#Mann=8,-1,0
  4524.3   0.045       0  4655.4   0.035       0  4748.9   0.045       0
  4885.3    0.07       0  5418.1   0.035       0  5430.1    0.07       0
  5435.7   0.035       0  5494.9    0.07       0
Bank Sta=5430.1,5435.7
Exp/Cntr=0.3,0.1

Type RM Length L Ch R = 1,9110,213,213,213
BEGIN DESCRIPTION:
UCFB HW Trib 02 15.8
END DESCRIPTION:
XS GIS Cut Line= 4
      1390430.03      6982063.01      1389041.33      6981435.77
      1388491.62      6981589.17      1388043.89      6981827.90
#Sta/Elev= 30
  3127.1 1936.49  3132.6 1938.07  3173.4 1933.78  3209.4 1932.78  3377.6 1931.32
  3470.0 1930.51  3470.4 1930.01  3475.6 1930.51  3732.5 1933.69  3880.5 1933.29
  4017.9 1933.08  4091.5 1933.30  4510.8 1932.74  4539.4 1933.76  4557.0 1933.58
  4562.5 1931.87  4600.0 1932.40  4624.9 1933.75  4675.4 1932.06  4680.6 1933.32
  4732.1 1933.38  5330.7 1934.16  5336.4 1932.95  5424.2 1933.09  5433.1 1934.26
  5446.2 1933.04  5601.4 1933.25  5632.5 1934.45  5698.4 1933.87  5729.0 1935.75
#Mann=10,-1,0
  3127.1    0.07       0  3377.6   0.045       0  3470.0    0.07       0
  3475.6   0.045       0  3880.5    0.07       0  4017.9   0.045       0
  4091.5    0.07       0  4600.0   0.035       0  4732.1    0.07       0
  5601.4   0.035       0
Bank Sta=3470,3475.6
Exp/Cntr=0.3,0.1

Type RM Length L Ch R = 1,8897,114,114,114
BEGIN DESCRIPTION:
UCFB HW Trib 02 15.7
END DESCRIPTION:
XS GIS Cut Line= 6
      1390412.91      6982037.04      1389696.09      6981364.92
      1388990.55      6981307.34      1388733.39      6981303.00
      1388511.19      6981397.47      1388138.47      6981620.09
#Sta/Elev= 30
  3009.0 1936.74  3042.3 1933.43  3168.9 1932.04  3281.9 1930.55  3377.2 1930.26
  3724.2 1932.06  3865.0 1933.63  4670.8 1931.35  5035.1 1928.95  5035.6 1928.45
  5040.8 1928.95  5111.4 1930.12  5327.0 1933.79  5364.0 1930.30  5369.8 1933.21
  5422.4 1930.72  5443.8 1933.92  5480.7 1930.48  5486.6 1933.11  5496.3 1931.47
  5502.1 1933.54  5517.7 1931.09  5523.5 1933.55  5554.7 1931.17  5560.5 1933.98
  5576.1 1930.95  5581.9 1933.60  5597.5 1930.59  5603.3 1933.48  5632.5 1931.13
#Mann=10,-1,0
  3009.0    0.07       0  3168.9   0.045       0  3281.9    0.07       0
  3377.2   0.045       0  3724.2    0.07       0  3865.0   0.035       0
  4670.8    0.07       0  5035.1    0.07       0  5040.8    0.07       0
  5111.4   0.035       0
Bank Sta=5035.1,5040.8
Exp/Cntr=0.3,0.1

Type RM Length L Ch R = 1,8783,326,326,326
BEGIN DESCRIPTION:
UCFB HW Trib 02 15.5
END DESCRIPTION:
XS GIS Cut Line= 6
      1390338.01      6981940.11      1389704.77      6981321.51
      1388950.63      6981271.85      1388695.37      6981192.06
      1388479.75      6981293.11      1388149.83      6981580.93
#Sta/Elev= 30
  3021.9 1932.50  3079.2 1932.04  3149.0 1931.14  3268.6 1930.21  3617.9 1932.06
  3669.1 1932.48  3697.2 1934.34  3721.6 1933.30  3775.1 1933.81  3782.1 1932.68
  3824.5 1933.82  3845.8 1933.05  3852.8 1931.23  3881.1 1931.06  4185.7 1930.63
  4197.5 1931.44  4606.7 1929.75  4721.0 1929.58  4726.3 1930.76  4742.2 1930.87
  4784.1 1928.35  4823.7 1930.64  4867.9 1927.83  5016.3 1925.54  5016.8 1925.04
  5022.0 1925.54  5182.5 1926.30  5317.3 1930.66  5588.6 1930.34  5606.3 1930.24
#Mann=10,-1,0
  3021.9    0.07       0  3079.2   0.045       0  3149.0    0.07       0
  3268.6   0.045       0  3617.9    0.07       0  3721.6   0.035       0
  4606.7    0.07       0  5016.3    0.07       0  5022.0    0.07       0
  5588.6   0.035       0
Bank Sta=5016.3,5022
Exp/Cntr=0.3,0.1

Type RM Length L Ch R = 1,8457,430,430,430
BEGIN DESCRIPTION:
UCFB HW Trib 02 15.0
END DESCRIPTION:
XS GIS Cut Line= 5
      1390392.88      6981941.14      1389215.35      6980708.63
      1389105.00      6980688.00      1389028.72      6980669.57
      1387470.52      6981424.79
#Sta/Elev= 30
  2472.3 1933.04  2591.0 1931.91  2634.4 1931.36  2758.9 1930.47  3135.4 1933.35
  3237.0 1933.85  3258.1 1931.05  3753.1 1926.98  3795.6 1927.87  3859.5 1924.33
  4000.7 1922.25  4540.2 1921.55  4566.3 1921.68  4669.9 1922.08  4698.0 1925.08
  4765.8 1921.10  5033.8 1918.00  5034.3 1917.50  5039.6 1918.00  5200.3 1918.75
  5265.6 1922.19  5296.1 1924.66  5327.5 1922.15  5335.7 1926.91  5363.9 1929.52
  5386.5 1928.67  5403.5 1924.56  5449.4 1925.13  5911.3 1923.42  6099.2 1925.06
#Mann=12,-1,0
  2472.3    0.07       0  2591.0   0.045       0  2634.4    0.07       0
  2758.9   0.045       0  3135.4   0.035       0  3753.1    0.07       0
  4540.2   0.045       0  4566.3    0.07       0  5033.8    0.07       0
  5039.6    0.07       0  5265.6   0.035       0  5449.4   0.045       0
Bank Sta=5033.8,5039.6
Exp/Cntr=0.3,0.1

Type RM Length L Ch R = 1,8027,337,337,337
BEGIN DESCRIPTION:
UCFB HW Trib 02 14.0
END DESCRIPTION:
XS GIS Cut Line= 2
      1389258.20      6980178.08      1386705.40      6981236.18
#Sta/Elev= 30
  3834.0 1919.42  3874.2 1920.07  4052.2 1918.45  4110.8 1919.37  4129.2 1917.99
  4134.6 1918.83  4158.5 1917.60  4307.7 1917.24  4400.5 1917.63  4442.9 1916.44
  4565.6 1915.81  4581.3 1915.71  4839.0 1912.96  5028.8 1913.04  5070.2 1913.02
  5099.5 1914.20  5104.9 1912.43  5137.3 1912.48  5144.3 1912.27  5144.8 1911.77
  5150.2 1912.27  5158.1 1914.79  5182.0 1915.67  5228.0 1913.74  5384.5 1913.73
  6194.6 1916.87  6301.0 1917.67  6359.7 1919.83  6431.2 1918.84  6597.4 1920.18
#Mann=10,-1,0
  3834.0    0.07       0  4307.7   0.045       0  4565.6    0.07       0
  4581.3   0.045       0  5028.8   0.035       0  5137.3   0.045       0
  5144.3   0.045       0  5150.2   0.045       0  5228.0   0.035       0
  5384.5   0.045       0
Bank Sta=5144.3,5150.2
Exp/Cntr=0.3,0.1

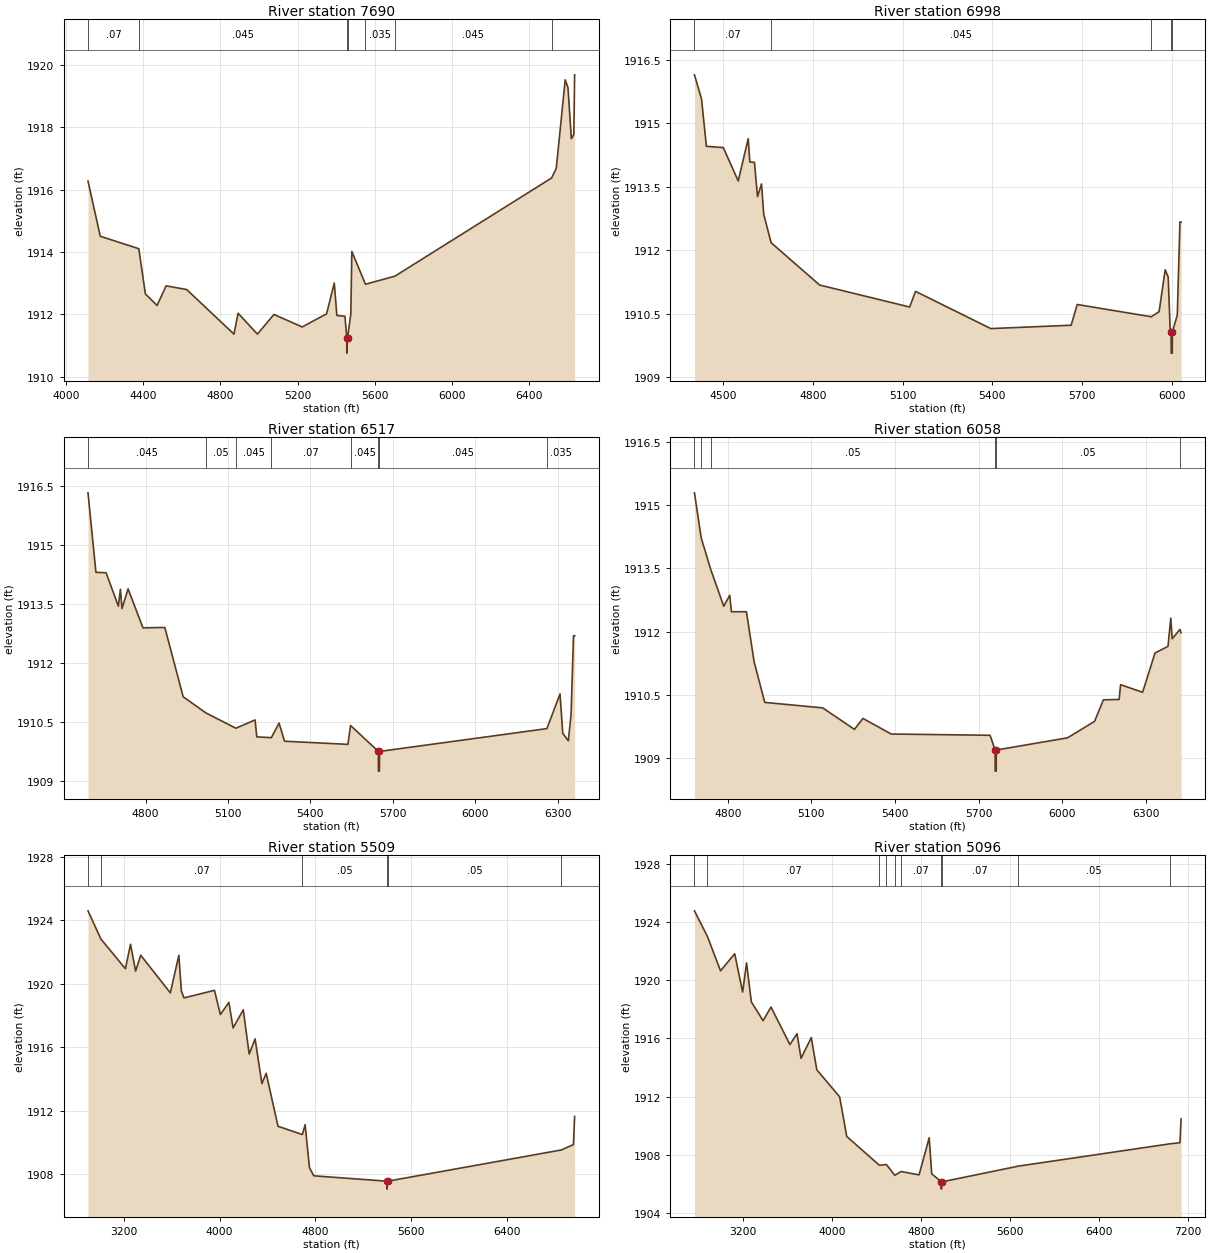
Type RM Length L Ch R = 1,7690,692,692,692
BEGIN DESCRIPTION:
UCFB HW Trib 02 13.0
END DESCRIPTION:
XS GIS Cut Line= 2
      1388754.71      6980098.00      1386389.23      6980975.51
#Sta/Elev= 30
  4113.6 1916.27  4177.3 1914.50  4377.2 1914.10  4411.1 1912.65  4471.8 1912.28
  4518.6 1912.91  4625.3 1912.79  4870.4 1911.36  4891.9 1912.03  4991.9 1911.36
  5077.7 1911.99  5224.2 1911.59  5350.5 1912.01  5390.5 1913.00  5403.9 1911.96
  5445.9 1911.93  5455.2 1911.25  5455.4 1910.75  5459.2 1911.25  5476.3 1912.00
  5481.6 1914.01  5552.2 1912.96  5705.1 1913.22  6517.3 1916.37  6541.5 1916.68
  6587.8 1919.52  6602.2 1919.27  6619.8 1917.63  6632.6 1917.77  6636.6 1919.68
#Mann=7,-1,0
  4113.6    0.07       0  4377.2   0.045       0  5455.2   0.045       0
  5459.2   0.045       0  5552.2   0.035       0  5705.1   0.045       0
  6517.3   0.035       0
Bank Sta=5455.2,5459.2
Exp/Cntr=0.3,0.1

Type RM Length L Ch R = 1,6998,481,481,481
BEGIN DESCRIPTION:
UCFB HW Trib 02 12.0
END DESCRIPTION:
XS GIS Cut Line= 4
      1388787.72      6980044.15      1388503.90      6979962.79
      1387987.41      6979819.56      1387202.52      6979687.24
#Sta/Elev= 30
  4403.9 1916.15  4427.5 1915.58  4443.8 1914.46  4500.4 1914.43  4550.2 1913.64
  4583.6 1914.64  4589.1 1914.09  4604.4 1914.08  4614.8 1913.27  4628.1 1913.57
  4635.6 1912.85  4660.3 1912.18  4822.5 1911.18  5123.5 1910.66  5143.2 1911.03
  5394.8 1910.15  5663.5 1910.23  5683.8 1910.72  5931.3 1910.43  5957.6 1910.55
  5977.9 1911.54  5988.0 1911.37  5994.8 1910.10  5997.9 1910.07  5998.1 1909.57
  6001.6 1909.57  6001.9 1910.07  6018.4 1910.47  6027.3 1912.67  6031.1 1912.67
#Mann=5,-1,0
  4403.9    0.07       0  4660.3   0.045       0  5931.3   0.035       0
  5997.9   0.045       0  6001.9   0.035       0
Bank Sta=5997.9,6001.9
Exp/Cntr=0.3,0.1

Type RM Length L Ch R = 1,6517,459,459,459
BEGIN DESCRIPTION:
UCFB HW Trib 02 11.5
END DESCRIPTION:
XS GIS Cut Line= 3
      1388963.69      6979777.14      1388410.40      6979497.33
      1387262.08      6979406.83
#Sta/Elev= 30
  4590.4 1916.33  4619.3 1914.31  4656.2 1914.30  4701.0 1913.45  4708.5 1913.88
  4714.1 1913.39  4736.4 1913.89  4790.6 1912.90  4870.1 1912.91  4936.9 1911.15
  5019.4 1910.74  5128.8 1910.35  5198.8 1910.56  5205.0 1910.13  5258.0 1910.11
  5286.1 1910.48  5306.1 1910.02  5536.8 1909.94  5546.4 1910.42  5647.8 1909.76
  5648.0 1909.26  5651.5 1909.26  5651.8 1909.76  6261.3 1910.34  6309.2 1911.22
  6319.2 1910.22  6339.3 1910.03  6349.3 1910.69  6358.3 1912.70  6362.3 1912.70
#Mann=8,-1,0
  4590.4   0.045       0  5019.4    0.05       0  5128.8   0.045       0
  5258.0    0.07       0  5546.4   0.045       0  5647.8   0.045       0
  5651.8   0.045       0  6261.3   0.035       0
Bank Sta=5647.8,5651.8
Exp/Cntr=0.3,0.1

Type RM Length L Ch R = 1,6058,549,549,549
BEGIN DESCRIPTION:
UCFB HW Trib 02 11.0
END DESCRIPTION:
XS GIS Cut Line= 4
      1389220.85      6979490.77      1389134.92      6979405.21
      1388747.75      6979196.92      1387578.74      6979007.89
#Sta/Elev= 30
  4680.7 1915.29  4704.9 1914.22  4739.7 1913.46  4785.8 1912.60  4807.1 1912.86
  4813.2 1912.47  4867.1 1912.47  4894.7 1911.28  4932.9 1910.32  5140.6 1910.19
  5254.5 1909.68  5284.9 1909.94  5386.2 1909.57  5740.8 1909.54  5759.0 1909.19
  5759.3 1908.69  5762.8 1908.69  5763.0 1909.19  6018.6 1909.48  6115.6 1909.87
  6147.1 1910.38  6203.7 1910.39  6208.8 1910.74  6287.8 1910.56  6332.2 1911.49
  6378.9 1911.65  6388.9 1912.32  6393.9 1911.83  6421.7 1912.05  6425.8 1911.97
#Mann=6,-1,0
  4680.7    0.07       0  4704.9   0.045       0  4739.7    0.05       0
  5759.0    0.05       0  5763.0    0.05       0  6421.7    0.07       0
Bank Sta=5759,5763
Exp/Cntr=0.3,0.1

Type RM Length L Ch R = 1,5509,413,413,413
BEGIN DESCRIPTION:
UCFB HW Trib 02 10.5
END DESCRIPTION:
XS GIS Cut Line= 4
      1390953.45      6980330.95      1389571.12      6979091.08
      1389238.73      6978858.94      1387465.56      6978537.54
#Sta/Elev= 30
  2901.1 1924.59  3009.3 1922.81  3213.6 1920.94  3256.2 1922.48  3298.8 1920.79
  3341.5 1921.79  3588.9 1919.42  3659.9 1921.79  3680.8 1919.55  3702.5 1919.10
  3957.4 1919.58  4006.8 1918.05  4077.8 1918.82  4112.9 1917.21  4198.2 1918.35
  4247.5 1915.56  4296.8 1916.52  4353.6 1913.70  4389.5 1914.35  4488.2 1911.01
  4691.5 1910.49  4714.7 1911.11  4750.6 1908.41  4786.7 1907.89  5398.0 1907.55
  5398.5 1907.05  5404.0 1907.55  6855.9 1909.52  6955.9 1909.86  6965.5 1911.63
#Mann=6,-1,0
  2901.1   0.035       0  3009.3    0.07       0  4691.5    0.05       0
  5398.0    0.05       0  5404.0    0.05       0  6855.9   0.035       0
Bank Sta=5398,5404
Exp/Cntr=0.3,0.1

Type RM Length L Ch R = 1,5096,446,446,446
BEGIN DESCRIPTION:
UCFB HW Trib 02 10.0
END DESCRIPTION:
XS GIS Cut Line= 4
      1391154.97      6980237.96      1389892.72      6978753.90
      1389481.25      6978559.76      1387534.92      6978246.55
#Sta/Elev= 30
  2762.1 1924.76  2879.0 1922.99  2996.5 1920.64  3123.9 1921.81  3195.3 1919.18
  3230.5 1921.18  3273.3 1918.51  3379.1 1917.21  3450.1 1918.15  3620.3 1915.57
  3684.0 1916.32  3720.3 1914.63  3812.3 1916.05  3861.9 1913.84  4067.3 1911.98
  4131.0 1909.26  4424.4 1907.28  4487.6 1907.33  4563.1 1906.59  4618.7 1906.85
  4781.2 1906.62  4872.3 1909.17  4895.1 1906.69  4981.3 1906.14  4981.8 1905.64
  4987.3 1906.14  5674.6 1907.22  7034.1 1908.75  7126.5 1908.83  7136.7 1910.46
#Mann=10,-1,0
  2762.1   0.035       0  2879.0    0.07       0  4424.4   0.035       0
  4487.6    0.07       0  4563.1   0.035       0  4618.7    0.07       0
  4981.3    0.07       0  4987.3    0.07       0  5674.6    0.05       0
  7034.1   0.035       0
Bank Sta=4981.3,4987.3
Exp/Cntr=0.3,0.1

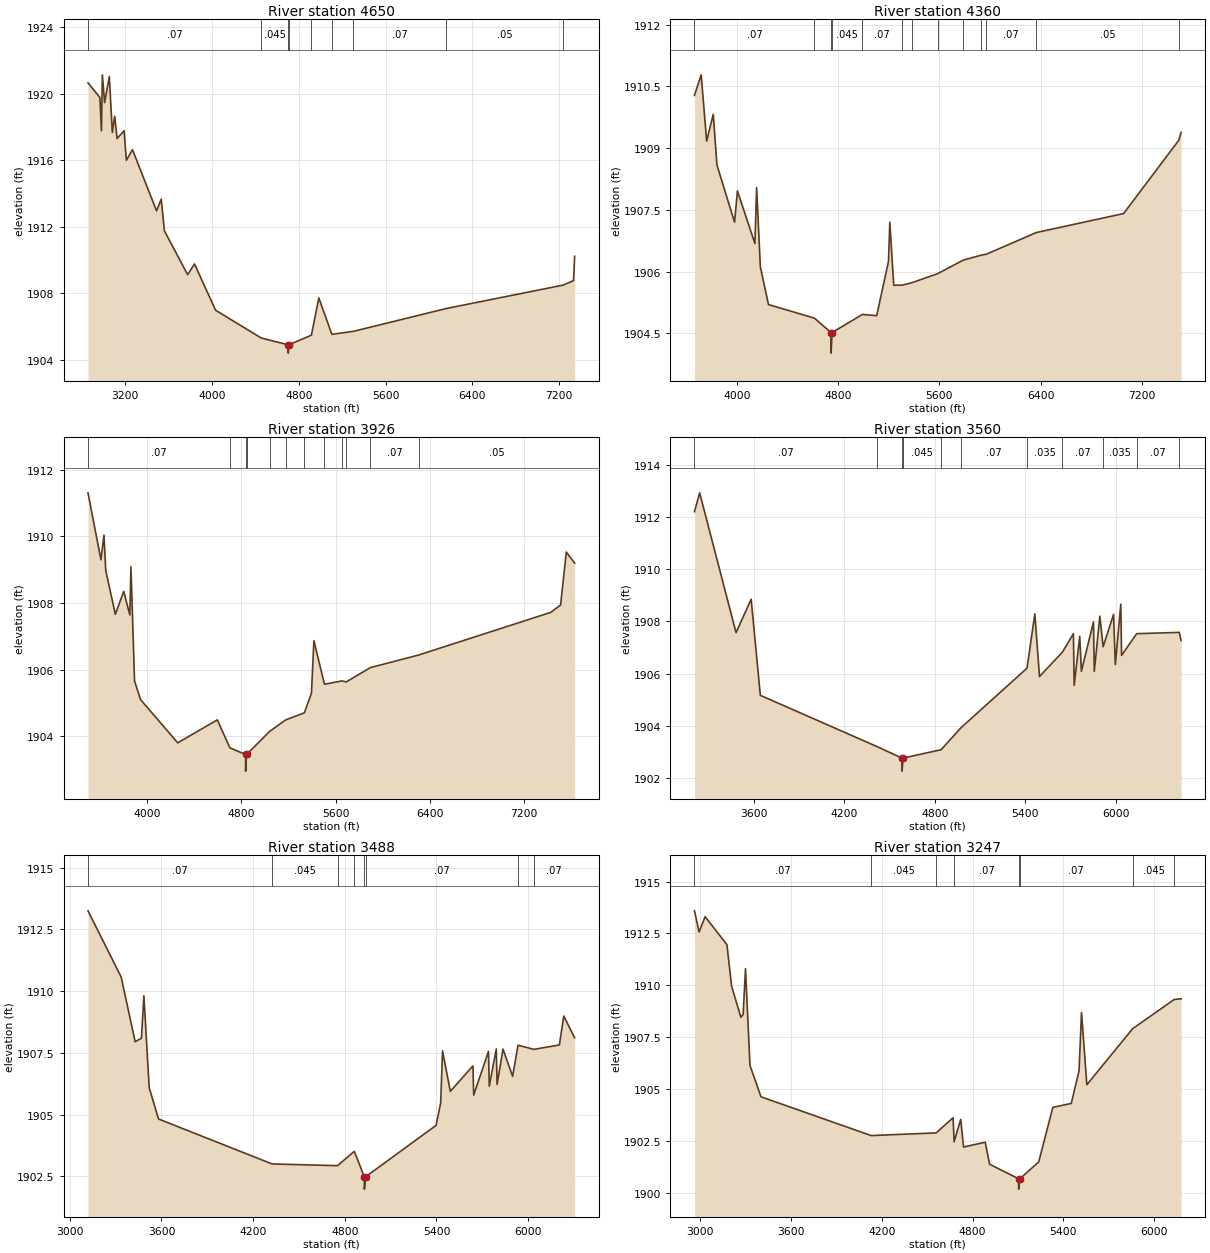
Type RM Length L Ch R = 1,4650,290,290,290
BEGIN DESCRIPTION:
UCFB HW Trib 02 9.0
END DESCRIPTION:
XS GIS Cut Line= 4
      1391231.42      6979935.92      1390030.00      6978313.00
      1389830.00      6978263.00      1387585.66      6977997.26
#Sta/Elev= 30
  2857.6 1920.65  2967.0 1919.77  2981.6 1917.77  2990.0 1921.13  3010.9 1919.46
  3054.1 1921.03  3081.8 1917.67  3103.9 1918.64  3125.7 1917.30  3190.4 1917.77
  3211.3 1915.99  3267.6 1916.63  3489.6 1912.95  3532.7 1913.66  3561.9 1911.75
  3775.7 1909.12  3839.5 1909.76  4033.6 1906.98  4454.2 1905.31  4702.7 1904.90
  4703.2 1904.40  4708.7 1904.90  4917.0 1905.48  4985.1 1907.72  5105.7 1905.53
  5304.5 1905.71  6158.6 1907.08  7238.2 1908.49  7333.6 1908.76  7343.0 1910.22
#Mann=9,-1,0
  2857.6    0.07       0  4454.2   0.045       0  4702.7    0.07       0
  4708.7   0.045       0  4917.0    0.07       0  5105.7   0.045       0
  5304.5    0.07       0  6158.6    0.05       0  7238.2   0.035       0
Bank Sta=4702.7,4708.7
Exp/Cntr=0.3,0.1

Type RM Length L Ch R = 1,4360,434,434,434
BEGIN DESCRIPTION:
UCFB HW Trib 02 9.6
END DESCRIPTION:
XS GIS Cut Line= 4
      1390805.72      6979281.04      1390235.41      6978317.56
      1390056.15      6978014.71      1387760.71      6977394.47
#Sta/Elev= 30
  3662.7 1910.28  3715.9 1910.78  3759.2 1909.17  3811.4 1909.82  3840.5 1908.59
  3980.0 1907.20  4002.5 1907.96  4141.0 1906.68  4154.3 1908.04  4183.8 1906.12
  4248.2 1905.20  4611.7 1904.87  4742.7 1904.52  4743.2 1904.02  4751.1 1904.52
  4991.5 1904.96  5104.2 1904.93  5197.6 1906.25  5207.9 1907.20  5239.0 1905.67
  5303.8 1905.67  5382.6 1905.73  5586.2 1905.95  5789.8 1906.28  5930.7 1906.40
  5969.0 1906.42  6368.0 1906.95  7057.3 1907.41  7493.7 1909.19  7512.0 1909.38
#Mann=13,-1,0
  3662.7    0.07       0  4611.7   0.045       0  4742.7    0.07       0
  4751.1   0.045       0  4991.5    0.07       0  5303.8   0.045       0
  5382.6    0.07       0  5586.2   0.045       0  5789.8    0.07       0
  5930.7    0.05       0  5969.0    0.07       0  6368.0    0.05       0
  7493.7   0.035       0
Bank Sta=4742.7,4751.1
Exp/Cntr=0.3,0.1

Type RM Length L Ch R = 1,3926,366,366,366
BEGIN DESCRIPTION:
UCFB HW Trib 02 9.5
END DESCRIPTION:
XS GIS Cut Line= 3
      1390895.40      6979275.74      1390647.90      6977972.17
      1387971.24      6977152.86
#Sta/Elev= 30
  3501.1 1911.31  3610.8 1909.30  3636.7 1910.04  3651.5 1908.98  3732.9 1907.66
  3804.2 1908.35  3855.9 1907.64  3865.2 1909.09  3895.8 1905.66  3946.7 1905.10
  4262.2 1903.80  4597.6 1904.49  4704.2 1903.65  4837.2 1903.45  4837.7 1902.95
  4845.6 1903.45  5040.4 1904.14  5178.0 1904.49  5335.5 1904.70  5395.7 1905.29
  5416.6 1906.87  5505.9 1905.56  5654.7 1905.66  5690.6 1905.63  5896.0 1906.06
  6306.7 1906.44  7425.8 1907.72  7508.2 1907.94  7556.8 1909.53  7627.2 1909.20
#Mann=12,-1,0
  3501.1    0.07       0  4704.2   0.045       0  4837.2   0.045       0
  4845.6   0.045       0  5040.4    0.07       0  5178.0   0.045       0
  5335.5    0.07       0  5505.9   0.045       0  5654.7    0.07       0
  5690.6   0.045       0  5896.0    0.07       0  6306.7    0.05       0
Bank Sta=4837.2,4845.6
Exp/Cntr=0.3,0.1

Type RM Length L Ch R = 1,3560,72,72,72
BEGIN DESCRIPTION:
UCFB HW Trib 02 7.5
END DESCRIPTION:
XS GIS Cut Line= 3
      1390975.42      6979308.86      1390686.10      6977599.72
      1389229.98      6977263.00
#Sta/Elev= 30
  3206.3 1912.20  3240.7 1912.92  3482.2 1907.57  3582.4 1908.85  3643.3 1905.17
  4417.1 1903.21  4582.3 1902.77  4582.8 1902.27  4590.7 1902.77  4842.5 1903.09
  4974.3 1903.93  5412.3 1906.21  5464.3 1908.29  5495.1 1905.89  5646.6 1906.82
  5720.0 1907.53  5725.1 1905.55  5762.0 1907.43  5773.0 1906.09  5853.3 1907.98
  5858.4 1906.09  5895.4 1908.20  5917.2 1907.03  5986.6 1908.27  5998.1 1906.35
  6034.4 1908.66  6039.5 1906.70  6139.9 1907.53  6422.2 1907.58  6434.3 1907.27
#Mann=11,-1,0
  3206.3    0.07       0  4417.1   0.045       0  4582.3    0.07       0
  4590.7   0.045       0  4842.5   0.035       0  4974.3    0.07       0
  5412.3   0.035       0  5646.6    0.07       0  5917.2   0.035       0
  6139.9    0.07       0  6422.2   0.035       0
Bank Sta=4582.3,4590.7
Exp/Cntr=0.3,0.1

Type RM Length L Ch R = 1,3488,241,241,241
BEGIN DESCRIPTION:
UCFB HW Trib 02 8.0
END DESCRIPTION:
XS GIS Cut Line= 3
      1391070.90      6979310.99      1390720.48      6977531.91
      1389375.40      6977262.80
#Sta/Elev= 30
  3119.1 1913.25  3336.2 1910.57  3427.9 1907.95  3468.7 1908.09  3485.0 1909.81
  3519.6 1906.09  3580.8 1904.82  4324.3 1903.00  4752.3 1902.93  4862.0 1903.51
  4927.6 1902.48  4928.1 1901.98  4936.1 1902.48  5396.9 1904.56  5427.5 1905.47
  5439.6 1907.58  5490.6 1905.94  5638.5 1906.97  5643.6 1905.79  5740.4 1907.56
  5745.5 1906.15  5791.4 1907.66  5796.5 1906.22  5835.4 1907.65  5898.5 1906.55
  5933.8 1907.81  6037.7 1907.64  6204.4 1907.82  6233.1 1908.99  6304.1 1908.11
#Mann=8,-1,0
  3119.1    0.07       0  4324.3   0.045       0  4752.3   0.035       0
  4862.0    0.07       0  4927.6    0.07       0  4936.1    0.07       0
  5933.8   0.045       0  6037.7    0.07       0
Bank Sta=4927.6,4936.1
Exp/Cntr=0.3,0.1

Type RM Length L Ch R = 1,3247,332,332,332
BEGIN DESCRIPTION:
UCFB HW Trib 02 7.0
END DESCRIPTION:
XS GIS Cut Line= 4
      1391155.00      6979287.98      1390718.19      6977174.32
      1390491.05      6977012.42      1389730.03      6976863.01
#Sta/Elev= 30
  2964.3 1913.59  2994.9 1912.57  3034.5 1913.31  3178.7 1911.96  3209.3 1909.97
  3270.6 1908.46  3285.7 1908.60  3301.2 1910.80  3330.8 1906.14  3403.4 1904.63
  4131.0 1902.76  4560.0 1902.89  4671.8 1903.62  4678.6 1902.46  4722.1 1903.54
  4741.0 1902.21  4884.0 1902.44  4912.8 1901.38  5104.4 1900.68  5104.9 1900.18
  5112.9 1900.68  5237.1 1901.49  5330.4 1904.12  5452.0 1904.31  5503.4 1905.88
  5519.8 1908.69  5554.9 1905.21  5857.2 1907.91  6132.1 1909.32  6177.1 1909.35
#Mann=8,-1,0
  2964.3    0.07       0  4131.0   0.045       0  4560.0   0.035       0
  4678.6    0.07       0  5104.4    0.07       0  5112.9    0.07       0
  5857.2   0.045       0  6132.1    0.07       0
Bank Sta=5104.4,5112.9
Exp/Cntr=0.3,0.1

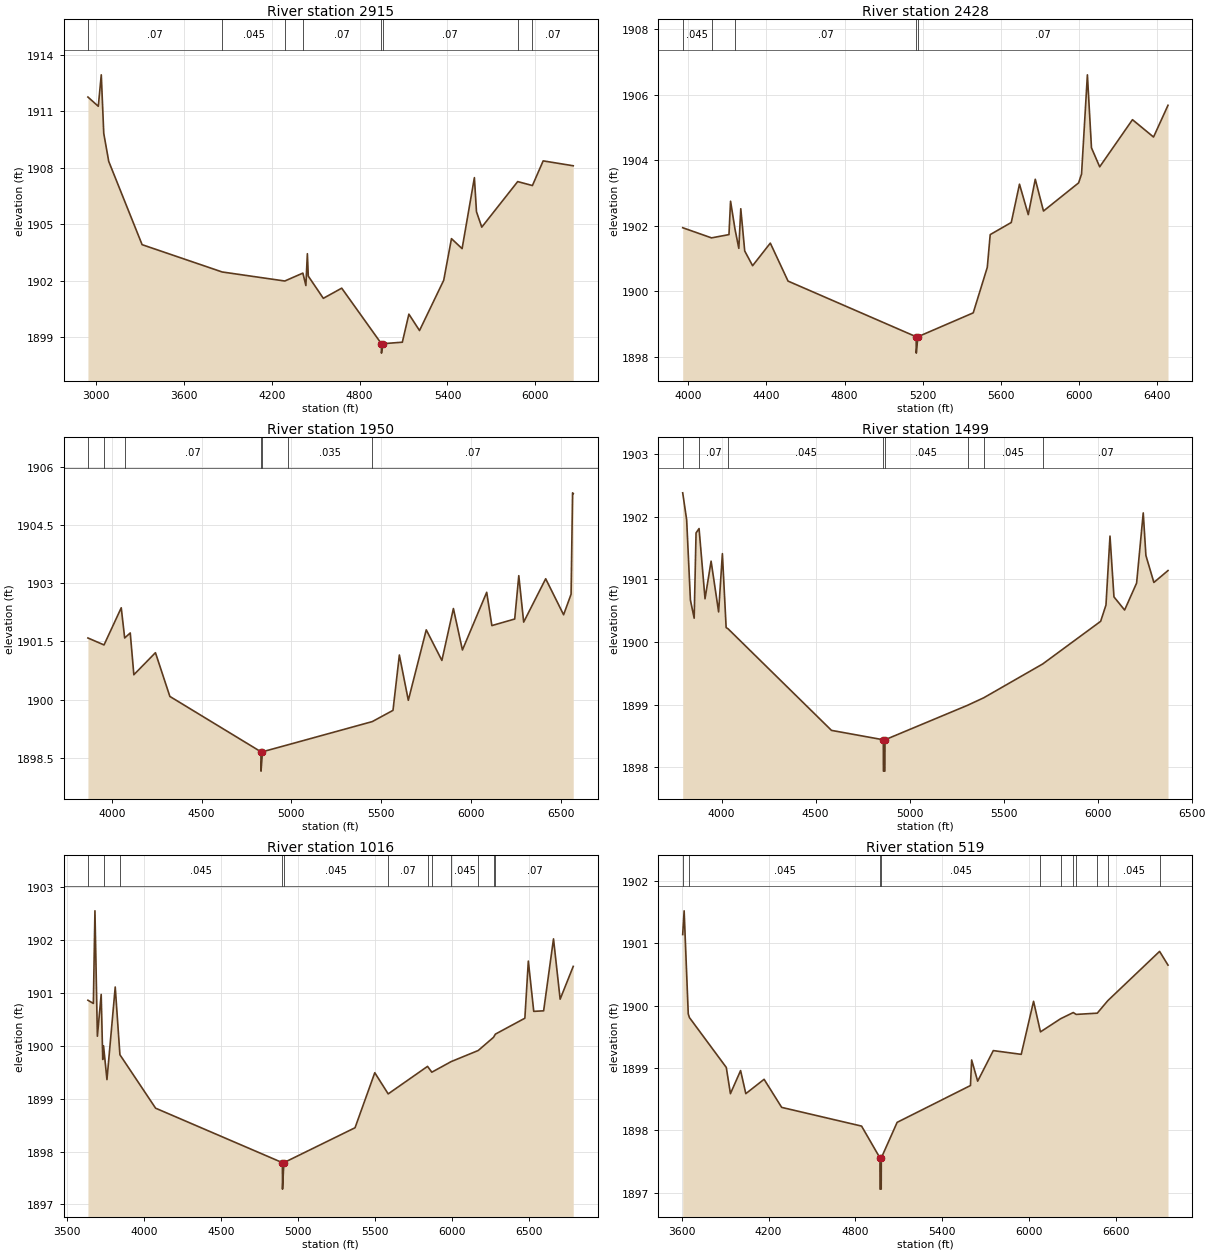
Type RM Length L Ch R = 1,2915,487,487,487
BEGIN DESCRIPTION:
UCFB HW Trib 02 6.0
END DESCRIPTION:
XS GIS Cut Line= 3
      1391351.22      6979097.37      1390955.00      6977088.00
      1389824.43      6976522.21
#Sta/Elev= 30
  2946.1 1911.76  3016.8 1911.27  3037.2 1912.94  3054.1 1909.83  3088.2 1908.34
  3315.9 1903.92  3862.3 1902.47  4289.7 1901.99  4413.2 1902.41  4433.6 1901.75
  4443.8 1903.44  4450.1 1902.25  4552.8 1901.07  4678.2 1901.61  4949.1 1898.66
  4949.6 1898.16  4957.6 1898.66  5092.0 1898.74  5136.7 1900.23  5209.3 1899.36
  5374.4 1902.03  5427.3 1904.24  5499.9 1903.71  5583.8 1907.48  5598.0 1905.67
  5634.1 1904.85  5879.3 1907.27  5979.8 1907.06  6053.2 1908.37  6258.4 1908.11
#Mann=8,-1,0
  2946.1    0.07       0  3862.3   0.045       0  4289.7   0.035       0
  4413.2    0.07       0  4949.1    0.07       0  4957.6    0.07       0
  5879.3   0.045       0  5979.8    0.07       0
Bank Sta=4949.1,4957.6
Exp/Cntr=0.3,0.1

Type RM Length L Ch R = 1,2428,478,478,478
BEGIN DESCRIPTION:
UCFB HW Trib 02 5.0
END DESCRIPTION:
XS GIS Cut Line= 3
      1391529.99      6978012.95      1391405.00      6976988.00
      1390204.74      6976174.17
#Sta/Elev= 30
  3971.8 1901.94  4119.2 1901.63  4208.5 1901.73  4216.6 1902.75  4239.3 1901.90
  4258.9 1901.31  4268.9 1902.52  4289.1 1901.23  4329.4 1900.78  4420.0 1901.47
  4510.7 1900.31  5166.2 1898.61  5166.7 1898.11  5174.8 1898.61  5458.1 1899.34
  5530.0 1900.73  5544.9 1901.73  5652.7 1902.10  5694.7 1903.27  5739.6 1902.34
  5775.5 1903.42  5817.5 1902.45  5997.2 1903.31  6012.2 1903.58  6042.1 1906.61
  6063.0 1904.38  6105.0 1903.80  6272.7 1905.24  6380.5 1904.71  6454.5 1905.68
#Mann=5,-1,0
  3971.8   0.045       0  4119.2   0.035       0  4239.3    0.07       0
  5166.2    0.07       0  5174.8    0.07       0
Bank Sta=5166.2,5174.8
Exp/Cntr=0.3,0.1

Type RM Length L Ch R = 1,1950,451,451,451
BEGIN DESCRIPTION:
UCFB HW Trib 02 4.0
END DESCRIPTION:
XS GIS Cut Line= 3
      1391780.00      6978013.00      1391855.00      6976888.00
      1390605.28      6975932.07
#Sta/Elev= 30
  3867.5 1901.59  3957.1 1901.41  4052.9 1902.37  4072.0 1901.59  4103.0 1901.72
  4123.1 1900.64  4243.3 1901.21  4323.5 1900.08  4830.3 1898.65  4830.8 1898.15
  4838.9 1898.65  4980.6 1898.83  5450.2 1899.43  5565.3 1899.72  5600.7 1901.15
  5650.6 1899.98  5750.4 1901.80  5837.4 1901.01  5901.5 1902.35  5951.7 1901.28
  6086.8 1902.77  6115.5 1901.91  6242.7 1902.08  6265.4 1903.20  6292.6 1902.00
  6415.1 1903.12  6514.8 1902.19  6556.4 1902.72  6564.7 1905.34  6568.4 1905.32
#Mann=7,-1,0
  3867.5   0.045       0  3957.1   0.035       0  4072.0    0.07       0
  4830.3   0.035       0  4838.9    0.07       0  4980.6   0.035       0
  5450.2    0.07       0
Bank Sta=4830.3,4838.9
Exp/Cntr=0.3,0.1

Type RM Length L Ch R = 1,1499,483,483,483
BEGIN DESCRIPTION:
UCFB HW Trib 02 3.0
END DESCRIPTION:
XS GIS Cut Line= 3
      1392227.22      6977948.99      1392255.00      6976738.00
      1391264.17      6975792.61
#Sta/Elev= 30
  3793.4 1902.38  3814.4 1901.95  3834.4 1900.67  3854.4 1900.38  3864.4 1901.74
  3880.4 1901.81  3912.1 1900.69  3944.4 1901.29  3984.4 1900.48  4004.4 1901.41
  4024.4 1900.23  4034.9 1900.21  4584.6 1898.59  4860.3 1898.44  4860.8 1897.94
  4868.6 1897.94  4869.1 1898.44  5308.0 1898.99  5394.2 1899.11  5708.0 1899.65
  6016.0 1900.33  6044.3 1900.59  6065.7 1901.69  6086.8 1900.72  6143.4 1900.51
  6207.2 1900.94  6242.5 1902.06  6256.7 1901.38  6299.1 1900.95  6374.2 1901.14
#Mann=8,-1,0
  3793.4   0.035       0  3880.4    0.07       0  4034.9   0.045       0
  4860.3   0.045       0  4869.1   0.045       0  5308.0    0.07       0
  5394.2   0.045       0  5708.0    0.07       0
Bank Sta=4860.3,4869.1
Exp/Cntr=0.3,0.1

Type RM Length L Ch R = 1,1016,497,497,497
BEGIN DESCRIPTION:
UCFB HW Trib 02 2.0
END DESCRIPTION:
XS GIS Cut Line= 3
      1392490.23      6977982.90      1392705.00      6976638.00
      1391308.59      6975524.27
#Sta/Elev= 30
  3637.9 1900.86  3673.2 1900.80  3683.4 1902.55  3699.2 1900.18  3723.9 1900.97
  3734.0 1899.74  3739.1 1900.00  3761.3 1899.36  3815.0 1901.11  3845.4 1899.83
  4076.8 1898.82  4899.6 1897.79  4900.1 1897.29  4908.8 1897.79  5370.6 1898.45
  5498.7 1899.49  5585.7 1899.09  5840.8 1899.61  5868.7 1899.50  5993.9 1899.70
  6169.7 1899.91  6269.1 1900.16  6281.2 1900.22  6472.2 1900.52  6494.7 1901.60
  6529.9 1900.65  6594.0 1900.66  6658.0 1902.02  6701.1 1900.88  6786.0 1901.50
#Mann=12,-1,0
  3637.9   0.035       0  3739.1    0.07       0  3845.4   0.045       0
  4899.6   0.045       0  4908.8   0.045       0  5585.7    0.07       0
  5840.8   0.045       0  5868.7    0.07       0  5993.9   0.045       0
  6169.7    0.07       0  6269.1   0.045       0  6281.2    0.07       0
Bank Sta=4899.6,4908.8
Exp/Cntr=0.3,0.1

Type RM Length L Ch R = 1,519,289,289,289
BEGIN DESCRIPTION:
UCFB HW Trib 02 1.0
END DESCRIPTION:
XS GIS Cut Line= 4
      1392597.86      6977835.38      1392930.14      6977540.27
      1393205.00      6976638.00      1391654.35      6975436.30
#Sta/Elev= 30
  3607.8 1901.14  3617.7 1901.52  3646.1 1899.87  3654.1 1899.81  3908.7 1899.01
  3937.2 1898.59  4007.4 1898.96  4043.4 1898.59  4169.6 1898.82  4290.9 1898.37
  4842.4 1898.07  4969.2 1897.56  4969.7 1897.06  4977.9 1897.06  4978.4 1897.56
  5087.8 1898.13  5593.8 1898.72  5602.0 1899.13  5643.6 1898.79  5751.4 1899.28
  5944.2 1899.22  6029.3 1900.07  6077.0 1899.58  6215.5 1899.79  6303.3 1899.89
  6323.2 1899.86  6469.0 1899.88  6541.6 1900.08  6899.1 1900.87  6957.2 1900.65
#Mann=11,-1,0
  3607.8    0.07       0  3654.1   0.045       0  4969.2   0.045       0
  4978.4   0.045       0  6077.0    0.07       0  6215.5   0.045       0
  6303.3    0.07       0  6323.2   0.045       0  6469.0    0.07       0
  6541.6   0.045       0  6899.1    0.07       0
Bank Sta=4969.2,4978.4
Exp/Cntr=0.3,0.1