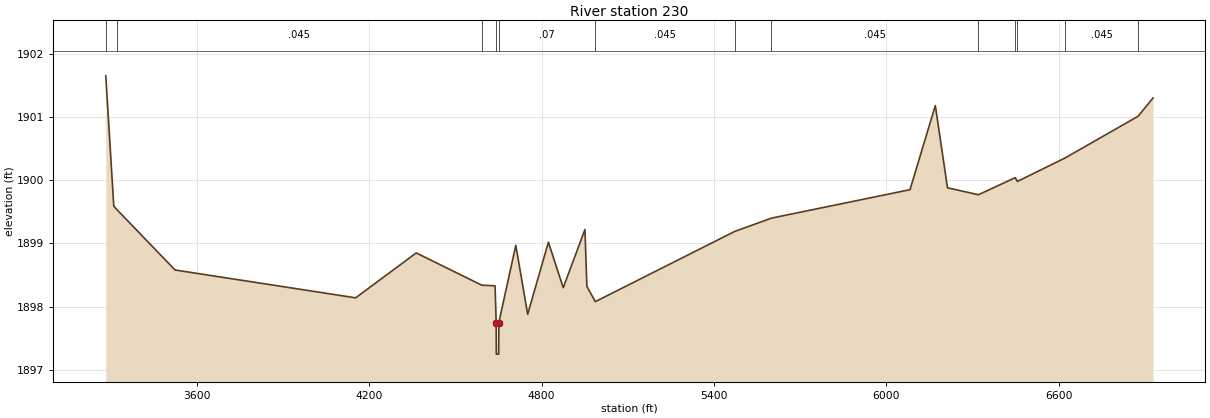
HEC-RAS study UCFB HW Trib 02.prj: UCFB HW Trib 02 Base Level Engineering

--- UCFB HW Trib 02.g01 (geometry) --- (continued)

Type RM Length L Ch R = 1,230,0,0,0
BEGIN DESCRIPTION:
UCFB HW Trib 02 0.5
END DESCRIPTION:
XS GIS Cut Line= 5
      1392686.28      6977848.80      1393229.28      6977395.65
      1393457.92      6976486.45      1393287.78      6976305.27
      1391809.67      6975367.66
#Sta/Elev= 30
  3283.8 1901.65  3311.6 1899.59  3321.4 1899.54  3525.0 1898.58  4153.2 1898.14
  4364.0 1898.85  4591.9 1898.34  4638.2 1898.33  4642.1 1897.75  4642.6 1897.25
  4650.9 1897.25  4651.4 1897.75  4710.4 1898.97  4751.7 1897.88  4823.8 1899.02
  4875.4 1898.30  4950.9 1899.22  4957.7 1898.32  4987.1 1898.08  5472.0 1899.19
  5599.9 1899.40  6081.9 1899.85  6170.0 1901.18  6212.3 1899.88  6320.0 1899.77
  6448.0 1900.04  6455.2 1899.98  6620.9 1900.35  6875.3 1901.01  6927.5 1901.30
#Mann=13,-1,0
  3283.8    0.07       0  3321.4   0.045       0  4591.9    0.07       0
  4642.1   0.045       0  4651.4    0.07       0  4987.1   0.045       0
  5472.0    0.07       0  5599.9   0.045       0  6320.0    0.07       0
  6448.0   0.045       0  6455.2    0.07       0  6620.9   0.045       0
  6875.3    0.07       0
Bank Sta=4642.1,4651.4
Exp/Cntr=0.3,0.1

Chan Stop Cuts=-1