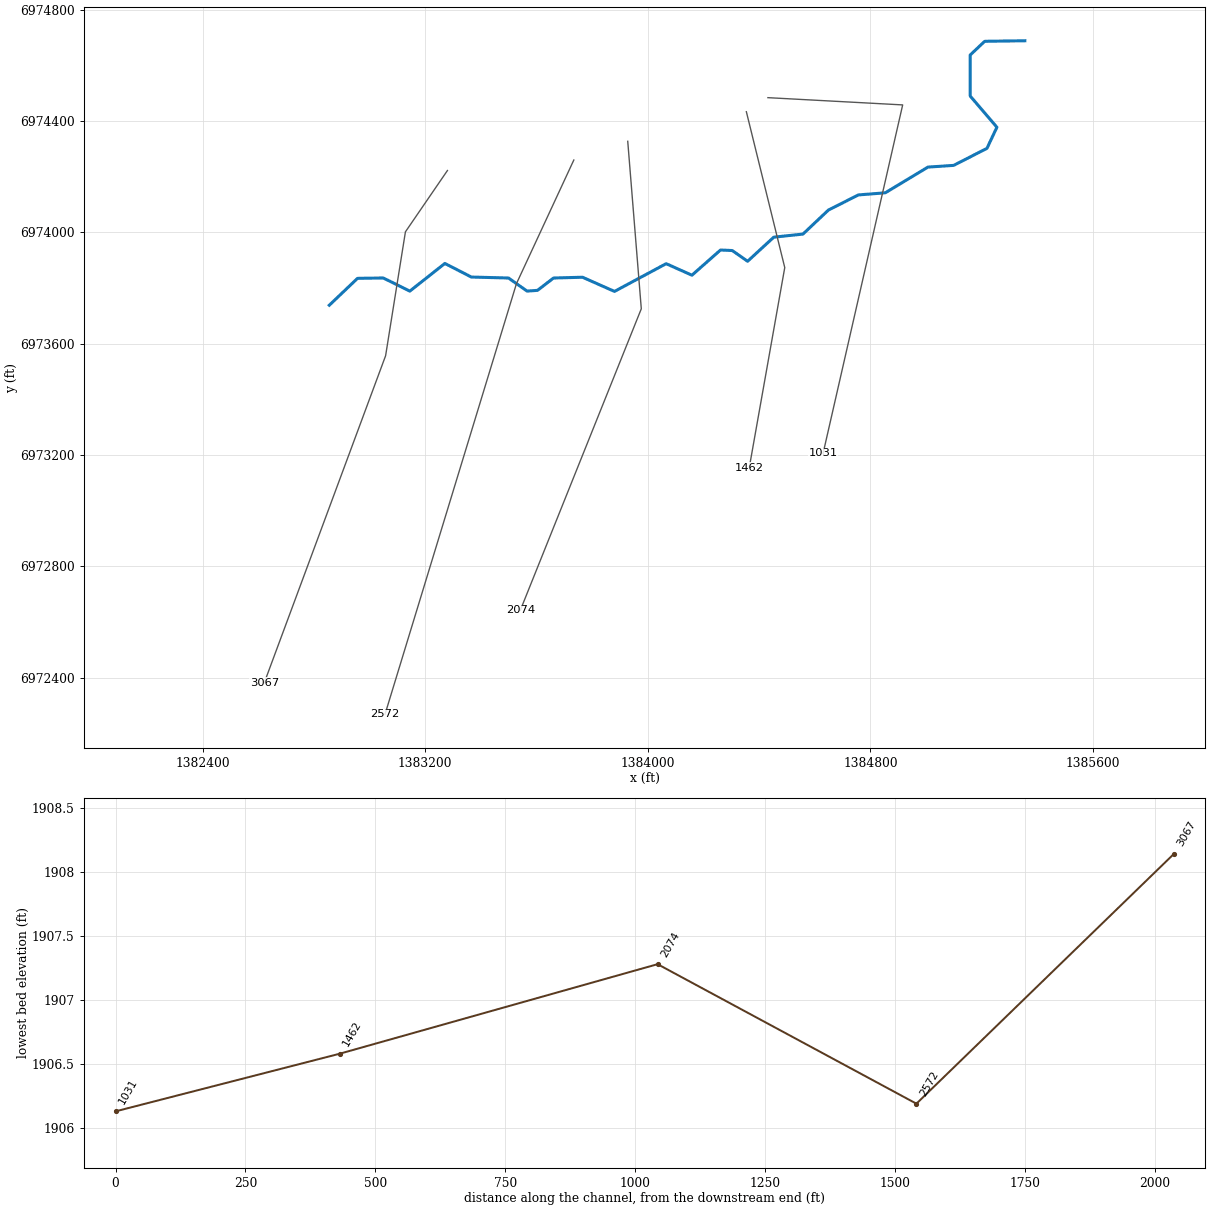
--- UCFB HW Trib 03-01.prj (project) ---

Proj Title=UCFB HW Trib 03-01 Base Level Engineering
Current Plan=p01
Default Exp/Contr=0.3,0.1
English Units
Geom File=g01
Flow File=f01
Plan File=p01
BEGIN DESCRIPTION:
UCFB HW Trib 03-01
END DESCRIPTION:

--- UCFB HW Trib 03-01.p01 (plan) ---

Plan Title=Multiple Run
Short Identifier=Multiple
Geom File=g01
Flow File=f01
Subcritical Flow
K Sum by GR= 0
Std Step Tol= 0.01
Critical Tol= 0.01
Num of Std Step Trials= 20
Max Error Tol= 0.3
Flow Tol Ratio= 0.001
Split Flow NTrial= 30
Split Flow Tol= 0.02
Split Flow Ratio= 0.02
Log Output Level= 0
Friction Slope Method= 1
Unsteady Friction Slope Method= 2
Unsteady Bridges Friction Slope Method= 1
Parabolic Critical Depth
Global Vel Dist=  1 , 1 , 1
Global Log Level= 0
CheckData=True
Encroach Param= -1, 0, 0, 0
BEGIN DESCRIPTION:
Multiple Run
END DESCRIPTION:

--- UCFB HW Trib 03-01.f01 (steady flow) ---

Flow Title=Multiple
Number of Profiles=7
Profile Names=10-year,25-year,50-year,1pct_min,100-year,1pct_plu,500-year
River Rch & RM= UCFB HW Trib 03-,Reach-1,3067
     262     362     444     270     540    1077     807
Boundary for River Rch & Prof#=UCFB HW Trib 03-,Reach-1,1
Up Type=0
Dn Type=3
Dn Slope=0.005
Boundary for River Rch & Prof#=UCFB HW Trib 03-,Reach-1,2
Up Type=0
Dn Type=3
Dn Slope=0.005
Boundary for River Rch & Prof#=UCFB HW Trib 03-,Reach-1,3
Up Type=0
Dn Type=3
Dn Slope=0.005
Boundary for River Rch & Prof#=UCFB HW Trib 03-,Reach-1,4
Up Type=0
Dn Type=3
Dn Slope=0.005
Boundary for River Rch & Prof#=UCFB HW Trib 03-,Reach-1,5
Up Type=0
Dn Type=3
Dn Slope=0.005
Boundary for River Rch & Prof#=UCFB HW Trib 03-,Reach-1,6
Up Type=0
Dn Type=3
Dn Slope=0.005
Boundary for River Rch & Prof#=UCFB HW Trib 03-,Reach-1,7
Up Type=0
Dn Type=3
Dn Slope=0.005

--- UCFB HW Trib 03-01.g01 (geometry) ---

Geom Title=Existing Conditions

River Reach=UCFB HW Trib 03-,Reach-1
Reach XY= 30
      1382855.00      6973738.00      1382956.48      6973834.59
      1383049.03      6973835.81      1383144.38      6973788.61
      1383270.34      6973888.04      1383365.50      6973839.25
      1383499.07      6973835.70      1383565.69      6973788.77
      1383603.26      6973791.37      1383660.93      6973835.72
      1383765.17      6973838.50      1383880.00      6973787.59
      1384065.70      6973887.20      1384158.40      6973845.84
      1384261.05      6973936.32      1384303.35      6973934.41
      1384358.40      6973895.84      1384452.57      6973982.45
      1384557.42      6973993.54      1384648.95      6974079.84
      1384756.58      6974134.17      1384853.42      6974141.83
      1385006.58      6974234.17      1385099.04      6974240.33
      1385218.71      6974301.47      1385254.46      6974377.31
      1385158.54      6974489.47      1385158.42      6974636.78
      1385210.62      6974686.08      1385355.00      6974688.00

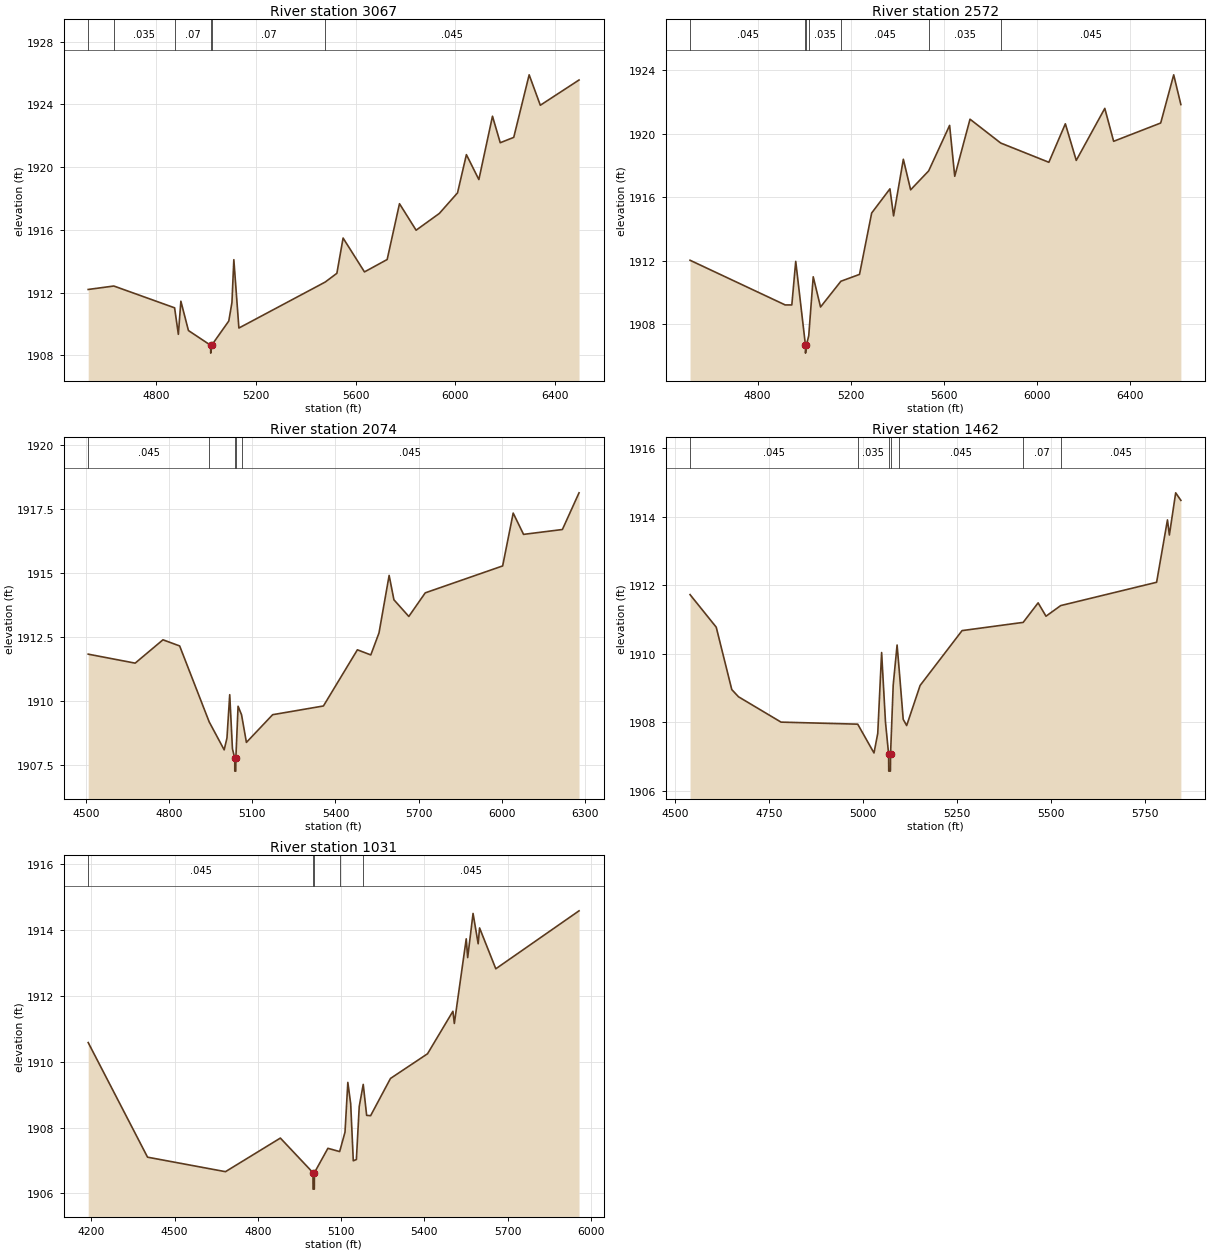
Type RM Length L Ch R = 1,3067,495,495,495
BEGIN DESCRIPTION:
UCFB HW Trib 03-01 3.0
END DESCRIPTION:
XS GIS Cut Line= 4
      1383279.56      6974221.88      1383128.56      6974001.57
      1383057.35      6973556.52      1382621.47      6972382.31
#Sta/Elev= 30
  4526.9 1912.20  4629.8 1912.42  4873.7 1911.03  4888.8 1909.34  4898.9 1911.45
  4929.3 1909.58  5018.4 1908.64  5018.7 1908.14  5022.4 1908.64  5091.3 1910.19
  5103.9 1911.37  5111.5 1914.10  5131.8 1909.74  5478.0 1912.67  5525.1 1913.23
  5550.1 1915.48  5635.9 1913.32  5727.0 1914.11  5776.5 1917.67  5843.2 1915.98
  5936.5 1917.05  6009.4 1918.36  6045.1 1920.80  6095.1 1919.21  6149.8 1923.25
  6180.9 1921.56  6235.1 1921.90  6297.0 1925.89  6341.8 1923.95  6497.2 1925.56
#Mann=6,-1,0
  4526.9   0.045       0  4629.8   0.035       0  4873.7    0.07       0
  5018.4    0.07       0  5022.4    0.07       0  5478.0   0.045       0
Bank Sta=5018.4,5022.4
Exp/Cntr=0.3,0.1

Type RM Length L Ch R = 1,2572,498,498,498
BEGIN DESCRIPTION:
UCFB HW Trib 03-01 2.0
END DESCRIPTION:
XS GIS Cut Line= 3
      1383733.81      6974259.55      1383527.57      6973815.29
      1383055.25      6972268.50
#Sta/Elev= 30
  4510.2 1912.03  4918.7 1909.22  4947.1 1909.22  4963.9 1911.96  5005.6 1906.69
  5005.9 1906.19  5009.6 1906.69  5019.7 1907.28  5039.0 1910.99  5070.4 1909.09
  5157.8 1910.71  5237.7 1911.14  5289.9 1915.00  5368.3 1916.52  5384.0 1914.82
  5425.9 1918.38  5457.2 1916.46  5534.6 1917.65  5624.5 1920.51  5646.5 1917.31
  5712.1 1920.90  5844.0 1919.40  6050.6 1918.19  6121.4 1920.61  6168.2 1918.31
  6290.7 1921.58  6328.7 1919.51  6530.7 1920.66  6586.5 1923.69  6617.3 1921.82
#Mann=7,-1,0
  4510.2   0.045       0  5005.6   0.045       0  5009.6   0.045       0
  5019.7   0.035       0  5157.8   0.045       0  5534.6   0.035       0
  5844.0   0.045       0
Bank Sta=5005.6,5009.6
Exp/Cntr=0.3,0.1

Type RM Length L Ch R = 1,2074,612,612,612
BEGIN DESCRIPTION:
UCFB HW Trib 03-01 1.0
END DESCRIPTION:
XS GIS Cut Line= 3
      1383927.62      6974326.86      1383976.35      6973725.15
      1383541.60      6972642.35
#Sta/Elev= 30
  4508.1 1911.84  4677.5 1911.49  4777.8 1912.40  4838.0 1912.16  4944.5 1909.20
  4998.6 1908.11  5008.6 1908.57  5018.6 1910.26  5028.4 1908.15  5036.7 1907.78
  5036.9 1907.28  5040.4 1907.28  5040.7 1907.78  5048.7 1909.81  5061.2 1909.48
  5078.8 1908.40  5173.4 1909.48  5356.6 1909.82  5479.1 1912.01  5527.5 1911.81
  5557.1 1912.67  5593.6 1914.91  5610.9 1913.96  5664.6 1913.31  5723.8 1914.23
  6003.1 1915.28  6041.1 1917.34  6078.5 1916.51  6218.6 1916.70  6278.6 1918.13
#Mann=5,-1,0
  4508.1   0.045       0  4944.5   0.035       0  5036.7   0.035       0
  5040.7   0.035       0  5061.2   0.045       0
Bank Sta=5036.7,5040.7
Exp/Cntr=0.3,0.1

Type RM Length L Ch R = 1,1462,431,431,431
BEGIN DESCRIPTION:
UCFB HW Trib 03-01 0.5
END DESCRIPTION:
XS GIS Cut Line= 3
      1384353.95      6974433.14      1384491.98      6973873.20
      1384364.37      6973154.44
#Sta/Elev= 30
  4540.0 1911.73  4609.7 1910.78  4651.1 1908.96  4668.9 1908.75  4782.2 1908.01
  4986.4 1907.95  5029.7 1907.11  5039.7 1907.68  5050.0 1910.04  5060.3 1908.01
  5068.6 1907.08  5069.0 1906.58  5073.4 1906.58  5073.8 1907.08  5080.9 1909.10
  5091.2 1910.26  5097.0 1909.51  5107.5 1908.09  5116.7 1907.91  5152.5 1909.08
  5264.2 1910.68  5426.9 1910.92  5466.7 1911.49  5487.6 1911.10  5526.8 1911.41
  5782.1 1912.09  5811.0 1913.91  5816.1 1913.47  5832.9 1914.70  5846.7 1914.48
#Mann=7,-1,0
  4540.0   0.045       0  4986.4   0.035       0  5068.6   0.035       0
  5073.8   0.035       0  5097.0   0.045       0  5426.9    0.07       0
  5526.8   0.045       0
Bank Sta=5068.6,5073.8
Exp/Cntr=0.3,0.1

Type RM Length L Ch R = 1,1031,0,0,0
BEGIN DESCRIPTION:
UCFB HW Trib 03-01 0.4
END DESCRIPTION:
XS GIS Cut Line= 3
      1384431.46      6974483.61      1384915.79      6974457.57
      1384629.67      6973205.58
#Sta/Elev= 30
  4188.3 1910.58  4402.2 1907.10  4683.1 1906.66  4881.0 1907.68  4998.5 1906.63
  4998.9 1906.13  5003.4 1906.13  5003.8 1906.63  5052.4 1907.37  5094.7 1907.27
  5114.0 1907.86  5124.2 1909.37  5134.5 1908.72  5143.9 1906.99  5155.0 1907.03
  5165.3 1908.64  5179.7 1909.31  5192.0 1908.37  5206.3 1908.36  5277.9 1909.49
  5411.5 1910.24  5503.0 1911.53  5508.1 1911.16  5551.0 1913.73  5556.2 1913.16
  5575.6 1914.50  5594.0 1913.58  5599.1 1914.06  5657.6 1912.82  5957.6 1914.58
#Mann=5,-1,0
  4188.3   0.045       0  4998.5   0.045       0  5003.8   0.045       0
  5094.7   0.035       0  5179.7   0.045       0
Bank Sta=4998.5,5003.8
Exp/Cntr=0.3,0.1

Chan Stop Cuts=-1