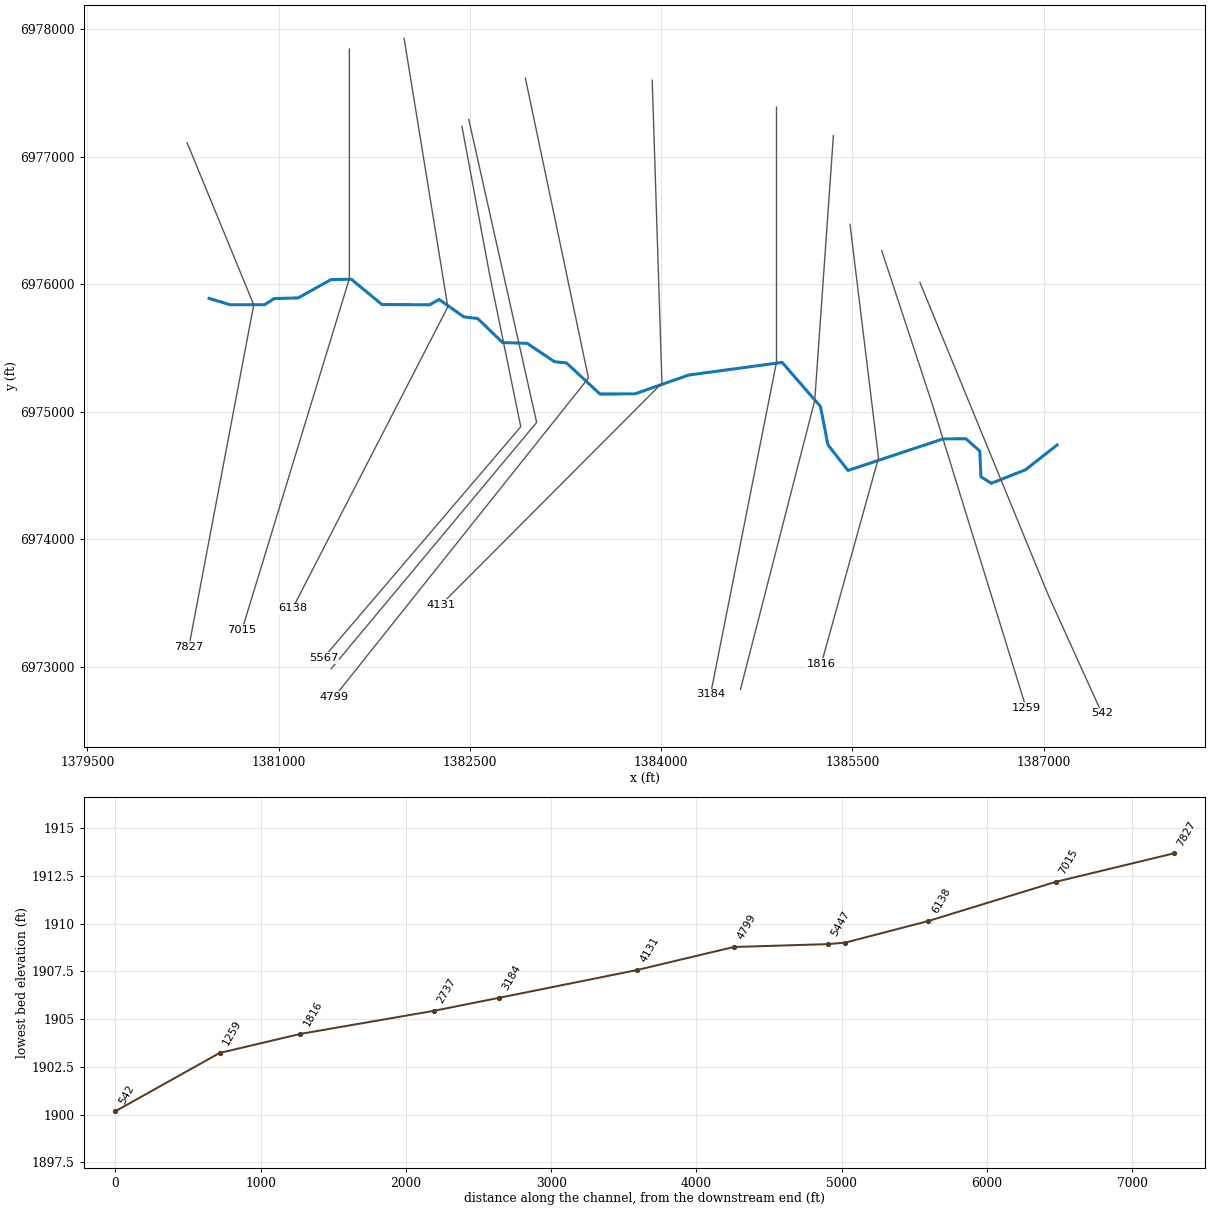
--- UCFB HW Trib 03.prj (project) ---

Proj Title=UCFB HW Trib 03 Base Level Engineering
Current Plan=p01
Default Exp/Contr=0.3,0.1
English Units
Geom File=g01
Flow File=f01
Plan File=p01
Y Axis Title=Elevation
X Axis Title(PF)=Main Channel Distance
X Axis Title(XS)=Station
BEGIN DESCRIPTION:
UCFB HW Trib 03
END DESCRIPTION:
DSS Export Rating Curves= 0
DSS Export Rating Curve Sorted= 0
DSS Export Volume Flow Curves= 0
DXF OffsetX= 0
DXF OffsetY= 0
DXF ScaleX= 1
DXF ScaleY= 10

--- UCFB HW Trib 03.p01 (plan) ---

Plan Title=Multiple Run
Short Identifier=Multiple
Geom File=g01
Flow File=f01
Subcritical Flow
K Sum by GR= 0
Std Step Tol= 0.01
Critical Tol= 0.01
Num of Std Step Trials= 20
Max Error Tol= 0.3
Flow Tol Ratio= 0.001
Split Flow NTrial= 30
Split Flow Tol= 0.02
Split Flow Ratio= 0.02
Log Output Level= 0
Friction Slope Method= 1
Unsteady Friction Slope Method= 2
Unsteady Bridges Friction Slope Method= 1
Parabolic Critical Depth
Global Vel Dist=  1 , 1 , 1
Global Log Level= 0
CheckData=True
Encroach Param= -1, 0, 0, 0
BEGIN DESCRIPTION:
Multiple Run
END DESCRIPTION:

--- UCFB HW Trib 03.f01 (steady flow) ---

Flow Title=Multiple
Number of Profiles=7
Profile Names=10-year,25-year,50-year,1pct_min,100-year,1pct_plu,500-year
River Rch & RM= UCFB HW Trib 03,Reach-1,7827
     301     423     524     323     644    1285     985
River Rch & RM= UCFB HW Trib 03,Reach-1,1816
     565     821    1040     654    1304    2602    2078
Boundary for River Rch & Prof#=UCFB HW Trib 03,Reach-1,1
Up Type=0
Dn Type=3
Dn Slope=0.005
Boundary for River Rch & Prof#=UCFB HW Trib 03,Reach-1,2
Up Type=0
Dn Type=3
Dn Slope=0.005
Boundary for River Rch & Prof#=UCFB HW Trib 03,Reach-1,3
Up Type=0
Dn Type=3
Dn Slope=0.005
Boundary for River Rch & Prof#=UCFB HW Trib 03,Reach-1,4
Up Type=0
Dn Type=3
Dn Slope=0.005
Boundary for River Rch & Prof#=UCFB HW Trib 03,Reach-1,5
Up Type=0
Dn Type=3
Dn Slope=0.005
Boundary for River Rch & Prof#=UCFB HW Trib 03,Reach-1,6
Up Type=0
Dn Type=3
Dn Slope=0.005
Boundary for River Rch & Prof#=UCFB HW Trib 03,Reach-1,7
Up Type=0
Dn Type=3
Dn Slope=0.005

--- UCFB HW Trib 03.g01 (geometry) ---

Geom Title=Existing Conditions

River Reach=UCFB HW Trib 03,Reach-1
Reach XY= 30
      1380455.00      6975888.00      1380620.21      6975838.51
      1380889.78      6975838.52      1380965.51      6975886.78
      1381153.45      6975891.75      1381410.93      6976035.76
      1381570.20      6976038.50      1381810.85      6975840.06
      1382185.02      6975838.18      1382258.32      6975879.96
      1382452.58      6975743.54      1382561.19      6975730.14
      1382756.52      6975541.74      1382949.07      6975535.76
      1383163.48      6975391.50      1383257.37      6975382.46
      1383520.16      6975138.38      1383794.50      6975139.22
      1384215.50      6975286.78      1384949.33      6975386.02
      1385249.53      6975040.45      1385308.39      6974739.40
      1385465.61      6974538.59      1386210.94      6974785.74
      1386389.85      6974787.62      1386499.55      6974690.47
      1386508.45      6974489.19      1386589.52      6974437.99
      1386857.43      6974543.52      1387105.00      6974738.00

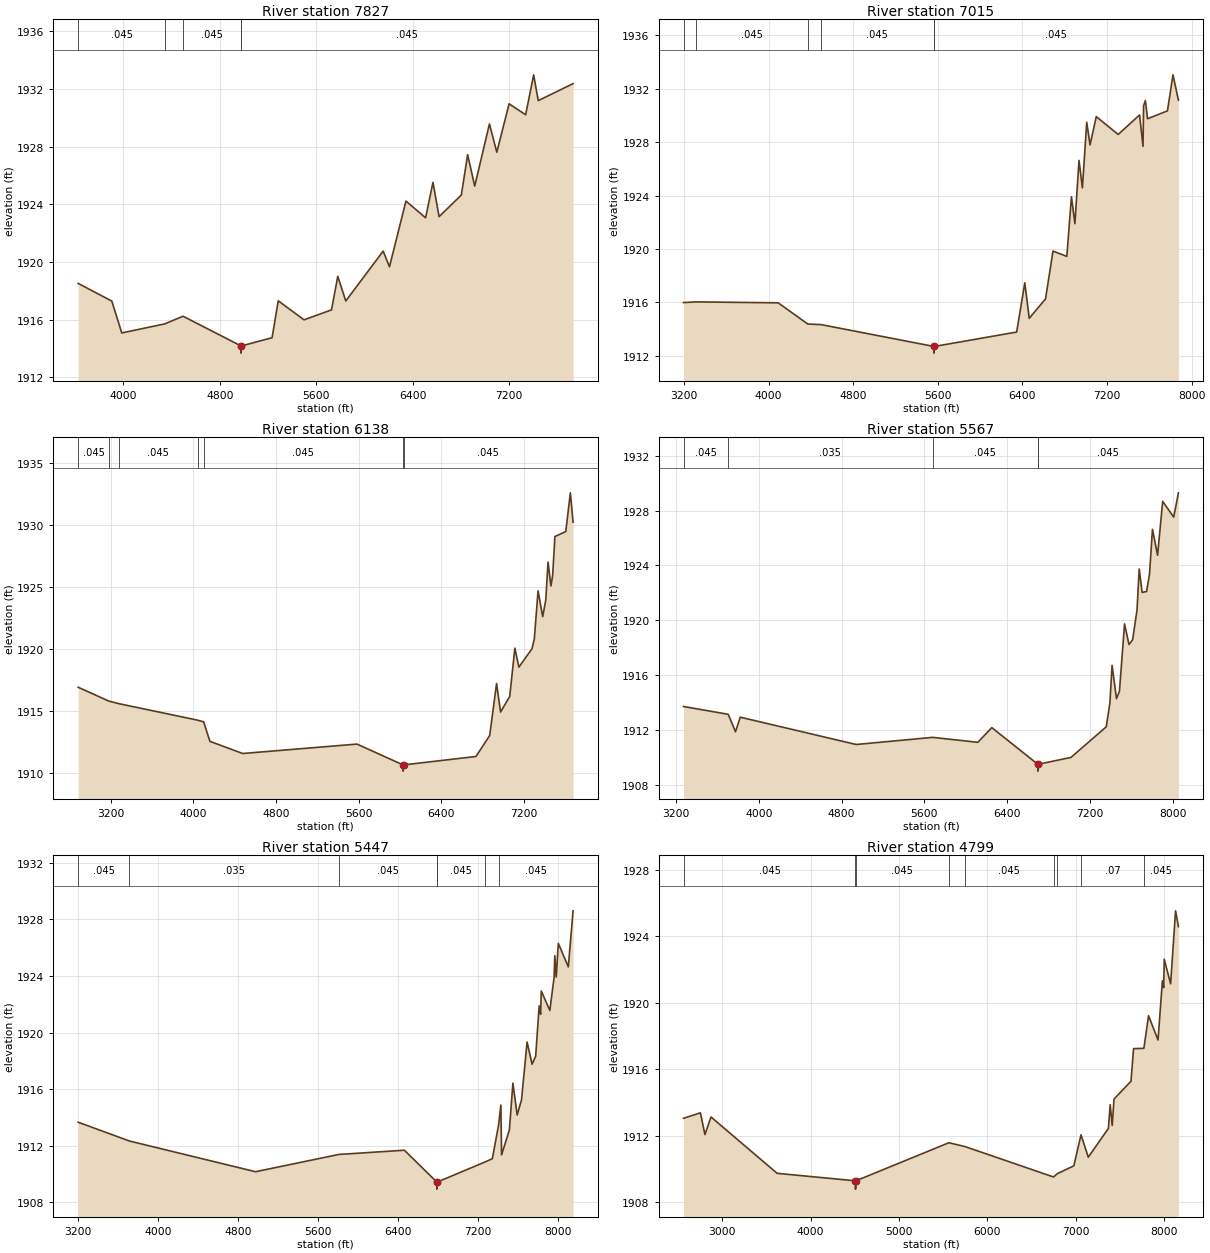
Type RM Length L Ch R = 1,7827,812,812,812
BEGIN DESCRIPTION:
UCFB HW Trib 03 11.0
END DESCRIPTION:
XS GIS Cut Line= 3
      1380282.83      6977108.27      1380805.00      6975838.00
      1380296.71      6973156.97
#Sta/Elev= 30
  3626.5 1918.52  3905.4 1917.29  3988.1 1915.08  4344.5 1915.71  4495.6 1916.24
  4976.2 1914.18  4976.5 1913.68  4980.3 1914.18  5234.0 1914.75  5284.9 1917.31
  5498.6 1915.99  5726.2 1916.68  5778.4 1919.01  5844.7 1917.30  6154.6 1920.76
  6206.9 1919.67  6343.4 1924.23  6506.3 1923.07  6567.3 1925.53  6618.2 1923.15
  6802.5 1924.65  6854.8 1927.45  6913.4 1925.27  7035.5 1929.58  7096.6 1927.62
  7198.4 1930.98  7335.5 1930.22  7401.9 1932.99  7440.1 1931.20  7728.7 1932.38
#Mann=5,-1,0
  3626.5   0.045       0  4344.5   0.035       0  4495.6   0.045       0
  4976.2   0.045       0  4980.3   0.045       0
Bank Sta=4976.2,4980.3
Exp/Cntr=0.3,0.1

Type RM Length L Ch R = 1,7015,877,877,877
BEGIN DESCRIPTION:
UCFB HW Trib 03 10.0
END DESCRIPTION:
XS GIS Cut Line= 3
      1381555.00      6977842.99      1381555.00      6976043.00
      1380713.36      6973288.82
#Sta/Elev= 30
  3195.2 1915.98  3315.3 1916.03  4090.2 1915.96  4370.7 1914.37  4494.5 1914.33
  5563.0 1912.69  5563.3 1912.19  5567.1 1912.69  6345.4 1913.77  6422.5 1917.46
  6464.3 1914.80  6618.2 1916.25  6689.1 1919.84  6819.9 1919.44  6863.5 1923.91
  6896.3 1921.89  6934.9 1926.64  6967.1 1924.58  7008.1 1929.49  7039.4 1927.80
  7098.3 1929.92  7305.5 1928.58  7507.5 1930.04  7540.3 1927.69  7545.5 1930.72
  7562.3 1931.12  7583.5 1929.76  7771.4 1930.35  7823.7 1933.05  7875.1 1931.15
#Mann=6,-1,0
  3195.2    0.07       0  3315.3   0.045       0  4370.7   0.035       0
  4494.5   0.045       0  5563.0   0.045       0  5567.1   0.045       0
Bank Sta=5563,5567.1
Exp/Cntr=0.3,0.1

Type RM Length L Ch R = 1,6138,571,571,571
BEGIN DESCRIPTION:
UCFB HW Trib 03 9.0
END DESCRIPTION:
XS GIS Cut Line= 3
      1381984.21      6977927.74      1382327.04      6975821.26
      1381109.61      6973456.31
#Sta/Elev= 30
  2883.5 1916.90  3182.0 1915.78  3281.9 1915.57  4039.6 1914.25  4099.1 1914.11
  4159.7 1912.54  4477.4 1911.56  5584.3 1912.32  6031.0 1910.64  6031.2 1910.14
  6035.1 1910.64  6736.9 1911.32  6869.9 1913.01  6936.4 1917.20  6975.2 1914.90
  7063.9 1916.16  7113.8 1920.05  7152.5 1918.52  7279.9 1920.01  7302.1 1920.80
  7338.3 1924.67  7383.3 1922.59  7413.0 1923.93  7435.1 1926.99  7462.9 1925.06
  7479.5 1925.90  7501.7 1929.05  7606.9 1929.45  7651.2 1932.57  7677.6 1930.20
#Mann=7,-1,0
  2883.5   0.045       0  3182.0    0.07       0  3281.9   0.045       0
  4039.6   0.035       0  4099.1   0.045       0  6031.0   0.045       0
  6035.1   0.045       0
Bank Sta=6031,6035.1
Exp/Cntr=0.3,0.1

Type RM Length L Ch R = 1,5567,120,120,120
BEGIN DESCRIPTION:
UCFB HW Trib 03 8.0
END DESCRIPTION:
XS GIS Cut Line= 4
      1382437.79      6977237.64      1382654.64      6976076.72
      1382899.43      6974881.41      1381350.86      6973067.68
#Sta/Elev= 30
  3270.5 1913.72  3703.1 1913.15  3773.2 1911.88  3819.5 1912.94  4940.2 1910.95
  5679.3 1911.47  6117.0 1911.11  6252.0 1912.18  6696.5 1909.51  6696.8 1909.01
  6701.3 1909.51  7017.3 1910.01  7358.7 1912.24  7393.8 1913.97  7414.7 1916.72
  7457.5 1914.29  7486.1 1914.83  7535.5 1919.74  7578.3 1918.24  7613.4 1918.58
  7656.2 1920.75  7677.1 1923.74  7705.6 1922.03  7748.4 1922.10  7777.0 1923.37
  7805.5 1926.63  7854.9 1924.74  7904.3 1928.67  8010.8 1927.52  8056.5 1929.29
#Mann=5,-1,0
  3270.5   0.045       0  3703.1   0.035       0  5679.3   0.045       0
  6696.5   0.035       0  6701.3   0.045       0
Bank Sta=6696.5,6701.3
Exp/Cntr=0.3,0.1

Type RM Length L Ch R = 1,5447,648,648,648
BEGIN DESCRIPTION:
UCFB HW Trib 03 7.5
END DESCRIPTION:
XS GIS Cut Line= 3
      1382491.48      6977291.59      1383023.74      6974915.26
      1381412.26      6972983.21
#Sta/Elev= 30
  3203.2 1913.66  3716.4 1912.33  4977.7 1910.16  5809.6 1911.38  6466.7 1911.68
  6791.0 1909.43  6791.4 1908.93  6795.8 1909.43  7277.0 1910.86  7346.6 1911.08
  7408.4 1913.43  7431.9 1914.87  7439.0 1911.35  7517.1 1913.11  7552.3 1916.42
  7595.2 1914.17  7638.2 1915.23  7694.1 1919.33  7744.4 1917.76  7780.0 1918.33
  7815.2 1921.88  7829.5 1921.29  7836.0 1922.93  7921.9 1921.56  7964.9 1923.93
  7971.4 1925.43  7985.7 1923.92  8006.5 1926.30  8106.7 1924.64  8154.3 1928.60
#Mann=7,-1,0
  3203.2   0.045       0  3716.4   0.035       0  5809.6   0.045       0
  6791.0   0.035       0  6795.8   0.045       0  7277.0    0.07       0
  7408.4   0.045       0
Bank Sta=6791,6795.8
Exp/Cntr=0.3,0.1

Type RM Length L Ch R = 1,4799,668,668,668
BEGIN DESCRIPTION:
UCFB HW Trib 03 7.0
END DESCRIPTION:
XS GIS Cut Line= 3
      1382935.59      6977615.28      1383430.00      6975263.00
      1381436.37      6972762.06
#Sta/Elev= 30
  2560.7 1913.04  2752.1 1913.37  2803.2 1912.06  2871.7 1913.12  3620.6 1909.73
  4507.3 1909.28  4507.6 1908.78  4512.1 1909.28  5564.5 1911.57  5746.7 1911.34
  6749.3 1909.51  6791.5 1909.71  6978.6 1910.18  7060.3 1912.05  7142.3 1910.70
  7369.7 1912.43  7390.5 1913.86  7412.9 1912.61  7433.8 1914.20  7625.9 1915.27
  7654.8 1917.23  7771.6 1917.25  7824.5 1919.21  7931.8 1917.75  7981.4 1921.31
  7995.8 1920.90  8002.2 1922.61  8074.3 1921.13  8130.4 1925.52  8162.7 1924.57
#Mann=9,-1,0
  2560.7   0.045       0  4507.3   0.045       0  4512.1   0.045       0
  5564.5   0.035       0  5746.7   0.045       0  6749.3    0.07       0
  6791.5   0.045       0  7060.3    0.07       0  7771.6   0.045       0
Bank Sta=4507.3,4512.1
Exp/Cntr=0.3,0.1

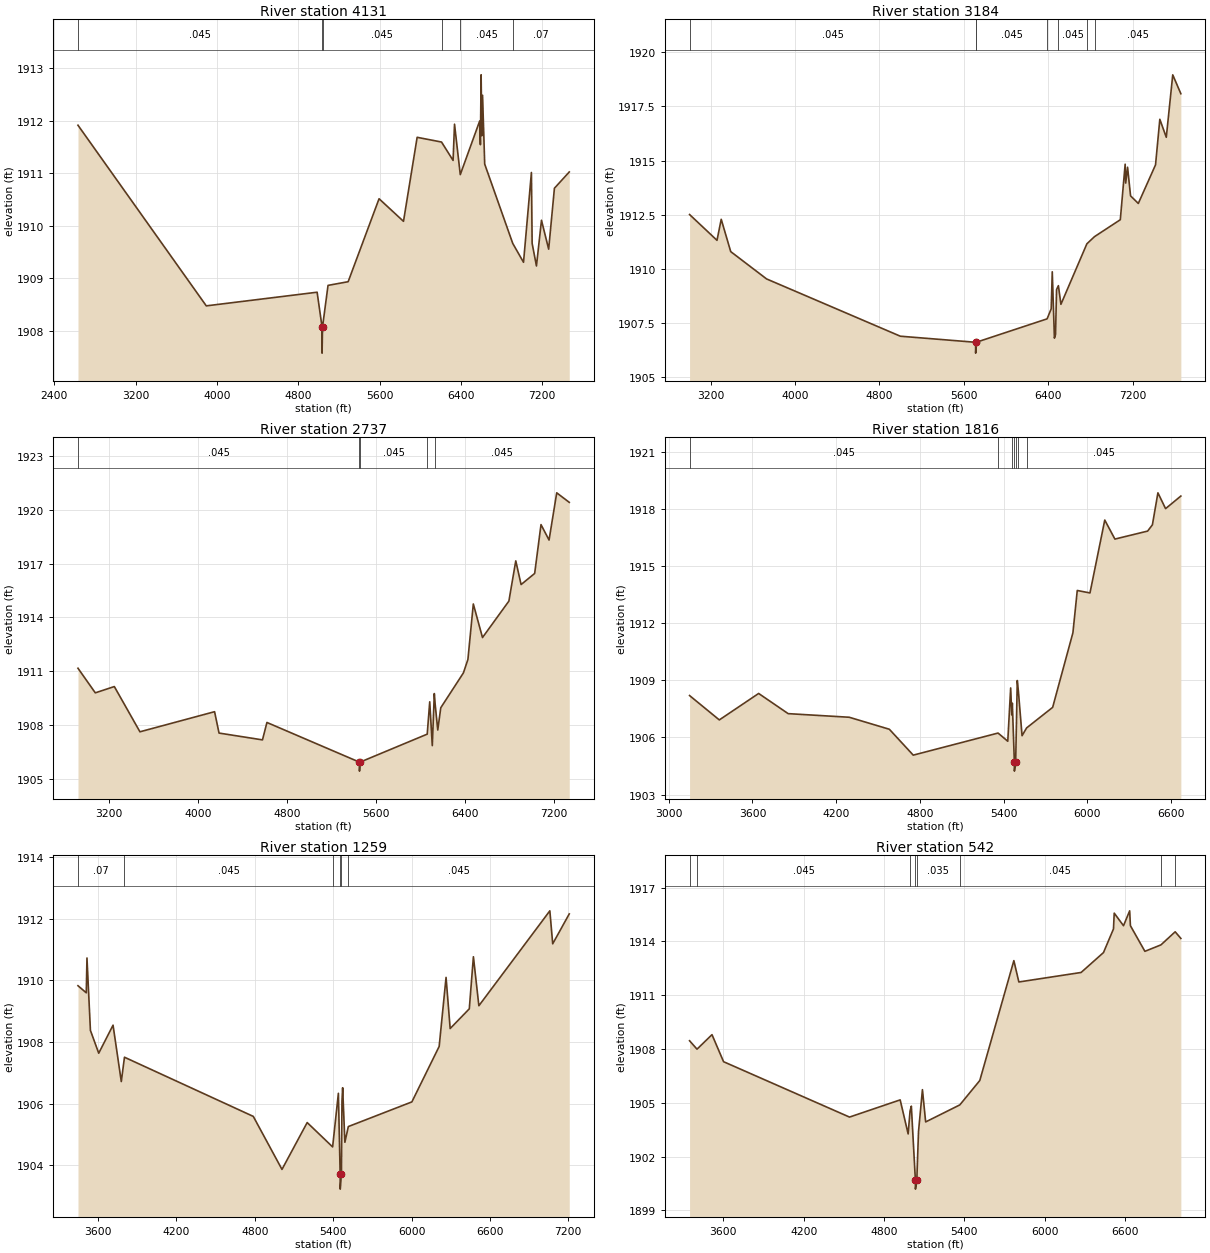
Type RM Length L Ch R = 1,4131,947,947,947
BEGIN DESCRIPTION:
UCFB HW Trib 03 6.0
END DESCRIPTION:
XS GIS Cut Line= 3
      1383930.18      6977599.70      1384006.53      6975223.33
      1382272.48      6973484.08
#Sta/Elev= 30
  2633.1 1911.91  3895.5 1908.47  4986.0 1908.73  5034.4 1908.07  5034.7 1907.57
  5039.2 1908.07  5093.3 1908.86  5291.3 1908.93  5595.4 1910.51  5835.8 1910.08
  5970.1 1911.68  6210.1 1911.59  6323.7 1911.24  6337.8 1911.93  6394.5 1910.97
  6585.3 1911.99  6592.4 1911.54  6599.5 1912.87  6606.5 1911.71  6613.6 1912.48
  6634.8 1911.17  6910.6 1909.66  7016.7 1909.30  7094.4 1911.01  7101.5 1909.66
  7143.9 1909.23  7193.4 1910.10  7264.1 1909.55  7320.7 1910.71  7466.7 1911.02
#Mann=6,-1,0
  2633.1   0.045       0  5034.4   0.045       0  5039.2   0.045       0
  6210.1   0.035       0  6394.5   0.045       0  6910.6    0.07       0
Bank Sta=5034.4,5039.2
Exp/Cntr=0.3,0.1

Type RM Length L Ch R = 1,3184,447,447,447
BEGIN DESCRIPTION:
UCFB HW Trib 03 5.0
END DESCRIPTION:
XS GIS Cut Line= 3
      1384905.00      6977388.01      1384905.00      6975388.00
      1384387.77      6972782.66
#Sta/Elev= 30
  3000.4 1912.51  3260.4 1911.32  3300.4 1912.29  3390.4 1910.80  3730.4 1909.54
  4997.9 1906.90  5711.4 1906.62  5711.8 1906.12  5716.8 1906.62  6388.9 1907.70
  6427.7 1908.16  6437.9 1909.87  6458.3 1906.81  6468.8 1906.98  6478.7 1909.05
  6496.0 1909.23  6520.0 1908.37  6766.0 1911.16  6838.3 1911.49  7082.8 1912.27
  7128.8 1914.83  7133.9 1913.96  7151.6 1914.69  7180.0 1913.37  7253.5 1913.02
  7416.7 1914.80  7457.4 1916.90  7518.6 1916.07  7579.8 1918.95  7656.6 1918.08
#Mann=7,-1,0
  3000.4   0.045       0  5711.4   0.045       0  5716.8   0.045       0
  6388.9   0.035       0  6496.0   0.045       0  6766.0    0.07       0
  6838.3   0.045       0
Bank Sta=5711.4,5716.8
Exp/Cntr=0.3,0.1

Type RM Length L Ch R = 1,2737,921,921,921
BEGIN DESCRIPTION:
UCFB HW Trib 03 4.0
END DESCRIPTION:
XS GIS Cut Line= 3
      1385351.25      6977164.29      1385205.00      6975088.00
      1384622.41      6972821.82
#Sta/Elev= 30
  2918.9 1911.17  3074.8 1909.80  3246.0 1910.15  3476.6 1907.63  4148.2 1908.75
  4188.3 1907.56  4579.3 1907.18  4619.4 1908.15  5451.9 1905.94  5452.4 1905.44
  5457.3 1905.94  6061.9 1907.50  6084.5 1909.30  6107.6 1906.86  6125.8 1909.76
  6132.8 1909.20  6156.8 1907.73  6183.9 1908.97  6387.5 1910.91  6428.2 1911.66
  6476.8 1914.75  6559.4 1912.88  6796.9 1914.91  6858.9 1917.15  6906.7 1915.83
  7028.9 1916.45  7086.0 1919.17  7158.3 1918.31  7227.4 1920.94  7340.2 1920.41
#Mann=5,-1,0
  2918.9   0.045       0  5451.9   0.045       0  5457.3   0.045       0
  6061.9   0.035       0  6132.8   0.045       0
Bank Sta=5451.9,5457.3
Exp/Cntr=0.3,0.1

Type RM Length L Ch R = 1,1816,557,557,557
BEGIN DESCRIPTION:
UCFB HW Trib 03 3.0
END DESCRIPTION:
XS GIS Cut Line= 3
      1385481.30      6976469.59      1385705.00      6974638.00
      1385256.60      6973022.47
#Sta/Elev= 30
  3149.2 1908.20  3362.4 1906.92  3644.4 1908.31  3856.0 1907.25  4293.7 1907.06
  4581.3 1906.43  4752.6 1905.07  5360.6 1906.23  5430.3 1905.80  5451.0 1908.60
  5459.0 1907.18  5462.9 1907.80  5477.4 1904.73  5477.9 1904.23  5486.9 1904.73
  5498.5 1908.99  5506.6 1908.41  5532.7 1906.09  5565.3 1906.50  5752.0 1907.58
  5897.3 1911.50  5928.4 1913.72  6019.6 1913.59  6125.6 1917.42  6198.2 1916.42
  6432.9 1916.84  6467.1 1917.17  6506.6 1918.85  6561.5 1918.02  6671.0 1918.68
#Mann=7,-1,0
  3149.2   0.045       0  5360.6   0.035       0  5462.9   0.045       0
  5477.4   0.045       0  5486.9   0.045       0  5506.6   0.035       0
  5565.3   0.045       0
Bank Sta=5477.4,5486.9
Exp/Cntr=0.3,0.1

Type RM Length L Ch R = 1,1259,717,717,717
BEGIN DESCRIPTION:
UCFB HW Trib 03 2.0
END DESCRIPTION:
XS GIS Cut Line= 3
      1385730.01      6976262.98      1386123.06      6975069.94
      1386862.59      6972676.93
#Sta/Elev= 30
  3446.4 1909.83  3509.9 1909.60  3515.2 1910.73  3541.7 1908.38  3605.2 1907.64
  3714.9 1908.55  3778.0 1906.72  3802.3 1907.51  4788.3 1905.59  5008.1 1903.87
  5201.0 1905.39  5395.7 1904.60  5439.9 1906.34  5453.4 1903.73  5453.9 1903.23
  5463.0 1903.73  5467.3 1906.08  5472.5 1906.52  5489.6 1904.75  5516.0 1905.26
  6002.4 1906.06  6211.4 1907.86  6264.1 1910.10  6295.5 1908.44  6442.0 1909.08
  6473.4 1910.77  6515.3 1909.18  7058.6 1912.26  7080.5 1911.19  7207.2 1912.16
#Mann=6,-1,0
  3446.4    0.07       0  3802.3   0.045       0  5395.7   0.035       0
  5453.4   0.045       0  5463.0   0.035       0  5516.0   0.045       0
Bank Sta=5453.4,5463
Exp/Cntr=0.3,0.1

Type RM Length L Ch R = 1,542,0,0,0
BEGIN DESCRIPTION:
UCFB HW Trib 03 1.0
END DESCRIPTION:
XS GIS Cut Line= 3
      1386030.01      6976012.98      1387039.20      6973554.84
      1387457.23      6972633.47
#Sta/Elev= 30
  3347.3 1908.46  3402.9 1907.99  3514.8 1908.80  3601.3 1907.29  4541.8 1904.20
  4920.1 1905.16  4979.7 1903.26  4993.9 1904.54  5003.6 1904.81  5033.7 1900.68
  5034.2 1900.18  5044.3 1900.68  5057.0 1903.38  5086.4 1905.73  5110.4 1903.93
  5365.6 1904.88  5514.7 1906.24  5769.2 1912.93  5806.5 1911.74  6271.4 1912.27
  6438.5 1913.38  6513.2 1914.70  6518.7 1915.58  6588.0 1914.88  6634.1 1915.71
  6639.6 1914.88  6747.8 1913.45  6867.7 1913.81  6973.9 1914.54  7016.3 1914.17
#Mann=8,-1,0
  3347.3    0.07       0  3402.9   0.045       0  4993.9   0.035       0
  5033.7   0.035       0  5044.3   0.035       0  5365.6   0.045       0
  6867.7   0.035       0  6973.9   0.045       0
Bank Sta=5033.7,5044.3
Exp/Cntr=0.3,0.1

Chan Stop Cuts=-1