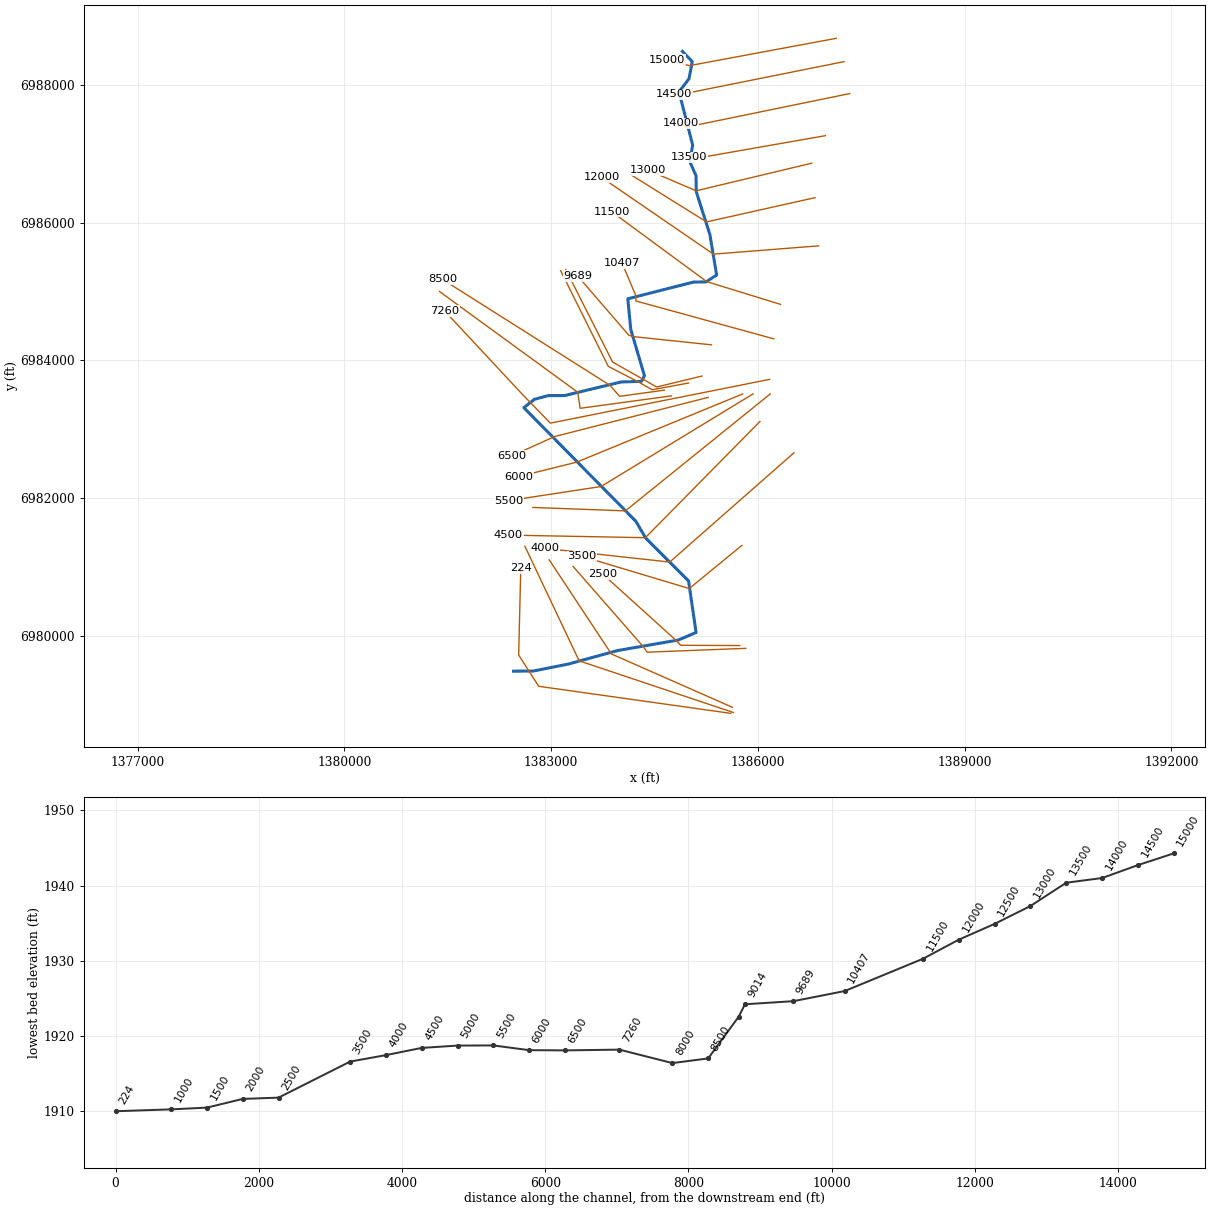
--- UCFB HW Trib 04-01.prj (project) ---

Proj Title=UCFB HW Trib 04-01 Base Level Engineering
Current Plan=p01
Default Exp/Contr=0.3,0.1
English Units
Geom File=g01
Flow File=f01
Plan File=p01
BEGIN DESCRIPTION:
UCFB HW Trib 04-01
END DESCRIPTION:

--- UCFB HW Trib 04-01.p01 (plan) ---

Plan Title=Multiple Run
Short Identifier=Multiple
Geom File=g01
Flow File=f01
Subcritical Flow
K Sum by GR= 0
Std Step Tol= 0.01
Critical Tol= 0.01
Num of Std Step Trials= 20
Max Error Tol= 0.3
Flow Tol Ratio= 0.001
Split Flow NTrial= 30
Split Flow Tol= 0.02
Split Flow Ratio= 0.02
Log Output Level= 0
Friction Slope Method= 1
Unsteady Friction Slope Method= 2
Unsteady Bridges Friction Slope Method= 1
Parabolic Critical Depth
Global Vel Dist=  1 , 1 , 1
Global Log Level= 0
CheckData=True
Encroach Param= -1, 0, 0, 0
BEGIN DESCRIPTION:
Multiple Run
END DESCRIPTION:

--- UCFB HW Trib 04-01.f01 (steady flow) ---

Flow Title=Multiple
Number of Profiles=7
Profile Names=10-year,25-year,50-year,1pct_min,100-year,1pct_plu,500-year
River Rch & RM= UCFB HW Trib 04-,Reach-1,15000
     289     404     498     305     609    1215     923
River Rch & RM= UCFB HW Trib 04-,Reach-1,9689
     308     432     534     328     654    1304     993
River Rch & RM= UCFB HW Trib 04-,Reach-1,7260
     437     622     776     480     958    1912    1482
Boundary for River Rch & Prof#=UCFB HW Trib 04-,Reach-1,1
Up Type=0
Dn Type=3
Dn Slope=0.005
Boundary for River Rch & Prof#=UCFB HW Trib 04-,Reach-1,2
Up Type=0
Dn Type=3
Dn Slope=0.005
Boundary for River Rch & Prof#=UCFB HW Trib 04-,Reach-1,3
Up Type=0
Dn Type=3
Dn Slope=0.005
Boundary for River Rch & Prof#=UCFB HW Trib 04-,Reach-1,4
Up Type=0
Dn Type=3
Dn Slope=0.005
Boundary for River Rch & Prof#=UCFB HW Trib 04-,Reach-1,5
Up Type=0
Dn Type=3
Dn Slope=0.005
Boundary for River Rch & Prof#=UCFB HW Trib 04-,Reach-1,6
Up Type=0
Dn Type=3
Dn Slope=0.005
Boundary for River Rch & Prof#=UCFB HW Trib 04-,Reach-1,7
Up Type=0
Dn Type=3
Dn Slope=0.005

--- UCFB HW Trib 04-01.g01 (geometry) ---

Geom Title=Existing Conditions

River Reach=UCFB HW Trib 04-,Reach-1
Reach XY= 30
      1384905.00      6988488.00      1385047.69      6988338.10
      1385001.25      6988089.55      1384855.57      6987899.09
      1385053.78      6987127.49      1385013.08      6986884.70
      1385102.74      6986682.06      1385106.22      6986448.50
      1385302.74      6985832.06      1385401.56      6985239.25
      1385249.07      6985140.24      1385065.51      6985136.78
      1384112.67      6984894.52      1384156.22      6984448.50
      1384354.30      6983777.24      1384311.57      6983695.69
      1384015.50      6983686.78      1383194.50      6983489.22
      1382955.00      6983488.00      1382756.55      6983434.25
      1382604.37      6983313.08      1384231.99      6981661.47
      1384371.65      6981421.33      1384994.52      6980797.80
      1385103.38      6980049.81      1384849.06      6979940.26
      1383965.51      6979786.78      1383244.49      6979589.22
      1382739.78      6979488.52      1382455.00      6979488.00

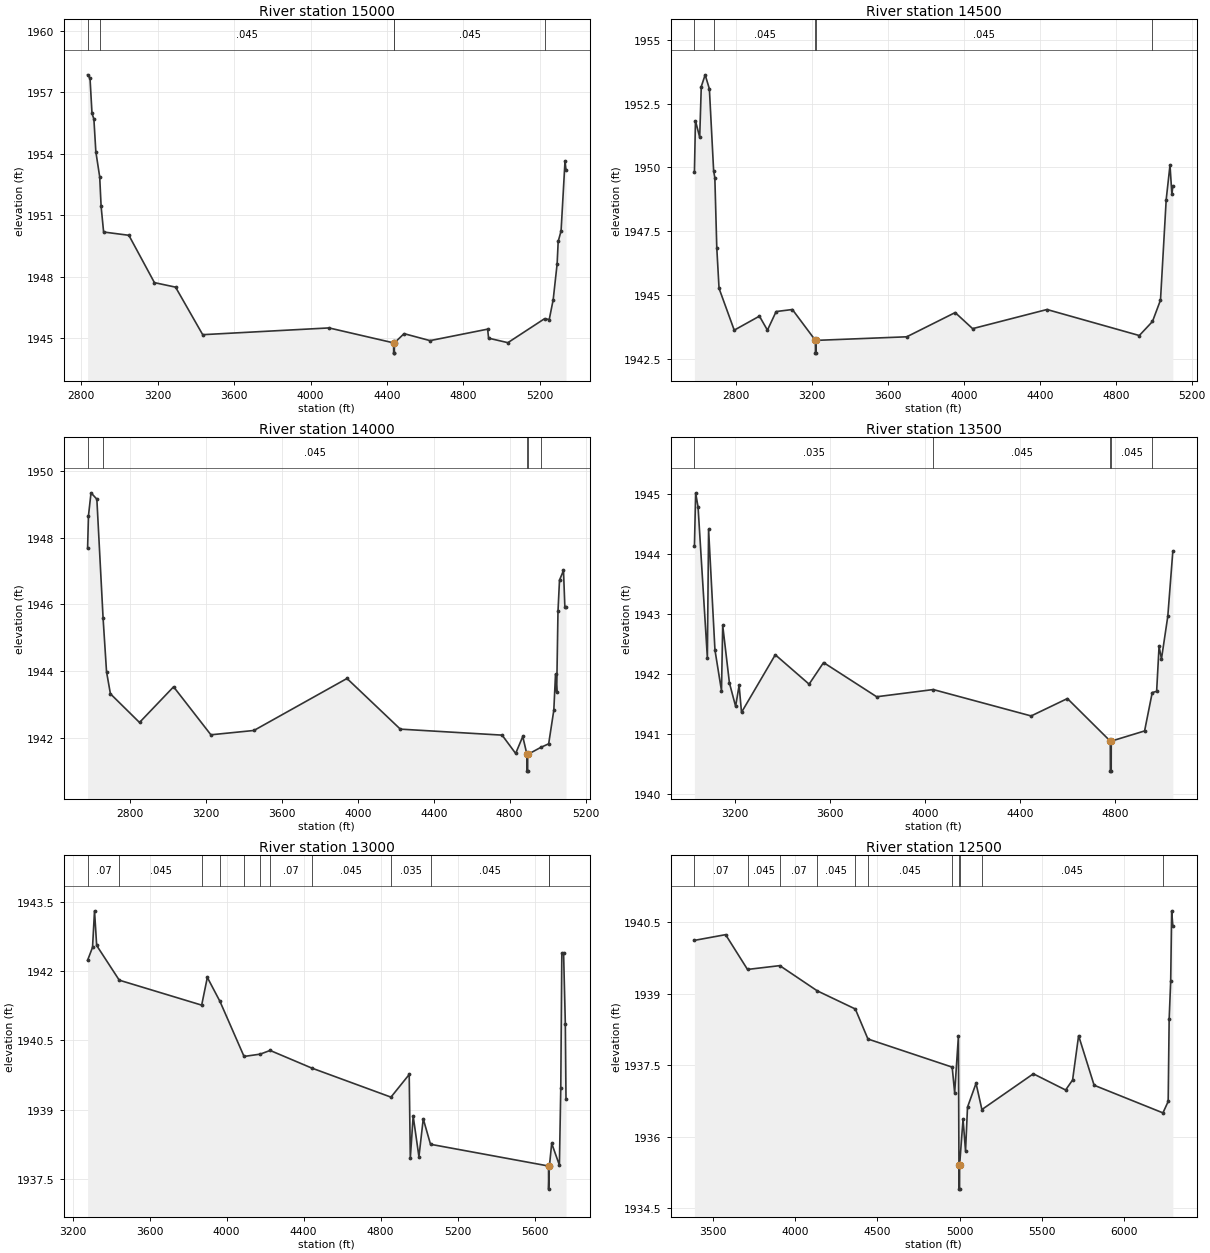
Type RM Length L Ch R = 1,15000,500,500,500
BEGIN DESCRIPTION:
UCFB HW Trib 04-01 28.0
END DESCRIPTION:
XS GIS Cut Line= 3
      1387137.46      6988676.35      1385006.94      6988279.89
      1384680.03      6988362.99
#Sta/Elev= 30
  2832.9 1957.86  2845.6 1957.70  2856.0 1955.98  2865.9 1955.70  2876.1 1954.11
  2896.3 1952.88  2903.7 1951.44  2916.8 1950.19  3049.0 1950.03  3182.8 1947.72
  3293.4 1947.50  3435.5 1945.18  4096.7 1945.51  4434.9 1944.78  4435.2 1944.28
  4438.7 1944.28  4438.9 1944.78  4489.7 1945.23  4625.6 1944.89  4927.0 1945.45
  4932.1 1945.01  5033.0 1944.79  5225.0 1945.96  5249.6 1945.92  5270.3 1946.89
  5290.9 1948.64  5296.4 1949.73  5311.5 1950.24  5332.2 1953.66  5337.3 1953.21
#Mann=5,-1,0
  2832.9   0.035       0  2896.3   0.045       0  4434.9   0.045       0
  4438.9   0.045       0  5225.0   0.035       0
Bank Sta=4434.9,4438.9
Exp/Cntr=0.3,0.1

Type RM Length L Ch R = 1,14500,500,500,500
BEGIN DESCRIPTION:
UCFB HW Trib 04-01 27.0
END DESCRIPTION:
XS GIS Cut Line= 3
      1387250.32      6988337.81      1384880.67      6987862.26
      1384779.97      6987863.00
#Sta/Elev= 30
  2583.1 1949.84  2588.5 1951.83  2610.8 1951.18  2619.1 1953.17  2639.5 1953.63
  2661.7 1953.08  2684.1 1949.87  2690.5 1949.59  2700.7 1946.85  2712.6 1945.26
  2792.5 1943.62  2925.1 1944.17  2967.2 1943.62  3013.0 1944.35  3098.5 1944.43
  3219.7 1943.22  3220.0 1942.72  3223.5 1942.72  3223.7 1943.22  3700.3 1943.36
  3955.2 1944.31  4047.0 1943.68  4438.4 1944.43  4924.2 1943.41  4993.5 1943.96
  5035.7 1944.80  5065.7 1948.74  5085.7 1950.09  5095.7 1948.94  5100.7 1949.28
#Mann=5,-1,0
  2583.1   0.035       0  2684.1   0.045       0  3219.7   0.035       0
  3223.7   0.045       0  4993.5   0.035       0
Bank Sta=3219.7,3223.7
Exp/Cntr=0.3,0.1

Type RM Length L Ch R = 1,14000,500,500,500
BEGIN DESCRIPTION:
UCFB HW Trib 04-01 26.0
END DESCRIPTION:
XS GIS Cut Line= 3
      1387332.77      6987874.27      1384960.09      6987386.97
      1384880.03      6987441.01
#Sta/Elev= 30
  2577.8 1947.68  2582.4 1948.66  2595.9 1949.35  2626.6 1949.16  2659.4 1945.59
  2677.6 1943.98  2698.0 1943.32  2851.2 1942.46  3030.6 1943.53  3227.0 1942.09
  3453.5 1942.22  3943.5 1943.78  4224.3 1942.26  4760.2 1942.08  4831.6 1941.53
  4869.0 1942.04  4890.9 1941.50  4891.2 1941.00  4894.7 1941.00  4894.9 1941.50
  4963.3 1941.71  5005.4 1941.82  5032.5 1942.83  5041.4 1943.91  5047.5 1943.36
  5054.4 1945.79  5062.4 1946.73  5083.4 1947.02  5090.6 1945.93  5096.6 1945.93
#Mann=5,-1,0
  2577.8   0.035       0  2659.4   0.045       0  4890.9   0.035       0
  4894.9   0.045       0  4963.3   0.035       0
Bank Sta=4890.9,4894.9
Exp/Cntr=0.3,0.1

Type RM Length L Ch R = 1,13500,500,500,500
BEGIN DESCRIPTION:
UCFB HW Trib 04-01 25.0
END DESCRIPTION:
XS GIS Cut Line= 3
      1386980.03      6987263.01      1385039.12      6986922.83
      1385004.46      6986946.38
#Sta/Elev= 30
  3029.5 1944.13  3034.6 1945.02  3044.8 1944.78  3083.9 1942.27  3089.0 1944.41
  3115.8 1942.40  3143.3 1941.72  3148.4 1942.81  3176.7 1941.85  3202.7 1941.46
  3217.4 1941.81  3227.5 1941.36  3369.6 1942.32  3511.8 1941.83  3572.7 1942.19
  3796.0 1941.62  4034.0 1941.74  4445.8 1941.30  4598.3 1941.59  4778.8 1940.88
  4779.1 1940.38  4782.6 1940.38  4782.8 1940.88  4923.0 1941.05  4955.2 1941.69
  4973.7 1941.71  4983.9 1942.46  4994.0 1942.25  5020.6 1942.96  5041.9 1944.05
#Mann=5,-1,0
  3029.5   0.035       0  4034.0   0.045       0  4778.8   0.035       0
  4782.8   0.045       0  4955.2   0.035       0
Bank Sta=4778.8,4782.8
Exp/Cntr=0.3,0.1

Type RM Length L Ch R = 1,13000,500,500,500
BEGIN DESCRIPTION:
UCFB HW Trib 04-01 24.0
END DESCRIPTION:
XS GIS Cut Line= 3
      1386780.02      6986863.00      1385104.82      6986462.53
      1384403.47      6986763.00
#Sta/Elev= 30
  3277.6 1942.23  3303.3 1942.51  3313.6 1943.30  3324.8 1942.55  3442.1 1941.80
  3870.3 1941.26  3899.7 1941.86  3965.4 1941.34  4090.4 1940.15  4174.3 1940.20
  4225.9 1940.28  4441.5 1939.90  4853.7 1939.27  4948.4 1939.76  4954.2 1937.95
  4969.0 1938.86  4999.0 1937.98  5021.4 1938.80  5059.1 1938.25  5672.3 1937.78
  5672.6 1937.28  5676.3 1937.78  5676.9 1937.78  5688.7 1938.27  5728.7 1937.80
  5735.9 1939.47  5741.3 1942.38  5750.5 1942.38  5759.5 1940.86  5763.0 1939.23
#Mann=13,-1,0
  3277.6    0.07       0  3442.1   0.045       0  3870.3    0.07       0
  3965.4   0.045       0  4090.4    0.07       0  4174.3   0.045       0
  4225.9    0.07       0  4441.5   0.045       0  4853.7   0.035       0
  5059.1   0.045       0  5672.3   0.035       0  5676.3   0.045       0
  5676.9   0.035       0
Bank Sta=5672.3,5676.3
Exp/Cntr=0.3,0.1

Type RM Length L Ch R = 1,12500,500,500,500
BEGIN DESCRIPTION:
UCFB HW Trib 04-01 23.0
END DESCRIPTION:
XS GIS Cut Line= 3
      1386830.03      6986363.01      1385255.25      6986010.77
      1384154.93      6986697.44
#Sta/Elev= 30
  3386.3 1940.12  3575.9 1940.24  3709.2 1939.51  3905.5 1939.59  4134.0 1939.06
  4365.1 1938.68  4441.9 1938.05  4954.5 1937.46  4969.5 1936.92  4992.5 1938.12
  4995.6 1935.40  4995.8 1934.90  4999.3 1934.90  4999.6 1935.40  5020.5 1936.37
  5035.7 1935.70  5047.7 1936.62  5099.6 1937.12  5135.2 1936.57  5448.2 1937.32
  5644.6 1936.98  5687.0 1937.19  5723.6 1938.12  5818.0 1937.08  6236.7 1936.50
  6268.6 1936.74  6274.5 1938.46  6283.9 1939.27  6289.8 1940.74  6297.0 1940.42
#Mann=11,-1,0
  3386.3    0.07       0  3709.2   0.045       0  3905.5    0.07       0
  4134.0   0.045       0  4365.1    0.07       0  4441.9   0.045       0
  4954.5   0.035       0  4995.6   0.035       0  4999.6   0.035       0
  5135.2   0.045       0  6236.7   0.035       0
Bank Sta=4995.6,4999.6
Exp/Cntr=0.3,0.1

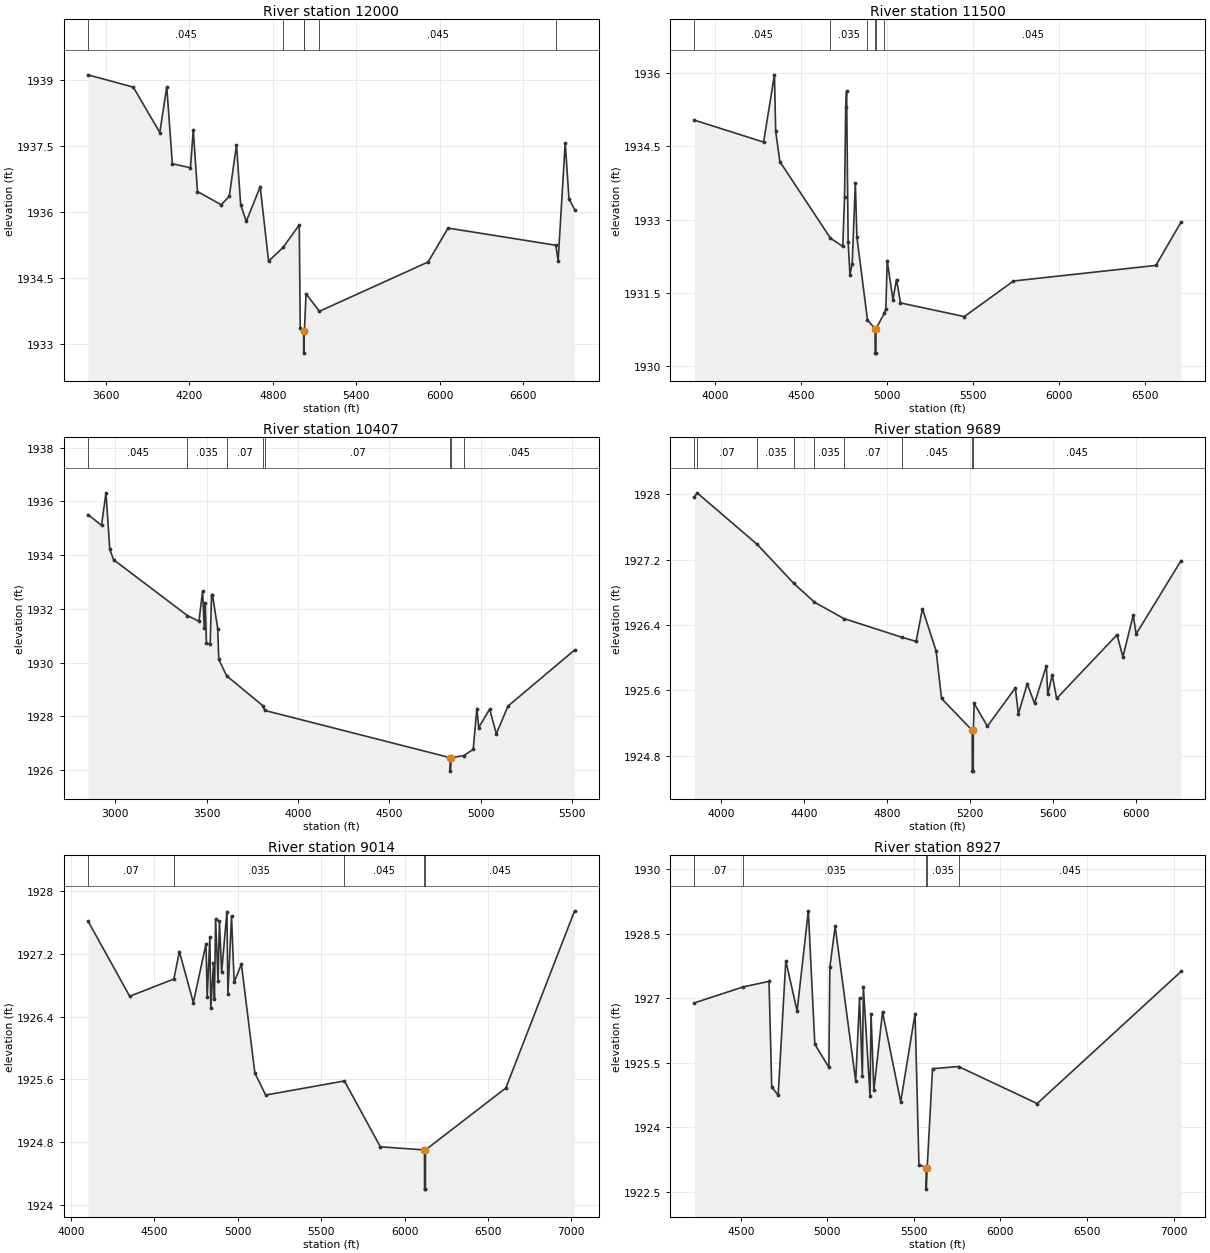
Type RM Length L Ch R = 1,12000,500,500,500
BEGIN DESCRIPTION:
UCFB HW Trib 04-01 22.0
END DESCRIPTION:
XS GIS Cut Line= 3
      1386879.95      6985663.00      1385355.37      6985543.04
      1383730.00      6986658.47
#Sta/Elev= 30
  3470.7 1939.12  3796.7 1938.84  3987.2 1937.81  4037.4 1938.85  4077.5 1937.10
  4207.9 1937.01  4228.0 1937.87  4258.1 1936.47  4428.6 1936.17  4487.1 1936.36
  4538.9 1937.53  4569.0 1936.17  4609.2 1935.79  4709.5 1936.58  4769.7 1934.89
  4874.2 1935.20  4990.3 1935.71  4997.7 1933.38  5022.0 1933.30  5022.4 1932.80
  5027.5 1933.30  5039.1 1934.15  5135.3 1933.75  5917.5 1934.87  6061.0 1935.64
  6835.8 1935.25  6852.8 1934.90  6903.6 1937.58  6930.6 1936.31  6971.3 1936.06
#Mann=6,-1,0
  3470.7   0.045       0  4874.2   0.035       0  5022.0   0.035       0
  5027.5   0.035       0  5135.3   0.045       0  6835.8   0.035       0
Bank Sta=5022,5027.5
Exp/Cntr=0.3,0.1

Type RM Length L Ch R = 1,11500,1093,1093,1093
BEGIN DESCRIPTION:
UCFB HW Trib 04-01 21.0
END DESCRIPTION:
XS GIS Cut Line= 3
      1386330.03      6984812.99      1385257.61      6985143.88
      1383879.98      6986158.43
#Sta/Elev= 30
  3877.7 1935.04  4280.1 1934.59  4343.4 1935.97  4350.6 1934.81  4374.8 1934.19
  4669.2 1932.62  4741.1 1932.45  4751.6 1933.46  4758.2 1935.30  4763.4 1935.63
  4772.5 1932.54  4783.0 1931.87  4796.1 1932.09  4814.4 1933.75  4823.5 1932.64
  4885.1 1930.94  4929.2 1930.76  4929.7 1930.26  4934.3 1930.26  4934.7 1930.76
  4983.4 1931.08  4992.0 1931.17  5000.0 1932.15  5033.3 1931.36  5054.1 1931.77
  5077.2 1931.29  5449.0 1931.01  5735.1 1931.74  6564.3 1932.06  6710.9 1932.95
#Mann=6,-1,0
  3877.7   0.045       0  4669.2   0.035       0  4885.1    0.07       0
  4929.2   0.045       0  4934.7    0.07       0  4983.4   0.045       0
Bank Sta=4929.2,4934.7
Exp/Cntr=0.3,0.1

Type RM Length L Ch R = 1,10407,718,718,718
BEGIN DESCRIPTION:
UCFB HW Trib 04-01 20.0
END DESCRIPTION:
XS GIS Cut Line= 4
      1386230.02      6984313.00      1384230.00      6984863.00
      1384229.81      6984938.24      1384030.00      6985413.00
#Sta/Elev= 30
  2850.5 1935.51  2924.5 1935.11  2949.0 1936.32  2969.8 1934.22  2990.5 1933.83
  3394.9 1931.75  3458.2 1931.54  3478.0 1932.67  3487.4 1931.27  3492.6 1932.23
  3498.7 1930.74  3519.5 1930.68  3527.0 1932.51  3532.2 1932.52  3560.9 1931.26
  3566.6 1930.12  3609.4 1929.51  3808.7 1928.39  3818.4 1928.22  4833.9 1926.46
  4834.3 1925.96  4839.4 1926.46  4908.8 1926.54  4959.8 1926.77  4979.8 1928.29
  4989.8 1927.58  5049.8 1928.27  5086.5 1927.35  5150.2 1928.38  5515.1 1930.47
#Mann=8,-1,0
  2850.5   0.045       0  3394.9   0.035       0  3609.4    0.07       0
  3808.7   0.035       0  3818.4    0.07       0  4833.9   0.045       0
  4839.4    0.07       0  4908.8   0.045       0
Bank Sta=4833.9,4839.4
Exp/Cntr=0.3,0.1

Type RM Length L Ch R = 1,9689,675,675,675
BEGIN DESCRIPTION:
UCFB HW Trib 04-01 19.0
END DESCRIPTION:
XS GIS Cut Line= 4
      1385326.38      6984225.88      1384209.51      6984343.18
      1384130.00      6984363.00      1383386.64      6985224.45
#Sta/Elev= 30
  3872.4 1927.97  3885.1 1928.02  4173.9 1927.39  4350.8 1926.91  4450.2 1926.68
  4591.4 1926.48  4871.0 1926.25  4939.6 1926.20  4969.8 1926.60  5036.1 1926.08
  5061.9 1925.50  5209.4 1925.11  5209.9 1924.61  5214.7 1924.61  5215.1 1925.11
  5218.9 1925.44  5282.5 1925.16  5417.4 1925.63  5431.7 1925.31  5474.5 1925.68
  5509.6 1925.44  5566.6 1925.90  5573.2 1925.55  5595.1 1925.79  5616.0 1925.50
  5906.7 1926.28  5935.2 1926.01  5984.6 1926.52  5998.9 1926.29  6215.2 1927.19
#Mann=9,-1,0
  3872.4   0.035       0  3885.1    0.07       0  4173.9   0.035       0
  4350.8    0.07       0  4450.2   0.035       0  4591.4    0.07       0
  4871.0   0.045       0  5209.4   0.045       0  5215.1   0.045       0
Bank Sta=5209.4,5215.1
Exp/Cntr=0.3,0.1

Type RM Length L Ch R = 1,9014,87,87,87
BEGIN DESCRIPTION:
UCFB HW Trib 04-01 18.5
END DESCRIPTION:
XS GIS Cut Line= 4
      1385189.22      6983772.76      1384532.18      6983613.50
      1383891.77      6983976.48      1383212.79      6985318.39
#Sta/Elev= 30
  4103.3 1927.62  4353.2 1926.66  4617.7 1926.88  4651.0 1927.23  4734.6 1926.58
  4810.6 1927.33  4817.6 1926.65  4833.5 1927.42  4839.3 1926.51  4855.2 1927.08
  4860.9 1926.63  4868.1 1927.65  4882.5 1926.86  4891.1 1927.62  4904.2 1926.97
  4935.9 1927.74  4941.7 1926.69  4963.3 1927.68  4979.2 1926.84  5022.5 1927.07
  5103.3 1925.68  5168.2 1925.40  5639.7 1925.58  5855.3 1924.74  6119.7 1924.70
  6120.2 1924.20  6125.2 1924.20  6125.7 1924.70  6607.3 1925.49  7019.4 1927.75
#Mann=5,-1,0
  4103.3    0.07       0  4617.7   0.035       0  5639.7   0.045       0
  6119.7   0.035       0  6125.7   0.045       0
Bank Sta=6119.7,6125.7
Exp/Cntr=0.3,0.1

Type RM Length L Ch R = 1,8927,427,427,427
BEGIN DESCRIPTION:
UCFB HW Trib 04-01 18.0
END DESCRIPTION:
XS GIS Cut Line= 5
      1384993.93      6983671.20      1384466.42      6983573.71
      1384266.77      6983686.55      1383830.00      6983913.00
      1383137.79      6985303.81
#Sta/Elev= 30
  4232.2 1926.89  4512.6 1927.26  4662.9 1927.39  4678.6 1924.94  4715.8 1924.74
  4759.9 1927.87  4825.1 1926.70  4890.0 1929.03  4927.6 1925.93  5008.8 1925.39
  5014.4 1927.72  5045.0 1928.67  5163.7 1925.07  5185.8 1927.00  5202.3 1925.19
  5207.9 1927.27  5246.6 1924.72  5252.2 1926.64  5268.7 1924.86  5318.6 1926.68
  5423.6 1924.59  5506.7 1926.64  5529.1 1923.13  5570.7 1923.06  5571.2 1922.56
  5576.7 1923.06  5607.5 1925.36  5757.7 1925.41  6212.1 1924.55  7043.5 1927.62
#Mann=5,-1,0
  4232.2    0.07       0  4512.6   0.035       0  5570.7   0.035       0
  5576.7   0.035       0  5757.7   0.045       0
Bank Sta=5570.7,5576.7
Exp/Cntr=0.3,0.1

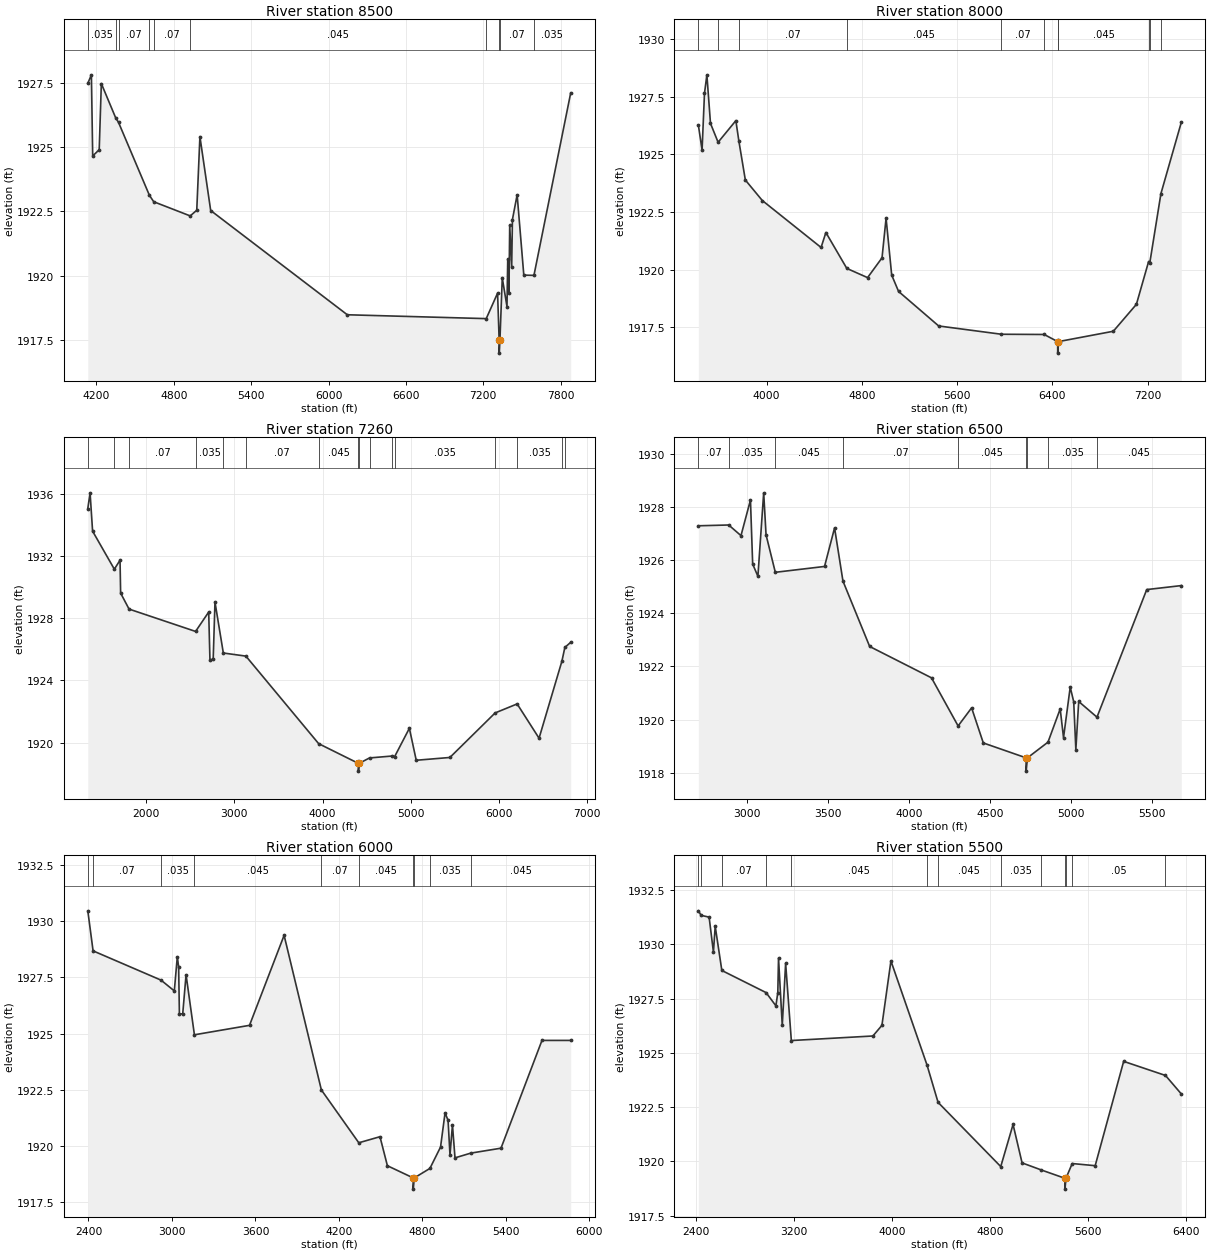
Type RM Length L Ch R = 1,8500,500,500,500
BEGIN DESCRIPTION:
UCFB HW Trib 04-01 17.0
END DESCRIPTION:
XS GIS Cut Line= 4
      1384642.57      6983567.46      1383993.87      6983478.39
      1383854.02      6983638.01      1381422.32      6985177.40
#Sta/Elev= 30
  4133.0 1927.47  4160.8 1927.80  4170.9 1924.65  4221.4 1924.89  4237.9 1927.46
  4349.1 1926.13  4371.4 1925.95  4610.7 1923.12  4644.2 1922.87  4927.1 1922.32
  4977.9 1922.54  5002.4 1925.40  5085.9 1922.53  6145.4 1918.48  7222.8 1918.33
  7310.8 1919.32  7323.0 1917.49  7323.5 1916.99  7329.0 1917.49  7347.2 1919.91
  7383.7 1918.80  7389.6 1920.64  7398.9 1919.34  7404.9 1921.96  7420.1 1920.33
  7426.0 1922.18  7462.5 1923.14  7514.2 1920.02  7592.8 1920.01  7878.0 1927.10
#Mann=10,-1,0
  4133.0   0.035       0  4349.1   0.045       0  4371.4    0.07       0
  4610.7   0.045       0  4644.2    0.07       0  4927.1   0.045       0
  7222.8    0.07       0  7323.0   0.045       0  7329.0    0.07       0
  7592.8   0.035       0
Bank Sta=7323,7329
Exp/Cntr=0.3,0.1

Type RM Length L Ch R = 1,8000,740,740,740
BEGIN DESCRIPTION:
UCFB HW Trib 04-01 16.0
END DESCRIPTION:
XS GIS Cut Line= 4
      1384745.88      6983485.00      1383422.08      6983304.44
      1383386.29      6983537.75      1381380.63      6985000.33
#Sta/Elev= 30
  3427.9 1926.28  3459.1 1925.19  3479.3 1927.65  3499.4 1928.46  3529.7 1926.35
  3593.6 1925.53  3742.7 1926.47  3767.8 1925.59  3822.4 1923.89  3964.7 1923.00
  4458.2 1920.96  4498.6 1921.61  4674.3 1920.05  4848.6 1919.65  4969.9 1920.51
  5003.9 1922.23  5051.1 1919.76  5108.8 1919.05  5445.6 1917.55  5972.3 1917.19
  6331.5 1917.18  6444.5 1916.87  6445.0 1916.37  6450.5 1916.87  6911.8 1917.32
  7105.6 1918.49  7208.2 1920.35  7218.0 1920.29  7311.5 1923.30  7482.3 1926.39
#Mann=11,-1,0
  3427.9   0.035       0  3593.6   0.045       0  3767.8    0.07       0
  4674.3   0.045       0  5972.3    0.07       0  6331.5   0.045       0
  6444.5   0.045       0  6450.5   0.045       0  7208.2    0.07       0
  7218.0   0.045       0  7311.5    0.07       0
Bank Sta=6444.5,6450.5
Exp/Cntr=0.3,0.1

Type RM Length L Ch R = 1,7260,760,760,760
BEGIN DESCRIPTION:
UCFB HW Trib 04-01 14.0
END DESCRIPTION:
XS GIS Cut Line= 4
      1386170.20      6983724.26      1382989.65      6983089.00
      1382591.94      6983497.70      1381456.21      6984717.07
#Sta/Elev= 30
  1336.3 1935.08  1362.0 1936.09  1390.6 1933.62  1637.3 1931.17  1701.9 1931.75
  1708.7 1929.63  1804.3 1928.60  2559.3 1927.16  2708.1 1928.41  2722.3 1925.33
  2759.1 1925.37  2779.4 1929.05  2874.2 1925.77  3130.2 1925.57  3955.8 1919.93
  4406.9 1918.66  4407.4 1918.16  4415.4 1918.66  4533.1 1919.01  4783.6 1919.13
  4818.6 1919.10  4985.3 1920.92  5063.2 1918.86  5445.2 1919.04  5958.6 1921.91
  6208.3 1922.49  6457.0 1920.28  6716.1 1925.24  6749.9 1926.13  6816.3 1926.46
#Mann=16,-1,0
  1336.3   0.045       0  1637.3   0.035       0  1804.3    0.07       0
  2559.3   0.035       0  2874.2   0.045       0  3130.2    0.07       0
  3955.8   0.045       0  4406.9   0.035       0  4415.4   0.045       0
  4533.1   0.035       0  4783.6   0.045       0  4818.6   0.035       0
  5958.6   0.045       0  6208.3   0.035       0  6716.1    0.07       0
  6749.9   0.035       0
Bank Sta=4406.9,4415.4
Exp/Cntr=0.3,0.1

Type RM Length L Ch R = 1,6500,500,500,500
BEGIN DESCRIPTION:
UCFB HW Trib 04-01 13.0
END DESCRIPTION:
XS GIS Cut Line= 3
      1385279.98      6983463.00      1383049.40      6982893.65
      1382430.01      6982613.01
#Sta/Elev= 30
  2697.9 1927.29  2885.2 1927.32  2961.1 1926.92  3019.6 1928.26  3033.3 1925.85
  3065.6 1925.39  3101.3 1928.53  3115.9 1926.95  3173.1 1925.54  3477.1 1925.76
  3539.0 1927.21  3590.8 1925.21  3755.7 1922.75  4137.6 1921.57  4301.9 1919.76
  4385.3 1920.44  4457.5 1919.12  4721.6 1918.56  4722.1 1918.06  4730.1 1918.56
  4856.9 1919.15  4932.3 1920.40  4952.9 1919.32  4994.2 1921.22  5015.8 1920.67
  5029.0 1918.87  5046.6 1920.68  5159.5 1920.09  5466.7 1924.89  5680.0 1925.04
#Mann=9,-1,0
  2697.9    0.07       0  2885.2   0.035       0  3173.1   0.045       0
  3590.8    0.07       0  4301.9   0.045       0  4721.6   0.035       0
  4730.1   0.045       0  4856.9   0.035       0  5159.5   0.045       0
Bank Sta=4721.6,4730.1
Exp/Cntr=0.3,0.1

Type RM Length L Ch R = 1,6000,500,500,500
BEGIN DESCRIPTION:
UCFB HW Trib 04-01 12.0
END DESCRIPTION:
XS GIS Cut Line= 3
      1385780.00      6983513.00      1383370.96      6982522.03
      1382529.95      6982312.99
#Sta/Elev= 30
  2395.1 1930.46  2433.0 1928.68  2921.4 1927.38  3016.9 1926.90  3038.5 1928.42
  3048.1 1927.96  3053.5 1925.88  3077.4 1925.88  3101.4 1927.62  3161.4 1924.95
  3557.5 1925.37  3806.2 1929.37  4074.0 1922.50  4343.1 1920.15  4495.4 1920.42
  4548.7 1919.13  4733.8 1918.59  4734.3 1918.09  4742.4 1918.59  4854.3 1919.01
  4930.8 1919.96  4963.2 1921.48  4984.8 1921.15  4998.7 1919.61  5016.4 1920.94
  5034.7 1919.48  5147.9 1919.69  5365.4 1919.91  5659.9 1924.70  5866.6 1924.70
#Mann=10,-1,0
  2395.1   0.035       0  2433.0    0.07       0  2921.4   0.035       0
  3161.4   0.045       0  4074.0    0.07       0  4343.1   0.045       0
  4733.8   0.035       0  4742.4   0.045       0  4854.3   0.035       0
  5147.9   0.045       0
Bank Sta=4733.8,4742.4
Exp/Cntr=0.3,0.1

Type RM Length L Ch R = 1,5500,500,500,500
BEGIN DESCRIPTION:
UCFB HW Trib 04-01 11.0
END DESCRIPTION:
XS GIS Cut Line= 3
      1385930.00      6983513.00      1383724.52      6982168.48
      1382380.03      6981963.00
#Sta/Elev= 30
  2417.0 1931.55  2440.1 1931.34  2504.8 1931.26  2540.0 1929.65  2554.5 1930.84
  2608.7 1928.80  2970.1 1927.78  3050.2 1927.17  3065.7 1927.78  3071.5 1929.37
  3102.1 1926.27  3129.6 1929.13  3176.1 1925.57  3842.2 1925.78  3915.8 1926.27
  3989.4 1929.24  4284.1 1924.44  4374.3 1922.72  4886.1 1919.76  4986.6 1921.70
  5060.2 1919.93  5218.8 1919.60  5410.0 1919.22  5410.5 1918.72  5418.6 1919.22
  5469.6 1919.90  5657.1 1919.80  5889.7 1924.61  6231.3 1923.96  6360.1 1923.11
#Mann=13,-1,0
  2417.0   0.045       0  2440.1   0.035       0  2608.7    0.07       0
  2970.1   0.035       0  3176.1   0.045       0  4284.1    0.07       0
  4374.3   0.045       0  4886.1   0.035       0  5218.8   0.045       0
  5410.0   0.035       0  5418.6   0.045       0  5469.6    0.05       0
  6231.3   0.045       0
Bank Sta=5410,5418.6
Exp/Cntr=0.3,0.1

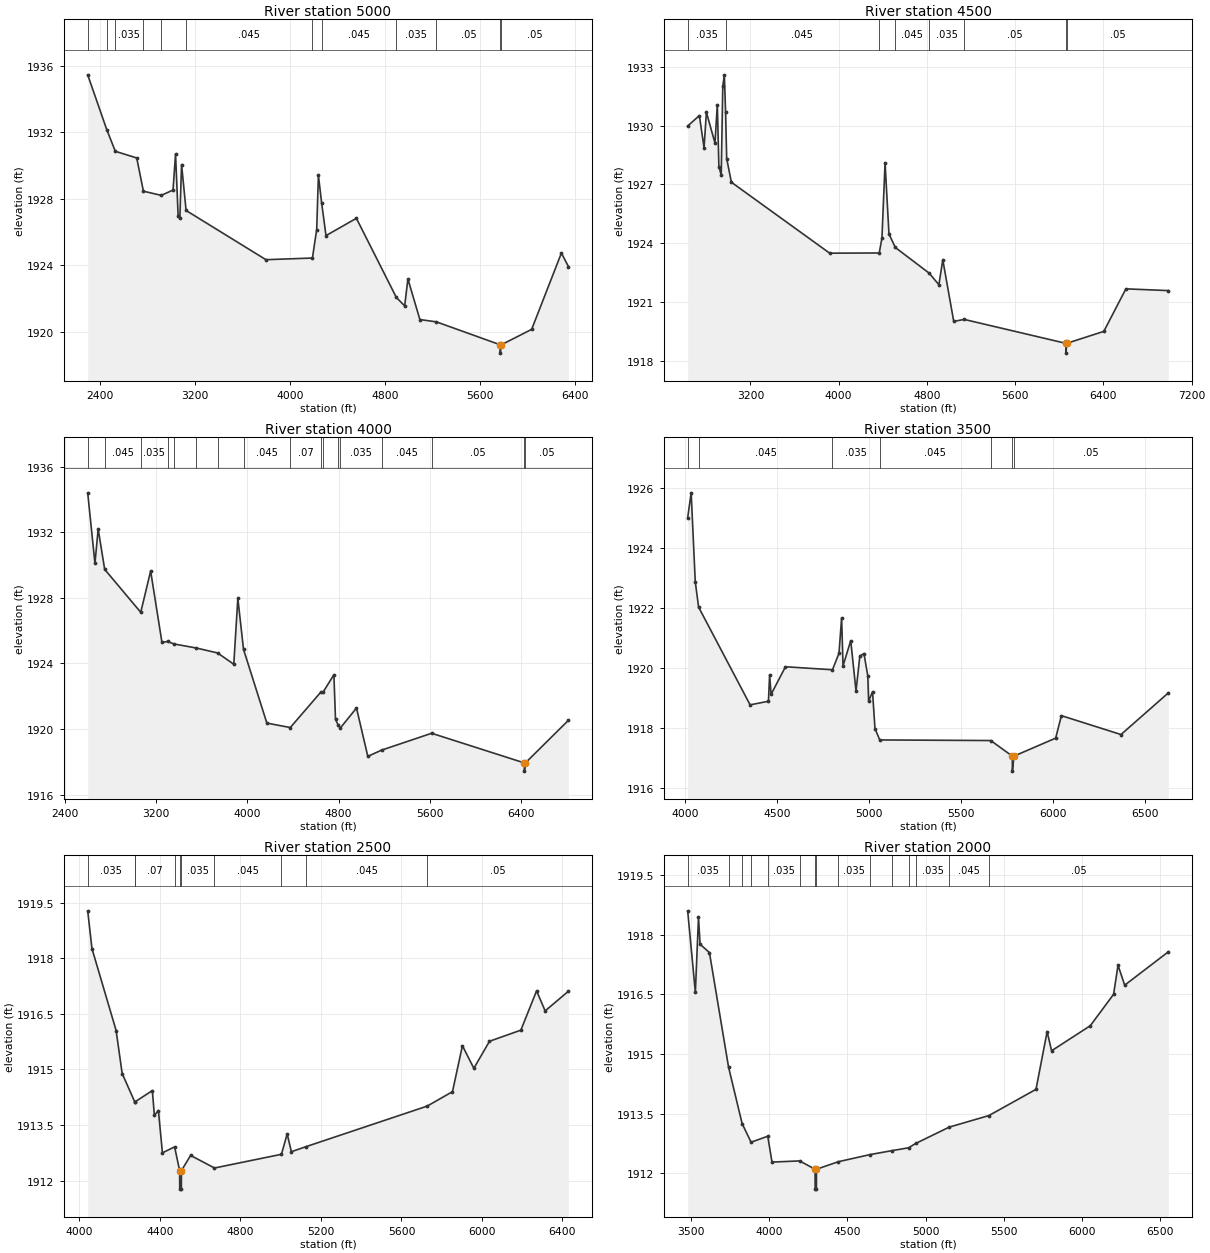
Type RM Length L Ch R = 1,5000,500,500,500
BEGIN DESCRIPTION:
UCFB HW Trib 04-01 10.0
END DESCRIPTION:
XS GIS Cut Line= 3
      1386179.98      6983512.98      1384078.08      6981814.94
      1382736.00      6981864.66
#Sta/Elev= 30
  2297.9 1935.44  2458.9 1932.13  2530.4 1930.84  2710.4 1930.44  2766.7 1928.44
  2917.1 1928.19  3015.9 1928.51  3037.1 1930.68  3059.0 1926.94  3073.4 1926.83
  3087.8 1930.04  3125.8 1927.28  3797.8 1924.32  4188.8 1924.42  4224.8 1926.13
  4239.2 1929.39  4266.0 1927.76  4303.1 1925.77  4559.0 1926.81  4895.1 1922.05
  4965.1 1921.54  4992.3 1923.16  5093.1 1920.72  5232.6 1920.58  5769.3 1919.20
  5769.8 1918.70  5777.9 1919.20  6033.8 1920.13  6284.0 1924.72  6343.0 1923.91
#Mann=12,-1,0
  2297.9   0.035       0  2458.9   0.045       0  2530.4   0.035       0
  2766.7    0.07       0  2917.1   0.035       0  3125.8   0.045       0
  4188.8    0.07       0  4266.0   0.045       0  4895.1   0.035       0
  5232.6    0.05       0  5769.3   0.035       0  5777.9    0.05       0
Bank Sta=5769.3,5777.9
Exp/Cntr=0.3,0.1

Type RM Length L Ch R = 1,4500,500,500,500
BEGIN DESCRIPTION:
UCFB HW Trib 04-01 9.0
END DESCRIPTION:
XS GIS Cut Line= 3
      1386030.02      6983113.02      1384368.02      6981425.55
      1382379.97      6981463.00
#Sta/Elev= 30
  2631.5 1929.98  2737.5 1930.51  2780.0 1928.87  2801.2 1930.68  2879.0 1929.11
  2900.2 1931.07  2914.4 1927.91  2935.6 1927.47  2949.7 1932.00  2963.8 1932.59
  2975.2 1930.70  2985.1 1928.32  3027.5 1927.11  3918.5 1923.49  4367.8 1923.50
  4392.3 1924.26  4420.6 1928.10  4455.9 1924.47  4513.5 1923.78  4820.4 1922.47
  4908.5 1921.88  4943.8 1923.15  5043.0 1920.01  5138.1 1920.11  6058.9 1918.89
  6059.4 1918.39  6067.5 1918.89  6403.3 1919.50  6603.3 1921.67  6988.4 1921.58
#Mann=8,-1,0
  2631.5   0.035       0  2975.2   0.045       0  4367.8    0.07       0
  4513.5   0.045       0  4820.4   0.035       0  5138.1    0.05       0
  6058.9   0.035       0  6067.5    0.05       0
Bank Sta=6058.9,6067.5
Exp/Cntr=0.3,0.1

Type RM Length L Ch R = 1,4000,500,500,500
BEGIN DESCRIPTION:
UCFB HW Trib 04-01 8.0
END DESCRIPTION:
XS GIS Cut Line= 3
      1386523.96      6982658.40      1384721.28      6981071.73
      1382915.20      6981269.72
#Sta/Elev= 30
  2598.5 1934.41  2662.1 1930.11  2690.4 1932.20  2747.5 1929.74  3064.0 1927.12
  3150.8 1929.64  3249.9 1925.29  3300.5 1925.34  3355.1 1925.19  3553.0 1924.94
  3738.6 1924.64  3880.4 1923.95  3916.0 1927.97  3965.8 1924.86  4170.7 1920.36
  4376.4 1920.09  4641.7 1922.23  4663.3 1922.24  4758.9 1923.31  4773.1 1920.58
  4795.8 1920.26  4814.2 1920.05  4957.2 1921.28  5056.6 1918.33  5176.9 1918.71
  5616.6 1919.74  6430.5 1917.93  6431.0 1917.43  6439.2 1917.93  6816.9 1920.53
#Mann=17,-1,0
  2598.5   0.035       0  2747.5   0.045       0  3064.0   0.035       0
  3300.5   0.045       0  3355.1   0.035       0  3553.0   0.045       0
  3738.6    0.07       0  3965.8   0.045       0  4376.4    0.07       0
  4641.7   0.045       0  4663.3   0.035       0  4795.8   0.045       0
  4814.2   0.035       0  5176.9   0.045       0  5616.6    0.05       0
  6430.5   0.035       0  6439.2    0.05       0
Bank Sta=6430.5,6439.2
Exp/Cntr=0.3,0.1

Type RM Length L Ch R = 1,3500,1000,1000,1000
BEGIN DESCRIPTION:
UCFB HW Trib 04-01 7.0
END DESCRIPTION:
XS GIS Cut Line= 3
      1385767.17      6981313.03      1385005.00      6980687.18
      1383448.46      6981154.24
#Sta/Elev= 30
  4013.8 1925.02  4032.8 1925.85  4055.0 1922.89  4073.1 1922.04  4353.0 1918.78
  4452.6 1918.90  4459.0 1919.78  4466.9 1919.13  4545.1 1920.05  4800.4 1919.95
  4835.8 1920.50  4850.1 1921.68  4857.7 1920.08  4899.6 1920.92  4928.3 1919.24
  4949.1 1920.41  4971.4 1920.49  4992.2 1919.75  4996.8 1918.90  5018.0 1919.22
  5031.3 1917.99  5057.2 1917.61  5660.2 1917.59  5777.3 1917.07  5777.8 1916.57
  5786.3 1917.07  6012.7 1917.67  6044.0 1918.42  6367.7 1917.79  6625.1 1919.18
#Mann=7,-1,0
  4013.8    0.07       0  4073.1   0.045       0  4800.4   0.035       0
  5057.2   0.045       0  5660.2    0.05       0  5777.3   0.035       0
  5786.3    0.05       0
Bank Sta=5777.3,5786.3
Exp/Cntr=0.3,0.1

Type RM Length L Ch R = 1,2500,500,500,500
BEGIN DESCRIPTION:
UCFB HW Trib 04-01 5.0
END DESCRIPTION:
XS GIS Cut Line= 4
      1385736.17      6979859.40      1384880.00      6979863.00
      1384809.79      6979937.57      1383749.82      6980896.55
#Sta/Elev= 30
  4041.4 1919.28  4062.6 1918.26  4182.6 1916.05  4212.6 1914.89  4274.7 1914.13
  4275.1 1914.12  4362.6 1914.43  4372.6 1913.76  4392.6 1913.89  4412.6 1912.75
  4473.1 1912.91  4498.1 1912.27  4498.6 1911.77  4506.6 1911.77  4507.1 1912.27
  4552.6 1912.68  4671.2 1912.34  5003.8 1912.71  5032.3 1913.26  5053.2 1912.78
  5128.1 1912.92  5727.7 1914.01  5853.5 1914.40  5902.8 1915.64  5959.6 1915.03
  6037.3 1915.76  6193.2 1916.06  6271.2 1917.12  6313.8 1916.58  6429.4 1917.11
#Mann=10,-1,0
  4041.4   0.035       0  4274.7   0.045       0  4275.1    0.07       0
  4473.1   0.035       0  4498.1   0.045       0  4507.1   0.035       0
  4671.2   0.045       0  5003.8   0.035       0  5128.1   0.045       0
  5727.7    0.05       0
Bank Sta=4498.1,4507.1
Exp/Cntr=0.3,0.1

Type RM Length L Ch R = 1,2000,500,500,500
BEGIN DESCRIPTION:
UCFB HW Trib 04-01 4.0
END DESCRIPTION:
XS GIS Cut Line= 4
      1385824.20      6979818.77      1384393.48      6979763.00
      1384342.06      6979837.70      1383319.50      6981007.34
#Sta/Elev= 30
  3477.5 1918.60  3526.7 1916.55  3546.8 1918.44  3556.8 1917.76  3616.8 1917.55
  3739.1 1914.67  3825.8 1913.25  3883.2 1912.78  3990.0 1912.93  4017.1 1912.28
  4193.8 1912.31  4292.8 1912.10  4293.3 1911.60  4301.3 1911.60  4301.8 1912.10
  4441.9 1912.29  4645.9 1912.47  4787.9 1912.57  4891.7 1912.64  4937.2 1912.75
  5151.5 1913.16  5404.8 1913.45  5706.5 1914.11  5777.7 1915.56  5806.2 1915.08
  6053.9 1915.71  6202.9 1916.50  6231.4 1917.23  6274.1 1916.73  6553.6 1917.57
#Mann=15,-1,0
  3477.5   0.035       0  3739.1   0.045       0  3825.8    0.07       0
  3883.2   0.045       0  3990.0   0.035       0  4193.8   0.045       0
  4292.8   0.035       0  4301.8   0.045       0  4441.9   0.035       0
  4645.9   0.045       0  4787.9   0.035       0  4891.7    0.07       0
  4937.2   0.035       0  5151.5   0.045       0  5404.8    0.05       0
Bank Sta=4292.8,4301.8
Exp/Cntr=0.3,0.1

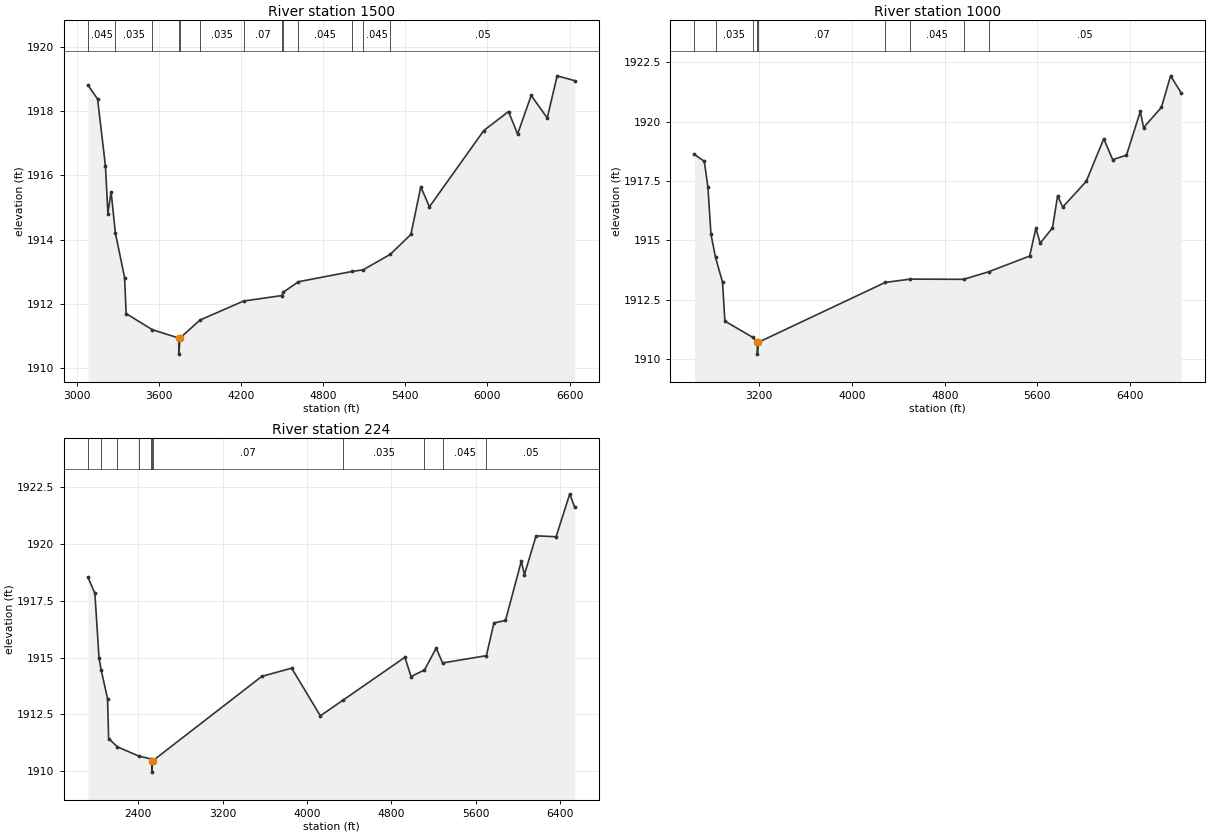
Type RM Length L Ch R = 1,1500,500,500,500
BEGIN DESCRIPTION:
UCFB HW Trib 04-01 3.0
END DESCRIPTION:
XS GIS Cut Line= 3
      1385630.01      6978962.99      1383874.33      6979737.67
      1382972.54      6981104.01
#Sta/Elev= 30
  3081.0 1918.80  3151.0 1918.37  3208.5 1916.29  3226.4 1914.81  3249.7 1915.49
  3281.3 1914.20  3348.4 1912.82  3359.7 1911.70  3550.4 1911.20  3744.2 1910.94
  3744.7 1910.44  3753.5 1910.94  3899.8 1911.50  4217.7 1912.09  4497.3 1912.26
  4509.3 1912.37  4618.9 1912.69  5011.6 1913.01  5091.7 1913.06  5289.5 1913.54
  5440.6 1914.16  5512.9 1915.64  5576.1 1915.02  5973.5 1917.39  6154.1 1917.98
  6220.4 1917.28  6319.7 1918.48  6437.1 1917.78  6509.4 1919.09  6637.1 1918.94
#Mann=13,-1,0
  3081.0   0.045       0  3281.3   0.035       0  3550.4    0.07       0
  3744.2   0.045       0  3753.5    0.07       0  3899.8   0.035       0
  4217.7    0.07       0  4497.3   0.035       0  4509.3    0.07       0
  4618.9   0.045       0  5011.6   0.035       0  5091.7   0.045       0
  5289.5    0.05       0
Bank Sta=3744.2,3753.5
Exp/Cntr=0.3,0.1

Type RM Length L Ch R = 1,1000,776,776,776
BEGIN DESCRIPTION:
UCFB HW Trib 04-01 2.0
END DESCRIPTION:
XS GIS Cut Line= 3
      1385643.93      6978887.36      1383406.59      6979637.66
      1382619.58      6981301.30
#Sta/Elev= 30
  2640.2 1918.62  2724.8 1918.33  2756.3 1917.25  2782.6 1915.26  2822.0 1914.28
  2882.5 1913.24  2902.8 1911.60  3142.0 1910.92  3182.8 1910.71  3183.3 1910.21
  3192.1 1910.71  4287.4 1913.23  4503.9 1913.37  4964.4 1913.36  5180.2 1913.68
  5533.4 1914.34  5586.7 1915.51  5624.4 1914.88  5730.5 1915.53  5774.8 1916.88
  5819.0 1916.40  6022.3 1917.49  6173.0 1919.28  6249.9 1918.40  6369.2 1918.59
  6488.5 1920.43  6516.8 1919.75  6670.5 1920.60  6749.8 1921.93  6840.4 1921.22
#Mann=9,-1,0
  2640.2   0.045       0  2822.0   0.035       0  3142.0    0.07       0
  3182.8   0.035       0  3192.1    0.07       0  4287.4   0.035       0
  4503.9   0.045       0  4964.4   0.035       0  5180.2    0.05       0
Bank Sta=3182.8,3192.1
Exp/Cntr=0.3,0.1

Type RM Length L Ch R = 1,224,0,0,0
BEGIN DESCRIPTION:
UCFB HW Trib 04-01 1.0
END DESCRIPTION:
XS GIS Cut Line= 4
      1385608.87      6978874.50      1382820.46      6979267.73
      1382529.51      6979721.58      1382559.88      6980983.82
#Sta/Elev= 30
  1922.6 1918.54  1987.8 1917.84  2027.5 1914.98  2047.8 1914.46  2108.3 1913.19
  2118.4 1911.44  2202.5 1911.07  2403.3 1910.67  2520.0 1910.54  2527.7 1910.46
  2528.2 1909.96  2537.1 1910.46  3572.6 1914.18  3855.4 1914.54  4127.4 1912.44
  4345.8 1913.14  4929.8 1915.02  4988.4 1914.17  5115.5 1914.46  5226.5 1915.42
  5287.6 1914.77  5703.1 1915.09  5774.3 1916.53  5884.3 1916.64  6034.3 1919.25
  6064.3 1918.66  6174.4 1920.37  6364.4 1920.33  6494.5 1922.22  6540.3 1921.63
#Mann=11,-1,0
  1922.6   0.045       0  2047.8   0.035       0  2202.5    0.07       0
  2403.3   0.035       0  2520.0    0.07       0  2527.7   0.035       0
  2537.1    0.07       0  4345.8   0.035       0  5115.5    0.07       0
  5287.6   0.045       0  5703.1    0.05       0
Bank Sta=2527.7,2537.1
Exp/Cntr=0.3,0.1

Chan Stop Cuts=-1