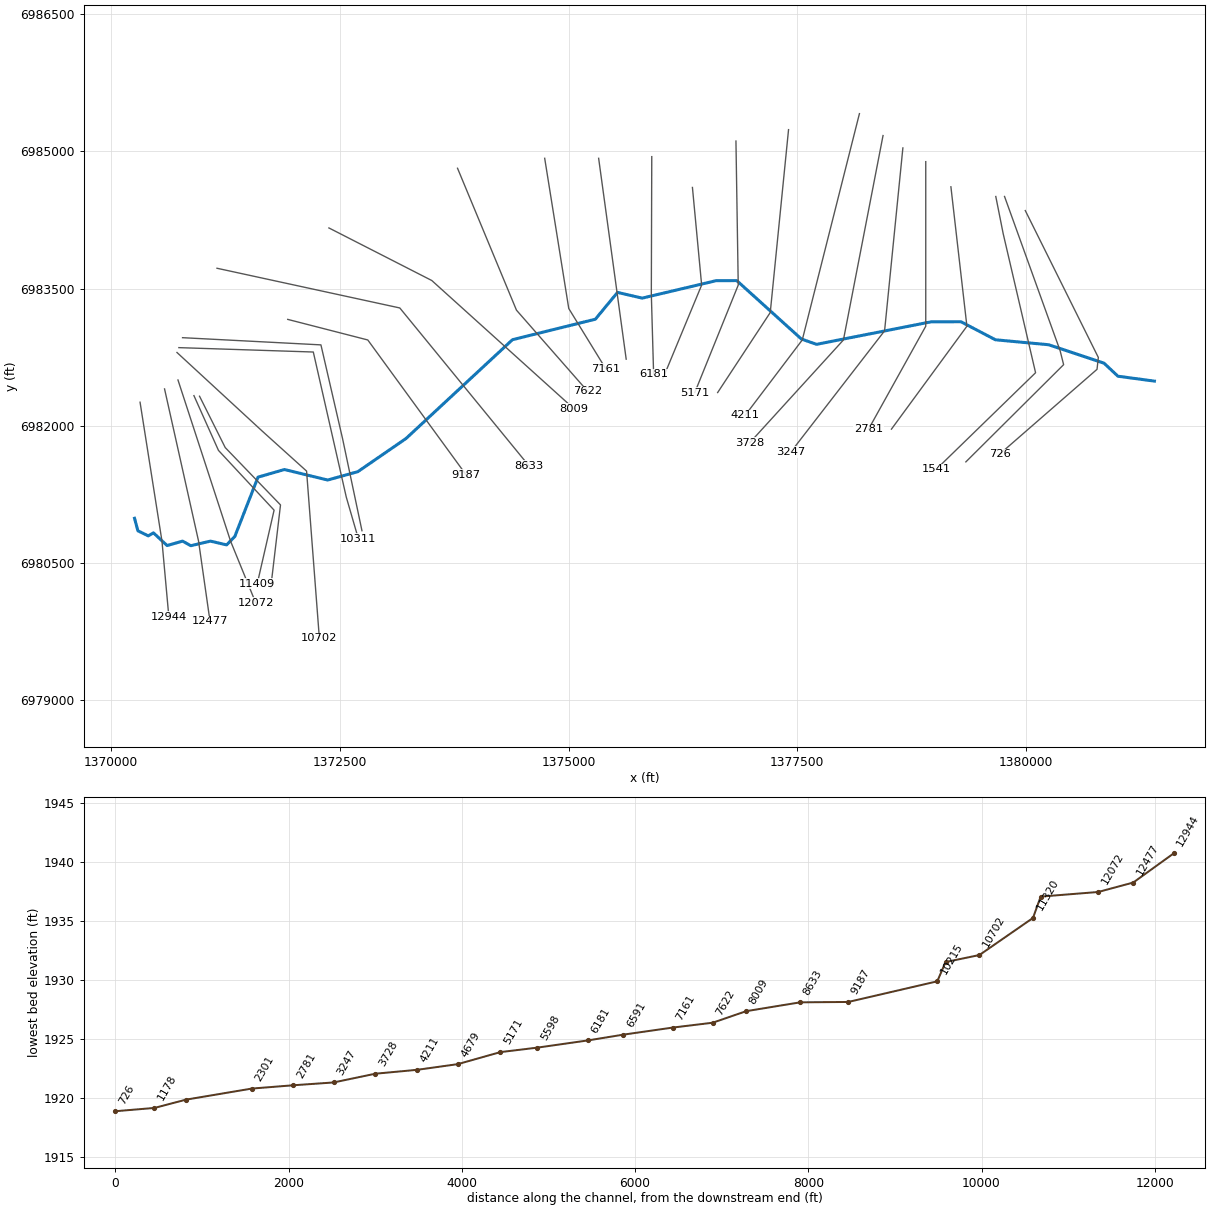
--- UCFB HW Trib 04-02.prj (project) ---

Proj Title=UCFB HW Trib 04-02 Base Level Engineering
Current Plan=p01
Default Exp/Contr=0.3,0.1
English Units
Geom File=g01
Flow File=f01
Plan File=p01
BEGIN DESCRIPTION:
UCFB HW Trib 04-02
END DESCRIPTION:

--- UCFB HW Trib 04-02.p01 (plan) ---

Plan Title=Multiple Run
Short Identifier=Multiple
Geom File=g01
Flow File=f01
Subcritical Flow
K Sum by GR= 0
Std Step Tol= 0.01
Critical Tol= 0.01
Num of Std Step Trials= 20
Max Error Tol= 0.3
Flow Tol Ratio= 0.001
Split Flow NTrial= 30
Split Flow Tol= 0.02
Split Flow Ratio= 0.02
Log Output Level= 0
Friction Slope Method= 1
Unsteady Friction Slope Method= 2
Unsteady Bridges Friction Slope Method= 1
Parabolic Critical Depth
Global Vel Dist=  1 , 1 , 1
Global Log Level= 0
CheckData=True
Encroach Param= -1, 0, 0, 0
BEGIN DESCRIPTION:
Multiple Run
END DESCRIPTION:

--- UCFB HW Trib 04-02.f01 (steady flow) ---

Flow Title=Multiple
Number of Profiles=7
Profile Names=10-year,25-year,50-year,1pct_min,100-year,1pct_plu,500-year
River Rch & RM= UCFB HW Trib 04-,Reach-1,12944
     268     371     456     278     554    1106     831
River Rch & RM= UCFB HW Trib 04-,Reach-1,3728
     292     406     500     305     609    1215     916
Boundary for River Rch & Prof#=UCFB HW Trib 04-,Reach-1,1
Up Type=0
Dn Type=3
Dn Slope=0.005
Boundary for River Rch & Prof#=UCFB HW Trib 04-,Reach-1,2
Up Type=0
Dn Type=3
Dn Slope=0.005
Boundary for River Rch & Prof#=UCFB HW Trib 04-,Reach-1,3
Up Type=0
Dn Type=3
Dn Slope=0.005
Boundary for River Rch & Prof#=UCFB HW Trib 04-,Reach-1,4
Up Type=0
Dn Type=3
Dn Slope=0.005
Boundary for River Rch & Prof#=UCFB HW Trib 04-,Reach-1,5
Up Type=0
Dn Type=3
Dn Slope=0.005
Boundary for River Rch & Prof#=UCFB HW Trib 04-,Reach-1,6
Up Type=0
Dn Type=3
Dn Slope=0.005
Boundary for River Rch & Prof#=UCFB HW Trib 04-,Reach-1,7
Up Type=0
Dn Type=3
Dn Slope=0.005

--- UCFB HW Trib 04-02.g01 (geometry) ---

Geom Title=Existing Conditions

River Reach=UCFB HW Trib 04-,Reach-1
Reach XY= 30
      1370255.00      6980988.00      1370291.38      6980851.41
      1370405.09      6980795.77      1370461.67      6980828.70
      1370610.89      6980689.96      1370780.00      6980738.39
      1370870.41      6980688.17      1371084.83      6980738.32
      1371261.76      6980697.12      1371351.39      6980789.47
      1371605.00      6981438.00      1371893.79      6981521.39
      1372366.06      6981406.47      1372695.93      6981497.62
      1373222.84      6981860.25      1374386.90      6982940.98
      1375293.15      6983164.94      1375535.04      6983458.09
      1375805.00      6983395.56      1376615.50      6983586.78
      1376839.06      6983587.08      1377545.21      6982948.52
      1377710.94      6982890.26      1378965.50      6983136.78
      1379289.79      6983137.49      1379666.97      6982939.96
      1380249.07      6982885.76      1380853.50      6982684.39
      1381006.46      6982541.54      1381405.00      6982488.00

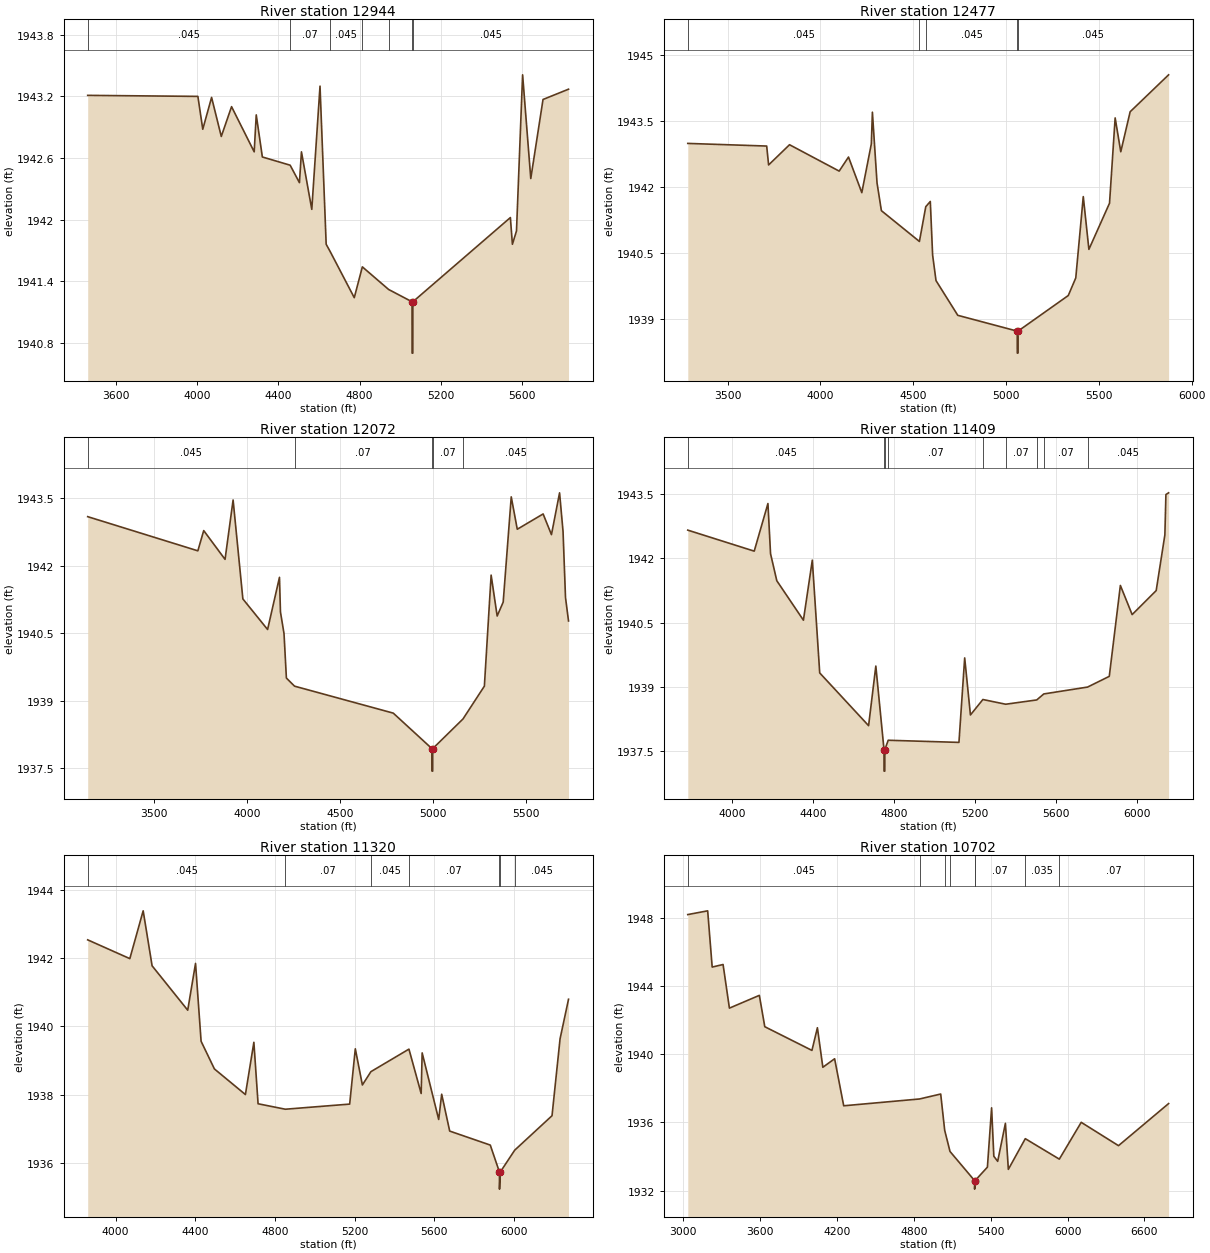
Type RM Length L Ch R = 1,12944,467,467,467
BEGIN DESCRIPTION:
UCFB HW Trib 04-02 17.0
END DESCRIPTION:
XS GIS Cut Line= 3
      1370315.32      6982257.49      1370555.00      6980738.00
      1370630.00      6979912.98
#Sta/Elev= 30
  3461.3 1943.21  4003.6 1943.20  4027.7 1942.88  4071.1 1943.19  4118.8 1942.81
  4169.4 1943.10  4280.8 1942.66  4290.9 1943.02  4321.0 1942.61  4457.8 1942.53
  4503.5 1942.36  4513.4 1942.66  4564.3 1942.10  4604.8 1943.30  4635.1 1941.76
  4654.6 1941.69  4773.4 1941.24  4813.2 1941.54  4942.4 1941.32  5057.8 1941.20
  5058.1 1940.70  5061.6 1940.70  5061.8 1941.20  5541.8 1942.02  5551.8 1941.76
  5571.9 1941.89  5602.0 1943.41  5642.2 1942.40  5702.5 1943.17  5828.0 1943.27
#Mann=7,-1,0
  3461.3   0.045       0  4457.8    0.07       0  4654.6   0.045       0
  4813.2    0.07       0  4942.4   0.045       0  5057.8   0.045       0
  5061.8   0.045       0
Bank Sta=5057.8,5061.8
Exp/Cntr=0.3,0.1

Type RM Length L Ch R = 1,12477,405,405,405
BEGIN DESCRIPTION:
UCFB HW Trib 04-02 16.0
END DESCRIPTION:
XS GIS Cut Line= 3
      1370583.12      6982402.79      1370955.00      6980738.00
      1371080.00      6979863.00
#Sta/Elev= 30
  3286.1 1943.00  3711.1 1942.94  3721.4 1942.51  3834.1 1942.97  4101.5 1942.37
  4151.7 1942.69  4223.4 1941.88  4274.7 1942.99  4280.4 1943.71  4305.4 1942.10
  4328.9 1941.47  4533.7 1940.77  4567.8 1941.56  4592.3 1941.68  4604.8 1940.46
  4623.0 1939.88  4740.3 1939.09  5060.6 1938.73  5060.9 1938.23  5064.4 1938.23
  5064.6 1938.73  5335.4 1939.54  5375.8 1939.94  5416.2 1941.79  5446.5 1940.59
  5557.6 1941.64  5587.9 1943.58  5618.2 1942.81  5668.7 1943.72  5875.8 1944.56
#Mann=5,-1,0
  3286.1   0.045       0  4533.7    0.07       0  4567.8   0.045       0
  5060.6   0.045       0  5064.6   0.045       0
Bank Sta=5060.6,5064.6
Exp/Cntr=0.3,0.1

Type RM Length L Ch R = 1,12072,663,663,663
BEGIN DESCRIPTION:
UCFB HW Trib 04-02 15.0
END DESCRIPTION:
XS GIS Cut Line= 3
      1370729.87      6982500.50      1371305.00      6980738.00
      1371579.99      6980063.03
#Sta/Elev= 30
  3145.4 1943.09  3737.1 1942.33  3768.6 1942.78  3883.2 1942.14  3926.4 1943.46
  3978.9 1941.26  4111.7 1940.58  4175.5 1941.74  4180.8 1940.97  4199.9 1940.49
  4212.7 1939.50  4256.4 1939.32  4786.8 1938.72  4994.7 1937.93  4995.0 1937.43
  4998.5 1937.43  4998.7 1937.93  5161.3 1938.59  5276.2 1939.32  5312.5 1941.79
  5344.9 1940.88  5377.3 1941.19  5420.5 1943.53  5452.9 1942.81  5591.8 1943.15
  5636.5 1942.69  5680.1 1943.62  5698.8 1942.76  5712.0 1941.29  5728.2 1940.77
#Mann=5,-1,0
  3145.4   0.045       0  4256.4    0.07       0  4994.7    0.07       0
  4998.7    0.07       0  5161.3   0.045       0
Bank Sta=4994.7,4998.7
Exp/Cntr=0.3,0.1

Type RM Length L Ch R = 1,11409,89,89,89
BEGIN DESCRIPTION:
UCFB HW Trib 04-02 14.6
END DESCRIPTION:
XS GIS Cut Line= 4
      1370904.42      6982329.10      1371172.68      6981730.29
      1371780.69      6981076.91      1371596.48      6980272.49
#Sta/Elev= 30
  3781.8 1942.66  4109.8 1942.17  4177.5 1943.28  4190.4 1942.11  4221.3 1941.48
  4352.7 1940.56  4396.6 1941.96  4433.2 1939.33  4674.5 1938.10  4710.2 1939.49
  4750.6 1937.54  4750.9 1937.04  4754.5 1937.04  4754.7 1937.54  4771.3 1937.76
  5120.6 1937.71  5148.9 1939.68  5177.3 1938.35  5238.8 1938.71  5351.3 1938.60
  5504.6 1938.70  5539.5 1938.84  5755.6 1939.00  5862.8 1939.25  5917.6 1941.37
  5975.7 1940.69  6094.4 1941.25  6137.3 1942.55  6142.4 1943.49  6155.7 1943.53
#Mann=9,-1,0
  3781.8   0.045       0  4750.6    0.07       0  4754.7   0.045       0
  4771.3    0.07       0  5238.8   0.045       0  5351.3    0.07       0
  5504.6   0.045       0  5539.5    0.07       0  5755.6   0.045       0
Bank Sta=4750.6,4754.7
Exp/Cntr=0.3,0.1

Type RM Length L Ch R = 1,11320,618,618,618
BEGIN DESCRIPTION:
UCFB HW Trib 04-02 12.5
END DESCRIPTION:
XS GIS Cut Line= 4
      1370965.76      6982322.61      1371246.35      6981761.43
      1371850.82      6981134.01      1371743.68      6980225.75
#Sta/Elev= 30
  3860.3 1942.53  4071.7 1941.98  4138.7 1943.38  4183.5 1941.77  4362.3 1940.47
  4401.5 1941.84  4429.4 1939.56  4496.2 1938.75  4651.8 1938.00  4694.3 1939.53
  4715.4 1937.73  4852.1 1937.57  5175.1 1937.72  5203.4 1939.34  5238.9 1938.28
  5281.7 1938.67  5472.6 1939.33  5533.9 1938.03  5538.9 1939.22  5621.9 1937.27
  5636.9 1938.01  5677.1 1936.93  5880.8 1936.52  5926.8 1935.73  5927.1 1935.23
  5930.9 1935.73  6003.3 1936.37  6190.7 1937.38  6231.0 1939.63  6273.5 1940.79
#Mann=7,-1,0
  3860.3   0.045       0  4852.1    0.07       0  5281.7   0.045       0
  5472.6    0.07       0  5926.8    0.07       0  5930.9    0.07       0
  6003.3   0.045       0
Bank Sta=5926.8,5930.9
Exp/Cntr=0.3,0.1

Type RM Length L Ch R = 1,10702,391,391,391
BEGIN DESCRIPTION:
UCFB HW Trib 04-02 14.2
END DESCRIPTION:
XS GIS Cut Line= 4
      1370718.98      6982801.07      1371653.64      6981939.00
      1372135.84      6981504.14      1372275.60      6979678.12
#Sta/Elev= 30
  3036.6 1948.20  3191.8 1948.42  3227.0 1945.12  3312.0 1945.27  3361.4 1942.71
  3595.0 1943.46  3637.5 1941.62  4005.5 1940.23  4048.1 1941.56  4090.6 1939.24
  4182.5 1939.74  4253.4 1936.98  4845.3 1937.38  5010.3 1937.67  5041.5 1935.54
  5082.9 1934.30  5274.7 1932.59  5275.0 1932.09  5278.8 1932.59  5374.8 1933.38
  5407.5 1936.86  5424.9 1934.02  5455.0 1933.72  5515.2 1935.95  5538.2 1933.25
  5670.4 1935.05  5936.0 1933.85  6106.9 1936.01  6397.8 1934.64  6788.8 1937.11
#Mann=8,-1,0
  3036.6   0.045       0  4845.3    0.07       0  5041.5   0.045       0
  5082.9    0.07       0  5274.7    0.07       0  5278.8    0.07       0
  5670.4   0.035       0  5936.0    0.07       0
Bank Sta=5274.7,5278.8
Exp/Cntr=0.3,0.1

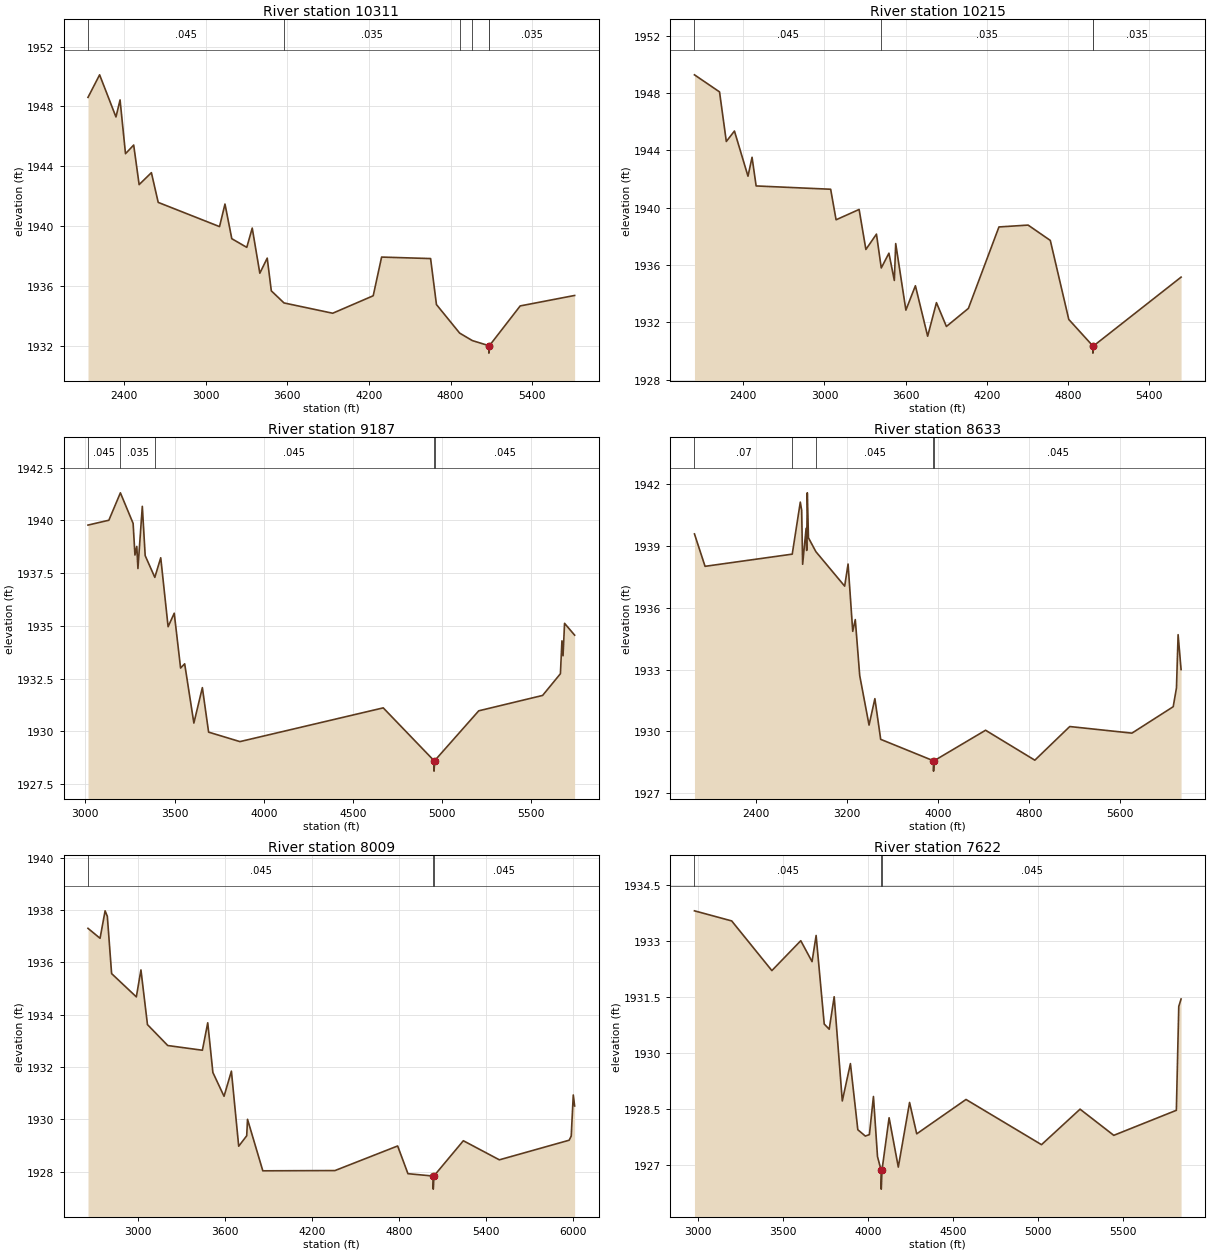
Type RM Length L Ch R = 1,10311,96,96,96
BEGIN DESCRIPTION:
UCFB HW Trib 04-02 14.0
END DESCRIPTION:
XS GIS Cut Line= 4
      1370739.71      6982854.18      1372209.45      6982806.21
      1372570.01      6981219.19      1372702.39      6980763.00
#Sta/Elev= 30
  2137.1 1948.61  2222.4 1950.12  2342.5 1947.30  2372.5 1948.44  2412.5 1944.84
  2472.6 1945.42  2512.6 1942.77  2602.6 1943.57  2652.7 1941.58  3102.9 1939.96
  3142.9 1941.47  3193.0 1939.15  3303.0 1938.57  3343.0 1939.86  3398.8 1936.84
  3453.1 1937.85  3483.1 1935.66  3576.2 1934.85  3933.9 1934.16  4231.3 1935.33
  4292.9 1937.92  4652.6 1937.82  4695.7 1934.74  4866.1 1932.83  4958.9 1932.33
  5080.3 1931.99  5080.6 1931.49  5084.6 1931.99  5310.6 1934.65  5710.1 1935.35
#Mann=6,-1,0
  2137.1   0.045       0  3576.2   0.035       0  4866.1    0.07       0
  4958.9   0.035       0  5080.3   0.035       0  5084.6   0.035       0
Bank Sta=5080.3,5084.6
Exp/Cntr=0.3,0.1

Type RM Length L Ch R = 1,10215,1028,1028,1028
BEGIN DESCRIPTION:
UCFB HW Trib 04-02 13.0
END DESCRIPTION:
XS GIS Cut Line= 4
      1370779.95      6982963.00      1372292.79      6982884.34
      1372529.40      6981858.34      1372741.30      6980852.32
#Sta/Elev= 30
  2039.4 1949.27  2224.7 1948.08  2274.8 1944.62  2334.8 1945.35  2435.0 1942.20
  2465.0 1943.52  2495.1 1941.52  3045.8 1941.29  3085.9 1939.16  3256.1 1939.88
  3306.2 1937.09  3384.3 1938.16  3419.8 1935.80  3476.4 1936.83  3516.4 1934.93
  3526.5 1937.50  3601.8 1932.86  3672.0 1934.56  3762.6 1931.04  3827.6 1933.38
  3901.2 1931.72  4063.6 1932.98  4289.4 1938.66  4504.9 1938.79  4668.9 1937.72
  4805.5 1932.21  4983.5 1930.36  4983.8 1929.86  4987.8 1930.36  5635.3 1935.16
#Mann=4,-1,0
  2039.4   0.045       0  3419.8   0.035       0  4983.5   0.035       0
  4987.8   0.035       0
Bank Sta=4983.5,4987.8
Exp/Cntr=0.3,0.1

Type RM Length L Ch R = 1,9187,554,554,554
BEGIN DESCRIPTION:
UCFB HW Trib 04-02 12.0
END DESCRIPTION:
XS GIS Cut Line= 3
      1371929.97      6983163.01      1372805.00      6982938.00
      1373880.02      6981462.97
#Sta/Elev= 30
  3014.8 1939.78  3131.8 1940.01  3196.5 1941.31  3267.8 1939.86  3278.1 1938.36
  3288.4 1938.77  3294.8 1937.72  3319.4 1940.67  3335.5 1938.33  3389.5 1937.30
  3422.7 1938.23  3464.0 1934.96  3498.4 1935.60  3534.0 1933.00  3556.9 1933.20
  3608.5 1930.39  3656.1 1932.07  3691.1 1929.96  3866.7 1929.51  4670.4 1931.11
  4954.8 1928.61  4955.1 1928.11  4959.2 1928.61  5205.8 1930.97  5564.0 1931.70
  5663.9 1932.73  5672.4 1934.29  5678.6 1933.58  5687.1 1935.12  5743.5 1934.56
#Mann=5,-1,0
  3014.8   0.045       0  3196.5   0.035       0  3389.5   0.045       0
  4954.8   0.045       0  4959.2   0.045       0
Bank Sta=4954.8,4959.2
Exp/Cntr=0.3,0.1

Type RM Length L Ch R = 1,8633,624,624,624
BEGIN DESCRIPTION:
UCFB HW Trib 04-02 11.0
END DESCRIPTION:
XS GIS Cut Line= 3
      1371156.46      6983722.23      1373155.00      6983288.00
      1374566.43      6981562.63
#Sta/Elev= 30
  1860.2 1939.57  1953.3 1938.00  2719.0 1938.59  2789.9 1941.11  2801.9 1940.71
  2810.4 1938.10  2840.8 1939.84  2845.9 1938.77  2851.3 1941.56  2861.6 1939.38
  2926.7 1938.71  3179.6 1937.04  3209.5 1938.11  3250.4 1934.85  3272.8 1935.42
  3311.7 1932.71  3393.7 1930.31  3444.9 1931.59  3496.0 1929.62  3959.8 1928.58
  3960.2 1928.08  3964.3 1928.58  4417.2 1930.06  4850.0 1928.61  5156.5 1930.24
  5702.8 1929.92  6065.3 1931.20  6094.0 1932.11  6108.4 1934.69  6134.5 1933.00
#Mann=5,-1,0
  1860.2    0.07       0  2719.0   0.035       0  2926.7   0.045       0
  3959.8   0.045       0  3964.3   0.045       0
Bank Sta=3959.8,3964.3
Exp/Cntr=0.3,0.1

Type RM Length L Ch R = 1,8009,387,387,387
BEGIN DESCRIPTION:
UCFB HW Trib 04-02 10.0
END DESCRIPTION:
XS GIS Cut Line= 3
      1372380.03      6984162.98      1373505.00      6983588.00
      1375057.20      6982187.23
#Sta/Elev= 30
  2658.2 1937.30  2741.4 1936.92  2776.1 1937.97  2791.5 1937.76  2821.0 1935.57
  2991.4 1934.68  3023.2 1935.71  3068.1 1933.62  3208.0 1932.82  3446.7 1932.64
  3483.6 1933.69  3519.0 1931.79  3595.9 1930.88  3646.7 1931.84  3697.0 1928.97
  3752.2 1929.37  3757.8 1930.00  3863.2 1928.03  4360.6 1928.04  4792.6 1928.98
  4863.6 1927.92  5037.7 1927.83  5038.0 1927.33  5042.2 1927.83  5245.5 1929.18
  5493.6 1928.45  5974.8 1929.20  5989.0 1929.36  6003.2 1930.93  6012.4 1930.51
#Mann=3,-1,0
  2658.2   0.045       0  5037.7   0.045       0  5042.2   0.045       0
Bank Sta=5037.7,5042.2
Exp/Cntr=0.3,0.1

Type RM Length L Ch R = 1,7622,461,461,461
BEGIN DESCRIPTION:
UCFB HW Trib 04-02 9.6
END DESCRIPTION:
XS GIS Cut Line= 3
      1373786.18      6984815.70      1374430.49      6983263.91
      1375210.61      6982374.63
#Sta/Elev= 30
  2978.5 1933.80  3197.5 1933.53  3434.0 1932.20  3604.0 1933.00  3670.4 1932.44
  3694.3 1933.14  3742.0 1930.77  3771.3 1930.63  3800.6 1931.50  3848.3 1928.71
  3896.1 1929.71  3939.7 1927.94  3983.9 1927.77  4007.8 1927.81  4031.6 1928.83
  4055.5 1927.22  4077.0 1926.85  4077.4 1926.35  4081.7 1926.85  4123.7 1928.26
  4177.9 1926.94  4244.2 1928.67  4286.2 1927.83  4576.2 1928.75  5020.5 1927.54
  5247.3 1928.49  5445.7 1927.79  5813.9 1928.46  5828.1 1931.24  5841.7 1931.44
#Mann=3,-1,0
  2978.5   0.045       0  4077.0   0.045       0  4081.7   0.045       0
Bank Sta=4077,4081.7
Exp/Cntr=0.3,0.1

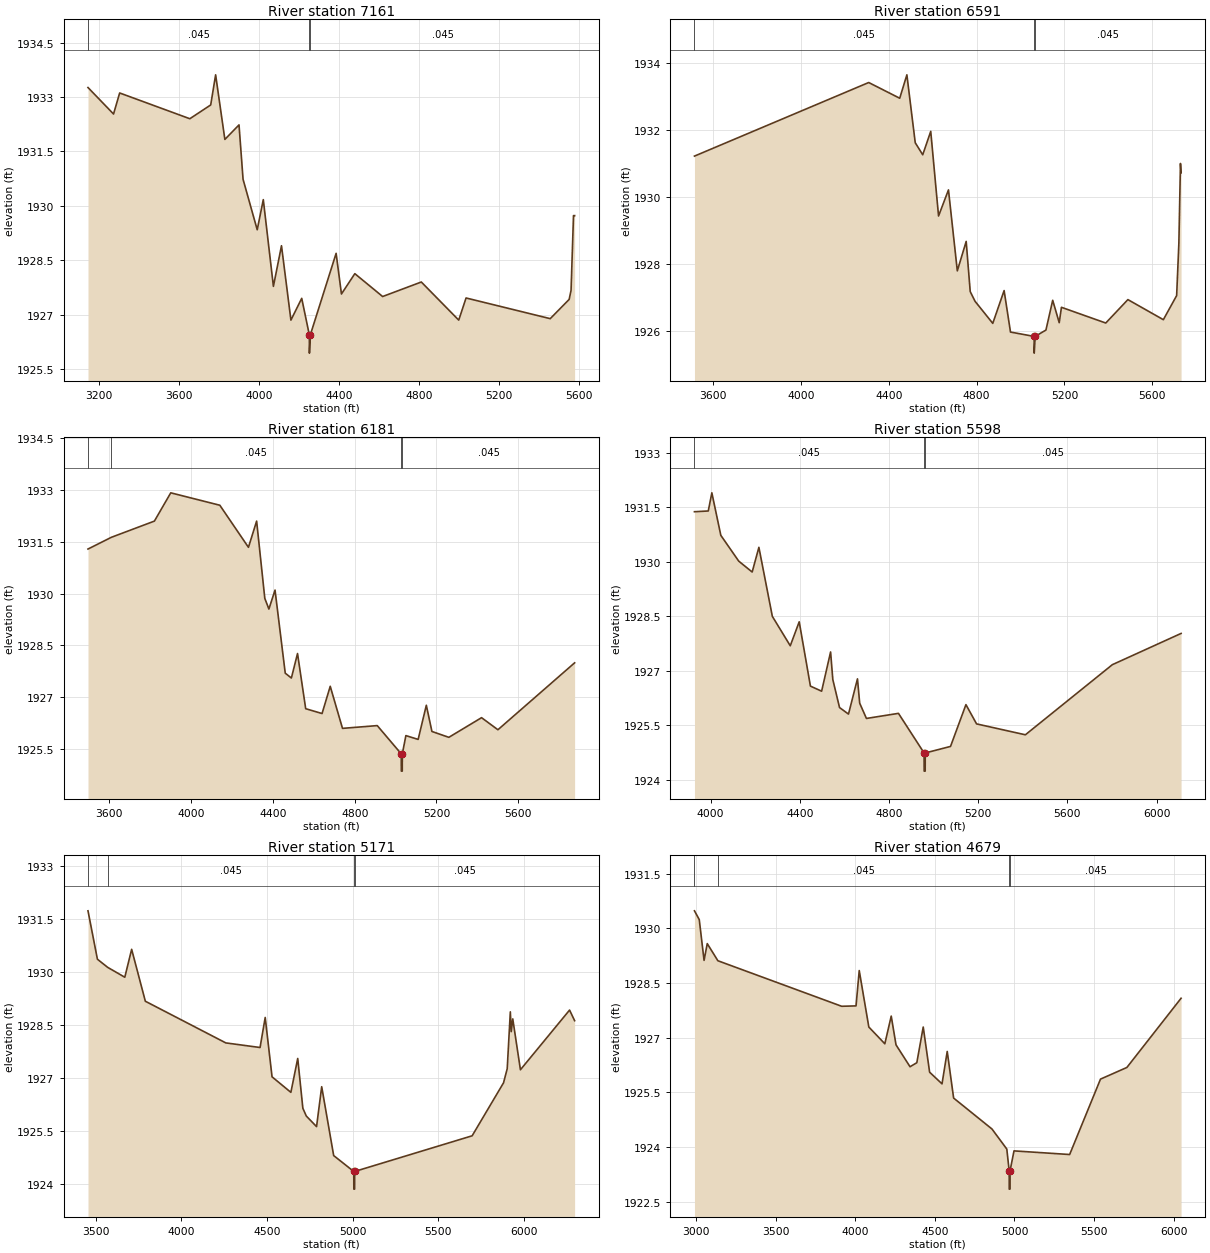
Type RM Length L Ch R = 1,7161,570,570,570
BEGIN DESCRIPTION:
UCFB HW Trib 04-02 9.3
END DESCRIPTION:
XS GIS Cut Line= 3
      1374739.03      6984924.62      1375002.20      6983282.06
      1375406.60      6982623.42
#Sta/Elev= 30
  3143.9 1933.26  3271.8 1932.53  3302.5 1933.11  3653.8 1932.40  3758.3 1932.78
  3782.9 1933.61  3829.2 1931.83  3900.0 1932.23  3920.3 1930.73  3991.2 1929.34
  4021.6 1930.17  4072.2 1927.78  4112.7 1928.90  4159.9 1926.85  4214.0 1927.45
  4252.2 1926.44  4252.5 1925.94  4256.9 1926.44  4386.2 1928.69  4412.9 1927.57
  4479.9 1928.13  4619.1 1927.50  4812.7 1927.90  5000.1 1926.85  5036.8 1927.46
  5458.2 1926.89  5552.9 1927.42  5562.5 1927.67  5574.7 1929.73  5580.3 1929.73
#Mann=3,-1,0
  3143.9   0.045       0  4252.2   0.045       0  4256.9   0.045       0
Bank Sta=4252.2,4256.9
Exp/Cntr=0.3,0.1

Type RM Length L Ch R = 1,6591,410,410,410
BEGIN DESCRIPTION:
UCFB HW Trib 04-02 9.2
END DESCRIPTION:
XS GIS Cut Line= 2
      1375328.89      6984924.54      1375630.06      6982727.99
#Sta/Elev= 30
  3514.5 1931.23  4308.4 1933.43  4449.7 1932.96  4482.3 1933.66  4520.4 1931.63
  4554.5 1931.27  4591.0 1931.97  4626.6 1929.44  4671.8 1930.22  4712.1 1927.80
  4752.5 1928.68  4770.9 1927.18  4792.9 1926.89  4873.6 1926.23  4925.3 1927.21
  4954.4 1925.97  5062.1 1925.84  5062.4 1925.34  5066.9 1925.84  5115.9 1926.03
  5146.7 1926.92  5176.4 1926.25  5186.5 1926.71  5388.4 1926.24  5489.3 1926.94
  5650.8 1926.34  5711.4 1927.06  5721.5 1928.62  5728.8 1931.01  5731.6 1930.73
#Mann=3,-1,0
  3514.5   0.045       0  5062.1   0.045       0  5066.9   0.045       0
Bank Sta=5062.1,5066.9
Exp/Cntr=0.3,0.1

Type RM Length L Ch R = 1,6181,583,583,583
BEGIN DESCRIPTION:
UCFB HW Trib 04-02 9.1
END DESCRIPTION:
XS GIS Cut Line= 3
      1375909.67      6984942.76      1375904.82      6983438.37
      1375930.00      6982563.03
#Sta/Elev= 30
  3495.6 1931.29  3609.8 1931.63  3820.4 1932.10  3900.4 1932.92  4140.4 1932.56
  4280.4 1931.34  4320.4 1932.10  4360.4 1929.86  4380.4 1929.55  4410.4 1930.10
  4460.4 1927.69  4490.4 1927.55  4520.4 1928.26  4560.4 1926.66  4640.4 1926.52
  4680.4 1927.31  4740.4 1926.09  4910.4 1926.17  5027.8 1925.35  5028.2 1924.85
  5032.6 1924.85  5033.0 1925.35  5050.4 1925.88  5110.4 1925.77  5150.4 1926.76
  5177.8 1926.00  5260.5 1925.83  5420.5 1926.40  5500.6 1926.05  5875.7 1927.99
#Mann=4,-1,0
  3495.6   0.035       0  3609.8   0.045       0  5027.8   0.045       0
  5033.0   0.045       0
Bank Sta=5027.8,5033
Exp/Cntr=0.3,0.1

Type RM Length L Ch R = 1,5598,427,427,427
BEGIN DESCRIPTION:
UCFB HW Trib 04-02 9.0
END DESCRIPTION:
XS GIS Cut Line= 3
      1376354.28      6984605.66      1376455.00      6983538.00
      1376030.01      6982513.02
#Sta/Elev= 30
  3927.6 1931.38  3989.5 1931.40  4005.6 1931.90  4045.8 1930.73  4126.1 1930.02
  4186.4 1929.72  4216.5 1930.40  4276.8 1928.50  4357.2 1927.69  4397.3 1928.35
  4447.6 1926.58  4497.8 1926.44  4538.0 1927.52  4548.0 1926.76  4578.1 1925.99
  4618.3 1925.81  4658.5 1926.78  4668.5 1926.11  4698.7 1925.69  4842.3 1925.83
  4957.2 1924.74  4957.6 1924.24  4962.1 1924.24  4962.5 1924.74  5075.8 1924.92
  5144.9 1926.07  5192.6 1925.54  5411.4 1925.24  5801.4 1927.17  6109.6 1928.03
#Mann=3,-1,0
  3927.6   0.045       0  4957.2   0.045       0  4962.5   0.045       0
Bank Sta=4957.2,4962.5
Exp/Cntr=0.3,0.1

Type RM Length L Ch R = 1,5171,492,492,492
BEGIN DESCRIPTION:
UCFB HW Trib 04-02 8.0
END DESCRIPTION:
XS GIS Cut Line= 3
      1376830.00      6985112.96      1376855.00      6983538.00
      1376380.01      6982363.03
#Sta/Elev= 30
  3454.4 1931.74  3509.4 1930.37  3569.2 1930.14  3669.4 1929.86  3709.4 1930.65
  3789.4 1929.18  4259.5 1928.00  4459.5 1927.87  4489.5 1928.72  4529.5 1927.04
  4639.5 1926.60  4679.5 1927.56  4709.5 1926.15  4729.5 1925.93  4789.5 1925.63
  4819.5 1926.76  4889.5 1924.81  5006.9 1924.36  5007.3 1923.86  5011.8 1923.86
  5012.2 1924.36  5698.3 1925.37  5881.7 1926.87  5903.2 1927.27  5921.4 1928.88
  5926.8 1928.32  5935.6 1928.68  5980.4 1927.24  6267.4 1928.93  6296.9 1928.63
#Mann=4,-1,0
  3454.4   0.035       0  3569.2   0.045       0  5006.9   0.045       0
  5012.2   0.045       0
Bank Sta=5006.9,5012.2
Exp/Cntr=0.3,0.1

Type RM Length L Ch R = 1,4679,468,468,468
BEGIN DESCRIPTION:
UCFB HW Trib 04-02 7.0
END DESCRIPTION:
XS GIS Cut Line= 3
      1377405.00      6985237.97      1377205.00      6983238.00
      1376629.98      6982362.97
#Sta/Elev= 30
  2989.8 1930.48  3019.9 1930.24  3050.1 1929.12  3070.2 1929.58  3136.8 1929.11
  3914.4 1927.86  4004.8 1927.87  4024.9 1928.84  4085.2 1927.29  4185.7 1926.83
  4225.9 1927.59  4256.1 1926.80  4344.0 1926.20  4386.7 1926.31  4426.9 1927.29
  4467.1 1926.05  4545.0 1925.73  4577.7 1926.62  4617.9 1925.34  4859.0 1924.49
  4952.0 1923.94  4966.9 1923.34  4967.3 1922.84  4971.8 1922.84  4972.2 1923.34
  4997.2 1923.89  5346.8 1923.79  5540.6 1925.86  5706.3 1926.18  6046.8 1928.08
#Mann=4,-1,0
  2989.8   0.035       0  3136.8   0.045       0  4966.9   0.045       0
  4972.2   0.045       0
Bank Sta=4966.9,4972.2
Exp/Cntr=0.3,0.1

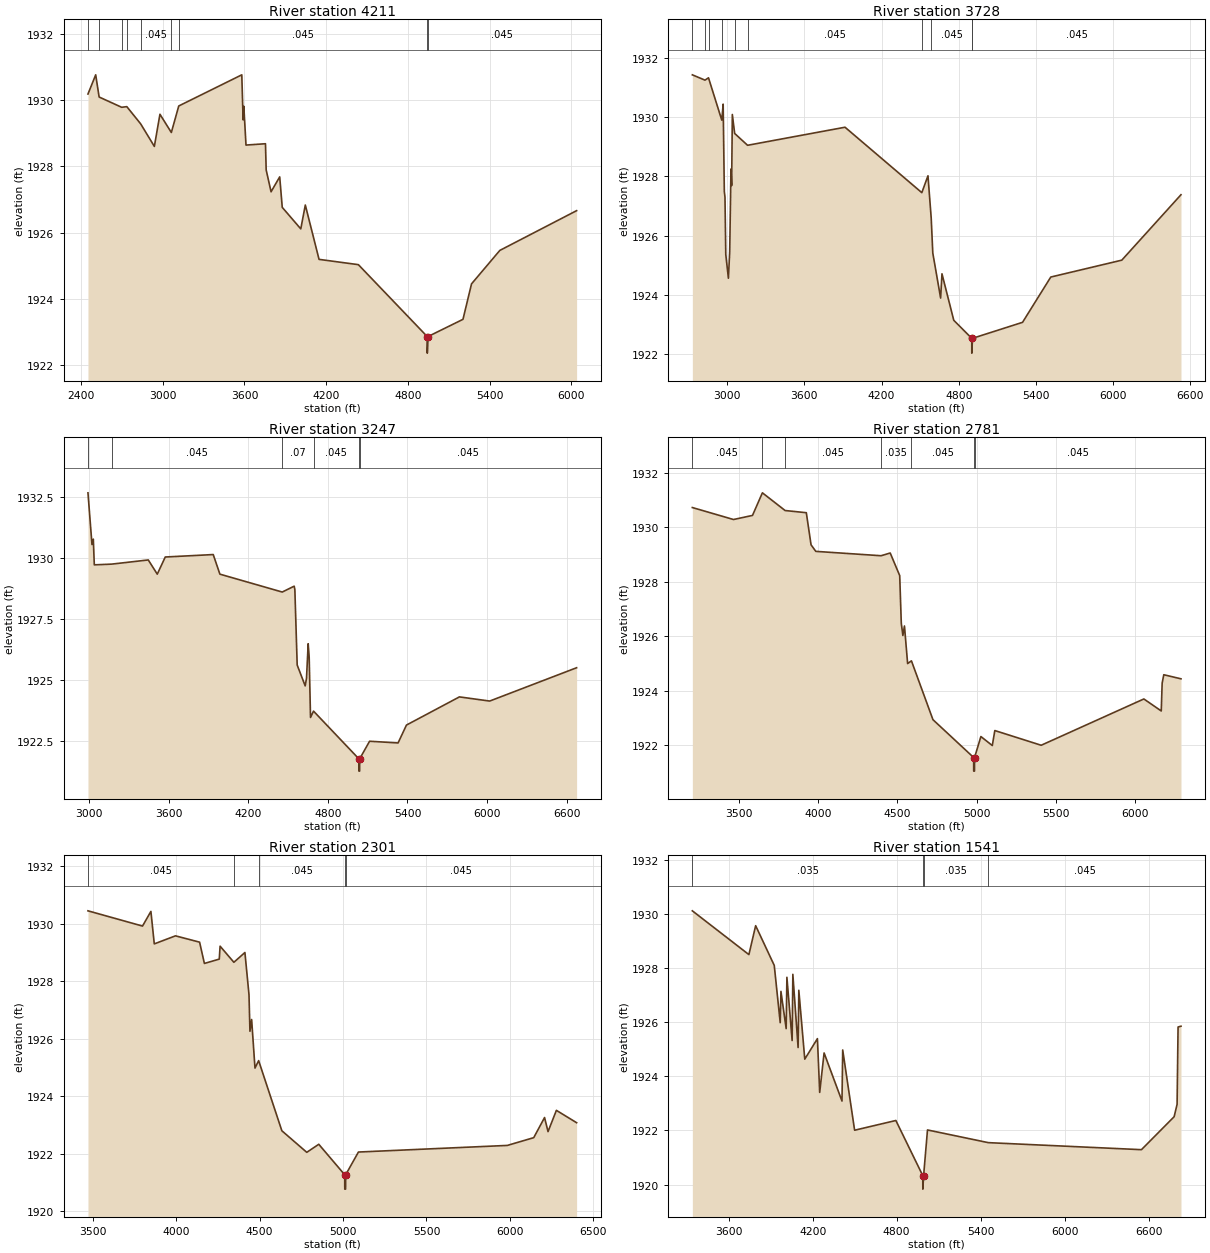
Type RM Length L Ch R = 1,4211,483,483,483
BEGIN DESCRIPTION:
UCFB HW Trib 04-02 6.0
END DESCRIPTION:
XS GIS Cut Line= 3
      1378180.00      6985412.99      1377555.00      6982938.00
      1376930.00      6982113.00
#Sta/Elev= 30
  2451.3 1930.18  2508.0 1930.76  2533.2 1930.09  2698.9 1929.78  2736.5 1929.80
  2838.2 1929.28  2938.7 1928.60  2979.8 1929.57  3063.4 1929.02  3117.9 1929.82
  3580.7 1930.76  3590.4 1929.40  3595.5 1929.81  3611.6 1928.64  3754.6 1928.68
  3759.7 1927.89  3795.6 1927.23  3859.1 1927.68  3877.7 1926.76  4013.8 1926.11
  4047.1 1926.83  4147.9 1925.19  4436.7 1925.03  4942.2 1922.86  4942.7 1922.36
  4947.7 1922.86  5204.7 1923.38  5267.4 1924.45  5475.2 1925.46  6039.0 1926.66
#Mann=9,-1,0
  2451.3   0.035       0  2533.2    0.07       0  2698.9   0.045       0
  2736.5    0.07       0  2838.2   0.045       0  3063.4    0.07       0
  3117.9   0.045       0  4942.2   0.045       0  4947.7   0.045       0
Bank Sta=4942.2,4947.7
Exp/Cntr=0.3,0.1

Type RM Length L Ch R = 1,3728,481,481,481
BEGIN DESCRIPTION:
UCFB HW Trib 04-02 5.0
END DESCRIPTION:
XS GIS Cut Line= 3
      1378438.01      6985173.22      1378005.00      6982938.00
      1376980.00      6981813.00
#Sta/Elev= 30
  2728.9 1931.43  2827.4 1931.25  2854.5 1931.33  2957.7 1929.90  2968.5 1930.44
  2977.5 1927.49  2982.6 1927.30  2988.9 1925.36  3009.2 1924.56  3019.4 1925.46
  3029.2 1928.25  3034.3 1927.69  3039.8 1930.09  3057.9 1929.45  3158.2 1929.05
  3915.8 1929.66  4512.9 1927.45  4560.7 1928.02  4585.7 1926.60  4598.2 1925.41
  4659.1 1923.89  4669.5 1924.71  4761.2 1923.14  4901.0 1922.53  4901.4 1922.03
  4906.7 1922.53  5295.9 1923.07  5515.5 1924.60  6067.5 1925.17  6527.6 1927.38
#Mann=10,-1,0
  2728.9   0.045       0  2827.4    0.07       0  2854.5   0.045       0
  2957.7    0.07       0  3057.9   0.035       0  3158.2   0.045       0
  4512.9    0.07       0  4585.7   0.045       0  4901.0   0.045       0
  4906.7   0.045       0
Bank Sta=4901,4906.7
Exp/Cntr=0.3,0.1

Type RM Length L Ch R = 1,3247,466,466,466
BEGIN DESCRIPTION:
UCFB HW Trib 04-02 4.0
END DESCRIPTION:
XS GIS Cut Line= 3
      1378655.00      6985038.03      1378455.00      6983038.00
      1377429.99      6981712.99
#Sta/Elev= 30
  2990.4 1932.65  3020.6 1930.54  3030.6 1930.76  3038.2 1929.71  3169.2 1929.74
  3445.2 1929.91  3513.0 1929.33  3573.3 1930.03  3935.1 1930.13  3985.4 1929.33
  4455.5 1928.60  4545.6 1928.84  4550.7 1928.70  4568.3 1925.62  4628.6 1924.77
  4638.6 1925.08  4651.2 1926.49  4658.7 1925.93  4668.8 1923.48  4691.4 1923.74
  5033.7 1921.79  5034.2 1921.29  5039.0 1921.29  5039.5 1921.79  5114.2 1922.51
  5329.1 1922.44  5392.3 1923.17  5791.8 1924.32  6020.0 1924.15  6675.6 1925.51
#Mann=6,-1,0
  2990.4    0.07       0  3169.2   0.045       0  4455.5    0.07       0
  4691.4   0.045       0  5033.7   0.045       0  5039.5   0.045       0
Bank Sta=5033.7,5039.5
Exp/Cntr=0.3,0.1

Type RM Length L Ch R = 1,2781,480,480,480
BEGIN DESCRIPTION:
UCFB HW Trib 04-02 3.0
END DESCRIPTION:
XS GIS Cut Line= 3
      1378905.00      6984887.97      1378905.00      6983088.00
      1378280.01      6981963.02
#Sta/Elev= 30
  3204.6 1930.73  3464.6 1930.29  3584.6 1930.44  3647.2 1931.27  3790.6 1930.62
  3924.6 1930.54  3954.6 1929.36  3984.6 1929.12  4397.1 1928.96  4454.6 1929.06
  4514.6 1928.23  4524.6 1926.48  4534.6 1926.03  4544.6 1926.38  4564.6 1925.00
  4588.7 1925.10  4724.6 1922.94  4981.7 1921.55  4982.1 1921.05  4987.0 1921.05
  4987.5 1921.55  5027.5 1922.32  5099.5 1921.99  5115.5 1922.54  5408.4 1922.00
  6057.0 1923.70  6166.8 1923.26  6172.6 1924.28  6182.8 1924.59  6291.5 1924.44
#Mann=7,-1,0
  3204.6   0.045       0  3647.2   0.035       0  3790.6   0.045       0
  4397.1   0.035       0  4588.7   0.045       0  4981.7   0.045       0
  4987.5   0.045       0
Bank Sta=4981.7,4987.5
Exp/Cntr=0.3,0.1

Type RM Length L Ch R = 1,2301,760,760,760
BEGIN DESCRIPTION:
UCFB HW Trib 04-02 2.0
END DESCRIPTION:
XS GIS Cut Line= 3
      1379180.00      6984612.98      1379355.00      6983088.00
      1378529.98      6981962.97
#Sta/Elev= 30
  3470.4 1930.45  3797.5 1929.92  3847.8 1930.43  3868.0 1929.30  3995.2 1929.58
  4139.7 1929.36  4168.5 1928.62  4257.7 1928.77  4262.7 1929.22  4345.3 1928.66
  4411.5 1929.00  4436.0 1927.53  4441.7 1926.26  4451.8 1926.67  4471.9 1924.98
  4493.8 1925.24  4633.0 1922.80  4782.5 1922.05  4854.4 1922.33  5009.8 1921.27
  5010.3 1920.77  5015.2 1920.77  5015.7 1921.27  5092.2 1922.06  5985.0 1922.29
  6143.4 1922.56  6208.3 1923.26  6229.1 1922.77  6279.3 1923.51  6400.5 1923.08
#Mann=5,-1,0
  3470.4   0.045       0  4345.3   0.035       0  4493.8   0.045       0
  5009.8   0.045       0  5015.7   0.045       0
Bank Sta=5009.8,5015.7
Exp/Cntr=0.3,0.1

Type RM Length L Ch R = 1,1541,363,363,363
BEGIN DESCRIPTION:
UCFB HW Trib 04-02 0.9
END DESCRIPTION:
XS GIS Cut Line= 4
      1379670.78      6984506.81      1379751.51      6984100.55
      1380105.68      6982579.72      1379019.92      6981523.75
#Sta/Elev= 30
  3340.6 1930.13  3744.6 1928.51  3792.8 1929.58  3925.7 1928.11  3968.3 1925.99
  3973.4 1927.15  4010.8 1925.77  4016.0 1927.67  4053.4 1925.33  4058.5 1927.78
  4096.0 1925.07  4101.1 1927.19  4143.7 1924.64  4234.0 1925.40  4250.3 1923.41
  4281.7 1924.87  4409.5 1923.09  4414.6 1924.98  4499.7 1922.01  4794.4 1922.37
  4986.5 1920.33  4987.0 1919.83  4992.5 1920.33  5020.3 1922.02  5454.9 1921.55
  6548.5 1921.29  6782.0 1922.51  6803.1 1922.97  6810.1 1925.83  6830.9 1925.86
#Mann=4,-1,0
  3340.6   0.035       0  4986.5   0.035       0  4992.5   0.035       0
  5454.9   0.045       0
Bank Sta=4986.5,4992.5
Exp/Cntr=0.3,0.1

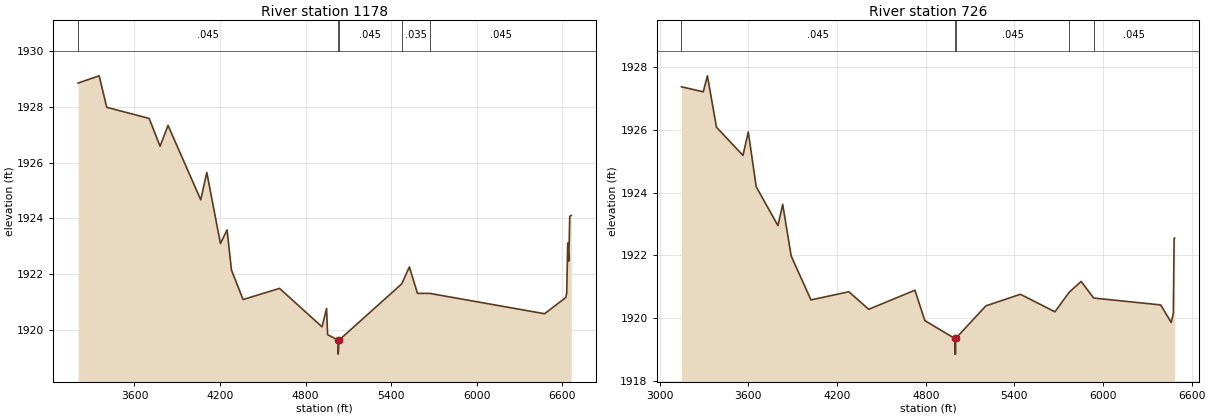
Type RM Length L Ch R = 1,1178,452,452,452
BEGIN DESCRIPTION:
UCFB HW Trib 04-02 0.7
END DESCRIPTION:
XS GIS Cut Line= 4
      1379766.41      6984507.15      1380374.41      6982819.25
      1380412.34      6982667.82      1379343.59      6981604.88
#Sta/Elev= 30
  3204.5 1928.86  3352.4 1929.12  3405.5 1927.99  3703.2 1927.59  3779.3 1926.59
  3835.4 1927.34  4064.5 1924.67  4107.1 1925.65  4202.7 1923.10  4249.2 1923.59
  4279.9 1922.15  4361.4 1921.09  4617.2 1921.49  4914.9 1920.11  4946.7 1920.77
  4954.0 1919.83  5027.8 1919.63  5028.3 1919.13  5033.8 1919.63  5473.3 1921.65
  5527.4 1922.26  5584.0 1921.31  5670.8 1921.31  6475.0 1920.58  6623.4 1921.16
  6630.5 1921.32  6637.6 1923.12  6644.7 1922.47  6651.7 1924.07  6662.0 1924.11
#Mann=5,-1,0
  3204.5   0.045       0  5027.8   0.045       0  5033.8   0.045       0
  5473.3   0.035       0  5670.8   0.045       0
Bank Sta=5027.8,5033.8
Exp/Cntr=0.3,0.1

Type RM Length L Ch R = 1,726,0,0,0
BEGIN DESCRIPTION:
UCFB HW Trib 04-02 0.5
END DESCRIPTION:
XS GIS Cut Line= 4
      1379993.26      6984352.91      1380791.85      6982746.65
      1380777.57      6982617.09      1379711.94      6981688.69
#Sta/Elev= 30
  3147.1 1927.38  3294.6 1927.22  3322.6 1927.73  3384.2 1926.09  3563.4 1925.19
  3599.3 1925.94  3653.0 1924.19  3800.3 1922.95  3832.2 1923.63  3889.7 1921.98
  4023.7 1920.58  4280.2 1920.84  4414.5 1920.28  4727.2 1920.89  4794.2 1919.92
  4996.9 1919.35  4997.4 1918.85  5002.4 1918.85  5002.9 1919.35  5207.3 1920.39
  5441.1 1920.76  5674.7 1920.20  5772.1 1920.83  5852.2 1921.17  5936.7 1920.64
  6390.5 1920.42  6461.7 1919.86  6476.0 1920.15  6481.3 1922.55  6484.6 1922.55
#Mann=5,-1,0
  3147.1   0.045       0  4996.9   0.045       0  5002.9   0.045       0
  5772.1   0.035       0  5936.7   0.045       0
Bank Sta=4996.9,5002.9
Exp/Cntr=0.3,0.1

Chan Stop Cuts=-1