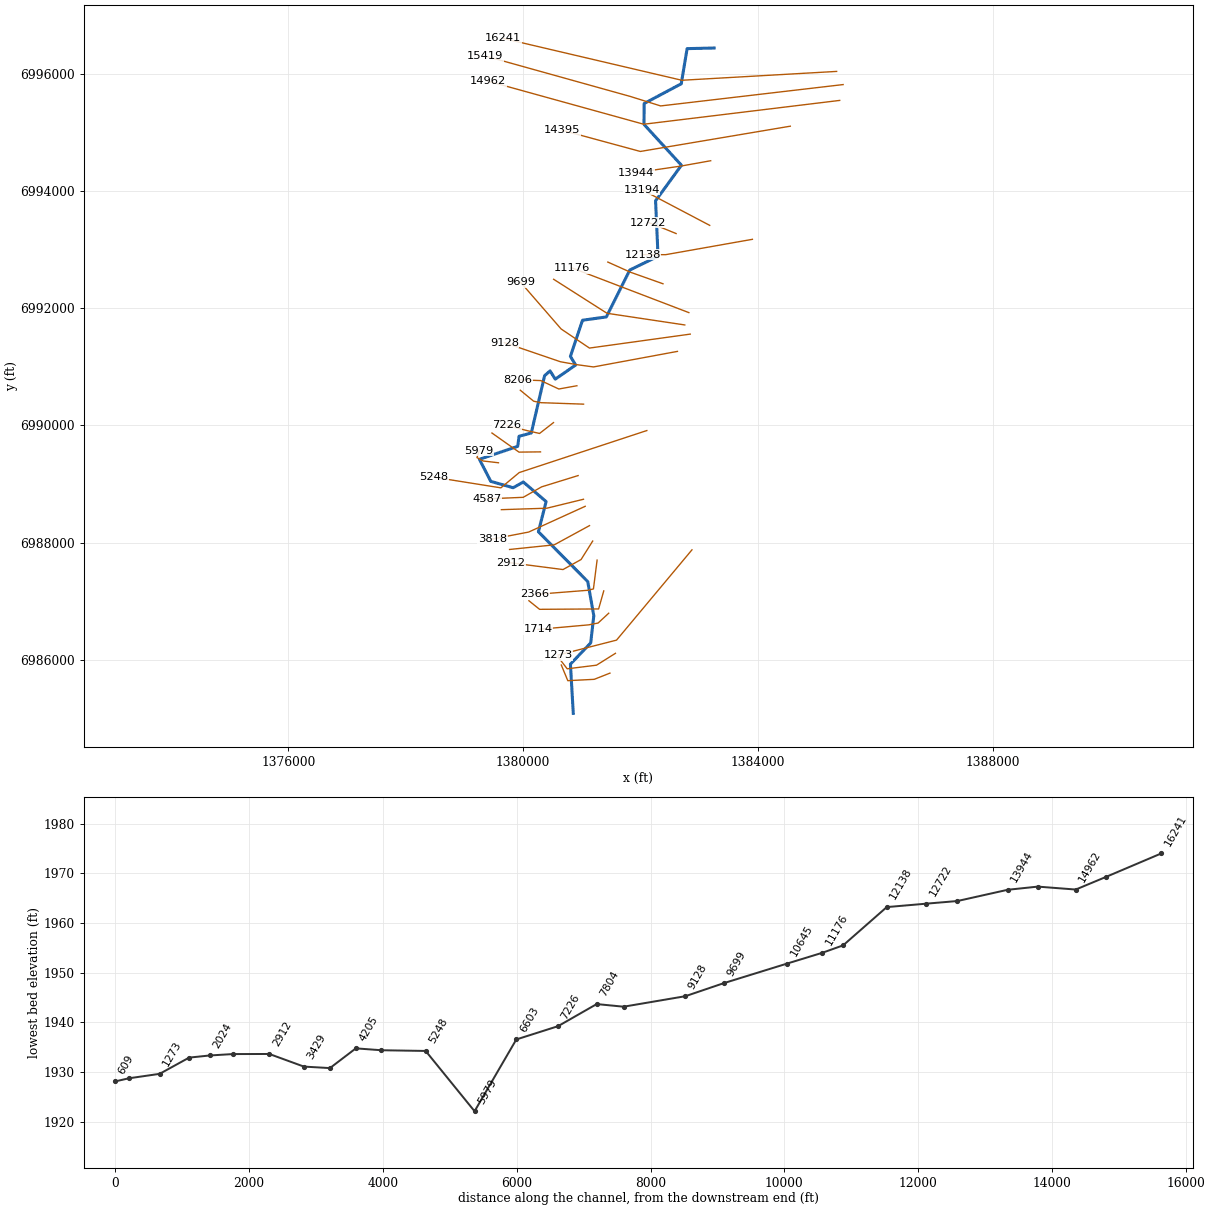
--- UCFB HW Trib 04-03.prj (project) ---

Proj Title=UCFB HW Trib 04-03 Base Level Engineering
Current Plan=p01
Default Exp/Contr=0.3,0.1
English Units
Geom File=g01
Flow File=f01
Plan File=p01
BEGIN DESCRIPTION:
UCFB HW Trib 04-03
END DESCRIPTION:

--- UCFB HW Trib 04-03.p01 (plan) ---

Plan Title=Multiple Run
Short Identifier=Multiple
Geom File=g01
Flow File=f01
Subcritical Flow
K Sum by GR= 0
Std Step Tol= 0.01
Critical Tol= 0.01
Num of Std Step Trials= 20
Max Error Tol= 0.3
Flow Tol Ratio= 0.001
Split Flow NTrial= 30
Split Flow Tol= 0.02
Split Flow Ratio= 0.02
Log Output Level= 0
Friction Slope Method= 1
Unsteady Friction Slope Method= 2
Unsteady Bridges Friction Slope Method= 1
Parabolic Critical Depth
Global Vel Dist=  1 , 1 , 1
Global Log Level= 0
CheckData=True
Encroach Param= -1, 0, 0, 0
BEGIN DESCRIPTION:
Multiple Run
END DESCRIPTION:

--- UCFB HW Trib 04-03.f01 (steady flow) ---

Flow Title=Multiple
Number of Profiles=7
Profile Names=10-year,25-year,50-year,1pct_min,100-year,1pct_plu,500-year
River Rch & RM= UCFB HW Trib 04-,Reach-1,16241
     316     444     551     339     677    1351    1036
River Rch & RM= UCFB HW Trib 04-,Reach-1,10645
     367     520     648     401     799    1595    1233
River Rch & RM= UCFB HW Trib 04-,Reach-1,5979
     443     635     798     497     992    1979    1554
River Rch & RM= UCFB HW Trib 04-,Reach-1,5248
     536     776     981     614    1225    2445    1941
River Rch & RM= UCFB HW Trib 04-,Reach-1,3818
     531     767     967     604    1206    2407    1903
Boundary for River Rch & Prof#=UCFB HW Trib 04-,Reach-1,1
Up Type=0
Dn Type=3
Dn Slope=0.005
Boundary for River Rch & Prof#=UCFB HW Trib 04-,Reach-1,2
Up Type=0
Dn Type=3
Dn Slope=0.005
Boundary for River Rch & Prof#=UCFB HW Trib 04-,Reach-1,3
Up Type=0
Dn Type=3
Dn Slope=0.005
Boundary for River Rch & Prof#=UCFB HW Trib 04-,Reach-1,4
Up Type=0
Dn Type=3
Dn Slope=0.005
Boundary for River Rch & Prof#=UCFB HW Trib 04-,Reach-1,5
Up Type=0
Dn Type=3
Dn Slope=0.005
Boundary for River Rch & Prof#=UCFB HW Trib 04-,Reach-1,6
Up Type=0
Dn Type=3
Dn Slope=0.005
Boundary for River Rch & Prof#=UCFB HW Trib 04-,Reach-1,7
Up Type=0
Dn Type=3
Dn Slope=0.005

--- UCFB HW Trib 04-03.g01 (geometry) ---

Geom Title=Existing Conditions

River Reach=UCFB HW Trib 04-,Reach-1
Reach XY= 30
      1383255.00      6996438.00      1382794.84      6996427.72
      1382694.68      6995827.82      1382062.88      6995491.58
      1382060.09      6995135.70      1382698.02      6994438.21
      1382257.24      6993832.07      1382299.55      6992885.54
      1381818.39      6992651.33      1381418.63      6991850.95
      1381012.35      6991794.39      1380805.57      6991177.36
      1380896.04      6991031.33      1380548.48      6990789.39
      1380458.60      6990930.53      1380366.10      6990848.11
      1380138.96      6989870.86      1379930.53      6989815.16
      1379907.61      6989643.01      1379255.11      6989422.28
      1379448.79      6989045.80      1379830.00      6988937.42
      1380003.57      6989034.99      1380391.63      6988701.32
      1380260.40      6988185.57      1381101.25      6987336.45
      1381204.63      6986753.27      1381151.46      6986289.46
      1380806.05      6985927.57      1380855.00      6985088.00

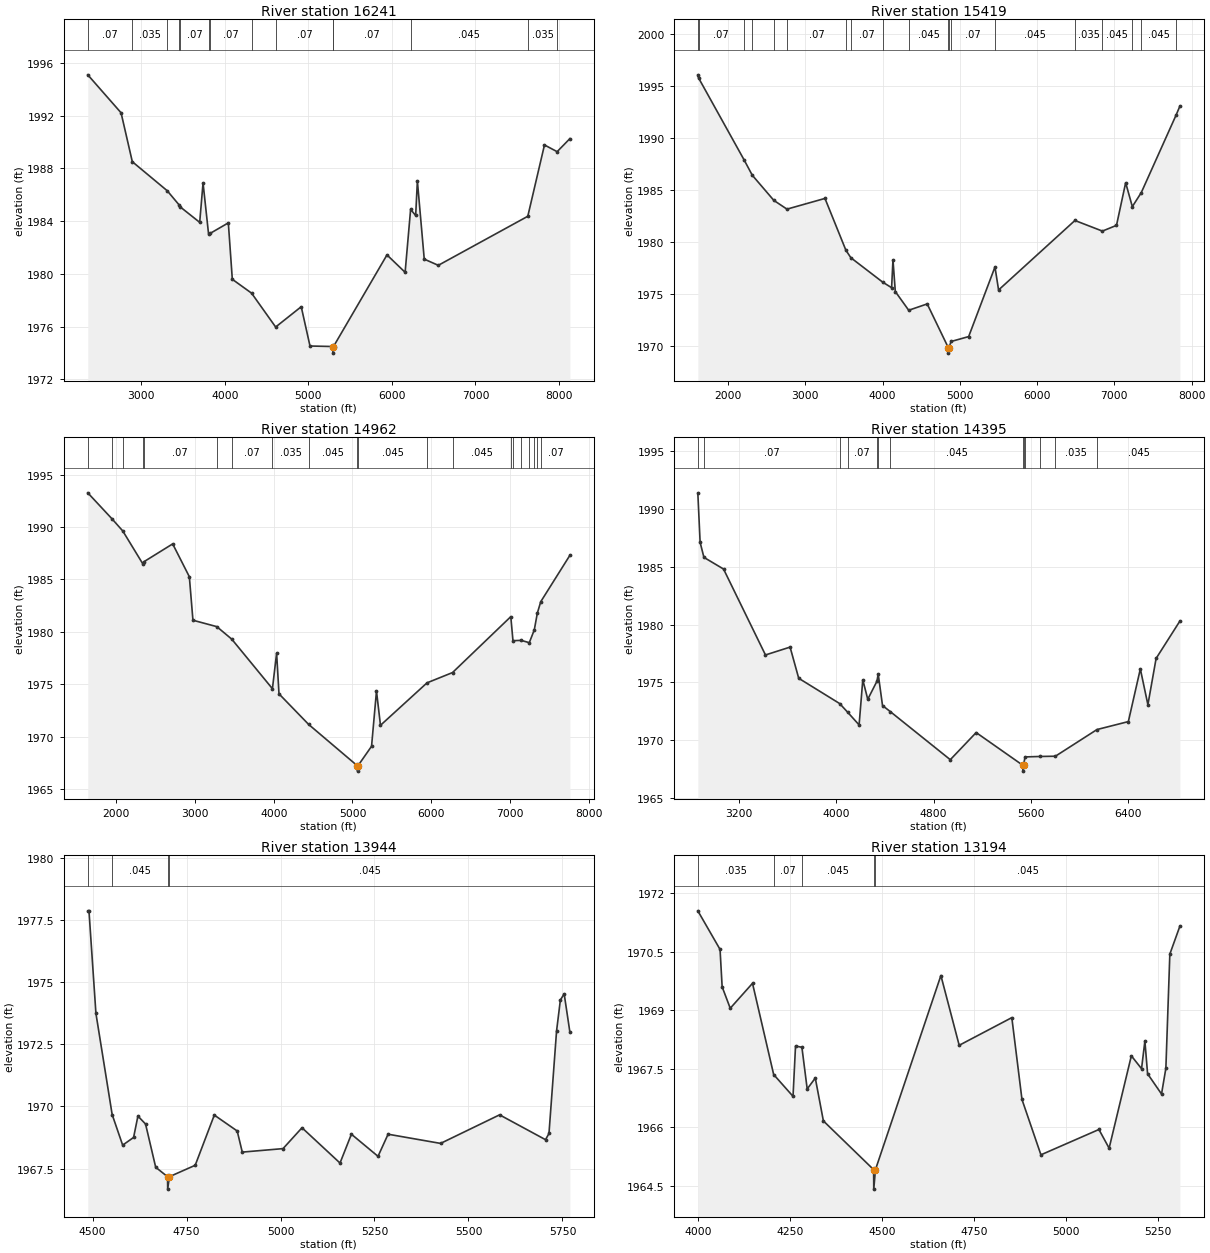
Type RM Length L Ch R = 1,16241,822,822,822
BEGIN DESCRIPTION:
UCFB HW Trib 04-03 12.0
END DESCRIPTION:
XS GIS Cut Line= 3
      1385343.01      6996039.07      1382705.00      6995888.00
      1379657.25      6996603.32
#Sta/Elev= 30
  2358.1 1995.10  2756.8 1992.22  2891.4 1988.51  3309.1 1986.31  3456.0 1985.20
  3463.6 1985.09  3698.3 1983.91  3738.4 1986.90  3804.3 1983.04  3822.8 1983.07
  4041.2 1983.87  4088.9 1979.59  4319.4 1978.54  4607.8 1975.97  4914.1 1977.51
  5019.1 1974.53  5296.3 1974.49  5296.5 1973.99  5300.4 1974.49  5940.8 1981.44
  6158.1 1980.12  6223.8 1984.89  6284.4 1984.43  6304.9 1987.05  6387.1 1981.12
  6555.3 1980.65  7627.0 1984.37  7826.8 1989.78  7978.3 1989.27  8131.0 1990.26
#Mann=14,-1,0
  2358.1    0.07       0  2891.4   0.035       0  3309.1    0.07       0
  3456.0   0.035       0  3463.6    0.07       0  3804.3   0.035       0
  3822.8    0.07       0  4319.4   0.035       0  4607.8    0.07       0
  5296.3    0.07       0  5300.4    0.07       0  6223.8   0.045       0
  7627.0   0.035       0  7978.3   0.045       0
Bank Sta=5296.3,5300.4
Exp/Cntr=0.3,0.1

Type RM Length L Ch R = 1,15419,457,457,457
BEGIN DESCRIPTION:
UCFB HW Trib 04-03 11.5
END DESCRIPTION:
XS GIS Cut Line= 4
      1385453.75      6995814.62      1382343.77      6995450.22
      1381821.74      6995613.35      1379354.22      6996302.01
#Sta/Elev= 30
  1608.6 1996.04  1617.6 1995.75  2207.1 1987.87  2313.5 1986.39  2592.7 1983.97
  2762.6 1983.13  3254.3 1984.16  3525.2 1979.18  3589.4 1978.46  4002.0 1976.11
  4116.9 1975.58  4134.5 1978.26  4164.7 1975.21  4338.1 1973.41  4577.5 1974.02
  4852.3 1969.79  4852.6 1969.29  4856.6 1969.79  4887.3 1970.41  5114.2 1970.88
  5454.7 1977.57  5501.4 1975.36  6489.6 1982.04  6845.0 1981.02  7027.6 1981.57
  7146.2 1985.67  7232.5 1983.37  7348.4 1984.72  7798.9 1992.17  7848.6 1993.04
#Mann=19,-1,0
  1608.6   0.035       0  1617.6    0.07       0  2207.1   0.035       0
  2313.5    0.07       0  2592.7   0.035       0  2762.6    0.07       0
  3525.2   0.035       0  3589.4    0.07       0  4002.0   0.035       0
  4338.1   0.045       0  4852.3    0.07       0  4856.6   0.045       0
  4887.3    0.07       0  5454.7   0.045       0  6489.6   0.035       0
  6845.0   0.045       0  7232.5    0.07       0  7348.4   0.045       0
  7798.9   0.035       0
Bank Sta=4852.3,4856.6
Exp/Cntr=0.3,0.1

Type RM Length L Ch R = 1,14962,567,567,567
BEGIN DESCRIPTION:
UCFB HW Trib 04-03 11.0
END DESCRIPTION:
XS GIS Cut Line= 3
      1385395.13      6995544.28      1382055.00      6995138.00
      1379398.44      6995873.71
#Sta/Elev= 30
  1639.0 1993.26  1946.6 1990.78  2083.7 1989.62  2337.6 1986.49  2347.9 1986.67
  2717.0 1988.39  2928.6 1985.26  2974.3 1981.11  3276.9 1980.50  3466.7 1979.31
  3983.5 1974.58  4036.7 1977.97  4066.9 1974.09  4443.9 1971.17  5063.6 1967.22
  5064.0 1966.72  5068.4 1967.22  5242.2 1969.09  5304.7 1974.35  5355.5 1971.09
  5946.5 1975.14  6270.4 1976.12  7010.0 1981.45  7037.7 1979.16  7141.3 1979.19
  7244.9 1978.97  7308.5 1980.19  7347.1 1981.79  7390.6 1982.88  7760.3 1987.30
#Mann=20,-1,0
  1639.0    0.07       0  1946.6   0.035       0  2083.7    0.07       0
  2337.6   0.035       0  2347.9    0.07       0  3276.9   0.035       0
  3466.7    0.07       0  3983.5   0.035       0  4443.9   0.045       0
  5063.6   0.045       0  5068.4   0.045       0  5946.5   0.035       0
  6270.4   0.045       0  7010.0    0.07       0  7037.7   0.045       0
  7141.3    0.07       0  7244.9   0.045       0  7308.5    0.07       0
  7347.1   0.045       0  7390.6    0.07       0
Bank Sta=5063.6,5068.4
Exp/Cntr=0.3,0.1

Type RM Length L Ch R = 1,14395,451,451,451
BEGIN DESCRIPTION:
UCFB HW Trib 04-03 10.5
END DESCRIPTION:
XS GIS Cut Line= 3
      1384553.71      6995104.79      1381997.93      6994673.70
      1380670.64      6995034.35
#Sta/Elev= 30
  2860.1 1991.41  2879.1 1987.12  2910.4 1985.82  3071.8 1984.81  3416.8 1977.37
  3619.4 1978.05  3690.4 1975.35  4027.5 1973.16  4093.2 1972.41  4187.3 1971.31
  4217.7 1975.22  4258.5 1973.53  4333.9 1975.09  4344.5 1975.72  4380.0 1972.99
  4444.5 1972.46  4937.7 1968.30  5150.6 1970.65  5535.5 1967.81  5535.8 1967.31
  5540.4 1967.81  5552.7 1968.54  5676.7 1968.58  5802.5 1968.60  6144.8 1970.91
  6403.0 1971.60  6501.6 1976.16  6563.8 1973.06  6631.4 1977.07  6827.4 1980.31
#Mann=13,-1,0
  2860.1   0.035       0  2910.4    0.07       0  4027.5   0.035       0
  4093.2    0.07       0  4333.9   0.035       0  4344.5    0.07       0
  4444.5   0.045       0  5535.5   0.045       0  5540.4   0.045       0
  5552.7    0.07       0  5676.7   0.045       0  5802.5   0.035       0
  6144.8   0.045       0
Bank Sta=5535.5,5540.4
Exp/Cntr=0.3,0.1

Type RM Length L Ch R = 1,13944,750,750,750
BEGIN DESCRIPTION:
UCFB HW Trib 04-03 10.0
END DESCRIPTION:
XS GIS Cut Line= 3
      1383196.31      6994515.12      1382691.64      6994424.77
      1381929.99      6994313.00
#Sta/Elev= 30
  4487.3 1977.87  4490.5 1977.87  4509.0 1973.74  4552.2 1969.67  4580.1 1968.44
  4609.2 1968.75  4620.7 1969.61  4641.0 1969.29  4668.0 1967.55  4699.5 1967.17
  4699.9 1966.67  4704.4 1967.17  4773.1 1967.63  4823.9 1969.65  4884.8 1969.01
  4898.3 1968.16  5006.7 1968.30  5057.2 1969.14  5158.3 1967.72  5188.6 1968.88
  5259.4 1967.99  5286.2 1968.88  5425.8 1968.51  5582.8 1969.66  5705.0 1968.66
  5714.2 1968.91  5734.4 1973.04  5744.5 1974.28  5754.6 1974.53  5769.8 1972.99
#Mann=4,-1,0
  4487.3   0.035       0  4552.2   0.045       0  4699.5   0.045       0
  4704.4   0.045       0
Bank Sta=4699.5,4704.4
Exp/Cntr=0.3,0.1

Type RM Length L Ch R = 1,13194,472,472,472
BEGIN DESCRIPTION:
UCFB HW Trib 04-03 9.4
END DESCRIPTION:
XS GIS Cut Line= 2
      1383179.97      6993413.01      1382020.73      6994023.14
#Sta/Elev= 30
  3999.2 1971.55  4059.6 1970.56  4065.3 1969.60  4087.3 1969.05  4147.8 1969.69
  4205.3 1967.35  4257.9 1966.79  4264.7 1968.08  4282.0 1968.05  4296.4 1966.98
  4318.4 1967.26  4340.4 1966.16  4476.9 1964.91  4477.3 1964.41  4481.9 1964.91
  4659.7 1969.89  4709.4 1968.10  4852.4 1968.81  4880.0 1966.71  4931.5 1965.29
  5089.1 1965.94  5116.8 1965.46  5177.2 1967.83  5204.9 1967.50  5214.0 1968.21
  5221.3 1967.37  5259.2 1966.85  5271.0 1967.51  5281.8 1970.44  5309.2 1971.16
#Mann=5,-1,0
  3999.2   0.035       0  4205.3    0.07       0  4282.0   0.045       0
  4476.9   0.045       0  4481.9   0.045       0
Bank Sta=4476.9,4481.9
Exp/Cntr=0.3,0.1

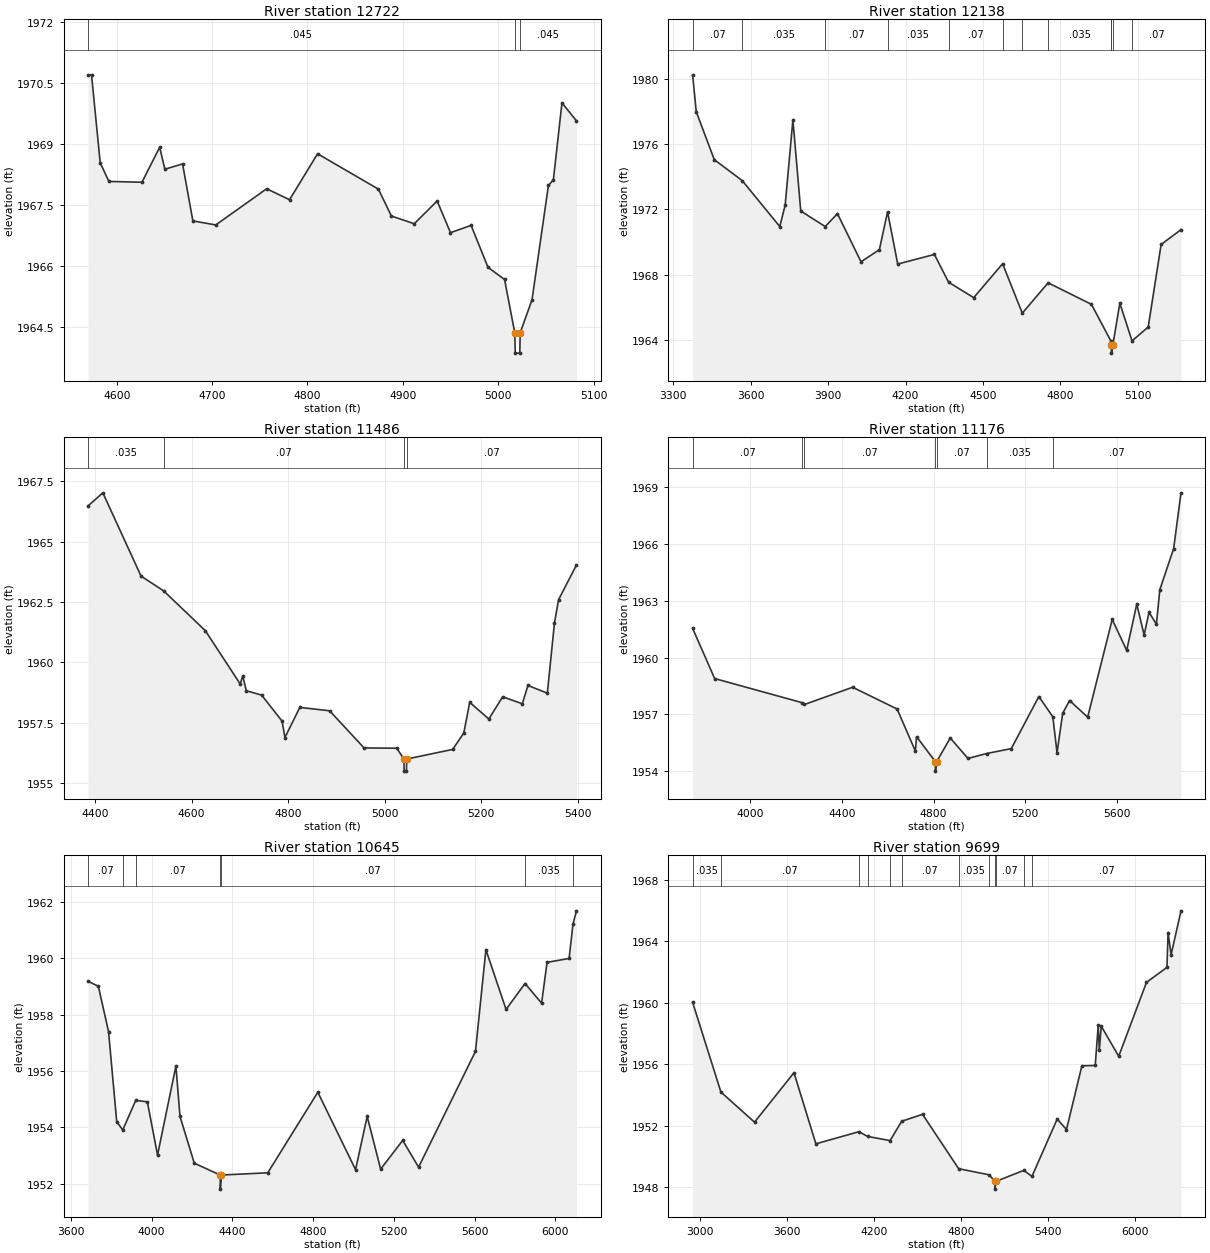
Type RM Length L Ch R = 1,12722,584,584,584
BEGIN DESCRIPTION:
UCFB HW Trib 04-03 9.1
END DESCRIPTION:
XS GIS Cut Line= 3
      1382606.71      6993273.35      1382205.00      6993438.00
      1382130.51      6993461.34
#Sta/Elev= 30
  4569.9 1970.71  4573.5 1970.71  4582.6 1968.55  4591.7 1968.09  4626.4 1968.07
  4645.0 1968.93  4650.4 1968.39  4669.0 1968.52  4679.8 1967.12  4703.8 1967.02
  4757.2 1967.91  4781.2 1967.64  4810.6 1968.77  4874.4 1967.90  4888.0 1967.24
  4912.0 1967.05  4936.0 1967.61  4950.0 1966.83  4971.6 1967.01  4989.3 1965.98
  5006.7 1965.68  5017.4 1964.37  5017.9 1963.87  5022.7 1963.87  5023.1 1964.37
  5035.5 1965.18  5052.7 1967.99  5057.9 1968.13  5066.9 1970.02  5082.1 1969.58
#Mann=3,-1,0
  4569.9   0.045       0  5017.4   0.045       0  5023.1   0.045       0
Bank Sta=5017.4,5023.1
Exp/Cntr=0.3,0.1

Type RM Length L Ch R = 1,12138,652,652,652
BEGIN DESCRIPTION:
UCFB HW Trib 04-03 9.5
END DESCRIPTION:
XS GIS Cut Line= 3
      1383907.62      6993174.76      1382430.00      6992913.00
      1382038.03      6992913.25
#Sta/Elev= 30
  3374.7 1980.25  3388.7 1977.99  3458.6 1975.05  3566.6 1973.77  3712.5 1970.95
  3733.3 1972.26  3763.3 1977.49  3793.7 1971.90  3888.4 1970.95  3935.9 1971.74
  4027.3 1968.79  4098.4 1969.53  4130.1 1971.85  4169.5 1968.65  4311.7 1969.24
  4366.5 1967.54  4464.0 1966.59  4575.9 1968.67  4652.3 1965.64  4752.4 1967.50
  4920.3 1966.18  4995.4 1963.94  4997.5 1963.69  4997.9 1963.19  5003.2 1963.69
  5030.3 1966.25  5077.5 1963.94  5140.3 1964.79  5190.3 1969.85  5267.3 1970.76
#Mann=12,-1,0
  3374.7    0.07       0  3566.6   0.035       0  3888.4    0.07       0
  4130.1   0.035       0  4366.5    0.07       0  4575.9   0.035       0
  4652.3    0.07       0  4752.4   0.035       0  4995.4   0.045       0
  4997.5   0.045       0  5003.2   0.045       0  5077.5    0.07       0
Bank Sta=4997.5,5003.2
Exp/Cntr=0.3,0.1

Type RM Length L Ch R = 1,11486,310,310,310
BEGIN DESCRIPTION:
UCFB HW Trib 04-03 8.0
END DESCRIPTION:
XS GIS Cut Line= 3
      1382383.80      6992416.49      1381830.00      6992613.00
      1381443.38      6992786.99
#Sta/Elev= 30
  4385.7 1966.48  4416.3 1967.02  4495.4 1963.57  4542.1 1962.96  4628.5 1961.31
  4700.8 1959.10  4706.1 1959.44  4713.4 1958.82  4745.2 1958.64  4787.6 1957.56
  4793.4 1956.88  4824.3 1958.13  4886.0 1957.99  4957.4 1956.45  5025.1 1956.44
  5039.9 1955.99  5040.4 1955.49  5045.2 1955.49  5045.6 1955.99  5140.9 1956.39
  5164.0 1957.07  5176.2 1958.34  5215.8 1957.65  5244.4 1958.57  5285.2 1958.28
  5296.8 1959.04  5337.0 1958.72  5351.7 1961.62  5360.2 1962.59  5397.3 1964.03
#Mann=4,-1,0
  4385.7   0.035       0  4542.1    0.07       0  5039.9    0.07       0
  5045.6    0.07       0
Bank Sta=5039.9,5045.6
Exp/Cntr=0.3,0.1

Type RM Length L Ch R = 1,11176,531,531,531
BEGIN DESCRIPTION:
UCFB HW Trib 04-03 7.5
END DESCRIPTION:
XS GIS Cut Line= 2
      1382824.73      6991924.53      1380834.73      6992686.25
#Sta/Elev= 30
  3748.3 1961.54  3844.4 1958.89  4227.6 1957.61  4236.3 1957.52  4446.4 1958.43
  4640.6 1957.28  4720.1 1955.06  4725.4 1955.82  4807.4 1954.50  4807.8 1954.00
  4813.1 1954.50  4872.3 1955.75  4949.7 1954.67  5031.3 1954.93  5138.7 1955.19
  5258.9 1957.94  5319.9 1956.87  5338.3 1954.97  5363.0 1957.06  5393.0 1957.73
  5471.9 1956.85  5579.0 1962.01  5642.1 1960.38  5686.1 1962.82  5718.2 1961.19
  5739.6 1962.39  5771.7 1961.76  5786.9 1963.59  5847.0 1965.75  5879.1 1968.70
#Mann=7,-1,0
  3748.3    0.07       0  4227.6   0.035       0  4236.3    0.07       0
  4807.4    0.07       0  4813.1    0.07       0  5031.3   0.035       0
  5319.9    0.07       0
Bank Sta=4807.4,4813.1
Exp/Cntr=0.3,0.1

Type RM Length L Ch R = 1,10645,946,946,946
BEGIN DESCRIPTION:
UCFB HW Trib 04-03 7.0
END DESCRIPTION:
XS GIS Cut Line= 3
      1382755.30      6991714.03      1381430.00      6991913.00
      1380520.16      6992493.12
#Sta/Elev= 30
  3685.1 1959.19  3736.0 1959.01  3786.5 1957.40  3827.0 1954.20  3856.8 1953.91
  3921.2 1954.96  3978.7 1954.91  4029.2 1953.02  4120.2 1956.18  4140.4 1954.39
  4211.2 1952.73  4339.7 1952.31  4340.2 1951.81  4345.6 1952.31  4575.3 1952.39
  4823.1 1955.25  5010.1 1952.50  5067.6 1954.39  5134.4 1952.52  5243.6 1953.54
  5322.3 1952.59  5604.1 1956.70  5655.7 1960.31  5755.6 1958.19  5849.7 1959.11
  5931.6 1958.41  5958.7 1959.86  6067.9 1960.00  6087.2 1961.22  6104.3 1961.69
#Mann=7,-1,0
  3685.1    0.07       0  3856.8   0.035       0  3921.2    0.07       0
  4339.7    0.07       0  4345.6    0.07       0  5849.7   0.035       0
  6087.2    0.07       0
Bank Sta=4339.7,4345.6
Exp/Cntr=0.3,0.1

Type RM Length L Ch R = 1,9699,571,571,571
BEGIN DESCRIPTION:
UCFB HW Trib 04-03 6.5
END DESCRIPTION:
XS GIS Cut Line= 4
      1382848.62      6991557.79      1381130.05      6991319.66
      1380647.17      6991645.93      1379954.62      6992444.22
#Sta/Elev= 30
  2946.3 1960.03  3141.8 1954.19  3374.0 1952.23  3646.6 1955.45  3798.0 1950.82
  4095.7 1951.61  4155.6 1951.30  4310.4 1951.03  4391.2 1952.29  4535.0 1952.74
  4784.5 1949.20  4995.8 1948.80  5034.4 1948.37  5034.9 1947.87  5040.4 1948.37
  5234.7 1949.09  5291.0 1948.70  5465.4 1952.43  5529.7 1951.75  5636.1 1955.90
  5728.2 1955.92  5749.0 1958.54  5756.6 1956.96  5769.9 1958.48  5890.5 1956.52
  6082.4 1961.33  6223.9 1962.31  6231.5 1964.57  6252.4 1963.13  6320.9 1965.99
#Mann=12,-1,0
  2946.3   0.035       0  3141.8    0.07       0  4095.7   0.035       0
  4155.6    0.07       0  4310.4   0.035       0  4391.2    0.07       0
  4784.5   0.035       0  4995.8    0.07       0  5034.4    0.07       0
  5040.4    0.07       0  5234.7   0.035       0  5291.0    0.07       0
Bank Sta=5034.4,5040.4
Exp/Cntr=0.3,0.1

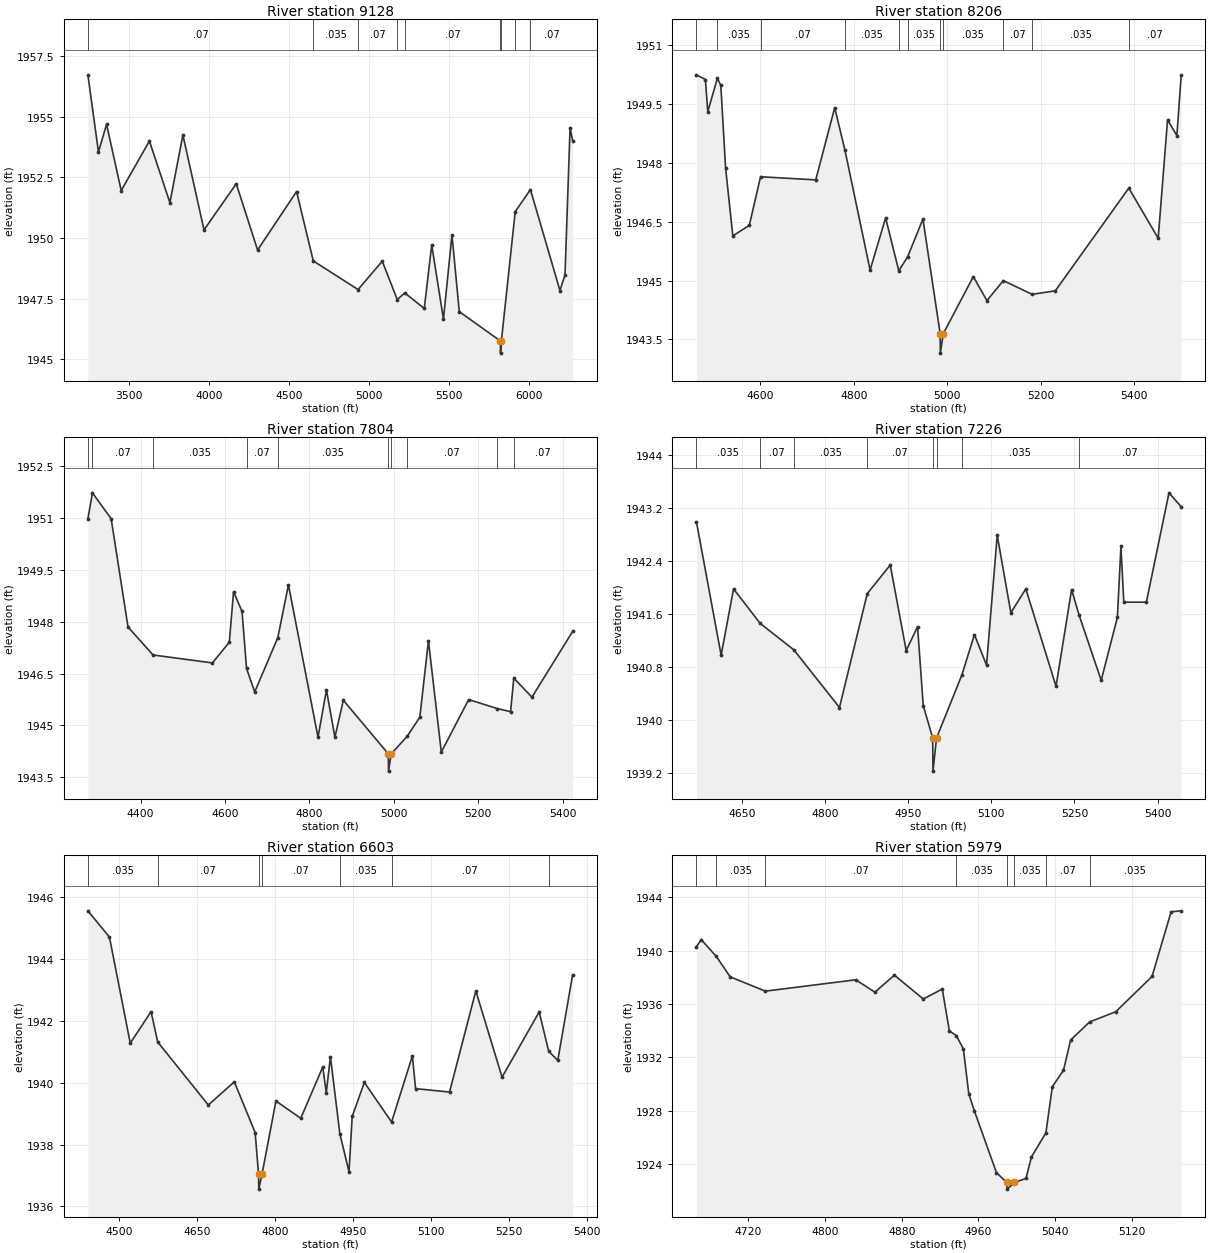
Type RM Length L Ch R = 1,9128,922,922,922
BEGIN DESCRIPTION:
UCFB HW Trib 04-03 6.0
END DESCRIPTION:
XS GIS Cut Line= 5
      1382629.97      6991263.00      1381198.82      6990997.74
      1380905.00      6991038.00      1380636.32      6991086.28
      1379679.97      6991413.01
#Sta/Elev= 30
  3240.5 1956.73  3306.6 1953.55  3357.4 1954.69  3449.0 1951.96  3625.8 1954.00
  3754.1 1951.46  3835.4 1954.25  3967.7 1950.34  4169.6 1952.24  4303.3 1949.51
  4547.4 1951.92  4652.0 1949.06  4932.5 1947.88  5084.0 1949.05  5177.7 1947.47
  5225.4 1947.74  5347.2 1947.10  5393.8 1949.72  5467.2 1946.66  5520.6 1950.13
  5566.4 1946.97  5824.1 1945.76  5824.6 1945.26  5830.1 1945.76  5916.8 1951.09
  6012.0 1952.00  6196.9 1947.84  6228.6 1948.48  6260.3 1954.55  6276.2 1954.02
#Mann=9,-1,0
  3240.5    0.07       0  4652.0   0.035       0  4932.5    0.07       0
  5177.7   0.035       0  5225.4    0.07       0  5824.1    0.07       0
  5830.1    0.07       0  5916.8   0.035       0  6012.0    0.07       0
Bank Sta=5824.1,5830.1
Exp/Cntr=0.3,0.1

Type RM Length L Ch R = 1,8206,402,402,402
BEGIN DESCRIPTION:
UCFB HW Trib 04-03 5.5
END DESCRIPTION:
XS GIS Cut Line= 4
      1380916.29      6990676.82      1380608.02      6990621.45
      1380301.33      6990765.00      1379915.79      6990778.55
#Sta/Elev= 30
  4463.3 1950.25  4482.4 1950.13  4487.5 1949.31  4508.0 1950.16  4515.4 1949.98
  4525.6 1947.88  4541.1 1946.14  4576.4 1946.41  4600.5 1947.65  4718.6 1947.57
  4759.2 1949.41  4780.9 1948.34  4835.0 1945.27  4868.2 1946.60  4896.4 1945.25
  4915.4 1945.61  4948.1 1946.57  4984.9 1943.65  4985.4 1943.15  4991.7 1943.65
  5055.9 1945.10  5085.1 1944.49  5120.2 1945.00  5181.8 1944.65  5231.5 1944.74
  5388.8 1947.36  5451.7 1946.08  5471.7 1949.10  5491.7 1948.70  5500.9 1950.24
#Mann=11,-1,0
  4463.3    0.07       0  4508.0   0.035       0  4600.5    0.07       0
  4780.9   0.035       0  4896.4    0.07       0  4915.4   0.035       0
  4984.9   0.035       0  4991.7   0.035       0  5120.2    0.07       0
  5181.8   0.035       0  5388.8    0.07       0
Bank Sta=4984.9,4991.7
Exp/Cntr=0.3,0.1

Type RM Length L Ch R = 1,7804,578,578,578
BEGIN DESCRIPTION:
UCFB HW Trib 04-03 5.0
END DESCRIPTION:
XS GIS Cut Line= 4
      1381030.04      6990363.00      1380305.00      6990388.00
      1380180.00      6990413.00      1379951.42      6990600.83
#Sta/Elev= 30
  4275.0 1950.98  4285.8 1951.73  4330.1 1950.98  4370.1 1947.85  4429.3 1947.04
  4570.2 1946.81  4610.2 1947.41  4620.2 1948.87  4640.3 1948.30  4651.0 1946.65
  4670.3 1945.97  4725.1 1947.54  4750.3 1949.07  4820.4 1944.66  4840.4 1946.03
  4860.4 1944.66  4880.4 1945.73  4987.0 1944.18  4987.5 1943.68  4993.9 1944.18
  5031.9 1944.69  5061.7 1945.24  5082.1 1947.45  5112.6 1944.23  5177.5 1945.75
  5245.3 1945.49  5276.8 1945.40  5284.4 1946.37  5327.4 1945.82  5423.8 1947.72
#Mann=10,-1,0
  4275.0   0.035       0  4285.8    0.07       0  4429.3   0.035       0
  4651.0    0.07       0  4725.1   0.035       0  4987.0   0.035       0
  4993.9   0.035       0  5031.9    0.07       0  5245.3   0.035       0
  5284.4    0.07       0
Bank Sta=4987,4993.9
Exp/Cntr=0.3,0.1

Type RM Length L Ch R = 1,7226,623,623,623
BEGIN DESCRIPTION:
UCFB HW Trib 04-03 4.5
END DESCRIPTION:
XS GIS Cut Line= 4
      1380517.76      6990048.32      1380280.00      6989863.00
      1380066.05      6989911.80      1379723.55      6989999.72
#Sta/Elev= 30
  4568.1 1942.99  4612.6 1940.98  4635.0 1941.98  4683.0 1941.46  4743.8 1941.06
  4826.1 1940.19  4876.3 1941.91  4917.7 1942.34  4946.5 1941.05  4967.0 1941.41
  4977.2 1940.22  4994.3 1939.73  4994.8 1939.23  5001.2 1939.73  5046.9 1940.68
  5069.6 1941.29  5091.4 1940.83  5110.7 1942.79  5135.3 1941.62  5162.3 1941.98
  5216.8 1940.51  5244.9 1941.97  5258.2 1941.59  5298.3 1940.60  5327.5 1941.55
  5333.9 1942.62  5339.1 1941.78  5379.8 1941.78  5420.6 1943.43  5442.6 1943.22
#Mann=8,-1,0
  4568.1   0.035       0  4683.0    0.07       0  4743.8   0.035       0
  4876.3    0.07       0  4994.3    0.07       0  5001.2    0.07       0
  5046.9   0.035       0  5258.2    0.07       0
Bank Sta=4994.3,5001.2
Exp/Cntr=0.3,0.1

Type RM Length L Ch R = 1,6603,624,624,624
BEGIN DESCRIPTION:
UCFB HW Trib 04-03 3.5
END DESCRIPTION:
XS GIS Cut Line= 3
      1380296.38      6989548.86      1379929.38      6989544.76
      1379468.48      6989870.67
#Sta/Elev= 30
  4440.3 1945.56  4481.7 1944.71  4521.7 1941.28  4561.7 1942.30  4574.4 1941.32
  4671.7 1939.28  4721.7 1940.03  4761.7 1938.39  4768.2 1937.06  4768.7 1936.56
  4775.1 1937.06  4801.7 1939.41  4849.4 1938.85  4891.6 1940.51  4898.4 1939.68
  4906.4 1940.84  4924.5 1938.35  4942.1 1937.12  4948.2 1938.91  4971.6 1940.01
  5023.9 1938.73  5063.9 1940.87  5070.0 1939.81  5135.3 1939.70  5185.8 1942.97
  5236.2 1940.18  5307.6 1942.29  5325.8 1941.02  5343.3 1940.72  5371.8 1943.49
#Mann=7,-1,0
  4440.3   0.035       0  4574.4    0.07       0  4768.2   0.035       0
  4775.1    0.07       0  4924.5   0.035       0  5023.9    0.07       0
  5325.8   0.035       0
Bank Sta=4768.2,4775.1
Exp/Cntr=0.3,0.1

Type RM Length L Ch R = 1,5979,731,731,731
BEGIN DESCRIPTION:
UCFB HW Trib 04-03 4.0
END DESCRIPTION:
XS GIS Cut Line= 4
      1379580.01      6989363.00      1379317.92      6989393.32
      1379213.75      6989450.83      1379250.31      6989568.03
#Sta/Elev= 30
  4665.9 1940.30  4670.9 1940.82  4686.6 1939.56  4701.1 1938.03  4737.8 1936.96
  4832.0 1937.81  4852.1 1936.88  4872.3 1938.16  4902.5 1936.37  4922.3 1937.12
  4929.7 1933.98  4937.0 1933.62  4944.3 1932.63  4950.0 1929.24  4955.9 1927.96
  4978.8 1923.36  4989.5 1922.62  4990.0 1922.12  4997.6 1922.62  5009.6 1922.92
  5015.3 1924.53  5030.4 1926.34  5037.1 1929.80  5048.7 1931.02  5056.2 1933.30
  5076.0 1934.65  5103.3 1935.42  5141.1 1938.06  5161.0 1942.91  5171.5 1942.98
#Mann=8,-1,0
  4665.9    0.07       0  4686.6   0.035       0  4737.8    0.07       0
  4937.0   0.035       0  4989.5   0.035       0  4997.6   0.035       0
  5030.4    0.07       0  5076.0   0.035       0
Bank Sta=4989.5,4997.6
Exp/Cntr=0.3,0.1

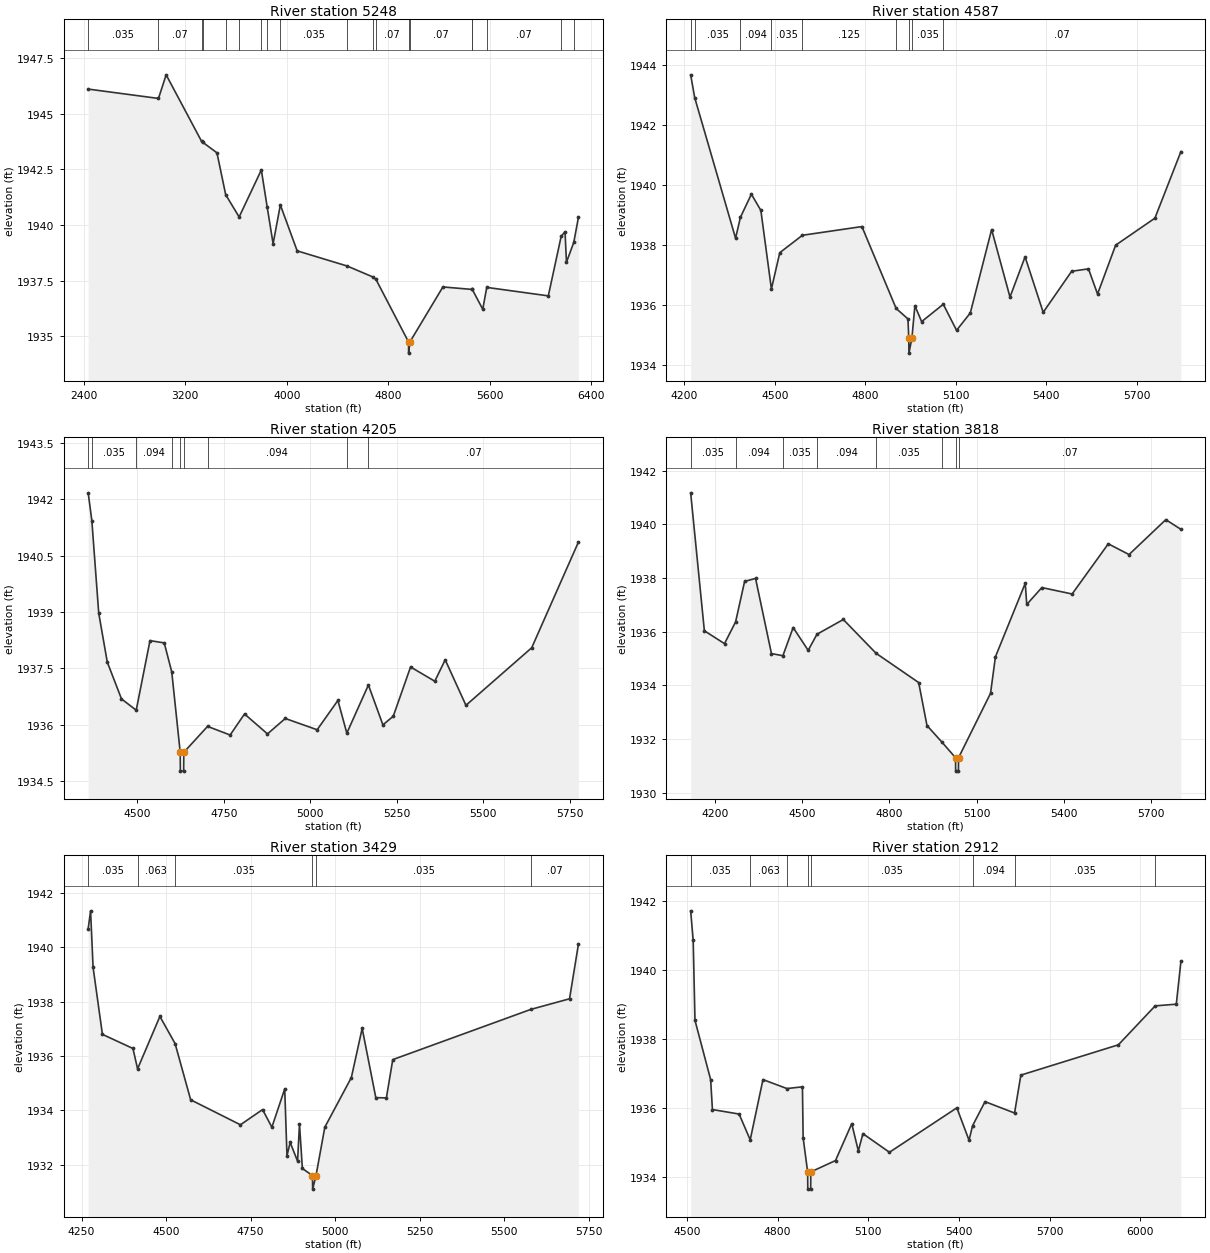
Type RM Length L Ch R = 1,5248,661,661,661
BEGIN DESCRIPTION:
UCFB HW Trib 04-03 3.4
END DESCRIPTION:
XS GIS Cut Line= 4
      1382108.35      6989912.63      1379933.20      6989195.66
      1379620.70      6988935.24      1378470.75      6989118.38
#Sta/Elev= 30
  2436.0 1946.10  2989.7 1945.68  3050.2 1946.74  3329.8 1943.75  3336.9 1943.72
  3450.3 1943.24  3519.2 1941.36  3625.0 1940.36  3799.9 1942.47  3846.4 1940.79
  3892.6 1939.16  3949.7 1940.90  4082.1 1938.84  4475.6 1938.16  4677.5 1937.67
  4702.7 1937.56  4959.6 1934.75  4960.1 1934.25  4969.9 1934.75  5230.0 1937.22
  5457.7 1937.11  5460.3 1937.12  5543.9 1936.22  5575.4 1937.20  6060.3 1936.82
  6161.6 1939.49  6191.9 1939.70  6203.4 1938.33  6260.9 1939.22  6297.5 1940.34
#Mann=19,-1,0
  2436.0   0.035       0  2989.7    0.07       0  3329.8   0.035       0
  3336.9    0.07       0  3519.2   0.035       0  3625.0    0.07       0
  3799.9   0.035       0  3846.4   0.094       0  3949.7   0.035       0
  4475.6    0.07       0  4677.5   0.035       0  4702.7    0.07       0
  4959.6   0.035       0  4969.9    0.07       0  5457.7    0.07       0
  5460.3   0.035       0  5575.4    0.07       0  6161.6   0.035       0
  6260.9    0.07       0
Bank Sta=4959.6,4969.9
Exp/Cntr=0.3,0.1

Type RM Length L Ch R = 1,4587,382,382,382
BEGIN DESCRIPTION:
UCFB HW Trib 04-03 2.5
END DESCRIPTION:
XS GIS Cut Line= 4
      1380937.25      6989144.60      1380314.14      6988951.64
      1380001.64      6988773.69      1379388.92      6988747.51
#Sta/Elev= 30
  4221.4 1943.67  4234.8 1942.91  4370.3 1938.22  4386.4 1938.92  4422.7 1939.69
  4454.1 1939.15  4489.1 1936.53  4516.9 1937.74  4591.9 1938.32  4789.1 1938.61
  4902.6 1935.88  4941.8 1935.53  4944.5 1934.89  4945.0 1934.39  4954.8 1934.89
  4964.8 1935.97  4987.1 1935.44  5058.9 1936.02  5102.9 1935.15  5148.5 1935.73
  5219.1 1938.51  5280.0 1936.26  5330.0 1937.60  5390.1 1935.75  5484.4 1937.12
  5540.2 1937.20  5570.3 1936.36  5630.3 1937.99  5760.4 1938.89  5846.6 1941.11
#Mann=9,-1,0
  4221.4    0.07       0  4234.8   0.035       0  4386.4   0.094       0
  4489.1   0.035       0  4591.9   0.125       0  4902.6   0.035       0
  4944.5   0.035       0  4954.8   0.035       0  5058.9    0.07       0
Bank Sta=4944.5,4954.8
Exp/Cntr=0.3,0.1

Type RM Length L Ch R = 1,4205,387,387,387
BEGIN DESCRIPTION:
UCFB HW Trib 04-03 3.0
END DESCRIPTION:
XS GIS Cut Line= 3
      1381028.58      6988740.51      1380405.00      6988588.00
      1379629.96      6988563.00
#Sta/Elev= 30
  4358.2 1942.17  4368.8 1941.43  4388.7 1938.97  4413.4 1937.67  4454.5 1936.69
  4497.1 1936.39  4536.9 1938.24  4578.1 1938.18  4599.8 1937.41  4624.3 1935.27
  4624.8 1934.77  4634.2 1934.77  4634.7 1935.27  4703.4 1935.96  4768.6 1935.73
  4810.2 1936.29  4876.6 1935.76  4928.1 1936.17  5020.2 1935.87  5080.2 1936.65
  5106.0 1935.78  5168.4 1937.06  5210.3 1936.00  5240.3 1936.23  5290.3 1937.54
  5360.3 1937.16  5390.4 1937.73  5450.4 1936.52  5640.5 1938.05  5775.6 1940.86
#Mann=9,-1,0
  4358.2    0.07       0  4368.8   0.035       0  4497.1   0.094       0
  4599.8   0.035       0  4624.3    0.07       0  4634.7   0.035       0
  4703.4   0.094       0  5106.0   0.035       0  5168.4    0.07       0
Bank Sta=4624.3,4634.7
Exp/Cntr=0.3,0.1

Type RM Length L Ch R = 1,3818,389,389,389
BEGIN DESCRIPTION:
UCFB HW Trib 04-03 2.1
END DESCRIPTION:
XS GIS Cut Line= 3
      1381057.88      6988620.28      1380094.36      6988181.06
      1379480.01      6988063.00
#Sta/Elev= 30
  4116.8 1941.17  4163.9 1936.03  4233.1 1935.55  4271.2 1936.36  4302.2 1937.87
  4339.8 1937.98  4394.4 1935.18  4433.7 1935.10  4469.0 1936.15  4520.6 1935.30
  4550.8 1935.90  4641.3 1936.45  4754.0 1935.19  4900.3 1934.10  4928.8 1932.50
  4980.2 1931.88  5026.9 1931.30  5027.4 1930.80  5036.8 1930.80  5037.3 1931.30
  5147.2 1933.70  5164.0 1935.06  5266.5 1937.80  5271.6 1937.01  5323.5 1937.64
  5427.5 1937.40  5551.8 1939.27  5623.1 1938.87  5749.4 1940.17  5801.3 1939.81
#Mann=8,-1,0
  4116.8   0.035       0  4271.2   0.094       0  4433.7   0.035       0
  4550.8   0.094       0  4754.0   0.035       0  4980.2    0.07       0
  5026.9    0.07       0  5037.3    0.07       0
Bank Sta=5026.9,5037.3
Exp/Cntr=0.3,0.1

Type RM Length L Ch R = 1,3429,517,517,517
BEGIN DESCRIPTION:
UCFB HW Trib 04-03 2.0
END DESCRIPTION:
XS GIS Cut Line= 3
      1381131.21      6988290.81      1380530.00      6987963.00
      1379768.88      6987883.86
#Sta/Elev= 30
  4269.4 1940.69  4276.5 1941.35  4283.9 1939.27  4311.5 1936.80  4401.8 1936.28
  4415.5 1935.53  4481.5 1937.46  4526.5 1936.46  4572.5 1934.39  4719.7 1933.47
  4785.2 1934.03  4812.7 1933.38  4850.7 1934.79  4857.4 1932.33  4866.8 1932.82
  4888.7 1932.13  4894.4 1933.50  4902.9 1931.86  4932.8 1931.60  4933.3 1931.10
  4943.3 1931.60  4969.3 1933.38  5047.8 1935.21  5079.8 1937.02  5120.1 1934.47
  5151.4 1934.46  5170.3 1935.87  5578.7 1937.72  5693.1 1938.11  5719.4 1940.12
#Mann=6,-1,0
  4269.4   0.035       0  4415.5   0.063       0  4526.5   0.035       0
  4932.8   0.035       0  4943.3   0.035       0  5578.7    0.07       0
Bank Sta=4932.8,4943.3
Exp/Cntr=0.3,0.1

Type RM Length L Ch R = 1,2912,546,546,546
BEGIN DESCRIPTION:
UCFB HW Trib 04-03 1.9
END DESCRIPTION:
XS GIS Cut Line= 4
      1381185.98      6988027.66      1380987.59      6987712.48
      1380679.80      6987541.47      1379789.88      6987656.15
#Sta/Elev= 30
  4512.1 1941.72  4520.5 1940.86  4526.4 1938.54  4578.2 1936.82  4584.1 1935.95
  4672.4 1935.82  4709.1 1935.07  4751.3 1936.82  4830.6 1936.56  4881.9 1936.61
  4884.2 1935.13  4899.1 1934.14  4899.6 1933.64  4909.1 1933.64  4909.6 1934.14
  4991.3 1934.47  5045.0 1935.54  5066.8 1934.75  5082.0 1935.25  5169.7 1934.71
  5392.7 1936.00  5433.0 1935.06  5444.7 1935.48  5485.9 1936.18  5583.6 1935.85
  5604.4 1936.95  5927.1 1937.83  6048.7 1938.96  6118.7 1939.01  6133.9 1940.25
#Mann=8,-1,0
  4512.1   0.035       0  4709.1   0.063       0  4830.6   0.035       0
  4899.1   0.035       0  4909.6   0.035       0  5444.7   0.094       0
  5583.6   0.035       0  6048.7    0.07       0
Bank Sta=4899.1,4909.6
Exp/Cntr=0.3,0.1

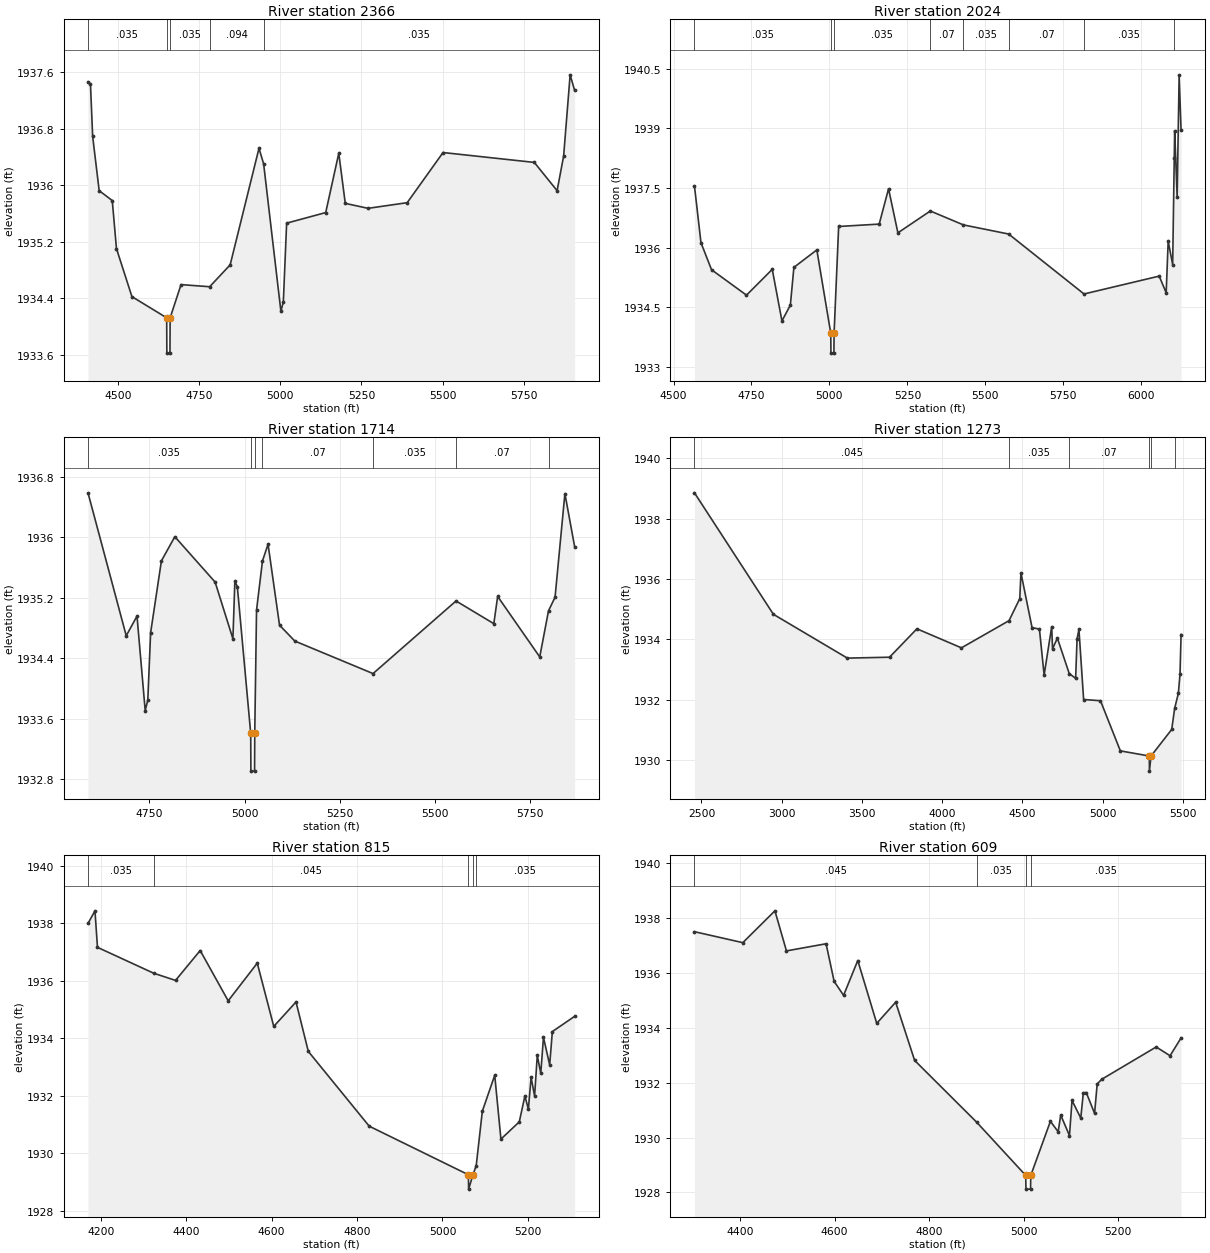
Type RM Length L Ch R = 1,2366,342,342,342
BEGIN DESCRIPTION:
UCFB HW Trib 04-03 1.0
END DESCRIPTION:
XS GIS Cut Line= 4
      1381260.76      6987702.15      1381198.26      6987210.82
      1381105.00      6987188.00      1380201.29      6987116.92
#Sta/Elev= 30
  4408.3 1937.46  4415.9 1937.43  4422.6 1936.69  4442.7 1935.92  4483.0 1935.78
  4495.9 1935.10  4543.5 1934.42  4650.5 1934.12  4651.0 1933.62  4660.6 1933.62
  4661.1 1934.12  4694.7 1934.59  4782.8 1934.56  4845.9 1934.87  4934.6 1936.52
  4948.9 1936.30  5002.1 1934.21  5009.6 1934.35  5019.7 1935.46  5140.0 1935.61
  5180.2 1936.45  5200.2 1935.74  5270.4 1935.67  5390.8 1935.75  5501.1 1936.46
  5782.0 1936.32  5852.2 1935.92  5872.3 1936.41  5892.3 1937.56  5906.1 1937.34
#Mann=5,-1,0
  4408.3   0.035       0  4650.5   0.035       0  4661.1   0.035       0
  4782.8   0.094       0  4948.9   0.035       0
Bank Sta=4650.5,4661.1
Exp/Cntr=0.3,0.1

Type RM Length L Ch R = 1,2024,310,310,310
BEGIN DESCRIPTION:
UCFB HW Trib 04-03 0.8
END DESCRIPTION:
XS GIS Cut Line= 4
      1381374.34      6987177.95      1381286.66      6986869.36
      1380280.00      6986863.00      1380098.51      6987009.61
#Sta/Elev= 30
  4567.1 1937.55  4588.0 1936.12  4621.9 1935.44  4734.0 1934.80  4816.6 1935.45
  4847.7 1934.15  4874.7 1934.55  4886.0 1935.50  4959.6 1935.94  5004.3 1933.84
  5004.8 1933.34  5014.4 1933.34  5014.9 1933.84  5029.6 1936.53  5159.6 1936.59
  5189.6 1937.48  5219.6 1936.37  5323.6 1936.92  5429.7 1936.57  5574.8 1936.34
  5816.6 1934.83  6057.7 1935.28  6080.1 1934.86  6086.5 1936.16  6100.9 1935.57
  6106.0 1938.26  6107.3 1938.94  6115.3 1937.28  6121.7 1940.35  6127.9 1938.95
#Mann=8,-1,0
  4567.1   0.035       0  5004.3   0.035       0  5014.9   0.035       0
  5323.6    0.07       0  5429.7   0.035       0  5574.8    0.07       0
  5816.6   0.035       0  6106.0    0.07       0
Bank Sta=5004.3,5014.9
Exp/Cntr=0.3,0.1

Type RM Length L Ch R = 1,1714,441,441,441
BEGIN DESCRIPTION:
UCFB HW Trib 04-03 0.9
END DESCRIPTION:
XS GIS Cut Line= 4
      1381458.64      6986796.39      1381277.68      6986629.06
      1381116.42      6986597.93      1380253.86      6986520.80
#Sta/Elev= 30
  4589.3 1936.59  4689.6 1934.70  4717.9 1934.96  4739.4 1933.71  4746.2 1933.85
  4753.6 1934.74  4781.9 1935.69  4817.1 1936.01  4922.8 1935.41  4969.5 1934.66
  4974.6 1935.42  4981.1 1935.35  5016.2 1933.41  5016.7 1932.91  5026.3 1932.91
  5026.8 1933.41  5031.5 1935.04  5047.1 1935.69  5061.7 1935.91  5091.8 1934.84
  5131.9 1934.63  5337.1 1934.20  5554.9 1935.16  5654.0 1934.86  5664.1 1935.22
  5774.5 1934.42  5797.5 1935.03  5814.7 1935.21  5840.5 1936.58  5866.0 1935.88
#Mann=7,-1,0
  4589.3   0.035       0  5016.2   0.035       0  5026.8   0.035       0
  5047.1    0.07       0  5337.1   0.035       0  5554.9    0.07       0
  5797.5   0.035       0
Bank Sta=5016.2,5026.8
Exp/Cntr=0.3,0.1

Type RM Length L Ch R = 1,1273,458,458,458
BEGIN DESCRIPTION:
UCFB HW Trib 04-03 0.7
END DESCRIPTION:
XS GIS Cut Line= 3
      1382877.52      6987877.66      1381592.20      6986337.59
      1380598.46      6986083.38
#Sta/Elev= 30
  2456.5 1938.85  2948.3 1934.83  3409.0 1933.38  3671.9 1933.41  3842.4 1934.35
  4119.7 1933.72  4416.4 1934.62  4483.2 1935.35  4490.5 1936.20  4559.7 1934.39
  4605.6 1934.34  4635.0 1932.82  4682.1 1934.42  4687.3 1933.69  4717.6 1934.04
  4791.3 1932.87  4831.2 1932.71  4840.2 1934.02  4851.8 1934.33  4881.0 1932.01
  4986.0 1931.97  5109.9 1930.31  5290.4 1930.14  5290.9 1929.64  5301.0 1930.14
  5429.8 1931.02  5448.3 1931.72  5471.1 1932.21  5481.4 1932.84  5488.2 1934.16
#Mann=6,-1,0
  2456.5   0.045       0  4416.4   0.035       0  4791.3    0.07       0
  5290.4    0.07       0  5301.0    0.07       0  5448.3   0.035       0
Bank Sta=5290.4,5301
Exp/Cntr=0.3,0.1

Type RM Length L Ch R = 1,815,206,206,206
BEGIN DESCRIPTION:
UCFB HW Trib 04-03 0.2
END DESCRIPTION:
XS GIS Cut Line= 4
      1381572.93      6986112.26      1381250.77      6985910.13
      1380751.58      6985848.14      1380595.25      6986050.43
#Sta/Elev= 30
  4170.3 1937.99  4186.6 1938.43  4192.5 1937.16  4324.0 1936.26  4375.2 1936.01
  4432.9 1937.05  4498.4 1935.30  4566.5 1936.61  4605.1 1934.41  4657.2 1935.26
  4686.0 1933.54  4828.5 1930.94  5060.7 1929.25  5061.2 1928.75  5071.4 1929.25
  5079.0 1929.57  5093.3 1931.46  5122.3 1932.71  5136.8 1930.49  5179.8 1931.09
  5192.9 1931.99  5201.1 1931.53  5207.4 1932.64  5215.6 1931.99  5221.9 1933.40
  5230.1 1932.78  5236.4 1934.03  5250.9 1933.07  5257.2 1934.23  5309.3 1934.76
#Mann=5,-1,0
  4170.3   0.035       0  4324.0   0.045       0  5060.7   0.045       0
  5071.4   0.045       0  5079.0   0.035       0
Bank Sta=5060.7,5071.4
Exp/Cntr=0.3,0.1

Type RM Length L Ch R = 1,609,257,257,257
BEGIN DESCRIPTION:
UCFB HW Trib 04-03 0.3
END DESCRIPTION:
XS GIS Cut Line= 4
      1381480.04      6985774.81      1381211.62      6985668.70
      1380761.37      6985645.86      1380650.51      6985913.22
#Sta/Elev= 30
  4303.9 1937.50  4406.1 1937.10  4474.0 1938.26  4498.4 1936.80  4582.2 1937.06
  4599.2 1935.69  4619.2 1935.18  4649.2 1936.45  4689.3 1934.16  4729.3 1934.93
  4769.4 1932.81  4900.5 1930.56  5004.3 1928.62  5004.8 1928.12  5014.5 1928.12
  5015.0 1928.62  5056.5 1930.59  5072.9 1930.21  5078.3 1930.82  5096.8 1930.07
  5102.2 1931.35  5120.7 1930.71  5126.1 1931.63  5132.3 1931.64  5149.9 1930.88
  5155.4 1931.95  5164.8 1932.12  5280.2 1933.30  5309.5 1932.98  5332.8 1933.63
#Mann=4,-1,0
  4303.9   0.045       0  4900.5   0.035       0  5004.3   0.035       0
  5015.0   0.035       0
Bank Sta=5004.3,5015
Exp/Cntr=0.3,0.1