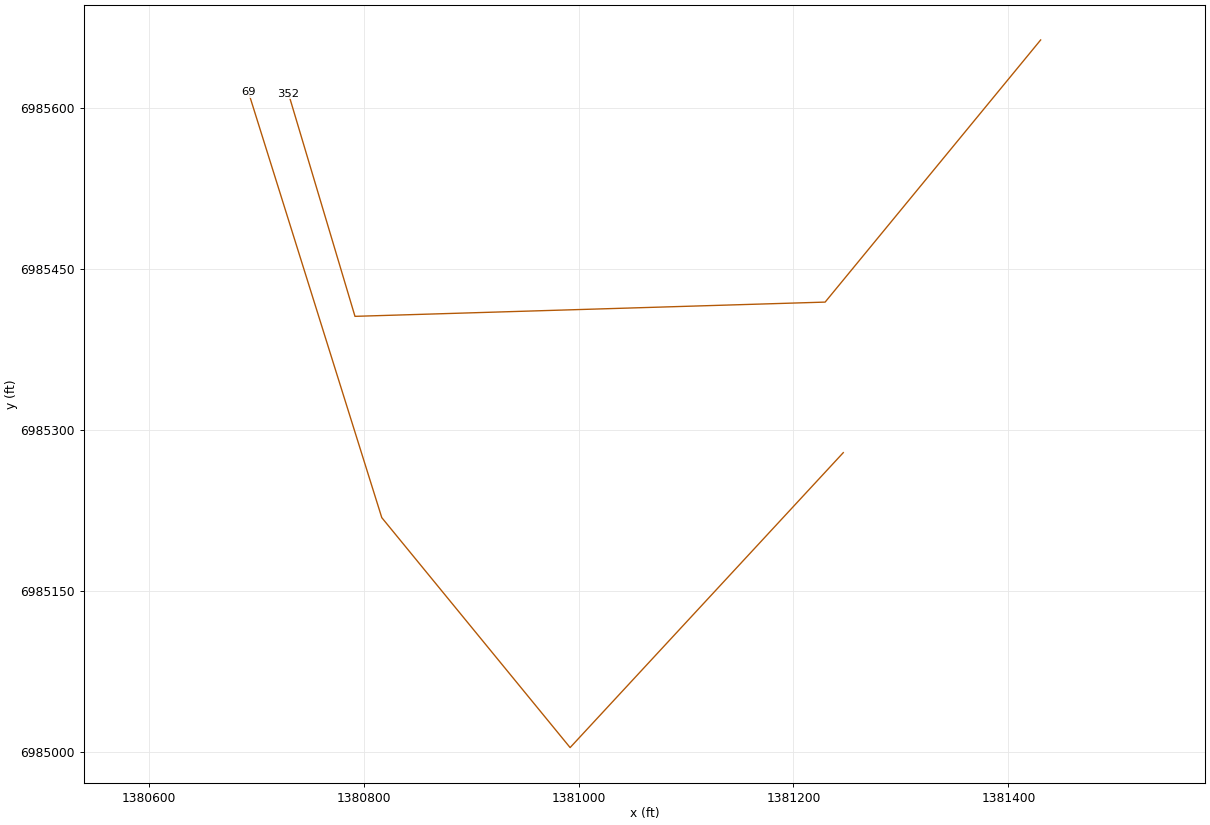
HEC-RAS study UCFB HW Trib 04-03.prj: UCFB HW Trib 04-03 Base Level Engineering

--- UCFB HW Trib 04-03.g01 (geometry) --- (continued)

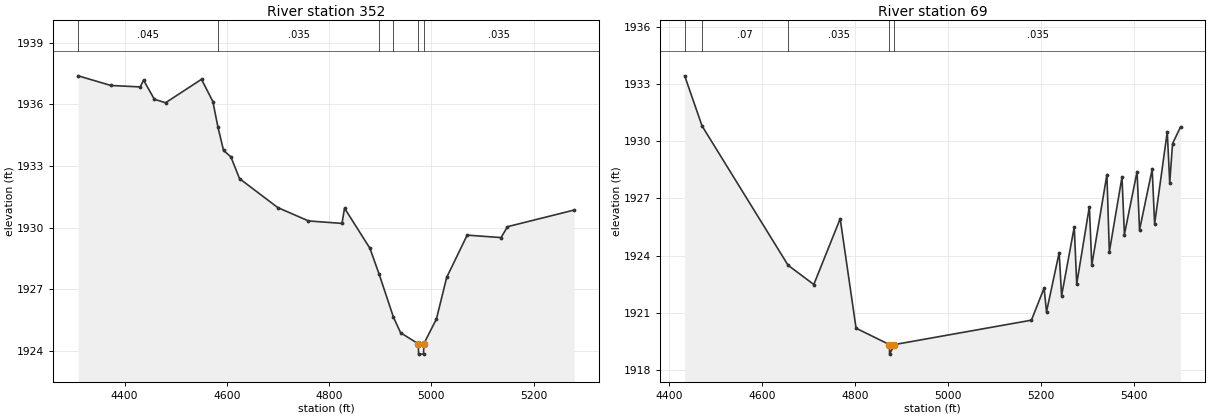
Type RM Length L Ch R = 1,352,283,283,283
BEGIN DESCRIPTION:
UCFB HW Trib 04-03 0.6
END DESCRIPTION:
XS GIS Cut Line= 4
      1381430.03      6985663.04      1381229.45      6985419.07
      1380791.88      6985405.81      1380730.01      6985612.97
#Sta/Elev= 30
  4309.3 1937.39  4373.2 1936.92  4430.6 1936.85  4437.1 1937.18  4458.2 1936.25
  4480.1 1936.08  4550.4 1937.22  4572.6 1936.14  4582.4 1934.91  4593.5 1933.76
  4607.8 1933.45  4624.7 1932.39  4699.6 1930.98  4759.6 1930.33  4825.1 1930.21
  4830.1 1930.95  4879.7 1929.00  4897.6 1927.75  4925.7 1925.65  4939.7 1924.89
  4974.4 1924.35  4974.9 1923.85  4984.6 1923.85  4985.1 1924.35  5009.8 1925.56
  5029.8 1927.58  5069.9 1929.64  5136.2 1929.52  5148.7 1930.05  5279.1 1930.86
#Mann=6,-1,0
  4309.3   0.045       0  4582.4   0.035       0  4897.6    0.07       0
  4925.7   0.035       0  4974.4   0.035       0  4985.1   0.035       0
Bank Sta=4974.4,4985.1
Exp/Cntr=0.3,0.1

Type RM Length L Ch R = 1,69,0,0,0
BEGIN DESCRIPTION:
UCFB HW Trib 04-03 0.5
END DESCRIPTION:
XS GIS Cut Line= 4
      1381246.34      6985278.95      1380992.11      6985004.46
      1380816.83      6985218.45      1380692.72      6985614.51
#Sta/Elev= 30
  4434.2 1933.42  4471.6 1930.79  4656.4 1923.49  4711.7 1922.48  4768.4 1925.93
  4802.5 1920.19  4874.1 1919.33  4874.6 1918.83  4884.8 1919.33  5179.4 1920.61
  5206.6 1922.29  5211.8 1921.05  5239.0 1924.15  5244.2 1921.89  5271.4 1925.49
  5276.7 1922.51  5303.9 1926.56  5309.1 1923.49  5341.6 1928.24  5346.8 1924.19
  5374.0 1928.11  5379.2 1925.10  5406.4 1928.40  5411.7 1925.34  5438.9 1928.52
  5444.1 1925.66  5471.3 1930.49  5476.6 1927.81  5482.7 1929.87  5500.0 1930.75
#Mann=5,-1,0
  4434.2   0.035       0  4471.6    0.07       0  4656.4   0.035       0
  4874.1   0.035       0  4884.8   0.035       0
Bank Sta=4874.1,4884.8
Exp/Cntr=0.3,0.1

Chan Stop Cuts=-1