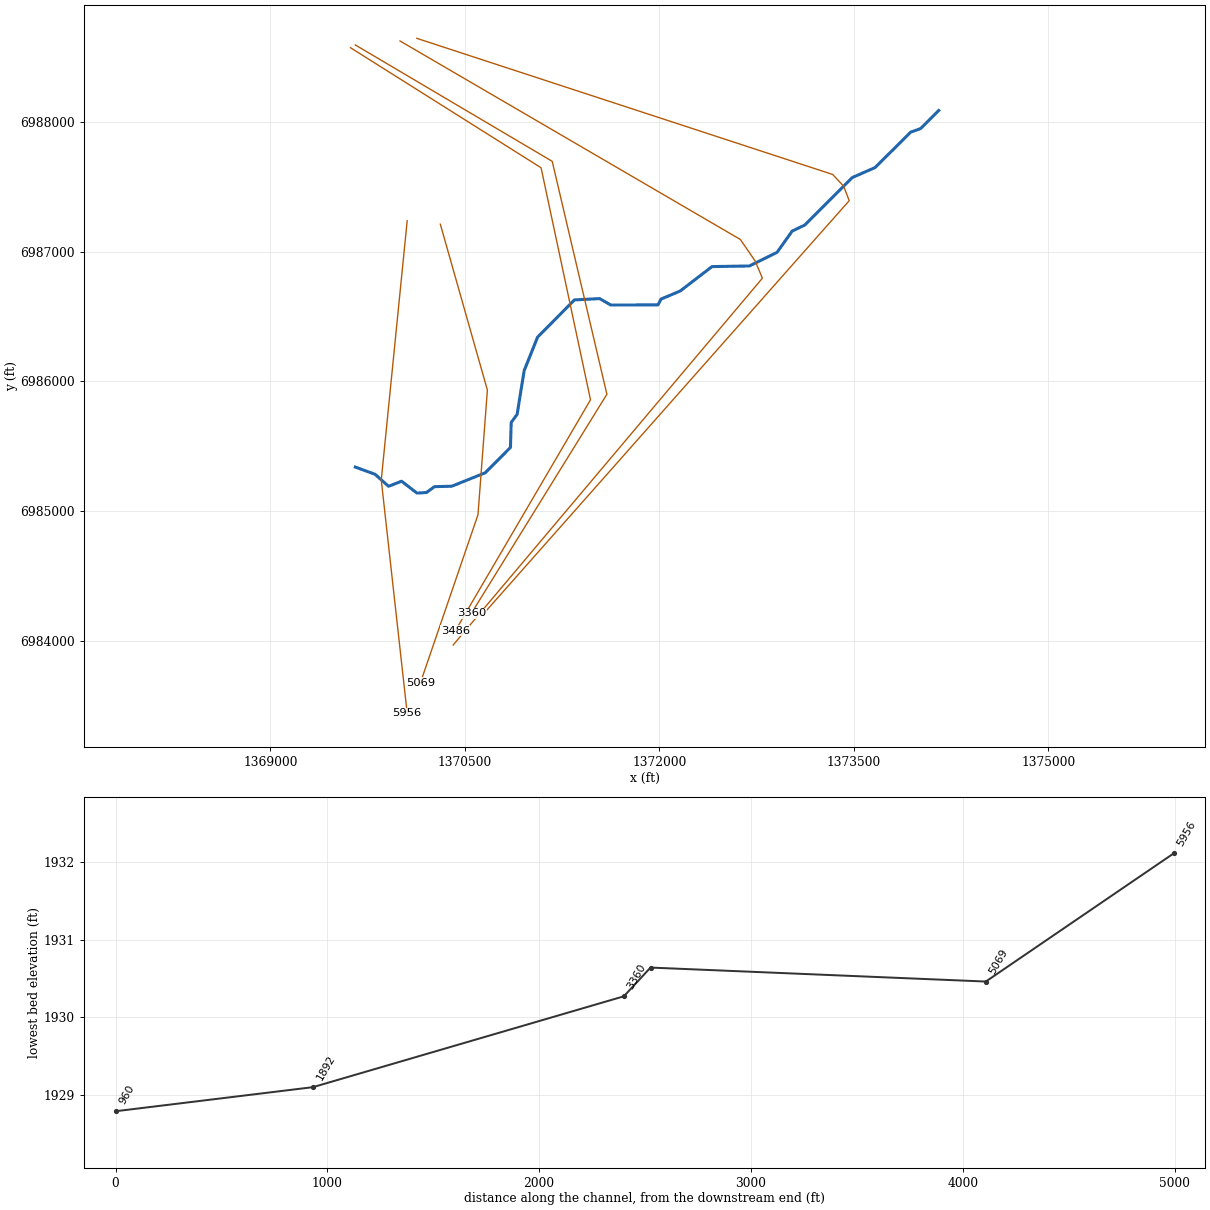
--- UCFB HW Trib 04-04.prj (project) ---

Proj Title=UCFB HW Trib 04-04 Base Level Engineering
Current Plan=p01
Default Exp/Contr=0.3,0.1
English Units
Geom File=g01
Flow File=f01
Plan File=p01
Y Axis Title=Elevation
X Axis Title(PF)=Main Channel Distance
X Axis Title(XS)=Station
BEGIN DESCRIPTION:
UCFB HW Trib 04-04
END DESCRIPTION:
DSS Export Rating Curves= 0
DSS Export Rating Curve Sorted= 0
DSS Export Volume Flow Curves= 0
DXF OffsetX= 0
DXF OffsetY= 0
DXF ScaleX= 1
DXF ScaleY= 10

--- UCFB HW Trib 04-04.p01 (plan) ---

Plan Title=Multiple Run
Short Identifier=Multiple
Geom File=g01
Flow File=f01
Subcritical Flow
K Sum by GR= 0
Std Step Tol= 0.01
Critical Tol= 0.01
Num of Std Step Trials= 20
Max Error Tol= 0.3
Flow Tol Ratio= 0.001
Split Flow NTrial= 30
Split Flow Tol= 0.02
Split Flow Ratio= 0.02
Log Output Level= 0
Friction Slope Method= 1
Unsteady Friction Slope Method= 2
Unsteady Bridges Friction Slope Method= 1
Parabolic Critical Depth
Global Vel Dist=  1 , 1 , 1
Global Log Level= 0
CheckData=True
Encroach Param= -1, 0, 0, 0
BEGIN DESCRIPTION:
Multiple Run
END DESCRIPTION:

--- UCFB HW Trib 04-04.f01 (steady flow) ---

Flow Title=Multiple
Program Version=4.10
Number of Profiles= 9
Profile Names=2-year,5-year,10-year,25-year,50-year,1pct_min,100-year,1pct_plu,500-year
River Rch & RM=UCFB HW Trib 04-,Reach-1         ,5956
     105     196     272     379     467     286     571    1139     864
Boundary for River Rch & Prof#=UCFB HW Trib 04-,Reach-1         , 1
Up Type= 0
Dn Type= 3
Dn Slope=0.0007
Boundary for River Rch & Prof#=UCFB HW Trib 04-,Reach-1         , 2
Up Type= 0
Dn Type= 3
Dn Slope=0.0007
Boundary for River Rch & Prof#=UCFB HW Trib 04-,Reach-1         , 3
Up Type= 0
Dn Type= 3
Dn Slope=0.0007
Boundary for River Rch & Prof#=UCFB HW Trib 04-,Reach-1         , 4
Up Type= 0
Dn Type= 3
Dn Slope=0.0007
Boundary for River Rch & Prof#=UCFB HW Trib 04-,Reach-1         , 5
Up Type= 0
Dn Type= 3
Dn Slope=0.0007
Boundary for River Rch & Prof#=UCFB HW Trib 04-,Reach-1         , 6
Up Type= 0
Dn Type= 3
Dn Slope=0.0007
Boundary for River Rch & Prof#=UCFB HW Trib 04-,Reach-1         , 7
Up Type= 0
Dn Type= 3
Dn Slope=0.0007
Boundary for River Rch & Prof#=UCFB HW Trib 04-,Reach-1         , 8
Up Type= 0
Dn Type= 3
Dn Slope=0.0007
Boundary for River Rch & Prof#=UCFB HW Trib 04-,Reach-1         , 9
Up Type= 0
Dn Type= 3
Dn Slope=0.0007
DSS Import GetInterval= 0
DSS Import GetPeak= 0
DSS Import FillOption= 0

--- UCFB HW Trib 04-04.g01 (geometry) ---

Geom Title=Existing Conditions

River Reach=UCFB HW Trib 04-,Reach-1
Reach XY= 30
      1369655.00      6985338.00      1369807.30      6985282.17
      1369911.05      6985189.67      1370011.72      6985228.83
      1370129.96      6985137.51      1370203.40      6985141.70
      1370265.51      6985186.77      1370399.06      6985190.27
      1370657.30      6985293.83      1370851.46      6985489.46
      1370857.26      6985682.06      1370902.73      6985743.94
      1370957.27      6986082.06      1371060.83      6986340.30
      1371345.20      6986627.52      1371539.78      6986637.48
      1371625.03      6986588.07      1371989.06      6986588.92
      1372013.65      6986634.09      1372161.05      6986696.16
      1372406.47      6986884.45      1372694.50      6986889.20
      1372907.55      6986993.73      1373024.77      6987158.42
      1373121.67      6987204.65      1373488.32      6987571.36
      1373664.68      6987648.76      1373938.33      6987921.35
      1374014.68      6987948.77      1374155.00      6988088.00

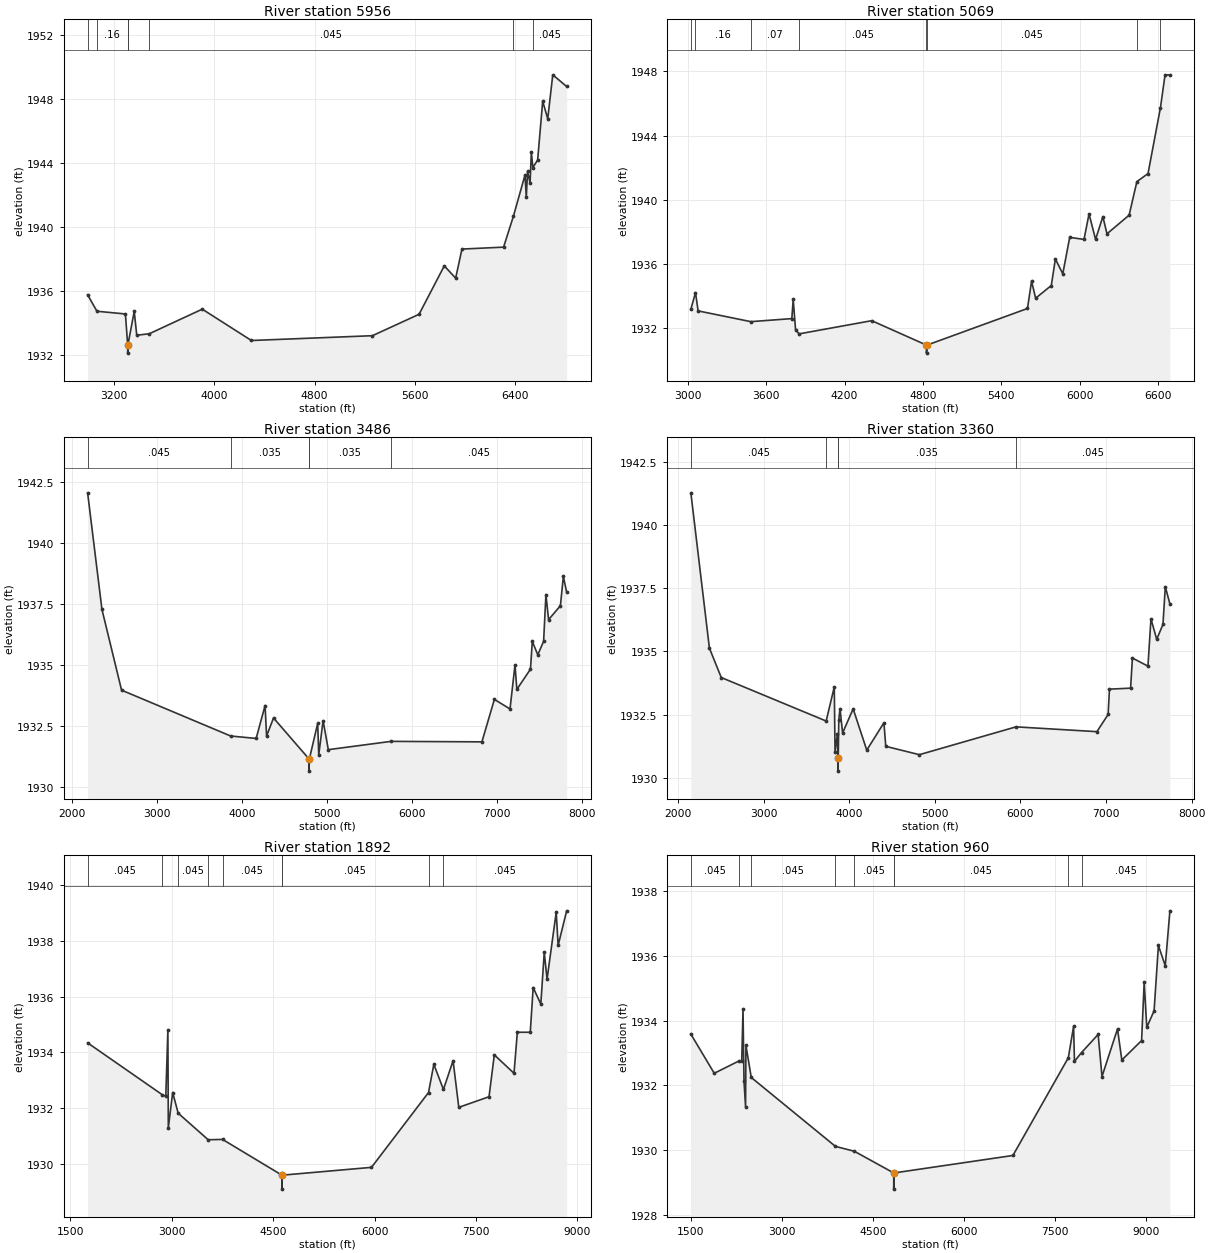
Type RM Length L Ch R = 1,5956,887,887,887
BEGIN DESCRIPTION:
UCFB HW Trib 04-04 3.0
END DESCRIPTION:
XS GIS Cut Line= 3
      1370055.00      6987237.96      1369855.00      6985238.00
      1370055.00      6983438.01
#Sta/Elev= 30
  2990.0 1935.76  3064.4 1934.73  3291.5 1934.56  3309.6 1932.61  3309.8 1932.11
  3313.6 1932.61  3314.6 1932.76  3361.8 1934.72  3381.9 1933.23  3481.1 1933.32
  3904.5 1934.86  4296.4 1932.90  5261.5 1933.20  5633.8 1934.54  5835.0 1937.57
  5925.6 1936.80  5975.9 1938.62  6307.9 1938.74  6387.0 1940.69  6479.0 1943.26
  6489.0 1941.86  6499.1 1943.48  6519.2 1942.74  6529.3 1944.68  6541.4 1943.72
  6579.6 1944.19  6619.8 1947.87  6660.1 1946.77  6700.3 1949.52  6811.0 1948.79
#Mann=8,-1,0
  2990.0    0.07       0  3064.4    0.16       0  3309.6   0.045       0
  3313.6    0.16       0  3314.6    0.07       0  3481.1   0.045       0
  6387.0   0.035       0  6541.4   0.045       0
Bank Sta=3309.6,3313.6
Exp/Cntr=0.3,0.1

Type RM Length L Ch R = 1,5069,1583,1583,1583
BEGIN DESCRIPTION:
UCFB HW Trib 04-04 2.1
END DESCRIPTION:
XS GIS Cut Line= 4
      1370310.57      6987211.44      1370673.58      6985931.86
      1370600.98      6984969.95      1370156.44      6983672.62
#Sta/Elev= 30
  3023.7 1933.19  3059.2 1934.23  3079.2 1933.09  3482.4 1932.42  3796.5 1932.61
  3806.9 1933.81  3825.1 1931.91  3852.6 1931.66  4407.8 1932.48  4826.9 1930.96
  4827.2 1930.46  4831.0 1930.96  5599.8 1933.24  5631.1 1934.94  5662.4 1933.88
  5782.2 1934.67  5813.5 1936.32  5870.2 1935.40  5923.0 1937.67  6032.5 1937.54
  6071.0 1939.13  6121.0 1937.54  6176.7 1938.96  6208.4 1937.89  6377.6 1939.05
  6437.2 1941.14  6522.4 1941.64  6617.6 1945.75  6652.8 1947.79  6689.8 1947.78
#Mann=8,-1,0
  3023.7   0.035       0  3059.2    0.16       0  3482.4    0.07       0
  3852.6   0.045       0  4826.9   0.045       0  4831.0   0.045       0
  6437.2   0.035       0  6617.6   0.045       0
Bank Sta=4826.9,4831
Exp/Cntr=0.3,0.1

Type RM Length L Ch R = 1,3486,126,126,126
BEGIN DESCRIPTION:
UCFB HW Trib 04-04 2.0
END DESCRIPTION:
XS GIS Cut Line= 4
      1369617.68      6988572.82      1371087.65      6987646.94
      1371469.02      6985856.89      1370425.82      6984074.52
#Sta/Elev= 30
  2187.4 1942.05  2355.8 1937.27  2586.5 1933.96  3869.2 1932.08  4169.0 1931.98
  4274.1 1933.33  4291.7 1932.08  4373.4 1932.82  4790.3 1931.14  4790.7 1930.64
  4794.9 1931.14  4892.8 1932.60  4905.1 1931.31  4956.2 1932.71  5017.6 1931.52
  5755.2 1931.86  6823.7 1931.84  6970.2 1933.58  7154.2 1933.19  7212.8 1935.00
  7234.3 1933.99  7394.6 1934.82  7416.1 1935.96  7480.6 1935.41  7549.1 1935.96
  7576.4 1937.88  7607.5 1936.85  7746.5 1937.42  7781.3 1938.62  7820.1 1937.98
#Mann=5,-1,0
  2187.4   0.045       0  3869.2   0.035       0  4790.3   0.035       0
  4794.9   0.035       0  5755.2   0.045       0
Bank Sta=4790.3,4794.9
Exp/Cntr=0.3,0.1

Type RM Length L Ch R = 1,3360,1468,1468,1468
BEGIN DESCRIPTION:
UCFB HW Trib 04-04 1.5
END DESCRIPTION:
XS GIS Cut Line= 4
      1369654.87      6988594.16      1371173.59      6987696.42
      1371595.46      6985899.54      1370550.09      6984209.93
#Sta/Elev= 30
  2148.9 1941.27  2365.7 1935.13  2504.1 1933.97  3729.8 1932.25  3824.6 1933.60
  3833.4 1931.04  3861.7 1931.75  3866.0 1930.77  3866.3 1930.27  3870.6 1930.77
  3877.3 1932.31  3891.5 1932.74  3921.8 1931.78  4045.0 1932.73  4204.0 1931.10
  4404.5 1932.18  4426.3 1931.25  4818.4 1930.92  5947.6 1932.02  6893.0 1931.83
  7024.2 1932.51  7039.6 1933.51  7286.6 1933.55  7307.9 1934.74  7489.3 1934.42
  7524.5 1936.29  7591.5 1935.48  7664.8 1936.07  7692.0 1937.56  7745.7 1936.88
#Mann=5,-1,0
  2148.9   0.045       0  3729.8   0.035       0  3866.0   0.035       0
  3870.6   0.035       0  5947.6   0.045       0
Bank Sta=3866,3870.6
Exp/Cntr=0.3,0.1

Type RM Length L Ch R = 1,1892,932,932,932
BEGIN DESCRIPTION:
UCFB HW Trib 04-04 1.0
END DESCRIPTION:
XS GIS Cut Line= 5
      1369999.64      6988624.90      1372624.93      6987093.57
      1372739.15      6986927.26      1372795.07      6986794.96
      1370409.68      6983965.57
#Sta/Elev= 30
  1754.4 1934.34  2859.9 1932.48  2910.9 1932.43  2941.5 1934.81  2948.1 1931.30
  3012.6 1932.56  3093.9 1931.82  3537.2 1930.87  3750.9 1930.88  4628.5 1929.60
  4628.9 1929.10  4633.4 1929.60  5953.1 1929.88  6796.5 1932.56  6875.1 1933.57
  7017.2 1932.67  7159.8 1933.70  7244.4 1932.03  7691.7 1932.41  7769.7 1933.91
  8061.0 1933.25  8110.4 1934.72  8301.6 1934.72  8344.5 1936.32  8457.7 1935.73
  8508.3 1937.58  8550.0 1936.62  8685.2 1939.02  8713.8 1937.83  8839.8 1939.07
#Mann=9,-1,0
  1754.4   0.045       0  2859.9   0.035       0  3093.9   0.045       0
  3537.2   0.035       0  3750.9   0.045       0  4628.5   0.045       0
  4633.4   0.045       0  6796.5   0.035       0  7017.2   0.045       0
Bank Sta=4628.5,4633.4
Exp/Cntr=0.3,0.1

Type RM Length L Ch R = 1,960,0,0,0
BEGIN DESCRIPTION:
UCFB HW Trib 04-04 0.9
END DESCRIPTION:
XS GIS Cut Line= 5
      1370129.07      6988645.20      1373336.73      6987595.31
      1373421.65      6987504.70      1373464.66      6987392.93
      1370637.24      6984198.56
#Sta/Elev= 30
  1500.7 1933.58  1885.7 1932.37  2292.6 1932.75  2338.2 1932.75  2359.2 1934.35
  2375.4 1932.12  2401.3 1931.33  2407.2 1933.23  2494.9 1932.24  3881.2 1930.11
  4191.7 1929.96  4839.9 1929.29  4840.3 1928.79  4845.0 1929.29  6801.9 1929.83
  7713.9 1932.85  7800.6 1933.82  7814.9 1932.74  7931.4 1933.01  8204.6 1933.57
  8268.2 1932.27  8523.3 1933.74  8594.4 1932.78  8919.8 1933.38  8962.4 1935.18
  9005.1 1933.79  9125.5 1934.30  9196.7 1936.32  9309.6 1935.69  9385.7 1937.39
#Mann=9,-1,0
  1500.7   0.045       0  2292.6   0.035       0  2494.9   0.045       0
  3881.2   0.035       0  4191.7   0.045       0  4839.9   0.045       0
  4845.0   0.045       0  7713.9   0.035       0  7931.4   0.045       0
Bank Sta=4839.9,4845
Exp/Cntr=0.3,0.1

Chan Stop Cuts=-1