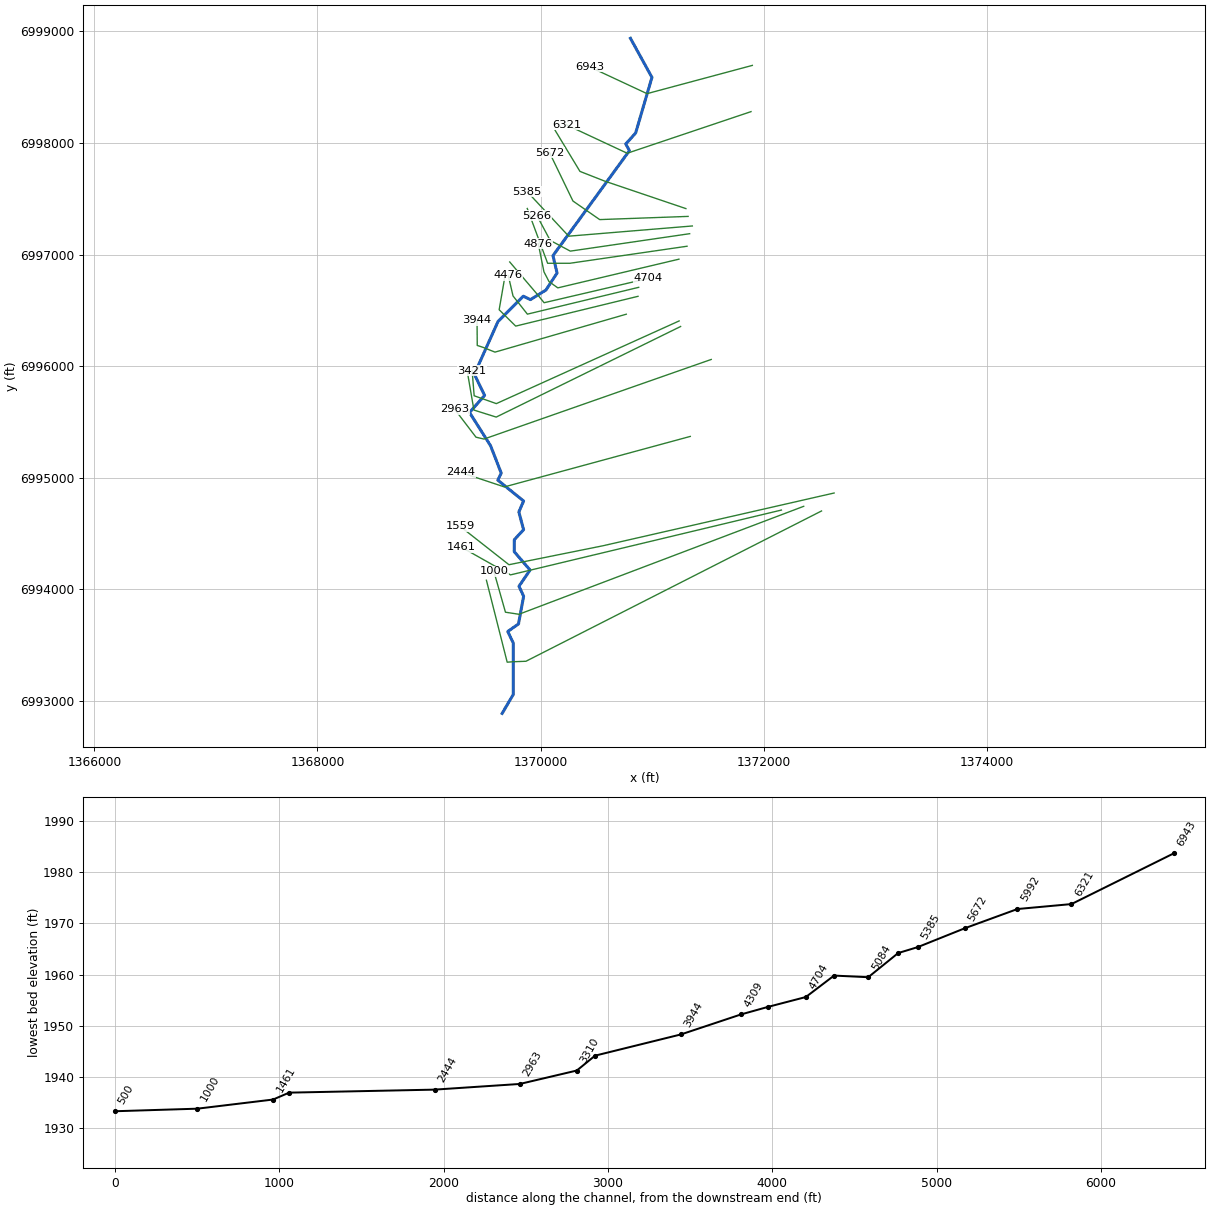
--- UCFB HW Trib 04-05.prj (project) ---

Proj Title=UCFB HW Trib 04-05 Base Level Engineering
Current Plan=p01
Default Exp/Contr=0.3,0.1
English Units
Geom File=g01
Flow File=f01
Plan File=p01
BEGIN DESCRIPTION:
UCFB HW Trib 04-05
END DESCRIPTION:

--- UCFB HW Trib 04-05.p01 (plan) ---

Plan Title=Multiple Run
Short Identifier=Multiple
Geom File=g01
Flow File=f01
Subcritical Flow
K Sum by GR= 0
Std Step Tol= 0.01
Critical Tol= 0.01
Num of Std Step Trials= 20
Max Error Tol= 0.3
Flow Tol Ratio= 0.001
Split Flow NTrial= 30
Split Flow Tol= 0.02
Split Flow Ratio= 0.02
Log Output Level= 0
Friction Slope Method= 1
Unsteady Friction Slope Method= 2
Unsteady Bridges Friction Slope Method= 1
Parabolic Critical Depth
Global Vel Dist=  1 , 1 , 1
Global Log Level= 0
CheckData=True
Encroach Param= -1, 0, 0, 0
BEGIN DESCRIPTION:
Multiple Run
END DESCRIPTION:

--- UCFB HW Trib 04-05.f01 (steady flow) ---

Flow Title=Multiple
Number of Profiles=7
Profile Names=10-year,25-year,50-year,1pct_min,100-year,1pct_plu,500-year
River Rch & RM= UCFB HW Trib 04-,Reach-1,6943
     230     321     397     244     488     973     745
River Rch & RM= UCFB HW Trib 04-,Reach-1,500
     248     349     433     267     533    1063     818
Boundary for River Rch & Prof#=UCFB HW Trib 04-,Reach-1,1
Up Type=0
Dn Type=3
Dn Slope=0.005
Boundary for River Rch & Prof#=UCFB HW Trib 04-,Reach-1,2
Up Type=0
Dn Type=3
Dn Slope=0.005
Boundary for River Rch & Prof#=UCFB HW Trib 04-,Reach-1,3
Up Type=0
Dn Type=3
Dn Slope=0.005
Boundary for River Rch & Prof#=UCFB HW Trib 04-,Reach-1,4
Up Type=0
Dn Type=3
Dn Slope=0.005
Boundary for River Rch & Prof#=UCFB HW Trib 04-,Reach-1,5
Up Type=0
Dn Type=3
Dn Slope=0.005
Boundary for River Rch & Prof#=UCFB HW Trib 04-,Reach-1,6
Up Type=0
Dn Type=3
Dn Slope=0.005
Boundary for River Rch & Prof#=UCFB HW Trib 04-,Reach-1,7
Up Type=0
Dn Type=3
Dn Slope=0.005

--- UCFB HW Trib 04-05.g01 (geometry) ---

Geom Title=Existing Conditions

River Reach=UCFB HW Trib 04-,Reach-1
Reach XY= 30
      1370805.00      6998938.00      1370997.44      6998588.00
      1370851.36      6998089.50      1370763.02      6997991.33
      1370795.68      6997931.34      1370110.40      6996990.43
      1370147.19      6996834.59      1370046.96      6996681.67
      1369908.23      6996596.25      1369845.00      6996626.76
      1369618.40      6996401.30      1369405.76      6995927.31
      1369497.71      6995737.91      1369362.60      6995584.67
      1369551.38      6995286.50      1369646.75      6995041.23
      1369616.23      6994977.98      1369847.21      6994791.43
      1369804.54      6994693.17      1369847.18      6994534.58
      1369764.33      6994444.67      1369762.54      6994338.00
      1369905.11      6994172.64      1369805.65      6994027.36
      1369847.41      6993938.01      1369801.52      6993689.26
      1369705.25      6993621.98      1369754.91      6993517.99
      1369755.04      6993057.98      1369655.00      6992888.00

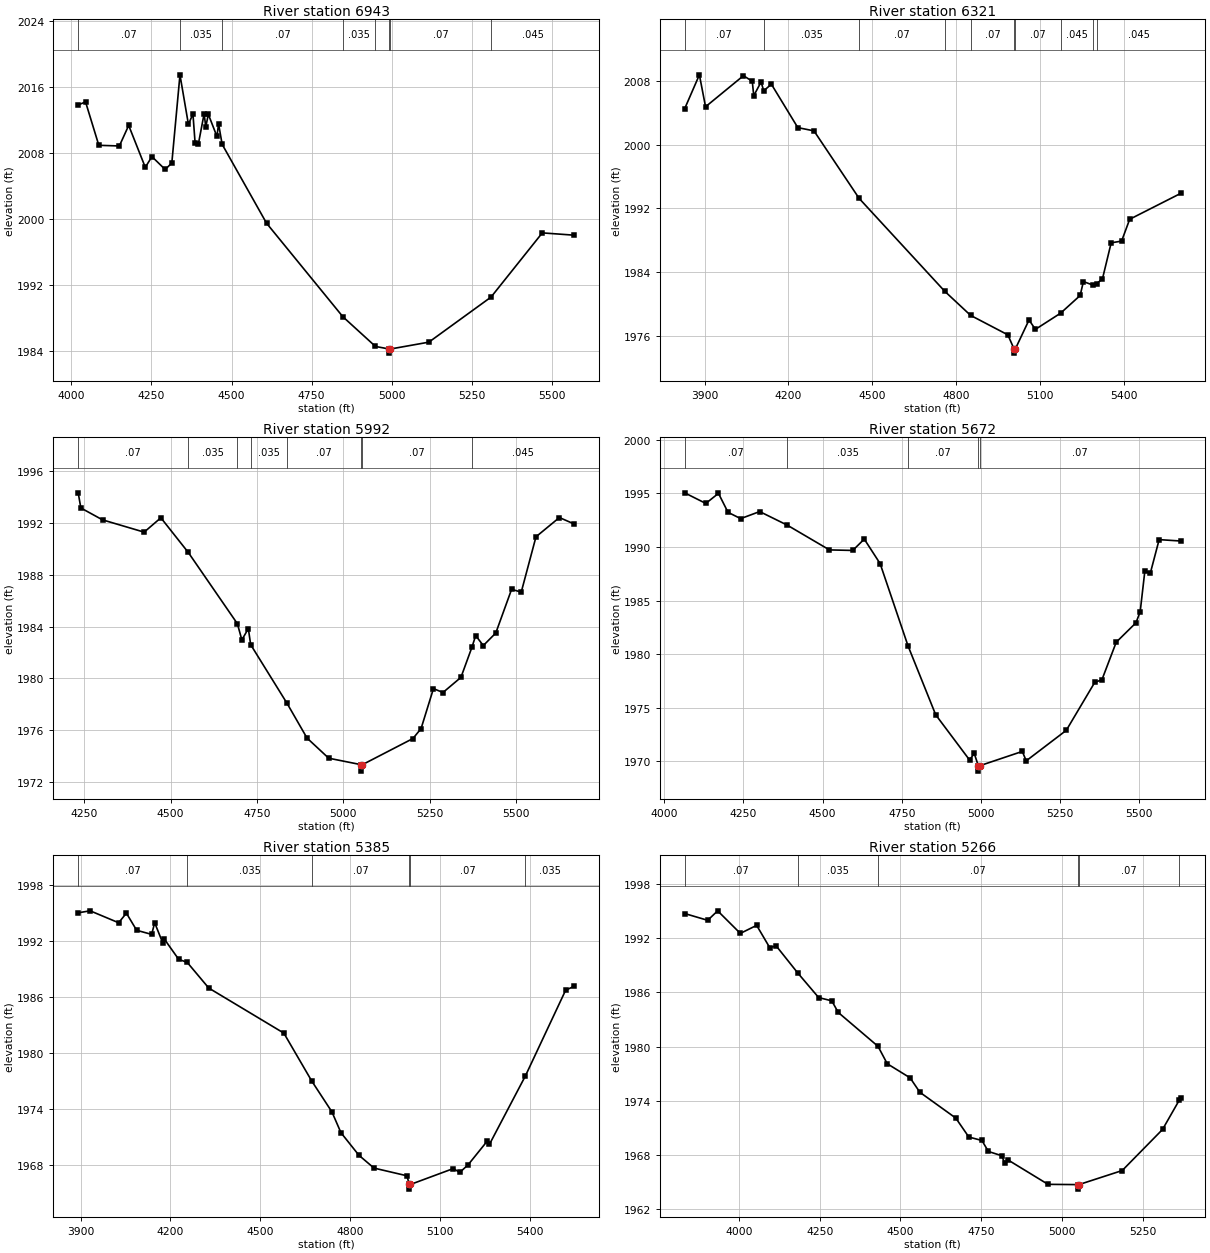
Type RM Length L Ch R = 1,6943,622,622,622
BEGIN DESCRIPTION:
UCFB HW Trib 04-05 12.0
END DESCRIPTION:
XS GIS Cut Line= 3
      1371897.15      6998695.42      1370953.47      6998442.24
      1370436.54      6998683.47
#Sta/Elev= 30
  4021.6 2013.79  4044.5 2014.16  4085.9 2008.90  4150.0 2008.82  4179.1 2011.31
  4230.9 2006.23  4251.6 2007.53  4293.0 2005.97  4313.7 2006.76  4339.1 2017.44
  4365.5 2011.43  4379.6 2012.71  4386.2 2009.24  4396.6 2009.07  4414.5 2012.73
  4419.6 2011.12  4427.6 2012.66  4454.5 2009.97  4459.6 2011.49  4470.7 2009.02
  4609.3 1999.46  4847.4 1988.13  4949.1 1984.53  4991.8 1984.22  4992.1 1983.72
  4995.8 1984.22  5115.8 1985.05  5309.7 1990.51  5469.7 1998.29  5569.1 1998.01
#Mann=8,-1,0
  4021.6    0.07       0  4339.1   0.035       0  4470.7    0.07       0
  4847.4   0.035       0  4949.1    0.07       0  4991.8    0.07       0
  4995.8    0.07       0  5309.7   0.045       0
Bank Sta=4991.8,4995.8
Exp/Cntr=0.3,0.1

Type RM Length L Ch R = 1,6321,329,329,329
BEGIN DESCRIPTION:
UCFB HW Trib 04-05 11.0
END DESCRIPTION:
XS GIS Cut Line= 3
      1371885.69      6998281.14      1370775.82      6997908.03
      1370230.03      6998162.98
#Sta/Elev= 30
  3829.1 2004.55  3881.7 2008.81  3903.7 2004.79  4039.2 2008.70  4070.8 2008.00
  4076.0 2006.18  4102.3 2007.91  4111.7 2006.80  4139.1 2007.63  4233.6 2002.17
  4291.4 2001.76  4453.0 1993.26  4758.7 1981.59  4851.4 1978.55  4984.7 1976.10
  5007.1 1974.30  5007.3 1973.80  5011.1 1974.30  5060.3 1977.97  5083.2 1976.79
  5173.4 1978.83  5243.1 1981.05  5254.8 1982.80  5289.2 1982.36  5301.7 1982.55
  5322.7 1983.11  5354.1 1987.68  5391.3 1987.89  5420.3 1990.64  5602.4 1993.89
#Mann=10,-1,0
  3829.1    0.07       0  4111.7   0.035       0  4453.0    0.07       0
  4758.7   0.035       0  4851.4    0.07       0  5007.1    0.07       0
  5011.1    0.07       0  5173.4   0.045       0  5289.2    0.07       0
  5301.7   0.045       0
Bank Sta=5007.1,5011.1
Exp/Cntr=0.3,0.1

Type RM Length L Ch R = 1,5992,320,320,320
BEGIN DESCRIPTION:
UCFB HW Trib 04-05 10.0
END DESCRIPTION:
XS GIS Cut Line= 4
      1371301.64      6997412.10      1370574.93      6997658.03
      1370352.35      6997745.44      1370130.00      6998112.99
#Sta/Elev= 30
  4232.8 1994.35  4240.4 1993.18  4303.2 1992.26  4423.7 1991.31  4472.1 1992.42
  4551.5 1989.74  4693.6 1984.23  4706.6 1982.98  4725.4 1983.85  4732.1 1982.61
  4837.7 1978.06  4895.2 1975.39  4958.0 1973.83  5051.6 1973.33  5051.9 1972.83
  5055.6 1973.33  5201.9 1975.35  5225.5 1976.12  5261.3 1979.21  5288.9 1978.91
  5340.9 1980.08  5372.6 1982.40  5383.6 1983.31  5405.7 1982.54  5441.8 1983.51
  5487.6 1986.89  5515.5 1986.67  5558.2 1990.95  5626.0 1992.44  5668.7 1991.94
#Mann=8,-1,0
  4232.8    0.07       0  4551.5   0.035       0  4693.6    0.07       0
  4732.1   0.035       0  4837.7    0.07       0  5051.6    0.07       0
  5055.6    0.07       0  5372.6   0.045       0
Bank Sta=5051.6,5055.6
Exp/Cntr=0.3,0.1

Type RM Length L Ch R = 1,5672,287,287,287
BEGIN DESCRIPTION:
UCFB HW Trib 04-05 9.5
END DESCRIPTION:
XS GIS Cut Line= 4
      1371321.67      6997342.12      1370529.10      6997313.48
      1370289.36      6997480.08      1370080.01      6997912.98
#Sta/Elev= 30
  4064.5 1995.06  4131.2 1994.07  4171.2 1995.01  4201.3 1993.24  4241.3 1992.65
  4301.3 1993.31  4388.5 1992.04  4521.5 1989.73  4595.2 1989.68  4631.5 1990.74
  4681.6 1988.45  4769.9 1980.75  4857.1 1974.33  4964.0 1970.11  4978.8 1970.72
  4991.7 1969.57  4991.9 1969.07  4995.7 1969.57  5130.5 1970.91  5142.9 1970.03
  5269.4 1972.88  5359.3 1977.36  5381.9 1977.60  5427.1 1981.11  5489.3 1982.92
  5502.7 1983.95  5517.5 1987.77  5534.5 1987.53  5562.6 1990.69  5630.4 1990.56
#Mann=5,-1,0
  4064.5    0.07       0  4388.5   0.035       0  4769.9    0.07       0
  4991.7    0.07       0  4995.7    0.07       0
Bank Sta=4991.7,4995.7
Exp/Cntr=0.3,0.1

Type RM Length L Ch R = 1,5385,119,119,119
BEGIN DESCRIPTION:
UCFB HW Trib 04-05 9.0
END DESCRIPTION:
XS GIS Cut Line= 3
      1371359.51      6997256.31      1370251.46      6997164.82
      1369879.98      6997563.02
#Sta/Elev= 30
  3892.0 1995.04  3931.9 1995.25  4027.0 1993.97  4052.9 1995.00  4087.2 1993.16
  4137.3 1992.72  4147.4 1993.97  4173.9 1991.84  4178.9 1992.25  4227.6 1990.04
  4255.9 1989.72  4328.0 1986.96  4578.8 1982.12  4671.9 1976.98  4739.4 1973.66
  4769.5 1971.43  4829.7 1969.00  4879.9 1967.63  4990.2 1966.80  4997.5 1965.87
  4997.8 1965.37  5001.5 1965.87  5144.9 1967.58  5166.3 1967.16  5194.7 1968.00
  5258.2 1970.53  5265.5 1970.18  5385.5 1977.52  5520.0 1986.73  5548.4 1987.15
#Mann=6,-1,0
  3892.0    0.07       0  4255.9   0.035       0  4671.9    0.07       0
  4997.5    0.07       0  5001.5    0.07       0  5385.5   0.035       0
Bank Sta=4997.5,5001.5
Exp/Cntr=0.3,0.1

Type RM Length L Ch R = 1,5266,182,182,182
BEGIN DESCRIPTION:
UCFB HW Trib 04-05 8.6
END DESCRIPTION:
XS GIS Cut Line= 4
      1371335.47      6997187.11      1370265.80      6997030.87
      1370085.52      6997127.02      1369967.48      6997347.35
#Sta/Elev= 30
  3831.9 1994.74  3903.1 1993.99  3934.0 1995.04  4004.2 1992.54  4054.7 1993.43
  4095.1 1990.97  4115.3 1991.15  4182.3 1988.14  4246.7 1985.43  4287.2 1985.07
  4307.4 1983.78  4430.4 1980.03  4459.0 1978.10  4529.7 1976.54  4560.0 1974.94
  4671.2 1972.08  4711.6 1969.98  4752.0 1969.60  4772.2 1968.38  4812.7 1967.92
  4822.8 1967.11  4833.5 1967.43  4956.7 1964.74  5048.2 1964.71  5048.5 1964.21
  5052.2 1964.71  5186.4 1966.27  5311.2 1970.82  5363.4 1974.09  5367.2 1974.35
#Mann=6,-1,0
  3831.9    0.07       0  4182.3   0.035       0  4430.4    0.07       0
  5048.2    0.07       0  5052.2    0.07       0  5363.4   0.035       0
Bank Sta=5048.2,5052.2
Exp/Cntr=0.3,0.1

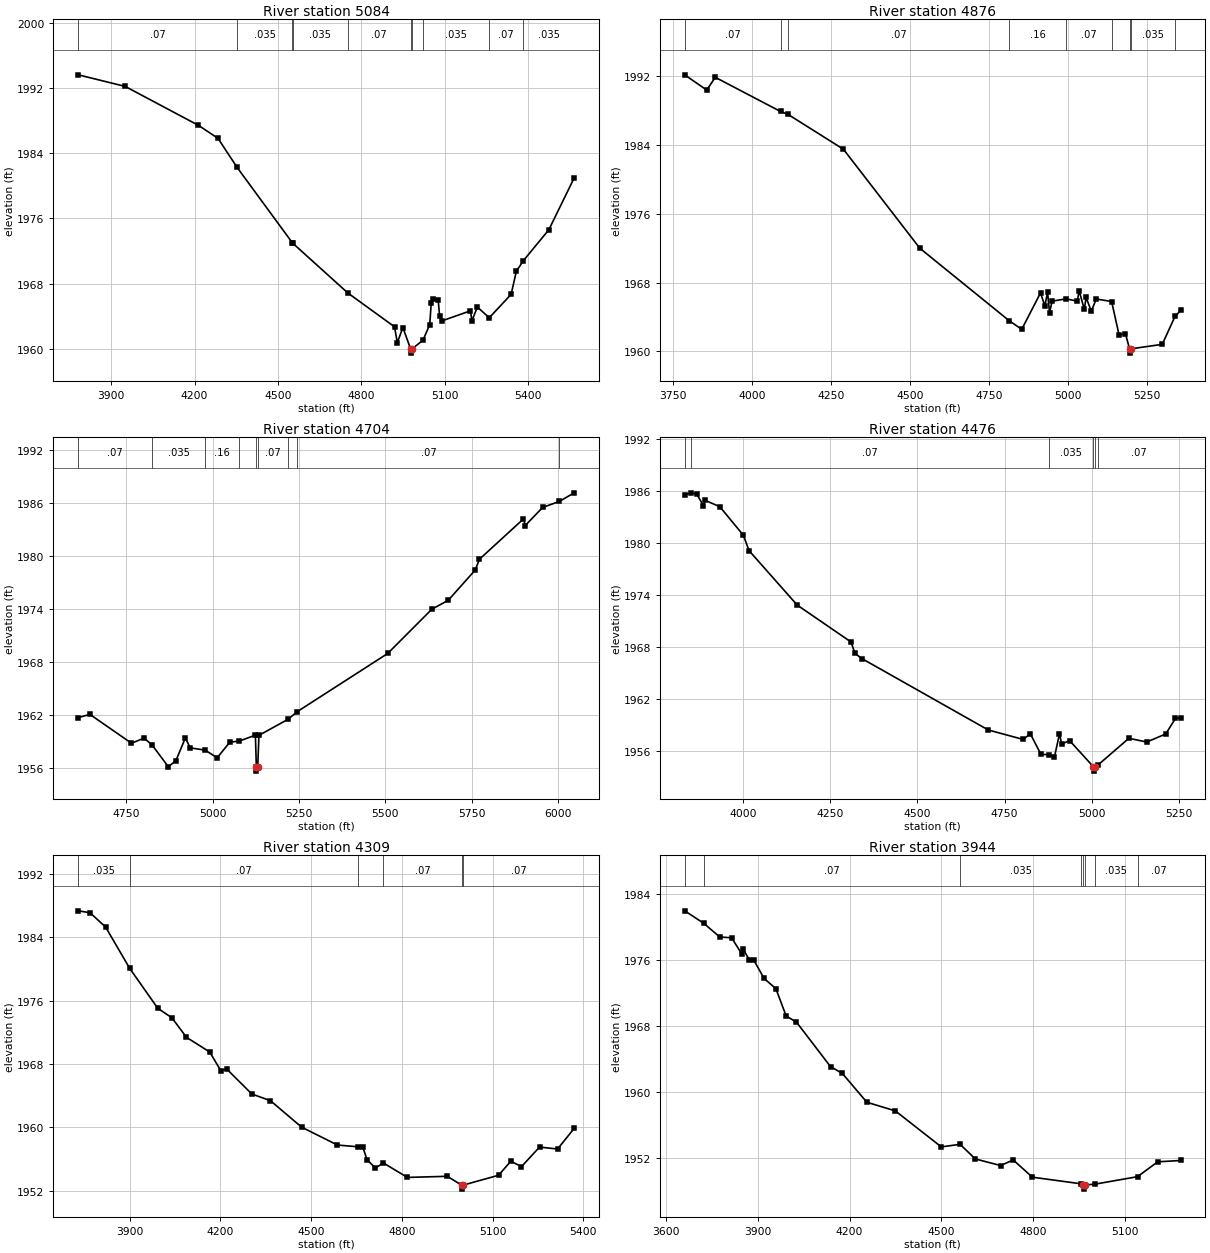
Type RM Length L Ch R = 1,5084,208,208,208
BEGIN DESCRIPTION:
UCFB HW Trib 04-05 8.5
END DESCRIPTION:
XS GIS Cut Line= 4
      1371312.13      6997074.75      1370261.72      6996921.96
      1370062.49      6996921.96      1369880.01      6997412.96
#Sta/Elev= 30
  3781.2 1993.62  3950.1 1992.20  4214.0 1987.42  4284.1 1985.83  4353.0 1982.26
  4551.0 1973.05  4552.3 1972.99  4751.7 1966.85  4919.4 1962.71  4929.4 1960.76
  4949.4 1962.62  4977.4 1959.98  4977.6 1959.48  4981.4 1959.98  5021.8 1961.06
  5046.0 1962.98  5051.4 1965.58  5059.0 1966.15  5076.4 1966.01  5081.7 1963.98
  5091.0 1963.45  5192.5 1964.67  5197.8 1963.46  5217.5 1965.13  5260.3 1963.82
  5338.9 1966.69  5357.7 1969.52  5382.7 1970.81  5474.7 1974.62  5565.7 1980.97
#Mann=10,-1,0
  3781.2    0.07       0  4353.0   0.035       0  4551.0    0.07       0
  4552.3   0.035       0  4751.7    0.07       0  4977.4    0.07       0
  4981.4    0.07       0  5021.8   0.035       0  5260.3    0.07       0
  5382.7   0.035       0
Bank Sta=4977.4,4981.4
Exp/Cntr=0.3,0.1

Type RM Length L Ch R = 1,4876,172,172,172
BEGIN DESCRIPTION:
UCFB HW Trib 04-05 7.6
END DESCRIPTION:
XS GIS Cut Line= 5
      1371239.33      6996958.77      1370153.64      6996701.49
      1370074.98      6996757.98      1370029.51      6996845.59
      1369978.29      6997099.06
#Sta/Elev= 30
  3787.3 1992.15  3857.1 1990.38  3884.2 1991.86  4090.7 1987.89  4113.6 1987.57
  4289.8 1983.50  4531.7 1971.99  4814.8 1963.56  4854.3 1962.57  4913.7 1966.80
  4927.5 1965.28  4936.0 1966.90  4942.2 1964.52  4950.6 1965.84  4995.1 1966.11
  5030.3 1965.84  5035.9 1967.06  5052.4 1964.88  5058.0 1966.28  5074.5 1964.67
  5090.1 1966.09  5138.8 1965.80  5162.3 1961.92  5182.7 1962.04  5195.5 1960.30
  5195.8 1959.80  5199.5 1960.30  5299.0 1960.82  5339.5 1964.07  5357.2 1964.76
#Mann=9,-1,0
  3787.3    0.07       0  4090.7   0.035       0  4113.6    0.07       0
  4814.8    0.16       0  4995.1    0.07       0  5138.8   0.035       0
  5195.5    0.07       0  5199.5   0.035       0  5339.5    0.07       0
Bank Sta=5195.5,5199.5
Exp/Cntr=0.3,0.1

Type RM Length L Ch R = 1,4704,228,228,228
BEGIN DESCRIPTION:
UCFB HW Trib 04-05 8.0
END DESCRIPTION:
XS GIS Cut Line= 5
      1369722.78      6996933.84      1369884.84      6996743.52
      1369975.23      6996637.36      1370030.78      6996568.36
      1370964.04      6996786.07
#Sta/Elev= 30
  4610.6 1961.66  4644.5 1962.02  4764.9 1958.76  4801.2 1959.33  4824.2 1958.58
  4871.5 1956.10  4893.5 1956.78  4920.9 1959.36  4935.1 1958.23  4978.1 1957.98
  5013.0 1957.11  5049.8 1958.88  5076.9 1959.00  5123.7 1959.67  5126.5 1956.10
  5126.8 1955.60  5130.5 1956.10  5134.0 1959.65  5218.5 1961.47  5245.3 1962.34
  5507.0 1968.92  5634.6 1973.92  5682.3 1974.94  5760.4 1978.36  5772.5 1979.58
  5900.2 1984.15  5905.3 1983.40  5955.5 1985.44  6004.2 1986.13  6046.9 1987.10
#Mann=9,-1,0
  4610.6    0.07       0  4824.2   0.035       0  4978.1    0.16       0
  5076.9    0.07       0  5126.5    0.07       0  5130.5    0.07       0
  5218.5    0.16       0  5245.3    0.07       0  6004.2   0.035       0
Bank Sta=5126.5,5130.5
Exp/Cntr=0.3,0.1

Type RM Length L Ch R = 1,4476,167,167,167
BEGIN DESCRIPTION:
UCFB HW Trib 04-05 7.7
END DESCRIPTION:
XS GIS Cut Line= 4
      1370878.72      6996706.37      1369881.21      6996466.00
      1369752.40      6996629.15      1369709.91      6996812.56
#Sta/Elev= 30
  3832.6 1985.60  3850.0 1985.82  3867.3 1985.67  3886.2 1984.34  3891.3 1984.95
  3933.3 1984.22  4001.0 1980.92  4017.1 1979.15  4155.3 1972.86  4309.6 1968.60
  4320.8 1967.29  4340.5 1966.69  4703.2 1958.44  4803.3 1957.35  4823.8 1958.00
  4854.1 1955.64  4877.3 1955.58  4893.0 1955.33  4907.4 1957.99  4913.8 1956.81
  4936.3 1957.22  5004.8 1954.19  5005.0 1953.69  5008.8 1954.19  5016.8 1954.36
  5106.4 1957.48  5157.7 1957.05  5212.1 1957.98  5239.9 1959.77  5254.8 1959.82
#Mann=6,-1,0
  3832.6   0.035       0  3850.0    0.07       0  4877.3   0.035       0
  5004.8   0.035       0  5008.8   0.035       0  5016.8    0.07       0
Bank Sta=5004.8,5008.8
Exp/Cntr=0.3,0.1

Type RM Length L Ch R = 1,4309,365,365,365
BEGIN DESCRIPTION:
UCFB HW Trib 04-05 7.5
END DESCRIPTION:
XS GIS Cut Line= 4
      1370872.87      6996625.94      1369776.38      6996358.89
      1369628.12      6996505.46      1369679.78      6996804.31
#Sta/Elev= 30
  3729.6 1987.35  3768.6 1987.11  3820.0 1985.31  3900.1 1980.07  3992.7 1975.04
  4039.6 1973.83  4087.6 1971.37  4164.7 1969.51  4200.9 1967.17  4221.4 1967.34
  4303.8 1964.21  4365.5 1963.36  4468.5 1960.02  4587.0 1957.76  4654.5 1957.54
  4670.4 1957.56  4684.6 1955.93  4712.2 1954.86  4739.1 1955.49  4818.4 1953.67
  4950.4 1953.81  4997.9 1952.69  4998.2 1952.19  5001.9 1952.69  5119.9 1953.94
  5160.5 1955.72  5195.6 1955.03  5255.4 1957.50  5315.1 1957.26  5369.9 1959.86
#Mann=6,-1,0
  3729.6   0.035       0  3900.1    0.07       0  4654.5   0.035       0
  4739.1    0.07       0  4997.9    0.07       0  5001.9    0.07       0
Bank Sta=4997.9,5001.9
Exp/Cntr=0.3,0.1

Type RM Length L Ch R = 1,3944,523,523,523
BEGIN DESCRIPTION:
UCFB HW Trib 04-05 7.0
END DESCRIPTION:
XS GIS Cut Line= 5
      1370767.49      6996465.59      1369590.68      6996125.65
      1369484.51      6996168.20      1369431.82      6996185.55
      1369430.00      6996412.97
#Sta/Elev= 30
  3660.7 1982.01  3722.7 1980.51  3775.4 1978.84  3814.2 1978.74  3847.8 1976.77
  3853.0 1977.33  3871.5 1976.08  3886.7 1976.04  3920.3 1973.82  3959.1 1972.57
  3992.7 1969.26  4026.4 1968.52  4137.7 1963.13  4176.5 1962.30  4256.6 1958.81
  4349.9 1957.76  4500.0 1953.40  4561.5 1953.71  4611.3 1951.94  4693.8 1951.14
  4735.4 1951.81  4797.9 1949.73  4958.1 1948.92  4965.2 1948.78  4965.4 1948.28
  4969.2 1948.78  5002.2 1948.88  5142.0 1949.79  5207.9 1951.59  5282.9 1951.75
#Mann=8,-1,0
  3660.7   0.035       0  3722.7    0.07       0  4561.5   0.035       0
  4958.1    0.07       0  4965.2    0.07       0  4969.2    0.07       0
  5002.2   0.035       0  5142.0    0.07       0
Bank Sta=4965.2,4969.2
Exp/Cntr=0.3,0.1

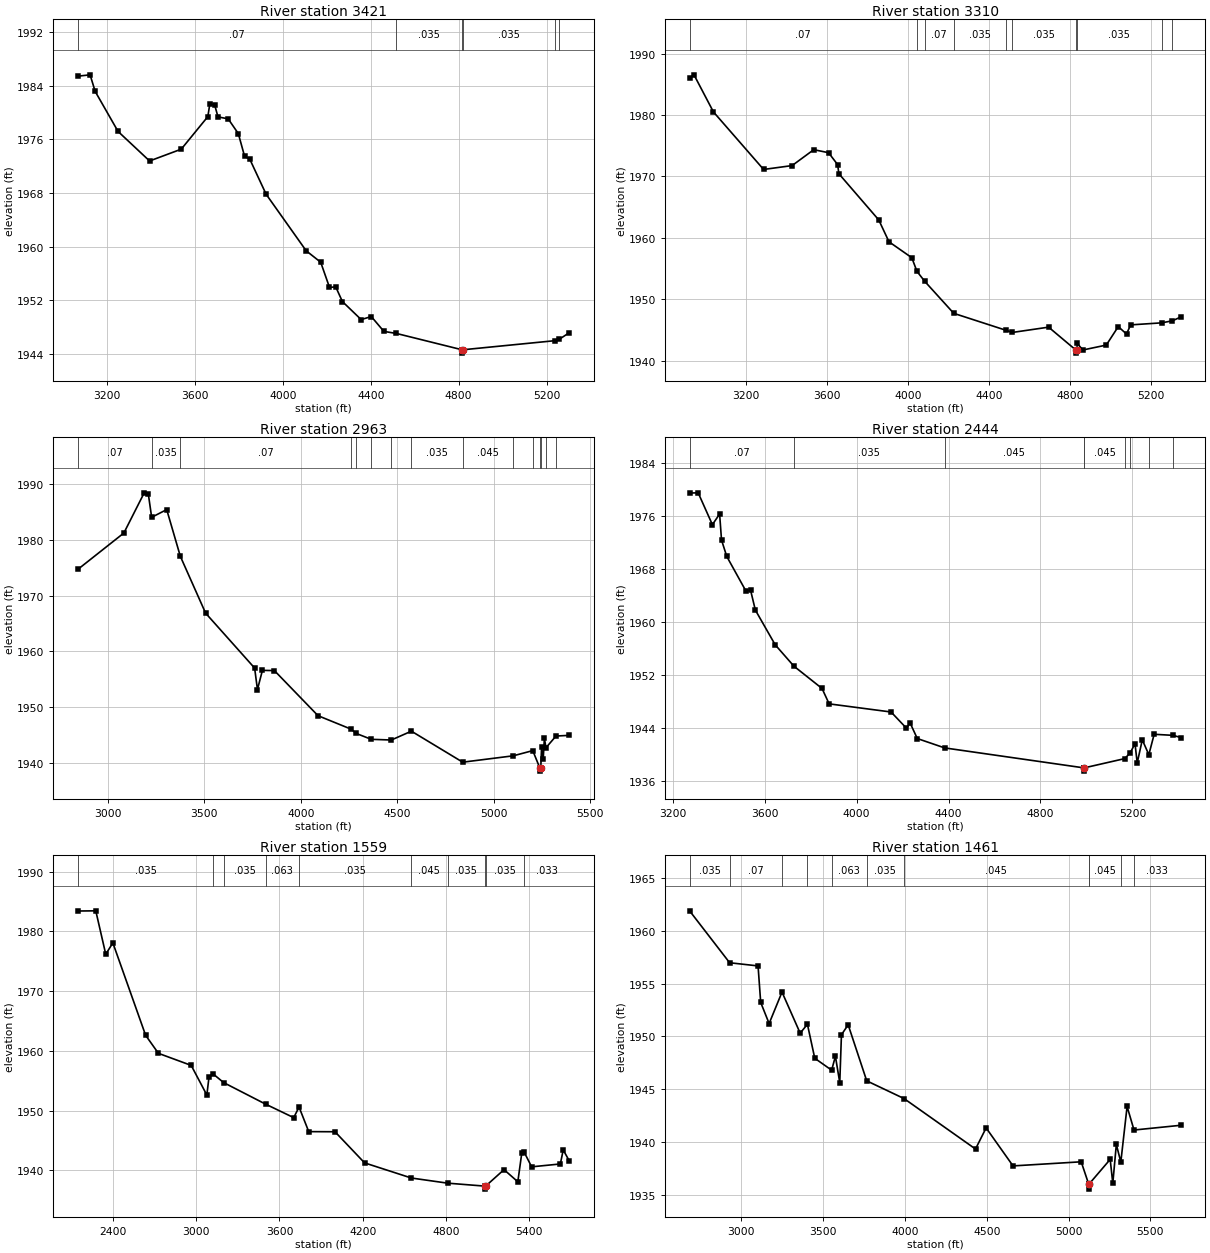
Type RM Length L Ch R = 1,3421,111,111,111
BEGIN DESCRIPTION:
UCFB HW Trib 04-05 6.0
END DESCRIPTION:
XS GIS Cut Line= 4
      1371241.21      6996405.28      1369602.75      6995664.14
      1369404.18      6995734.43      1369385.74      6995960.15
#Sta/Elev= 30
  3068.0 1985.40  3123.1 1985.60  3146.2 1983.13  3250.4 1977.16  3393.8 1972.76
  3537.9 1974.52  3658.9 1979.37  3667.5 1981.19  3689.4 1981.17  3705.1 1979.33
  3751.4 1979.04  3797.6 1976.84  3826.2 1973.44  3849.3 1973.06  3924.1 1967.80
  4106.5 1959.37  4172.4 1957.67  4212.4 1953.92  4240.9 1953.99  4271.1 1951.81
  4356.5 1949.12  4402.7 1949.57  4459.9 1947.36  4517.2 1947.05  4815.5 1944.62
  4815.7 1944.12  4819.5 1944.62  5236.6 1945.97  5258.6 1946.20  5303.4 1947.16
#Mann=6,-1,0
  3068.0    0.07       0  4517.2   0.035       0  4815.5   0.035       0
  4819.5   0.035       0  5236.6    0.07       0  5258.6   0.035       0
Bank Sta=4815.5,4819.5
Exp/Cntr=0.3,0.1

Type RM Length L Ch R = 1,3310,347,347,347
BEGIN DESCRIPTION:
UCFB HW Trib 04-05 6.5
END DESCRIPTION:
XS GIS Cut Line= 4
      1371254.56      6996355.36      1369601.67      6995543.46
      1369402.01      6995606.39      1369339.08      6995972.05
#Sta/Elev= 30
  2923.8 1985.97  2945.6 1986.53  3041.4 1980.49  3288.7 1971.12  3429.2 1971.75
  3536.0 1974.34  3609.0 1973.85  3654.0 1971.89  3659.6 1970.43  3856.4 1962.90
  3906.9 1959.34  4019.3 1956.75  4044.8 1954.52  4083.1 1952.90  4226.1 1947.69
  4481.9 1944.95  4515.4 1944.58  4693.8 1945.44  4828.2 1941.71  4828.4 1941.21
  4832.2 1941.71  4835.4 1942.78  4862.5 1941.72  4978.0 1942.52  5037.2 1945.53
  5077.8 1944.32  5098.1 1945.81  5250.7 1946.14  5303.8 1946.47  5345.7 1947.10
#Mann=10,-1,0
  2923.8    0.07       0  4044.8   0.035       0  4083.1    0.07       0
  4226.1   0.035       0  4481.9    0.07       0  4515.4   0.035       0
  4828.2   0.035       0  4832.2   0.035       0  5250.7    0.07       0
  5303.8   0.035       0
Bank Sta=4828.2,4832.2
Exp/Cntr=0.3,0.1

Type RM Length L Ch R = 1,2963,519,519,519
BEGIN DESCRIPTION:
UCFB HW Trib 04-05 5.0
END DESCRIPTION:
XS GIS Cut Line= 4
      1371528.92      6996060.03      1369491.92      6995346.51
      1369420.49      6995363.31      1369229.99      6995613.01
#Sta/Elev= 30
  2845.0 1974.70  3082.8 1981.19  3188.2 1988.38  3209.4 1988.20  3226.8 1984.00
  3304.8 1985.38  3375.4 1977.02  3506.4 1966.85  3760.4 1957.02  3775.0 1953.18
  3800.7 1956.61  3862.8 1956.57  4088.9 1948.50  4261.1 1946.08  4287.0 1945.32
  4365.0 1944.27  4468.9 1944.15  4572.8 1945.73  4838.8 1940.18  5100.5 1941.32
  5201.7 1942.25  5239.1 1939.08  5239.4 1938.58  5243.1 1939.08  5247.4 1942.84
  5255.7 1940.69  5261.9 1944.43  5270.2 1942.77  5322.2 1944.86  5390.8 1944.98
#Mann=15,-1,0
  2845.0    0.07       0  3226.8   0.035       0  3375.4    0.07       0
  4261.1   0.035       0  4287.0    0.07       0  4365.0   0.035       0
  4468.9    0.07       0  4572.8   0.035       0  4838.8   0.045       0
  5100.5    0.07       0  5201.7   0.045       0  5239.1   0.045       0
  5243.1   0.045       0  5270.2    0.07       0  5322.2   0.035       0
Bank Sta=5239.1,5243.1
Exp/Cntr=0.3,0.1

Type RM Length L Ch R = 1,2444,885,885,885
BEGIN DESCRIPTION:
UCFB HW Trib 04-05 4.0
END DESCRIPTION:
XS GIS Cut Line= 3
      1371341.11      6995370.24      1369674.68      6994917.62
      1369284.78      6995047.29
#Sta/Elev= 30
  3273.2 1979.52  3310.6 1979.55  3372.4 1974.74  3403.9 1976.34  3412.2 1972.42
  3435.0 1969.93  3517.9 1964.73  3538.6 1964.83  3559.3 1961.83  3645.8 1956.57
  3727.2 1953.34  3849.5 1949.97  3880.5 1947.64  4150.0 1946.41  4216.9 1943.96
  4232.9 1944.75  4263.9 1942.40  4383.3 1940.98  4987.3 1937.97  4987.6 1937.47
  4991.3 1937.97  5166.2 1939.36  5189.8 1940.19  5211.4 1941.62  5221.0 1938.71
  5243.1 1942.20  5271.6 1939.96  5294.7 1943.04  5376.9 1942.88  5410.9 1942.55
#Mann=9,-1,0
  3273.2    0.07       0  3727.2   0.035       0  4383.3   0.045       0
  4987.3   0.045       0  4991.3   0.045       0  5166.2   0.035       0
  5189.8   0.045       0  5271.6   0.035       0  5376.9   0.033       0
Bank Sta=4987.3,4991.3
Exp/Cntr=0.3,0.1

Type RM Length L Ch R = 1,1559,98,98,98
BEGIN DESCRIPTION:
UCFB HW Trib 04-05 3.0
END DESCRIPTION:
XS GIS Cut Line= 4
      1372630.03      6994863.01      1370557.99      6994390.08
      1369715.93      6994220.35      1369280.00      6994563.00
#Sta/Elev= 30
  2148.9 1983.41  2277.1 1983.44  2348.9 1976.18  2400.2 1978.08  2636.1 1962.62
  2728.2 1959.60  2964.4 1957.58  3077.2 1952.62  3092.6 1955.63  3121.0 1956.18
  3198.4 1954.70  3501.2 1951.09  3702.9 1948.84  3741.4 1950.61  3811.1 1946.50
  4000.3 1946.48  4213.4 1941.27  4550.1 1938.74  4810.8 1937.88  5081.2 1937.38
  5081.4 1936.88  5085.2 1937.38  5217.8 1940.14  5317.2 1938.11  5346.1 1942.98
  5364.0 1943.02  5416.6 1940.61  5623.5 1941.09  5644.3 1943.44  5687.7 1941.61
#Mann=10,-1,0
  2148.9   0.035       0  3121.0    0.07       0  3198.4   0.035       0
  3501.2   0.063       0  3741.4   0.035       0  4550.1   0.045       0
  4810.8   0.035       0  5081.2   0.035       0  5085.2   0.035       0
  5364.0   0.033       0
Bank Sta=5081.2,5085.2
Exp/Cntr=0.3,0.1

Type RM Length L Ch R = 1,1461,461,461,461
BEGIN DESCRIPTION:
UCFB HW Trib 04-05 2.5
END DESCRIPTION:
XS GIS Cut Line= 3
      1372157.80      6994710.26      1369730.04      6994129.20
      1369288.78      6994378.00
#Sta/Elev= 30
  2683.8 1961.90  2928.7 1956.98  3102.4 1956.68  3118.5 1953.22  3170.0 1951.22
  3248.8 1954.20  3359.8 1950.31  3404.1 1951.15  3449.0 1947.93  3552.2 1946.80
  3575.2 1948.12  3601.8 1945.62  3612.1 1950.16  3653.2 1951.10  3766.6 1945.79
  3994.8 1944.11  4431.5 1939.33  4496.4 1941.33  4660.9 1937.73  5077.6 1938.12
  5122.8 1936.03  5123.1 1935.53  5126.8 1936.03  5254.8 1938.35  5270.7 1936.07
  5292.3 1939.76  5319.8 1938.10  5358.1 1943.36  5400.4 1941.13  5686.7 1941.58
#Mann=11,-1,0
  2683.8   0.035       0  2928.7    0.07       0  3248.8   0.035       0
  3404.1    0.07       0  3552.2   0.063       0  3766.6   0.035       0
  3994.8   0.045       0  5122.8   0.045       0  5126.8   0.045       0
  5319.8   0.035       0  5400.4   0.033       0
Bank Sta=5122.8,5126.8
Exp/Cntr=0.3,0.1

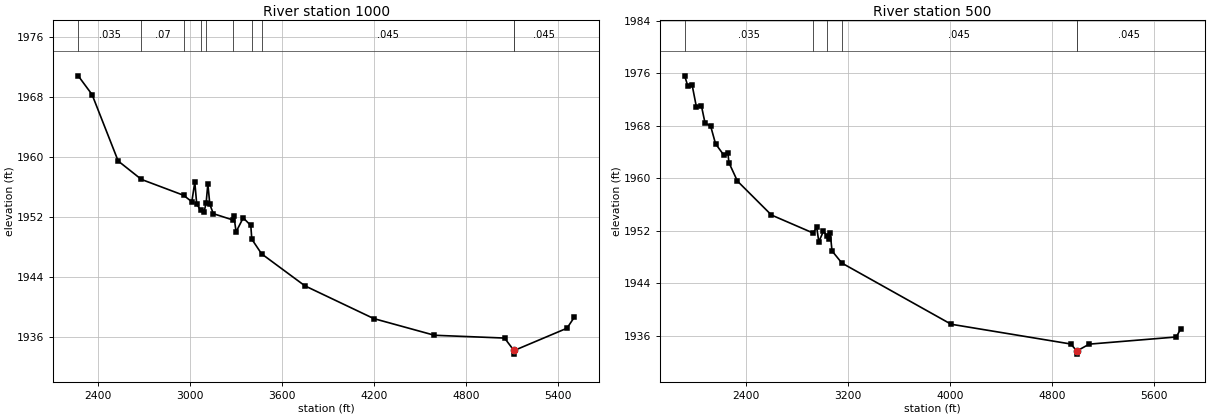
Type RM Length L Ch R = 1,1000,500,500,500
BEGIN DESCRIPTION:
UCFB HW Trib 04-05 2.0
END DESCRIPTION:
XS GIS Cut Line= 4
      1372357.71      6994743.83      1369805.12      6993776.11
      1369684.62      6993794.78      1369580.00      6994163.00
#Sta/Elev= 30
  2270.1 1970.79  2360.5 1968.29  2530.7 1959.45  2682.2 1957.00  2957.0 1954.89
  3011.1 1954.03  3030.5 1956.63  3043.0 1953.73  3067.9 1952.90  3090.8 1952.67
  3104.4 1953.85  3115.6 1956.41  3128.6 1953.68  3151.1 1952.44  3277.5 1951.61
  3285.8 1952.12  3299.7 1950.01  3346.1 1951.88  3395.7 1950.87  3402.3 1949.04
  3466.2 1947.09  3748.8 1942.83  4198.0 1938.47  4593.7 1936.25  5050.7 1935.88
  5111.4 1934.24  5111.6 1933.74  5115.4 1934.24  5457.9 1937.19  5504.7 1938.62
#Mann=10,-1,0
  2270.1   0.035       0  2682.2    0.07       0  2957.0   0.035       0
  3067.9    0.07       0  3104.4   0.035       0  3277.5   0.063       0
  3402.3   0.035       0  3466.2   0.045       0  5111.4   0.045       0
  5115.4   0.045       0
Bank Sta=5111.4,5115.4
Exp/Cntr=0.3,0.1

Type RM Length L Ch R = 1,500,0,0,0
BEGIN DESCRIPTION:
UCFB HW Trib 04-05 1.0
END DESCRIPTION:
XS GIS Cut Line= 5
      1372517.40      6994702.15      1369868.37      6993355.08
      1369755.02      6993350.62      1369700.04      6993346.79
      1369514.03      6994081.28
#Sta/Elev= 30
  1914.7 1975.61  1940.2 1973.99  1973.4 1974.19  2007.1 1970.85  2045.8 1971.09
  2074.5 1968.44  2119.3 1967.92  2157.1 1965.28  2223.8 1963.49  2254.0 1963.93
  2262.7 1962.38  2329.4 1959.58  2596.4 1954.42  2923.8 1951.68  2952.4 1952.53
  2969.1 1950.34  3005.6 1951.96  3033.3 1951.24  3050.5 1950.83  3058.1 1951.75
  3072.9 1948.95  3150.5 1947.10  4009.2 1937.79  4950.0 1934.78  4995.5 1933.74
  4995.8 1933.24  4999.5 1933.74  5094.2 1934.76  5778.5 1935.85  5812.8 1937.06
#Mann=6,-1,0
  1914.7   0.035       0  2923.8   0.063       0  3033.3   0.035       0
  3150.5   0.045       0  4995.5   0.045       0  4999.5   0.045       0
Bank Sta=4995.5,4999.5
Exp/Cntr=0.3,0.1

Chan Stop Cuts=-1