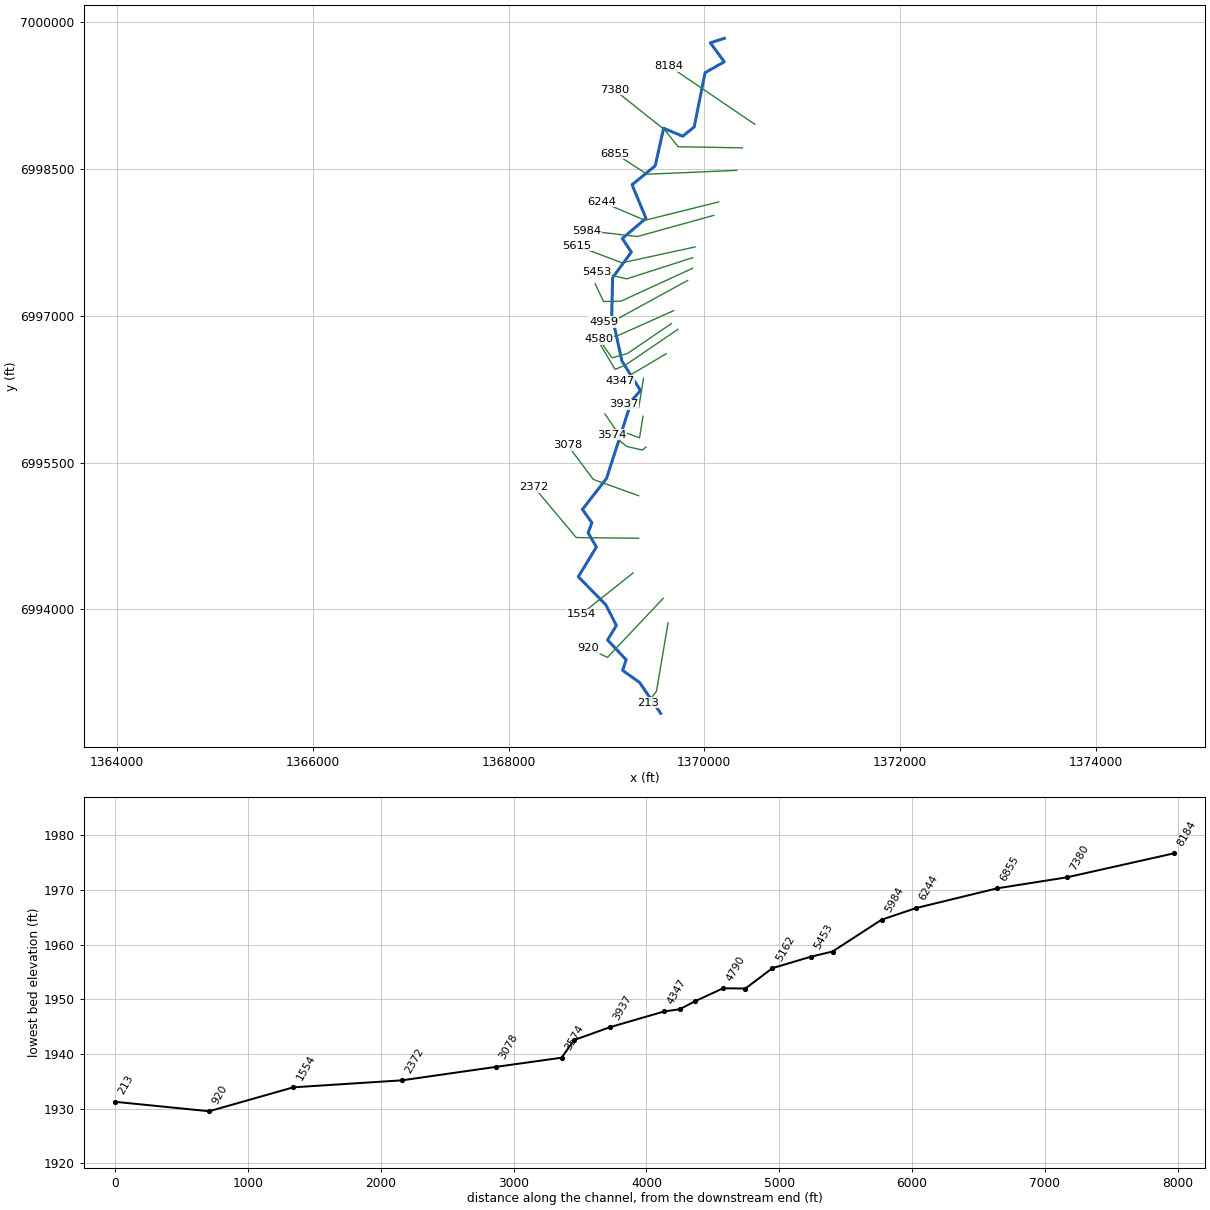
--- UCFB HW Trib 04-05A.prj (project) ---

Proj Title=UCFB HW Trib 04-05A Base Level Engineering
Current Plan=p01
Default Exp/Contr=0.3,0.1
English Units
Geom File=g01
Flow File=f01
Plan File=p01
BEGIN DESCRIPTION:
UCFB HW Trib 04-05A
END DESCRIPTION:

--- UCFB HW Trib 04-05A.p01 (plan) ---

Plan Title=Multiple Run
Short Identifier=Multiple
Geom File=g01
Flow File=f01
Subcritical Flow
K Sum by GR= 0
Std Step Tol= 0.01
Critical Tol= 0.01
Num of Std Step Trials= 20
Max Error Tol= 0.3
Flow Tol Ratio= 0.001
Split Flow NTrial= 30
Split Flow Tol= 0.02
Split Flow Ratio= 0.02
Log Output Level= 0
Friction Slope Method= 1
Unsteady Friction Slope Method= 2
Unsteady Bridges Friction Slope Method= 1
Parabolic Critical Depth
Global Vel Dist=  1 , 1 , 1
Global Log Level= 0
CheckData=True
Encroach Param= -1, 0, 0, 0
BEGIN DESCRIPTION:
Multiple Run
END DESCRIPTION:

--- UCFB HW Trib 04-05A.f01 (steady flow) ---

Flow Title=Multiple
Number of Profiles=7
Profile Names=10-year,25-year,50-year,1pct_min,100-year,1pct_plu,500-year
River Rch & RM= UCFB HW Trib 04-,Reach-1,8184
     185     255     313     191     381     760     573
Boundary for River Rch & Prof#=UCFB HW Trib 04-,Reach-1,1
Up Type=0
Dn Type=3
Dn Slope=0.005
Boundary for River Rch & Prof#=UCFB HW Trib 04-,Reach-1,2
Up Type=0
Dn Type=3
Dn Slope=0.005
Boundary for River Rch & Prof#=UCFB HW Trib 04-,Reach-1,3
Up Type=0
Dn Type=3
Dn Slope=0.005
Boundary for River Rch & Prof#=UCFB HW Trib 04-,Reach-1,4
Up Type=0
Dn Type=3
Dn Slope=0.005
Boundary for River Rch & Prof#=UCFB HW Trib 04-,Reach-1,5
Up Type=0
Dn Type=3
Dn Slope=0.005
Boundary for River Rch & Prof#=UCFB HW Trib 04-,Reach-1,6
Up Type=0
Dn Type=3
Dn Slope=0.005
Boundary for River Rch & Prof#=UCFB HW Trib 04-,Reach-1,7
Up Type=0
Dn Type=3
Dn Slope=0.005

--- UCFB HW Trib 04-05A.g01 (geometry) ---

Geom Title=Existing Conditions

River Reach=UCFB HW Trib 04-,Reach-1
Reach XY= 30
      1370205.00      6999838.00      1370062.43      6999791.61
      1370204.45      6999598.31      1370008.54      6999486.56
      1369897.15      6998931.81      1369780.04      6998837.49
      1369584.51      6998918.99      1369499.48      6998535.56
      1369262.59      6998341.35      1369404.07      6997998.48
      1369162.49      6997791.58      1369255.11      6997653.36
      1369063.24      6997391.23      1369054.80      6997012.92
      1369158.76      6996539.56      1369347.91      6996238.00
      1369258.64      6996136.50      1369001.38      6995339.50
      1368754.89      6995022.64      1368851.83      6994886.35
      1368813.07      6994784.69      1368897.50      6994638.00
      1368712.78      6994334.60      1368994.24      6994047.70
      1369101.69      6993836.26      1369012.08      6993688.00
      1369201.84      6993486.35      1369165.98      6993377.63
      1369338.36      6993254.71      1369555.00      6992938.00

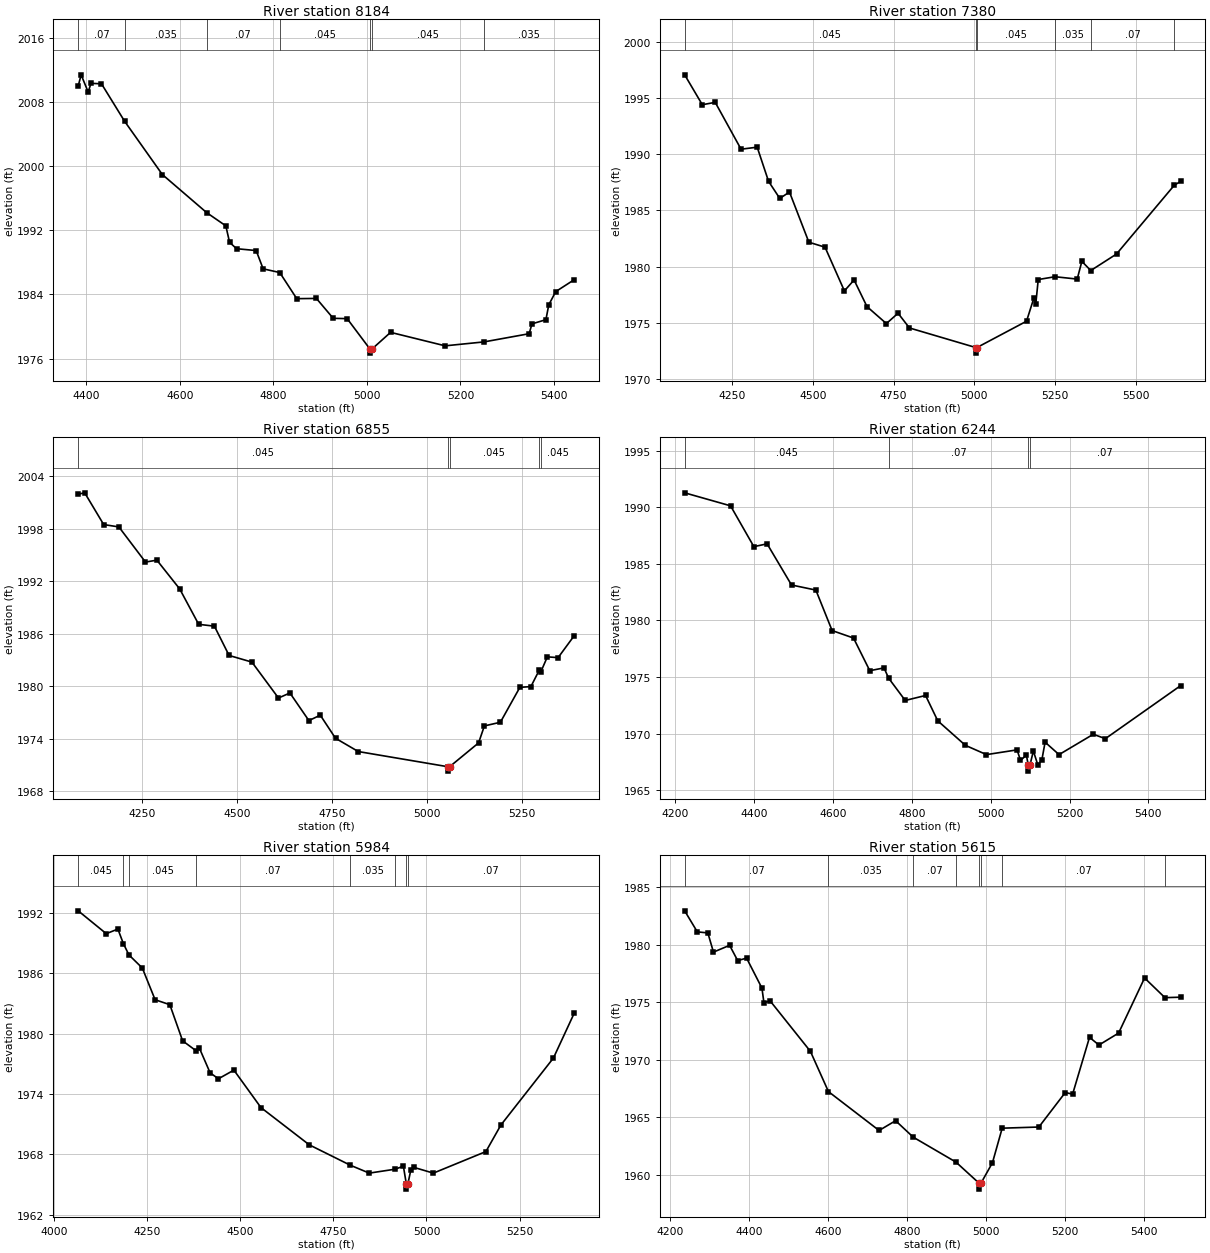
Type RM Length L Ch R = 1,8184,804,804,804
BEGIN DESCRIPTION:
UCFB HW Trib 04-05A 10.0
END DESCRIPTION:
XS GIS Cut Line= 2
      1370516.19      6998960.09      1369638.68      6999555.96
#Sta/Elev= 30
  4382.4 2009.99  4388.7 2011.37  4403.7 2009.22  4409.7 2010.31  4432.2 2010.25
  4481.5 2005.59  4562.3 1998.94  4657.1 1994.19  4698.1 1992.54  4706.1 1990.49
  4721.0 1989.69  4763.0 1989.46  4777.9 1987.18  4813.4 1986.72  4849.8 1983.46
  4891.8 1983.49  4927.8 1981.01  4957.6 1980.97  5006.5 1977.17  5006.7 1976.67
  5010.5 1977.17  5050.5 1979.26  5167.2 1977.58  5250.4 1978.07  5346.8 1979.09
  5352.9 1980.32  5382.7 1980.84  5388.8 1982.69  5403.7 1984.34  5443.1 1985.82
#Mann=7,-1,0
  4382.4    0.07       0  4481.5   0.035       0  4657.1    0.07       0
  4813.4   0.045       0  5006.5   0.045       0  5010.5   0.045       0
  5250.4   0.035       0
Bank Sta=5006.5,5010.5
Exp/Cntr=0.3,0.1

Type RM Length L Ch R = 1,7380,525,525,525
BEGIN DESCRIPTION:
UCFB HW Trib 04-05A 9.0
END DESCRIPTION:
XS GIS Cut Line= 4
      1370389.59      6998718.44      1369733.59      6998729.95
      1369595.49      6998902.57      1369080.00      6999313.00
#Sta/Elev= 30
  4103.2 1997.07  4157.8 1994.41  4197.8 1994.62  4277.8 1990.45  4327.8 1990.63
  4363.0 1987.59  4397.8 1986.07  4427.8 1986.64  4487.9 1982.17  4537.9 1981.73
  4597.9 1977.84  4627.9 1978.81  4667.9 1976.44  4727.9 1974.93  4764.1 1975.85
  4799.4 1974.54  5004.6 1972.80  5004.8 1972.30  5008.6 1972.80  5162.0 1975.14
  5184.4 1977.17  5190.8 1976.71  5198.3 1978.85  5250.3 1979.10  5319.0 1978.89
  5333.4 1980.47  5361.0 1979.65  5440.7 1981.12  5620.2 1987.26  5639.3 1987.58
#Mann=6,-1,0
  4103.2   0.045       0  5004.6   0.045       0  5008.6   0.045       0
  5250.3   0.035       0  5361.0    0.07       0  5620.2   0.063       0
Bank Sta=5004.6,5008.6
Exp/Cntr=0.3,0.1

Type RM Length L Ch R = 1,6855,611,611,611
BEGIN DESCRIPTION:
UCFB HW Trib 04-05A 8.0
END DESCRIPTION:
XS GIS Cut Line= 3
      1370332.05      6998488.27      1369414.70      6998448.77
      1369089.53      6998660.63
#Sta/Elev= 30
  4081.8 2001.97  4098.9 2002.12  4148.9 1998.49  4188.9 1998.22  4259.0 1994.20
  4289.0 1994.42  4349.1 1991.13  4399.1 1987.08  4440.5 1986.87  4479.2 1983.52
  4539.3 1982.76  4609.3 1978.65  4639.4 1979.23  4689.4 1976.07  4719.4 1976.69
  4759.5 1974.05  4819.5 1972.53  5056.0 1970.79  5056.3 1970.29  5060.0 1970.79
  5136.4 1973.52  5151.6 1975.46  5193.8 1975.88  5245.1 1979.87  5274.2 1979.96
  5295.7 1981.80  5300.6 1981.67  5317.5 1983.36  5345.8 1983.27  5388.1 1985.77
#Mann=5,-1,0
  4081.8   0.045       0  5056.0   0.045       0  5060.0   0.045       0
  5295.7    0.07       0  5300.6   0.045       0
Bank Sta=5056,5060
Exp/Cntr=0.3,0.1

Type RM Length L Ch R = 1,6244,260,260,260
BEGIN DESCRIPTION:
UCFB HW Trib 04-05A 7.0
END DESCRIPTION:
XS GIS Cut Line= 3
      1370147.90      6998166.04      1369394.57      6997978.21
      1368951.00      6998166.05
#Sta/Elev= 30
  4223.6 1991.29  4340.0 1990.14  4399.1 1986.53  4432.7 1986.78  4494.6 1983.14
  4556.4 1982.69  4597.6 1979.11  4651.9 1978.45  4693.2 1975.56  4729.3 1975.81
  4741.0 1974.90  4783.1 1972.93  4834.7 1973.37  4865.6 1971.13  4935.7 1968.96
  4989.2 1968.14  5066.8 1968.56  5075.5 1967.63  5090.5 1968.09  5095.3 1967.18
  5095.5 1966.68  5099.3 1967.18  5108.1 1968.46  5119.6 1967.22  5129.8 1967.69
  5137.9 1969.24  5173.3 1968.14  5260.2 1969.94  5290.8 1969.55  5481.7 1974.24
#Mann=4,-1,0
  4223.6   0.045       0  4741.0    0.07       0  5095.3    0.07       0
  5099.3    0.07       0
Bank Sta=5095.3,5099.3
Exp/Cntr=0.3,0.1

Type RM Length L Ch R = 1,5984,369,369,369
BEGIN DESCRIPTION:
UCFB HW Trib 04-05A 6.5
END DESCRIPTION:
XS GIS Cut Line= 3
      1370097.54      6998028.40      1369316.34      6997812.07
      1368799.82      6997872.13
#Sta/Elev= 30
  4065.7 1992.19  4141.0 1989.92  4172.1 1990.38  4186.8 1988.94  4201.8 1987.81
  4237.7 1986.51  4272.0 1983.36  4311.5 1982.87  4345.8 1979.28  4381.6 1978.30
  4390.4 1978.59  4419.6 1976.10  4441.9 1975.51  4483.4 1976.37  4556.0 1972.65
  4685.6 1968.95  4796.0 1966.92  4846.6 1966.14  4916.0 1966.53  4938.1 1966.83
  4946.1 1965.05  4946.4 1964.55  4950.1 1965.05  4958.2 1966.47  4967.1 1966.70
  5018.6 1966.14  5159.5 1968.28  5199.8 1970.92  5340.7 1977.57  5396.3 1982.01
#Mann=8,-1,0
  4065.7   0.045       0  4186.8    0.07       0  4201.8   0.045       0
  4381.6    0.07       0  4796.0   0.035       0  4916.0    0.07       0
  4946.1    0.07       0  4950.1    0.07       0
Bank Sta=4946.1,4950.1
Exp/Cntr=0.3,0.1

Type RM Length L Ch R = 1,5615,162,162,162
BEGIN DESCRIPTION:
UCFB HW Trib 04-05A 6.0
END DESCRIPTION:
XS GIS Cut Line= 3
      1369906.22      6997705.71      1369160.09      6997543.33
      1368698.94      6997716.81
#Sta/Elev= 30
  4236.4 1982.94  4268.4 1981.11  4295.1 1981.02  4309.3 1979.35  4350.2 1979.94
  4370.7 1978.61  4393.2 1978.83  4432.1 1976.22  4437.2 1974.94  4452.6 1975.12
  4554.9 1970.72  4600.6 1967.22  4728.9 1963.84  4770.7 1964.69  4815.3 1963.26
  4923.6 1961.09  4982.7 1959.24  4983.0 1958.74  4986.7 1959.24  5016.1 1961.04
  5040.7 1964.04  5133.6 1964.14  5200.5 1967.14  5219.1 1967.00  5261.9 1971.94
  5285.8 1971.27  5335.6 1972.31  5401.4 1977.10  5453.0 1975.39  5492.7 1975.43
#Mann=8,-1,0
  4236.4    0.07       0  4600.6   0.035       0  4815.3    0.07       0
  4923.6   0.035       0  4982.7   0.035       0  4986.7   0.035       0
  5040.7    0.07       0  5453.0   0.035       0
Bank Sta=4982.7,4986.7
Exp/Cntr=0.3,0.1

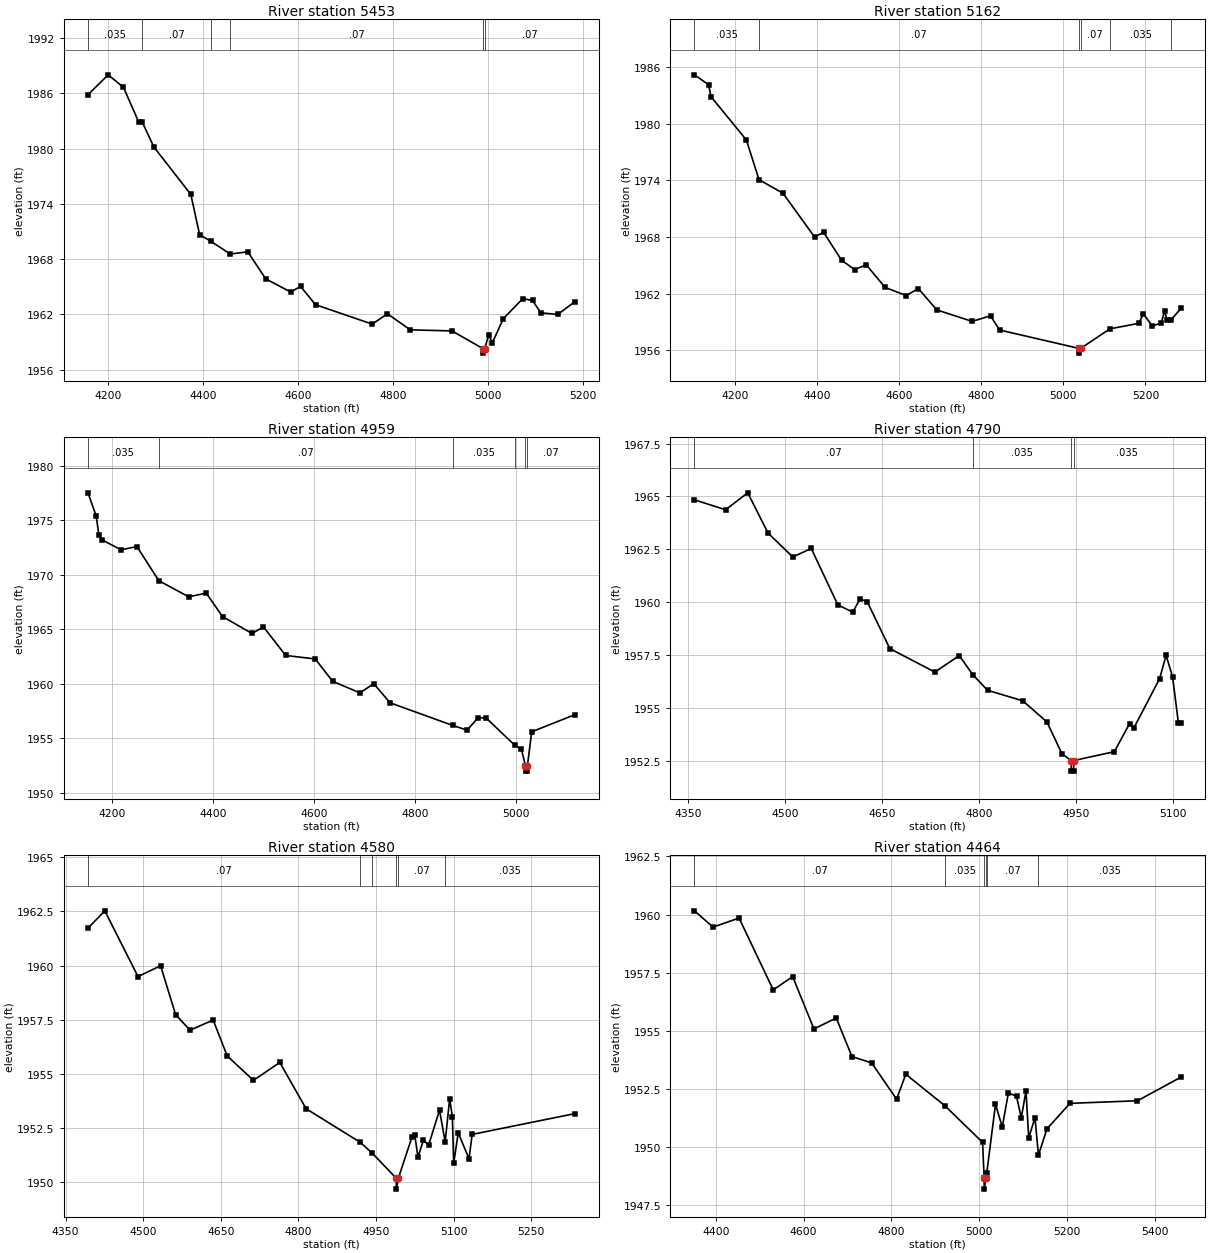
Type RM Length L Ch R = 1,5453,291,291,291
BEGIN DESCRIPTION:
UCFB HW Trib 04-05A 5.9
END DESCRIPTION:
XS GIS Cut Line= 4
      1369881.25      6997595.75      1369208.17      6997379.40
      1368965.47      6997436.21      1368898.63      6997451.85
#Sta/Elev= 30
  4158.2 1985.86  4200.7 1988.02  4232.8 1986.67  4264.9 1982.91  4272.4 1982.89
  4297.0 1980.18  4374.8 1975.03  4393.3 1970.66  4416.3 1969.97  4457.8 1968.56
  4494.8 1968.80  4532.4 1965.87  4584.9 1964.44  4605.9 1965.04  4637.4 1963.06
  4756.8 1960.95  4788.9 1962.07  4837.0 1960.33  4924.9 1960.21  4989.7 1958.30
  4989.9 1957.80  4993.7 1958.30  5002.0 1959.75  5009.9 1958.93  5032.8 1961.53
  5073.9 1963.72  5094.4 1963.52  5112.1 1962.17  5147.6 1962.00  5183.1 1963.37
#Mann=6,-1,0
  4158.2   0.035       0  4272.4    0.07       0  4416.3   0.035       0
  4457.8    0.07       0  4989.7    0.07       0  4993.7    0.07       0
Bank Sta=4989.7,4993.7
Exp/Cntr=0.3,0.1

Type RM Length L Ch R = 1,5162,203,203,203
BEGIN DESCRIPTION:
UCFB HW Trib 04-05A 5.8
END DESCRIPTION:
XS GIS Cut Line= 4
      1369881.21      6997487.57      1369148.08      6997151.05
      1368970.70      6997148.10      1368883.88      6997331.29
#Sta/Elev= 30
  4100.2 1985.17  4134.8 1984.12  4140.3 1982.87  4226.8 1978.27  4257.6 1974.07
  4316.1 1972.63  4393.1 1968.00  4415.1 1968.49  4459.1 1965.53  4490.7 1964.55
  4519.2 1965.05  4565.1 1962.66  4616.6 1961.80  4646.2 1962.54  4691.1 1960.28
  4777.5 1959.06  4822.2 1959.65  4844.2 1958.15  5038.0 1956.20  5038.2 1955.70
  5042.0 1956.20  5113.5 1958.27  5184.3 1958.86  5194.8 1959.88  5217.0 1958.55
  5239.1 1958.93  5247.0 1960.21  5252.5 1959.18  5262.9 1959.26  5287.0 1960.43
#Mann=6,-1,0
  4100.2   0.035       0  4257.6    0.07       0  5038.0    0.07       0
  5042.0    0.07       0  5113.5   0.035       0  5262.9    0.07       0
Bank Sta=5038,5042
Exp/Cntr=0.3,0.1

Type RM Length L Ch R = 1,4959,169,169,169
BEGIN DESCRIPTION:
UCFB HW Trib 04-05A 5.0
END DESCRIPTION:
XS GIS Cut Line= 3
      1369829.99      6997362.99      1369089.13      6996957.67
      1368971.09      6996938.32
#Sta/Elev= 30
  4152.0 1977.51  4168.1 1975.40  4173.8 1973.60  4180.5 1973.18  4217.4 1972.28
  4248.9 1972.58  4292.3 1969.45  4351.5 1967.97  4386.3 1968.31  4418.5 1966.16
  4476.9 1964.61  4499.6 1965.21  4543.7 1962.59  4602.2 1962.27  4636.7 1960.22
  4690.7 1959.16  4718.2 1960.00  4750.4 1958.25  4874.6 1956.17  4903.2 1955.74
  4925.0 1956.89  4941.1 1956.84  4997.4 1954.36  5010.8 1953.97  5018.6 1952.48
  5018.9 1951.98  5022.4 1951.98  5022.6 1952.48  5031.1 1955.59  5116.1 1957.15
#Mann=6,-1,0
  4152.0   0.035       0  4292.3    0.07       0  4874.6   0.035       0
  4997.4    0.07       0  5018.6    0.07       0  5022.6    0.07       0
Bank Sta=5018.6,5022.6
Exp/Cntr=0.3,0.1

Type RM Length L Ch R = 1,4790,210,210,210
BEGIN DESCRIPTION:
UCFB HW Trib 04-05A 4.9
END DESCRIPTION:
XS GIS Cut Line= 3
      1369688.95      6997054.92      1369104.68      6996793.97
      1368991.83      6996790.50
#Sta/Elev= 30
  4360.1 1964.84  4408.2 1964.37  4442.5 1965.17  4473.9 1963.27  4512.1 1962.14
  4540.8 1962.54  4581.8 1959.88  4605.0 1959.53  4616.3 1960.16  4627.3 1960.03
  4662.3 1957.81  4732.0 1956.70  4769.7 1957.48  4790.6 1956.58  4813.5 1955.84
  4868.2 1955.34  4905.4 1954.34  4928.6 1952.84  4942.9 1952.52  4943.1 1952.02
  4946.6 1952.02  4946.9 1952.52  5009.7 1952.94  5033.1 1954.26  5039.7 1954.05
  5079.7 1956.39  5089.7 1957.49  5099.7 1956.48  5108.8 1954.28  5112.9 1954.28
#Mann=4,-1,0
  4360.1    0.07       0  4790.6   0.035       0  4942.9   0.035       0
  4946.9   0.035       0
Bank Sta=4942.9,4946.9
Exp/Cntr=0.3,0.1

Type RM Length L Ch R = 1,4580,116,116,116
BEGIN DESCRIPTION:
UCFB HW Trib 04-05A 4.8
END DESCRIPTION:
XS GIS Cut Line= 4
      1369664.88      6996922.71      1369216.82      6996617.36
      1369057.15      6996571.54      1368924.26      6996761.93
#Sta/Elev= 30
  4393.3 1961.73  4425.8 1962.53  4490.0 1959.49  4533.6 1959.99  4562.6 1957.73
  4590.5 1957.01  4635.2 1957.48  4662.3 1955.82  4713.1 1954.69  4764.0 1955.52
  4814.8 1953.38  4919.1 1951.83  4942.5 1951.33  4989.1 1950.16  4989.3 1949.66
  4993.1 1950.16  5019.6 1952.08  5024.8 1952.17  5031.0 1951.14  5041.4 1951.91
  5051.8 1951.71  5072.7 1953.31  5083.6 1951.84  5092.3 1953.84  5097.5 1953.01
  5100.1 1950.85  5108.8 1952.26  5129.7 1951.07  5135.8 1952.19  5333.8 1953.15
#Mann=6,-1,0
  4393.3    0.07       0  4919.1   0.035       0  4942.5    0.07       0
  4989.1    0.07       0  4993.1    0.07       0  5083.6   0.035       0
Bank Sta=4989.1,4993.1
Exp/Cntr=0.3,0.1

Type RM Length L Ch R = 1,4464,117,117,117
BEGIN DESCRIPTION:
UCFB HW Trib 04-05A 4.0
END DESCRIPTION:
XS GIS Cut Line= 4
      1369730.03      6996863.02      1369193.86      6996497.53
      1369088.32      6996454.17      1368911.33      6996751.94
#Sta/Elev= 30
  4351.1 1960.16  4393.5 1959.46  4452.8 1959.85  4530.7 1956.76  4575.0 1957.33
  4623.5 1955.08  4674.3 1955.55  4710.2 1953.89  4755.0 1953.62  4811.9 1952.06
  4832.9 1953.13  4922.4 1951.77  5008.0 1950.20  5011.4 1948.69  5011.7 1948.19
  5015.4 1948.69  5017.6 1948.90  5037.4 1951.84  5052.8 1950.86  5066.8 1952.33
  5085.3 1952.18  5096.2 1951.26  5106.9 1952.41  5113.2 1950.39  5127.4 1951.27
  5135.3 1949.65  5154.6 1950.78  5207.2 1951.88  5361.1 1951.99  5460.5 1953.01
#Mann=6,-1,0
  4351.1    0.07       0  4922.4   0.035       0  5011.4   0.035       0
  5015.4   0.035       0  5017.6    0.07       0  5135.3   0.035       0
Bank Sta=5011.4,5015.4
Exp/Cntr=0.3,0.1

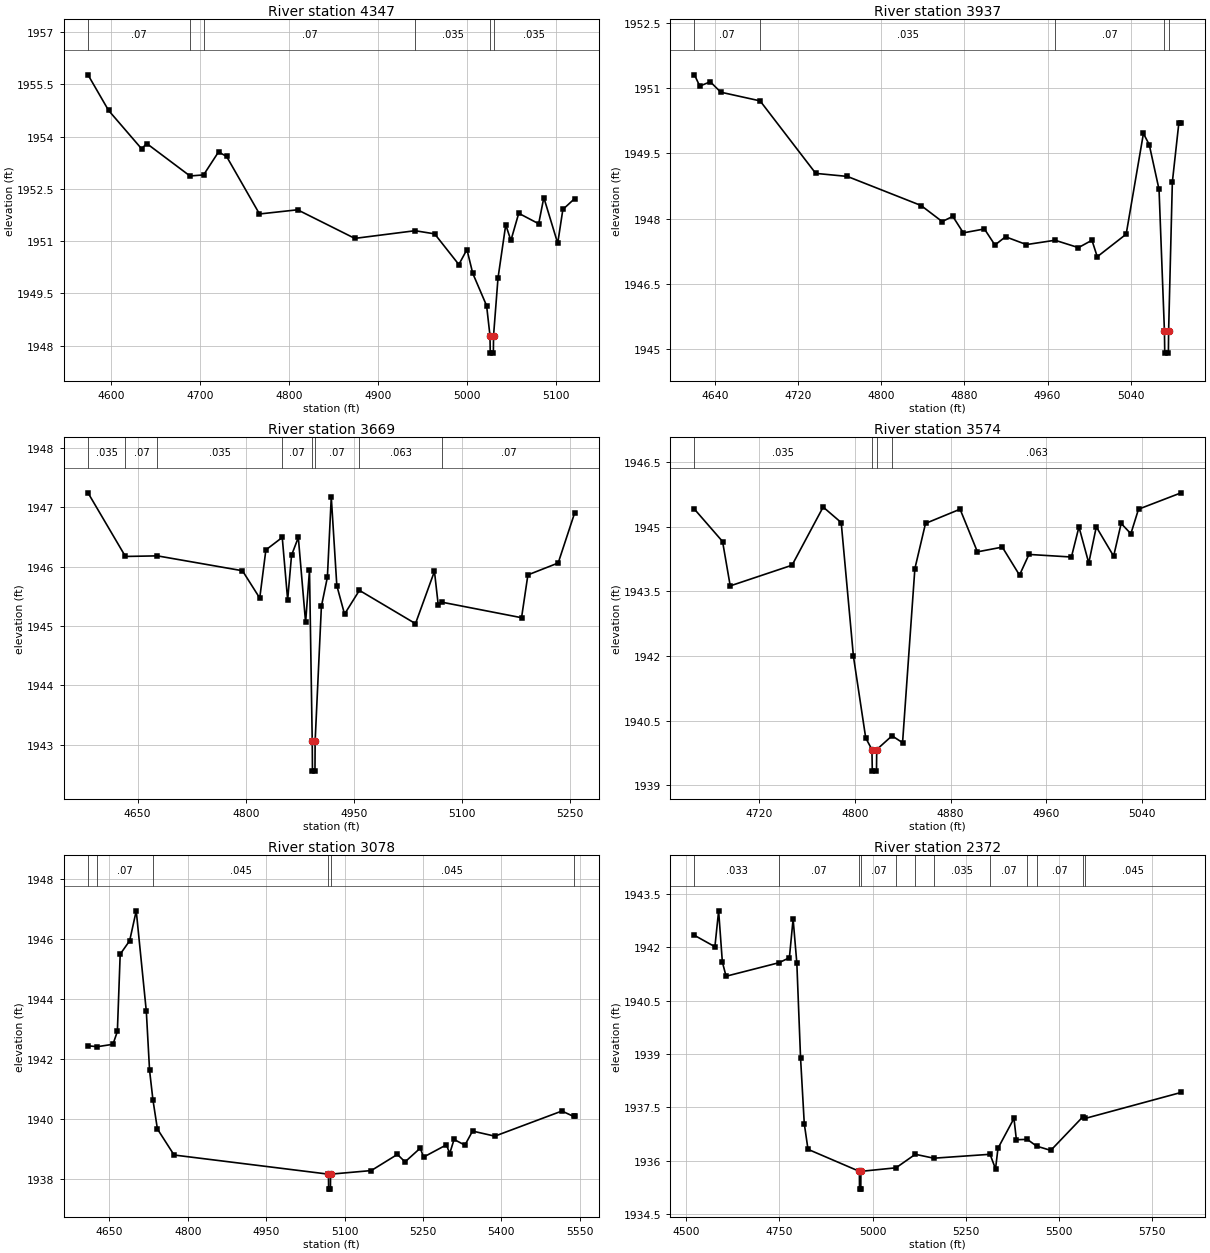
Type RM Length L Ch R = 1,4347,410,410,410
BEGIN DESCRIPTION:
UCFB HW Trib 04-05A 3.9
END DESCRIPTION:
XS GIS Cut Line= 2
      1369611.15      6996614.08      1369141.00      6996334.89
#Sta/Elev= 30
  4573.8 1955.77  4596.9 1954.75  4634.0 1953.65  4639.8 1953.80  4688.4 1952.87
  4703.7 1952.90  4720.5 1953.56  4729.5 1953.43  4766.5 1951.78  4809.3 1951.90
  4873.6 1951.08  4941.3 1951.30  4963.3 1951.21  4990.5 1950.33  4999.6 1950.76
  5006.1 1950.08  5021.7 1949.15  5025.5 1948.29  5025.8 1947.79  5029.3 1947.79
  5029.5 1948.29  5034.5 1949.94  5043.2 1951.47  5049.0 1951.02  5057.8 1951.80
  5080.2 1951.50  5086.0 1952.25  5101.6 1950.94  5107.4 1951.91  5120.6 1952.22
#Mann=6,-1,0
  4573.8    0.07       0  4688.4   0.035       0  4703.7    0.07       0
  4941.3   0.035       0  5025.5   0.035       0  5029.5   0.035       0
Bank Sta=5025.5,5029.5
Exp/Cntr=0.3,0.1

Type RM Length L Ch R = 1,3937,268,268,268
BEGIN DESCRIPTION:
UCFB HW Trib 04-05A 3.0
END DESCRIPTION:
XS GIS Cut Line= 4
      1369380.00      6996362.98      1369330.00      6996063.00
      1369254.63      6996058.35      1369176.10      6996098.65
#Sta/Elev= 30
  4620.5 1951.31  4625.6 1951.05  4635.7 1951.15  4645.8 1950.91  4683.6 1950.71
  4737.1 1949.04  4767.5 1948.97  4838.4 1948.30  4858.7 1947.93  4868.9 1948.05
  4879.0 1947.67  4899.3 1947.76  4909.4 1947.39  4919.6 1947.58  4939.7 1947.40
  4967.2 1947.50  4989.7 1947.33  5002.7 1947.50  5007.8 1947.12  5035.6 1947.64
  5052.2 1949.96  5057.8 1949.70  5067.2 1948.67  5072.4 1945.40  5072.7 1944.90
  5076.2 1944.90  5076.4 1945.40  5080.0 1948.84  5086.2 1950.19  5088.4 1950.19
#Mann=5,-1,0
  4620.5    0.07       0  4683.6   0.035       0  4967.2    0.07       0
  5072.4    0.07       0  5076.4   0.035       0
Bank Sta=5072.4,5076.4
Exp/Cntr=0.3,0.1

Type RM Length L Ch R = 1,3669,95,95,95
BEGIN DESCRIPTION:
UCFB HW Trib 04-05A 2.0
END DESCRIPTION:
XS GIS Cut Line= 5
      1369374.37      6995974.96      1369338.32      6995753.87
      1369155.95      6995822.61      1369090.06      6995844.69
      1368985.07      6995998.84
#Sta/Elev= 30
  4581.1 1947.24  4633.0 1946.17  4677.3 1946.18  4795.3 1945.93  4819.3 1945.47
  4827.8 1946.28  4850.5 1946.49  4858.0 1945.44  4863.4 1946.19  4872.8 1946.49
  4882.9 1945.06  4888.3 1945.94  4892.1 1943.06  4892.4 1942.56  4895.9 1942.56
  4896.1 1943.06  4904.8 1945.33  4913.1 1945.82  4918.5 1947.17  4926.2 1945.68
  4936.9 1945.20  4957.5 1945.60  5035.3 1945.04  5061.6 1945.92  5066.8 1945.36
  5072.3 1945.40  5182.4 1945.14  5191.2 1945.86  5233.2 1946.06  5256.0 1946.90
#Mann=8,-1,0
  4581.1   0.035       0  4633.0    0.07       0  4677.3   0.035       0
  4850.5    0.07       0  4892.1   0.063       0  4896.1    0.07       0
  4957.5   0.063       0  5072.3    0.07       0
Bank Sta=4892.1,4896.1
Exp/Cntr=0.3,0.1

Type RM Length L Ch R = 1,3574,496,496,496
BEGIN DESCRIPTION:
UCFB HW Trib 04-05A 1.0
END DESCRIPTION:
XS GIS Cut Line= 4
      1369405.18      6995660.14      1369366.96      6995629.74
      1369209.67      6995665.96      1369054.89      6995787.28
#Sta/Elev= 30
  4665.8 1945.41  4689.3 1944.66  4695.7 1943.63  4747.4 1944.11  4773.4 1945.46
  4788.5 1945.10  4798.7 1942.00  4809.0 1940.10  4814.2 1939.83  4814.5 1939.33
  4818.0 1939.33  4818.2 1939.83  4831.0 1940.15  4839.8 1939.99  4850.1 1944.03
  4859.0 1945.08  4887.9 1945.41  4902.4 1944.42  4923.2 1944.53  4937.6 1943.88
  4945.5 1944.36  4981.0 1944.30  4987.3 1945.00  4995.5 1944.16  5001.8 1945.00
  5016.3 1944.32  5022.6 1945.08  5030.7 1944.84  5037.1 1945.41  5072.7 1945.79
#Mann=4,-1,0
  4665.8   0.035       0  4814.2   0.063       0  4818.2   0.035       0
  4831.0   0.063       0
Bank Sta=4814.2,4818.2
Exp/Cntr=0.3,0.1

Type RM Length L Ch R = 1,3078,706,706,706
BEGIN DESCRIPTION:
UCFB HW Trib 04-05A 0.9
END DESCRIPTION:
XS GIS Cut Line= 3
      1369330.04      6995162.99      1368866.13      6995329.18
      1368603.86      6995680.37
#Sta/Elev= 30
  4609.1 1942.44  4627.0 1942.41  4656.9 1942.49  4665.3 1942.92  4670.7 1945.50
  4688.8 1945.95  4701.4 1946.95  4720.7 1943.59  4726.9 1941.62  4733.3 1940.64
  4741.9 1939.66  4773.8 1938.79  5069.2 1938.15  5069.5 1937.65  5073.0 1937.65
  5073.2 1938.15  5151.1 1938.27  5201.1 1938.81  5215.7 1938.56  5244.9 1939.02
  5251.1 1938.72  5294.9 1939.13  5301.2 1938.84  5309.5 1939.31  5330.3 1939.12
  5344.9 1939.59  5387.5 1939.42  5515.9 1940.26  5538.1 1940.08  5540.2 1940.08
#Mann=6,-1,0
  4609.1   0.035       0  4627.0    0.07       0  4733.3   0.045       0
  5069.2   0.045       0  5073.2   0.045       0  5538.1    0.07       0
Bank Sta=5069.2,5073.2
Exp/Cntr=0.3,0.1

Type RM Length L Ch R = 1,2372,818,818,818
BEGIN DESCRIPTION:
UCFB HW Trib 04-05A 0.8
END DESCRIPTION:
XS GIS Cut Line= 3
      1369329.88      6994727.77      1368692.23      6994735.01
      1368262.18      6995247.62
#Sta/Elev= 30
  4521.8 1942.34  4576.7 1942.02  4586.7 1943.03  4596.7 1941.59  4606.7 1941.19
  4748.7 1941.57  4776.7 1941.71  4786.7 1942.80  4796.7 1941.56  4806.7 1938.89
  4816.7 1937.04  4826.7 1936.32  4964.7 1935.70  4965.0 1935.20  4968.5 1935.20
  4968.7 1935.70  5063.1 1935.80  5114.9 1936.18  5164.4 1936.07  5315.6 1936.18
  5330.3 1935.77  5336.9 1936.35  5379.8 1937.19  5386.3 1936.59  5415.6 1936.60
  5440.5 1936.41  5478.7 1936.29  5565.3 1937.24  5571.3 1937.19  5828.6 1937.92
#Mann=12,-1,0
  4521.8   0.033       0  4748.7    0.07       0  4964.7    0.07       0
  4968.7    0.07       0  5063.1   0.035       0  5114.9    0.07       0
  5164.4   0.035       0  5315.6    0.07       0  5415.6   0.045       0
  5440.5    0.07       0  5565.3   0.035       0  5571.3   0.045       0
Bank Sta=4964.7,4968.7
Exp/Cntr=0.3,0.1

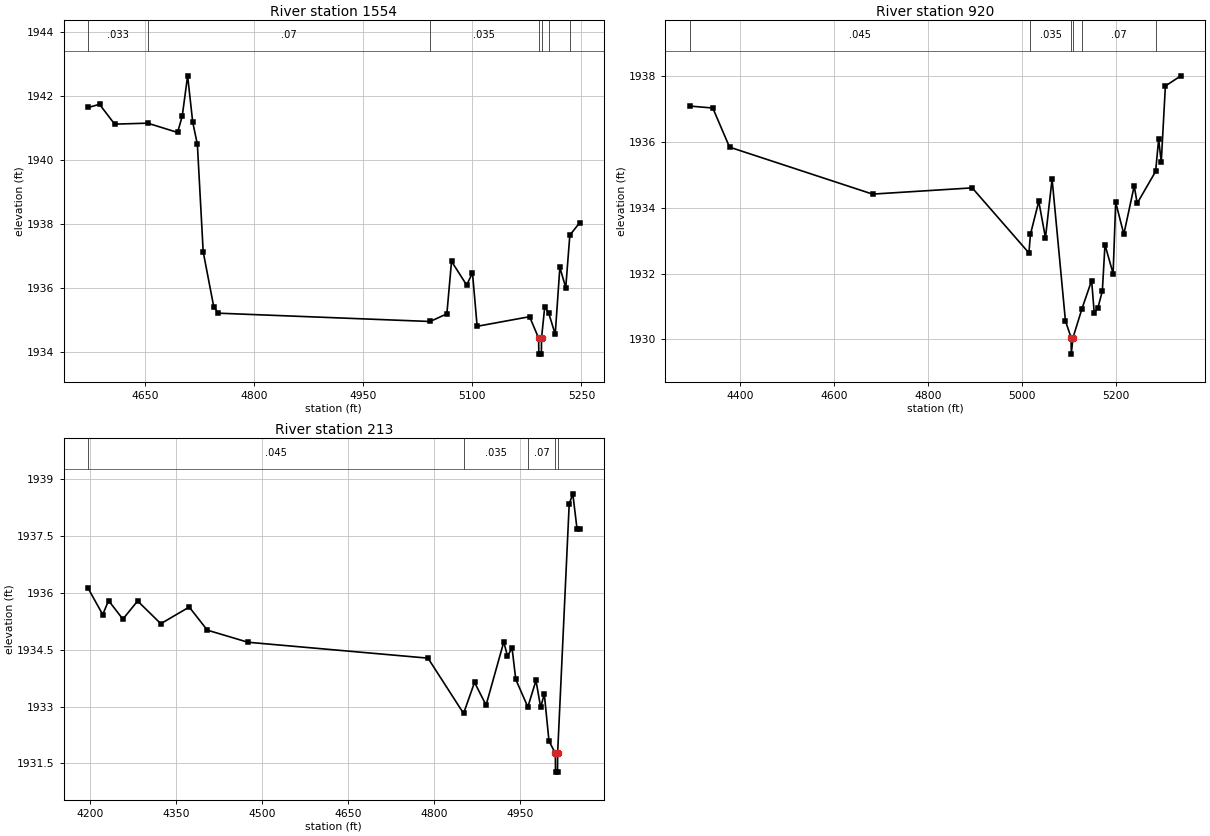
Type RM Length L Ch R = 1,1554,634,634,634
BEGIN DESCRIPTION:
UCFB HW Trib 04-05A 0.7
END DESCRIPTION:
XS GIS Cut Line= 2
      1369271.93      6994372.74      1368743.28      6993952.72
#Sta/Elev= 30
  4572.2 1941.63  4587.7 1941.73  4608.5 1941.11  4653.9 1941.14  4695.0 1940.85
  4701.4 1941.36  4708.8 1942.62  4715.8 1941.17  4722.2 1940.48  4730.2 1937.12
  4744.7 1935.40  4751.0 1935.20  5042.1 1934.94  5065.1 1935.18  5071.5 1936.82
  5092.3 1936.08  5100.3 1936.46  5106.7 1934.79  5178.8 1935.09  5191.2 1934.42
  5191.5 1933.92  5195.0 1933.92  5195.2 1934.42  5199.6 1935.40  5205.1 1935.20
  5214.0 1934.54  5220.4 1936.63  5228.5 1936.00  5234.1 1937.64  5247.4 1938.02
#Mann=7,-1,0
  4572.2   0.033       0  4653.9    0.07       0  5042.1   0.035       0
  5191.2    0.07       0  5195.2   0.035       0  5205.1    0.07       0
  5234.1   0.063       0
Bank Sta=5191.2,5195.2
Exp/Cntr=0.3,0.1

Type RM Length L Ch R = 1,920,707,707,707
BEGIN DESCRIPTION:
UCFB HW Trib 04-05A 0.6
END DESCRIPTION:
XS GIS Cut Line= 3
      1369580.03      6994113.03      1369011.05      6993510.45
      1368815.15      6993602.01
#Sta/Elev= 30
  4292.5 1937.10  4341.9 1937.04  4377.5 1935.85  4681.7 1934.42  4893.7 1934.61
  5014.3 1932.63  5017.6 1933.20  5035.3 1934.20  5049.5 1933.09  5063.6 1934.88
  5092.0 1930.56  5104.1 1930.05  5104.4 1929.55  5108.1 1930.05  5127.1 1930.93
  5147.7 1931.79  5153.2 1930.81  5161.1 1930.96  5170.5 1931.47  5176.1 1932.88
  5193.4 1932.00  5198.9 1934.17  5216.2 1933.20  5238.3 1934.67  5244.6 1934.14
  5283.8 1935.11  5290.3 1936.09  5295.8 1935.39  5304.6 1937.71  5337.5 1938.02
#Mann=6,-1,0
  4292.5   0.045       0  5017.6   0.035       0  5104.1   0.045       0
  5108.1   0.035       0  5127.1    0.07       0  5283.8   0.035       0
Bank Sta=5104.1,5108.1
Exp/Cntr=0.3,0.1

Type RM Length L Ch R = 1,213,0,0,0
BEGIN DESCRIPTION:
UCFB HW Trib 04-05A 0.5
END DESCRIPTION:
XS GIS Cut Line= 3
      1369629.99      6993862.97      1369512.20      6993164.64
      1369421.02      6993046.16
#Sta/Elev= 30
  4196.6 1936.12  4221.9 1935.43  4232.1 1935.80  4257.1 1935.31  4282.8 1935.79
  4323.3 1935.19  4372.9 1935.63  4404.5 1935.02  4475.5 1934.70  4789.8 1934.28
  4851.9 1932.82  4871.0 1933.64  4891.2 1933.04  4922.1 1934.71  4928.4 1934.34
  4936.6 1934.54  4943.0 1933.72  4964.1 1932.99  4978.3 1933.69  4986.5 1932.98
  4992.8 1933.34  5001.0 1932.09  5012.1 1931.77  5012.4 1931.27  5015.9 1931.27
  5016.1 1931.77  5036.3 1938.35  5042.6 1938.62  5050.0 1937.69  5054.3 1937.69
#Mann=5,-1,0
  4196.6   0.045       0  4851.9   0.035       0  4964.1    0.07       0
  5012.1    0.07       0  5016.1    0.07       0
Bank Sta=5012.1,5016.1
Exp/Cntr=0.3,0.1

Chan Stop Cuts=-1