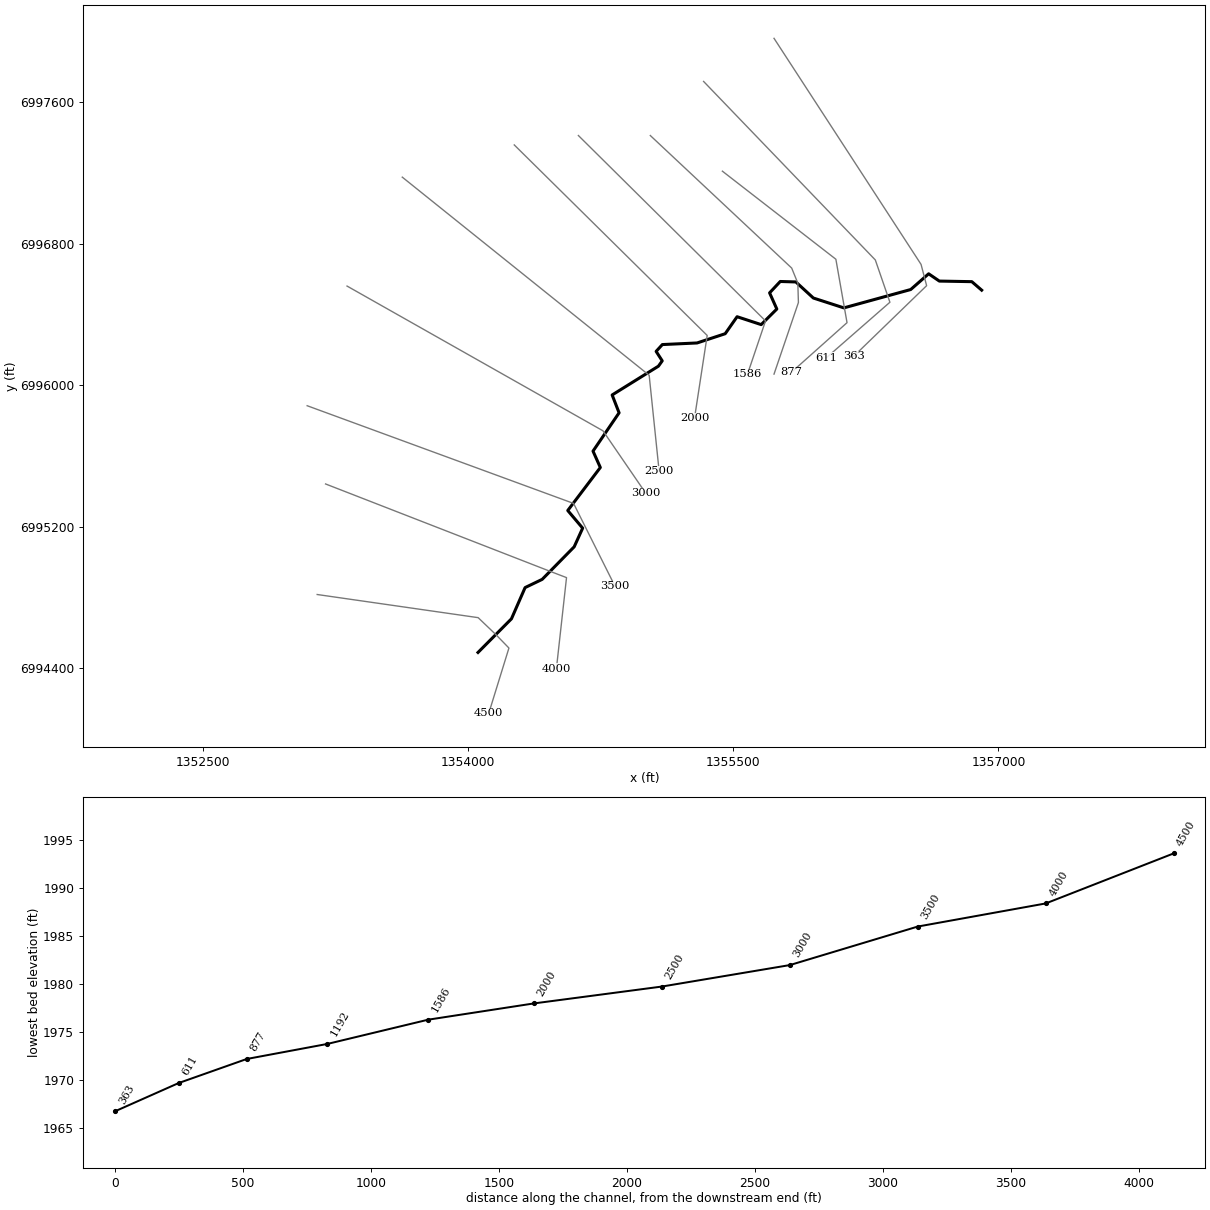
--- UCFB HW Trib 04-09-02.prj (project) ---

Proj Title=UCFB HW Trib 04-09-02 Base Level Engineering
Current Plan=p01
Default Exp/Contr=0.3,0.1
English Units
Geom File=g01
Flow File=f01
Plan File=p01
BEGIN DESCRIPTION:
UCFB HW Trib 04-09-02
END DESCRIPTION:

--- UCFB HW Trib 04-09-02.p01 (plan) ---

Plan Title=Multiple Run
Short Identifier=Multiple
Geom File=g01
Flow File=f01
Subcritical Flow
K Sum by GR= 0
Std Step Tol= 0.01
Critical Tol= 0.01
Num of Std Step Trials= 20
Max Error Tol= 0.3
Flow Tol Ratio= 0.001
Split Flow NTrial= 30
Split Flow Tol= 0.02
Split Flow Ratio= 0.02
Log Output Level= 0
Friction Slope Method= 1
Unsteady Friction Slope Method= 2
Unsteady Bridges Friction Slope Method= 1
Parabolic Critical Depth
Global Vel Dist=  1 , 1 , 1
Global Log Level= 0
CheckData=True
Encroach Param= -1, 0, 0, 0
BEGIN DESCRIPTION:
Multiple Run
END DESCRIPTION:

--- UCFB HW Trib 04-09-02.f01 (steady flow) ---

Flow Title=Multiple
Number of Profiles=7
Profile Names=10-year,25-year,50-year,1pct_min,100-year,1pct_plu,500-year
River Rch & RM= UCFB HW Trib 04-,Reach-1,4500
     205     284     348     213     425     847     638
Boundary for River Rch & Prof#=UCFB HW Trib 04-,Reach-1,1
Up Type=0
Dn Type=3
Dn Slope=0.005
Boundary for River Rch & Prof#=UCFB HW Trib 04-,Reach-1,2
Up Type=0
Dn Type=3
Dn Slope=0.005
Boundary for River Rch & Prof#=UCFB HW Trib 04-,Reach-1,3
Up Type=0
Dn Type=3
Dn Slope=0.005
Boundary for River Rch & Prof#=UCFB HW Trib 04-,Reach-1,4
Up Type=0
Dn Type=3
Dn Slope=0.005
Boundary for River Rch & Prof#=UCFB HW Trib 04-,Reach-1,5
Up Type=0
Dn Type=3
Dn Slope=0.005
Boundary for River Rch & Prof#=UCFB HW Trib 04-,Reach-1,6
Up Type=0
Dn Type=3
Dn Slope=0.005
Boundary for River Rch & Prof#=UCFB HW Trib 04-,Reach-1,7
Up Type=0
Dn Type=3
Dn Slope=0.005

--- UCFB HW Trib 04-09-02.g01 (geometry) ---

Geom Title=Existing Conditions

River Reach=UCFB HW Trib 04-,Reach-1
Reach XY= 30
      1354055.00      6994488.00      1354244.24      6994678.32
      1354321.49      6994855.05      1354418.20      6994901.64
      1354599.20      6995085.71      1354647.20      6995191.41
      1354562.85      6995291.23      1354747.18      6995534.59
      1354705.80      6995627.30      1354853.33      6995844.05
      1354814.03      6995945.01      1355075.93      6996107.93
      1355097.44      6996138.00      1355062.88      6996191.62
      1355098.18      6996230.19      1355294.50      6996239.22
      1355453.71      6996291.56      1355521.02      6996387.75
      1355657.33      6996343.09      1355745.86      6996431.25
      1355704.96      6996522.78      1355765.29      6996587.13
      1355853.49      6996584.53      1355952.58      6996493.54
      1356125.18      6996437.72      1356503.50      6996541.64
      1356604.90      6996630.67      1356665.43      6996589.39
      1356849.22      6996586.11      1356905.00      6996538.00

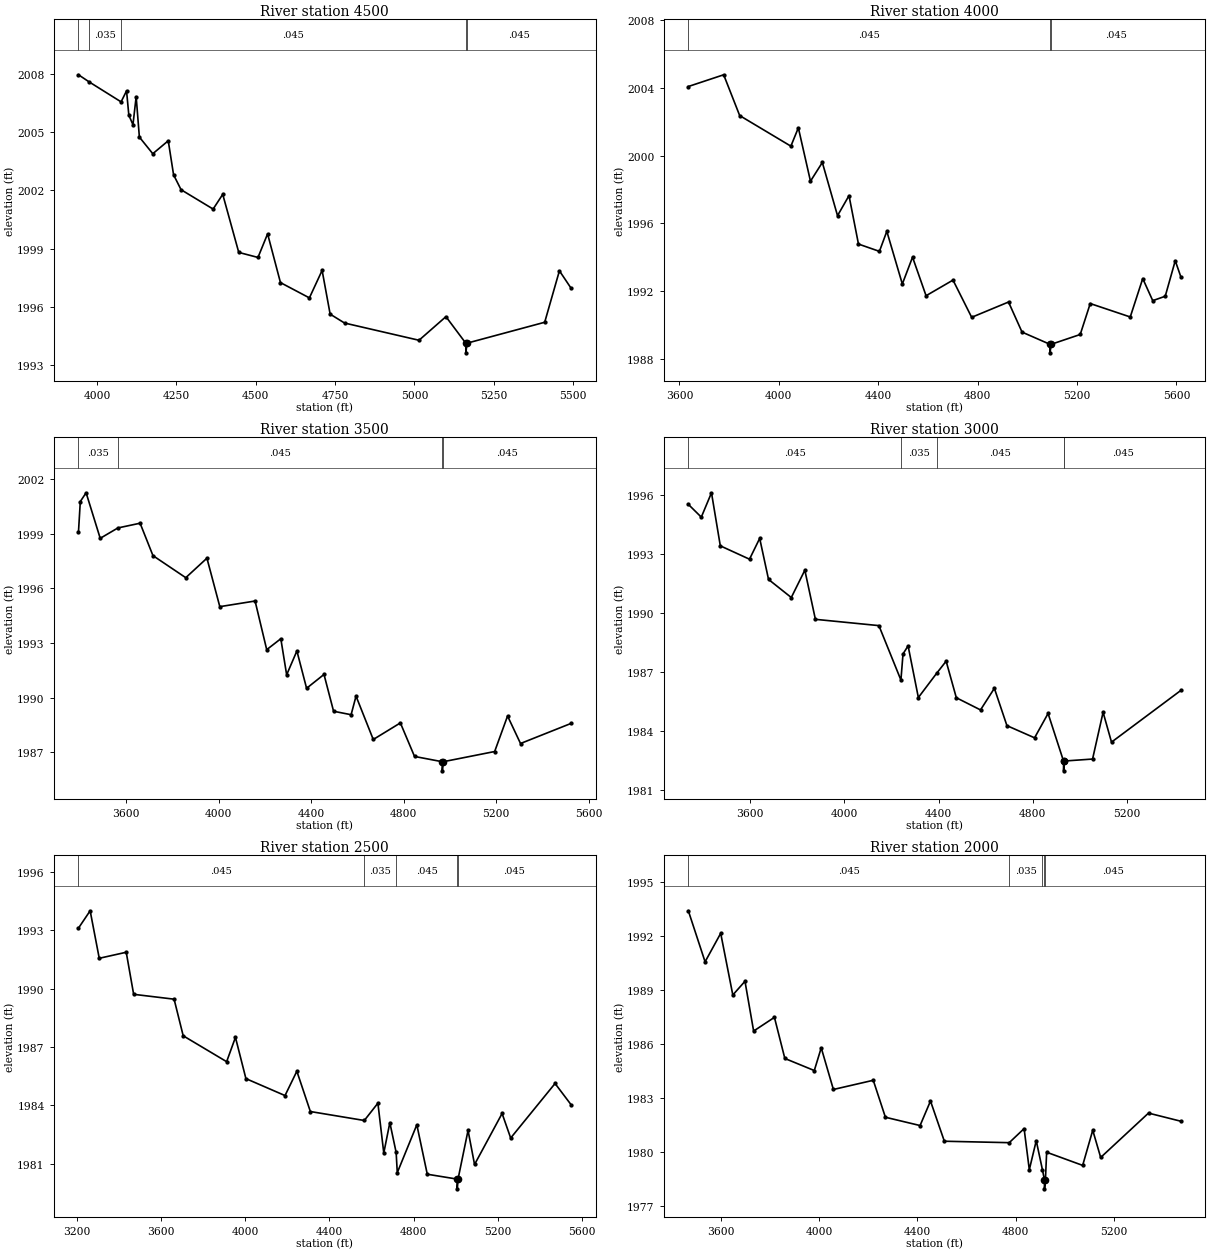
Type RM Length L Ch R = 1,4500,500,500,500
BEGIN DESCRIPTION:
UCFB HW Trib 04-09-02 9.0
END DESCRIPTION:
XS GIS Cut Line= 5
      1353145.03      6994815.89      1354055.86      6994684.92
      1354156.11      6994589.07      1354230.00      6994513.00
      1354115.77      6994143.29
#Sta/Elev= 30
  3941.1 2007.98  3974.9 2007.61  4075.4 2006.58  4092.6 2007.15  4099.8 2005.89
  4112.8 2005.40  4122.9 2006.85  4133.0 2004.76  4175.3 2003.90  4224.0 2004.57
  4240.8 2002.81  4264.4 2002.04  4365.4 2001.04  4395.7 2001.80  4446.2 1998.80
  4506.8 1998.54  4537.1 1999.76  4577.6 1997.24  4668.8 1996.45  4708.9 1997.87
  4734.2 1995.61  4779.6 1995.15  5014.2 1994.26  5099.1 1995.48  5161.6 1994.11
  5161.9 1993.61  5165.6 1994.11  5410.3 1995.19  5456.7 1997.85  5493.0 1996.96
#Mann=5,-1,0
  3941.1   0.045       0  3974.9   0.035       0  4075.4   0.045       0
  5161.6   0.045       0  5165.6   0.045       0
Bank Sta=5161.6,5165.6
Exp/Cntr=0.3,0.1

Type RM Length L Ch R = 1,4000,500,500,500
BEGIN DESCRIPTION:
UCFB HW Trib 04-09-02 8.0
END DESCRIPTION:
XS GIS Cut Line= 4
      1353192.47      6995441.42      1354463.92      6994946.70
      1354555.86      6994911.48      1354498.57      6994395.81
#Sta/Elev= 30
  3635.7 2004.06  3777.9 2004.75  3842.3 2002.35  4048.3 2000.55  4078.4 2001.63
  4127.2 1998.49  4174.9 1999.59  4236.0 1996.46  4282.2 1997.64  4320.3 1994.79
  4404.6 1994.36  4434.4 1995.54  4496.8 1992.44  4537.9 1994.02  4592.3 1991.75
  4700.7 1992.67  4775.8 1990.48  4924.1 1991.38  4978.5 1989.61  5091.2 1988.89
  5091.4 1988.39  5095.2 1988.89  5212.6 1989.47  5252.9 1991.29  5413.9 1990.50
  5464.2 1992.76  5504.4 1991.46  5554.7 1991.72  5595.0 1993.81  5617.3 1992.87
#Mann=3,-1,0
  3635.7   0.045       0  5091.2   0.045       0  5095.2   0.045       0
Bank Sta=5091.2,5095.2
Exp/Cntr=0.3,0.1

Type RM Length L Ch R = 1,3500,500,500,500
BEGIN DESCRIPTION:
UCFB HW Trib 04-09-02 7.0
END DESCRIPTION:
XS GIS Cut Line= 3
      1353088.29      6995884.13      1354595.74      6995331.36
      1354830.01      6994862.98
#Sta/Elev= 30
  3394.4 1999.09  3402.3 2000.76  3427.4 2001.24  3488.4 1998.74  3564.8 1999.31
  3660.8 1999.57  3716.5 1997.79  3858.3 1996.58  3949.8 1997.65  4005.5 1994.99
  4158.0 1995.30  4208.3 1992.63  4269.3 1993.23  4294.5 1991.25  4338.8 1992.56
  4380.7 1990.51  4456.0 1991.27  4497.4 1989.25  4573.2 1989.06  4594.5 1990.08
  4669.0 1987.70  4786.2 1988.61  4847.4 1986.77  4967.4 1986.48  4967.6 1985.98
  4971.4 1986.48  5193.9 1987.04  5249.7 1988.99  5305.7 1987.48  5523.7 1988.58
#Mann=4,-1,0
  3394.4   0.035       0  3564.8   0.045       0  4967.4   0.045       0
  4971.4   0.045       0
Bank Sta=4967.4,4971.4
Exp/Cntr=0.3,0.1

Type RM Length L Ch R = 1,3000,500,500,500
BEGIN DESCRIPTION:
UCFB HW Trib 04-09-02 6.0
END DESCRIPTION:
XS GIS Cut Line= 3
      1353313.99      6996561.21      1354762.05      6995742.25
      1355005.02      6995387.96
#Sta/Elev= 30
  3336.4 1995.52  3391.5 1994.87  3434.8 1996.11  3472.3 1993.41  3596.4 1992.73
  3639.7 1993.79  3677.3 1991.70  3774.0 1990.78  3831.6 1992.17  3876.5 1989.67
  4146.4 1989.35  4240.0 1986.58  4248.9 1987.91  4270.5 1988.32  4314.1 1985.69
  4391.6 1986.92  4432.2 1987.54  4475.5 1985.68  4578.3 1985.06  4637.2 1986.16
  4690.6 1984.26  4808.1 1983.64  4865.5 1984.88  4931.1 1982.46  4931.4 1981.96
  4935.1 1982.46  5054.6 1982.56  5099.3 1984.94  5135.1 1983.42  5429.6 1986.05
#Mann=5,-1,0
  3336.4   0.045       0  4240.0   0.035       0  4391.6   0.045       0
  4931.1   0.045       0  4935.1   0.045       0
Bank Sta=4931.1,4935.1
Exp/Cntr=0.3,0.1

Type RM Length L Ch R = 1,2500,500,500,500
BEGIN DESCRIPTION:
UCFB HW Trib 04-09-02 5.0
END DESCRIPTION:
XS GIS Cut Line= 3
      1353626.52      6997177.51      1355023.58      6996056.35
      1355080.00      6995512.97
#Sta/Elev= 30
  3208.7 1993.11  3264.1 1994.00  3307.3 1991.56  3435.4 1991.87  3470.6 1989.71
  3662.6 1989.46  3705.8 1987.58  3912.0 1986.25  3953.8 1987.50  4003.5 1985.38
  4189.1 1984.51  4245.3 1985.76  4309.4 1983.69  4565.5 1983.23  4630.0 1984.12
  4657.9 1981.56  4686.7 1983.12  4716.6 1981.59  4722.0 1980.55  4814.8 1983.01
  4864.4 1980.47  5006.4 1980.22  5006.6 1979.72  5010.4 1980.22  5057.9 1982.72
  5088.8 1980.97  5219.5 1983.59  5260.3 1982.33  5470.9 1985.13  5546.3 1984.05
#Mann=5,-1,0
  3208.7   0.045       0  4565.5   0.035       0  4716.6   0.045       0
  5006.4   0.045       0  5010.4   0.045       0
Bank Sta=5006.4,5010.4
Exp/Cntr=0.3,0.1

Type RM Length L Ch R = 1,2000,414,414,414
BEGIN DESCRIPTION:
UCFB HW Trib 04-09-02 4.0
END DESCRIPTION:
XS GIS Cut Line= 3
      1354260.21      6997359.79      1355351.88      6996281.67
      1355280.01      6995813.05
#Sta/Elev= 30
  3465.7 1993.38  3534.0 1990.55  3597.7 1992.13  3647.1 1988.71  3696.7 1989.47
  3732.0 1986.71  3816.8 1987.47  3859.3 1985.19  3979.4 1984.52  4007.7 1985.78
  4057.3 1983.47  4219.9 1983.98  4269.4 1981.93  4410.8 1981.47  4453.3 1982.83
  4509.8 1980.60  4774.4 1980.52  4835.1 1981.30  4856.3 1979.02  4884.6 1980.63
  4909.8 1979.02  4918.0 1978.46  4918.2 1977.96  4922.0 1978.46  4927.0 1979.99
  5073.9 1979.26  5115.0 1981.21  5147.4 1979.70  5342.4 1982.16  5474.1 1981.71
#Mann=5,-1,0
  3465.7   0.045       0  4774.4   0.035       0  4909.8   0.045       0
  4918.0   0.045       0  4922.0   0.045       0
Bank Sta=4918,4922
Exp/Cntr=0.3,0.1

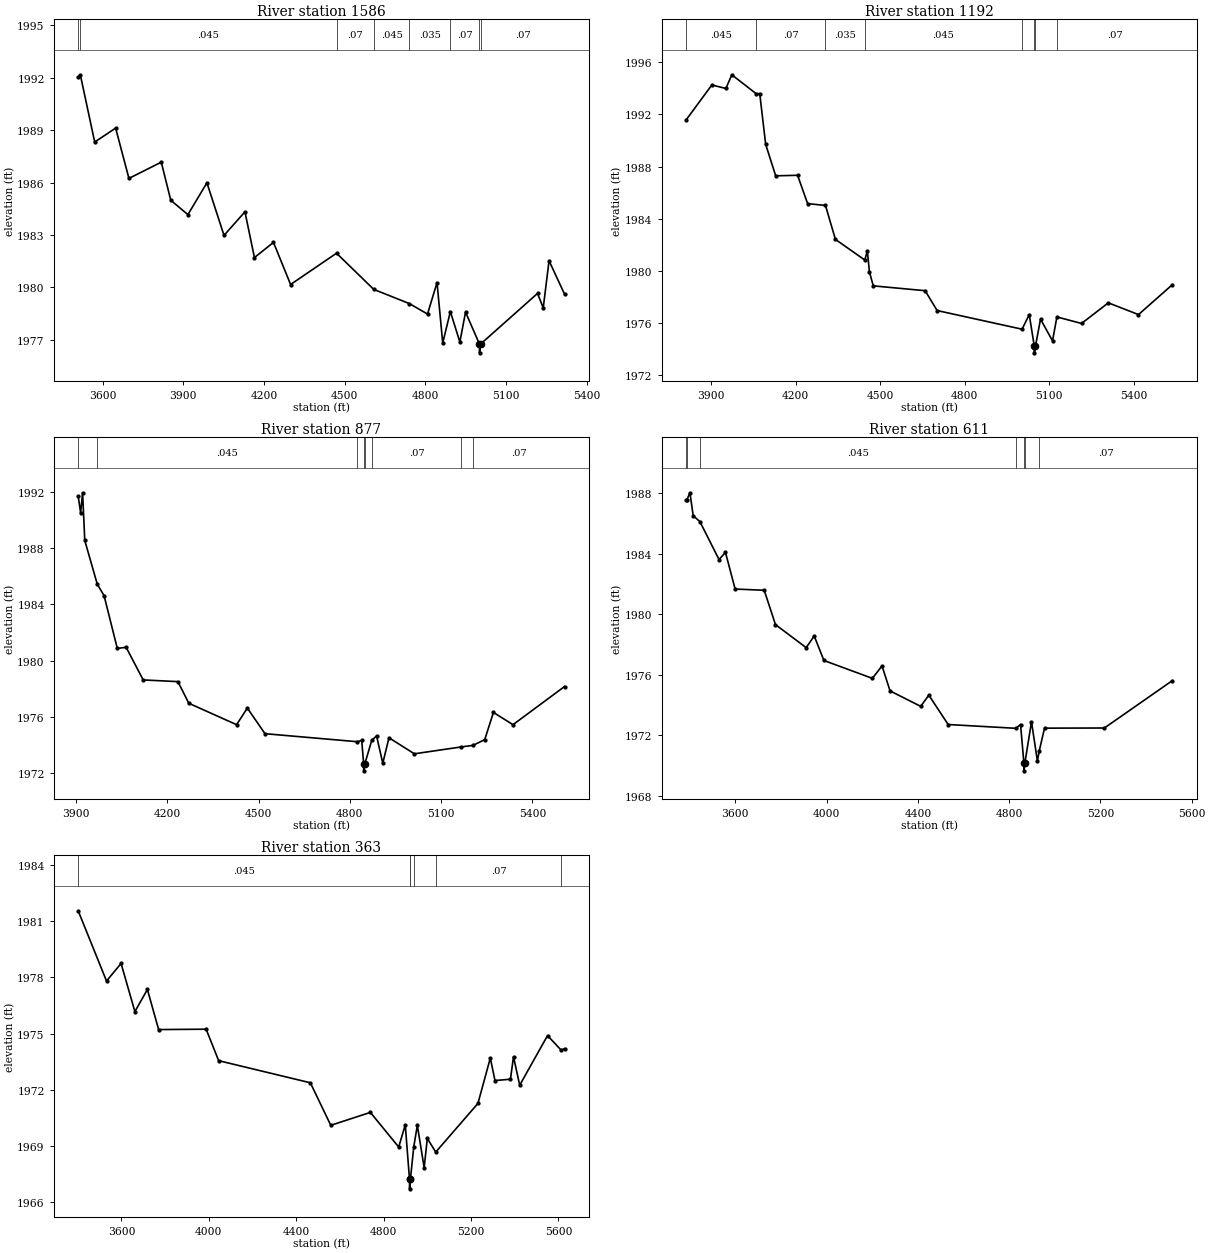
Type RM Length L Ch R = 1,1586,394,394,394
BEGIN DESCRIPTION:
UCFB HW Trib 04-09-02 3.0
END DESCRIPTION:
XS GIS Cut Line= 3
      1354623.05      6997413.00      1355681.95      6996364.04
      1355580.01      6996063.03
#Sta/Elev= 30
  3509.5 1992.02  3517.5 1992.17  3571.0 1988.32  3648.8 1989.12  3698.2 1986.24
  3818.5 1987.17  3853.8 1984.99  3917.5 1984.17  3988.2 1985.99  4051.8 1982.98
  4129.6 1984.33  4164.9 1981.71  4235.7 1982.58  4299.3 1980.17  4470.1 1981.96
  4608.5 1979.89  4740.6 1979.08  4808.4 1978.48  4843.8 1980.28  4865.0 1976.82
  4893.4 1978.62  4928.7 1976.88  4949.8 1978.59  5001.6 1976.76  5001.8 1976.26
  5005.6 1976.76  5217.5 1979.66  5238.7 1978.83  5260.3 1981.53  5317.8 1979.62
#Mann=8,-1,0
  3509.5    0.07       0  3517.5   0.045       0  4470.1    0.07       0
  4608.5   0.045       0  4740.6   0.035       0  4893.4    0.07       0
  5001.6    0.07       0  5005.6    0.07       0
Bank Sta=5001.6,5005.6
Exp/Cntr=0.3,0.1

Type RM Length L Ch R = 1,1192,315,315,315
BEGIN DESCRIPTION:
UCFB HW Trib 04-09-02 2.0
END DESCRIPTION:
XS GIS Cut Line= 5
      1355030.03      6997412.97      1355830.00      6996663.00
      1355864.77      6996577.54      1355868.02      6996467.99
      1355729.99      6996062.97
#Sta/Elev= 30
  3811.2 1991.56  3903.0 1994.25  3952.8 1993.98  3973.8 1995.03  4060.3 1993.58
  4073.0 1993.58  4094.0 1989.70  4129.6 1987.29  4207.3 1987.33  4242.9 1985.16
  4306.3 1985.02  4341.6 1982.42  4445.9 1980.84  4454.9 1981.54  4462.3 1979.93
  4476.0 1978.86  4660.1 1978.49  4702.6 1976.97  5004.1 1975.54  5029.6 1976.66
  5047.6 1974.23  5047.8 1973.73  5051.6 1974.23  5069.6 1976.31  5112.2 1974.65
  5127.8 1976.48  5215.2 1975.98  5310.3 1977.56  5417.4 1976.66  5537.5 1978.95
#Mann=8,-1,0
  3811.2   0.045       0  4060.3    0.07       0  4306.3   0.035       0
  4445.9   0.045       0  5004.1   0.035       0  5047.6   0.045       0
  5051.6   0.035       0  5127.8    0.07       0
Bank Sta=5047.6,5051.6
Exp/Cntr=0.3,0.1

Type RM Length L Ch R = 1,877,266,266,266
BEGIN DESCRIPTION:
UCFB HW Trib 04-09-02 1.2
END DESCRIPTION:
XS GIS Cut Line= 4
      1355437.83      6997211.28      1356080.00      6996713.00
      1356143.10      6996354.09      1355829.45      6996074.20
#Sta/Elev= 30
  3907.6 1991.68  3915.7 1990.50  3922.1 1991.92  3929.3 1988.53  3970.4 1985.42
  3992.7 1984.61  4036.1 1980.86  4065.1 1980.94  4121.2 1978.62  4235.2 1978.50
  4271.1 1976.96  4428.0 1975.44  4463.3 1976.62  4521.3 1974.80  4824.3 1974.23
  4839.1 1974.32  4845.3 1972.66  4845.6 1972.16  4849.3 1972.66  4872.2 1974.34
  4887.9 1974.64  4908.2 1972.70  4928.6 1974.51  5012.0 1973.37  5166.3 1973.86
  5204.9 1973.97  5243.2 1974.38  5271.7 1976.31  5336.0 1975.44  5505.2 1978.15
#Mann=8,-1,0
  3907.6   0.035       0  3970.4   0.045       0  4824.3   0.035       0
  4845.3    0.07       0  4849.3   0.035       0  4872.2    0.07       0
  5166.3   0.035       0  5204.9    0.07       0
Bank Sta=4845.3,4849.3
Exp/Cntr=0.3,0.1

Type RM Length L Ch R = 1,611,248,248,248
BEGIN DESCRIPTION:
UCFB HW Trib 04-09-02 1.1
END DESCRIPTION:
XS GIS Cut Line= 4
      1355331.49      6997719.10      1356303.22      6996708.92
      1356385.72      6996469.66      1356026.83      6996156.15
#Sta/Elev= 30
  3384.0 1987.55  3387.8 1987.55  3401.3 1988.02  3415.5 1986.51  3445.2 1986.11
  3528.7 1983.61  3557.0 1984.08  3599.4 1981.66  3726.8 1981.58  3776.1 1979.31
  3910.7 1977.79  3945.9 1978.56  3988.4 1976.94  4200.7 1975.76  4243.1 1976.58
  4278.3 1974.93  4412.6 1973.91  4448.1 1974.65  4533.0 1972.71  4829.8 1972.46
  4850.1 1972.71  4864.9 1970.15  4865.2 1969.65  4868.9 1970.15  4898.1 1972.89
  4924.0 1970.30  4932.4 1970.99  4955.2 1972.47  5217.5 1972.48  5515.3 1975.61
#Mann=7,-1,0
  3384.0    0.07       0  3387.8   0.035       0  3445.2   0.045       0
  4829.8   0.035       0  4864.9    0.07       0  4868.9   0.035       0
  4932.4    0.07       0
Bank Sta=4864.9,4868.9
Exp/Cntr=0.3,0.1

Type RM Length L Ch R = 1,363,0,0,0
BEGIN DESCRIPTION:
UCFB HW Trib 04-09-02 1.0
END DESCRIPTION:
XS GIS Cut Line= 4
      1355730.02      6997962.96      1356562.03      6996683.85
      1356593.49      6996563.41      1356179.98      6996162.98
#Sta/Elev= 30
  3402.0 1981.55  3531.8 1977.80  3598.3 1978.74  3661.6 1976.17  3718.9 1977.35
  3770.3 1975.21  3987.7 1975.23  4045.0 1973.55  4464.7 1972.37  4558.2 1970.10
  4739.4 1970.79  4869.2 1968.94  4899.1 1970.13  4918.6 1967.21  4918.8 1966.71
  4922.6 1967.21  4938.0 1968.95  4954.4 1970.10  4985.6 1967.84  5000.1 1969.40
  5038.5 1968.67  5231.8 1971.27  5288.4 1973.69  5309.8 1972.49  5380.5 1972.56
  5394.6 1973.76  5422.9 1972.24  5550.3 1974.89  5612.9 1974.11  5628.0 1974.19
#Mann=6,-1,0
  3402.0   0.045       0  4918.6   0.035       0  4922.6   0.045       0
  4938.0   0.035       0  5038.5    0.07       0  5612.9   0.035       0
Bank Sta=4918.6,4922.6
Exp/Cntr=0.3,0.1

Chan Stop Cuts=-1