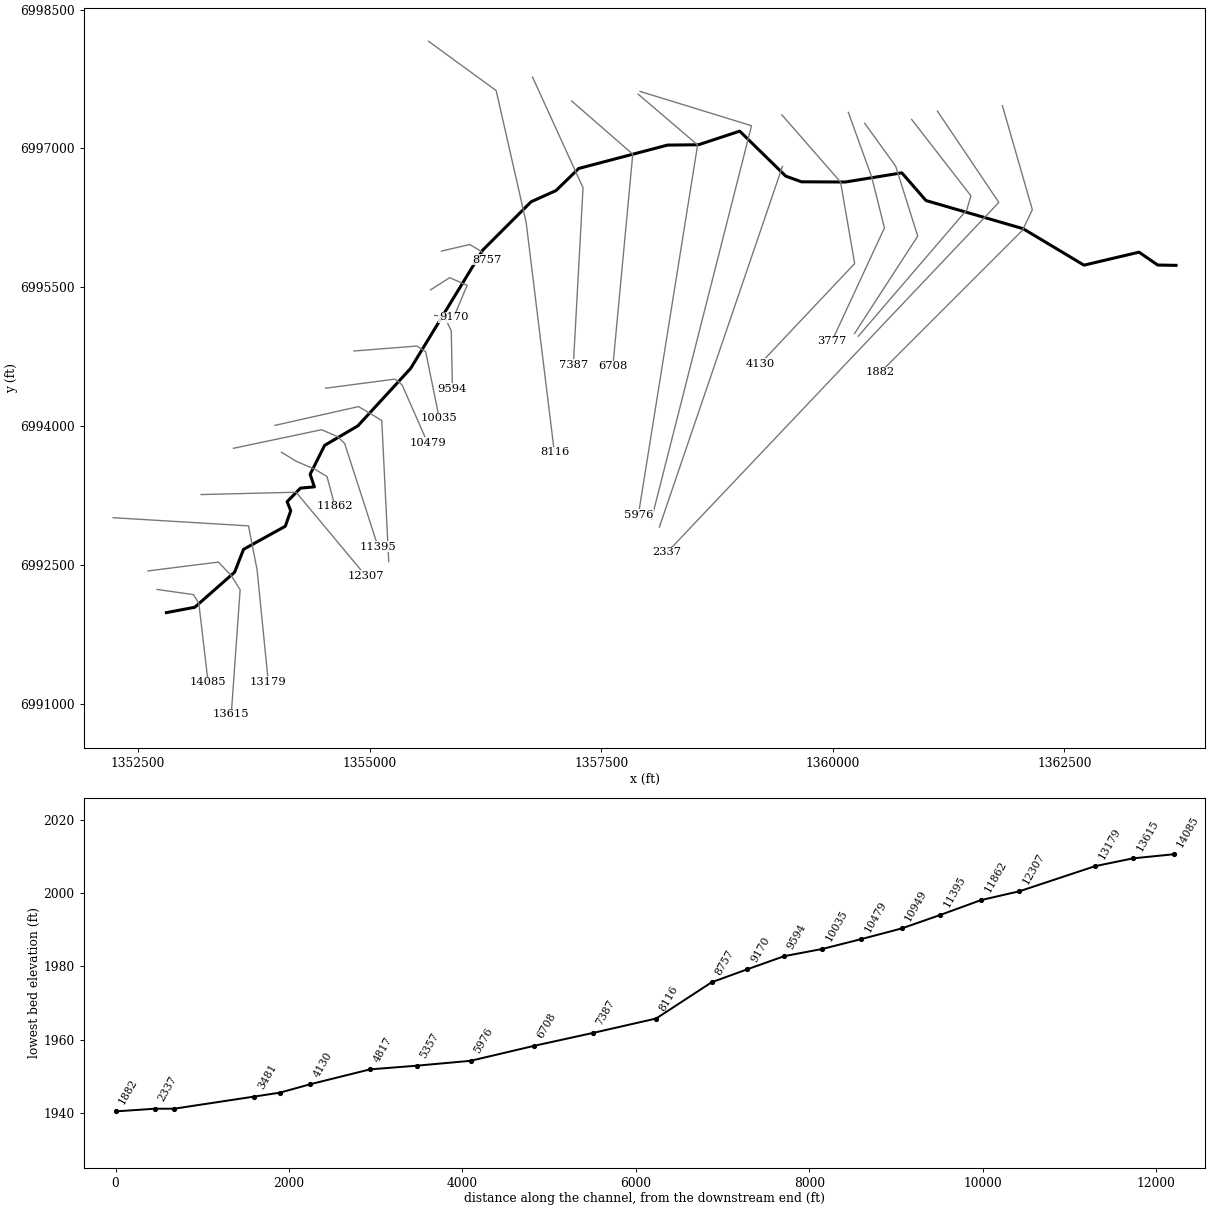
--- UCFB HW Trib 04-09.prj (project) ---

Proj Title=UCFB HW Trib 04-09 Base Level Engineering
Current Plan=p01
Default Exp/Contr=0.3,0.1
English Units
Geom File=g01
Flow File=f01
Plan File=p01
Y Axis Title=Elevation
X Axis Title(PF)=Main Channel Distance
X Axis Title(XS)=Station
BEGIN DESCRIPTION:
UCFB HW Trib 04-09
END DESCRIPTION:
DSS Export Rating Curves= 0
DSS Export Rating Curve Sorted= 0
DSS Export Volume Flow Curves= 0
DXF OffsetX= 0
DXF OffsetY= 0
DXF ScaleX= 1
DXF ScaleY= 10

--- UCFB HW Trib 04-09.p01 (plan) ---

Plan Title=Multiple Run
Short Identifier=Multiple
Geom File=g01
Flow File=f01
Subcritical Flow
K Sum by GR= 0
Std Step Tol= 0.01
Critical Tol= 0.01
Num of Std Step Trials= 20
Max Error Tol= 0.3
Flow Tol Ratio= 0.001
Split Flow NTrial= 30
Split Flow Tol= 0.02
Split Flow Ratio= 0.02
Log Output Level= 0
Friction Slope Method= 1
Unsteady Friction Slope Method= 2
Unsteady Bridges Friction Slope Method= 1
Parabolic Critical Depth
Global Vel Dist=  1 , 1 , 1
Global Log Level= 0
CheckData=True
Encroach Param= -1, 0, 0, 0
BEGIN DESCRIPTION:
Multiple Run
END DESCRIPTION:

--- UCFB HW Trib 04-09.f01 (steady flow) ---

Flow Title=Multiple
Program Version=4.10
Number of Profiles= 7
Profile Names=10-year,25-year,50-year,1pct_min,100-year,1pct_plu,500-year
River Rch & RM=UCFB HW Trib 04-,Reach-1         ,14085
     220     306     376     230     460     918     695
River Rch & RM=UCFB HW Trib 04-,Reach-1         ,10949
     307     435     543     337     672    1341    1042
River Rch & RM=UCFB HW Trib 04-,Reach-1         ,8116
     319     454     567     352     703    1402    1093
River Rch & RM=UCFB HW Trib 04-,Reach-1         ,7387
     466     675     853     536    1069    2133    1701
River Rch & RM=UCFB HW Trib 04-,Reach-1         ,4130
     545     795    1009     636    1268    2530    2031
Boundary for River Rch & Prof#=UCFB HW Trib 04-,Reach-1         , 1
Up Type= 0
Dn Type= 3
Dn Slope=0.005
Boundary for River Rch & Prof#=UCFB HW Trib 04-,Reach-1         , 2
Up Type= 0
Dn Type= 3
Dn Slope=0.005
Boundary for River Rch & Prof#=UCFB HW Trib 04-,Reach-1         , 3
Up Type= 0
Dn Type= 3
Dn Slope=0.005
Boundary for River Rch & Prof#=UCFB HW Trib 04-,Reach-1         , 4
Up Type= 0
Dn Type= 3
Dn Slope=0.005
Boundary for River Rch & Prof#=UCFB HW Trib 04-,Reach-1         , 5
Up Type= 0
Dn Type= 3
Dn Slope=0.005
Boundary for River Rch & Prof#=UCFB HW Trib 04-,Reach-1         , 6
Up Type= 0
Dn Type= 3
Dn Slope=0.005
Boundary for River Rch & Prof#=UCFB HW Trib 04-,Reach-1         , 7
Up Type= 0
Dn Type= 3
Dn Slope=0.005
DSS Import GetInterval= 0
DSS Import GetPeak= 0
DSS Import FillOption= 0

--- UCFB HW Trib 04-09.g01 (geometry) ---

Geom Title=Existing Conditions

River Reach=UCFB HW Trib 04-,Reach-1
Reach XY= 30
      1352805.00      6991988.00      1353111.19      6992045.81
      1353541.38      6992424.78      1353637.87      6992671.54
      1354088.70      6992920.87      1354147.41      6993088.01
      1354108.16      6993186.35      1354252.56      6993332.53
      1354402.52      6993346.10      1354356.83      6993481.88
      1354513.15      6993794.07      1354871.68      6994004.64
      1355441.37      6994624.79      1356218.63      6995901.21
      1356741.79      6996424.37      1357011.22      6996545.74
      1357256.50      6996784.39      1358215.50      6997036.78
      1358549.06      6997040.26      1358994.32      6997187.25
      1359491.69      6996701.40      1359660.94      6996640.26
      1360134.97      6996638.07      1360744.53      6996737.07
      1361005.00      6996438.00      1362053.42      6996134.17
      1362710.97      6995740.14      1363305.01      6995880.47
      1363506.47      6995741.54      1363705.00      6995738.00

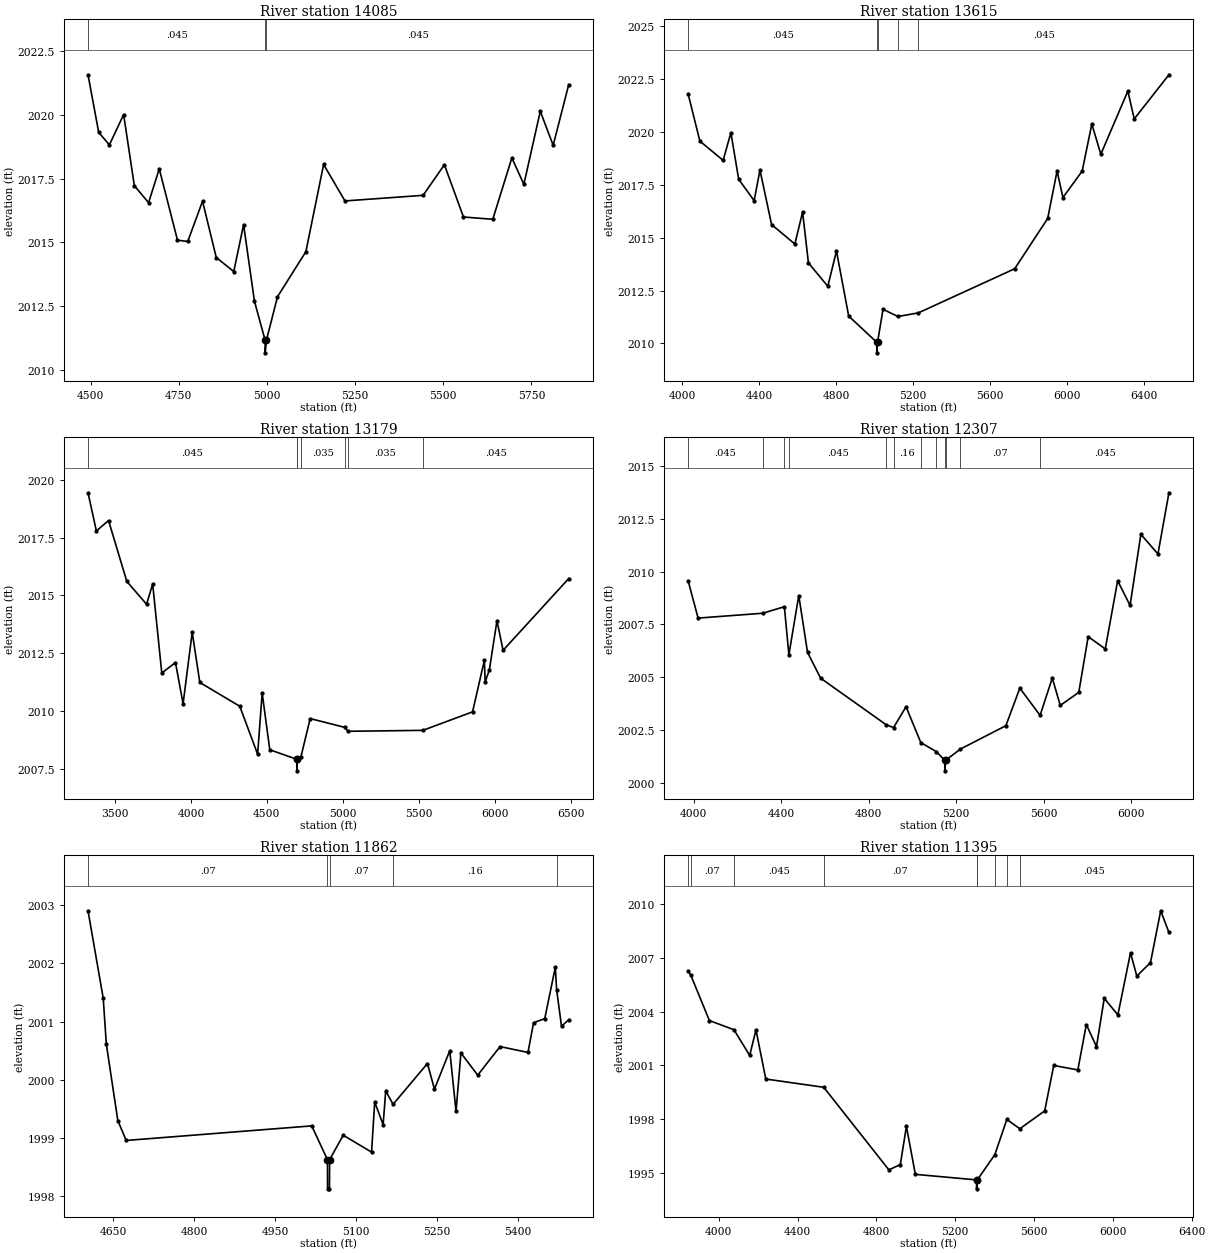
Type RM Length L Ch R = 1,14085,470,470,470
BEGIN DESCRIPTION:
UCFB HW Trib 04-09 13.0
END DESCRIPTION:
XS GIS Cut Line= 4
      1352704.95      6992238.01      1353097.30      6992182.45
      1353155.00      6992088.00      1353255.00      6991238.01
#Sta/Elev= 30
  4492.7 2021.58  4523.0 2019.32  4553.3 2018.83  4593.7 2020.02  4624.0 2017.23
  4664.4 2016.56  4694.7 2017.89  4746.4 2015.09  4775.5 2015.04  4817.4 2016.62
  4856.3 2014.41  4905.9 2013.86  4933.8 2015.70  4964.5 2012.70  4994.7 2011.17
  4995.0 2010.67  4998.7 2011.17  5029.9 2012.87  5110.4 2014.64  5160.7 2018.06
  5221.2 2016.63  5442.7 2016.85  5503.1 2018.05  5557.2 2016.00  5640.3 2015.91
  5694.4 2018.32  5728.4 2017.28  5775.0 2020.15  5811.5 2018.81  5855.5 2021.19
#Mann=3,-1,0
  4492.7   0.045       0  4994.7   0.045       0  4998.7   0.045       0
Bank Sta=4994.7,4998.7
Exp/Cntr=0.3,0.1

Type RM Length L Ch R = 1,13615,436,436,436
BEGIN DESCRIPTION:
UCFB HW Trib 04-09 12.0
END DESCRIPTION:
XS GIS Cut Line= 5
      1352604.99      6992438.00      1353366.40      6992534.02
      1353505.00      6992388.00      1353600.78      6992234.54
      1353505.00      6990888.00
#Sta/Elev= 30
  4031.0 2021.78  4091.5 2019.57  4212.4 2018.66  4252.8 2019.97  4293.1 2017.77
  4373.7 2016.75  4403.9 2018.20  4464.4 2015.62  4585.4 2014.70  4625.6 2016.21
  4655.9 2013.81  4756.7 2012.70  4801.8 2014.37  4865.3 2011.29  5011.3 2010.05
  5011.6 2009.55  5015.3 2010.05  5044.0 2011.61  5121.1 2011.27  5227.3 2011.44
  5728.6 2013.53  5900.2 2015.91  5949.1 2018.16  5979.2 2016.90  6079.5 2018.15
  6129.6 2020.38  6176.5 2018.95  6317.1 2021.94  6350.1 2020.62  6530.6 2022.71
#Mann=5,-1,0
  4031.0   0.045       0  5011.3   0.045       0  5015.3   0.045       0
  5121.1   0.035       0  5227.3   0.045       0
Bank Sta=5011.3,5015.3
Exp/Cntr=0.3,0.1

Type RM Length L Ch R = 1,13179,872,872,872
BEGIN DESCRIPTION:
UCFB HW Trib 04-09 11.0
END DESCRIPTION:
XS GIS Cut Line= 4
      1352229.95      6993013.00      1353691.36      6992924.92
      1353783.56      6992452.37      1353905.00      6991238.04
#Sta/Elev= 30
  3322.0 2019.44  3377.1 2017.79  3457.3 2018.24  3577.5 2015.61  3707.7 2014.62
  3747.8 2015.50  3807.9 2011.65  3898.1 2012.10  3948.2 2010.32  4008.3 2013.41
  4058.4 2011.24  4321.6 2010.21  4439.1 2008.14  4469.1 2010.78  4519.2 2008.33
  4697.5 2007.92  4697.8 2007.42  4701.5 2007.92  4723.7 2008.01  4785.4 2009.68
  5012.3 2009.30  5034.3 2009.13  5527.3 2009.17  5854.8 2009.97  5932.7 2012.20
  5937.7 2011.26  5965.3 2011.78  6015.6 2013.91  6055.8 2012.63  6487.9 2015.73
#Mann=7,-1,0
  3322.0   0.045       0  4697.5   0.035       0  4701.5   0.045       0
  4723.7   0.035       0  5012.3   0.045       0  5034.3   0.035       0
  5527.3   0.045       0
Bank Sta=4697.5,4701.5
Exp/Cntr=0.3,0.1

Type RM Length L Ch R = 1,12307,445,445,445
BEGIN DESCRIPTION:
UCFB HW Trib 04-09 10.0
END DESCRIPTION:
XS GIS Cut Line= 3
      1353180.01      6993263.00      1354205.00      6993288.00
      1354954.98      6992388.03
#Sta/Elev= 30
  3975.1 2009.55  4020.1 2007.80  4315.4 2008.03  4414.4 2008.34  4435.0 2006.06
  4480.2 2008.87  4520.3 2006.17  4580.3 2004.95  4880.3 2002.74  4913.4 2002.61
  4970.4 2003.60  5037.9 2001.90  5108.8 2001.47  5147.4 2001.06  5147.7 2000.56
  5151.4 2001.06  5218.7 2001.59  5426.7 2002.70  5490.5 2004.48  5583.1 2003.19
  5638.9 2004.96  5675.3 2003.66  5759.9 2004.28  5802.9 2006.92  5881.0 2006.34
  5937.6 2009.57  5994.3 2008.40  6043.7 2011.77  6121.8 2010.84  6171.9 2013.74
#Mann=12,-1,0
  3975.1   0.045       0  4315.4   0.035       0  4414.4    0.07       0
  4435.0   0.045       0  4880.3    0.07       0  4913.4    0.16       0
  5037.9    0.07       0  5108.8    0.16       0  5147.4    0.07       0
  5151.4    0.16       0  5218.7    0.07       0  5583.1   0.045       0
Bank Sta=5147.4,5151.4
Exp/Cntr=0.3,0.1

Type RM Length L Ch R = 1,11862,467,467,467
BEGIN DESCRIPTION:
UCFB HW Trib 04-09 9.0
END DESCRIPTION:
XS GIS Cut Line= 5
      1354048.09      6993718.91      1354212.75      6993619.09
      1354405.00      6993538.00      1354538.28      6993458.50
      1354625.38      6993135.11
#Sta/Elev= 30
  4603.0 2002.90  4631.2 2001.40  4637.0 2000.61  4658.3 1999.30  4673.8 1998.96
  5017.8 1999.21  5047.0 1998.63  5047.2 1998.13  5050.7 1998.13  5051.0 1998.63
  5076.2 1999.05  5128.8 1998.76  5134.6 1999.62  5150.2 1999.23  5155.0 1999.81
  5168.7 1999.58  5232.4 2000.28  5245.4 1999.84  5273.8 2000.50  5285.4 1999.46
  5294.5 2000.46  5325.6 2000.08  5367.0 2000.57  5418.8 2000.47  5429.2 2000.98
  5449.9 2001.05  5469.5 2001.93  5472.0 2001.54  5481.0 2000.92  5494.3 2001.03
#Mann=5,-1,0
  4603.0    0.07       0  5047.0    0.07       0  5051.0    0.07       0
  5168.7    0.16       0  5472.0    0.07       0
Bank Sta=5047,5051
Exp/Cntr=0.3,0.1

Type RM Length L Ch R = 1,11395,446,446,446
BEGIN DESCRIPTION:
UCFB HW Trib 04-09 8.0
END DESCRIPTION:
XS GIS Cut Line= 5
      1353530.00      6993763.00      1354480.00      6993963.00
      1354655.00      6993888.00      1354730.00      6993813.00
      1355090.17      6992698.33
#Sta/Elev= 30
  3845.6 2006.26  3858.9 2006.03  3952.9 2003.50  4077.2 2002.99  4157.3 2001.55
  4189.2 2002.98  4239.0 2000.23  4532.9 1999.77  4863.6 1995.15  4921.6 1995.45
  4952.4 1997.58  4997.8 1994.90  5308.3 1994.59  5308.5 1994.09  5312.3 1994.59
  5401.3 1996.01  5461.9 1997.97  5527.8 1997.45  5654.1 1998.45  5699.9 2000.99
  5822.2 2000.74  5865.2 2003.28  5916.8 2002.04  5956.1 2004.74  6025.4 2003.82
  6089.4 2007.29  6121.4 2005.99  6190.7 2006.74  6242.6 2009.64  6284.3 2008.43
#Mann=9,-1,0
  3845.6   0.045       0  3858.9    0.07       0  4077.2   0.045       0
  4532.9    0.07       0  5308.3    0.07       0  5312.3    0.07       0
  5401.3   0.045       0  5461.9    0.07       0  5527.8   0.045       0
Bank Sta=5308.3,5312.3
Exp/Cntr=0.3,0.1

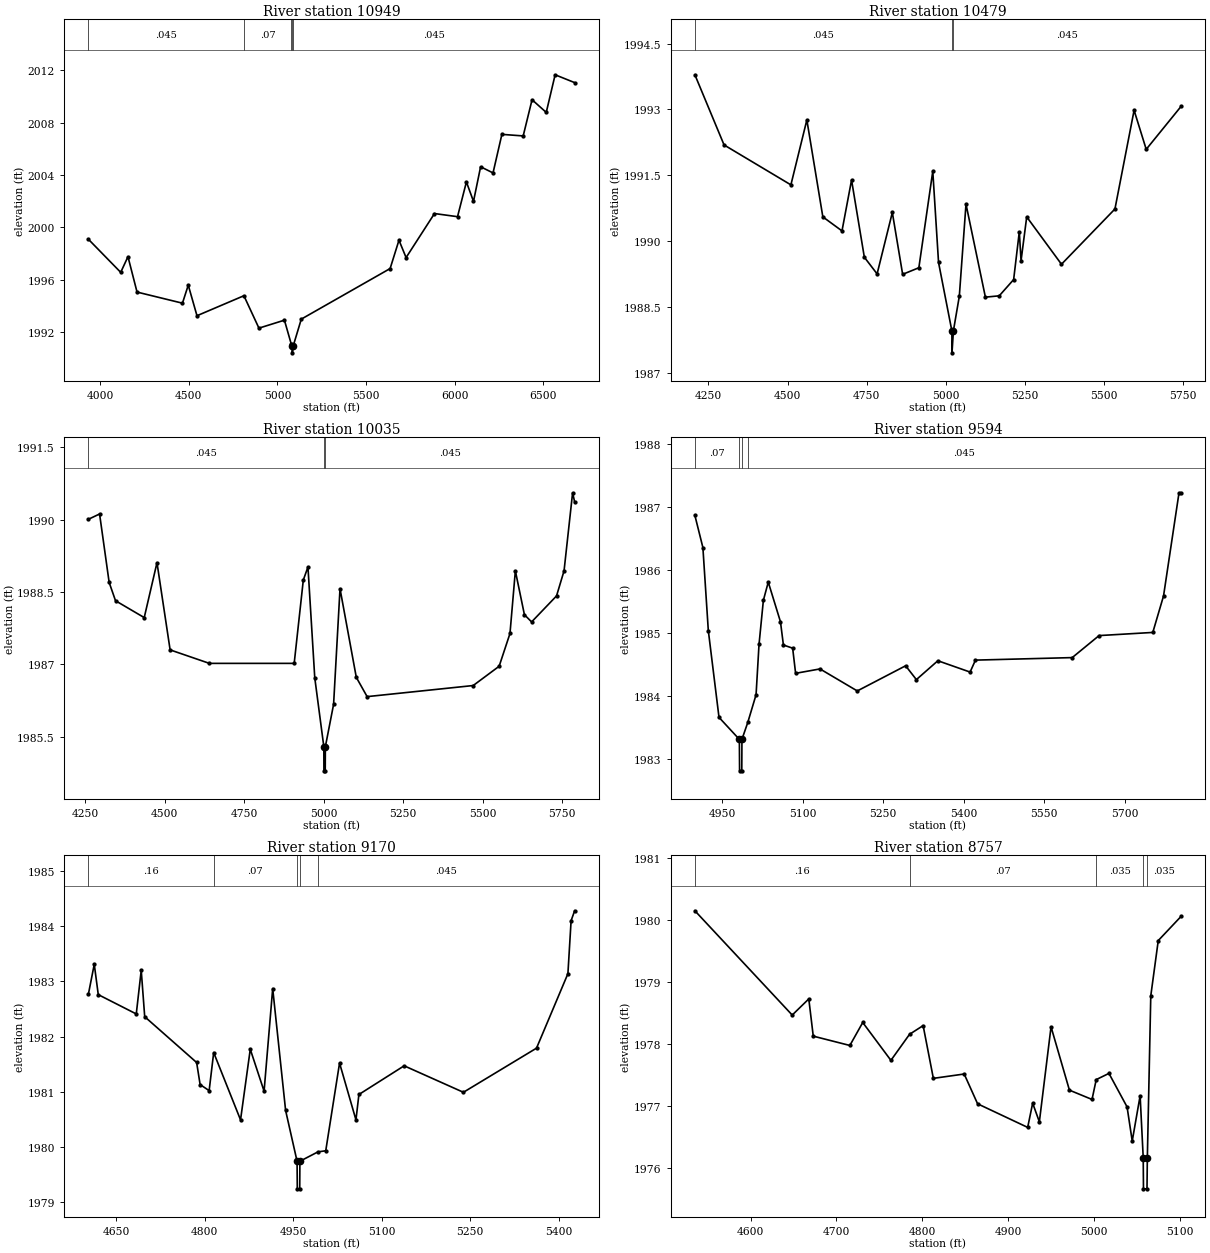
Type RM Length L Ch R = 1,10949,470,470,470
BEGIN DESCRIPTION:
UCFB HW Trib 04-09 7.0
END DESCRIPTION:
XS GIS Cut Line= 5
      1353977.27      6994010.19      1354880.00      6994213.00
      1355005.00      6994138.00      1355130.00      6994063.00
      1355205.00      6992538.02
#Sta/Elev= 30
  3933.4 1999.08  4115.6 1996.55  4156.6 1997.75  4207.8 1995.04  4464.0 1994.19
  4496.8 1995.57  4546.0 1993.23  4810.8 1994.76  4895.6 1992.28  5039.4 1992.89
  5078.6 1991.03  5083.6 1990.89  5084.0 1990.39  5088.4 1990.89  5134.6 1992.97
  5635.8 1996.84  5685.8 1999.01  5725.9 1997.68  5886.1 2001.05  6016.2 2000.81
  6066.3 2003.47  6106.3 2001.98  6146.4 2004.63  6216.5 2004.16  6266.5 2007.11
  6386.7 2006.99  6436.7 2009.76  6516.8 2008.79  6566.9 2011.67  6677.0 2011.07
#Mann=5,-1,0
  3933.4   0.045       0  4810.8    0.07       0  5078.6   0.045       0
  5083.6    0.07       0  5088.4   0.045       0
Bank Sta=5083.6,5088.4
Exp/Cntr=0.3,0.1

Type RM Length L Ch R = 1,10479,444,444,444
BEGIN DESCRIPTION:
UCFB HW Trib 04-09 6.0
END DESCRIPTION:
XS GIS Cut Line= 5
      1354524.27      6994411.56      1355269.40      6994509.27
      1355305.00      6994488.00      1355351.24      6994443.37
      1355624.30      6993822.08
#Sta/Elev= 30
  4207.0 1993.79  4299.2 1992.19  4510.3 1991.28  4560.7 1992.76  4611.2 1990.55
  4671.7 1990.23  4701.9 1991.39  4742.3 1989.63  4782.6 1989.25  4830.7 1990.65
  4863.3 1989.24  4914.5 1989.39  4958.5 1991.59  4976.7 1989.51  5018.8 1987.95
  5019.2 1987.45  5023.6 1987.95  5042.3 1988.74  5063.4 1990.84  5124.7 1988.72
  5168.4 1988.75  5213.9 1989.12  5231.8 1990.21  5237.3 1989.55  5255.2 1990.55
  5365.0 1989.47  5533.9 1990.73  5594.4 1992.98  5632.7 1992.09  5742.9 1993.07
#Mann=3,-1,0
  4207.0   0.045       0  5018.8   0.045       0  5023.6   0.045       0
Bank Sta=5018.8,5023.6
Exp/Cntr=0.3,0.1

Type RM Length L Ch R = 1,10035,441,441,441
BEGIN DESCRIPTION:
UCFB HW Trib 04-09 5.0
END DESCRIPTION:
XS GIS Cut Line= 5
      1354830.03      6994813.00      1355507.19      6994866.69
      1355555.00      6994838.00      1355603.72      6994805.96
      1355751.03      6994085.42
#Sta/Elev= 30
  4260.5 1990.01  4295.6 1990.12  4325.7 1988.70  4345.7 1988.32  4436.0 1987.97
  4476.1 1989.11  4517.4 1987.30  4640.9 1987.02  4907.5 1987.02  4936.2 1988.75
  4950.8 1989.02  4972.2 1986.72  5000.7 1985.29  5001.0 1984.79  5005.1 1984.79
  5005.5 1985.29  5031.4 1986.17  5051.6 1988.57  5102.8 1986.73  5136.8 1986.33
  5470.3 1986.56  5551.9 1986.96  5586.0 1987.64  5602.9 1988.94  5631.4 1988.03
  5654.0 1987.88  5732.4 1988.42  5756.0 1988.94  5782.9 1990.56  5789.3 1990.37
#Mann=3,-1,0
  4260.5   0.045       0  5000.7   0.045       0  5005.5   0.045       0
Bank Sta=5000.7,5005.5
Exp/Cntr=0.3,0.1

Type RM Length L Ch R = 1,9594,424,424,424
BEGIN DESCRIPTION:
UCFB HW Trib 04-09 4.0
END DESCRIPTION:
XS GIS Cut Line= 4
      1355700.11      6995197.47      1355805.00      6995188.00
      1355880.09      6995030.48      1355892.74      6994405.32
#Sta/Elev= 30
  4899.5 1986.87  4914.4 1986.36  4924.5 1985.04  4944.4 1983.66  4982.3 1983.31
  4982.7 1982.81  4986.8 1982.81  4987.1 1983.31  4998.0 1983.58  5013.4 1984.02
  5018.9 1984.82  5027.0 1985.52  5036.1 1985.81  5058.8 1985.18  5064.3 1984.81
  5081.5 1984.76  5087.0 1984.36  5132.4 1984.43  5201.8 1984.08  5291.8 1984.48
  5311.8 1984.26  5351.8 1984.56  5411.8 1984.38  5421.8 1984.57  5601.9 1984.61
  5651.9 1984.96  5751.9 1985.01  5771.9 1985.59  5800.7 1987.23  5804.6 1987.23
#Mann=4,-1,0
  4899.5    0.07       0  4982.3   0.045       0  4987.1    0.07       0
  4998.0   0.045       0
Bank Sta=4982.3,4987.1
Exp/Cntr=0.3,0.1

Type RM Length L Ch R = 1,9170,413,413,413
BEGIN DESCRIPTION:
UCFB HW Trib 04-09 3.0
END DESCRIPTION:
XS GIS Cut Line= 4
      1355656.64      6995473.60      1355862.85      6995605.01
      1356051.93      6995522.36      1355907.26      6995178.42
#Sta/Elev= 30
  4603.1 1982.77  4613.0 1983.31  4619.8 1982.76  4684.2 1982.41  4692.6 1983.20
  4698.5 1982.36  4786.5 1981.53  4792.4 1981.13  4807.7 1981.02  4815.4 1981.71
  4860.9 1980.49  4877.4 1981.77  4900.8 1981.01  4915.4 1982.87  4937.3 1980.66
  4956.7 1979.74  4957.1 1979.24  4961.2 1979.24  4961.5 1979.74  4992.1 1979.91
  5005.3 1979.93  5028.7 1981.52  5056.5 1980.49  5061.5 1980.95  5138.2 1981.47
  5238.6 1980.99  5362.5 1981.79  5415.7 1983.14  5421.1 1984.10  5427.1 1984.28
#Mann=5,-1,0
  4603.1    0.16       0  4815.4    0.07       0  4956.7   0.045       0
  4961.5    0.07       0  4992.1   0.045       0
Bank Sta=4956.7,4961.5
Exp/Cntr=0.3,0.1

Type RM Length L Ch R = 1,8757,641,641,641
BEGIN DESCRIPTION:
UCFB HW Trib 04-09 2.0
END DESCRIPTION:
XS GIS Cut Line= 4
      1355774.61      6995892.13      1356080.00      6995963.00
      1356205.00      6995888.00      1356262.93      6995798.37
#Sta/Elev= 30
  4535.2 1980.15  4648.5 1978.47  4667.8 1978.73  4673.0 1978.13  4715.6 1977.98
  4730.6 1978.35  4763.4 1977.74  4785.1 1978.16  4800.9 1978.30  4812.8 1977.45
  4848.7 1977.52  4864.3 1977.04  4922.6 1976.66  4928.4 1977.05  4936.2 1976.75
  4949.8 1978.28  4971.2 1977.26  4997.5 1977.11  5002.4 1977.43  5017.2 1977.53
  5038.3 1976.99  5044.3 1976.44  5053.5 1977.17  5057.1 1976.17  5057.4 1975.67
  5061.5 1975.67  5061.9 1976.17  5065.9 1978.78  5074.6 1979.67  5101.2 1980.06
#Mann=5,-1,0
  4535.2    0.16       0  4785.1    0.07       0  5002.4   0.035       0
  5057.1    0.07       0  5061.9   0.035       0
Bank Sta=5057.1,5061.9
Exp/Cntr=0.3,0.1

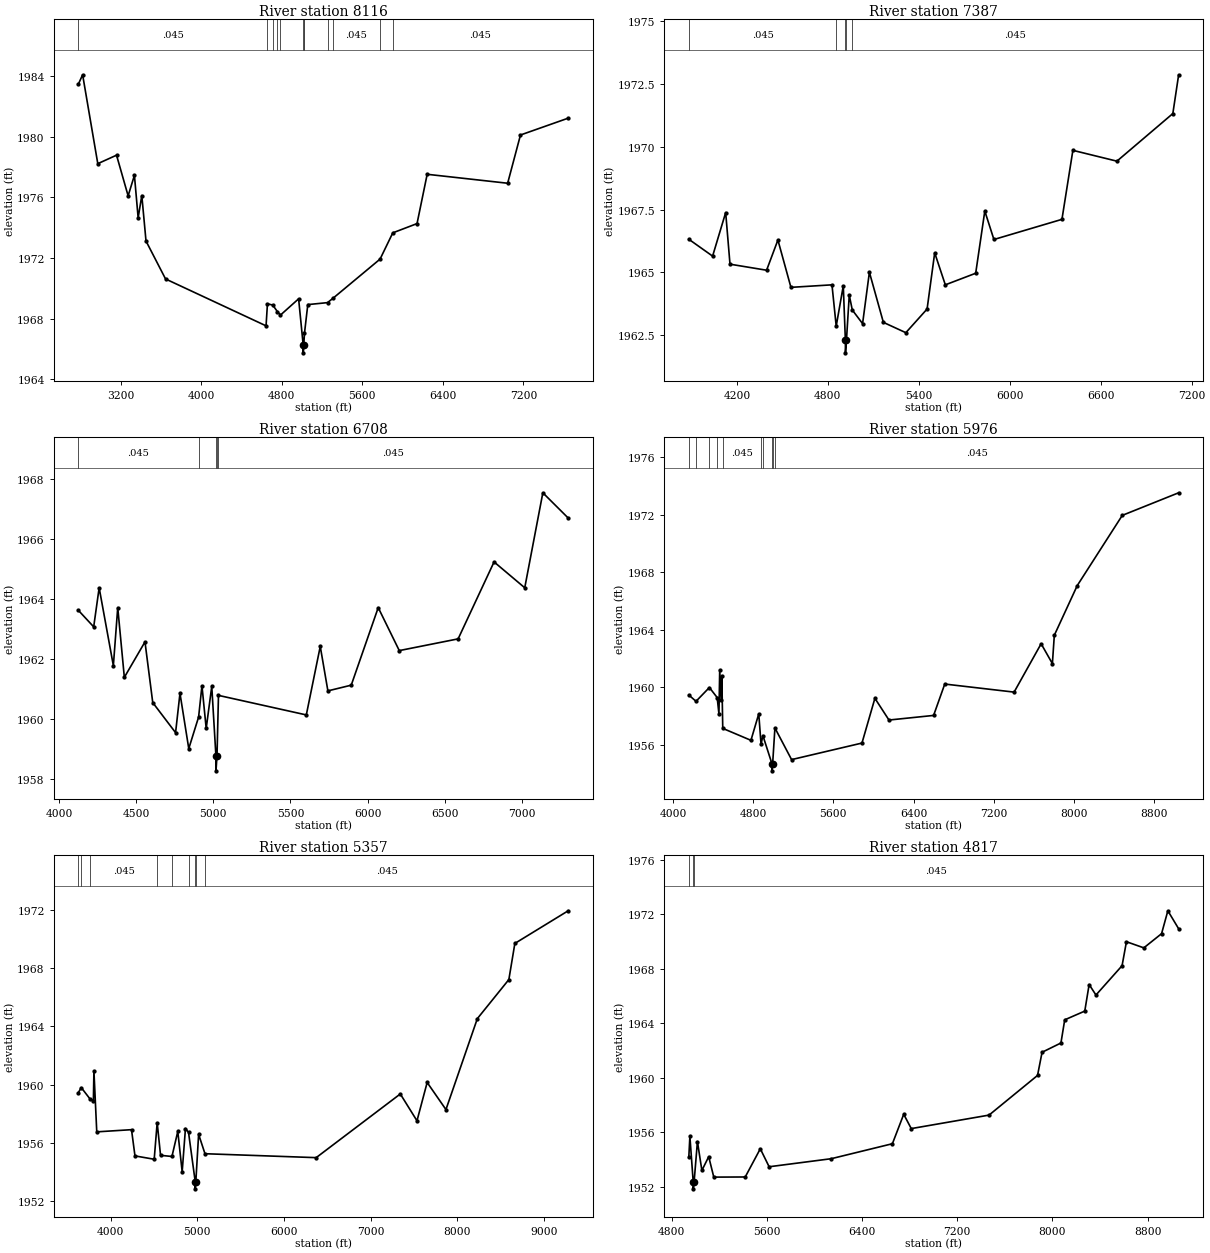
Type RM Length L Ch R = 1,8116,729,729,729
BEGIN DESCRIPTION:
UCFB HW Trib 04-09 1.5
END DESCRIPTION:
XS GIS Cut Line= 4
      1355634.87      6998157.52      1356365.08      6997625.26
      1356688.72      6996201.83      1356993.39      6993717.41
#Sta/Elev= 30
  2778.6 1983.46  2821.1 1984.08  2971.8 1978.22  3158.0 1978.78  3273.1 1976.10
  3335.7 1977.45  3372.7 1974.65  3409.0 1976.12  3450.8 1973.12  3645.0 1970.62
  4643.4 1967.53  4657.2 1968.98  4709.6 1968.90  4757.0 1968.46  4786.6 1968.24
  4966.9 1969.31  5012.6 1966.25  5013.0 1965.75  5017.6 1966.25  5025.3 1967.05
  5058.1 1968.93  5253.9 1969.06  5307.2 1969.34  5776.2 1971.93  5902.4 1973.66
  6143.3 1974.27  6244.0 1977.52  7043.5 1976.93  7170.9 1980.11  7645.0 1981.22
#Mann=12,-1,0
  2778.6   0.045       0  4657.2   0.035       0  4709.6    0.07       0
  4757.0   0.045       0  4786.6    0.07       0  5012.6    0.07       0
  5017.6    0.07       0  5025.3   0.045       0  5253.9    0.07       0
  5307.2   0.045       0  5776.2    0.07       0  5902.4   0.045       0
Bank Sta=5012.6,5017.6
Exp/Cntr=0.3,0.1

Type RM Length L Ch R = 1,7387,679,679,679
BEGIN DESCRIPTION:
UCFB HW Trib 04-09 0.8
END DESCRIPTION:
XS GIS Cut Line= 3
      1356757.54      6997770.84      1357302.86      6996575.33
      1357198.09      6994661.40
#Sta/Elev= 30
  3883.1 1966.32  4040.1 1965.65  4126.3 1967.38  4154.8 1965.33  4396.2 1965.09
  4470.8 1966.29  4556.7 1964.41  4827.4 1964.51  4855.3 1962.87  4902.0 1964.47
  4915.8 1962.31  4916.3 1961.81  4922.9 1962.31  4941.4 1964.10  4961.5 1963.51
  5029.3 1962.97  5074.2 1965.01  5166.4 1963.02  5314.6 1962.61  5454.8 1963.55
  5504.9 1965.78  5575.0 1964.51  5775.3 1964.97  5835.4 1967.44  5895.5 1966.31
  6344.2 1967.11  6416.3 1969.85  6706.7 1969.42  7075.6 1971.31  7113.9 1972.85
#Mann=5,-1,0
  3883.1   0.045       0  4855.3   0.035       0  4915.8   0.045       0
  4922.9   0.035       0  4961.5   0.045       0
Bank Sta=4915.8,4922.9
Exp/Cntr=0.3,0.1

Type RM Length L Ch R = 1,6708,732,732,732
BEGIN DESCRIPTION:
UCFB HW Trib 04-09 0.7
END DESCRIPTION:
XS GIS Cut Line= 3
      1357179.97      6997513.02      1357839.84      6996938.39
      1357624.80      6994647.56
#Sta/Elev= 30
  4125.0 1963.62  4224.5 1963.07  4259.9 1964.37  4352.0 1961.78  4380.4 1963.71
  4423.2 1961.39  4557.0 1962.57  4607.4 1960.55  4755.4 1959.55  4783.9 1960.86
  4840.9 1959.02  4904.7 1960.07  4926.4 1961.11  4953.9 1959.69  4990.0 1961.09
  5016.9 1958.78  5017.4 1958.28  5024.0 1958.78  5033.5 1960.79  5603.0 1960.14
  5693.4 1962.42  5742.9 1960.94  5894.3 1961.13  6069.2 1963.71  6205.7 1962.28
  6587.3 1962.67  6820.3 1965.23  7019.2 1964.37  7136.5 1967.53  7300.9 1966.69
#Mann=5,-1,0
  4125.0   0.045       0  4904.7   0.035       0  5016.9   0.035       0
  5024.0   0.035       0  5033.5   0.045       0
Bank Sta=5016.9,5024
Exp/Cntr=0.3,0.1

Type RM Length L Ch R = 1,5976,619,619,619
BEGIN DESCRIPTION:
UCFB HW Trib 04-09 0.6
END DESCRIPTION:
XS GIS Cut Line= 3
      1357898.35      6997585.98      1358539.78      6997038.52
      1357900.11      6993042.40
#Sta/Elev= 30
  4156.7 1959.46  4228.7 1959.02  4362.2 1959.98  4440.1 1959.28  4457.6 1958.14
  4465.3 1961.20  4479.6 1959.12  4486.2 1960.80  4495.7 1957.14  4777.1 1956.31
  4855.1 1958.15  4878.0 1956.03  4896.3 1956.64  4986.5 1954.69  4987.0 1954.19
  4993.8 1954.69  5016.4 1957.17  5182.8 1954.97  5885.5 1956.12  6014.6 1959.23
  6155.0 1957.72  6600.6 1958.04  6712.0 1960.22  7404.3 1959.66  7674.1 1963.02
  7786.5 1961.64  7805.8 1963.61  8034.5 1967.06  8484.3 1971.94  9047.0 1973.51
#Mann=10,-1,0
  4156.7   0.045       0  4228.7   0.035       0  4362.2   0.045       0
  4440.1   0.035       0  4495.7   0.045       0  4878.0   0.035       0
  4896.3    0.07       0  4986.5    0.07       0  4993.8    0.07       0
  5016.4   0.045       0
Bank Sta=4986.5,4993.8
Exp/Cntr=0.3,0.1

Type RM Length L Ch R = 1,5357,540,540,540
BEGIN DESCRIPTION:
UCFB HW Trib 04-09 0.55
END DESCRIPTION:
XS GIS Cut Line= 3
      1357919.23      6997616.11      1359121.93      6997245.84
      1358040.98      6992992.04
#Sta/Elev= 30
  3628.9 1959.46  3662.3 1959.81  3766.9 1959.00  3802.3 1958.92  3808.5 1960.95
  3841.2 1956.77  4241.8 1956.92  4281.8 1955.12  4503.4 1954.89  4537.7 1957.40
  4576.6 1955.16  4708.0 1955.08  4775.4 1956.80  4825.8 1954.03  4863.7 1957.00
  4899.3 1956.73  4976.1 1953.36  4976.6 1952.86  4983.4 1953.36  5015.5 1956.60
  5088.8 1955.27  6370.8 1955.00  7340.7 1959.37  7533.0 1957.53  7650.3 1960.16
  7866.9 1958.30  8228.9 1964.54  8592.2 1967.22  8661.4 1969.70  9276.3 1971.94
#Mann=9,-1,0
  3628.9   0.045       0  3662.3   0.035       0  3766.9   0.045       0
  4537.7    0.07       0  4708.0   0.035       0  4899.3    0.07       0
  4976.1    0.07       0  4983.4    0.07       0  5088.8   0.045       0
Bank Sta=4976.1,4983.4
Exp/Cntr=0.3,0.1

Type RM Length L Ch R = 1,4817,687,687,687
BEGIN DESCRIPTION:
UCFB HW Trib 04-09 0.5
END DESCRIPTION:
XS GIS Cut Line= 3
      1359455.59      6996806.64      1359437.93      6996754.87
      1358126.89      6992912.17
#Sta/Elev= 30
  4945.3 1954.16  4954.4 1955.70  4982.4 1952.35  4982.9 1951.85  4989.8 1952.35
  5017.8 1955.32  5055.2 1953.20  5112.5 1954.21  5155.2 1952.71  5419.3 1952.72
  5545.9 1954.79  5620.1 1953.47  6141.3 1954.06  6655.6 1955.16  6750.7 1957.32
  6814.0 1956.27  7467.5 1957.26  7874.8 1960.17  7912.9 1961.87  8071.4 1962.55
  8103.1 1964.25  8271.6 1964.89  8308.2 1966.84  8365.6 1966.07  8584.9 1968.22
  8621.6 1969.98  8767.7 1969.53  8916.7 1970.57  8969.5 1972.25  9060.2 1970.93
#Mann=3,-1,0
  4945.3   0.045       0  4982.4   0.045       0  4989.8   0.045       0
Bank Sta=4982.4,4989.8
Exp/Cntr=0.3,0.1

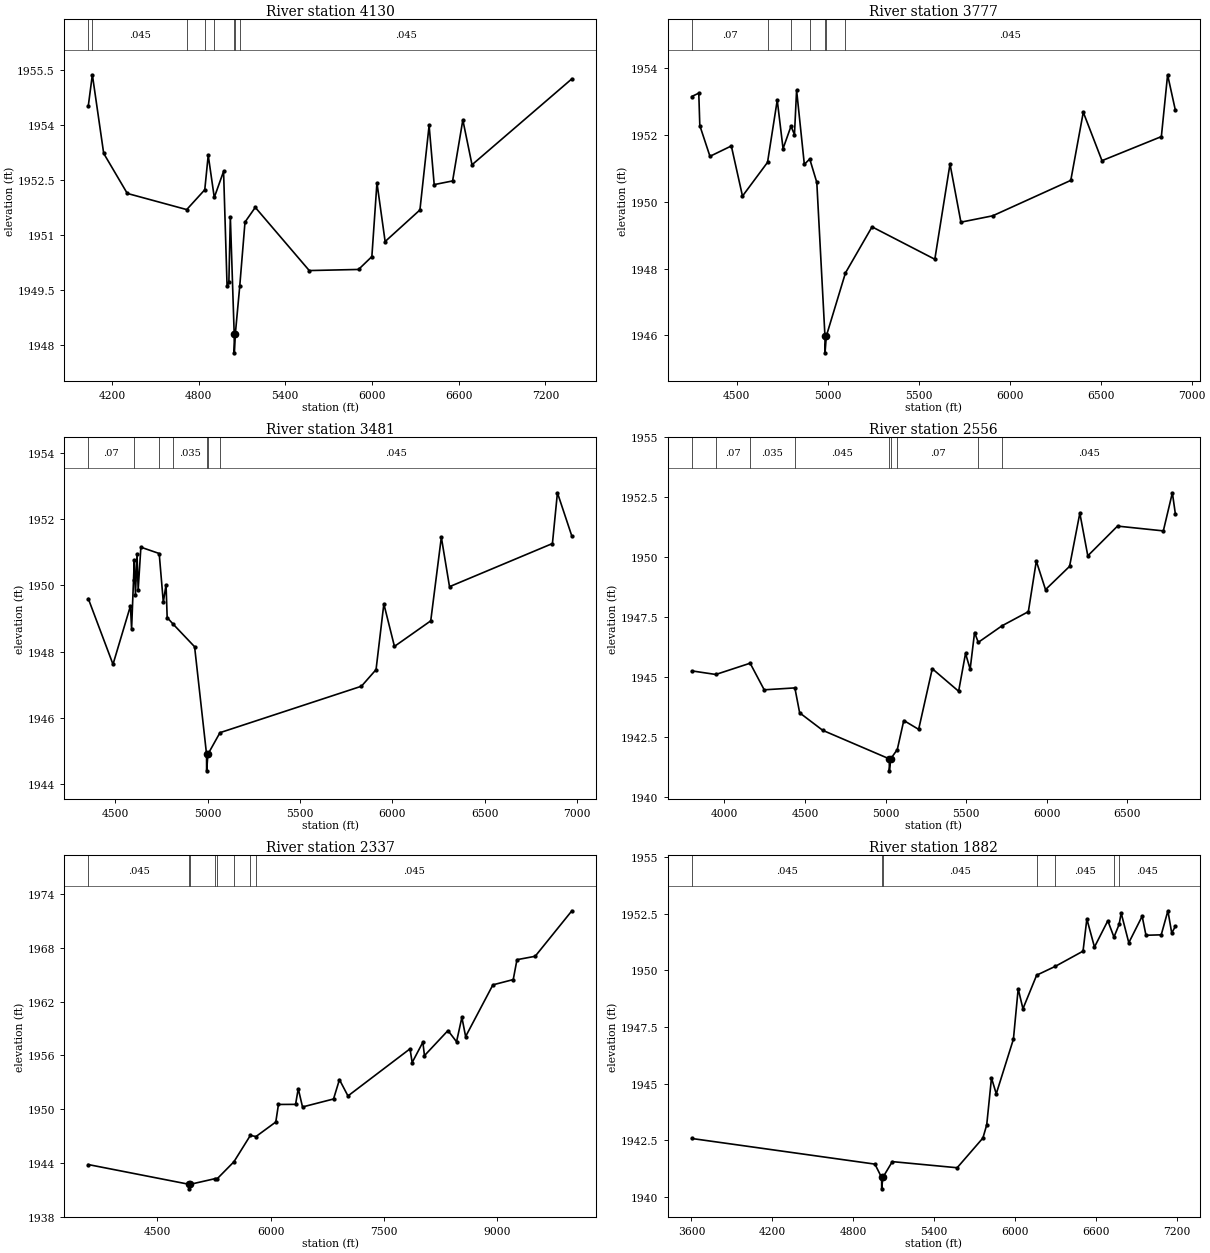
Type RM Length L Ch R = 1,4130,353,353,353
BEGIN DESCRIPTION:
UCFB HW Trib 04-09 0.4
END DESCRIPTION:
XS GIS Cut Line= 4
      1359449.65      6997362.98      1360083.00      6996637.99
      1360235.20      6995757.59      1359212.87      6994673.42
#Sta/Elev= 30
  4037.1 1954.52  4065.3 1955.37  4143.7 1953.23  4306.9 1952.14  4718.2 1951.70
  4843.1 1952.24  4867.0 1953.18  4908.9 1952.03  4973.2 1952.74  4997.5 1949.61
  5009.9 1949.73  5020.1 1951.50  5046.8 1948.30  5047.3 1947.80  5054.2 1948.30
  5085.0 1949.61  5121.5 1951.36  5192.6 1951.76  5566.1 1950.04  5907.1 1950.07
  5999.3 1950.42  6034.5 1952.43  6091.1 1950.83  6331.9 1951.69  6395.4 1953.99
  6430.6 1952.38  6558.0 1952.48  6628.8 1954.14  6692.3 1952.92  7383.4 1955.26
#Mann=8,-1,0
  4037.1   0.035       0  4065.3   0.045       0  4718.2    0.07       0
  4843.1   0.035       0  4908.9    0.07       0  5046.8    0.07       0
  5054.2    0.07       0  5085.0   0.045       0
Bank Sta=5046.8,5054.2
Exp/Cntr=0.3,0.1

Type RM Length L Ch R = 1,3777,296,296,296
BEGIN DESCRIPTION:
UCFB HW Trib 04-09 0.3
END DESCRIPTION:
XS GIS Cut Line= 4
      1360166.99      6997389.66      1360420.30      6996687.98
      1360556.56      6996142.14      1359989.42      6994919.35
#Sta/Elev= 30
  4254.0 1953.15  4292.6 1953.25  4298.3 1952.28  4354.0 1951.36  4471.4 1951.67
  4532.7 1950.17  4670.3 1951.18  4723.6 1953.04  4755.5 1951.59  4799.1 1952.26
  4818.2 1952.01  4829.9 1953.34  4872.4 1951.12  4902.1 1951.28  4940.9 1950.58
  4985.7 1945.98  4986.2 1945.48  4993.1 1945.98  5098.2 1947.87  5244.3 1949.25
  5589.2 1948.28  5672.6 1951.13  5732.5 1949.39  5907.1 1949.58  6336.0 1950.64
  6404.7 1952.68  6507.4 1951.23  6833.6 1951.95  6867.9 1953.80  6910.5 1952.74
#Mann=7,-1,0
  4254.0    0.07       0  4670.3   0.035       0  4799.1    0.16       0
  4902.1   0.035       0  4985.7   0.035       0  4993.1   0.035       0
  5098.2   0.045       0
Bank Sta=4985.7,4993.1
Exp/Cntr=0.3,0.1

Type RM Length L Ch R = 1,3481,925,925,925
BEGIN DESCRIPTION:
UCFB HW Trib 04-09 0.2
END DESCRIPTION:
XS GIS Cut Line= 4
      1360342.75      6997273.00      1360677.80      6996809.26
      1360915.97      6996053.60      1360234.15      6995002.25
#Sta/Elev= 30
  4354.0 1949.60  4487.8 1947.62  4582.2 1949.38  4588.4 1948.68  4598.8 1950.16
  4603.1 1950.77  4609.3 1949.72  4617.8 1950.94  4624.0 1949.87  4638.7 1951.15
  4737.8 1950.96  4760.1 1949.49  4774.8 1950.02  4781.0 1949.03  4811.8 1948.84
  4929.4 1948.15  4994.1 1944.91  4994.6 1944.41  5001.5 1944.91  5066.7 1945.56
  5832.4 1946.96  5911.5 1947.46  5953.7 1949.44  6011.1 1948.16  6207.5 1948.93
  6264.9 1951.45  6309.1 1949.96  6866.1 1951.26  6893.2 1952.79  6971.5 1951.48
#Mann=7,-1,0
  4354.0    0.07       0  4598.8   0.035       0  4737.8    0.16       0
  4811.8   0.035       0  4994.1   0.035       0  5001.5   0.035       0
  5066.7   0.045       0
Bank Sta=4994.1,5001.5
Exp/Cntr=0.3,0.1

Type RM Length L Ch R = 1,2556,219,219,219
BEGIN DESCRIPTION:
UCFB HW Trib 04-09 0.15
END DESCRIPTION:
XS GIS Cut Line= 4
      1360850.86      6997313.31      1361490.40      6996488.75
      1361445.54      6996336.53      1360274.61      6994972.74
#Sta/Elev= 30
  3797.8 1945.26  3947.0 1945.11  4159.9 1945.58  4247.2 1944.47  4437.4 1944.55
  4467.1 1943.51  4610.2 1942.78  5023.0 1941.59  5023.5 1941.09  5031.8 1941.59
  5072.8 1941.98  5113.0 1943.19  5205.2 1942.82  5289.7 1945.35  5453.2 1944.41
  5496.0 1945.99  5524.6 1945.33  5552.0 1946.86  5575.0 1946.45  5722.1 1947.14
  5885.6 1947.73  5935.0 1949.84  5992.1 1948.65  6141.3 1949.62  6205.0 1951.84
  6254.4 1950.06  6438.7 1951.30  6722.9 1951.10  6778.9 1952.69  6797.5 1951.81
#Mann=9,-1,0
  3797.8   0.035       0  3947.0    0.07       0  4159.9   0.035       0
  4437.4   0.045       0  5023.0   0.045       0  5031.8   0.045       0
  5072.8    0.07       0  5575.0   0.035       0  5722.1   0.045       0
Bank Sta=5023,5031.8
Exp/Cntr=0.3,0.1

Type RM Length L Ch R = 1,2337,455,455,455
BEGIN DESCRIPTION:
UCFB HW Trib 04-09 0.1
END DESCRIPTION:
XS GIS Cut Line= 3
      1361128.66      6997403.56      1361791.65      6996417.65
      1358208.81      6992637.33
#Sta/Elev= 30
  3588.4 1943.80  4925.0 1941.59  4925.5 1941.09  4933.8 1941.59  5267.4 1942.23
  5296.2 1942.24  5514.7 1944.11  5731.7 1947.05  5806.8 1946.93  6068.5 1948.55
  6103.7 1950.51  6330.2 1950.52  6365.4 1952.27  6422.0 1950.23  6832.2 1951.12
  6910.3 1953.28  7023.1 1951.46  7843.9 1956.72  7872.2 1955.19  8013.8 1957.46
  8034.8 1955.96  8345.9 1958.76  8459.2 1957.51  8529.9 1960.23  8579.3 1958.09
  8940.1 1963.86  9209.1 1964.45  9258.5 1966.67  9499.2 1967.05  9984.9 1972.13
#Mann=8,-1,0
  3588.4   0.045       0  4925.0   0.045       0  4933.8   0.045       0
  5267.4    0.07       0  5296.2   0.035       0  5514.7    0.07       0
  5731.7   0.035       0  5806.8   0.045       0
Bank Sta=4925,4933.8
Exp/Cntr=0.3,0.1

Type RM Length L Ch R = 1,1882,0,0,0
BEGIN DESCRIPTION:
UCFB HW Trib 04-09 0.05
END DESCRIPTION:
XS GIS Cut Line= 4
      1361830.01      6997462.98      1362153.24      6996339.30
      1362047.79      6996117.50      1360512.54      6994582.26
#Sta/Elev= 30
  3602.6 1942.58  4960.8 1941.45  5010.5 1940.86  5011.0 1940.36  5019.3 1940.86
  5089.8 1941.56  5570.6 1941.29  5761.5 1942.60  5789.8 1943.18  5825.2 1945.25
  5860.5 1944.55  5987.8 1946.96  6023.1 1949.18  6058.5 1948.30  6160.0 1949.78
  6298.5 1950.17  6504.0 1950.84  6532.3 1952.26  6588.8 1951.02  6687.8 1952.18
  6733.3 1951.46  6771.6 1952.02  6786.8 1952.52  6843.4 1951.21  6942.4 1952.38
  6970.7 1951.54  7083.8 1951.56  7133.3 1952.62  7161.6 1951.64  7188.6 1951.93
#Mann=7,-1,0
  3602.6   0.045       0  5010.5   0.045       0  5019.3   0.045       0
  6160.0   0.035       0  6298.5   0.045       0  6733.3   0.035       0
  6771.6   0.045       0
Bank Sta=5010.5,5019.3
Exp/Cntr=0.3,0.1

Chan Stop Cuts=-1