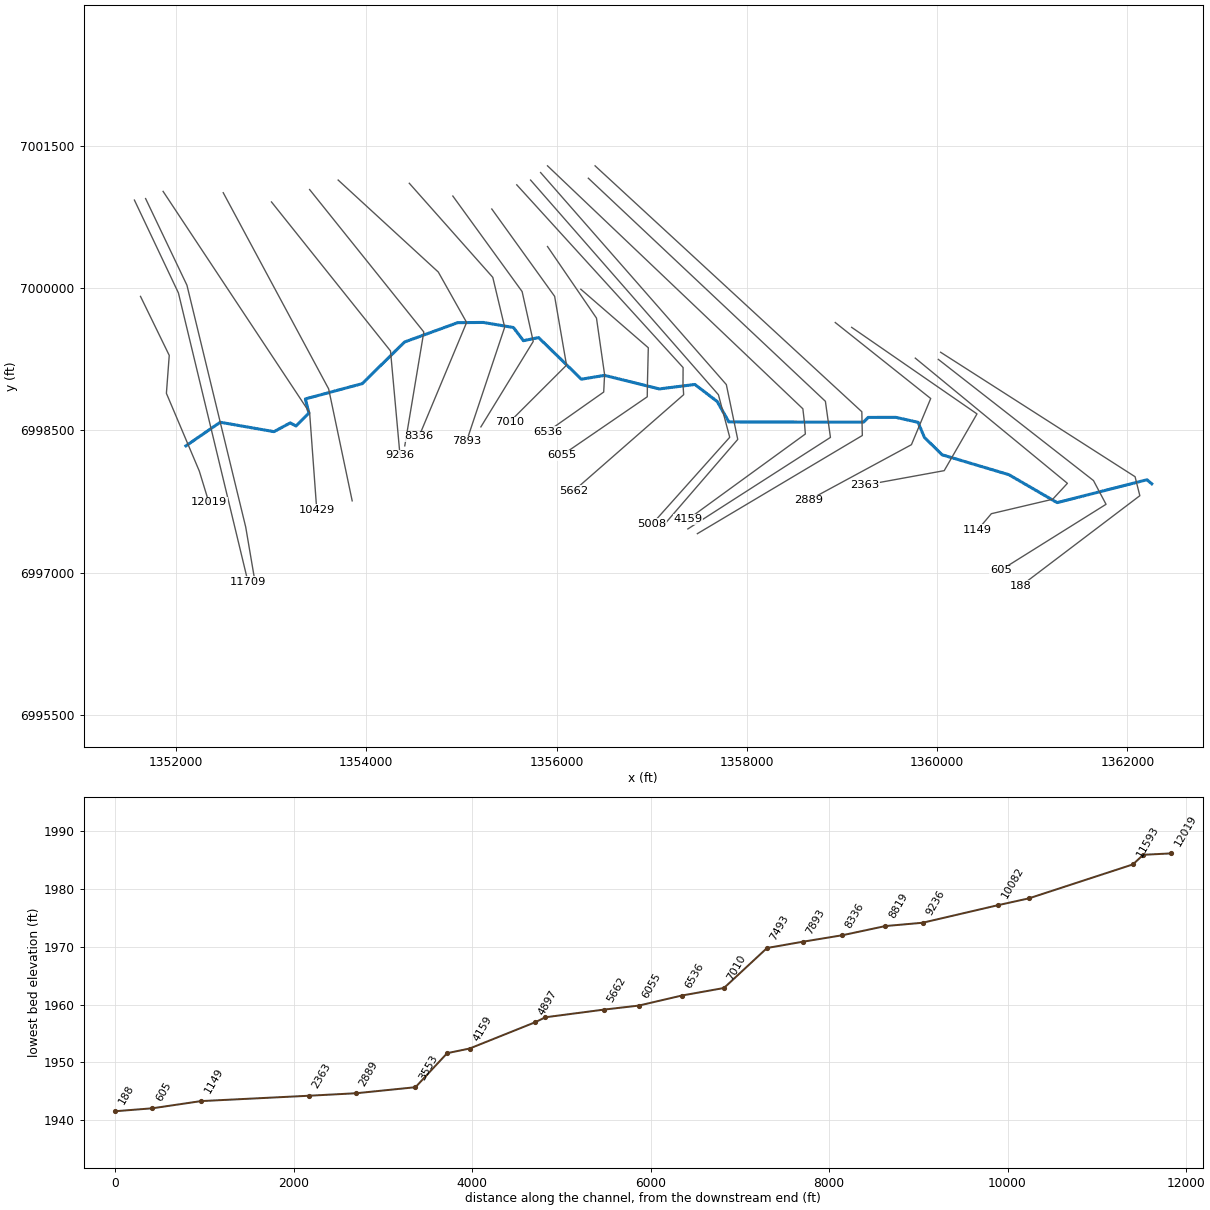
--- UCFB HW Trib 04-10.prj (project) ---

Proj Title=UCFB HW Trib 04-10 Base Level Engineering
Current Plan=p01
Default Exp/Contr=0.3,0.1
English Units
Geom File=g01
Flow File=f01
Plan File=p01
Y Axis Title=Elevation
X Axis Title(PF)=Main Channel Distance
X Axis Title(XS)=Station
BEGIN DESCRIPTION:
UCFB HW Trib 04-10
END DESCRIPTION:
DSS Export Rating Curves= 0
DSS Export Rating Curve Sorted= 0
DSS Export Volume Flow Curves= 0
DXF OffsetX= 0
DXF OffsetY= 0
DXF ScaleX= 1
DXF ScaleY= 10

--- UCFB HW Trib 04-10.p01 (plan) ---

Plan Title=Multiple Run
Short Identifier=Multiple
Geom File=g01
Flow File=f01
Subcritical Flow
K Sum by GR= 0
Std Step Tol= 0.01
Critical Tol= 0.01
Num of Std Step Trials= 20
Max Error Tol= 0.3
Flow Tol Ratio= 0.001
Split Flow NTrial= 30
Split Flow Tol= 0.02
Split Flow Ratio= 0.02
Log Output Level= 0
Friction Slope Method= 1
Unsteady Friction Slope Method= 2
Unsteady Bridges Friction Slope Method= 1
Parabolic Critical Depth
Global Vel Dist=  1 , 1 , 1
Global Log Level= 0
CheckData=True
Encroach Param= -1, 0, 0, 0
BEGIN DESCRIPTION:
Multiple Run
END DESCRIPTION:

--- UCFB HW Trib 04-10.f01 (steady flow) ---

Flow Title=Multiple
Program Version=4.10
Number of Profiles= 7
Profile Names=10-year,25-year,50-year,1pct_min,100-year,1pct_plu,500-year
River Rch & RM=UCFB HW Trib 04-,Reach-1         ,12019
     196     270     330     200     400     798     596
River Rch & RM=UCFB HW Trib 04-,Reach-1         ,10429
     859    1275    1639    1044    2082    4154    3407
Boundary for River Rch & Prof#=UCFB HW Trib 04-,Reach-1         , 1
Up Type= 0
Dn Type= 3
Dn Slope=0.005
Boundary for River Rch & Prof#=UCFB HW Trib 04-,Reach-1         , 2
Up Type= 0
Dn Type= 3
Dn Slope=0.005
Boundary for River Rch & Prof#=UCFB HW Trib 04-,Reach-1         , 3
Up Type= 0
Dn Type= 3
Dn Slope=0.005
Boundary for River Rch & Prof#=UCFB HW Trib 04-,Reach-1         , 4
Up Type= 0
Dn Type= 3
Dn Slope=0.005
Boundary for River Rch & Prof#=UCFB HW Trib 04-,Reach-1         , 5
Up Type= 0
Dn Type= 3
Dn Slope=0.005
Boundary for River Rch & Prof#=UCFB HW Trib 04-,Reach-1         , 6
Up Type= 0
Dn Type= 3
Dn Slope=0.005
Boundary for River Rch & Prof#=UCFB HW Trib 04-,Reach-1         , 7
Up Type= 0
Dn Type= 3
Dn Slope=0.005
DSS Import GetInterval= 0
DSS Import GetPeak= 0
DSS Import FillOption= 0

--- UCFB HW Trib 04-10.g01 (geometry) ---

Geom Title=Existing Conditions

River Reach=UCFB HW Trib 04-,Reach-1
Reach XY= 30
      1352105.00      6998338.00      1352465.50      6998586.81
      1353030.00      6998487.59      1353201.67      6998579.98
      1353261.67      6998547.30      1353397.20      6998684.58
      1353360.10      6998832.56      1353957.68      6998993.40
      1354402.71      6999432.15      1354960.94      6999635.74
      1355230.09      6999638.19      1355546.66      6999584.84
      1355651.65      6999445.98      1355811.67      6999478.71
      1356260.85      6999040.06      1356505.00      6999080.44
      1357079.92      6998937.80      1357453.64      6998984.73
      1357688.70      6998805.13      1357810.84      6998590.05
      1359225.36      6998587.64      1359275.30      6998637.70
      1359565.19      6998638.45      1359799.35      6998586.02
      1359865.52      6998428.22      1360052.70      6998243.83
      1360753.53      6998034.44      1361260.89      6997739.97
      1362205.14      6997981.09      1362255.00      6997938.00

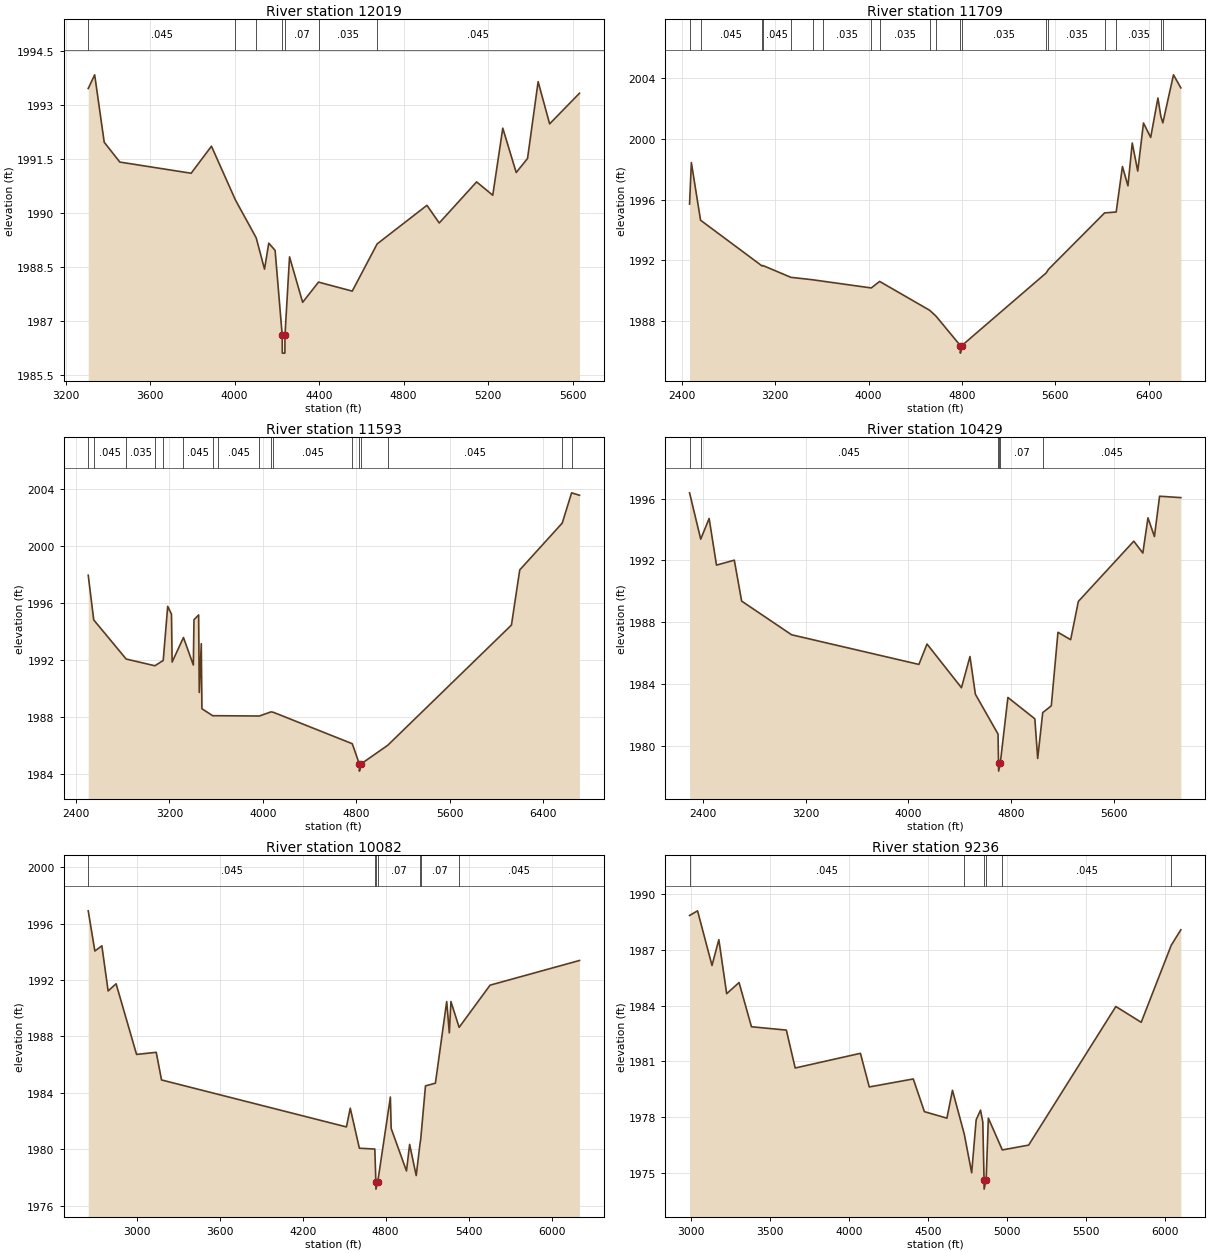
Type RM Length L Ch R = 1,12019,310,310,310
BEGIN DESCRIPTION:
UCFB HW Trib 04-10 15.5
END DESCRIPTION:
XS GIS Cut Line= 5
      1351627.68      6999912.59      1351929.75      6999291.09
      1351899.87      6998891.40      1352245.72      6998072.34
      1352346.33      6997742.77
#Sta/Elev= 30
  3307.2 1993.45  3337.7 1993.83  3382.9 1991.96  3456.8 1991.41  3794.4 1991.10
  3890.5 1991.85  4003.9 1990.36  4102.2 1989.31  4141.7 1988.44  4161.8 1989.16
  4191.8 1988.96  4225.4 1986.61  4225.9 1986.11  4238.1 1986.11  4238.6 1986.61
  4260.1 1988.78  4322.2 1987.52  4397.2 1988.08  4556.9 1987.83  4674.8 1989.14
  4910.5 1990.21  4968.8 1989.72  5145.6 1990.86  5222.1 1990.49  5269.5 1992.35
  5333.1 1991.12  5386.7 1991.51  5436.8 1993.64  5491.3 1992.47  5632.7 1993.32
#Mann=7,-1,0
  3307.2   0.045       0  4003.9   0.035       0  4102.2    0.07       0
  4225.4   0.045       0  4238.6    0.07       0  4397.2   0.035       0
  4674.8   0.045       0
Bank Sta=4225.4,4238.6
Exp/Cntr=0.3,0.1

Type RM Length L Ch R = 1,11709,116,116,116
BEGIN DESCRIPTION:
UCFB HW Trib 04-10 15
END DESCRIPTION:
XS GIS Cut Line= 3
      1351563.63      7000927.26      1352026.10      6999949.07
      1352756.98      6996906.53
#Sta/Elev= 30
  2465.2 1995.70  2480.5 1998.44  2559.4 1994.64  3086.9 1991.62  3093.6 1991.65
  3333.8 1990.87  3520.9 1990.71  3612.4 1990.61  4022.5 1990.17  4094.5 1990.60
  4522.4 1988.70  4576.5 1988.32  4786.1 1986.37  4786.6 1985.87  4799.4 1986.37
  5522.1 1991.16  5540.7 1991.39  6022.8 1995.12  6122.0 1995.18  6175.7 1998.18
  6222.8 1996.91  6259.7 1999.73  6306.8 1997.88  6356.0 2001.05  6417.7 2000.10
  6479.8 2002.70  6504.8 2001.49  6521.9 2001.06  6613.1 2004.23  6676.3 2003.37
#Mann=19,-1,0
  2465.2   0.035       0  2559.4   0.045       0  3086.9   0.035       0
  3093.6   0.045       0  3333.8   0.035       0  3520.9   0.045       0
  3612.4   0.035       0  4022.5    0.07       0  4094.5   0.035       0
  4522.4   0.045       0  4576.5   0.035       0  4786.1   0.035       0
  4799.4   0.035       0  5522.1   0.045       0  5540.7   0.035       0
  6022.8   0.045       0  6122.0   0.035       0  6504.8   0.045       0
  6521.9   0.035       0
Bank Sta=4786.1,4799.4
Exp/Cntr=0.3,0.1

Type RM Length L Ch R = 1,11593,1164,1164,1164
BEGIN DESCRIPTION:
UCFB HW Trib 04-10 14.0
END DESCRIPTION:
XS GIS Cut Line= 4
      1351681.35      7000942.92      1352115.84      7000029.95
      1352733.55      6997482.04      1352830.01      6996912.96
#Sta/Elev= 30
  2504.0 1997.93  2551.2 1994.80  2829.3 1992.06  3074.8 1991.59  3146.6 1991.96
  3185.0 1995.75  3217.5 1995.20  3223.0 1991.85  3320.2 1993.57  3404.7 1991.64
  3410.2 1994.81  3450.1 1995.15  3455.6 1989.72  3472.8 1993.13  3478.4 1988.58
  3570.6 1988.09  3613.3 1988.09  3970.7 1988.07  4070.7 1988.36  4090.6 1988.33
  4766.6 1986.13  4827.5 1984.71  4828.0 1984.21  4840.8 1984.71  5070.6 1986.02
  6130.7 1994.44  6201.8 1998.30  6565.9 2001.58  6646.2 2003.70  6714.0 2003.53
#Mann=17,-1,0
  2504.0   0.035       0  2551.2   0.045       0  2829.3   0.035       0
  3074.8   0.045       0  3146.6   0.035       0  3320.2   0.045       0
  3570.6   0.035       0  3613.3   0.045       0  3970.7    0.07       0
  4070.7   0.035       0  4090.6   0.045       0  4766.6    0.07       0
  4827.5    0.07       0  4840.8    0.07       0  5070.6   0.045       0
  6565.9   0.035       0  6646.2   0.045       0
Bank Sta=4827.5,4840.8
Exp/Cntr=0.3,0.1

Type RM Length L Ch R = 1,10429,347,347,347
BEGIN DESCRIPTION:
UCFB HW Trib 04-10 13.0
END DESCRIPTION:
XS GIS Cut Line= 3
      1351865.20      7001018.69      1353405.00      6998688.00
      1353480.00      6997663.04
#Sta/Elev= 30
  2298.1 1996.37  2384.8 1993.37  2450.3 1994.71  2507.5 1991.69  2646.0 1992.01
  2703.2 1989.36  3091.4 1987.18  4081.7 1985.26  4144.9 1986.58  4412.8 1983.75
  4479.0 1985.77  4521.1 1983.33  4697.2 1980.75  4701.3 1978.85  4701.8 1978.35
  4714.6 1978.85  4774.0 1983.12  4983.6 1981.74  5005.7 1979.17  5044.9 1982.14
  5111.6 1982.58  5163.4 1987.34  5262.0 1986.86  5322.1 1989.34  5753.3 1993.24
  5823.5 1992.47  5863.6 1994.75  5913.7 1993.54  5953.8 1996.15  6119.2 1996.06
#Mann=6,-1,0
  2298.1   0.035       0  2384.8   0.045       0  4697.2    0.07       0
  4701.3    0.07       0  4714.6    0.07       0  5044.9   0.045       0
Bank Sta=4701.3,4714.6
Exp/Cntr=0.3,0.1

Type RM Length L Ch R = 1,10082,846,846,846
BEGIN DESCRIPTION:
UCFB HW Trib 04-10 12.0
END DESCRIPTION:
XS GIS Cut Line= 3
      1352497.16      7001004.78      1353605.00      6998938.00
      1353852.34      6997758.83
#Sta/Elev= 30
  2650.8 1996.90  2698.7 1994.05  2749.3 1994.42  2794.6 1991.22  2852.2 1991.73
  3000.0 1986.72  3142.2 1986.87  3180.4 1984.91  4516.5 1981.58  4544.1 1982.91
  4610.0 1980.07  4721.6 1980.01  4729.2 1977.67  4729.7 1977.17  4742.5 1977.67
  4834.1 1983.70  4839.8 1981.47  4950.4 1978.46  4973.1 1980.34  5020.7 1978.13
  5047.3 1980.33  5053.0 1980.69  5087.7 1984.49  5159.3 1984.68  5241.0 1990.47
  5260.0 1988.25  5271.6 1990.47  5330.8 1988.64  5554.3 1991.63  6200.6 1993.38
#Mann=7,-1,0
  2650.8   0.045       0  4721.6    0.07       0  4729.2    0.07       0
  4742.5    0.07       0  5047.3   0.045       0  5053.0    0.07       0
  5330.8   0.045       0
Bank Sta=4729.2,4742.5
Exp/Cntr=0.3,0.1

Type RM Length L Ch R = 1,9236,417,417,417
BEGIN DESCRIPTION:
UCFB HW Trib 04-10 11.0
END DESCRIPTION:
XS GIS Cut Line= 3
      1353004.12      7000907.54      1354255.00      6999338.00
      1354355.00      6998237.96
#Sta/Elev= 30
  2988.4 1988.86  3039.0 1989.11  3130.5 1986.17  3173.8 1987.56  3223.4 1984.65
  3301.9 1985.25  3380.4 1982.87  3601.4 1982.69  3657.4 1980.65  4070.6 1981.44
  4126.6 1979.63  4405.3 1980.06  4475.8 1978.30  4618.3 1977.95  4653.5 1979.45
  4728.3 1977.09  4775.2 1975.01  4803.6 1977.86  4831.3 1978.38  4845.7 1977.74
  4853.5 1974.63  4854.0 1974.13  4866.8 1974.63  4880.9 1977.95  4969.2 1976.24
  5136.0 1976.50  5688.3 1983.96  5848.9 1983.11  6039.3 1987.26  6100.0 1988.09
#Mann=6,-1,0
  2988.4   0.045       0  4728.3    0.07       0  4853.5   0.045       0
  4866.8    0.07       0  4969.2   0.045       0  6039.3    0.07       0
Bank Sta=4853.5,4866.8
Exp/Cntr=0.3,0.1

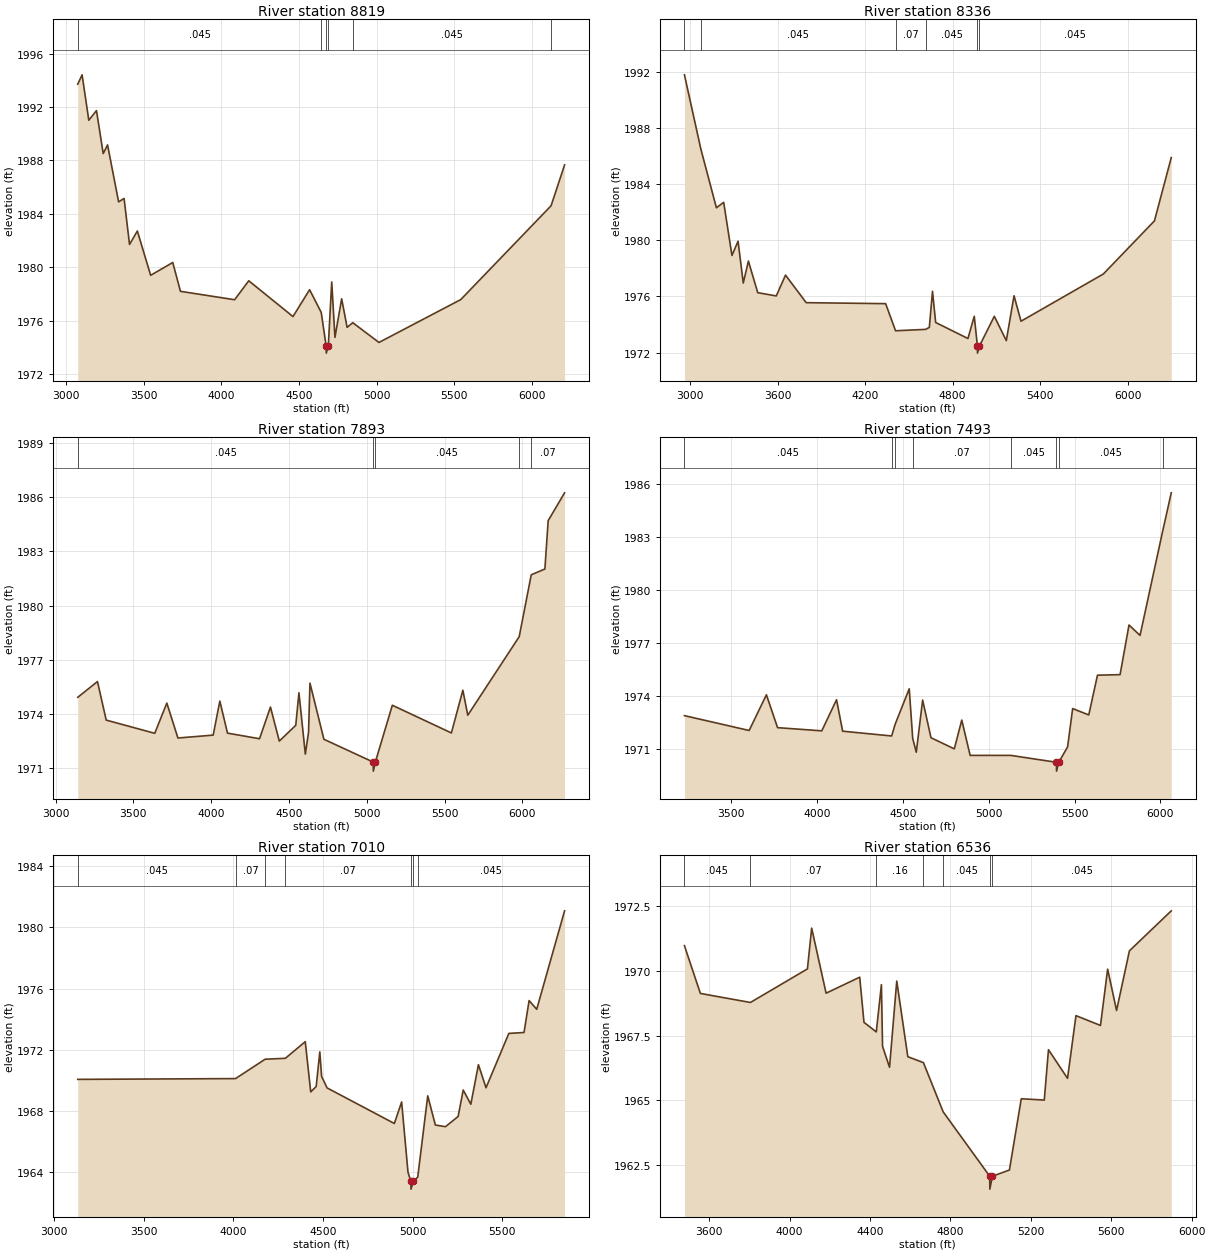
Type RM Length L Ch R = 1,8819,483,483,483
BEGIN DESCRIPTION:
UCFB HW Trib 04-10 10.0
END DESCRIPTION:
XS GIS Cut Line= 3
      1353405.02      7001037.97      1354605.00      6999538.00
      1354404.99      6998337.95
#Sta/Elev= 30
  3074.0 1993.71  3102.0 1994.41  3145.2 1991.01  3194.8 1991.73  3238.0 1988.51
  3266.1 1989.16  3337.3 1984.89  3372.5 1985.15  3407.7 1981.70  3458.1 1982.71
  3543.8 1979.39  3686.3 1980.35  3735.9 1978.19  4084.9 1977.56  4176.1 1978.98
  4461.0 1976.30  4568.3 1978.31  4643.1 1976.61  4675.2 1974.06  4675.7 1973.56
  4688.6 1974.06  4710.8 1978.89  4731.6 1974.74  4774.8 1977.63  4810.0 1975.49
  4846.4 1975.84  5015.2 1974.36  5542.3 1977.57  6124.5 1984.60  6211.5 1987.66
#Mann=6,-1,0
  3074.0   0.045       0  4643.1    0.07       0  4675.2   0.045       0
  4688.6    0.07       0  4846.4   0.045       0  6124.5    0.07       0
Bank Sta=4675.2,4688.6
Exp/Cntr=0.3,0.1

Type RM Length L Ch R = 1,8336,443,443,443
BEGIN DESCRIPTION:
UCFB HW Trib 04-10 9.0
END DESCRIPTION:
XS GIS Cut Line= 4
      1353704.99      7001138.01      1354757.31      7000169.20
      1355055.00      6999638.00      1354555.00      6998438.00
#Sta/Elev= 30
  2960.8 1991.77  3073.1 1986.50  3180.0 1982.31  3229.9 1982.70  3286.6 1978.92
  3328.6 1979.93  3364.3 1976.96  3399.5 1978.52  3463.6 1976.27  3590.6 1976.04
  3654.1 1977.52  3795.9 1975.56  4340.9 1975.49  4408.9 1973.56  4615.4 1973.66
  4640.6 1973.80  4662.3 1976.37  4684.0 1974.15  4905.4 1973.01  4948.7 1974.59
  4970.5 1972.47  4971.0 1971.97  4983.9 1972.47  5086.2 1974.59  5168.6 1972.86
  5221.6 1976.05  5269.3 1974.24  5834.3 1977.60  6184.7 1981.38  6300.1 1985.88
#Mann=6,-1,0
  2960.8    0.07       0  3073.1   0.045       0  4408.9    0.07       0
  4615.4   0.045       0  4970.5   0.045       0  4983.9   0.045       0
Bank Sta=4970.5,4983.9
Exp/Cntr=0.3,0.1

Type RM Length L Ch R = 1,7893,400,400,400
BEGIN DESCRIPTION:
UCFB HW Trib 04-10 8.0
END DESCRIPTION:
XS GIS Cut Line= 4
      1354452.65      7001104.14      1355330.00      7000113.00
      1355455.00      6999588.00      1355054.98      6998387.95
#Sta/Elev= 30
  3142.4 1974.93  3269.1 1975.80  3325.2 1973.67  3637.2 1972.94  3714.9 1974.61
  3786.1 1972.68  4012.7 1972.84  4055.4 1974.72  4104.7 1972.95  4310.5 1972.64
  4380.7 1974.39  4437.6 1972.51  4543.2 1973.38  4563.7 1975.18  4604.8 1971.79
  4625.4 1973.00  4634.6 1975.71  4724.1 1972.61  5041.2 1971.35  5041.7 1970.85
  5054.6 1971.35  5163.9 1974.49  5543.3 1972.96  5617.1 1975.32  5648.7 1973.94
  5979.1 1978.28  6056.5 1981.70  6144.2 1982.02  6165.2 1984.69  6270.7 1986.23
#Mann=5,-1,0
  3142.4   0.045       0  5041.2   0.045       0  5054.6   0.045       0
  5979.1   0.035       0  6056.5    0.07       0
Bank Sta=5041.2,5054.6
Exp/Cntr=0.3,0.1

Type RM Length L Ch R = 1,7493,483,483,483
BEGIN DESCRIPTION:
UCFB HW Trib 04-10 7.0
END DESCRIPTION:
XS GIS Cut Line= 4
      1354910.15      7000969.61      1355638.27      6999963.27
      1355755.00      6999438.00      1355204.98      6998537.97
#Sta/Elev= 30
  3228.3 1972.91  3605.1 1972.07  3705.6 1974.09  3770.6 1972.23  4028.1 1972.05
  4114.0 1973.81  4149.6 1972.03  4434.9 1971.76  4455.6 1972.43  4537.3 1974.43
  4557.6 1971.62  4578.3 1970.84  4615.4 1973.79  4664.1 1971.66  4799.8 1971.03
  4843.3 1972.66  4892.0 1970.66  5129.4 1970.66  5394.7 1970.27  5395.2 1969.77
  5408.1 1970.27  5459.5 1971.14  5489.0 1973.31  5582.8 1972.95  5633.6 1975.20
  5765.2 1975.23  5817.2 1978.04  5881.4 1977.45  6013.4 1983.36  6063.3 1985.52
#Mann=8,-1,0
  3228.3   0.045       0  4434.9    0.07       0  4455.6    0.16       0
  4557.6    0.07       0  5129.4   0.045       0  5394.7    0.07       0
  5408.1   0.045       0  6013.4   0.035       0
Bank Sta=5394.7,5408.1
Exp/Cntr=0.3,0.1

Type RM Length L Ch R = 1,7010,474,474,474
BEGIN DESCRIPTION:
UCFB HW Trib 04-10 6.0
END DESCRIPTION:
XS GIS Cut Line= 4
      1355319.50      7000833.18      1355980.00      6999913.00
      1356105.00      6999188.00      1355505.01      6998588.01
#Sta/Elev= 30
  3131.6 1970.05  4012.1 1970.10  4177.4 1971.37  4290.4 1971.43  4401.3 1972.52
  4431.7 1969.23  4462.2 1969.58  4482.5 1971.85  4492.6 1970.24  4523.1 1969.49
  4898.5 1967.16  4939.1 1968.57  4974.6 1963.97  4990.8 1963.36  4991.3 1962.86
  5004.2 1963.36  5029.0 1963.65  5084.8 1968.97  5127.3 1967.06  5183.8 1966.95
  5254.5 1967.62  5282.8 1969.35  5325.3 1968.42  5367.7 1971.01  5410.1 1969.50
  5537.4 1973.06  5622.2 1973.12  5650.5 1975.21  5693.0 1974.64  5848.5 1981.09
#Mann=7,-1,0
  3131.6   0.045       0  4012.1    0.07       0  4177.4    0.16       0
  4290.4    0.07       0  4990.8    0.07       0  5004.2    0.07       0
  5029.0   0.045       0
Bank Sta=4990.8,5004.2
Exp/Cntr=0.3,0.1

Type RM Length L Ch R = 1,6536,481,481,481
BEGIN DESCRIPTION:
UCFB HW Trib 04-10 5.0
END DESCRIPTION:
XS GIS Cut Line= 5
      1355905.00      7000438.00      1356419.63      6999683.96
      1356505.00      6999088.00      1356495.59      6998904.88
      1355905.02      6998488.02
#Sta/Elev= 30
  3477.4 1970.98  3556.7 1969.13  3805.5 1968.78  4089.1 1970.08  4110.1 1971.66
  4181.9 1969.14  4349.1 1969.76  4370.3 1968.01  4431.5 1967.64  4457.0 1969.47
  4462.7 1967.08  4497.4 1966.27  4533.3 1969.61  4588.3 1966.68  4665.9 1966.45
  4764.4 1964.54  4995.7 1962.05  4996.2 1961.55  5009.1 1962.05  5093.6 1962.29
  5152.6 1965.05  5267.0 1965.00  5287.9 1966.95  5382.7 1965.84  5424.6 1968.27
  5546.5 1967.89  5582.2 1970.07  5626.5 1968.47  5690.5 1970.78  5898.6 1972.33
#Mann=7,-1,0
  3477.4   0.045       0  3805.5    0.07       0  4431.5    0.16       0
  4665.9    0.07       0  4764.4   0.045       0  4995.7   0.045       0
  5009.1   0.045       0
Bank Sta=4995.7,5009.1
Exp/Cntr=0.3,0.1

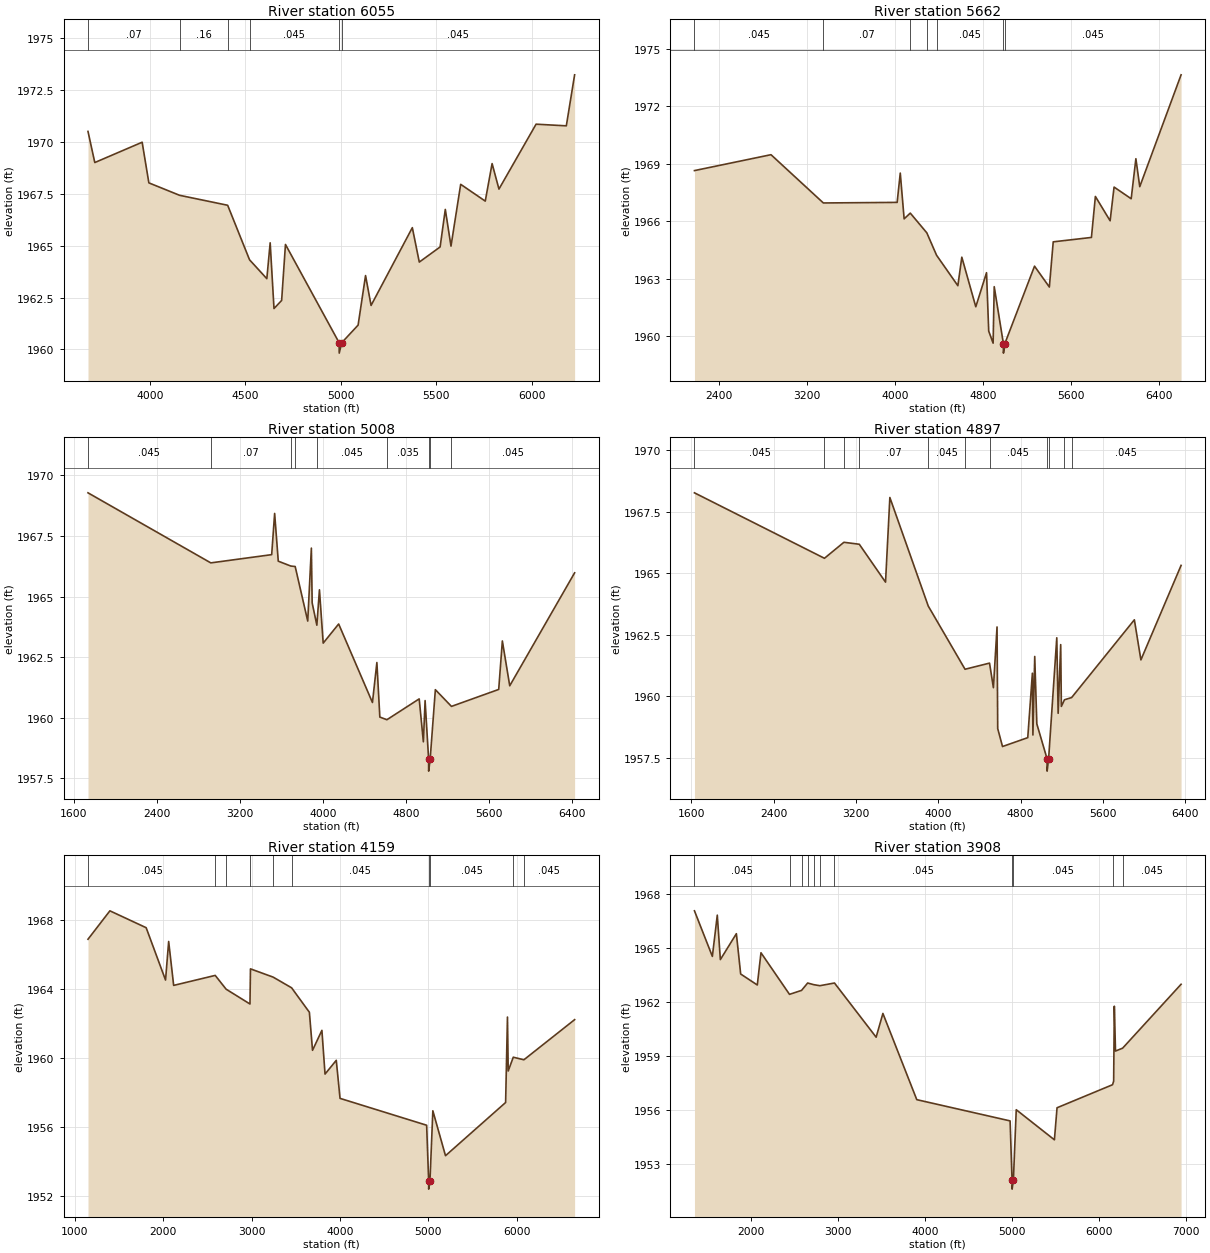
Type RM Length L Ch R = 1,6055,393,393,393
BEGIN DESCRIPTION:
UCFB HW Trib 04-10 4.0
END DESCRIPTION:
XS GIS Cut Line= 5
      1356255.01      6999987.99      1356964.34      6999371.46
      1356955.00      6998988.00      1356953.49      6998854.97
      1356054.96      6998237.97
#Sta/Elev= 30
  3677.0 1970.51  3712.6 1969.01  3960.4 1969.99  3995.5 1968.03  4156.5 1967.43
  4407.9 1966.95  4522.4 1964.32  4612.8 1963.41  4630.3 1965.14  4650.3 1961.97
  4690.3 1962.36  4710.3 1965.06  4991.2 1960.32  4991.7 1959.82  5004.6 1960.32
  5090.4 1961.17  5129.4 1963.56  5158.3 1962.12  5374.2 1965.87  5410.6 1964.21
  5519.6 1964.94  5546.7 1966.75  5576.5 1964.98  5627.2 1967.96  5755.8 1967.15
  5791.6 1968.96  5827.5 1967.73  6021.7 1970.86  6180.0 1970.78  6223.4 1973.24
#Mann=6,-1,0
  3677.0    0.07       0  4156.5    0.16       0  4407.9    0.07       0
  4522.4   0.045       0  4991.2   0.045       0  5004.6   0.045       0
Bank Sta=4991.2,5004.6
Exp/Cntr=0.3,0.1

Type RM Length L Ch R = 1,5662,654,654,654
BEGIN DESCRIPTION:
UCFB HW Trib 04-10 3.0
END DESCRIPTION:
XS GIS Cut Line= 5
      1355581.92      7001087.83      1357330.00      6999163.00
      1357328.92      6998984.74      1357335.87      6998877.10
      1356180.03      6997863.03
#Sta/Elev= 30
  2174.6 1968.65  2870.4 1969.48  3346.4 1966.96  4017.2 1966.99  4045.6 1968.52
  4080.7 1966.13  4136.6 1966.43  4287.0 1965.40  4375.6 1964.23  4569.3 1962.64
  4605.1 1964.13  4732.2 1961.54  4829.7 1963.32  4849.7 1960.27  4889.7 1959.64
  4899.7 1962.59  4983.1 1959.62  4983.6 1959.12  4996.5 1959.62  5266.2 1963.66
  5401.0 1962.57  5436.1 1964.93  5783.4 1965.16  5819.4 1967.30  5953.3 1966.03
  5989.3 1967.79  6144.9 1967.18  6187.6 1969.27  6222.8 1967.81  6598.5 1973.65
#Mann=7,-1,0
  2174.6   0.045       0  3346.4    0.07       0  4136.6    0.16       0
  4287.0    0.07       0  4375.6   0.045       0  4983.1   0.045       0
  4996.5   0.045       0
Bank Sta=4983.1,4996.5
Exp/Cntr=0.3,0.1

Type RM Length L Ch R = 1,5008,111,111,111
BEGIN DESCRIPTION:
UCFB HW Trib 04-10 2.6
END DESCRIPTION:
XS GIS Cut Line= 4
      1355727.12      7001138.08      1357701.44      6998876.40
      1357820.02      6998428.43      1357005.15      6997514.82
#Sta/Elev= 30
  1736.7 1969.28  2920.4 1966.39  3507.0 1966.73  3535.4 1968.43  3570.5 1966.46
  3691.3 1966.26  3733.5 1966.24  3854.4 1963.99  3889.5 1967.00  3897.1 1964.74
  3942.3 1963.82  3967.3 1965.28  4003.4 1963.08  4152.5 1963.87  4478.1 1960.63
  4520.8 1962.28  4549.3 1960.03  4617.3 1959.92  4928.6 1960.78  4968.9 1959.01
  4985.5 1960.71  5019.4 1958.30  5019.9 1957.80  5034.4 1958.30  5084.4 1961.16
  5239.5 1960.47  5695.0 1961.17  5730.1 1963.17  5801.2 1961.32  6426.5 1965.98
#Mann=9,-1,0
  1736.7   0.045       0  2920.4    0.07       0  3691.3    0.16       0
  3733.5    0.07       0  3942.3   0.045       0  4617.3   0.035       0
  5019.4   0.035       0  5034.4   0.035       0  5239.5   0.045       0
Bank Sta=5019.4,5034.4
Exp/Cntr=0.3,0.1

Type RM Length L Ch R = 1,4897,738,738,738
BEGIN DESCRIPTION:
UCFB HW Trib 04-10 2.4
END DESCRIPTION:
XS GIS Cut Line= 4
      1355832.53      7001217.13      1357784.35      6998983.64
      1357904.36      6998406.05      1357136.91      6997514.82
#Sta/Elev= 30
  1629.4 1968.27  2893.5 1965.61  3082.8 1966.26  3232.3 1966.18  3487.5 1964.64
  3529.6 1968.08  3902.8 1963.67  4260.7 1961.10  4498.8 1961.35  4536.6 1960.35
  4571.8 1962.82  4578.4 1958.69  4625.1 1957.96  4870.6 1958.32  4915.6 1960.94
  4920.7 1958.43  4938.4 1961.62  4958.8 1958.88  5058.4 1957.46  5058.9 1956.96
  5073.4 1957.46  5152.8 1962.38  5166.1 1959.31  5190.8 1962.10  5197.4 1959.59
  5227.7 1959.86  5297.2 1959.95  5907.3 1963.11  5970.9 1961.48  6361.6 1965.32
#Mann=11,-1,0
  1629.4   0.045       0  2893.5    0.07       0  3082.8    0.16       0
  3232.3    0.07       0  3902.8   0.045       0  4260.7   0.035       0
  4498.8   0.045       0  5058.4   0.045       0  5073.4   0.045       0
  5227.7   0.035       0  5297.2   0.045       0
Bank Sta=5058.4,5073.4
Exp/Cntr=0.3,0.1

Type RM Length L Ch R = 1,4159,251,251,251
BEGIN DESCRIPTION:
UCFB HW Trib 04-10 2.0
END DESCRIPTION:
XS GIS Cut Line= 5
      1355905.00      7001288.00      1358588.71      6998728.52
      1358605.00      6998588.00      1358614.75      6998462.89
      1357379.97      6997562.98
#Sta/Elev= 30
  1150.0 1966.91  1397.7 1968.56  1807.8 1967.58  2027.0 1964.54  2062.3 1966.78
  2118.9 1964.23  2588.9 1964.81  2712.0 1964.01  2981.9 1963.15  2987.5 1965.19
  3244.1 1964.71  3452.7 1964.09  3653.8 1962.67  3689.3 1960.46  3795.3 1961.62
  3830.8 1959.08  3957.9 1959.88  4000.4 1957.67  4979.9 1956.11  5002.5 1952.90
  5003.0 1952.40  5017.6 1952.90  5050.1 1956.95  5193.2 1954.34  5873.1 1957.43
  5893.9 1962.39  5902.4 1959.26  5959.7 1960.06  6079.7 1959.91  6653.4 1962.24
#Mann=10,-1,0
  1150.0   0.045       0  2588.9    0.07       0  2712.0    0.16       0
  2987.5    0.07       0  3244.1   0.035       0  3452.7   0.045       0
  5002.5   0.045       0  5017.6   0.045       0  5959.7   0.035       0
  6079.7   0.045       0
Bank Sta=5002.5,5017.6
Exp/Cntr=0.3,0.1

Type RM Length L Ch R = 1,3908,355,355,355
BEGIN DESCRIPTION:
UCFB HW Trib 04-10 1.2
END DESCRIPTION:
XS GIS Cut Line= 4
      1356334.02      7001157.48      1358825.50      6998807.44
      1358878.49      6998427.18      1357379.96      6997462.97
#Sta/Elev= 30
  1353.5 1967.06  1559.1 1964.53  1615.8 1966.82  1651.0 1964.35  1835.0 1965.79
  1884.4 1963.55  2075.4 1962.94  2117.8 1964.73  2445.4 1962.42  2583.9 1962.64
  2654.0 1963.05  2722.4 1962.96  2794.0 1962.90  2962.2 1963.05  3440.8 1960.04
  3518.5 1961.36  3907.7 1956.57  4979.8 1955.39  5002.5 1952.10  5003.0 1951.60
  5017.6 1952.10  5050.5 1956.01  5488.9 1954.34  5519.3 1956.12  6157.0 1957.40
  6169.7 1957.60  6177.3 1961.76  6190.8 1959.27  6272.6 1959.43  6944.3 1962.98
#Mann=11,-1,0
  1353.5   0.045       0  2445.4    0.07       0  2583.9    0.16       0
  2654.0   0.035       0  2722.4    0.16       0  2794.0   0.035       0
  2962.2   0.045       0  5002.5   0.045       0  5017.6   0.045       0
  6157.0   0.035       0  6272.6   0.045       0
Bank Sta=5002.5,5017.6
Exp/Cntr=0.3,0.1

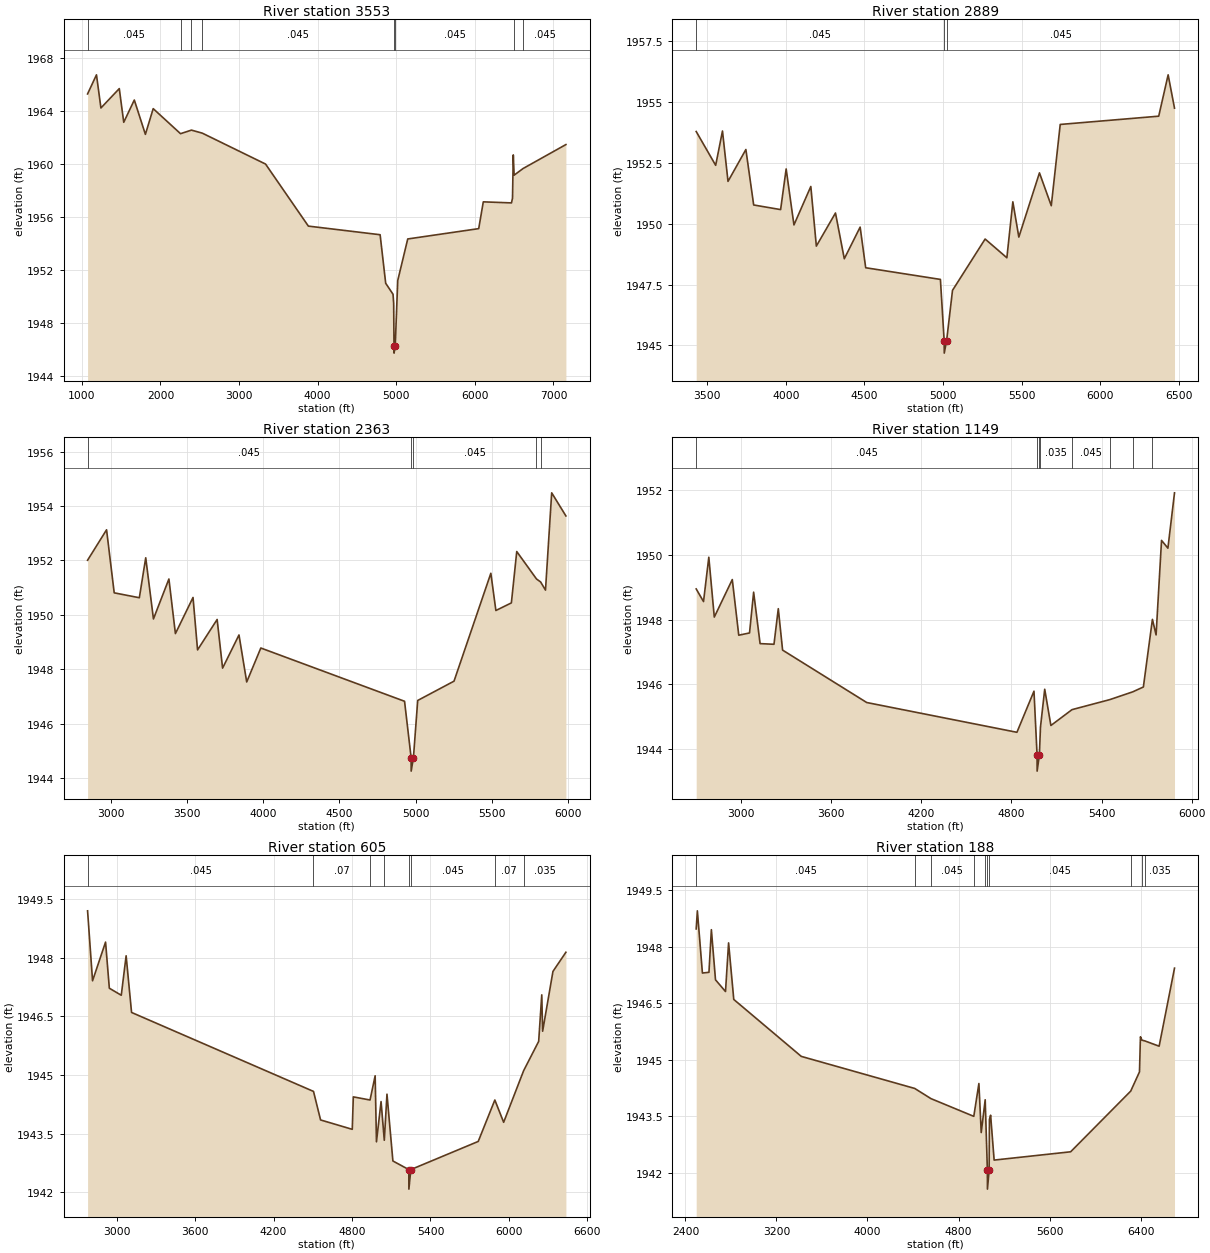
Type RM Length L Ch R = 1,3553,664,664,664
BEGIN DESCRIPTION:
UCFB HW Trib 04-10 1.0
END DESCRIPTION:
XS GIS Cut Line= 5
      1356405.00      7001288.00      1359208.50      6998697.27
      1359210.54      6998587.46      1359213.71      6998447.27
      1357480.01      6997413.00
#Sta/Elev= 30
  1072.9 1965.27  1186.0 1966.71  1242.7 1964.21  1476.3 1965.67  1533.0 1963.13
  1667.4 1964.81  1808.6 1962.22  1907.8 1964.16  2255.7 1962.27  2394.3 1962.54
  2532.9 1962.31  3337.3 1959.98  3882.2 1955.30  4795.1 1954.65  4866.0 1950.99
  4959.5 1950.16  4967.7 1949.45  4971.9 1946.22  4972.4 1945.72  4987.0 1946.22
  5019.5 1951.20  5146.6 1954.33  6049.6 1955.11  6108.0 1957.13  6466.2 1957.05
  6479.7 1957.40  6489.5 1960.67  6499.9 1959.14  6613.3 1959.64  7159.0 1961.45
#Mann=8,-1,0
  1072.9   0.045       0  2255.7   0.035       0  2394.3    0.16       0
  2532.9   0.045       0  4971.9   0.045       0  4987.0   0.045       0
  6499.9   0.035       0  6613.3   0.045       0
Bank Sta=4971.9,4987
Exp/Cntr=0.3,0.1

Type RM Length L Ch R = 1,2889,526,526,526
BEGIN DESCRIPTION:
UCFB HW Trib 04-10 0.9
END DESCRIPTION:
XS GIS Cut Line= 4
      1358929.22      6999637.18      1359932.27      6998836.76
      1359729.64      6998350.44      1358645.74      6997762.91
#Sta/Elev= 30
  3429.9 1953.79  3553.8 1952.40  3597.1 1953.81  3632.3 1951.74  3746.0 1953.05
  3795.6 1950.77  3967.0 1950.58  4002.2 1952.25  4051.8 1949.95  4159.1 1951.53
  4194.3 1949.08  4316.0 1950.44  4372.1 1948.56  4472.9 1949.86  4508.2 1948.19
  4983.6 1947.71  5007.5 1945.18  5008.0 1944.68  5022.8 1945.18  5060.5 1947.26
  5268.0 1949.37  5406.4 1948.60  5444.4 1950.90  5482.5 1949.45  5613.7 1952.09
  5688.9 1950.74  5745.8 1954.08  6372.4 1954.42  6432.3 1956.12  6472.9 1954.75
#Mann=3,-1,0
  3429.9   0.045       0  5007.5   0.045       0  5022.8   0.045       0
Bank Sta=5007.5,5022.8
Exp/Cntr=0.3,0.1

Type RM Length L Ch R = 1,2363,1214,1214,1214
BEGIN DESCRIPTION:
UCFB HW Trib 04-10 0.8
END DESCRIPTION:
XS GIS Cut Line= 4
      1359101.47      6999586.50      1360418.59      6998674.66
      1360074.11      6998076.89      1359243.36      6997924.92
#Sta/Elev= 30
  2849.5 1952.01  2974.0 1953.13  3024.1 1950.81  3188.9 1950.63  3230.8 1952.10
  3281.4 1949.85  3382.8 1951.32  3425.4 1949.31  3540.9 1950.64  3570.6 1948.71
  3699.0 1949.83  3734.8 1948.04  3842.3 1949.26  3892.9 1947.53  3985.5 1948.78
  4927.9 1946.82  4970.9 1944.75  4971.4 1944.25  4986.2 1944.75  5014.2 1946.85
  5252.3 1947.56  5493.8 1951.53  5526.8 1950.16  5628.4 1950.44  5663.6 1952.33
  5793.1 1951.32  5820.2 1951.21  5852.1 1950.91  5892.7 1954.49  5985.9 1953.64
#Mann=5,-1,0
  2849.5   0.045       0  4970.9   0.045       0  4986.2   0.045       0
  5793.1    0.07       0  5820.2   0.045       0
Bank Sta=4970.9,4986.2
Exp/Cntr=0.3,0.1

Type RM Length L Ch R = 1,1149,544,544,544
BEGIN DESCRIPTION:
UCFB HW Trib 04-10 0.7
END DESCRIPTION:
XS GIS Cut Line= 5
      1359770.17      6999262.28      1361368.85      6997943.40
      1361214.48      6997775.73      1360569.62      6997623.48
      1360426.34      6997454.43
#Sta/Elev= 30
  2701.3 1948.95  2750.1 1948.56  2785.3 1949.93  2821.8 1948.08  2941.6 1949.24
  2984.7 1947.52  3056.4 1947.59  3083.7 1948.85  3126.7 1947.26  3219.2 1947.24
  3247.9 1948.34  3276.5 1947.06  3836.7 1945.44  4836.7 1944.52  4950.2 1945.79
  4970.8 1943.82  4971.3 1943.32  4986.2 1943.82  4993.5 1944.68  5021.7 1945.85
  5062.8 1944.73  5203.4 1945.22  5455.3 1945.53  5607.7 1945.77  5678.6 1945.92
  5738.8 1948.01  5763.2 1947.53  5799.5 1950.45  5841.9 1950.21  5885.9 1951.92
#Mann=8,-1,0
  2701.3   0.045       0  4970.8   0.035       0  4986.2   0.045       0
  4993.5   0.035       0  5203.4   0.045       0  5455.3   0.035       0
  5607.7   0.045       0  5738.8   0.063       0
Bank Sta=4970.8,4986.2
Exp/Cntr=0.3,0.1

Type RM Length L Ch R = 1,605,417,417,417
BEGIN DESCRIPTION:
UCFB HW Trib 04-10 0.5
END DESCRIPTION:
XS GIS Cut Line= 4
      1360012.87      6999248.60      1361642.93      6997972.41
      1361774.87      6997722.41      1360668.61      6997028.83
#Sta/Elev= 30
  2777.4 1949.20  2815.4 1947.41  2914.9 1948.40  2943.8 1947.22  3035.1 1947.04
  3072.2 1948.05  3113.8 1946.60  4505.4 1944.58  4559.6 1943.85  4801.9 1943.61
  4810.0 1944.44  4937.9 1944.36  4977.0 1944.98  4987.0 1943.29  5022.2 1944.32
  5047.0 1943.33  5067.4 1944.51  5112.7 1942.80  5234.5 1942.58  5235.0 1942.08
  5249.9 1942.58  5765.4 1943.30  5892.5 1944.36  5959.9 1943.79  6112.7 1945.11
  6227.8 1945.86  6251.4 1947.05  6258.0 1946.12  6337.0 1947.65  6436.0 1948.14
#Mann=8,-1,0
  2777.4   0.045       0  4505.4    0.07       0  4937.9   0.035       0
  5047.0   0.045       0  5234.5   0.035       0  5249.9   0.045       0
  5892.5    0.07       0  6112.7   0.035       0
Bank Sta=5234.5,5249.9
Exp/Cntr=0.3,0.1

Type RM Length L Ch R = 1,188,0,0,0
BEGIN DESCRIPTION:
UCFB HW Trib 04-10 0.6
END DESCRIPTION:
XS GIS Cut Line= 4
      1360036.33      6999324.10      1362080.00      6998013.00
      1362130.00      6997813.00      1360879.97      6996862.98
#Sta/Elev= 30
  2494.4 1948.47  2504.7 1948.95  2549.1 1947.30  2606.6 1947.32  2627.8 1948.45
  2664.1 1947.12  2752.0 1946.81  2779.1 1948.10  2824.7 1946.60  3418.0 1945.09
  4415.1 1944.24  4558.0 1943.97  4934.4 1943.50  4979.2 1944.37  4999.8 1943.07
  5034.6 1943.94  5053.9 1942.07  5054.4 1941.57  5069.3 1942.07  5071.9 1943.42
  5082.3 1943.53  5113.2 1942.34  5785.7 1942.56  6313.9 1944.17  6390.9 1944.68
  6399.2 1945.61  6412.6 1945.52  6438.3 1945.50  6563.5 1945.36  6698.7 1947.43
#Mann=10,-1,0
  2494.4   0.045       0  4415.1    0.07       0  4558.0   0.045       0
  4934.4   0.035       0  5034.6   0.045       0  5053.9   0.035       0
  5069.3   0.045       0  6313.9   0.035       0  6412.6    0.07       0
  6438.3   0.035       0
Bank Sta=5053.9,5069.3
Exp/Cntr=0.3,0.1

Chan Stop Cuts=-1