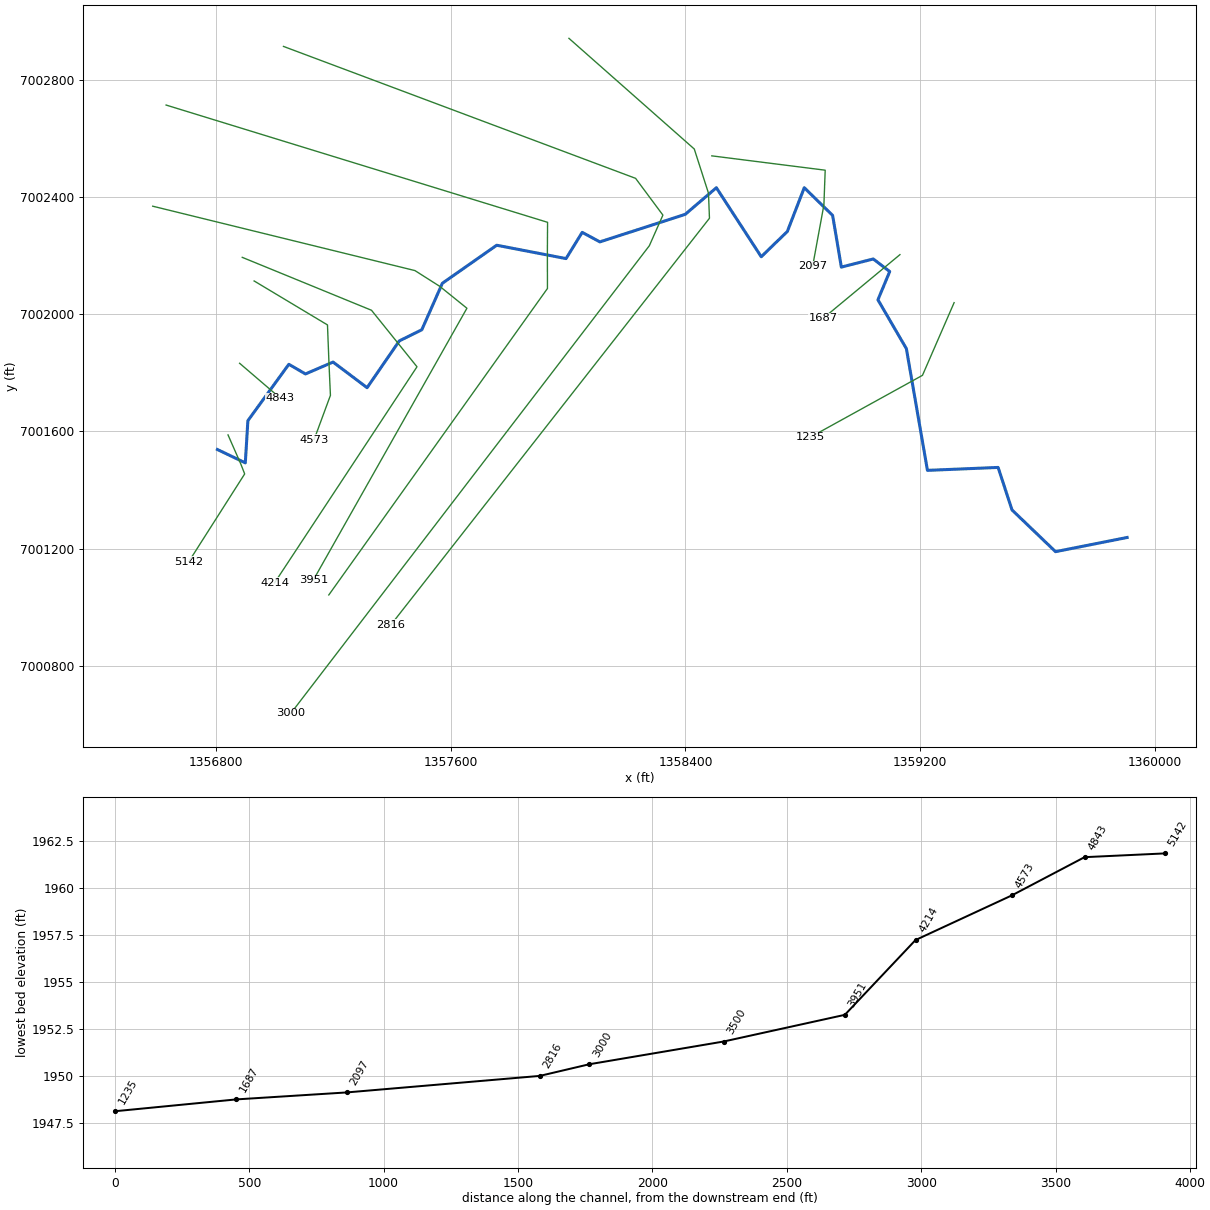
--- UCFB HW Trib 04-12.prj (project) ---

Proj Title=UCFB HW Trib 04-12 Base Level Engineering
Current Plan=p01
Default Exp/Contr=0.3,0.1
English Units
Geom File=g01
Flow File=f01
Plan File=p01
BEGIN DESCRIPTION:
UCFB HW Trib 04-12
END DESCRIPTION:

--- UCFB HW Trib 04-12.p01 (plan) ---

Plan Title=Multiple Run
Short Identifier=Multiple
Geom File=g01
Flow File=f01
Subcritical Flow
K Sum by GR= 0
Std Step Tol= 0.01
Critical Tol= 0.01
Num of Std Step Trials= 20
Max Error Tol= 0.3
Flow Tol Ratio= 0.001
Split Flow NTrial= 30
Split Flow Tol= 0.02
Split Flow Ratio= 0.02
Log Output Level= 0
Friction Slope Method= 1
Unsteady Friction Slope Method= 2
Unsteady Bridges Friction Slope Method= 1
Parabolic Critical Depth
Global Vel Dist=  1 , 1 , 1
Global Log Level= 0
CheckData=True
Encroach Param= -1, 0, 0, 0
BEGIN DESCRIPTION:
Multiple Run
END DESCRIPTION:

--- UCFB HW Trib 04-12.f01 (steady flow) ---

Flow Title=Multiple
Number of Profiles=7
Profile Names=10-year,25-year,50-year,1pct_min,100-year,1pct_plu,500-year
River Rch & RM= UCFB HW Trib 04-,Reach-1,5142
     133     177     212     126     252     502     359
Boundary for River Rch & Prof#=UCFB HW Trib 04-,Reach-1,1
Up Type=0
Dn Type=3
Dn Slope=0.005
Boundary for River Rch & Prof#=UCFB HW Trib 04-,Reach-1,2
Up Type=0
Dn Type=3
Dn Slope=0.005
Boundary for River Rch & Prof#=UCFB HW Trib 04-,Reach-1,3
Up Type=0
Dn Type=3
Dn Slope=0.005
Boundary for River Rch & Prof#=UCFB HW Trib 04-,Reach-1,4
Up Type=0
Dn Type=3
Dn Slope=0.005
Boundary for River Rch & Prof#=UCFB HW Trib 04-,Reach-1,5
Up Type=0
Dn Type=3
Dn Slope=0.005
Boundary for River Rch & Prof#=UCFB HW Trib 04-,Reach-1,6
Up Type=0
Dn Type=3
Dn Slope=0.005
Boundary for River Rch & Prof#=UCFB HW Trib 04-,Reach-1,7
Up Type=0
Dn Type=3
Dn Slope=0.005

--- UCFB HW Trib 04-12.g01 (geometry) ---

Geom Title=Existing Conditions

River Reach=UCFB HW Trib 04-,Reach-1
Reach XY= 30
      1356805.00      7001538.00      1356899.97      7001492.50
      1356908.76      7001636.44      1357048.31      7001828.71
      1357104.91      7001795.84      1357198.95      7001836.33
      1357315.02      7001748.95      1357424.73      7001908.43
      1357501.46      7001946.49      1357571.49      7002105.05
      1357756.65      7002234.83      1357992.97      7002189.26
      1358048.07      7002278.77      1358108.21      7002246.29
      1358399.11      7002340.17      1358505.22      7002431.01
      1358658.17      7002195.50      1358747.14      7002281.79
      1358804.77      7002431.03      1358901.46      7002336.56
      1358931.14      7002160.25      1359039.91      7002187.99
      1359095.97      7002145.11      1359055.80      7002048.71
      1359152.76      7001882.07      1359224.59      7001466.90
      1359465.37      7001476.92      1359512.86      7001331.83
      1359661.03      7001189.62      1359905.00      7001238.00

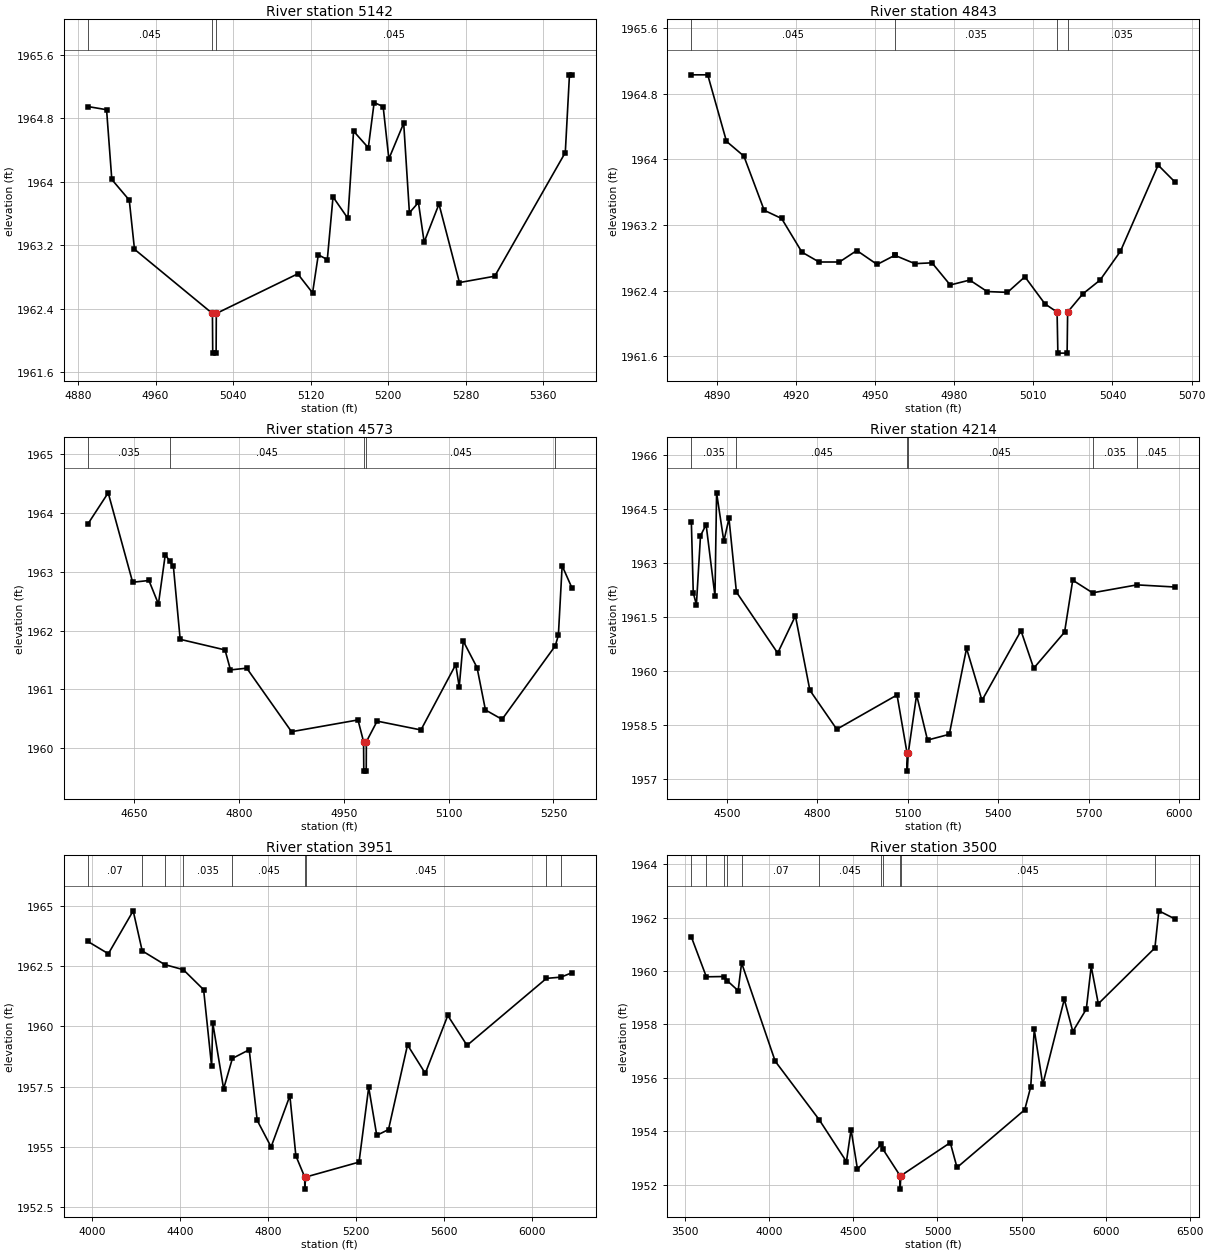
Type RM Length L Ch R = 1,5142,299,299,299
BEGIN DESCRIPTION:
UCFB HW Trib 04-12 10.0
END DESCRIPTION:
XS GIS Cut Line= 4
      1356841.03      7001587.88      1356885.15      7001487.34
      1356897.79      7001454.74      1356707.47      7001155.73
#Sta/Elev= 30
  4890.2 1964.95  4909.5 1964.91  4914.9 1964.03  4932.9 1963.77  4938.3 1963.15
  5018.7 1962.34  5019.0 1961.84  5022.5 1961.84  5022.7 1962.34  5106.7 1962.84
  5122.0 1962.60  5127.9 1963.08  5137.2 1963.02  5143.1 1963.81  5158.4 1963.54
  5164.3 1964.64  5179.5 1964.43  5185.5 1965.00  5194.8 1964.95  5200.7 1964.29
  5216.0 1964.74  5221.9 1963.61  5231.2 1963.74  5237.1 1963.24  5252.4 1963.72
  5273.5 1962.73  5309.9 1962.81  5382.7 1964.37  5387.0 1965.35  5389.4 1965.35
#Mann=3,-1,0
  4890.2   0.045       0  5018.7   0.045       0  5022.7   0.045       0
Bank Sta=5018.7,5022.7
Exp/Cntr=0.3,0.1

Type RM Length L Ch R = 1,4843,270,270,270
BEGIN DESCRIPTION:
UCFB HW Trib 04-12 9.5
END DESCRIPTION:
XS GIS Cut Line= 2
      1356880.52      7001832.22      1357019.71      7001712.80
#Sta/Elev= 30
  4880.4 1965.03  4886.6 1965.03  4893.7 1964.22  4900.3 1964.04  4908.0 1963.38
  4914.6 1963.28  4922.3 1962.87  4928.8 1962.75  4936.5 1962.75  4943.1 1962.89
  4950.8 1962.72  4957.4 1962.83  4957.6 1962.83  4965.1 1962.73  4971.6 1962.74
  4978.5 1962.47  4985.9 1962.53  4992.5 1962.39  5000.2 1962.38  5006.8 1962.57
  5014.4 1962.24  5019.0 1962.14  5019.3 1961.64  5022.8 1961.64  5023.0 1962.14
  5028.7 1962.36  5035.3 1962.53  5043.0 1962.88  5057.3 1963.93  5063.8 1963.72
#Mann=4,-1,0
  4880.4   0.045       0  4957.6   0.035       0  5019.0   0.035       0
  5023.0   0.035       0
Bank Sta=5019,5023
Exp/Cntr=0.3,0.1

Type RM Length L Ch R = 1,4573,359,359,359
BEGIN DESCRIPTION:
UCFB HW Trib 04-12 9.0
END DESCRIPTION:
XS GIS Cut Line= 5
      1356930.02      7002112.99      1357180.00      7001963.00
      1357184.84      7001838.32      1357190.04      7001722.71
      1357134.46      7001572.06
#Sta/Elev= 30
  4583.7 1963.81  4612.8 1964.34  4647.8 1962.82  4671.1 1962.85  4684.7 1962.45
  4694.5 1963.29  4700.7 1963.18  4706.1 1963.09  4715.8 1961.85  4780.0 1961.67
  4787.8 1961.33  4811.1 1961.36  4875.2 1960.28  4970.3 1960.48  4978.3 1960.11
  4978.6 1959.61  4982.1 1959.61  4982.3 1960.11  4997.7 1960.46  5060.4 1960.31
  5110.2 1961.42  5115.2 1961.04  5121.0 1961.82  5140.7 1961.37  5152.7 1960.65
  5176.5 1960.49  5252.7 1961.74  5257.1 1961.92  5262.5 1963.10  5276.3 1962.73
#Mann=5,-1,0
  4583.7   0.035       0  4700.7   0.045       0  4978.3   0.045       0
  4982.3   0.045       0  5252.7   0.035       0
Bank Sta=4978.3,4982.3
Exp/Cntr=0.3,0.1

Type RM Length L Ch R = 1,4214,263,263,263
BEGIN DESCRIPTION:
UCFB HW Trib 04-12 8.5
END DESCRIPTION:
XS GIS Cut Line= 4
      1356889.55      7002193.49      1357330.00      7002013.00
      1357485.02      7001820.24      1356999.76      7001083.44
#Sta/Elev= 30
  4381.8 1964.12  4388.1 1962.17  4398.5 1961.84  4412.1 1963.75  4430.7 1964.06
  4460.1 1962.08  4465.5 1964.94  4489.5 1963.60  4506.6 1964.23  4531.3 1962.19
  4668.2 1960.50  4727.0 1961.53  4775.0 1959.47  4864.2 1958.39  5064.2 1959.34
  5097.4 1957.73  5097.6 1957.23  5101.4 1957.73  5129.1 1959.34  5165.3 1958.09
  5237.6 1958.25  5294.8 1960.63  5346.0 1959.19  5475.5 1961.12  5517.6 1960.08
  5620.0 1961.08  5647.1 1962.52  5712.9 1962.17  5860.4 1962.39  5987.4 1962.33
#Mann=6,-1,0
  4381.8   0.035       0  4531.3   0.045       0  5097.4   0.045       0
  5101.4   0.045       0  5712.9   0.035       0  5860.4   0.045       0
Bank Sta=5097.4,5101.4
Exp/Cntr=0.3,0.1

Type RM Length L Ch R = 1,3951,451,451,451
BEGIN DESCRIPTION:
UCFB HW Trib 04-12 8.0
END DESCRIPTION:
XS GIS Cut Line= 5
      1356584.44      7002367.99      1357478.07      7002148.36
      1357563.02      7002094.34      1357655.16      7002019.89
      1357131.56      7001092.43
#Sta/Elev= 30
  3979.1 1963.52  4072.4 1963.01  4185.6 1964.79  4226.6 1963.13  4329.4 1962.56
  4413.9 1962.35  4506.4 1961.52  4542.8 1958.34  4547.9 1960.15  4597.5 1957.41
  4637.5 1958.67  4714.1 1959.03  4750.5 1956.10  4813.8 1955.00  4899.3 1957.12
  4926.6 1954.63  4967.0 1953.75  4967.2 1953.25  4971.0 1953.75  5214.3 1954.37
  5258.4 1957.47  5295.1 1955.48  5348.6 1955.72  5435.2 1959.23  5516.1 1958.05
  5618.6 1960.45  5706.3 1959.21  6068.2 1961.99  6134.1 1962.04  6183.5 1962.22
#Mann=9,-1,0
  3979.1    0.07       0  4226.6   0.035       0  4329.4    0.07       0
  4413.9   0.035       0  4637.5   0.045       0  4967.0   0.045       0
  4971.0   0.045       0  6068.2   0.035       0  6134.1   0.045       0
Bank Sta=4967,4971
Exp/Cntr=0.3,0.1

Type RM Length L Ch R = 1,3500,500,500,500
BEGIN DESCRIPTION:
UCFB HW Trib 04-12 7.0
END DESCRIPTION:
XS GIS Cut Line= 5
      1356630.00      7002713.00      1357930.00      7002313.00
      1357929.36      7002213.75      1357929.62      7002087.29
      1357184.56      7001042.01
#Sta/Elev= 30
  3540.6 1961.27  3629.4 1959.78  3733.9 1959.79  3752.1 1959.64  3817.9 1959.26
  3838.5 1960.30  4037.6 1956.62  4298.4 1954.43  4460.0 1952.86  4487.5 1954.06
  4525.4 1952.58  4667.8 1953.51  4675.0 1953.34  4778.4 1952.33  4778.7 1951.83
  4782.4 1952.33  5075.8 1953.57  5115.8 1952.64  5517.2 1954.80  5552.9 1955.66
  5573.8 1957.81  5624.2 1955.75  5752.0 1958.94  5802.4 1957.73  5882.4 1958.57
  5911.5 1960.17  5953.6 1958.77  6289.1 1960.86  6312.6 1962.25  6410.1 1961.94
#Mann=11,-1,0
  3540.6   0.045       0  3629.4   0.035       0  3733.9    0.07       0
  3752.1   0.035       0  3838.5    0.07       0  4298.4   0.045       0
  4667.8   0.035       0  4675.0   0.045       0  4778.4   0.045       0
  4782.4   0.045       0  6289.1   0.035       0
Bank Sta=4778.4,4782.4
Exp/Cntr=0.3,0.1

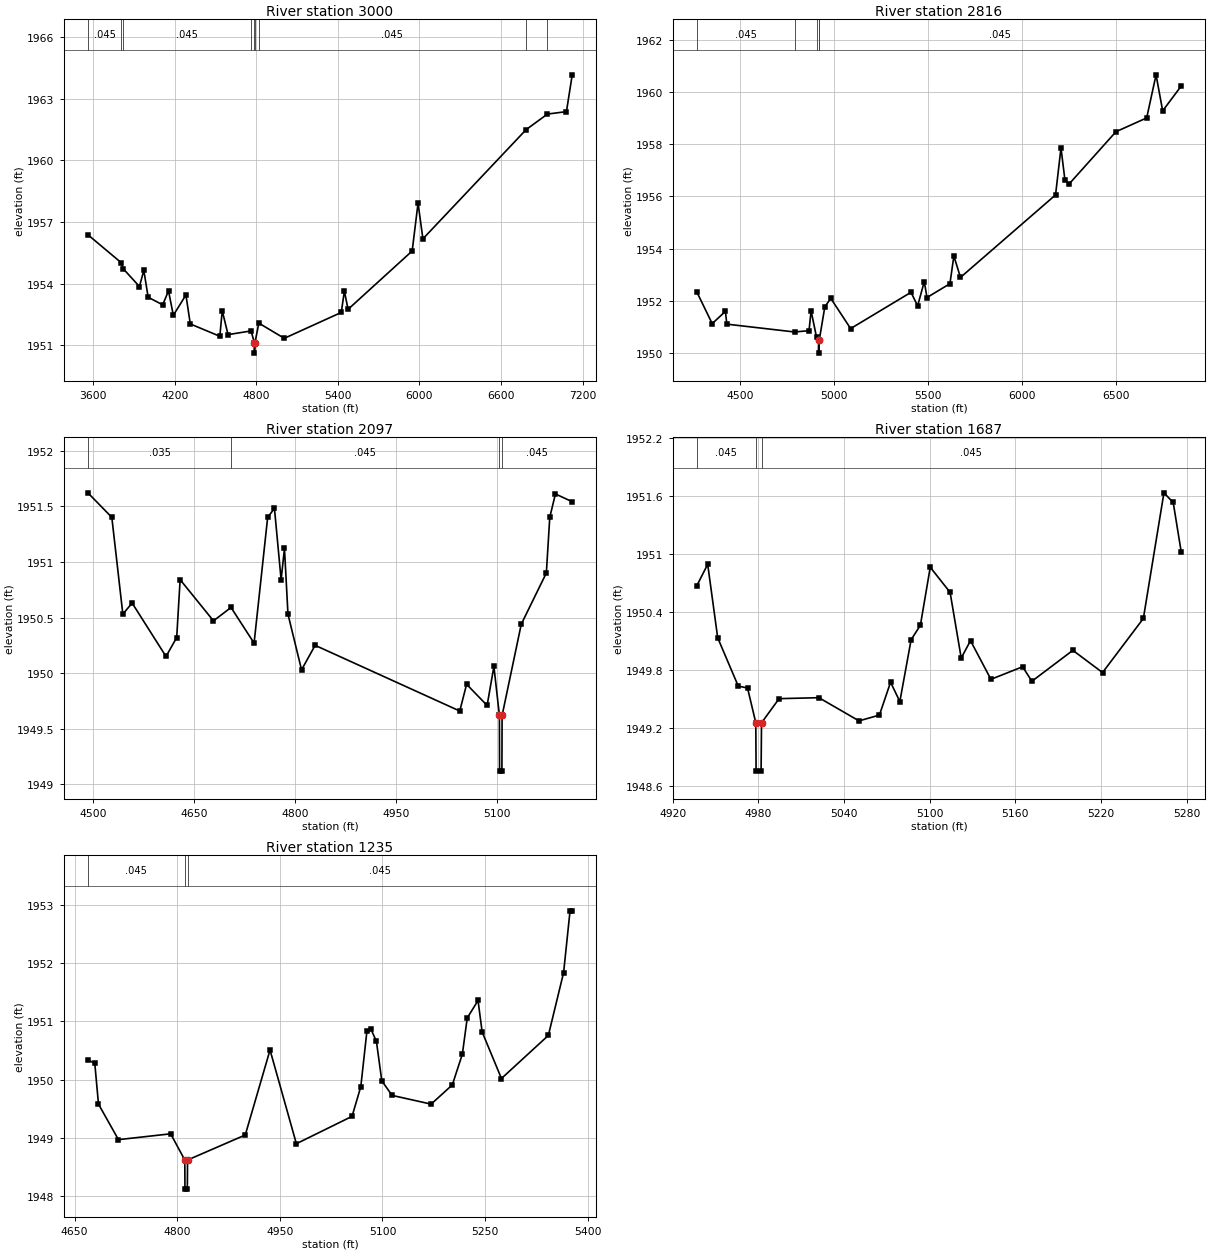
Type RM Length L Ch R = 1,3000,184,184,184
BEGIN DESCRIPTION:
UCFB HW Trib 04-12 6.0
END DESCRIPTION:
XS GIS Cut Line= 5
      1357029.97      7002913.01      1358230.00      7002463.00
      1358323.05      7002337.57      1358276.84      7002233.13
      1357055.01      7000638.02
#Sta/Elev= 30
  3562.2 1956.38  3809.2 1955.01  3821.5 1954.73  3941.4 1953.86  3973.4 1954.65
  4005.4 1953.34  4112.2 1952.97  4155.0 1953.65  4190.6 1952.46  4283.1 1953.45
  4315.2 1952.04  4532.3 1951.44  4550.1 1952.68  4592.8 1951.52  4762.0 1951.70
  4786.6 1951.12  4786.9 1950.62  4790.6 1951.12  4819.1 1952.08  5006.3 1951.34
  5425.4 1952.60  5448.1 1953.64  5475.2 1952.75  5946.7 1955.59  5989.8 1957.92
  6025.6 1956.18  6783.9 1961.49  6940.9 1962.25  7080.9 1962.37  7123.5 1964.16
#Mann=9,-1,0
  3562.2   0.045       0  3809.2    0.07       0  3821.5   0.045       0
  4762.0   0.035       0  4786.6   0.045       0  4790.6   0.035       0
  4819.1   0.045       0  6783.9   0.035       0  6940.9   0.045       0
Bank Sta=4786.6,4790.6
Exp/Cntr=0.3,0.1

Type RM Length L Ch R = 1,2816,719,719,719
BEGIN DESCRIPTION:
UCFB HW Trib 04-12 5.0
END DESCRIPTION:
XS GIS Cut Line= 5
      1358002.82      7002940.54      1358430.00      7002563.00
      1358478.41      7002412.29      1358481.70      7002326.88
      1357395.98      7000939.73
#Sta/Elev= 30
  4271.6 1952.34  4353.2 1951.13  4423.4 1951.60  4431.0 1951.11  4791.5 1950.81
  4868.0 1950.86  4879.1 1951.62  4907.9 1950.61  4918.5 1950.50  4918.7 1950.00
  4922.5 1950.50  4952.0 1951.77  4983.5 1952.10  5089.3 1950.94  5410.3 1952.33
  5445.6 1951.81  5480.8 1952.74  5495.3 1952.13  5617.3 1952.66  5638.2 1953.72
  5673.4 1952.90  6178.9 1956.06  6207.8 1957.86  6228.6 1956.64  6251.2 1956.48
  6499.9 1958.48  6663.5 1959.01  6713.3 1960.66  6748.5 1959.28  6847.0 1960.23
#Mann=5,-1,0
  4271.6   0.045       0  4791.5   0.035       0  4907.9   0.045       0
  4918.5   0.045       0  4922.5   0.045       0
Bank Sta=4918.5,4922.5
Exp/Cntr=0.3,0.1

Type RM Length L Ch R = 1,2097,410,410,410
BEGIN DESCRIPTION:
UCFB HW Trib 04-12 4.0
END DESCRIPTION:
XS GIS Cut Line= 4
      1358489.71      7002539.68      1358876.11      7002490.80
      1358871.68      7002372.16      1358833.37      7002163.44
#Sta/Elev= 30
  4491.8 1951.62  4527.4 1951.40  4543.8 1950.53  4557.6 1950.63  4608.0 1950.15
  4623.9 1950.32  4629.0 1950.84  4678.6 1950.47  4704.7 1950.59  4739.0 1950.27
  4759.2 1951.40  4769.3 1951.48  4779.2 1950.84  4784.2 1951.12  4789.4 1950.53
  4809.6 1950.03  4829.8 1950.25  5044.9 1949.66  5055.1 1949.90  5085.6 1949.71
  5095.7 1950.06  5103.9 1949.62  5104.1 1949.12  5107.6 1949.12  5107.9 1949.62
  5136.4 1950.44  5173.7 1950.90  5178.8 1951.40  5187.2 1951.61  5212.2 1951.54
#Mann=4,-1,0
  4491.8   0.035       0  4704.7   0.045       0  5103.9   0.045       0
  5107.9   0.045       0
Bank Sta=5103.9,5107.9
Exp/Cntr=0.3,0.1

Type RM Length L Ch R = 1,1687,452,452,452
BEGIN DESCRIPTION:
UCFB HW Trib 04-12 3.0
END DESCRIPTION:
XS GIS Cut Line= 2
      1359130.81      7002202.72      1358869.76      7001985.98
#Sta/Elev= 30
  4936.9 1950.67  4944.5 1950.89  4951.5 1950.13  4965.9 1949.63  4972.4 1949.61
  4978.2 1949.25  4978.4 1948.75  4981.9 1948.75  4982.2 1949.25  4994.5 1949.50
  5022.4 1949.51  5050.5 1949.27  5064.8 1949.33  5072.6 1949.67  5079.1 1949.47
  5087.0 1950.11  5093.5 1950.26  5100.4 1950.86  5114.3 1950.60  5122.1 1949.92
  5128.6 1950.10  5142.9 1949.70  5165.1 1949.83  5171.6 1949.68  5200.3 1950.00
  5221.1 1949.77  5249.7 1950.33  5264.1 1951.63  5270.6 1951.53  5276.2 1951.02
#Mann=3,-1,0
  4936.9   0.045       0  4978.2   0.045       0  4982.2   0.045       0
Bank Sta=4978.2,4982.2
Exp/Cntr=0.3,0.1

Type RM Length L Ch R = 1,1235,0,0,0
BEGIN DESCRIPTION:
UCFB HW Trib 04-12 1.0
END DESCRIPTION:
XS GIS Cut Line= 3
      1359315.45      7002038.98      1359207.65      7001791.09
      1358824.41      7001579.47
#Sta/Elev= 30
  4669.3 1950.34  4679.4 1950.28  4684.8 1949.58  4714.0 1948.97  4790.3 1949.07
  4811.0 1948.62  4811.2 1948.12  4814.7 1948.12  4815.0 1948.62  4899.4 1949.05
  4935.6 1950.51  4974.1 1948.90  5055.5 1949.37  5068.3 1949.88  5077.2 1950.83
  5083.0 1950.87  5091.1 1950.66  5099.0 1949.98  5114.0 1949.73  5171.1 1949.58
  5202.1 1949.91  5216.8 1950.44  5223.9 1951.06  5239.7 1951.36  5245.7 1950.82
  5273.9 1950.02  5342.5 1950.76  5364.8 1951.84  5374.2 1952.90  5377.4 1952.90
#Mann=3,-1,0
  4669.3   0.045       0  4811.0   0.045       0  4815.0   0.045       0
Bank Sta=4811,4815
Exp/Cntr=0.3,0.1

Chan Stop Cuts=-1