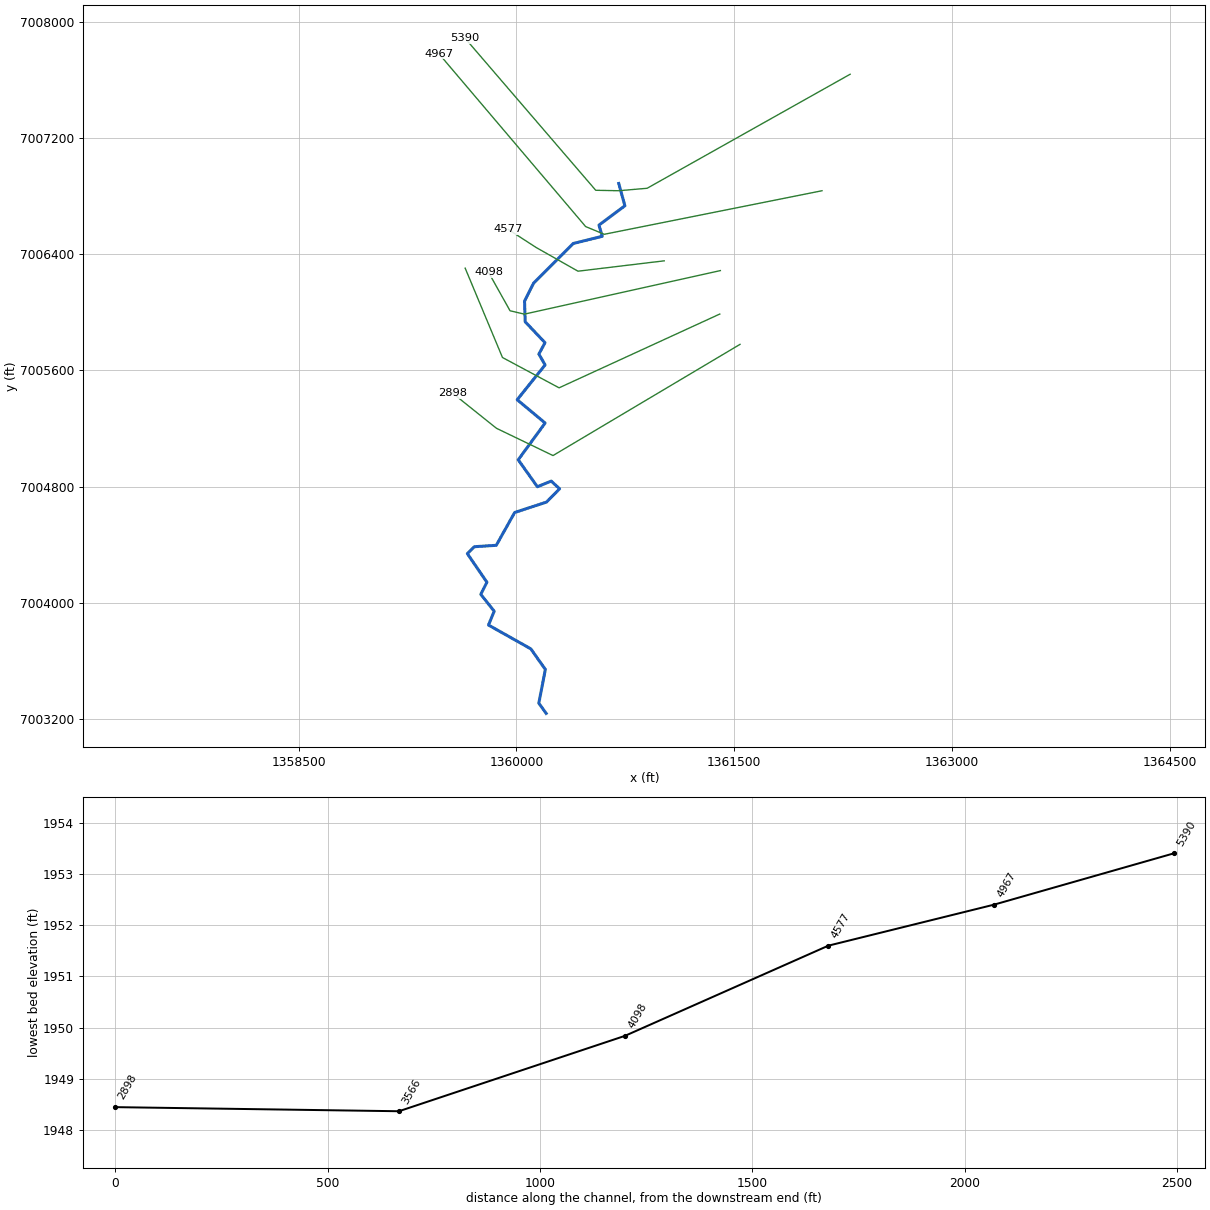
--- UCFB HW Trib 04-13-01.prj (project) ---

Proj Title=UCFB HW Trib 04-13-01 Base Level Engineering
Current Plan=p01
Default Exp/Contr=0.3,0.1
English Units
Geom File=g01
Flow File=f01
Plan File=p01
BEGIN DESCRIPTION:
UCFB HW Trib 04-13-01
END DESCRIPTION:

--- UCFB HW Trib 04-13-01.p01 (plan) ---

Plan Title=Multiple Run
Short Identifier=Multiple
Geom File=g01
Flow File=f01
Subcritical Flow
K Sum by GR= 0
Std Step Tol= 0.01
Critical Tol= 0.01
Num of Std Step Trials= 20
Max Error Tol= 0.3
Flow Tol Ratio= 0.001
Split Flow NTrial= 30
Split Flow Tol= 0.02
Split Flow Ratio= 0.02
Log Output Level= 0
Friction Slope Method= 1
Unsteady Friction Slope Method= 2
Unsteady Bridges Friction Slope Method= 1
Parabolic Critical Depth
Global Vel Dist=  1 , 1 , 1
Global Log Level= 0
CheckData=True
Encroach Param= -1, 0, 0, 0
BEGIN DESCRIPTION:
Multiple Run
END DESCRIPTION:

--- UCFB HW Trib 04-13-01.f01 (steady flow) ---

Flow Title=Multiple
Number of Profiles=7
Profile Names=10-year,25-year,50-year,1pct_min,100-year,1pct_plu,500-year
River Rch & RM= UCFB HW Trib 04-,Reach-1,5390
     166     226     273     164     328     654     479
Boundary for River Rch & Prof#=UCFB HW Trib 04-,Reach-1,1
Up Type=0
Dn Type=3
Dn Slope=0.005
Boundary for River Rch & Prof#=UCFB HW Trib 04-,Reach-1,2
Up Type=0
Dn Type=3
Dn Slope=0.005
Boundary for River Rch & Prof#=UCFB HW Trib 04-,Reach-1,3
Up Type=0
Dn Type=3
Dn Slope=0.005
Boundary for River Rch & Prof#=UCFB HW Trib 04-,Reach-1,4
Up Type=0
Dn Type=3
Dn Slope=0.005
Boundary for River Rch & Prof#=UCFB HW Trib 04-,Reach-1,5
Up Type=0
Dn Type=3
Dn Slope=0.005
Boundary for River Rch & Prof#=UCFB HW Trib 04-,Reach-1,6
Up Type=0
Dn Type=3
Dn Slope=0.005
Boundary for River Rch & Prof#=UCFB HW Trib 04-,Reach-1,7
Up Type=0
Dn Type=3
Dn Slope=0.005

--- UCFB HW Trib 04-13-01.g01 (geometry) ---

Geom Title=Existing Conditions

River Reach=UCFB HW Trib 04-,Reach-1
Reach XY= 30
      1360705.00      7006888.00      1360747.35      7006734.33
      1360568.64      7006601.35      1360591.53      7006524.24
      1360391.68      7006474.63      1360118.54      7006201.54
      1360056.19      7006077.50      1360060.45      7005935.55
      1360197.18      7005791.41      1360154.79      7005713.00
      1360197.65      7005637.91      1360005.48      7005398.49
      1360197.92      7005238.02      1360012.61      7004984.67
      1360144.63      7004798.98      1360239.92      7004837.99
      1360297.50      7004784.88      1360207.46      7004693.52
      1359987.94      7004621.52      1359861.47      7004395.70
      1359710.44      7004385.93      1359661.98      7004338.25
      1359796.93      7004141.31      1359754.68      7004058.16
      1359847.15      7003941.38      1359807.66      7003846.48
      1360099.38      7003682.38      1360199.53      7003540.45
      1360154.45      7003308.21      1360205.00      7003238.00

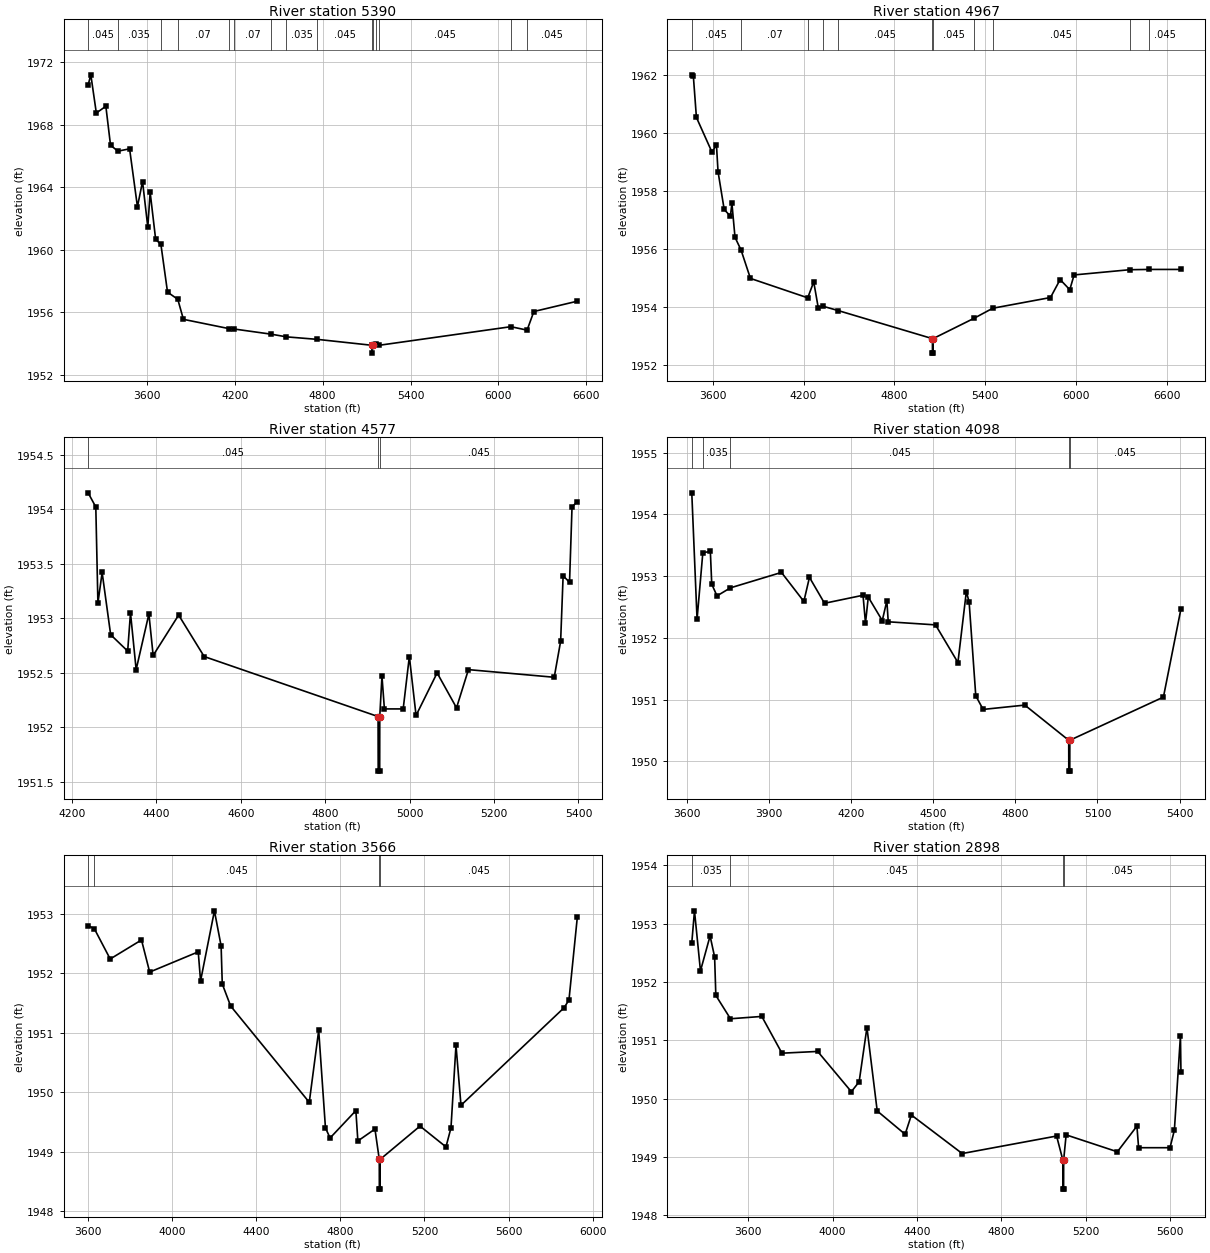
Type RM Length L Ch R = 1,5390,423,423,423
BEGIN DESCRIPTION:
UCFB HW Trib 04-13-01 3.0
END DESCRIPTION:
XS GIS Cut Line= 5
      1362298.81      7007640.43      1360900.63      7006855.06
      1360705.00      7006838.00      1360546.46      7006841.17
      1359646.88      7007887.80
#Sta/Elev= 30
  3199.4 1970.54  3217.8 1971.19  3255.4 1968.75  3320.4 1969.18  3352.3 1966.69
  3402.7 1966.31  3482.4 1966.46  3536.0 1962.76  3570.8 1964.37  3606.7 1961.46
  3622.7 1963.68  3660.3 1960.67  3696.1 1960.35  3741.3 1957.30  3811.4 1956.84
  3849.7 1955.56  4159.0 1954.97  4197.1 1954.94  4449.8 1954.61  4553.1 1954.44
  4763.3 1954.28  5137.5 1953.90  5137.7 1953.40  5141.5 1953.90  5162.5 1953.98
  5184.6 1953.90  6084.8 1955.09  6195.3 1954.87  6241.7 1956.06  6538.1 1956.72
#Mann=15,-1,0
  3199.4   0.045       0  3402.7   0.035       0  3696.1   0.045       0
  3811.4    0.07       0  4159.0   0.045       0  4197.1    0.07       0
  4449.8   0.045       0  4553.1   0.035       0  4763.3   0.045       0
  5137.5   0.045       0  5141.5   0.045       0  5162.5   0.035       0
  5184.6   0.045       0  6084.8   0.035       0  6195.3   0.045       0
Bank Sta=5137.5,5141.5
Exp/Cntr=0.3,0.1

Type RM Length L Ch R = 1,4967,390,390,390
BEGIN DESCRIPTION:
UCFB HW Trib 04-13-01 2.0
END DESCRIPTION:
XS GIS Cut Line= 4
      1362105.02      7006838.00      1360605.00      7006538.00
      1360477.02      7006591.17      1359464.84      7007783.33
#Sta/Elev= 30
  3461.4 1962.01  3471.6 1961.98  3492.0 1960.54  3594.0 1959.35  3624.6 1959.58
  3634.8 1958.67  3675.6 1957.36  3716.4 1957.13  3726.6 1957.57  3747.0 1956.40
  3786.9 1955.96  3848.9 1954.98  4227.5 1954.31  4267.1 1954.86  4297.7 1953.95
  4327.9 1954.02  4428.4 1953.87  5051.5 1952.90  5051.7 1952.40  5055.2 1952.40
  5055.5 1952.90  5325.3 1953.60  5450.0 1953.95  5831.6 1954.32  5895.3 1954.94
  5959.0 1954.59  5987.6 1955.10  6354.5 1955.28  6479.9 1955.29  6693.6 1955.29
#Mann=11,-1,0
  3461.4   0.045       0  3786.9    0.07       0  4227.5   0.045       0
  4327.9   0.035       0  4428.4   0.045       0  5051.5   0.045       0
  5055.5   0.045       0  5325.3   0.035       0  5450.0   0.045       0
  6354.5   0.035       0  6479.9   0.045       0
Bank Sta=5051.5,5055.5
Exp/Cntr=0.3,0.1

Type RM Length L Ch R = 1,4577,479,479,479
BEGIN DESCRIPTION:
UCFB HW Trib 04-13-01 1.5
END DESCRIPTION:
XS GIS Cut Line= 4
      1361017.99      7006355.18      1360424.27      7006283.80
      1360136.27      7006446.99      1359942.97      7006571.98
#Sta/Elev= 30
  4238.0 1954.15  4256.2 1954.02  4261.2 1953.14  4271.2 1953.42  4291.4 1952.85
  4331.7 1952.70  4338.4 1953.05  4351.8 1952.53  4382.0 1953.04  4392.1 1952.66
  4452.5 1953.03  4513.0 1952.65  4925.1 1952.10  4925.4 1951.60  4928.9 1951.60
  4929.1 1952.10  4934.3 1952.47  4940.1 1952.17  4984.6 1952.17  4999.2 1952.65
  5015.1 1952.11  5065.0 1952.50  5111.0 1952.18  5139.2 1952.53  5342.5 1952.46
  5357.7 1952.79  5363.6 1953.39  5378.8 1953.33  5384.7 1954.02  5397.2 1954.07
#Mann=3,-1,0
  4238.0   0.045       0  4925.1   0.045       0  4929.1   0.045       0
Bank Sta=4925.1,4929.1
Exp/Cntr=0.3,0.1

Type RM Length L Ch R = 1,4098,532,532,532
BEGIN DESCRIPTION:
UCFB HW Trib 04-13-01 1.0
END DESCRIPTION:
XS GIS Cut Line= 4
      1361405.04      7006288.01      1360055.00      7005988.00
      1359956.18      7006011.31      1359807.57      7006276.85
#Sta/Elev= 30
  3616.5 1954.35  3635.8 1952.30  3656.9 1953.38  3684.4 1953.40  3689.5 1952.87
  3708.7 1952.68  3757.7 1952.81  3944.4 1953.06  4026.3 1952.59  4046.8 1952.98
  4101.9 1952.56  4242.7 1952.69  4251.7 1952.24  4261.9 1952.66  4313.1 1952.28
  4329.8 1952.60  4334.9 1952.26  4507.8 1952.21  4589.7 1951.60  4620.5 1952.75
  4630.7 1952.58  4655.0 1951.06  4681.9 1950.84  4834.3 1950.91  4994.9 1950.34
  4995.2 1949.84  4998.7 1949.84  4998.9 1950.34  5341.2 1951.04  5405.3 1952.47
#Mann=5,-1,0
  3616.5   0.045       0  3656.9   0.035       0  3757.7   0.045       0
  4994.9   0.045       0  4998.9   0.045       0
Bank Sta=4994.9,4998.9
Exp/Cntr=0.3,0.1

Type RM Length L Ch R = 1,3566,668,668,668
BEGIN DESCRIPTION:
UCFB HW Trib 04-13-01 0.2
END DESCRIPTION:
XS GIS Cut Line= 4
      1361401.10      7005988.77      1360293.99      7005480.48
      1359904.05      7005689.37      1359647.22      7006304.63
#Sta/Elev= 30
  3599.8 1952.80  3629.2 1952.75  3704.8 1952.24  3853.7 1952.56  3892.6 1952.02
  4123.7 1952.36  4134.7 1951.87  4200.7 1953.05  4232.5 1952.46  4238.0 1951.82
  4277.7 1951.45  4651.9 1949.83  4696.8 1951.04  4728.9 1949.40  4750.9 1949.23
  4873.6 1949.69  4883.1 1949.18  4964.4 1949.38  4985.0 1948.87  4985.3 1948.37
  4988.8 1948.37  4989.0 1948.87  5178.8 1949.43  5302.3 1949.08  5326.1 1949.40
  5349.9 1950.79  5373.7 1949.78  5864.1 1951.42  5887.4 1951.55  5927.1 1952.94
#Mann=4,-1,0
  3599.8   0.035       0  3629.2   0.045       0  4985.0   0.045       0
  4989.0   0.045       0
Bank Sta=4985,4989
Exp/Cntr=0.3,0.1

Type RM Length L Ch R = 1,2898,0,0,0
BEGIN DESCRIPTION:
UCFB HW Trib 04-13-01 0.1
END DESCRIPTION:
XS GIS Cut Line= 4
      1361540.42      7005779.90      1360252.21      7005013.94
      1359862.27      7005201.95      1359558.64      7005444.92
#Sta/Elev= 30
  3332.2 1952.67  3345.0 1953.22  3373.4 1952.19  3419.0 1952.79  3440.5 1952.43
  3446.3 1951.77  3515.7 1951.37  3664.4 1951.41  3759.9 1950.78  3929.4 1950.81
  4089.1 1950.12  4126.1 1950.29  4163.1 1951.22  4211.8 1949.79  4344.2 1949.39
  4373.9 1949.72  4615.0 1949.06  5062.8 1949.36  5092.3 1948.95  5092.5 1948.45
  5096.0 1948.45  5096.3 1948.95  5108.0 1949.38  5351.0 1949.09  5443.8 1949.53
  5451.8 1949.16  5600.7 1949.16  5621.5 1949.46  5650.3 1951.08  5652.7 1950.45
#Mann=4,-1,0
  3332.2   0.035       0  3515.7   0.045       0  5092.3   0.045       0
  5096.3   0.045       0
Bank Sta=5092.3,5096.3
Exp/Cntr=0.3,0.1

Chan Stop Cuts=-1