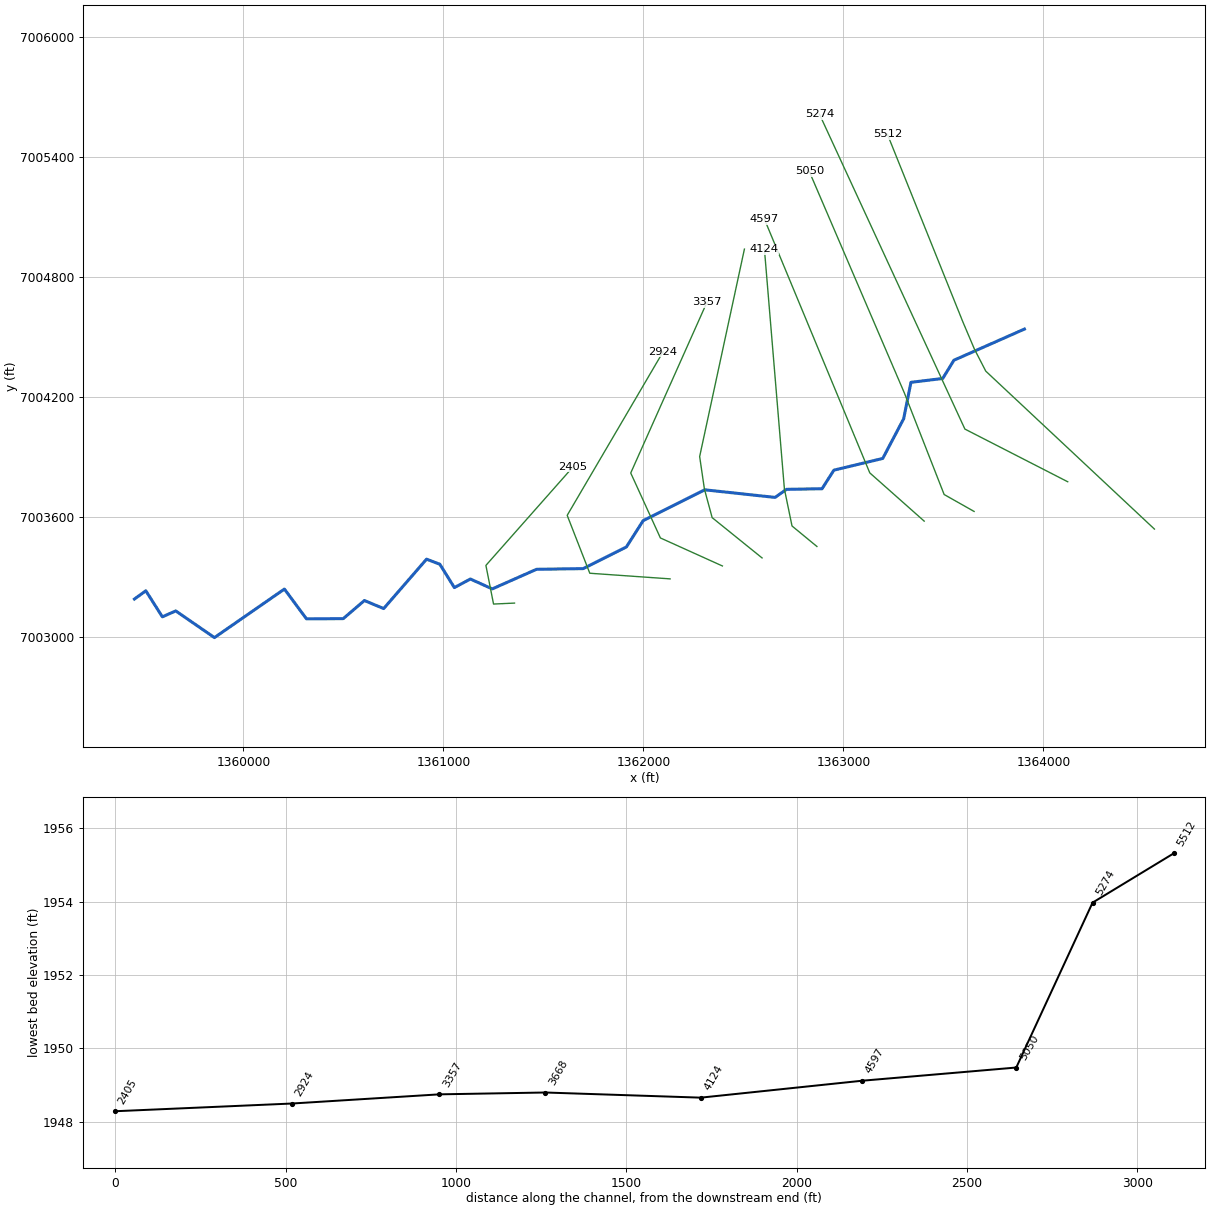
--- UCFB HW Trib 04-13.prj (project) ---

Proj Title=UCFB HW Trib 04-13 Base Level Engineering
Current Plan=p01
Default Exp/Contr=0.3,0.1
English Units
Geom File=g01
Flow File=f01
Plan File=p01
BEGIN DESCRIPTION:
UCFB HW Trib 04-13
END DESCRIPTION:

--- UCFB HW Trib 04-13.p01 (plan) ---

Plan Title=Multiple Run
Short Identifier=Multiple
Geom File=g01
Flow File=f01
Subcritical Flow
K Sum by GR= 0
Std Step Tol= 0.01
Critical Tol= 0.01
Num of Std Step Trials= 20
Max Error Tol= 0.3
Flow Tol Ratio= 0.001
Split Flow NTrial= 30
Split Flow Tol= 0.02
Split Flow Ratio= 0.02
Log Output Level= 0
Friction Slope Method= 1
Unsteady Friction Slope Method= 2
Unsteady Bridges Friction Slope Method= 1
Parabolic Critical Depth
Global Vel Dist=  1 , 1 , 1
Global Log Level= 0
CheckData=True
Encroach Param= -1, 0, 0, 0
BEGIN DESCRIPTION:
Multiple Run
END DESCRIPTION:

--- UCFB HW Trib 04-13.f01 (steady flow) ---

Flow Title=Multiple
Number of Profiles=7
Profile Names=10-year,25-year,50-year,1pct_min,100-year,1pct_plu,500-year
River Rch & RM= UCFB HW Trib 04-,Reach-1,5512
     182     248     301     182     363     724     535
Boundary for River Rch & Prof#=UCFB HW Trib 04-,Reach-1,1
Up Type=0
Dn Type=3
Dn Slope=0.005
Boundary for River Rch & Prof#=UCFB HW Trib 04-,Reach-1,2
Up Type=0
Dn Type=3
Dn Slope=0.005
Boundary for River Rch & Prof#=UCFB HW Trib 04-,Reach-1,3
Up Type=0
Dn Type=3
Dn Slope=0.005
Boundary for River Rch & Prof#=UCFB HW Trib 04-,Reach-1,4
Up Type=0
Dn Type=3
Dn Slope=0.005
Boundary for River Rch & Prof#=UCFB HW Trib 04-,Reach-1,5
Up Type=0
Dn Type=3
Dn Slope=0.005
Boundary for River Rch & Prof#=UCFB HW Trib 04-,Reach-1,6
Up Type=0
Dn Type=3
Dn Slope=0.005
Boundary for River Rch & Prof#=UCFB HW Trib 04-,Reach-1,7
Up Type=0
Dn Type=3
Dn Slope=0.005

--- UCFB HW Trib 04-13.g01 (geometry) ---

Geom Title=Existing Conditions

River Reach=UCFB HW Trib 04-,Reach-1
Reach XY= 30
      1363905.00      7004538.00      1363552.47      7004382.23
      1363496.69      7004291.10      1363337.78      7004271.76
      1363301.24      7004089.56      1363196.68      7003891.15
      1362952.34      7003832.54      1362893.17      7003739.65
      1362715.44      7003736.62      1362658.22      7003696.28
      1362306.56      7003734.26      1361998.66      7003579.97
      1361915.00      7003448.63      1361699.07      7003340.24
      1361465.50      7003336.78      1361244.31      7003238.77
      1361134.79      7003288.19      1361054.70      7003245.26
      1360982.14      7003362.08      1360915.68      7003387.47
      1360701.28      7003140.37      1360604.92      7003180.64
      1360499.15      7003090.07      1360315.28      7003088.98
      1360205.00      7003238.00      1359855.09      7002995.28
      1359661.65      7003128.68      1359594.68      7003099.11
      1359512.04      7003229.38      1359455.00      7003188.00

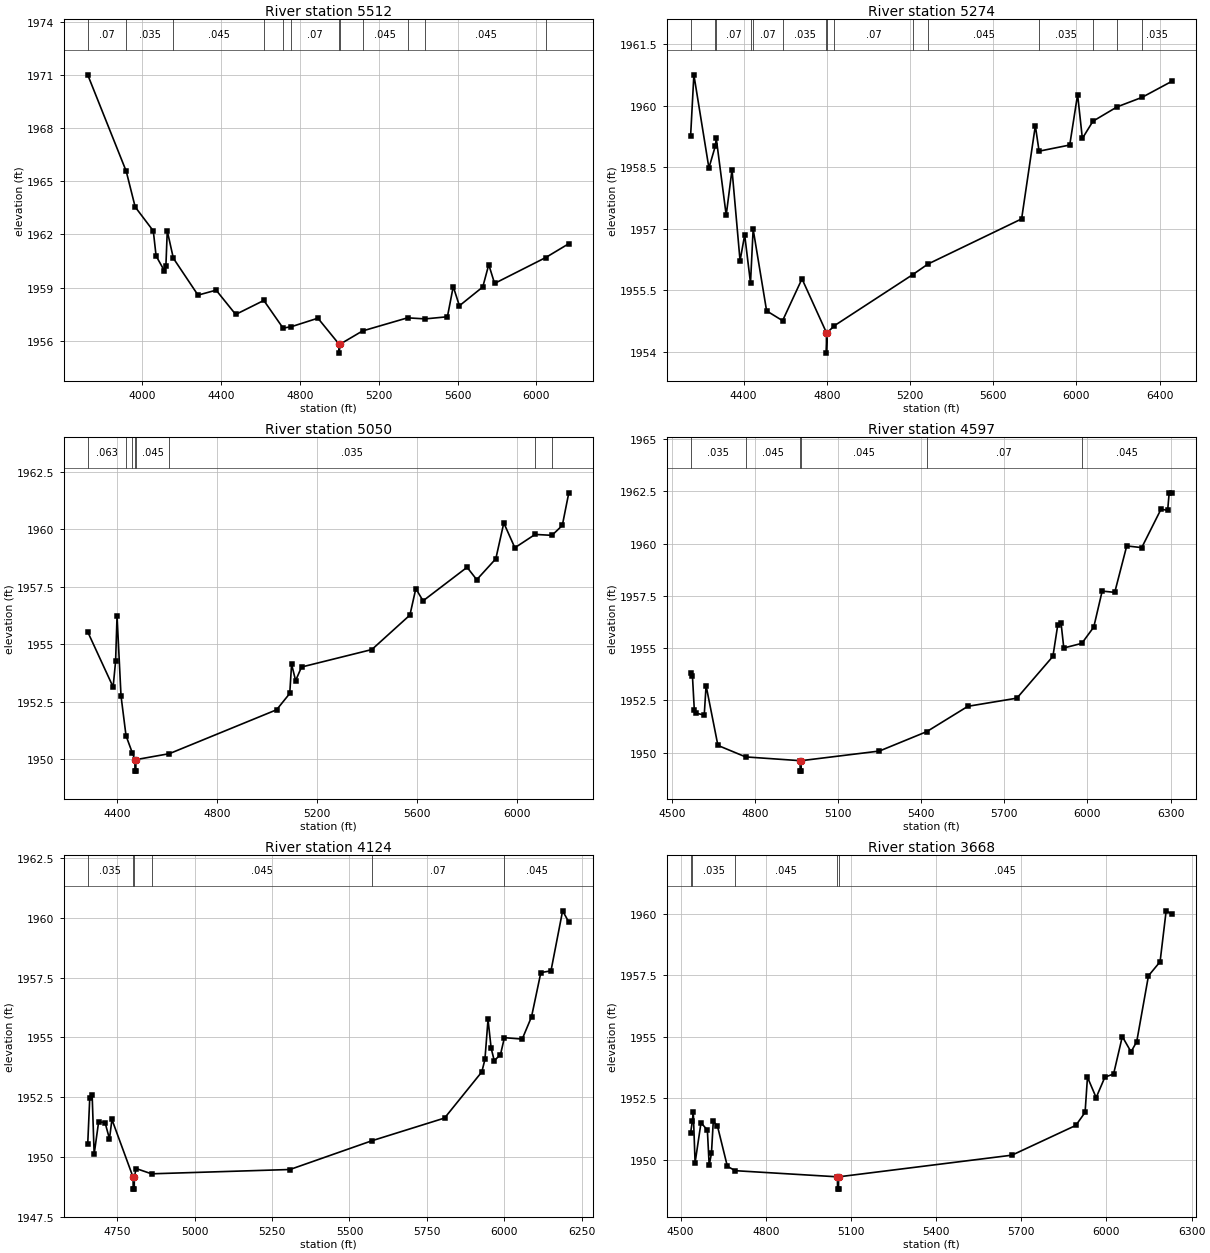
Type RM Length L Ch R = 1,5512,238,238,238
BEGIN DESCRIPTION:
UCFB HW Trib 04-13 7.0
END DESCRIPTION:
XS GIS Cut Line= 5
      1364555.01      7003537.99      1363711.74      7004327.75
      1363655.00      7004438.00      1363597.15      7004574.27
      1363219.83      7005512.56
#Sta/Elev= 30
  3725.2 1971.00  3920.5 1965.56  3965.8 1963.55  4057.6 1962.20  4071.8 1960.79
  4114.3 1959.94  4121.6 1960.25  4128.4 1962.20  4159.3 1960.66  4284.3 1958.58
  4376.1 1958.86  4475.3 1957.49  4617.9 1958.28  4715.5 1956.72  4757.4 1956.80
  4892.1 1957.28  4999.7 1955.81  5000.0 1955.31  5003.7 1955.81  5118.2 1956.56
  5346.6 1957.30  5435.6 1957.24  5548.5 1957.36  5578.1 1959.06  5609.3 1957.98
  5727.8 1959.04  5758.1 1960.30  5787.7 1959.24  6047.1 1960.70  6163.9 1961.48
#Mann=12,-1,0
  3725.2    0.07       0  3920.5   0.035       0  4159.3   0.045       0
  4617.9   0.035       0  4715.5   0.045       0  4757.4    0.07       0
  4999.7    0.07       0  5003.7    0.07       0  5118.2   0.045       0
  5346.6    0.07       0  5435.6   0.045       0  6047.1    0.07       0
Bank Sta=4999.7,5003.7
Exp/Cntr=0.3,0.1

Type RM Length L Ch R = 1,5274,224,224,224
BEGIN DESCRIPTION:
UCFB HW Trib 04-13 5.5
END DESCRIPTION:
XS GIS Cut Line= 3
      1364121.51      7003774.55      1363607.42      7004038.00
      1362880.02      7005612.97
#Sta/Elev= 30
  4145.6 1959.26  4161.3 1960.75  4233.6 1958.48  4264.1 1959.01  4269.0 1959.20
  4316.7 1957.33  4344.6 1958.44  4383.3 1956.22  4405.5 1956.85  4433.5 1955.68
  4446.2 1956.99  4510.9 1955.00  4587.7 1954.76  4681.0 1955.78  4798.4 1954.47
  4798.6 1953.97  4802.4 1954.47  4837.2 1954.64  5212.5 1955.88  5286.4 1956.14
  5736.7 1957.24  5802.7 1959.51  5820.6 1958.89  5968.0 1959.04  6005.8 1960.27
  6028.7 1959.20  6079.6 1959.62  6195.9 1959.97  6315.1 1960.20  6458.1 1960.59
#Mann=15,-1,0
  4145.6   0.035       0  4264.1   0.045       0  4269.0    0.07       0
  4433.5   0.035       0  4446.2    0.07       0  4587.7   0.035       0
  4798.4    0.07       0  4802.4   0.035       0  4837.2    0.07       0
  5212.5   0.035       0  5286.4   0.045       0  5820.6   0.035       0
  6079.6    0.07       0  6195.9   0.045       0  6315.1   0.035       0
Bank Sta=4798.4,4802.4
Exp/Cntr=0.3,0.1

Type RM Length L Ch R = 1,5050,453,453,453
BEGIN DESCRIPTION:
UCFB HW Trib 04-13 6.0
END DESCRIPTION:
XS GIS Cut Line= 4
      1363653.40      7003626.12      1363503.68      7003710.74
      1363304.93      7004218.12      1362829.38      7005326.08
#Sta/Elev= 30
  4283.1 1955.54  4384.6 1953.14  4394.5 1954.26  4400.3 1956.23  4416.2 1952.75
  4436.2 1951.02  4461.2 1950.28  4471.6 1949.98  4471.9 1949.48  4475.4 1949.48
  4475.6 1949.98  4609.4 1950.24  5037.9 1952.15  5090.5 1952.86  5097.8 1954.13
  5114.0 1953.42  5137.6 1954.01  5418.5 1954.77  5570.7 1956.27  5594.3 1957.42
  5623.3 1956.89  5799.1 1958.35  5837.8 1957.81  5914.0 1958.72  5945.9 1960.28
  5990.1 1959.20  6071.0 1959.78  6138.4 1959.74  6179.7 1960.17  6205.7 1961.59
#Mann=8,-1,0
  4283.1   0.063       0  4436.2   0.035       0  4461.2   0.045       0
  4471.6   0.035       0  4475.6   0.045       0  4609.4   0.035       0
  6071.0    0.07       0  6138.4   0.035       0
Bank Sta=4471.6,4475.6
Exp/Cntr=0.3,0.1

Type RM Length L Ch R = 1,4597,473,473,473
BEGIN DESCRIPTION:
UCFB HW Trib 04-13 5.0
END DESCRIPTION:
XS GIS Cut Line= 3
      1363403.88      7003577.71      1363131.87      7003818.95
      1362605.02      7005087.96
#Sta/Elev= 30
  4566.7 1953.83  4573.3 1953.68  4580.0 1952.06  4587.5 1951.89  4615.9 1951.80
  4622.6 1953.21  4665.3 1950.35  4765.5 1949.80  4962.2 1949.62  4962.4 1949.12
  4965.9 1949.12  4966.2 1949.62  5248.4 1950.08  5419.8 1951.01  5568.1 1952.22
  5745.2 1952.61  5875.3 1954.61  5892.9 1956.12  5904.6 1956.21  5914.6 1955.01
  5979.6 1955.23  6022.8 1956.01  6053.2 1957.73  6098.6 1957.67  6141.9 1959.89
  6196.1 1959.81  6265.8 1961.65  6289.7 1961.59  6295.1 1962.41  6304.3 1962.43
#Mann=6,-1,0
  4566.7   0.035       0  4765.5   0.045       0  4962.2   0.045       0
  4966.2   0.045       0  5419.8    0.07       0  5979.6   0.045       0
Bank Sta=4962.2,4966.2
Exp/Cntr=0.3,0.1

Type RM Length L Ch R = 1,4124,456,456,456
BEGIN DESCRIPTION:
UCFB HW Trib 04-13 4.0
END DESCRIPTION:
XS GIS Cut Line= 4
      1362867.46      7003450.92      1362742.99      7003553.44
      1362705.00      7003738.00      1362605.00      7004937.95
#Sta/Elev= 30
  4654.7 1950.54  4661.2 1952.45  4669.0 1952.60  4675.5 1950.12  4689.9 1951.47
  4710.7 1951.44  4725.0 1950.76  4732.9 1951.57  4801.2 1949.16  4801.5 1948.66
  4805.0 1948.66  4805.2 1949.16  4811.1 1949.52  4860.8 1949.30  5307.9 1949.48
  5572.2 1950.68  5807.2 1951.63  5927.6 1953.56  5937.6 1954.08  5947.6 1955.75
  5957.7 1954.55  5967.7 1954.03  5987.8 1954.28  6000.5 1954.99  6058.0 1954.93
  6088.1 1955.86  6118.2 1957.71  6150.9 1957.78  6188.5 1960.29  6208.5 1959.82
#Mann=6,-1,0
  4654.7   0.035       0  4801.2   0.045       0  4805.2   0.035       0
  4860.8   0.045       0  5572.2    0.07       0  6000.5   0.045       0
Bank Sta=4801.2,4805.2
Exp/Cntr=0.3,0.1

Type RM Length L Ch R = 1,3668,311,311,311
BEGIN DESCRIPTION:
UCFB HW Trib 04-13 3.0
END DESCRIPTION:
XS GIS Cut Line= 5
      1362593.13      7003393.73      1362343.68      7003595.11
      1362305.00      7003738.00      1362281.18      7003900.66
      1362504.99      7004937.97
#Sta/Elev= 30
  4535.5 1951.09  4541.6 1951.56  4544.9 1951.93  4551.3 1949.87  4572.1 1951.50
  4594.5 1951.20  4600.9 1949.77  4608.9 1950.25  4615.3 1951.55  4629.7 1951.38
  4664.9 1949.73  4692.2 1949.55  5052.7 1949.30  5052.9 1948.80  5056.4 1948.80
  5056.7 1949.30  5667.1 1950.18  5892.1 1951.39  5924.7 1951.92  5933.1 1953.35
  5963.7 1952.52  5994.4 1953.35  6025.1 1953.48  6055.8 1955.00  6086.5 1954.38
  6106.5 1954.79  6147.9 1957.47  6188.8 1958.04  6210.2 1960.11  6229.7 1959.98
#Mann=5,-1,0
  4535.5    0.07       0  4541.6   0.035       0  4692.2   0.045       0
  5052.7   0.045       0  5056.7   0.045       0
Bank Sta=5052.7,5056.7
Exp/Cntr=0.3,0.1

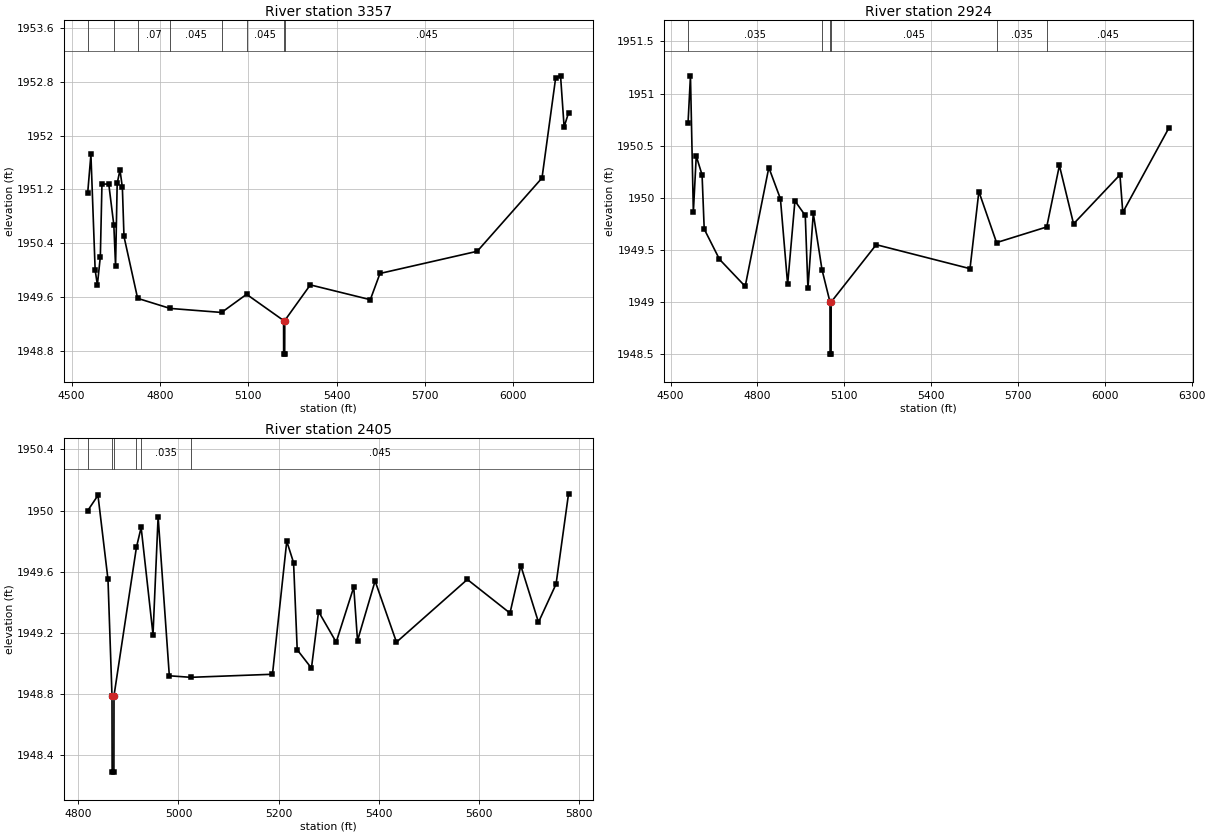
Type RM Length L Ch R = 1,3357,433,433,433
BEGIN DESCRIPTION:
UCFB HW Trib 04-13 2.0
END DESCRIPTION:
XS GIS Cut Line= 4
      1362394.91      7003353.44      1362084.88      7003493.61
      1361936.60      7003818.40      1362317.86      7004672.71
#Sta/Elev= 30
  4554.6 1951.15  4565.5 1951.72  4579.9 1950.00  4587.4 1949.78  4597.5 1950.20
  4603.0 1951.28  4626.1 1951.28  4643.3 1950.67  4649.2 1950.06  4654.7 1951.29
  4664.2 1951.49  4672.3 1951.23  4677.8 1950.50  4724.1 1949.58  4834.2 1949.43
  5009.3 1949.37  5094.1 1949.64  5219.8 1949.25  5220.0 1948.75  5223.5 1948.75
  5223.8 1949.25  5310.5 1949.78  5514.3 1949.56  5547.1 1949.95  5877.4 1950.28
  6097.3 1951.37  6143.7 1952.86  6160.3 1952.89  6172.4 1952.13  6187.4 1952.34
#Mann=8,-1,0
  4554.6    0.07       0  4643.3   0.035       0  4724.1    0.07       0
  4834.2   0.045       0  5009.3   0.035       0  5094.1   0.045       0
  5219.8   0.045       0  5223.8   0.045       0
Bank Sta=5219.8,5223.8
Exp/Cntr=0.3,0.1

Type RM Length L Ch R = 1,2924,519,519,519
BEGIN DESCRIPTION:
UCFB HW Trib 04-13 1.0
END DESCRIPTION:
XS GIS Cut Line= 4
      1362133.27      7003288.92      1361731.84      7003317.09
      1361618.87      7003606.58      1362098.21      7004424.27
#Sta/Elev= 30
  4560.3 1950.72  4568.6 1951.17  4578.6 1949.86  4588.6 1950.40  4608.7 1950.22
  4616.1 1949.70  4668.8 1949.41  4757.7 1949.15  4839.3 1950.29  4879.4 1949.99
  4904.3 1949.17  4929.5 1949.97  4965.2 1949.83  4974.4 1949.13  4992.9 1949.85
  5023.0 1949.31  5050.6 1949.00  5050.9 1948.50  5054.4 1948.50  5054.6 1949.00
  5210.3 1949.55  5534.3 1949.32  5564.9 1950.06  5626.0 1949.57  5799.3 1949.72
  5843.1 1950.31  5892.0 1949.75  6052.2 1950.22  6062.1 1949.86  6221.3 1950.67
#Mann=6,-1,0
  4560.3   0.035       0  5023.0   0.045       0  5050.6   0.035       0
  5054.6   0.045       0  5626.0   0.035       0  5799.3   0.045       0
Bank Sta=5050.6,5054.6
Exp/Cntr=0.3,0.1

Type RM Length L Ch R = 1,2405,0,0,0
BEGIN DESCRIPTION:
UCFB HW Trib 04-13 0.5
END DESCRIPTION:
XS GIS Cut Line= 4
      1361355.48      7003167.88      1361250.65      7003163.00
      1361212.45      7003356.25      1361648.52      7003849.36
#Sta/Elev= 30
  4818.8 1950.00  4839.3 1950.10  4859.3 1949.55  4867.3 1948.79  4867.6 1948.29
  4871.1 1948.29  4871.3 1948.79  4916.1 1949.76  4925.5 1949.89  4949.2 1949.19
  4959.4 1949.96  4981.8 1948.92  5024.7 1948.91  5187.8 1948.93  5216.3 1949.80
  5229.9 1949.66  5237.2 1949.09  5265.6 1948.97  5279.8 1949.34  5315.0 1949.14
  5350.1 1949.50  5357.6 1949.15  5392.7 1949.54  5435.4 1949.14  5576.9 1949.55
  5662.1 1949.33  5683.7 1949.64  5719.0 1949.27  5754.1 1949.52  5779.0 1950.11
#Mann=6,-1,0
  4818.8   0.035       0  4867.3   0.035       0  4871.3   0.035       0
  4916.1   0.045       0  4925.5   0.035       0  5024.7   0.045       0
Bank Sta=4867.3,4871.3
Exp/Cntr=0.3,0.1

Chan Stop Cuts=-1