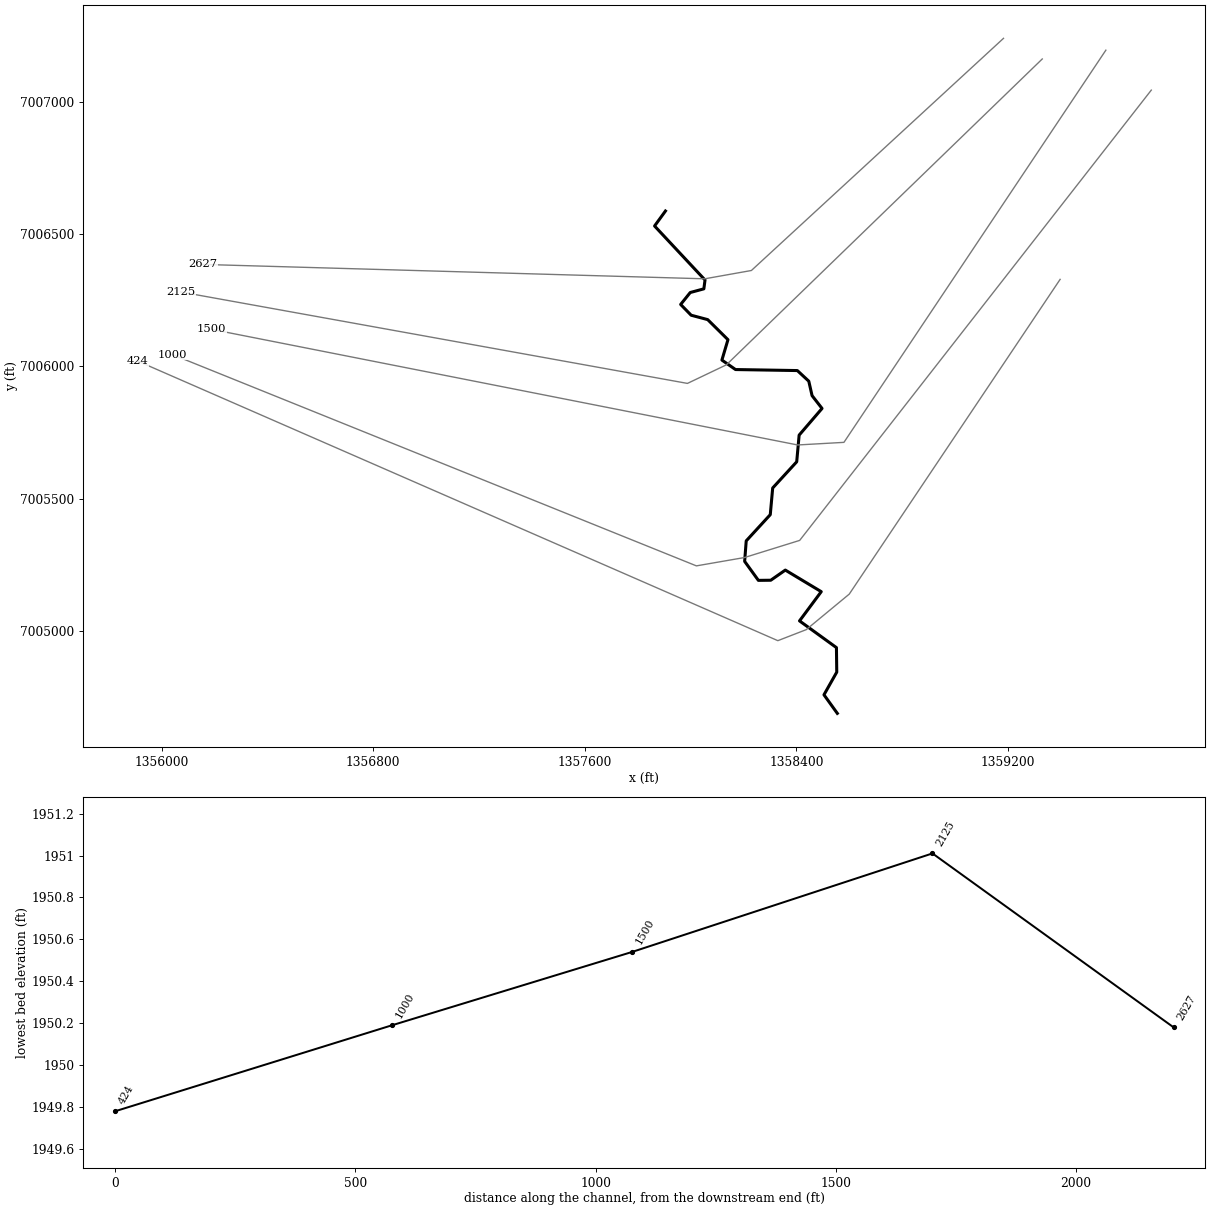
--- UCFB HW Trib 04-14.prj (project) ---

Proj Title=UCFB HW Trib 04-14 Base Level Engineering
Current Plan=p01
Default Exp/Contr=0.3,0.1
English Units
Geom File=g01
Flow File=f01
Plan File=p01
BEGIN DESCRIPTION:
UCFB HW Trib 04-14
END DESCRIPTION:

--- UCFB HW Trib 04-14.p01 (plan) ---

Plan Title=Multiple Run
Short Identifier=Multiple
Geom File=g01
Flow File=f01
Subcritical Flow
K Sum by GR= 0
Std Step Tol= 0.01
Critical Tol= 0.01
Num of Std Step Trials= 20
Max Error Tol= 0.3
Flow Tol Ratio= 0.001
Split Flow NTrial= 30
Split Flow Tol= 0.02
Split Flow Ratio= 0.02
Log Output Level= 0
Friction Slope Method= 1
Unsteady Friction Slope Method= 2
Unsteady Bridges Friction Slope Method= 1
Parabolic Critical Depth
Global Vel Dist=  1 , 1 , 1
Global Log Level= 0
CheckData=True
Encroach Param= -1, 0, 0, 0
BEGIN DESCRIPTION:
Multiple Run
END DESCRIPTION:

--- UCFB HW Trib 04-14.f01 (steady flow) ---

Flow Title=Multiple
Number of Profiles=7
Profile Names=10-year,25-year,50-year,1pct_min,100-year,1pct_plu,500-year
River Rch & RM= UCFB HW Trib 04-,Reach-1,2627
     105     136     160      93     185     370     253
Boundary for River Rch & Prof#=UCFB HW Trib 04-,Reach-1,1
Up Type=0
Dn Type=3
Dn Slope=0.005
Boundary for River Rch & Prof#=UCFB HW Trib 04-,Reach-1,2
Up Type=0
Dn Type=3
Dn Slope=0.005
Boundary for River Rch & Prof#=UCFB HW Trib 04-,Reach-1,3
Up Type=0
Dn Type=3
Dn Slope=0.005
Boundary for River Rch & Prof#=UCFB HW Trib 04-,Reach-1,4
Up Type=0
Dn Type=3
Dn Slope=0.005
Boundary for River Rch & Prof#=UCFB HW Trib 04-,Reach-1,5
Up Type=0
Dn Type=3
Dn Slope=0.005
Boundary for River Rch & Prof#=UCFB HW Trib 04-,Reach-1,6
Up Type=0
Dn Type=3
Dn Slope=0.005
Boundary for River Rch & Prof#=UCFB HW Trib 04-,Reach-1,7
Up Type=0
Dn Type=3
Dn Slope=0.005

--- UCFB HW Trib 04-14.g01 (geometry) ---

Geom Title=Existing Conditions

River Reach=UCFB HW Trib 04-,Reach-1
Reach XY= 30
      1357905.00      7006588.00      1357863.77      7006531.33
      1358054.60      7006326.98      1358050.19      7006293.62
      1357998.68      7006279.70      1357962.44      7006234.59
      1358002.14      7006193.87      1358064.69      7006177.22
      1358141.36      7006101.35      1358118.47      7006024.24
      1358169.89      7005988.38      1358403.75      7005984.55
      1358447.02      7005944.38      1358459.48      7005889.68
      1358497.16      7005841.24      1358410.55      7005740.43
      1358401.37      7005639.50      1358310.54      7005540.42
      1358301.37      7005439.50      1358210.41      7005340.42
      1358204.46      7005262.86      1358256.40      7005191.06
      1358303.32      7005191.56      1358358.31      7005229.93
      1358494.17      7005148.32      1358412.01      7005037.79
      1358551.63      7004936.72      1358552.83      7004843.97
      1358504.45      7004758.21      1358555.00      7004688.00

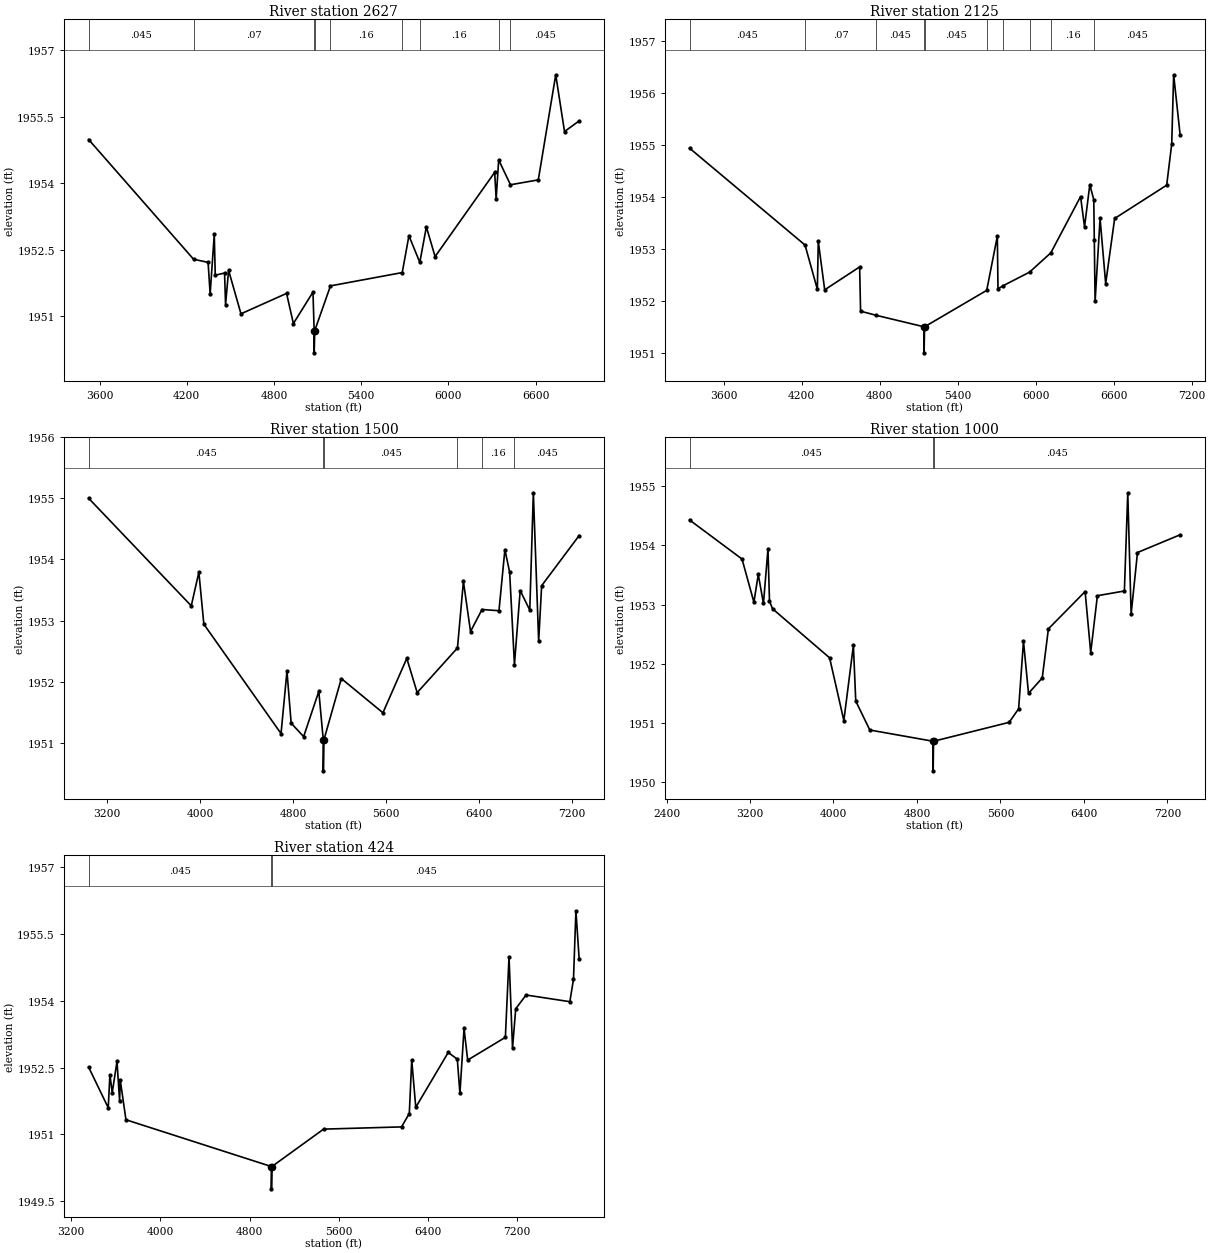
Type RM Length L Ch R = 1,2627,502,502,502
BEGIN DESCRIPTION:
UCFB HW Trib 04-14 5.0
END DESCRIPTION:
XS GIS Cut Line= 4
      1359183.49      7007241.05      1358230.00      7006363.00
      1358053.57      7006331.57      1356153.95      7006386.03
#Sta/Elev= 30
  3524.6 1954.99  4247.0 1952.29  4346.7 1952.22  4360.9 1951.51  4389.2 1952.85
  4396.0 1951.93  4460.1 1951.98  4466.9 1951.27  4487.9 1952.04  4573.0 1951.06
  4886.8 1951.52  4933.7 1950.84  5068.6 1951.55  5076.6 1950.68  5076.9 1950.18
  5080.6 1950.68  5189.0 1951.69  5682.9 1951.99  5728.9 1952.82  5803.8 1952.22
  5848.9 1953.02  5908.9 1952.35  6319.1 1954.25  6329.1 1953.65  6346.7 1954.53
  6427.6 1953.97  6619.2 1954.08  6739.3 1956.45  6799.6 1955.17  6900.4 1955.41
#Mann=9,-1,0
  3524.6   0.045       0  4247.0    0.07       0  5076.6    0.07       0
  5080.6    0.07       0  5189.0    0.16       0  5682.9    0.07       0
  5803.8    0.16       0  6346.7    0.07       0  6427.6   0.045       0
Bank Sta=5076.6,5080.6
Exp/Cntr=0.3,0.1

Type RM Length L Ch R = 1,2125,625,625,625
BEGIN DESCRIPTION:
UCFB HW Trib 04-14 4.0
END DESCRIPTION:
XS GIS Cut Line= 4
      1359330.02      7007163.02      1358135.41      7006006.24
      1357988.13      7005935.96      1356071.49      7006281.86
#Sta/Elev= 30
  3337.1 1954.94  4225.4 1953.08  4320.1 1952.23  4327.2 1953.15  4376.6 1952.22
  4645.4 1952.66  4652.6 1951.81  4773.9 1951.73  5140.9 1951.51  5141.2 1951.01
  5144.9 1951.51  5623.1 1952.21  5704.7 1953.25  5709.8 1952.24  5750.3 1952.30
  5952.6 1952.56  6116.2 1952.93  6345.1 1954.01  6375.6 1953.43  6416.2 1954.24
  6446.7 1953.95  6450.8 1953.17  6456.9 1952.00  6495.1 1953.59  6538.2 1952.34
  6607.3 1953.59  7007.6 1954.23  7046.3 1955.02  7061.2 1956.35  7110.8 1955.20
#Mann=10,-1,0
  3337.1   0.045       0  4225.4    0.07       0  4773.9   0.045       0
  5140.9   0.045       0  5144.9   0.045       0  5623.1    0.07       0
  5750.3    0.16       0  5952.6    0.07       0  6116.2    0.16       0
  6450.8   0.045       0
Bank Sta=5140.9,5144.9
Exp/Cntr=0.3,0.1

Type RM Length L Ch R = 1,1500,500,500,500
BEGIN DESCRIPTION:
UCFB HW Trib 04-14 3.0
END DESCRIPTION:
XS GIS Cut Line= 4
      1359570.59      7007196.30      1358580.00      7005713.00
      1358404.84      7005703.13      1356188.57      7006140.45
#Sta/Elev= 30
  3040.9 1955.00  3923.5 1953.24  3988.8 1953.79  4031.6 1952.94  4695.4 1951.15
  4746.4 1952.17  4782.5 1951.32  4889.7 1951.10  5020.2 1951.84  5059.0 1951.04
  5059.2 1950.54  5063.0 1951.04  5213.9 1952.05  5571.6 1951.49  5776.9 1952.38
  5866.2 1951.82  6212.5 1952.55  6263.7 1953.64  6324.9 1952.82  6423.8 1953.18
  6569.5 1953.16  6620.5 1954.16  6661.3 1953.79  6702.6 1952.28  6751.8 1953.49
  6834.5 1953.17  6865.1 1955.09  6910.8 1952.66  6936.5 1953.57  7259.0 1954.39
#Mann=6,-1,0
  3040.9   0.045       0  5059.0   0.045       0  5063.0   0.045       0
  6212.5    0.07       0  6423.8    0.16       0  6702.6   0.045       0
Bank Sta=5059,5063
Exp/Cntr=0.3,0.1

Type RM Length L Ch R = 1,1000,576,576,576
BEGIN DESCRIPTION:
UCFB HW Trib 04-14 2.0
END DESCRIPTION:
XS GIS Cut Line= 5
      1359742.46      7007045.24      1358412.61      7005342.21
      1358204.17      7005277.47      1358021.98      7005245.86
      1356039.79      7006045.18
#Sta/Elev= 30
  2621.0 1954.43  3123.7 1953.77  3237.6 1953.04  3279.3 1953.51  3329.0 1953.02
  3372.4 1953.94  3386.9 1953.06  3415.8 1952.93  3963.0 1952.10  4099.6 1951.04
  4191.0 1952.31  4213.6 1951.37  4348.3 1950.88  4955.3 1950.69  4955.5 1950.19
  4959.3 1950.69  5684.2 1951.01  5774.7 1951.24  5821.1 1952.38  5869.4 1951.50
  6001.0 1951.76  6060.0 1952.59  6411.8 1953.22  6465.5 1952.19  6529.5 1953.15
  6788.2 1953.23  6820.6 1954.89  6852.9 1952.84  6913.8 1953.88  7322.2 1954.18
#Mann=3,-1,0
  2621.0   0.045       0  4955.3   0.045       0  4959.3   0.045       0
Bank Sta=4955.3,4959.3
Exp/Cntr=0.3,0.1

Type RM Length L Ch R = 1,424,0,0,0
BEGIN DESCRIPTION:
UCFB HW Trib 04-14 1.0
END DESCRIPTION:
XS GIS Cut Line= 5
      1359397.62      7006329.48      1358600.11      7005139.09
      1358437.41      7005004.66      1358330.00      7004963.00
      1355908.31      7006020.69
#Sta/Elev= 30
  3356.1 1952.51  3532.0 1951.60  3547.0 1952.34  3568.0 1951.94  3610.7 1952.64
  3634.0 1951.75  3640.0 1952.22  3691.0 1951.33  4996.3 1950.28  4996.6 1949.78
  5000.3 1950.28  5464.7 1951.12  6163.7 1951.17  6233.7 1951.47  6255.5 1952.67
  6291.6 1951.61  6582.9 1952.84  6664.5 1952.69  6687.9 1951.92  6724.8 1953.38
  6757.5 1952.67  7095.8 1953.18  7128.5 1954.99  7159.9 1952.94  7188.7 1953.82
  7281.3 1954.13  7674.1 1953.98  7706.9 1954.48  7728.7 1956.02  7757.8 1954.94
#Mann=3,-1,0
  3356.1   0.045       0  4996.3   0.045       0  5000.3   0.045       0
Bank Sta=4996.3,5000.3
Exp/Cntr=0.3,0.1

Chan Stop Cuts=-1