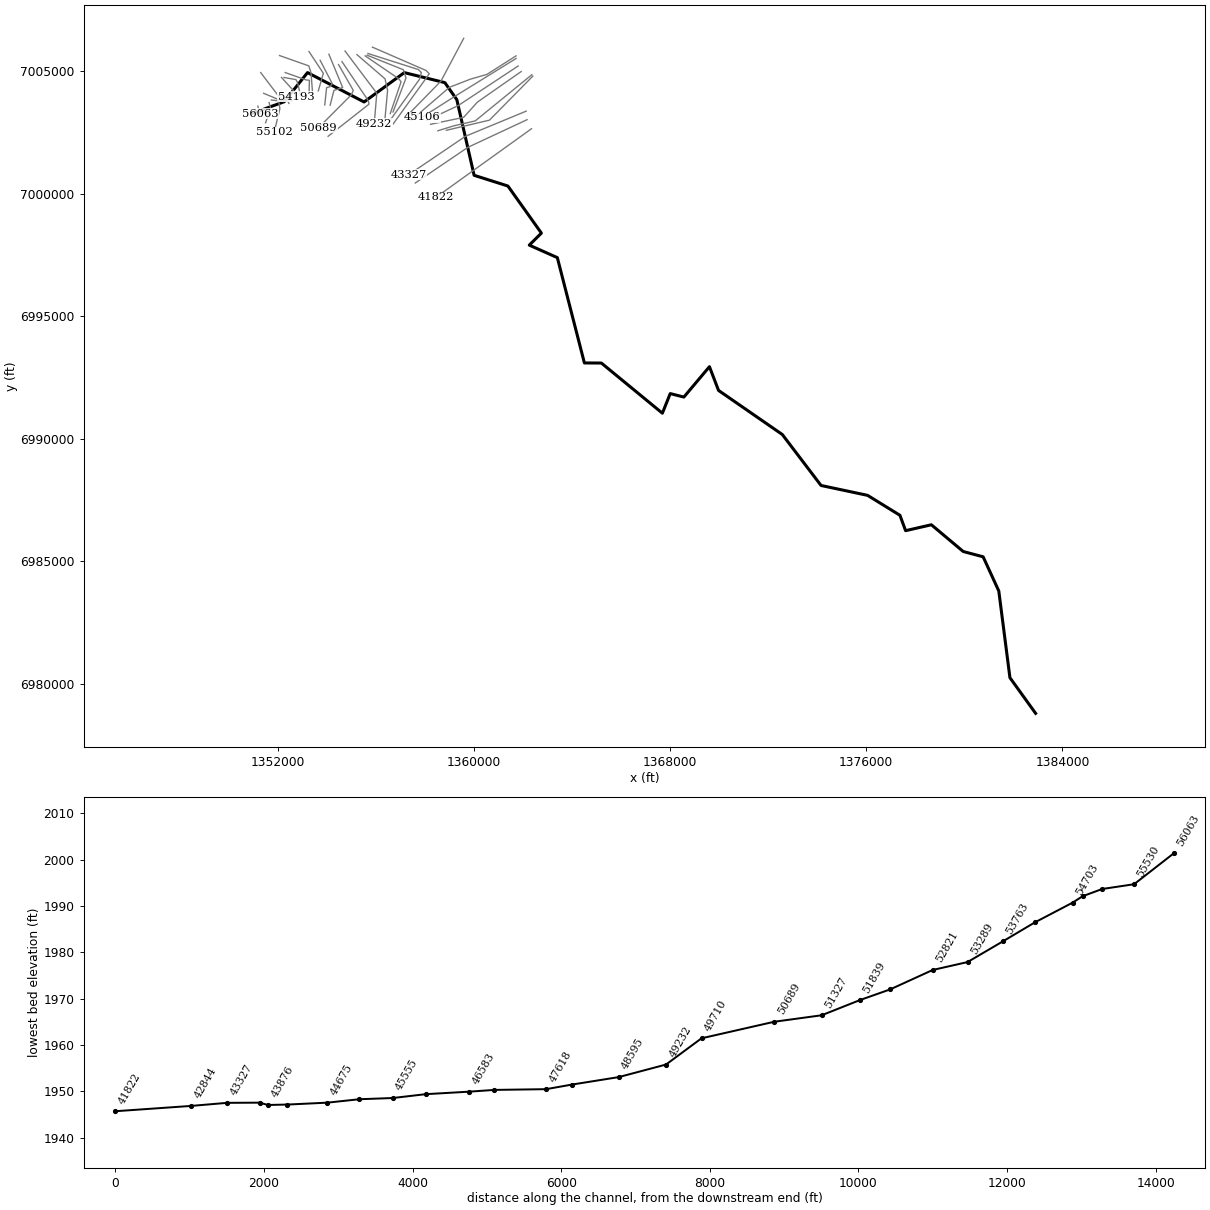
--- UCFB HW Trib 04.prj (project) ---

Proj Title=UCFB HW Trib 04 Base Level Engineering
Current Plan=p01
Default Exp/Contr=0.3,0.1
English Units
Geom File=g01
Flow File=f01
Plan File=p01
Y Axis Title=Elevation
X Axis Title(PF)=Main Channel Distance
X Axis Title(XS)=Station
BEGIN DESCRIPTION:
UCFB HW Trib 04
END DESCRIPTION:
DSS Export Rating Curves= 0
DSS Export Rating Curve Sorted= 0
DSS Export Volume Flow Curves= 0
DXF OffsetX= 0
DXF OffsetY= 0
DXF ScaleX= 1
DXF ScaleY= 10

--- UCFB HW Trib 04.p01 (plan) ---

Plan Title=Multiple Run
Short Identifier=Multiple
Geom File=g01
Flow File=f01
Subcritical Flow
K Sum by GR= 0
Std Step Tol= 0.01
Critical Tol= 0.01
Num of Std Step Trials= 20
Max Error Tol= 0.3
Flow Tol Ratio= 0.001
Split Flow NTrial= 30
Split Flow Tol= 0.02
Split Flow Ratio= 0.02
Log Output Level= 0
Friction Slope Method= 1
Unsteady Friction Slope Method= 2
Unsteady Bridges Friction Slope Method= 1
Parabolic Critical Depth
Global Vel Dist=  1 , 1 , 1
Global Log Level= 0
CheckData=True
Encroach Param= -1, 0, 0, 0
BEGIN DESCRIPTION:
Multiple Run
END DESCRIPTION:

--- UCFB HW Trib 04.f01 (steady flow) ---

Flow Title=Multiple
Program Version=4.10
Number of Profiles= 7
Profile Names=10-year,25-year,50-year,1pct_min,100-year,1pct_plu,500-year
River Rch & RM=UCFB HW Trib 04,Reach-1         ,56063
     248     347     430     265     528    1054     808
River Rch & RM=UCFB HW Trib 04,Reach-1         ,47970
     312     443     553     343     684    1366    1063
River Rch & RM=UCFB HW Trib 04,Reach-1         ,45999
     442     639     808     506    1011    2016    1604
River Rch & RM=UCFB HW Trib 04,Reach-1         ,45555
     717    1060    1359     864    1724    3441    2813
River Rch & RM=UCFB HW Trib 04,Reach-1         ,41822
     793    1174    1506     958    1911    3813    3118
River Rch & RM=UCFB HW Trib 04,Reach-1         ,39839
     801    1186    1522     968    1931    3853    3151
River Rch & RM=UCFB HW Trib 04,Reach-1         ,36807
     895    1331    1714    1093    2180    4350    3578
River Rch & RM=UCFB HW Trib 04,Reach-1         ,35080
    1433    2169    2825    1820    3632    7246    6086
River Rch & RM=UCFB HW Trib 04,Reach-1         ,33380
    1669    2536    3312    2138    4266    8512    7180
River Rch & RM=UCFB HW Trib 04,Reach-1         ,32831
    1745    2652    3465    2237    4464    8906    7513
River Rch & RM=UCFB HW Trib 04,Reach-1         ,29007
    1898    2891    3782    2446    4880    9737    8237
River Rch & RM=UCFB HW Trib 04,Reach-1         ,25191
    1938    2950    3859    2494    4976    9928    8390
River Rch & RM=UCFB HW Trib 04,Reach-1         ,22843
    1998    3038    3971    2564    5117   10209    8612
River Rch & RM=UCFB HW Trib 04,Reach-1         ,18829
    2024    3072    4012    2587    5162   10300    8667
River Rch & RM=UCFB HW Trib 04,Reach-1         ,15504
    2105    3193    4166    2685    5357   10688    8977
River Rch & RM=UCFB HW Trib 04,Reach-1         ,11640
    2096    3177    4142    2667    5322   10618    8905
River Rch & RM=UCFB HW Trib 04,Reach-1         ,7233
    2267    3438    4486    2891    5767   11507    9661
River Rch & RM=UCFB HW Trib 04,Reach-1         ,4346
    2383    3620    4728    3049    6083   12137   10207
Boundary for River Rch & Prof#=UCFB HW Trib 04,Reach-1         , 1
Up Type= 0
Dn Type= 3
Dn Slope=0.002
Boundary for River Rch & Prof#=UCFB HW Trib 04,Reach-1         , 2
Up Type= 0
Dn Type= 3
Dn Slope=0.002
Boundary for River Rch & Prof#=UCFB HW Trib 04,Reach-1         , 3
Up Type= 0
Dn Type= 3
Dn Slope=0.002
Boundary for River Rch & Prof#=UCFB HW Trib 04,Reach-1         , 4
Up Type= 0
Dn Type= 3
Dn Slope=0.002
Boundary for River Rch & Prof#=UCFB HW Trib 04,Reach-1         , 5
Up Type= 0
Dn Type= 3
Dn Slope=0.002
Boundary for River Rch & Prof#=UCFB HW Trib 04,Reach-1         , 6
Up Type= 0
Dn Type= 3
Dn Slope=0.002
Boundary for River Rch & Prof#=UCFB HW Trib 04,Reach-1         , 7
Up Type= 0
Dn Type= 3
Dn Slope=0.002
DSS Import GetInterval= 0
DSS Import GetPeak= 0
DSS Import FillOption= 0

--- UCFB HW Trib 04.g01 (geometry) ---

Geom Title=Existing Conditions

River Reach=UCFB HW Trib 04,Reach-1
Reach XY= 30
      1351005.00      7003288.00      1352265.22      7003748.39
      1353215.27      7004937.04      1355520.76      7003737.88
      1357160.84      7004935.95      1358814.68      7004527.24
      1359302.74      7003832.06      1360007.92      7000745.91
      1361385.23      7000308.42      1362751.46      6998386.54
      1362257.50      6997895.95      1363401.26      6997386.48
      1364505.00      6993088.00      1365196.85      6993084.63
      1367684.92      6991037.39      1368005.00      6991838.00
      1368561.19      6991695.81      1369604.33      6992936.39
      1369974.59      6991966.90      1372575.09      6990168.22
      1374155.00      6988088.00      1376053.53      6987684.46
      1377371.77      6986871.57      1377602.69      6986243.82
      1378653.54      6986484.46      1379952.57      6985393.52
      1380764.71      6985177.30      1381402.94      6983782.15
      1381857.06      6980243.85      1382905.00      6978788.00

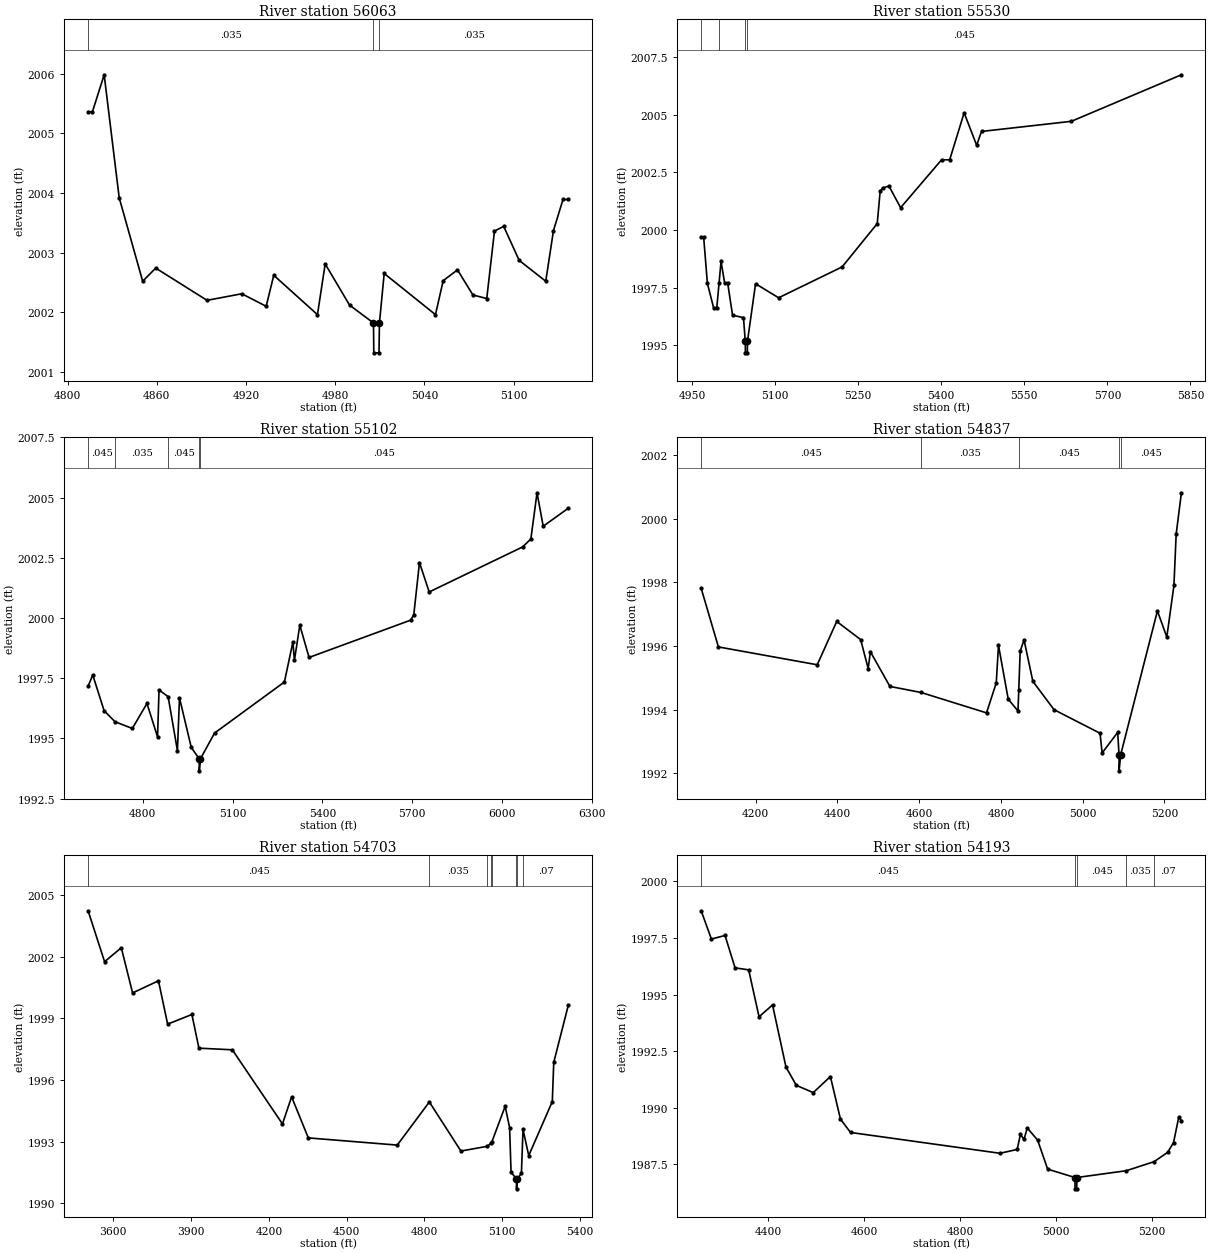
Type RM Length L Ch R = 1,56063,533,533,533
BEGIN DESCRIPTION:
UCFB HW Trib 04 66.0
END DESCRIPTION:
XS GIS Cut Line= 3
      1351193.05      7003568.70      1351198.06      7003531.75
      1351273.35      7003256.03
#Sta/Elev= 30
  4813.8 2005.36  4816.7 2005.36  4824.6 2005.98  4834.7 2003.92  4850.5 2002.52
  4859.3 2002.74  4893.8 2002.20  4917.2 2002.31  4933.6 2002.10  4938.7 2002.62
  4968.1 2001.96  4973.3 2002.81  4989.7 2002.12  5005.8 2001.82  5006.0 2001.32
  5009.5 2001.32  5009.8 2001.82  5013.0 2002.65  5047.5 2001.96  5052.7 2002.53
  5062.3 2002.71  5072.7 2002.29  5082.0 2002.23  5087.2 2003.36  5093.4 2003.44
  5103.8 2002.87  5121.7 2002.52  5126.9 2003.37  5133.3 2003.89  5136.9 2003.89
#Mann=3,-1,0
  4813.8   0.035       0  5005.8   0.035       0  5009.8   0.035       0
Bank Sta=5005.8,5009.8
Exp/Cntr=0.3,0.1

Type RM Length L Ch R = 1,55530,428,428,428
BEGIN DESCRIPTION:
UCFB HW Trib 04 65.0
END DESCRIPTION:
XS GIS Cut Line= 4
      1351644.41      7003711.19      1351655.00      7003688.00
      1351710.35      7003492.30      1351505.00      7002888.00
#Sta/Elev= 30
  4966.5 1999.69  4971.0 1999.69  4977.7 1997.69  4989.2 1996.60  4994.6 1996.60
  4998.8 1997.70  5002.4 1998.64  5009.0 1997.68  5014.2 1997.72  5023.2 1996.30
  5042.9 1996.20  5046.1 1995.17  5046.4 1994.67  5049.9 1994.67  5050.1 1995.17
  5064.7 1997.67  5106.3 1997.06  5221.0 1998.40  5284.4 2000.28  5289.7 2001.69
  5295.0 2001.83  5305.5 2001.91  5326.6 2000.97  5400.6 2003.05  5415.2 2003.05
  5441.3 2005.09  5463.9 2003.68  5472.7 2004.28  5634.9 2004.72  5833.6 2006.74
#Mann=4,-1,0
  4966.5   0.035       0  4998.8   0.045       0  5046.1   0.045       0
  5050.1   0.045       0
Bank Sta=5046.1,5050.1
Exp/Cntr=0.3,0.1

Type RM Length L Ch R = 1,55102,265,265,265
BEGIN DESCRIPTION:
UCFB HW Trib 04 64.0
END DESCRIPTION:
XS GIS Cut Line= 5
      1351739.64      7003819.39      1352009.64      7003788.47
      1352055.00      7003688.00      1352087.95      7003461.92
      1351853.48      7002496.35
#Sta/Elev= 30
  4617.6 1997.17  4633.1 1997.63  4671.0 1996.15  4707.4 1995.69  4765.3 1995.41
  4814.2 1996.45  4849.5 1995.06  4854.5 1997.01  4884.9 1996.73  4915.9 1994.49
  4922.8 1996.68  4962.2 1994.62  4988.8 1994.15  4989.0 1993.65  4992.8 1994.15
  5040.0 1995.22  5273.3 1997.34  5301.6 1999.00  5306.7 1998.24  5324.7 1999.70
  5355.6 1998.36  5695.2 1999.91  5705.5 2000.14  5724.4 2002.30  5756.9 2001.08
  6068.9 2002.95  6096.5 2003.28  6117.1 2005.20  6137.7 2003.81  6221.7 2004.56
#Mann=5,-1,0
  4617.6   0.045       0  4707.4   0.035       0  4884.9   0.045       0
  4988.8   0.045       0  4992.8   0.045       0
Bank Sta=4988.8,4992.8
Exp/Cntr=0.3,0.1

Type RM Length L Ch R = 1,54837,134,134,134
BEGIN DESCRIPTION:
UCFB HW Trib 04 63.5
END DESCRIPTION:
XS GIS Cut Line= 4
      1351425.37      7004090.97      1352225.71      7003758.51
      1352401.54      7003797.93      1352455.39      7003681.41
#Sta/Elev= 30
  4066.5 1997.81  4108.7 1995.97  4350.5 1995.41  4398.2 1996.77  4456.8 1996.20
  4475.2 1995.29  4480.6 1995.82  4528.4 1994.73  4604.6 1994.54  4764.8 1993.90
  4788.6 1994.84  4794.1 1996.02  4817.9 1994.33  4841.8 1993.96  4843.7 1994.62
  4847.2 1995.84  4856.6 1996.19  4878.2 1994.89  4930.0 1994.00  5042.6 1993.26
  5047.7 1992.64  5085.9 1993.29  5089.0 1992.58  5089.3 1992.08  5093.0 1992.58
  5183.0 1997.10  5206.0 1996.28  5223.4 1997.90  5228.9 1999.51  5241.7 2000.81
#Mann=5,-1,0
  4066.5   0.045       0  4604.6   0.035       0  4843.7   0.045       0
  5089.0   0.045       0  5093.0   0.045       0
Bank Sta=5089,5093
Exp/Cntr=0.3,0.1

Type RM Length L Ch R = 1,54703,510,510,510
BEGIN DESCRIPTION:
UCFB HW Trib 04 63.0
END DESCRIPTION:
XS GIS Cut Line= 5
      1351304.99      7004938.02      1352125.18      7003857.77
      1352255.00      7003888.00      1352316.16      7003896.83
      1352588.48      7003767.72
#Sta/Elev= 30
  3502.8 2004.24  3566.3 2001.76  3630.8 2002.44  3674.4 2000.24  3774.2 2000.83
  3809.6 1998.72  3903.2 1999.19  3930.3 1997.55  4059.2 1997.47  4252.6 1993.86
  4287.9 1995.18  4352.4 1993.18  4695.5 1992.83  4819.3 1994.93  4941.1 1992.54
  5042.4 1992.77  5057.2 1992.92  5060.3 1992.98  5111.8 1994.72  5129.0 1993.68
  5134.6 1991.50  5155.3 1991.20  5155.6 1990.70  5159.3 1991.20  5174.5 1991.45
  5180.7 1993.59  5202.8 1992.32  5293.7 1994.95  5299.3 1996.86  5355.6 1999.65
#Mann=8,-1,0
  3502.8   0.045       0  4819.3   0.035       0  5042.4   0.045       0
  5057.2   0.035       0  5060.3   0.045       0  5155.3   0.035       0
  5159.3   0.045       0  5180.7    0.07       0
Bank Sta=5155.3,5159.3
Exp/Cntr=0.3,0.1

Type RM Length L Ch R = 1,54193,430,430,430
BEGIN DESCRIPTION:
UCFB HW Trib 04 62.0
END DESCRIPTION:
XS GIS Cut Line= 3
      1352154.99      7004738.01      1352655.00      7004188.00
      1352759.99      7003953.01
#Sta/Elev= 30
  4260.9 1998.70  4282.2 1997.45  4310.6 1997.61  4331.5 1996.18  4359.9 1996.09
  4381.5 1994.02  4409.6 1994.54  4437.6 1991.80  4459.2 1990.99  4494.4 1990.67
  4530.2 1991.38  4551.1 1989.50  4572.1 1988.91  4883.6 1987.99  4919.4 1988.16
  4926.2 1988.83  4933.6 1988.60  4940.4 1989.11  4962.0 1988.57  4982.9 1987.29
  5039.8 1986.92  5040.0 1986.42  5043.5 1986.42  5043.8 1986.92  5146.7 1987.22
  5204.7 1987.62  5232.9 1988.03  5245.2 1988.46  5256.1 1989.59  5261.6 1989.43
#Mann=5,-1,0
  4260.9   0.045       0  5039.8   0.045       0  5043.8   0.045       0
  5146.7   0.035       0  5204.7    0.07       0
Bank Sta=5039.8,5043.8
Exp/Cntr=0.3,0.1

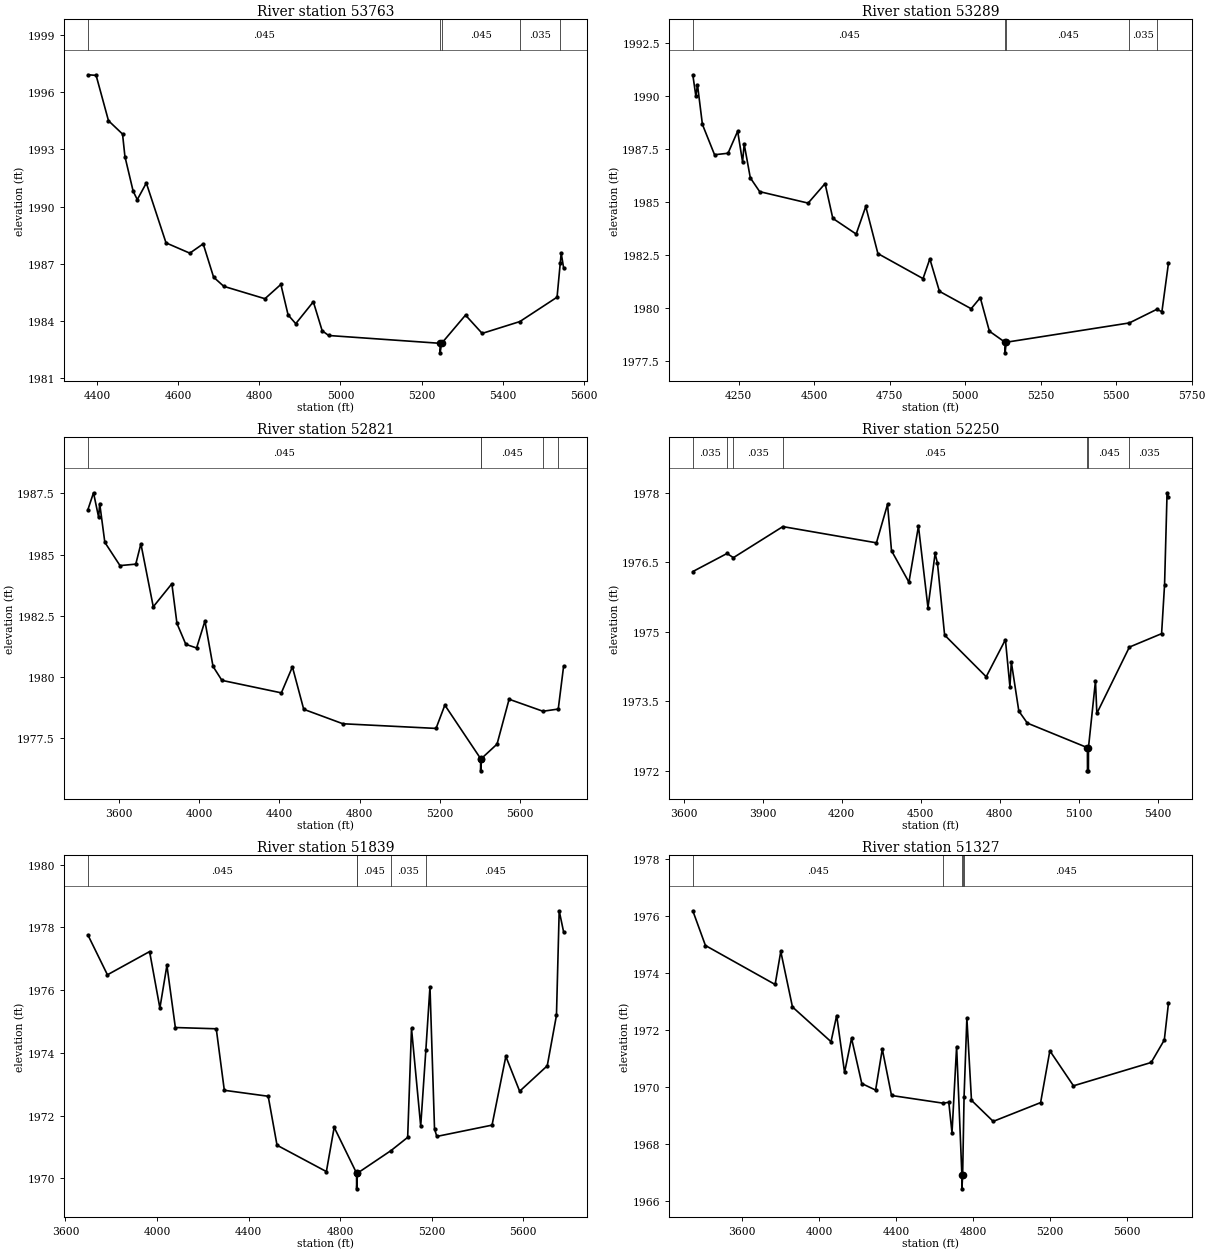
Type RM Length L Ch R = 1,53763,474,474,474
BEGIN DESCRIPTION:
UCFB HW Trib 04 61.0
END DESCRIPTION:
XS GIS Cut Line= 4
      1352255.04      7004737.99      1352742.47      7004650.29
      1352805.00      7004538.00      1352929.69      7004002.30
#Sta/Elev= 30
  4376.7 1996.92  4397.0 1996.89  4427.5 1994.51  4462.2 1993.81  4468.1 1992.63
  4488.4 1990.81  4498.6 1990.37  4520.9 1991.24  4569.5 1988.10  4628.2 1987.56
  4661.2 1988.05  4686.9 1986.30  4712.0 1985.82  4813.6 1985.17  4852.9 1985.92
  4870.7 1984.32  4889.6 1983.86  4933.0 1985.01  4954.8 1983.49  4970.8 1983.24
  5245.6 1982.83  5245.8 1982.33  5249.6 1982.83  5308.5 1984.31  5349.6 1983.35
  5442.5 1983.97  5534.4 1985.25  5542.3 1987.04  5544.6 1987.56  5550.5 1986.80
#Mann=5,-1,0
  4376.7   0.045       0  5245.6   0.045       0  5249.6   0.045       0
  5442.5   0.035       0  5542.3    0.07       0
Bank Sta=5245.6,5249.6
Exp/Cntr=0.3,0.1

Type RM Length L Ch R = 1,53289,468,468,468
BEGIN DESCRIPTION:
UCFB HW Trib 04 60.0
END DESCRIPTION:
XS GIS Cut Line= 4
      1352305.01      7004938.00      1353155.00      7004638.00
      1353291.08      7004622.51      1353277.08      7004086.23
#Sta/Elev= 30
  4098.5 1990.99  4108.7 1989.98  4114.0 1990.52  4130.3 1988.65  4170.5 1987.22
  4215.1 1987.29  4247.0 1988.33  4263.3 1986.88  4268.6 1987.72  4288.9 1986.13
  4319.9 1985.48  4480.3 1984.94  4536.4 1985.86  4562.0 1984.22  4639.3 1983.48
  4671.1 1984.78  4711.3 1982.56  4860.7 1981.38  4883.2 1982.31  4915.0 1980.78
  5020.0 1979.96  5050.2 1980.48  5080.4 1978.90  5132.1 1978.38  5132.4 1977.88
  5136.1 1978.38  5543.7 1979.29  5634.4 1979.93  5651.5 1979.82  5673.3 1982.12
#Mann=5,-1,0
  4098.5   0.045       0  5132.1   0.045       0  5136.1   0.045       0
  5543.7   0.035       0  5634.4   0.045       0
Bank Sta=5132.1,5136.1
Exp/Cntr=0.3,0.1

Type RM Length L Ch R = 1,52821,571,571,571
BEGIN DESCRIPTION:
UCFB HW Trib 04 59.0
END DESCRIPTION:
XS GIS Cut Line= 4
      1352073.75      7005632.46      1353267.81      7005210.36
      1353355.00      7004938.00      1353420.75      7004116.67
#Sta/Elev= 30
  3443.1 1986.83  3471.2 1987.52  3496.8 1986.52  3502.1 1987.08  3527.7 1985.50
  3603.5 1984.55  3682.3 1984.61  3707.9 1985.44  3769.7 1982.87  3862.5 1983.81
  3888.1 1982.19  3932.3 1981.34  3986.1 1981.19  4027.8 1982.29  4068.2 1980.44
  4112.6 1979.87  4409.6 1979.36  4464.8 1980.42  4521.3 1978.69  4717.0 1978.10
  5182.3 1977.91  5226.3 1978.86  5404.9 1976.68  5405.1 1976.18  5408.9 1976.68
  5487.1 1977.27  5547.3 1979.10  5716.4 1978.61  5792.9 1978.70  5819.5 1980.44
#Mann=5,-1,0
  3443.1   0.045       0  5404.9   0.045       0  5408.9   0.045       0
  5716.4   0.035       0  5792.9   0.045       0
Bank Sta=5404.9,5408.9
Exp/Cntr=0.3,0.1

Type RM Length L Ch R = 1,52250,411,411,411
BEGIN DESCRIPTION:
UCFB HW Trib 04 58.5
END DESCRIPTION:
XS GIS Cut Line= 3
      1353275.03      7005793.84      1353859.96      7004909.49
      1353654.75      7004192.77
#Sta/Elev= 30
  3635.2 1976.30  3765.1 1976.69  3789.3 1976.60  3977.0 1977.27  4332.3 1976.92
  4374.4 1977.75  4389.5 1976.75  4455.7 1976.07  4491.8 1977.28  4527.9 1975.52
  4555.0 1976.69  4564.0 1976.48  4591.1 1974.93  4749.0 1974.03  4821.9 1974.83
  4839.1 1973.81  4844.3 1974.35  4872.8 1973.29  4905.1 1973.03  5133.2 1972.50
  5133.5 1972.00  5137.0 1972.00  5137.2 1972.50  5163.8 1973.94  5169.0 1973.24
  5292.5 1974.67  5414.8 1974.96  5426.1 1976.02  5435.6 1978.00  5441.0 1977.90
#Mann=7,-1,0
  3635.2   0.035       0  3765.1   0.045       0  3789.3   0.035       0
  3977.0   0.045       0  5133.2   0.045       0  5137.2   0.045       0
  5292.5   0.035       0
Bank Sta=5133.2,5137.2
Exp/Cntr=0.3,0.1

Type RM Length L Ch R = 1,51839,512,512,512
BEGIN DESCRIPTION:
UCFB HW Trib 04 58.0
END DESCRIPTION:
XS GIS Cut Line= 5
      1353730.01      7005437.49      1354223.23      7004485.04
      1354129.48      7004361.34      1353992.76      7004322.28
      1353917.63      7003617.05
#Sta/Elev= 30
  3697.9 1977.76  3783.3 1976.49  3967.6 1977.23  4012.6 1975.43  4043.3 1976.79
  4080.2 1974.81  4259.0 1974.77  4294.2 1972.81  4486.0 1972.62  4524.6 1971.06
  4740.3 1970.22  4774.4 1971.63  4872.3 1970.17  4872.5 1969.67  4876.3 1970.17
  5023.0 1970.89  5095.6 1971.31  5112.4 1974.78  5152.6 1971.67  5175.0 1974.08
  5193.1 1976.11  5213.0 1971.58  5223.0 1971.34  5464.4 1971.70  5524.7 1973.89
  5585.1 1972.78  5705.7 1973.59  5746.0 1975.20  5757.9 1978.53  5777.1 1977.86
#Mann=5,-1,0
  3697.9   0.045       0  4872.3   0.045       0  4876.3   0.045       0
  5023.0   0.035       0  5175.0   0.045       0
Bank Sta=4872.3,4876.3
Exp/Cntr=0.3,0.1

Type RM Length L Ch R = 1,51327,638,638,638
BEGIN DESCRIPTION:
UCFB HW Trib 04 56.5
END DESCRIPTION:
XS GIS Cut Line= 4
      1354086.07      7005686.24      1354648.14      7004325.64
      1354291.37      7004209.76      1354137.54      7003606.92
#Sta/Elev= 30
  3344.3 1976.18  3409.9 1974.96  3771.7 1973.59  3801.0 1974.75  3861.7 1972.80
  4061.8 1971.58  4091.2 1972.50  4132.2 1970.50  4168.3 1971.70  4221.5 1970.11
  4293.3 1969.88  4328.0 1971.32  4375.9 1969.69  4643.4 1969.42  4673.2 1969.45
  4689.9 1968.38  4713.8 1971.41  4741.1 1966.91  4741.4 1966.41  4745.1 1966.91
  4752.5 1969.65  4767.0 1972.41  4791.0 1969.52  4903.8 1968.78  5149.8 1969.44
  5197.8 1971.26  5320.4 1970.03  5723.9 1970.85  5791.9 1971.64  5813.7 1972.94
#Mann=5,-1,0
  3344.3   0.045       0  4643.4   0.035       0  4741.1   0.045       0
  4745.1   0.035       0  4752.5   0.045       0
Bank Sta=4741.1,4745.1
Exp/Cntr=0.3,0.1

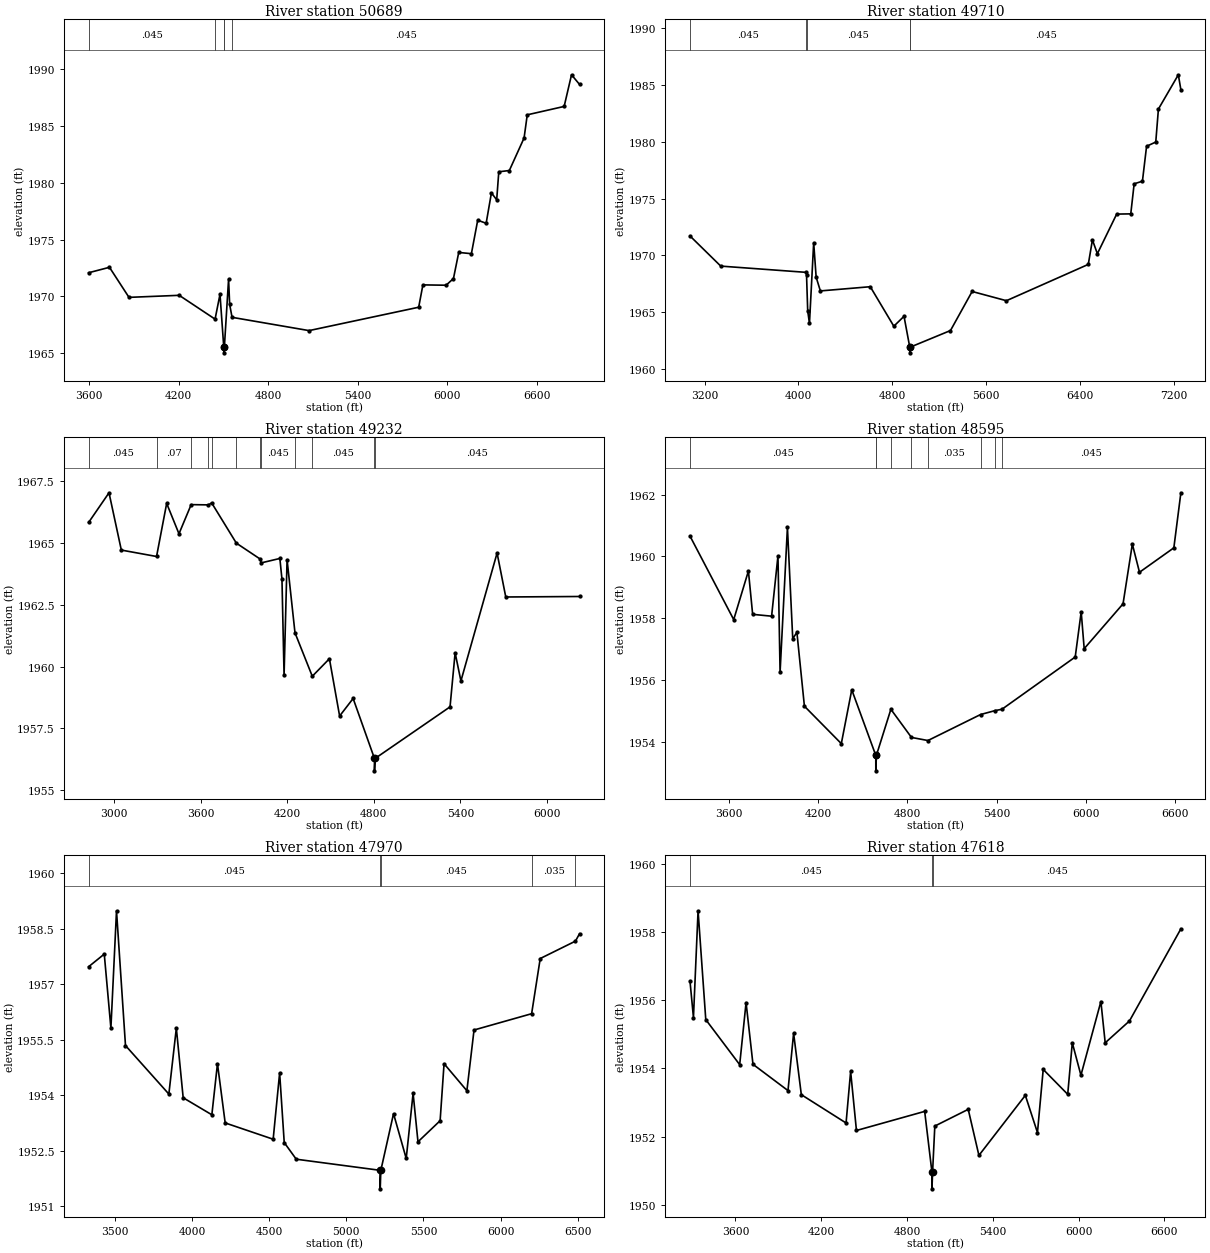
Type RM Length L Ch R = 1,50689,979,979,979
BEGIN DESCRIPTION:
UCFB HW Trib 04 57.5
END DESCRIPTION:
XS GIS Cut Line= 4
      1354480.01      7005262.99      1355080.00      7004213.00
      1355008.89      7004039.08      1353671.93      7002695.16
#Sta/Elev= 30
  3595.6 1972.07  3735.2 1972.55  3866.2 1969.90  4203.1 1970.08  4443.7 1967.98
  4476.7 1970.17  4502.0 1965.51  4502.3 1965.01  4506.0 1965.51  4534.3 1971.51
  4541.5 1969.28  4557.6 1968.14  5074.1 1966.97  5809.5 1969.03  5837.8 1971.00
  5993.4 1970.97  6042.8 1971.56  6078.2 1973.86  6163.1 1973.75  6205.5 1976.70
  6262.1 1976.43  6297.4 1979.11  6332.8 1978.50  6346.9 1980.97  6417.6 1981.08
  6516.6 1983.95  6537.8 1985.99  6785.3 1986.73  6834.8 1989.52  6888.5 1988.67
#Mann=5,-1,0
  3595.6   0.045       0  4443.7   0.035       0  4502.0   0.045       0
  4506.0   0.035       0  4557.6   0.045       0
Bank Sta=4502,4506
Exp/Cntr=0.3,0.1

Type RM Length L Ch R = 1,49710,478,478,478
BEGIN DESCRIPTION:
UCFB HW Trib 04 57.0
END DESCRIPTION:
XS GIS Cut Line= 4
      1354618.84      7005385.77      1355694.36      7003788.64
      1355720.94      7003647.86      1354054.99      7002337.99
#Sta/Elev= 30
  3074.5 1971.71  3337.0 1969.06  4067.9 1968.51  4068.7 1968.32  4078.8 1965.13
  4093.8 1964.02  4129.8 1971.12  4150.8 1968.09  4186.8 1966.88  4612.6 1967.25
  4813.5 1963.78  4900.5 1964.65  4949.5 1961.94  4949.7 1961.44  4953.5 1961.94
  5296.9 1963.40  5481.6 1966.83  5774.2 1966.02  6472.6 1969.21  6507.9 1971.36
  6550.1 1970.15  6714.8 1973.63  6835.0 1973.65  6863.9 1976.29  6934.5 1976.52
  6969.9 1979.59  7048.3 1979.96  7070.9 1982.86  7240.8 1985.87  7262.5 1984.56
#Mann=5,-1,0
  3074.5   0.045       0  4067.9   0.035       0  4068.7   0.045       0
  4949.5   0.045       0  4953.5   0.045       0
Bank Sta=4949.5,4953.5
Exp/Cntr=0.3,0.1

Type RM Length L Ch R = 1,49232,637,637,637
BEGIN DESCRIPTION:
UCFB HW Trib 04 56.8
END DESCRIPTION:
XS GIS Cut Line= 3
      1354744.27      7005814.73      1356039.45      7004094.79
      1355935.00      7002848.33
#Sta/Elev= 30
  2822.4 1965.84  2963.6 1967.04  3049.0 1964.72  3293.3 1964.46  3363.4 1966.61
  3448.7 1965.38  3533.3 1966.56  3653.3 1966.55  3675.4 1966.63  3846.7 1965.00
  4013.3 1964.35  4017.9 1964.20  4148.3 1964.38  4162.9 1963.54  4177.5 1959.65
  4198.3 1964.33  4253.2 1961.37  4373.2 1959.61  4491.9 1960.32  4562.7 1958.00
  4656.4 1958.71  4804.3 1956.28  4804.5 1955.78  4808.3 1956.28  5328.3 1958.37
  5363.6 1960.56  5403.8 1959.42  5654.6 1964.60  5714.8 1962.82  6226.3 1962.84
#Mann=12,-1,0
  2822.4   0.045       0  3293.3    0.07       0  3533.3   0.045       0
  3653.3    0.07       0  3675.4   0.035       0  3846.7   0.045       0
  4013.3   0.035       0  4017.9   0.045       0  4253.2   0.035       0
  4373.2   0.045       0  4804.3   0.045       0  4808.3   0.045       0
Bank Sta=4804.3,4808.3
Exp/Cntr=0.3,0.1

Type RM Length L Ch R = 1,48595,625,625,625
BEGIN DESCRIPTION:
UCFB HW Trib 04 56.6
END DESCRIPTION:
XS GIS Cut Line= 4
      1355231.73      7005668.47      1356374.56      7004684.49
      1356480.00      7004213.00      1356359.76      7002911.05
#Sta/Elev= 30
  3338.9 1960.66  3632.7 1957.96  3731.5 1959.53  3760.0 1958.13  3887.3 1958.07
  3930.1 1960.02  3944.3 1956.26  3993.7 1960.94  4029.4 1957.34  4057.3 1957.55
  4107.8 1955.16  4355.8 1953.95  4426.0 1955.69  4587.4 1953.57  4587.7 1953.07
  4591.5 1953.57  4688.9 1955.06  4827.2 1954.15  4937.9 1954.05  5291.4 1954.89
  5391.0 1955.02  5435.0 1955.06  5927.6 1956.75  5967.8 1958.21  5987.9 1957.02
  6249.0 1958.47  6311.5 1960.40  6359.5 1959.49  6590.4 1960.28  6637.6 1962.06
#Mann=9,-1,0
  3338.9   0.045       0  4587.4   0.035       0  4591.5   0.045       0
  4688.9   0.035       0  4827.2   0.045       0  4937.9   0.035       0
  5291.4   0.045       0  5391.0   0.035       0  5435.0   0.045       0
Bank Sta=4587.4,4591.5
Exp/Cntr=0.3,0.1

Type RM Length L Ch R = 1,47970,352,352,352
BEGIN DESCRIPTION:
UCFB HW Trib 04 56.4
END DESCRIPTION:
XS GIS Cut Line= 4
      1355565.95      7005619.74      1356930.75      7004686.67
      1357030.00      7004563.00      1356589.78      7003266.85
#Sta/Elev= 30
  3330.4 1957.47  3431.6 1957.81  3474.6 1955.81  3510.9 1958.98  3569.1 1955.34
  3850.1 1954.03  3898.6 1955.81  3942.9 1953.93  4128.7 1953.47  4165.1 1954.85
  4215.1 1953.25  4526.0 1952.81  4567.9 1954.60  4597.7 1952.72  4675.6 1952.27
  5219.1 1951.97  5219.5 1951.47  5223.7 1951.97  5305.9 1953.50  5388.1 1952.29
  5432.7 1954.05  5464.3 1952.74  5607.8 1953.31  5633.3 1954.85  5781.2 1954.12
  5827.5 1955.76  6200.7 1956.20  6256.4 1957.69  6484.6 1958.16  6511.1 1958.36
#Mann=5,-1,0
  3330.4   0.045       0  5219.1   0.045       0  5223.7   0.045       0
  6200.7   0.035       0  6484.6   0.045       0
Bank Sta=5219.1,5223.7
Exp/Cntr=0.3,0.1

Type RM Length L Ch R = 1,47618,694,694,694
BEGIN DESCRIPTION:
UCFB HW Trib 04 56.2
END DESCRIPTION:
XS GIS Cut Line= 5
      1355642.52      7005647.60      1357119.38      7005054.97
      1357161.14      7004936.01      1357230.00      7004713.00
      1356700.97      7003328.86
#Sta/Elev= 30
  3282.6 1956.56  3306.8 1955.49  3339.1 1958.62  3393.0 1955.43  3630.1 1954.11
  3674.7 1955.93  3723.1 1954.12  3967.9 1953.35  4007.2 1955.03  4061.1 1953.23
  4374.0 1952.40  4405.9 1953.91  4446.6 1952.18  4923.7 1952.74  4974.2 1950.97
  4974.6 1950.47  4979.1 1950.97  4994.6 1952.31  5228.2 1952.80  5303.0 1951.45
  5627.5 1953.21  5712.4 1952.12  5752.6 1953.97  5923.9 1953.24  5956.0 1954.75
  6016.3 1953.80  6155.9 1955.96  6186.0 1954.75  6355.6 1955.39  6715.2 1958.09
#Mann=3,-1,0
  3282.6   0.045       0  4974.2   0.045       0  4979.1   0.045       0
Bank Sta=4974.2,4979.1
Exp/Cntr=0.3,0.1

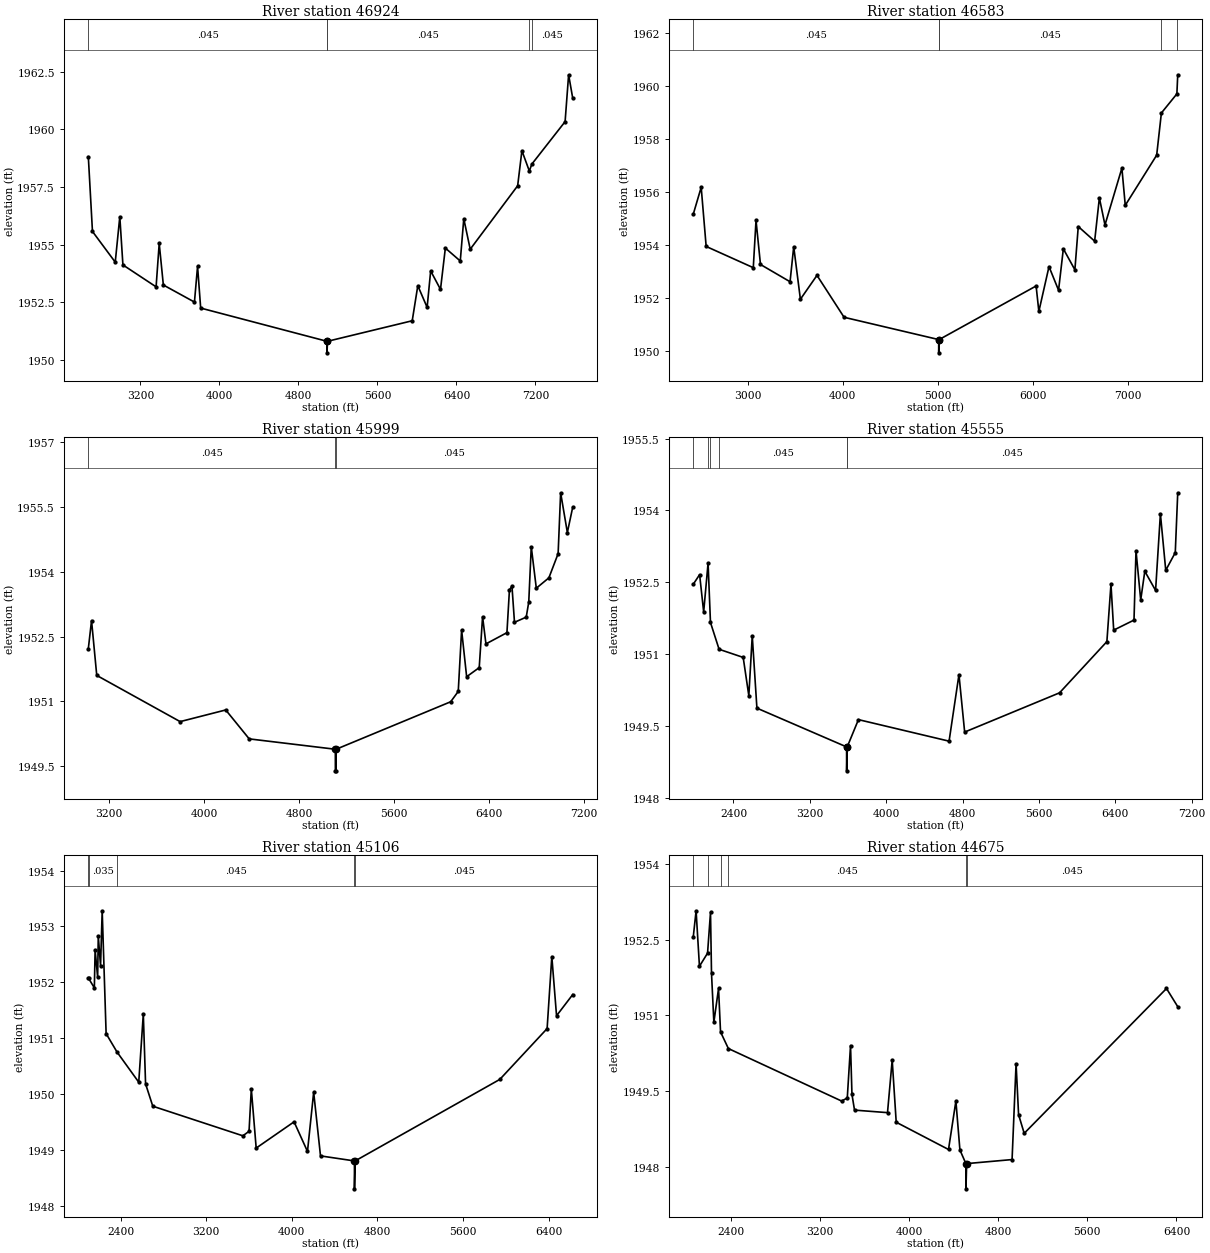
Type RM Length L Ch R = 1,46924,341,341,341
BEGIN DESCRIPTION:
UCFB HW Trib 04 56.0
END DESCRIPTION:
XS GIS Cut Line= 5
      1355681.34      7005716.10      1357730.00      7005063.00
      1357855.00      7004938.00      1357780.00      7004663.00
      1356445.28      7002799.44
#Sta/Elev= 30
  2673.0 1958.81  2714.9 1955.57  2945.5 1954.24  2991.7 1956.21  3023.2 1954.12
  3359.1 1953.17  3390.6 1955.05  3432.5 1953.25  3747.4 1952.51  3778.9 1954.06
  3810.4 1952.25  5089.1 1950.81  5089.5 1950.31  5094.0 1950.81  5952.1 1951.70
  6008.6 1953.22  6103.0 1952.28  6138.8 1953.86  6238.3 1953.06  6287.5 1954.85
  6438.5 1954.29  6474.1 1956.12  6539.2 1954.80  7019.5 1957.55  7062.5 1959.07
  7137.7 1958.19  7163.3 1958.49  7499.8 1960.33  7535.4 1962.36  7577.3 1961.34
#Mann=5,-1,0
  2673.0   0.045       0  5089.1   0.045       0  5094.0   0.045       0
  7137.7   0.035       0  7163.3   0.045       0
Bank Sta=5089.1,5094
Exp/Cntr=0.3,0.1

Type RM Length L Ch R = 1,46583,584,584,584
BEGIN DESCRIPTION:
UCFB HW Trib 04 55.0
END DESCRIPTION:
XS GIS Cut Line= 4
      1355861.37      7005975.05      1358046.46      7005023.72
      1358180.00      7004888.01      1356705.00      7002838.00
#Sta/Elev= 30
  2426.4 1955.16  2509.4 1956.17  2561.7 1953.94  3057.7 1953.14  3086.5 1954.92
  3133.4 1953.26  3444.7 1952.61  3483.3 1953.93  3553.6 1951.95  3728.2 1952.85
  4013.5 1951.27  5009.2 1950.43  5009.6 1949.93  5014.1 1950.43  6034.8 1952.45
  6063.6 1951.49  6170.4 1953.18  6271.1 1952.29  6321.4 1953.85  6442.9 1953.06
  6478.5 1954.69  6650.8 1954.14  6700.7 1955.77  6759.6 1954.75  6937.6 1956.89
  6973.2 1955.49  7303.8 1957.38  7353.4 1958.97  7516.5 1959.69  7525.5 1960.41
#Mann=5,-1,0
  2426.4   0.045       0  5009.2   0.045       0  5014.1   0.045       0
  7353.4   0.035       0  7516.5   0.045       0
Bank Sta=5009.2,5014.1
Exp/Cntr=0.3,0.1

Type RM Length L Ch R = 1,45999,444,444,444
BEGIN DESCRIPTION:
UCFB HW Trib 04 54.0
END DESCRIPTION:
XS GIS Cut Line= 3
      1359583.82      7006334.81      1358655.00      7004588.00
      1357184.82      7003083.85
#Sta/Elev= 30
  3025.9 1952.22  3053.0 1952.87  3096.9 1951.60  3799.5 1950.53  4183.7 1950.80
  4381.5 1950.13  5107.1 1949.89  5107.6 1949.39  5113.2 1949.39  5113.7 1949.89
  6079.2 1950.99  6142.8 1951.23  6171.1 1952.65  6213.5 1951.57  6319.5 1951.78
  6347.8 1952.96  6376.1 1952.33  6553.0 1952.59  6574.1 1953.58  6595.4 1953.67
  6616.6 1952.83  6715.6 1952.95  6736.9 1953.30  6758.0 1954.58  6800.5 1953.62
  6906.5 1953.86  6984.3 1954.42  7005.5 1955.83  7062.1 1954.91  7107.6 1955.50
#Mann=3,-1,0
  3025.9   0.045       0  5107.1   0.045       0  5113.7   0.045       0
Bank Sta=5107.1,5113.7
Exp/Cntr=0.3,0.1

Type RM Length L Ch R = 1,45555,449,449,449
BEGIN DESCRIPTION:
UCFB HW Trib 04 53.0
END DESCRIPTION:
XS GIS Cut Line= 5
      1361715.61      7005618.65      1360530.00      7004863.00
      1359845.83      7004665.54      1359005.00      7004338.00
      1357448.63      7002997.79
#Sta/Elev= 30
  1979.6 1952.46  2045.7 1952.66  2088.1 1951.88  2134.3 1952.90  2159.4 1951.66
  2249.6 1951.10  2502.1 1950.93  2561.2 1950.13  2597.0 1951.38  2645.8 1949.87
  3585.2 1949.06  3585.7 1948.56  3591.8 1949.06  3709.2 1949.63  4658.8 1949.18
  4762.2 1950.57  4821.9 1949.37  5815.8 1950.19  6311.7 1951.26  6354.5 1952.46
  6383.0 1951.50  6595.8 1951.71  6616.7 1953.16  6666.1 1952.13  6708.9 1952.73
  6821.9 1952.33  6872.3 1953.93  6928.3 1952.75  7028.1 1953.12  7053.9 1954.37
#Mann=6,-1,0
  1979.6   0.035       0  2134.3   0.045       0  2159.4   0.035       0
  2249.6   0.045       0  3585.2   0.045       0  3591.8   0.045       0
Bank Sta=3585.2,3591.8
Exp/Cntr=0.3,0.1

Type RM Length L Ch R = 1,45106,431,431,431
BEGIN DESCRIPTION:
UCFB HW Trib 04 52.0
END DESCRIPTION:
XS GIS Cut Line= 3
      1361719.04      7005511.93      1359255.00      7003988.00
      1357880.02      7003113.01
#Sta/Elev= 30
  2098.5 1952.07  2100.8 1952.07  2154.8 1951.90  2162.0 1952.58  2185.6 1952.09
  2191.5 1952.83  2212.7 1952.29  2228.1 1953.28  2264.8 1951.08  2366.8 1950.75
  2569.7 1950.21  2612.3 1951.43  2633.5 1950.18  2700.9 1949.78  3542.5 1949.25
  3600.4 1949.33  3621.6 1950.09  3667.1 1949.03  4021.2 1949.50  4146.5 1948.97
  4204.4 1950.03  4268.2 1948.89  4585.2 1948.80  4585.7 1948.30  4591.9 1948.80
  5944.0 1950.26  6385.9 1951.17  6429.9 1952.46  6474.0 1951.40  6625.5 1951.78
#Mann=5,-1,0
  2098.5   0.045       0  2100.8   0.035       0  2366.8   0.045       0
  4585.2   0.045       0  4591.9   0.045       0
Bank Sta=4585.2,4591.9
Exp/Cntr=0.3,0.1

Type RM Length L Ch R = 1,44675,538,538,538
BEGIN DESCRIPTION:
UCFB HW Trib 04 51.0
END DESCRIPTION:
XS GIS Cut Line= 3
      1361802.52      7005205.64      1359355.00      7003588.00
      1358073.69      7002986.62
#Sta/Elev= 30
  2062.1 1952.56  2087.1 1953.07  2117.2 1951.97  2190.0 1952.23  2216.5 1953.04
  2225.5 1951.83  2246.6 1950.86  2288.7 1951.53  2306.5 1950.67  2376.9 1950.34
  3393.2 1949.30  3444.4 1949.36  3473.6 1950.40  3486.5 1949.43  3509.5 1949.12
  3805.6 1949.07  3847.7 1950.11  3883.8 1948.88  4353.3 1948.34  4419.6 1949.30
  4455.7 1948.33  4509.4 1948.06  4509.9 1947.56  4516.2 1948.06  4924.0 1948.14
  4959.9 1950.04  4982.4 1949.03  5032.9 1948.66  6310.4 1951.53  6411.3 1951.17
#Mann=6,-1,0
  2062.1   0.035       0  2190.0   0.045       0  2306.5   0.035       0
  2376.9   0.045       0  4509.4   0.045       0  4516.2   0.045       0
Bank Sta=4509.4,4516.2
Exp/Cntr=0.3,0.1

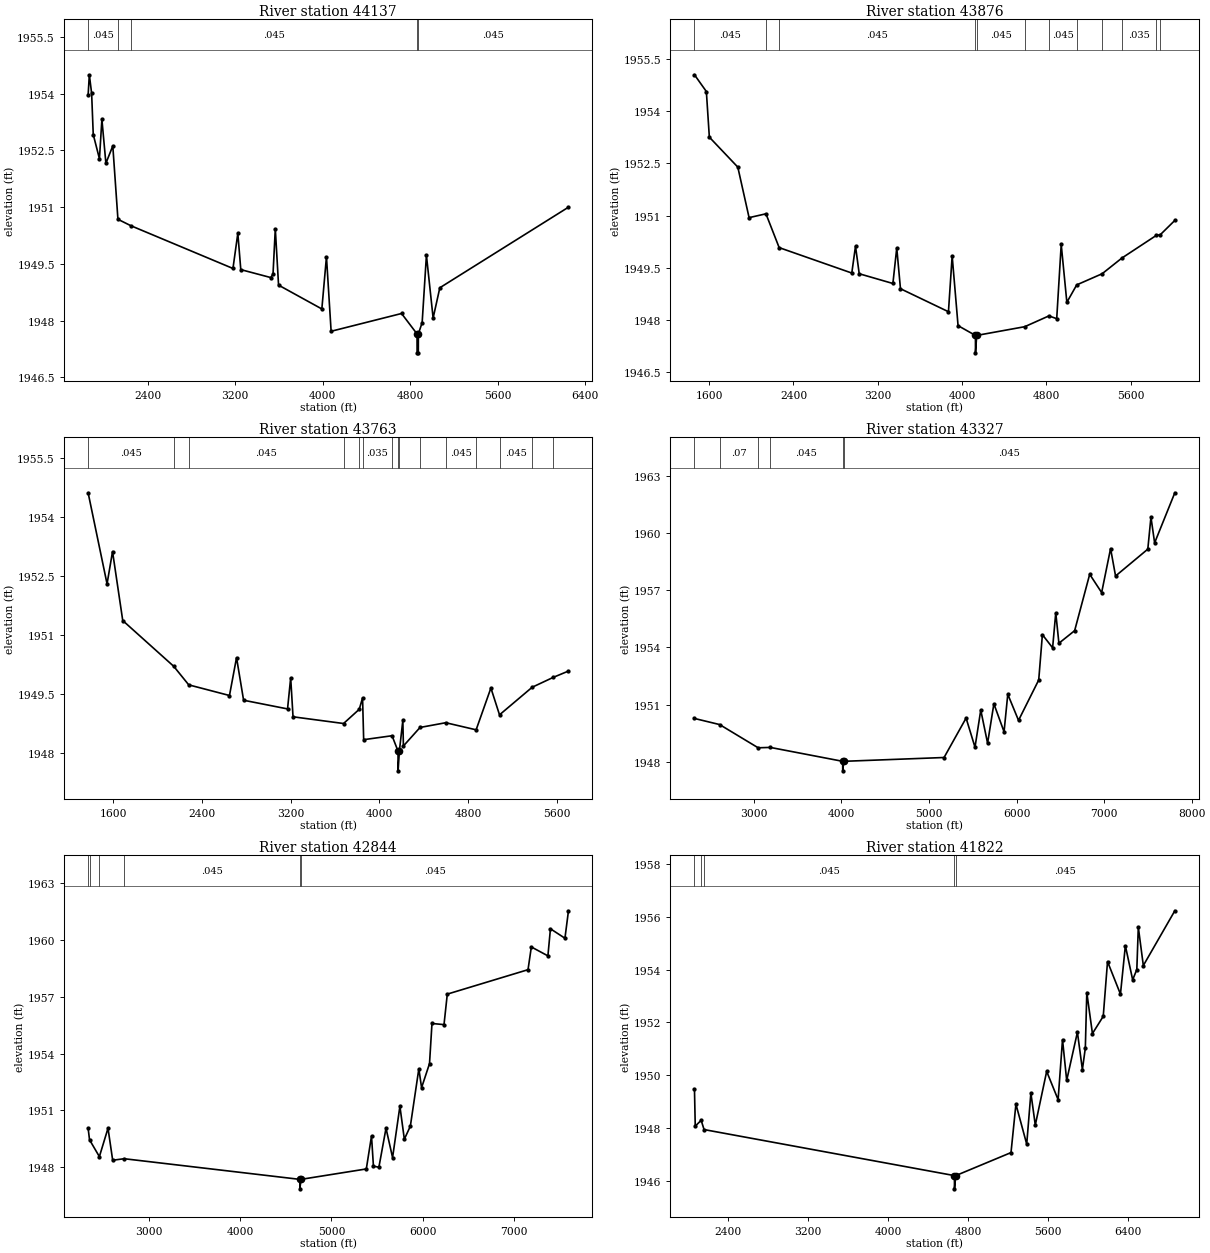
Type RM Length L Ch R = 1,44137,261,261,261
BEGIN DESCRIPTION:
UCFB HW Trib 04 50.0
END DESCRIPTION:
XS GIS Cut Line= 4
      1361928.36      7004979.92      1360144.01      7003734.33
      1359581.30      7003110.37      1358233.49      7002826.93
#Sta/Elev= 30
  1854.1 1953.96  1865.2 1954.50  1886.2 1954.01  1901.0 1952.92  1957.7 1952.28
  1980.1 1953.32  2016.7 1952.16  2079.8 1952.62  2126.8 1950.68  2245.2 1950.51
  3178.9 1949.38  3223.4 1950.31  3250.5 1949.35  3524.4 1949.14  3545.3 1949.23
  3566.2 1950.43  3595.9 1948.94  3991.9 1948.31  4034.1 1949.69  4076.7 1947.72
  4720.9 1948.19  4862.6 1947.65  4863.1 1947.15  4874.2 1947.15  4874.7 1947.65
  4909.4 1947.95  4948.4 1949.73  5009.7 1948.07  5071.0 1948.87  6247.7 1951.00
#Mann=5,-1,0
  1854.1   0.045       0  2126.8   0.035       0  2245.2   0.045       0
  4862.6   0.045       0  4874.7   0.045       0
Bank Sta=4862.6,4874.7
Exp/Cntr=0.3,0.1

Type RM Length L Ch R = 1,43876,113,113,113
BEGIN DESCRIPTION:
UCFB HW Trib 04 49.0
END DESCRIPTION:
XS GIS Cut Line= 4
      1362362.39      7004849.71      1360054.21      7002966.37
      1359184.64      7002765.19      1358530.03      7002563.01
#Sta/Elev= 30
  1460.9 1955.04  1573.7 1954.56  1602.0 1953.25  1872.0 1952.39  1979.0 1950.94
  2139.0 1951.05  2264.2 1950.08  2953.3 1949.35  2988.5 1950.12  3023.7 1949.33
  3343.2 1949.05  3379.8 1950.07  3415.0 1948.90  3870.2 1948.24  3905.4 1949.84
  3961.4 1947.84  4126.2 1947.56  4126.7 1947.06  4138.3 1947.56  4593.7 1947.81
  4823.2 1948.12  4897.2 1948.04  4939.9 1950.17  4993.4 1948.51  5086.9 1949.01
  5328.2 1949.33  5515.4 1949.78  5841.8 1950.43  5879.8 1950.45  6017.6 1950.86
#Mann=12,-1,0
  1460.9   0.045       0  2139.0   0.035       0  2264.2   0.045       0
  4126.2   0.045       0  4138.3   0.045       0  4593.7   0.035       0
  4823.2   0.045       0  5086.9   0.035       0  5328.2   0.045       0
  5515.4   0.035       0  5841.8   0.045       0  5879.8   0.035       0
Bank Sta=4126.2,4138.3
Exp/Cntr=0.3,0.1

Type RM Length L Ch R = 1,43763,436,436,436
BEGIN DESCRIPTION:
UCFB HW Trib 04 48.5
END DESCRIPTION:
XS GIS Cut Line= 3
      1362401.90      7004792.29      1360633.56      7002995.96
      1358873.91      7002581.86
#Sta/Elev= 30
  1374.5 1954.61  1545.1 1952.30  1594.5 1953.12  1686.5 1951.37  2146.0 1950.21
  2281.0 1949.74  2648.2 1949.47  2711.9 1950.43  2775.4 1949.35  3171.5 1949.13
  3199.8 1949.92  3220.9 1948.93  3676.3 1948.76  3817.5 1949.12  3847.5 1949.41
  3857.4 1948.35  4113.0 1948.45  4167.1 1948.06  4167.6 1947.56  4179.2 1948.06
  4210.4 1948.84  4215.5 1948.19  4365.4 1948.66  4597.2 1948.78  4870.8 1948.60
  5003.9 1949.66  5081.5 1948.98  5376.1 1949.68  5565.8 1949.93  5702.9 1950.09
#Mann=15,-1,0
  1374.5   0.045       0  2146.0   0.035       0  2281.0   0.045       0
  3676.3   0.035       0  3817.5   0.045       0  3847.5   0.035       0
  4113.0   0.045       0  4167.1   0.035       0  4179.2   0.045       0
  4365.4   0.035       0  4597.2   0.045       0  4870.8   0.035       0
  5081.5   0.045       0  5376.1   0.035       0  5565.8   0.045       0
Bank Sta=4167.1,4179.2
Exp/Cntr=0.3,0.1

Type RM Length L Ch R = 1,43327,483,483,483
BEGIN DESCRIPTION:
UCFB HW Trib 04 48.0
END DESCRIPTION:
XS GIS Cut Line= 3
      1362129.97      7003362.99      1359655.00      7002338.00
      1357329.97      7000762.98
#Sta/Elev= 30
  2320.7 1950.27  2608.0 1949.95  3048.2 1948.73  3186.6 1948.75  4013.7 1948.02
  4014.2 1947.52  4025.8 1948.02  5171.8 1948.22  5423.4 1950.29  5525.2 1948.76
  5591.1 1950.71  5669.0 1948.97  5740.9 1951.04  5857.1 1949.57  5899.7 1951.54
  6022.4 1950.17  6253.1 1952.29  6295.1 1954.67  6411.8 1953.98  6447.8 1955.82
  6483.7 1954.22  6663.5 1954.88  6835.4 1957.84  6972.0 1956.88  7073.9 1959.19
  7130.8 1957.75  7499.2 1959.16  7535.1 1960.84  7577.1 1959.49  7807.8 1962.12
#Mann=6,-1,0
  2320.7   0.035       0  2608.0    0.07       0  3048.2   0.035       0
  3186.6   0.045       0  4013.7   0.045       0  4025.8   0.045       0
Bank Sta=4013.7,4025.8
Exp/Cntr=0.3,0.1

Type RM Length L Ch R = 1,42844,1022,1022,1022
BEGIN DESCRIPTION:
UCFB HW Trib 04 47.0
END DESCRIPTION:
XS GIS Cut Line= 3
      1362167.32      7003015.04      1359755.00      7001888.00
      1357608.77      7000430.78
#Sta/Elev= 30
  2336.9 1950.06  2352.3 1949.45  2460.1 1948.56  2554.5 1950.06  2605.7 1948.37
  2731.9 1948.45  4653.9 1947.36  4654.4 1946.86  4666.0 1947.36  5381.3 1947.91
  5438.2 1949.65  5459.2 1948.06  5519.0 1948.00  5596.9 1950.06  5668.7 1948.51
  5748.9 1951.22  5797.5 1949.48  5863.3 1950.17  5956.2 1953.20  5986.1 1952.20
  6072.9 1953.47  6099.9 1955.59  6231.6 1955.53  6267.5 1957.14  7151.0 1958.43
  7187.3 1959.63  7368.6 1959.16  7396.4 1960.59  7555.0 1960.09  7593.7 1961.54
#Mann=6,-1,0
  2336.9    0.07       0  2352.3   0.035       0  2460.1    0.07       0
  2731.9   0.045       0  4653.9   0.045       0  4666.0   0.045       0
Bank Sta=4653.9,4666
Exp/Cntr=0.3,0.1

Type RM Length L Ch R = 1,41822,1157,1157,1157
BEGIN DESCRIPTION:
UCFB HW Trib 04 46.5
END DESCRIPTION:
XS GIS Cut Line= 2
      1362348.91      7002645.72      1358442.89      6999839.77
#Sta/Elev= 30
  2062.5 1949.48  2070.3 1948.08  2129.6 1948.30  2158.5 1947.95  4665.3 1946.21
  4665.8 1945.71  4678.7 1946.21  5231.7 1947.08  5281.0 1948.91  5389.0 1947.40
  5430.7 1949.33  5474.9 1948.12  5588.8 1950.15  5703.3 1949.08  5747.5 1951.35
  5789.2 1949.81  5896.6 1951.63  5946.4 1950.22  5975.9 1951.03  5990.6 1953.13
  6047.1 1951.58  6155.2 1952.23  6198.1 1954.30  6327.5 1953.07  6376.8 1954.90
  6449.8 1953.61  6491.5 1954.00  6506.3 1955.60  6556.6 1954.15  6871.9 1956.22
#Mann=5,-1,0
  2062.5    0.07       0  2129.6   0.035       0  2158.5   0.045       0
  4665.3   0.045       0  4678.7   0.045       0
Bank Sta=4665.3,4678.7
Exp/Cntr=0.3,0.1