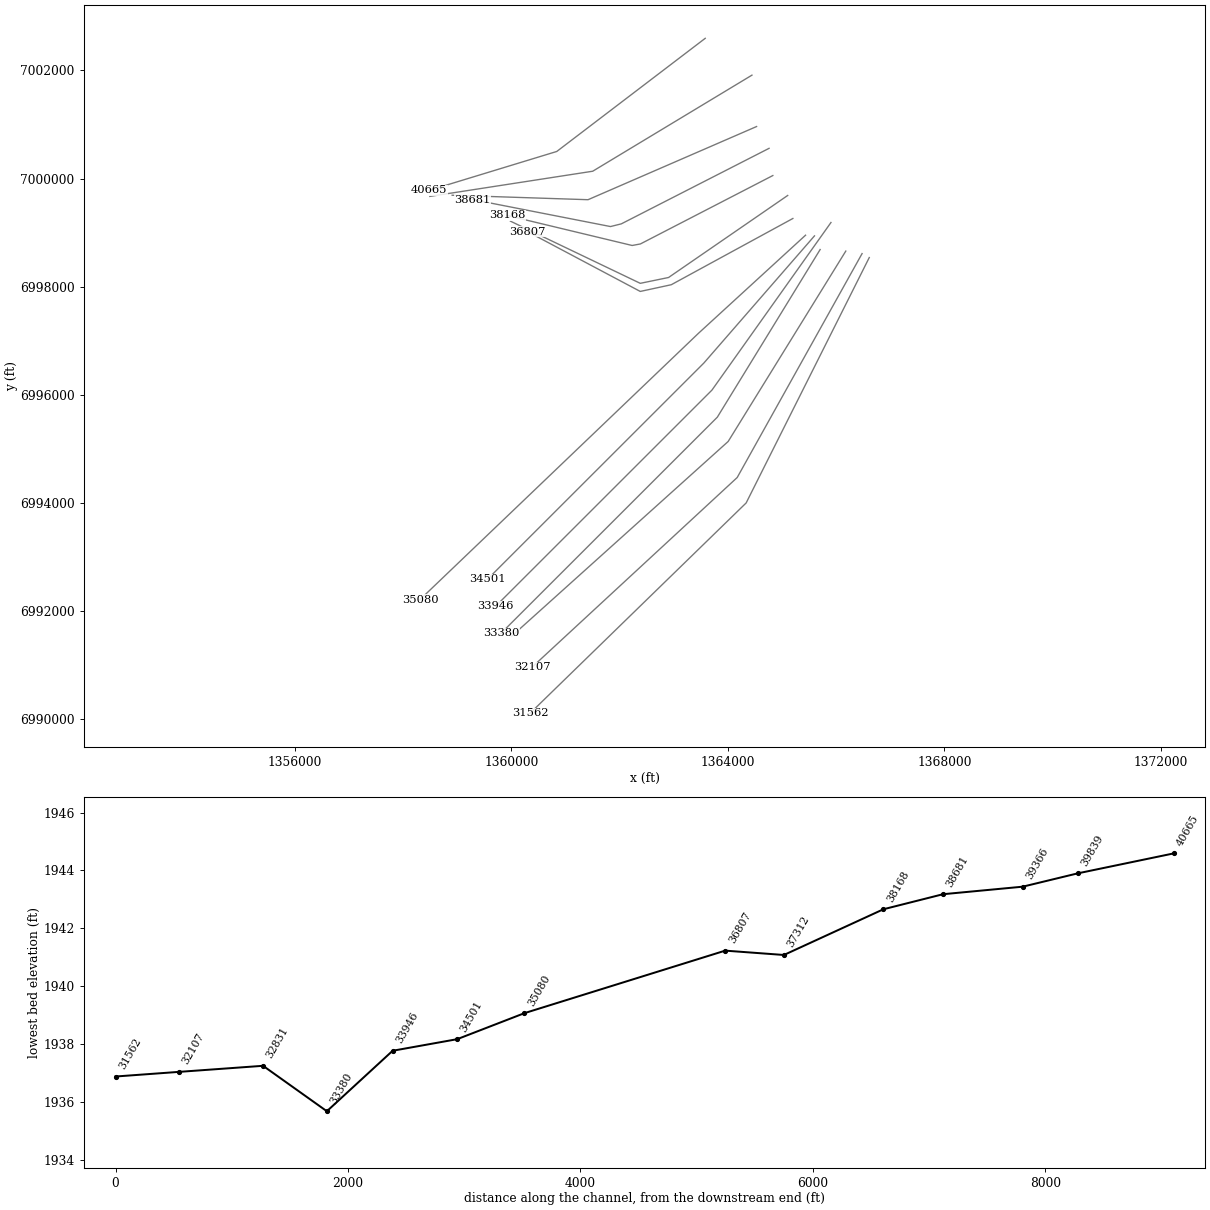
HEC-RAS study UCFB HW Trib 04.prj: UCFB HW Trib 04 Base Level Engineering

--- UCFB HW Trib 04.g01 (geometry) --- (continued)

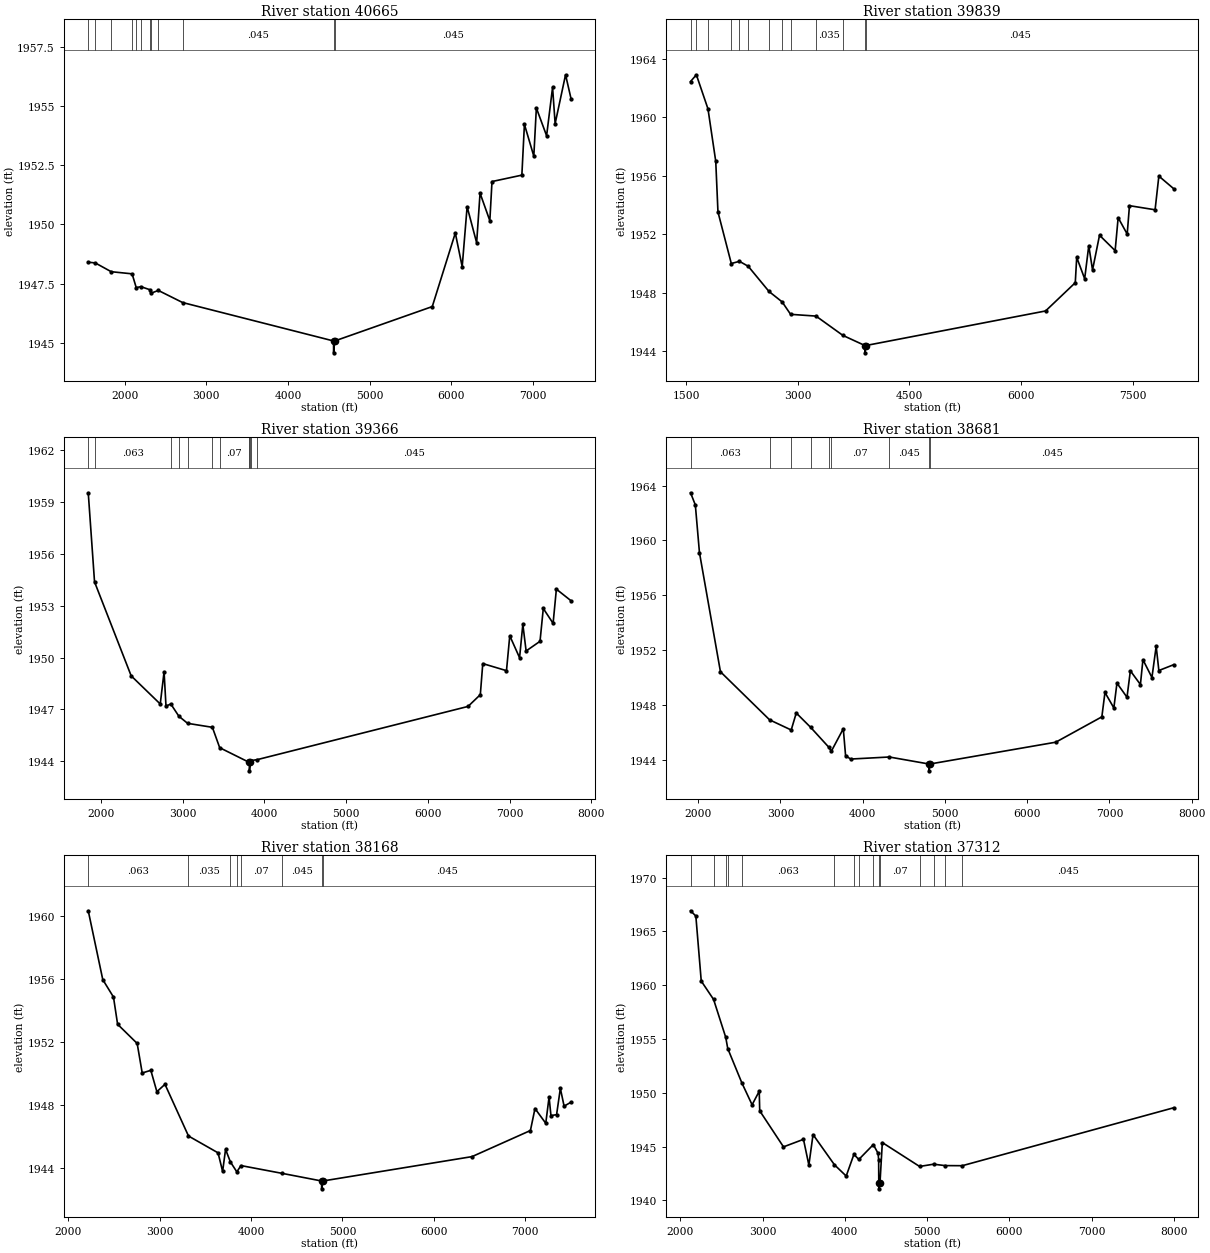
Type RM Length L Ch R = 1,40665,826,826,826
BEGIN DESCRIPTION:
UCFB HW Trib 04 46.0
END DESCRIPTION:
XS GIS Cut Line= 3
      1363580.68      7002594.38      1360836.94      7000501.89
      1358476.51      6999781.88
#Sta/Elev= 30
  1552.6 1948.41  1638.2 1948.38  1833.9 1948.01  2089.8 1947.92  2140.5 1947.34
  2197.2 1947.38  2308.0 1947.25  2319.1 1947.10  2411.3 1947.22  2708.9 1946.71
  4558.8 1945.09  4559.3 1944.59  4572.2 1945.09  5768.4 1946.54  6050.7 1949.64
  6135.0 1948.22  6195.4 1950.75  6312.1 1949.23  6353.9 1951.32  6473.7 1950.16
  6500.3 1951.81  6866.2 1952.08  6897.6 1954.22  7012.6 1952.88  7043.9 1954.91
  7169.4 1953.74  7242.6 1955.78  7273.9 1954.25  7401.6 1956.31  7471.0 1955.27
#Mann=12,-1,0
  1552.6    0.07       0  1638.2   0.035       0  1833.9    0.07       0
  2089.8   0.035       0  2140.5    0.07       0  2197.2   0.035       0
  2308.0    0.07       0  2319.1   0.045       0  2411.3   0.035       0
  2708.9   0.045       0  4558.8   0.045       0  4572.2   0.045       0
Bank Sta=4558.8,4572.2
Exp/Cntr=0.3,0.1

Type RM Length L Ch R = 1,39839,473,473,473
BEGIN DESCRIPTION:
UCFB HW Trib 04 45.0
END DESCRIPTION:
XS GIS Cut Line= 3
      1364444.48      7001913.54      1361501.18      7000136.42
      1358490.37      6999670.77
#Sta/Elev= 30
  1561.8 1962.43  1639.9 1962.89  1795.8 1960.56  1900.0 1956.98  1929.8 1953.52
  2108.9 1950.00  2218.4 1950.15  2336.4 1949.81  2615.2 1948.09  2791.3 1947.38
  2905.0 1946.53  3246.2 1946.41  3607.4 1945.09  3902.6 1944.40  3903.1 1943.90
  3916.2 1944.40  6328.8 1946.76  6727.5 1948.69  6746.7 1950.42  6853.6 1948.96
  6908.6 1951.22  6959.2 1949.56  7053.0 1951.93  7262.8 1950.88  7303.2 1953.13
  7424.7 1952.01  7455.0 1953.95  7799.1 1953.67  7849.7 1955.97  8046.6 1955.12
#Mann=13,-1,0
  1561.8   0.063       0  1639.9   0.035       0  1795.8   0.063       0
  2108.9   0.035       0  2218.4   0.063       0  2336.4   0.035       0
  2615.2    0.07       0  2791.3   0.035       0  2905.0    0.07       0
  3246.2   0.035       0  3607.4   0.045       0  3902.6   0.045       0
  3916.2   0.045       0
Bank Sta=3902.6,3916.2
Exp/Cntr=0.3,0.1

Type RM Length L Ch R = 1,39366,685,685,685
BEGIN DESCRIPTION:
UCFB HW Trib 04 44.5
END DESCRIPTION:
XS GIS Cut Line= 3
      1364530.04      7000963.02      1361414.80      6999609.67
      1358903.46      6999692.14
#Sta/Elev= 30
  1845.3 1959.54  1922.2 1954.38  2370.5 1948.94  2726.1 1947.31  2773.0 1949.17
  2796.5 1947.19  2855.4 1947.31  2954.3 1946.60  3060.9 1946.19  3364.1 1945.96
  3453.5 1944.78  3810.6 1943.94  3816.5 1943.94  3817.0 1943.44  3830.2 1943.94
  3831.5 1944.03  3914.2 1944.09  6492.3 1947.17  6642.4 1947.85  6672.4 1949.65
  6962.5 1949.24  7002.6 1951.26  7122.6 1949.99  7162.6 1951.92  7202.7 1950.38
  7372.8 1950.94  7412.8 1952.84  7532.8 1951.98  7572.9 1953.96  7754.5 1953.28
#Mann=12,-1,0
  1845.3   0.035       0  1922.2   0.063       0  2855.4    0.07       0
  2954.3   0.035       0  3060.9    0.07       0  3364.1   0.035       0
  3453.5    0.07       0  3810.6   0.045       0  3816.5   0.045       0
  3830.2   0.045       0  3831.5    0.07       0  3914.2   0.045       0
Bank Sta=3816.5,3830.2
Exp/Cntr=0.3,0.1

Type RM Length L Ch R = 1,38681,513,513,513
BEGIN DESCRIPTION:
UCFB HW Trib 04 44.0
END DESCRIPTION:
XS GIS Cut Line= 4
      1364760.97      7000559.90      1362030.00      6999163.00
      1361830.00      6999113.00      1359280.01      6999613.00
#Sta/Elev= 30
  1907.3 1963.47  1965.5 1962.58  2015.5 1959.10  2270.8 1950.41  2868.7 1946.90
  3131.1 1946.16  3192.5 1947.40  3366.4 1946.36  3585.5 1944.92  3618.9 1944.61
  3764.4 1946.25  3792.2 1944.29  3853.2 1944.04  4323.5 1944.19  4804.9 1943.68
  4805.4 1943.18  4818.9 1943.68  6347.8 1945.27  6908.2 1947.12  6945.9 1948.90
  7054.0 1947.77  7091.7 1949.58  7213.9 1948.55  7254.7 1950.48  7377.0 1949.48
  7407.6 1951.29  7517.1 1949.99  7568.6 1952.27  7601.2 1950.50  7779.5 1950.92
#Mann=9,-1,0
  1907.3   0.063       0  2868.7    0.07       0  3131.1   0.035       0
  3366.4   0.063       0  3585.5   0.035       0  3618.9    0.07       0
  4323.5   0.045       0  4804.9   0.045       0  4818.9   0.045       0
Bank Sta=4804.9,4818.9
Exp/Cntr=0.3,0.1

Type RM Length L Ch R = 1,38168,856,856,856
BEGIN DESCRIPTION:
UCFB HW Trib 04 43.0
END DESCRIPTION:
XS GIS Cut Line= 4
      1364830.41      7000056.42      1362382.40      6998791.31
      1362230.00      6998763.00      1359919.36      6999318.20
#Sta/Elev= 30
  2217.8 1960.35  2376.8 1955.97  2494.0 1954.86  2539.1 1953.13  2753.3 1951.91
  2808.5 1950.03  2902.7 1950.20  2969.1 1948.84  3057.7 1949.31  3315.2 1946.02
  3638.8 1944.95  3688.7 1943.77  3721.0 1945.17  3774.0 1944.37  3844.3 1943.74
  3889.3 1944.14  4335.3 1943.65  4772.2 1943.16  4772.7 1942.66  4786.2 1943.16
  6419.1 1944.71  7058.2 1946.37  7108.2 1947.77  7226.1 1946.83  7262.4 1948.50
  7283.0 1947.32  7344.7 1947.38  7385.9 1949.05  7427.0 1947.92  7504.8 1948.18
#Mann=8,-1,0
  2217.8   0.063       0  3315.2   0.035       0  3774.0    0.07       0
  3844.3   0.035       0  3889.3    0.07       0  4335.3   0.045       0
  4772.2   0.045       0  4786.2   0.045       0
Bank Sta=4772.2,4786.2
Exp/Cntr=0.3,0.1

Type RM Length L Ch R = 1,37312,505,505,505
BEGIN DESCRIPTION:
UCFB HW Trib 04 42.0
END DESCRIPTION:
XS GIS Cut Line= 4
      1365105.03      6999688.02      1362903.18      6998170.91
      1362380.00      6998063.00      1359979.99      6999213.00
#Sta/Elev= 30
  2125.5 1966.92  2189.8 1966.43  2255.4 1960.39  2405.4 1958.68  2553.0 1955.16
  2577.4 1954.12  2748.7 1950.93  2873.5 1948.89  2960.1 1950.15  2966.1 1948.33
  3254.9 1944.98  3497.8 1945.68  3563.3 1943.29  3614.0 1946.12  3874.7 1943.31
  4017.1 1942.27  4110.6 1944.28  4170.4 1943.81  4346.5 1945.19  4405.2 1944.37
  4411.3 1943.75  4413.0 1941.58  4413.5 1941.08  4427.2 1941.58  4456.0 1945.38
  4908.8 1943.16  5079.1 1943.37  5217.6 1943.24  5427.8 1943.23  7994.9 1948.61
#Mann=15,-1,0
  2125.5   0.063       0  2405.4   0.094       0  2553.0   0.125       0
  2577.4   0.094       0  2748.7   0.063       0  3874.7   0.035       0
  4110.6    0.07       0  4170.4   0.063       0  4346.5    0.07       0
  4413.0   0.045       0  4427.2    0.07       0  4908.8   0.045       0
  5079.1   0.035       0  5217.6    0.07       0  5427.8   0.045       0
Bank Sta=4413,4427.2
Exp/Cntr=0.3,0.1

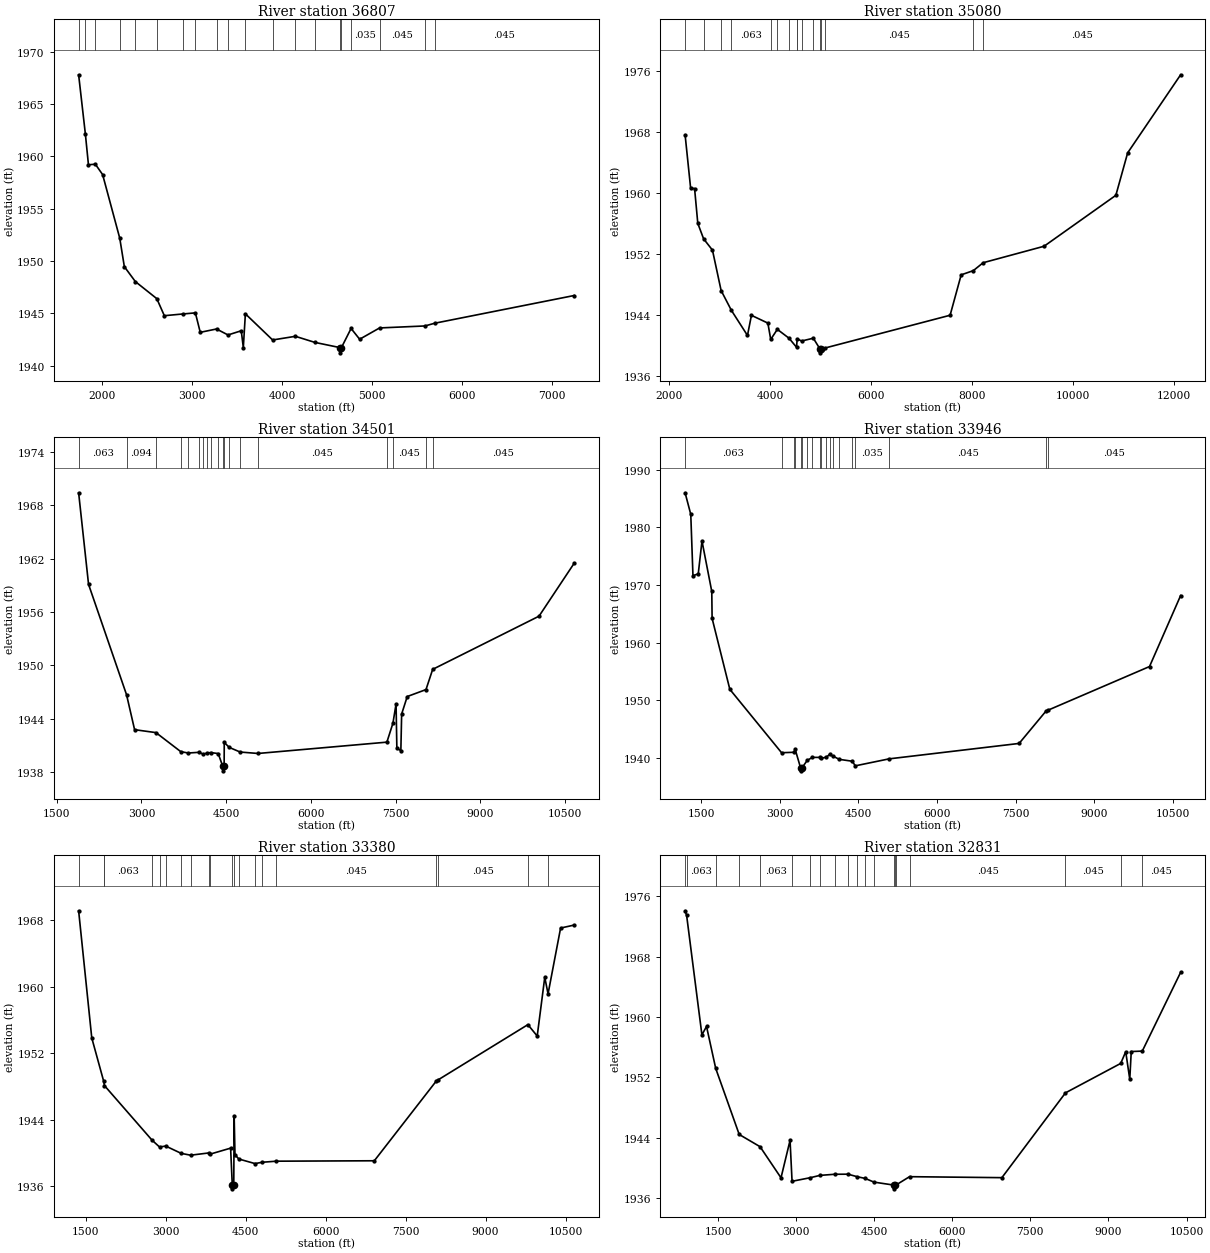
Type RM Length L Ch R = 1,36807,1727,1727,1727
BEGIN DESCRIPTION:
UCFB HW Trib 04 41.5
END DESCRIPTION:
XS GIS Cut Line= 4
      1365200.71      6999262.29      1362953.53      6998037.23
      1362380.00      6997913.00      1360298.51      6999018.33
#Sta/Elev= 30
  1742.0 1967.81  1816.8 1962.15  1851.0 1959.21  1927.8 1959.26  2008.4 1958.27
  2198.6 1952.19  2249.6 1949.47  2372.1 1948.04  2610.1 1946.41  2693.8 1944.78
  2905.4 1944.95  3038.5 1945.05  3092.5 1943.19  3273.1 1943.51  3400.8 1942.94
  3548.0 1943.34  3570.8 1941.74  3593.8 1944.96  3896.3 1942.46  4149.1 1942.81
  4364.7 1942.23  4644.5 1941.73  4645.0 1941.23  4660.4 1941.73  4767.6 1943.56
  4862.7 1942.53  5084.1 1943.61  5588.3 1943.80  5696.2 1944.06  7245.0 1946.71
#Mann=20,-1,0
  1742.0   0.035       0  1816.8   0.063       0  1927.8   0.094       0
  2198.6   0.125       0  2372.1   0.063       0  2610.1   0.125       0
  2905.4   0.094       0  3038.5   0.063       0  3273.1    0.07       0
  3400.8   0.035       0  3593.8   0.063       0  3896.3   0.035       0
  4149.1    0.07       0  4364.7   0.045       0  4644.5   0.035       0
  4660.4   0.045       0  4767.6   0.035       0  5084.1   0.045       0
  5588.3    0.07       0  5696.2   0.045       0
Bank Sta=4644.5,4660.4
Exp/Cntr=0.3,0.1

Type RM Length L Ch R = 1,35080,579,579,579
BEGIN DESCRIPTION:
UCFB HW Trib 04 41.0
END DESCRIPTION:
XS GIS Cut Line= 3
      1365435.11      6998953.10      1363455.00      6997138.00
      1358307.75      6992212.04
#Sta/Elev= 30
  2314.3 1967.67  2423.9 1960.66  2502.2 1960.62  2565.7 1956.05  2681.0 1954.02
  2856.1 1952.54  3027.4 1947.24  3231.8 1944.63  3549.2 1941.35  3627.5 1943.99
  3953.1 1942.97  4009.5 1940.83  4140.4 1942.15  4371.5 1940.99  4520.8 1939.80
  4533.1 1940.91  4620.4 1940.62  4853.0 1940.99  4985.1 1939.57  4985.6 1939.07
  5009.1 1939.57  5088.6 1939.71  7560.9 1944.00  7780.2 1949.30  8019.9 1949.85
  8215.5 1950.89  9420.9 1953.05 10842.4 1959.73 11076.1 1965.30 12125.0 1975.54
#Mann=16,-1,0
  2314.3   0.063       0  2681.0   0.125       0  3027.4   0.094       0
  3231.8   0.063       0  4009.5   0.035       0  4140.4    0.07       0
  4371.5   0.035       0  4520.8    0.16       0  4533.1   0.035       0
  4620.4    0.16       0  4853.0   0.035       0  4985.1   0.035       0
  5009.1   0.035       0  5088.6   0.045       0  8019.9   0.035       0
  8215.5   0.045       0
Bank Sta=4985.1,5009.1
Exp/Cntr=0.3,0.1

Type RM Length L Ch R = 1,34501,555,555,555
BEGIN DESCRIPTION:
UCFB HW Trib 04 40.0
END DESCRIPTION:
XS GIS Cut Line= 3
      1365600.20      6998940.62      1363555.00      6996588.00
      1359554.98      6992587.98
#Sta/Elev= 30
  1887.4 1969.38  2063.1 1959.10  2735.9 1946.71  2878.2 1942.79  3256.7 1942.46
  3694.6 1940.33  3827.4 1940.17  4022.6 1940.25  4093.2 1940.04  4168.8 1940.18
  4226.0 1940.22  4358.9 1940.11  4439.6 1938.67  4440.1 1938.17  4463.7 1938.67
  4465.9 1941.36  4554.2 1940.80  4747.6 1940.28  5063.1 1940.12  7345.4 1941.39
  7452.8 1943.52  7507.9 1945.68  7522.0 1940.72  7592.7 1940.43  7606.9 1944.55
  7705.9 1946.51  8037.9 1947.29  8156.1 1949.56 10039.3 1955.53 10661.6 1961.47
#Mann=19,-1,0
  1887.4   0.063       0  2735.9   0.094       0  3256.7   0.063       0
  3694.6    0.07       0  3827.4   0.035       0  4022.6    0.07       0
  4093.2   0.035       0  4168.8    0.16       0  4226.0   0.035       0
  4358.9    0.16       0  4439.6   0.035       0  4463.7    0.16       0
  4554.2    0.16       0  4747.6   0.035       0  5063.1   0.045       0
  7345.4    0.07       0  7452.8   0.045       0  8037.9   0.035       0
  8156.1   0.045       0
Bank Sta=4439.6,4463.7
Exp/Cntr=0.3,0.1

Type RM Length L Ch R = 1,33946,566,566,566
BEGIN DESCRIPTION:
UCFB HW Trib 04 39.0
END DESCRIPTION:
XS GIS Cut Line= 3
      1365905.02      6999188.03      1363705.00      6996088.00
      1359705.01      6992088.01
#Sta/Elev= 30
  1193.6 1985.97  1301.9 1982.23  1343.7 1971.60  1444.6 1971.92  1515.9 1977.61
  1702.9 1968.86  1709.1 1964.20  2047.4 1951.90  3034.9 1940.91  3279.8 1940.99
  3292.4 1941.56  3398.4 1938.27  3398.9 1937.77  3422.5 1938.27  3524.6 1939.58
  3621.4 1940.10  3769.4 1940.10  3785.8 1939.93  3891.8 1940.15  3950.3 1940.61
  4014.2 1940.33  4136.6 1939.76  4381.4 1939.44  4443.6 1938.64  5089.0 1939.85
  7568.8 1942.52  8078.4 1948.09  8124.7 1948.30 10057.8 1955.85 10651.8 1968.16
#Mann=19,-1,0
  1193.6   0.063       0  3034.9    0.07       0  3279.8   0.035       0
  3292.4    0.16       0  3398.4   0.035       0  3422.5    0.16       0
  3524.6   0.035       0  3621.4   0.094       0  3769.4    0.16       0
  3785.8    0.07       0  3891.8   0.035       0  3950.3    0.16       0
  4014.2   0.035       0  4136.6    0.16       0  4381.4    0.07       0
  4443.6   0.035       0  5089.0   0.045       0  8078.4   0.035       0
  8124.7   0.045       0
Bank Sta=3398.4,3422.5
Exp/Cntr=0.3,0.1

Type RM Length L Ch R = 1,33380,549,549,549
BEGIN DESCRIPTION:
UCFB HW Trib 04 38.0
END DESCRIPTION:
XS GIS Cut Line= 5
      1365705.00      6998688.00      1364066.91      6996015.32
      1363805.00      6995588.00      1363445.07      6995228.07
      1359804.99      6991587.99
#Sta/Elev= 30
  1369.5 1969.16  1615.8 1953.85  1836.0 1948.71  1853.9 1948.11  2744.8 1941.55
  2886.2 1940.72  3003.0 1940.83  3292.9 1939.95  3470.0 1939.73  3820.3 1940.01
  3830.9 1939.85  4219.6 1940.58  4250.6 1936.18  4251.1 1935.68  4278.7 1936.18
  4286.0 1944.49  4301.4 1939.79  4374.0 1939.27  4677.4 1938.72  4810.8 1938.88
  5078.0 1939.01  6914.6 1939.06  8070.3 1948.61  8115.6 1948.82  9794.2 1955.45
  9969.3 1954.08 10110.7 1961.15 10172.6 1959.16 10407.7 1967.08 10662.3 1967.44
#Mann=20,-1,0
  1369.5   0.063       0  1836.0   0.035       0  1853.9   0.063       0
  2744.8    0.07       0  2886.2   0.035       0  3003.0    0.16       0
  3292.9   0.035       0  3470.0    0.07       0  3820.3   0.035       0
  3830.9    0.07       0  4250.6   0.035       0  4278.7    0.07       0
  4374.0   0.035       0  4677.4    0.07       0  4810.8   0.035       0
  5078.0   0.045       0  8070.3   0.035       0  8115.6   0.045       0
  9794.2   0.035       0 10172.6   0.045       0
Bank Sta=4250.6,4278.7
Exp/Cntr=0.3,0.1

Type RM Length L Ch R = 1,32831,724,724,724
BEGIN DESCRIPTION:
UCFB HW Trib 04 37.0
END DESCRIPTION:
XS GIS Cut Line= 3
      1366178.84      6998659.10      1364005.00      6995138.00
      1360005.02      6991538.02
#Sta/Elev= 30
   867.2 1974.07   896.8 1973.45  1190.1 1957.64  1278.9 1958.75  1455.2 1953.20
  1906.7 1944.45  2307.3 1942.83  2709.6 1938.71  2883.4 1943.67  2921.9 1938.25
  3276.0 1938.73  3456.1 1939.03  3741.0 1939.18  3996.5 1939.19  4176.6 1938.85
  4326.0 1938.63  4495.9 1938.14  4873.5 1937.75  4874.0 1937.25  4902.0 1937.75
  4924.3 1937.78  5178.9 1938.86  6952.7 1938.73  8174.4 1949.96  9235.9 1953.86
  9331.7 1955.41  9409.5 1951.76  9437.9 1955.43  9649.9 1955.49 10386.7 1965.92
#Mann=20,-1,0
   867.2   0.035       0   896.8   0.063       0  1455.2   0.035       0
  1906.7    0.07       0  2307.3   0.063       0  2921.9    0.16       0
  3276.0   0.035       0  3456.1    0.07       0  3741.0   0.035       0
  3996.5    0.07       0  4176.6    0.16       0  4326.0    0.07       0
  4495.9   0.045       0  4873.5   0.035       0  4902.0   0.045       0
  4924.3   0.035       0  5178.9   0.045       0  8174.4   0.045       0
  9235.9   0.035       0  9649.9   0.045       0
Bank Sta=4873.5,4902
Exp/Cntr=0.3,0.1

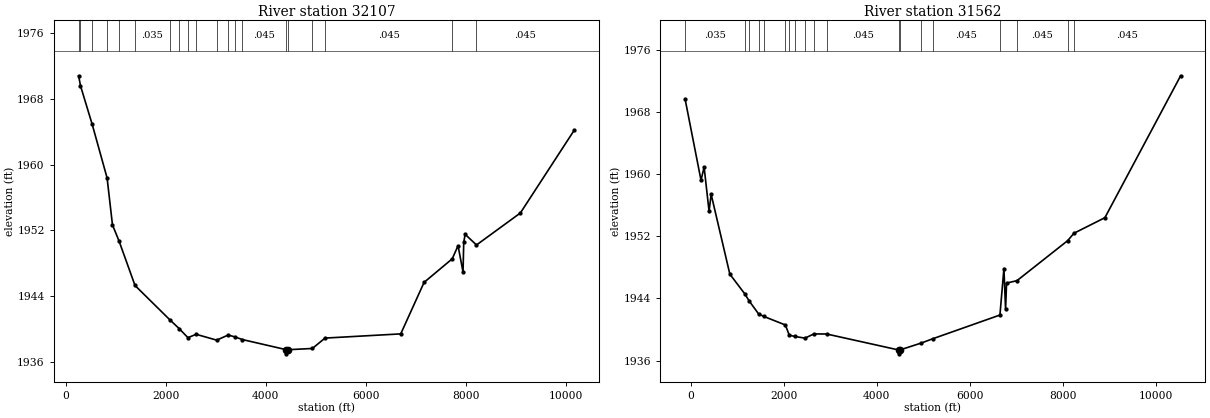
Type RM Length L Ch R = 1,32107,545,545,545
BEGIN DESCRIPTION:
UCFB HW Trib 04 36.0
END DESCRIPTION:
XS GIS Cut Line= 3
      1366480.00      6998613.00      1364171.90      6994471.43
      1360380.00      6990963.00
#Sta/Elev= 30
   258.7 1970.76   295.9 1969.55   529.4 1964.88   828.1 1958.36   935.4 1952.67
  1064.3 1950.76  1385.9 1945.33  2079.7 1941.18  2270.5 1940.09  2444.1 1939.00
  2607.3 1939.41  3019.2 1938.70  3248.3 1939.32  3379.6 1939.10  3534.0 1938.77
  4413.0 1937.54  4413.5 1937.04  4441.5 1937.54  4931.3 1937.69  5184.5 1938.95
  6698.7 1939.46  7165.5 1945.71  7727.7 1948.56  7844.7 1950.15  7944.0 1946.96
  7958.1 1950.58  7986.5 1951.53  8212.8 1950.24  9090.4 1954.12 10166.0 1964.15
#Mann=20,-1,0
   258.7   0.035       0   295.9   0.063       0   529.4    0.07       0
   828.1   0.035       0  1064.3    0.07       0  1385.9   0.035       0
  2079.7   0.035       0  2270.5    0.16       0  2444.1    0.07       0
  2607.3    0.16       0  3019.2    0.07       0  3248.3   0.035       0
  3379.6    0.07       0  3534.0   0.045       0  4413.0   0.035       0
  4441.5   0.045       0  4931.3   0.035       0  5184.5   0.045       0
  7727.7   0.035       0  8212.8   0.045       0
Bank Sta=4413,4441.5
Exp/Cntr=0.3,0.1

Type RM Length L Ch R = 1,31562,542,542,542
BEGIN DESCRIPTION:
UCFB HW Trib 04 35.0
END DESCRIPTION:
XS GIS Cut Line= 3
      1366612.88      6998539.76      1364337.47      6994001.19
      1360341.15      6990108.74
#Sta/Elev= 30
  -122.2 1969.64   219.9 1959.21   287.0 1960.89   393.1 1955.22   437.8 1957.40
   839.9 1947.13  1159.0 1944.61  1258.3 1943.66  1456.2 1942.03  1567.2 1941.70
  2033.8 1940.59  2118.0 1939.28  2233.2 1939.12  2455.3 1938.90  2647.1 1939.44
  2922.5 1939.43  4467.5 1937.38  4468.0 1936.88  4496.0 1937.38  4956.8 1938.27
  5203.1 1938.82  6647.6 1941.87  6733.7 1947.85  6769.2 1942.60  6790.3 1945.98
  7014.1 1946.29  8105.1 1951.44  8239.6 1952.39  8904.9 1954.39 10533.5 1972.64
#Mann=19,-1,0
  -122.2   0.035       0  1159.0   0.063       0  1258.3   0.035       0
  1456.2   0.063       0  1567.2    0.07       0  2033.8   0.035       0
  2118.0    0.07       0  2233.2   0.035       0  2455.3    0.16       0
  2647.1    0.07       0  2922.5   0.045       0  4467.5   0.035       0
  4496.0   0.045       0  4956.8   0.035       0  5203.1   0.045       0
  6647.6   0.035       0  7014.1   0.045       0  8105.1   0.035       0
  8239.6   0.045       0
Bank Sta=4467.5,4496
Exp/Cntr=0.3,0.1