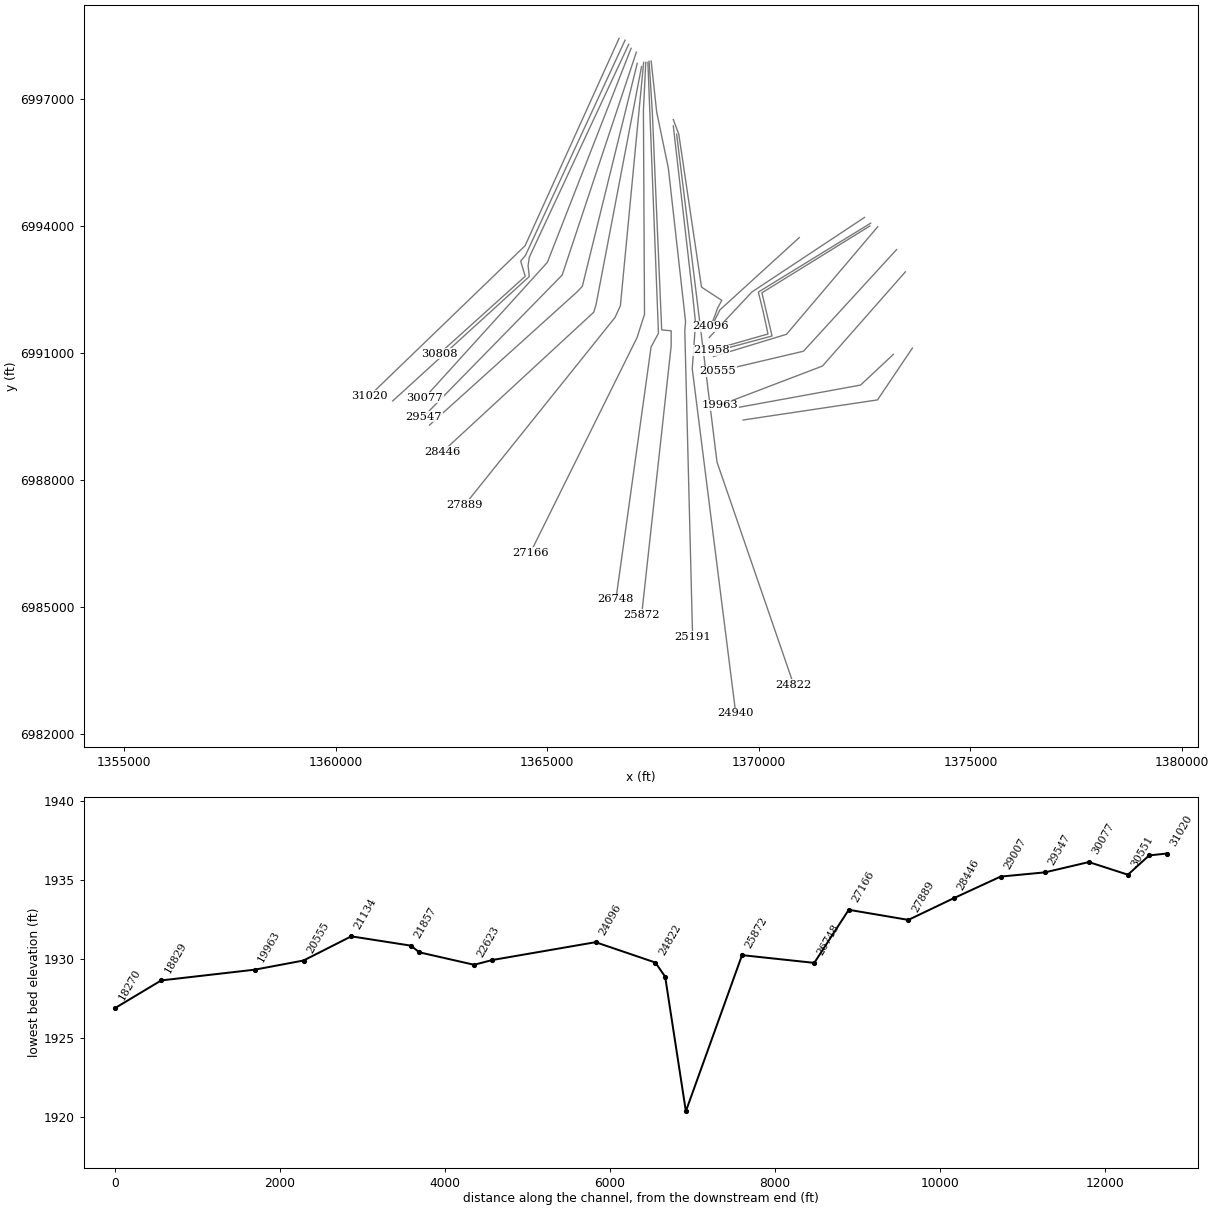
HEC-RAS study UCFB HW Trib 04.prj: UCFB HW Trib 04 Base Level Engineering

--- UCFB HW Trib 04.g01 (geometry) --- (continued)

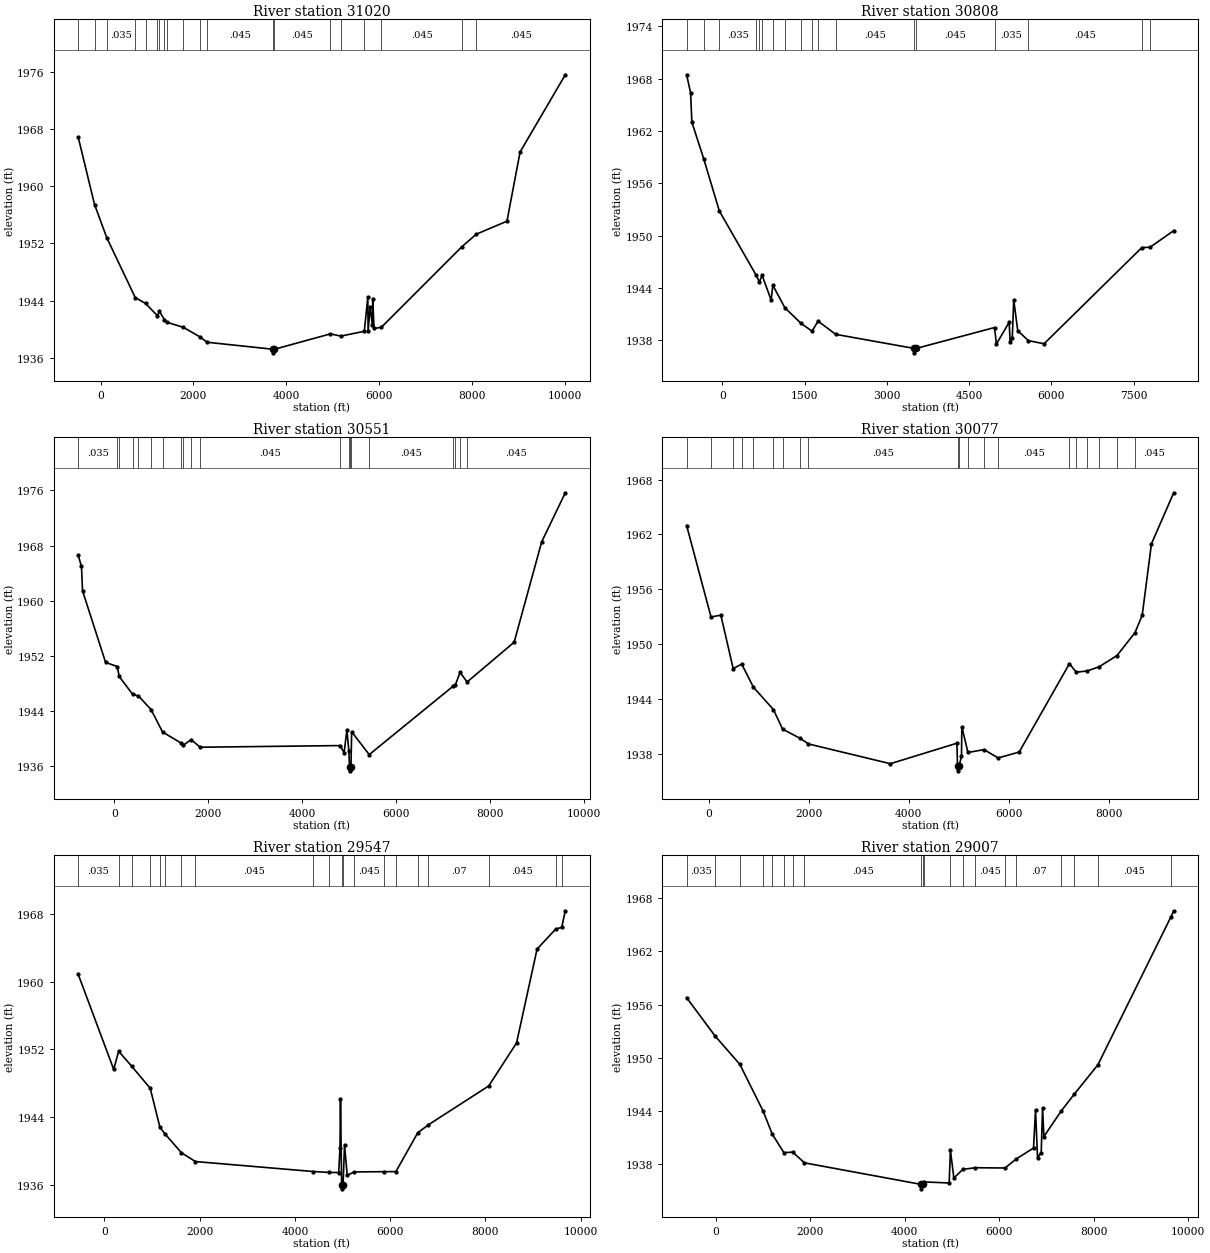
Type RM Length L Ch R = 1,31020,212,212,212
BEGIN DESCRIPTION:
UCFB HW Trib 04 34.0
END DESCRIPTION:
XS GIS Cut Line= 3
      1366699.68      6998431.25      1364478.78      6993531.58
      1360796.89      6989978.54
#Sta/Elev= 30
  -482.1 1966.83  -130.1 1957.42   132.5 1952.80   747.9 1944.41   969.6 1943.60
  1224.2 1941.89  1268.0 1942.50  1376.9 1941.33  1425.1 1940.98  1785.2 1940.26
  2138.5 1938.94  2296.1 1938.18  3717.7 1937.20  3718.2 1936.70  3746.2 1937.20
  4953.5 1939.35  5178.7 1939.04  5682.8 1939.71  5758.4 1944.45  5765.3 1939.72
  5807.8 1943.14  5857.4 1940.53  5864.4 1944.23  5892.7 1940.11  6049.2 1940.26
  7788.1 1951.54  8096.8 1953.28  8756.9 1955.09  9039.9 1964.76 10014.1 1975.55
#Mann=20,-1,0
  -482.1   0.035       0  -130.1    0.07       0   132.5   0.035       0
   747.9   0.063       0   969.6   0.063       0  1224.2   0.035       0
  1268.0   0.063       0  1376.9   0.035       0  1425.1    0.07       0
  1785.2   0.035       0  2138.5    0.07       0  2296.1   0.045       0
  3717.7   0.035       0  3746.2   0.045       0  4953.5   0.035       0
  5178.7   0.045       0  5682.8   0.035       0  6049.2   0.045       0
  7788.1   0.094       0  8096.8   0.045       0
Bank Sta=3717.7,3746.2
Exp/Cntr=0.3,0.1

Type RM Length L Ch R = 1,30808,257,257,257
BEGIN DESCRIPTION:
UCFB HW Trib 04 33.1
END DESCRIPTION:
XS GIS Cut Line= 5
      1366840.76      6998387.88      1364488.88      6993305.21
      1364374.61      6993167.51      1364481.17      6992808.06
      1362453.27      6990979.73
#Sta/Elev= 30
  -653.8 1968.44  -581.4 1966.38  -558.5 1963.02  -338.6 1958.74   -57.6 1952.84
   613.4 1945.49   673.0 1944.70   722.6 1945.47   888.7 1942.61   918.0 1944.33
  1138.6 1941.74  1428.0 1939.99  1633.1 1939.06  1744.5 1940.21  2065.1 1938.70
  3501.7 1937.08  3502.2 1936.58  3530.2 1937.08  4962.6 1939.48  4996.7 1937.59
  5229.4 1940.08  5247.5 1937.83  5286.0 1938.27  5312.8 1942.66  5385.7 1939.12
  5580.0 1937.98  5866.0 1937.62  7649.3 1948.64  7800.0 1948.68  8230.9 1950.58
#Mann=18,-1,0
  -653.8   0.035       0  -338.6    0.07       0   -57.6   0.035       0
   613.4    0.07       0   673.0   0.063       0   722.6   0.094       0
   918.0   0.063       0  1138.6   0.035       0  1428.0    0.07       0
  1633.1   0.035       0  1744.5    0.07       0  2065.1   0.045       0
  3501.7   0.035       0  3530.2   0.045       0  4962.6   0.035       0
  5580.0   0.045       0  7649.3   0.035       0  7800.0   0.045       0
Bank Sta=3501.7,3530.2
Exp/Cntr=0.3,0.1

Type RM Length L Ch R = 1,30551,474,474,474
BEGIN DESCRIPTION:
UCFB HW Trib 04 33.0
END DESCRIPTION:
XS GIS Cut Line= 5
      1366927.54      6998290.17      1364580.00      6993263.00
      1364549.27      6993061.96      1364576.96      6992802.23
      1361350.22      6989862.83
#Sta/Elev= 30
  -769.9 1966.56  -700.3 1964.99  -677.4 1961.44  -186.5 1951.07    62.0 1950.47
   103.2 1949.03   387.6 1946.47   514.1 1946.20   781.9 1944.24  1026.2 1941.00
  1416.7 1939.40  1464.7 1939.05  1636.9 1939.88  1829.1 1938.78  4807.7 1939.02
  4894.7 1937.99  4955.4 1941.29  4997.0 1938.19  5010.8 1935.86  5011.3 1935.36
  5041.1 1935.86  5056.1 1941.02  5430.4 1937.71  7216.0 1947.61  7265.7 1947.81
  7365.9 1949.63  7515.8 1948.23  8518.0 1953.99  9105.1 1968.54  9607.8 1975.64
#Mann=20,-1,0
  -769.9   0.035       0    62.0    0.07       0   103.2   0.035       0
   387.6    0.07       0   514.1   0.094       0   781.9   0.063       0
  1026.2   0.035       0  1416.7    0.07       0  1464.7   0.035       0
  1636.9    0.07       0  1829.1   0.045       0  4807.7   0.035       0
  4997.0    0.07       0  5010.8    0.07       0  5041.1    0.07       0
  5430.4   0.045       0  7216.0   0.035       0  7265.7   0.045       0
  7365.9   0.035       0  7515.8   0.045       0
Bank Sta=5010.8,5041.1
Exp/Cntr=0.3,0.1

Type RM Length L Ch R = 1,30077,530,530,530
BEGIN DESCRIPTION:
UCFB HW Trib 04 32.0
END DESCRIPTION:
XS GIS Cut Line= 3
      1366982.76      6998195.86      1365005.00      6993138.00
      1362104.97      6989937.97
#Sta/Elev= 30
  -446.2 1962.98    42.0 1952.98   238.7 1953.18   485.7 1947.34   656.6 1947.83
   892.1 1945.29  1291.1 1942.86  1474.6 1940.72  1829.6 1939.70  1992.7 1939.10
  3631.7 1936.94  4963.1 1939.18  4976.5 1936.66  4977.0 1936.16  5006.8 1936.66
  5055.2 1937.76  5062.7 1940.96  5184.3 1938.17  5507.6 1938.48  5787.6 1937.57
  6209.5 1938.21  7216.4 1947.88  7351.8 1946.94  7569.4 1947.08  7810.8 1947.54
  8165.5 1948.75  8528.8 1951.27  8672.9 1953.18  8857.5 1960.98  9303.2 1966.56
#Mann=20,-1,0
  -446.2   0.035       0    42.0    0.07       0   485.7   0.035       0
   656.6    0.07       0   892.1   0.035       0  1291.1   0.035       0
  1474.6    0.07       0  1829.6   0.035       0  1992.7   0.045       0
  4976.5    0.07       0  5006.8    0.07       0  5184.3   0.045       0
  5507.6   0.035       0  5787.6   0.045       0  7216.4   0.035       0
  7351.8   0.045       0  7569.4    0.07       0  7810.8   0.045       0
  8165.5    0.07       0  8528.8   0.045       0
Bank Sta=4976.5,5006.8
Exp/Cntr=0.3,0.1

Type RM Length L Ch R = 1,29547,540,540,540
BEGIN DESCRIPTION:
UCFB HW Trib 04 31.0
END DESCRIPTION:
XS GIS Cut Line= 3
      1367107.79      6998105.66      1365355.00      6992838.00
      1362081.33      6989493.56
#Sta/Elev= 30
  -551.6 1960.89   194.2 1949.64   297.5 1951.79   574.2 1950.00   960.6 1947.41
  1164.8 1942.80  1271.2 1942.01  1616.5 1939.78  1909.4 1938.74  4386.3 1937.56
  4719.9 1937.45  4920.9 1937.44  4947.3 1940.34  4957.9 1946.10  4982.2 1936.01
  4982.7 1935.51  5012.5 1936.01  5042.4 1940.71  5099.0 1937.12  5246.7 1937.51
  5866.3 1937.54  6121.9 1937.55  6579.3 1942.13  6804.7 1943.09  8071.2 1947.68
  8655.9 1952.77  9087.3 1963.88  9477.5 1966.24  9605.3 1966.45  9680.0 1968.41
#Mann=20,-1,0
  -551.6   0.035       0   297.5    0.07       0   574.2   0.035       0
   960.6   0.035       0  1164.8    0.07       0  1271.2   0.035       0
  1616.5    0.07       0  1909.4   0.045       0  4386.3   0.035       0
  4719.9    0.07       0  4982.2    0.07       0  5012.5    0.07       0
  5246.7   0.045       0  5866.3   0.035       0  6121.9   0.045       0
  6579.3   0.035       0  6804.7    0.07       0  8071.2   0.045       0
  9477.5    0.07       0  9605.3   0.045       0
Bank Sta=4982.2,5012.5
Exp/Cntr=0.3,0.1

Type RM Length L Ch R = 1,29007,561,561,561
BEGIN DESCRIPTION:
UCFB HW Trib 04 30.0
END DESCRIPTION:
XS GIS Cut Line= 4
      1367128.61      6997841.75      1365830.74      6992569.87
      1365705.00      6992438.00      1362220.22      6989293.91
#Sta/Elev= 30
  -611.5 1956.79    -8.8 1952.47   514.9 1949.27  1005.9 1944.02  1200.5 1941.40
  1446.6 1939.32  1632.3 1939.38  1882.0 1938.17  4351.4 1935.74  4351.9 1935.24
  4381.7 1935.74  4413.7 1936.02  4943.5 1935.90  4968.8 1939.61  5042.2 1936.45
  5230.9 1937.43  5491.0 1937.62  6126.5 1937.59  6356.5 1938.59  6727.4 1939.84
  6770.0 1944.13  6812.6 1938.76  6890.4 1939.33  6918.8 1944.34  6947.2 1941.14
  7311.2 1944.00  7589.2 1945.91  8091.3 1949.24  9630.2 1965.86  9693.5 1966.59
#Mann=20,-1,0
  -611.5   0.035       0    -8.8   0.035       0   514.9   0.063       0
  1005.9    0.07       0  1200.5   0.035       0  1446.6    0.07       0
  1632.3   0.035       0  1882.0   0.045       0  4351.4   0.035       0
  4381.7   0.035       0  4413.7    0.07       0  4968.8   0.035       0
  5230.9    0.16       0  5491.0   0.045       0  6126.5   0.035       0
  6356.5    0.07       0  7311.2   0.045       0  7589.2    0.07       0
  8091.3   0.045       0  9630.2   0.045       0
Bank Sta=4351.4,4381.7
Exp/Cntr=0.3,0.1

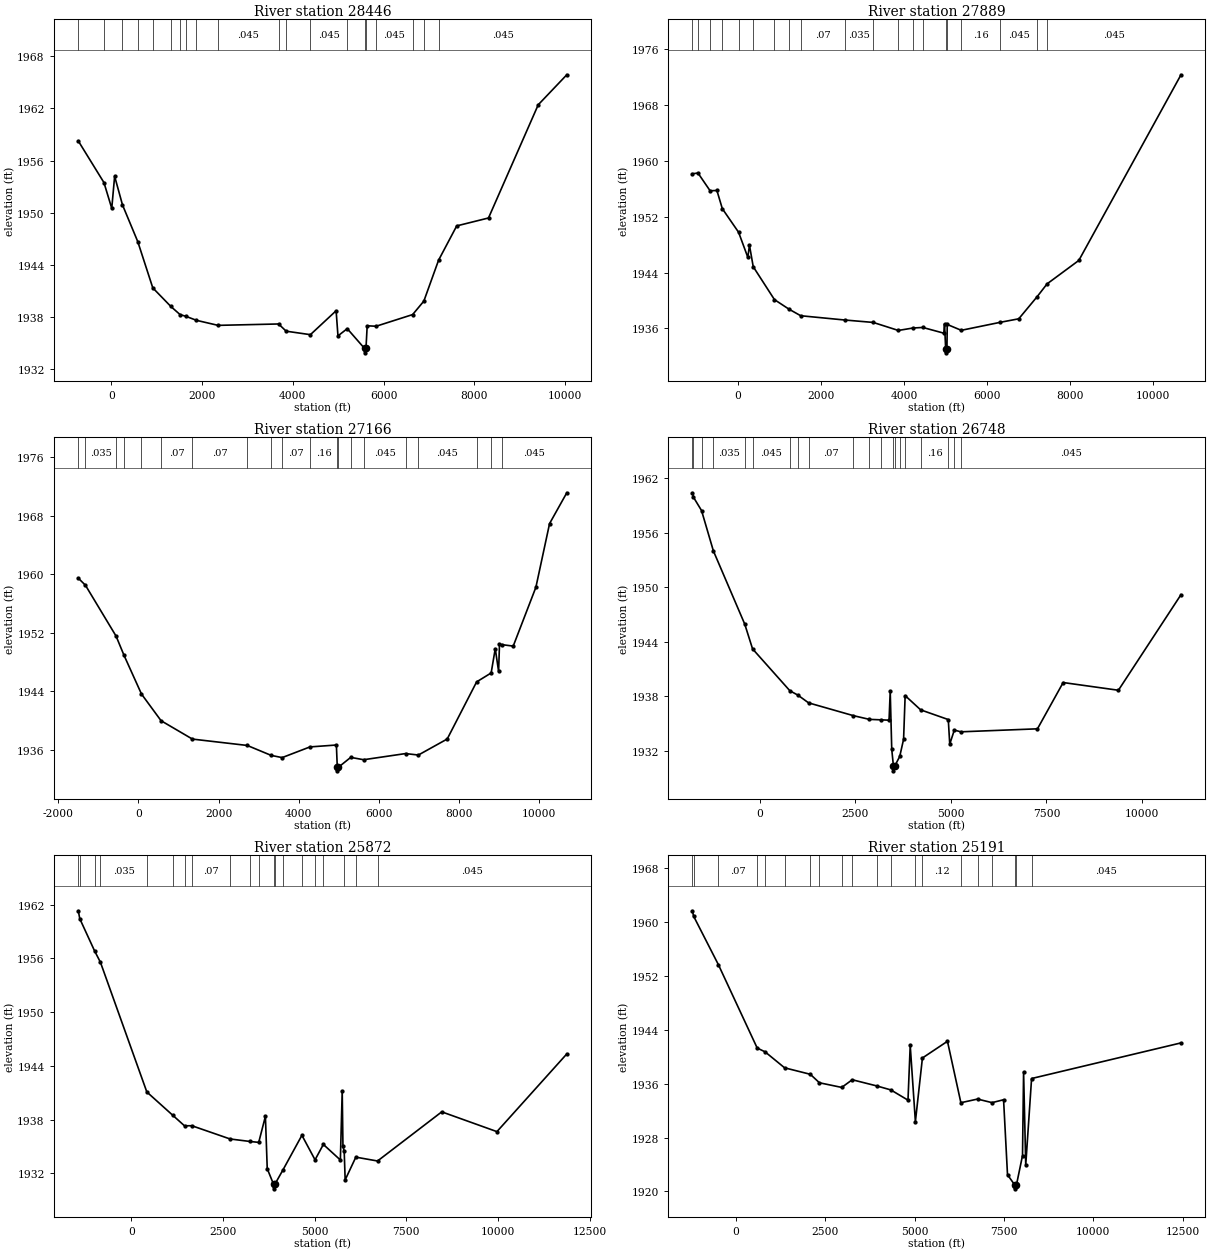
Type RM Length L Ch R = 1,28446,557,557,557
BEGIN DESCRIPTION:
UCFB HW Trib 04 29.0
END DESCRIPTION:
XS GIS Cut Line= 4
      1367230.01      6997763.05      1366155.00      6992138.00
      1366100.83      6991959.78      1362530.01      6988663.01
#Sta/Elev= 30
  -731.4 1958.26  -165.2 1953.47     6.8 1950.51    70.3 1954.20   243.7 1950.90
   581.3 1946.67   911.8 1941.36  1310.6 1939.22  1513.1 1938.29  1647.1 1938.08
  1874.5 1937.63  2351.2 1937.05  3686.3 1937.21  3852.8 1936.38  4387.4 1935.98
  4954.7 1938.73  4995.4 1935.84  5200.1 1936.67  5582.7 1934.39  5583.2 1933.89
  5613.0 1934.39  5639.8 1937.00  5837.5 1936.95  6641.8 1938.29  6889.4 1939.84
  7214.5 1944.55  7614.2 1948.49  8315.1 1949.40  9411.7 1962.42 10041.7 1965.87
#Mann=20,-1,0
  -731.4   0.035       0  -165.2   0.035       0   243.7   0.035       0
   581.3    0.07       0   911.8   0.045       0  1310.6    0.07       0
  1513.1   0.035       0  1647.1    0.07       0  1874.5   0.035       0
  2351.2   0.045       0  3686.3   0.045       0  3852.8    0.07       0
  4387.4   0.045       0  5200.1    0.16       0  5582.7   0.035       0
  5613.0    0.16       0  5837.5   0.045       0  6641.8   0.035       0
  6889.4    0.07       0  7214.5   0.045       0
Bank Sta=5582.7,5613
Exp/Cntr=0.3,0.1

Type RM Length L Ch R = 1,27889,723,723,723
BEGIN DESCRIPTION:
UCFB HW Trib 04 28.0
END DESCRIPTION:
XS GIS Cut Line= 4
      1367280.00      6997863.01      1366730.00      6992113.00
      1366605.00      6991838.00      1363055.81      6987411.51
#Sta/Elev= 30
 -1086.5 1958.18  -953.9 1958.28  -662.8 1955.74  -498.8 1955.78  -368.4 1953.17
    22.9 1949.79   244.6 1946.20   284.7 1947.92   375.0 1944.85   885.6 1940.13
  1235.9 1938.76  1517.1 1937.82  2571.7 1937.21  3261.6 1936.86  3866.0 1935.71
  4218.4 1936.06  4453.9 1936.14  4960.0 1935.32  4977.5 1936.67  5004.7 1933.00
  5005.2 1932.50  5035.0 1933.00  5042.2 1936.57  5380.2 1935.73  6319.7 1936.88
  6762.7 1937.38  7206.1 1940.56  7444.3 1942.39  8207.8 1945.75 10665.5 1972.37
#Mann=20,-1,0
 -1086.5   0.035       0  -953.9   0.035       0  -662.8    0.07       0
  -368.4   0.035       0    22.9   0.035       0   375.0    0.07       0
   885.6   0.045       0  1235.9    0.07       0  1517.1    0.07       0
  2571.7   0.035       0  3261.6   0.045       0  3866.0   0.045       0
  4218.4   0.045       0  4453.9    0.07       0  5004.7    0.07       0
  5035.0    0.07       0  5380.2    0.16       0  6319.7   0.045       0
  7206.1   0.035       0  7444.3   0.045       0
Bank Sta=5004.7,5035
Exp/Cntr=0.3,0.1

Type RM Length L Ch R = 1,27166,418,418,418
BEGIN DESCRIPTION:
UCFB HW Trib 04 27.0
END DESCRIPTION:
XS GIS Cut Line= 5
      1367330.00      6997862.99      1367274.44      6996723.67
      1367300.24      6991909.78      1367123.68      6991359.74
      1364606.66      6986282.30
#Sta/Elev= 30
 -1502.9 1959.48 -1324.1 1958.51  -559.4 1951.56  -360.6 1948.93    75.4 1943.64
   564.6 1939.99  1347.4 1937.48  2717.2 1936.61  3315.1 1935.25  3588.5 1934.95
  4282.8 1936.41  4942.6 1936.67  4964.9 1933.64  4965.4 1933.14  4995.2 1933.64
  5300.6 1934.98  5623.5 1934.66  6670.1 1935.50  6989.9 1935.30  7710.1 1937.49
  8444.8 1945.30  8807.5 1946.52  8910.1 1949.84  8993.6 1946.74  9015.9 1950.43
  9076.2 1950.39  9358.5 1950.19  9924.5 1958.23 10266.4 1966.94 10696.5 1971.15
#Mann=20,-1,0
 -1502.9   0.035       0 -1324.1   0.035       0  -559.4   0.063       0
  -360.6   0.035       0    75.4   0.045       0   564.6    0.07       0
  1347.4    0.07       0  2717.2    0.07       0  3315.1   0.045       0
  3588.5    0.07       0  4282.8    0.16       0  4964.9    0.07       0
  4995.2    0.16       0  5300.6    0.16       0  5623.5   0.045       0
  6670.1    0.07       0  6989.9   0.045       0  8444.8   0.035       0
  8807.5   0.035       0  9076.2   0.045       0
Bank Sta=4964.9,4995.2
Exp/Cntr=0.3,0.1

Type RM Length L Ch R = 1,26748,876,876,876
BEGIN DESCRIPTION:
UCFB HW Trib 04 26.0
END DESCRIPTION:
XS GIS Cut Line= 4
      1367380.00      6997863.03      1367630.00      6991463.00
      1367455.00      6991138.00      1366624.55      6985174.88
#Sta/Elev= 30
 -1769.7 1960.42 -1743.7 1959.93 -1532.1 1958.46 -1221.8 1954.01  -400.9 1945.95
  -196.1 1943.22   782.2 1938.60   992.6 1938.12  1271.3 1937.27  2445.2 1935.86
  2865.2 1935.45  3172.7 1935.40  3379.2 1935.36  3409.3 1938.55  3449.3 1932.15
  3494.2 1930.28  3494.7 1929.78  3524.5 1930.28  3658.8 1931.37  3759.5 1933.26
  3800.3 1938.07  4206.2 1936.50  4930.2 1935.43  4968.6 1932.72  5088.1 1934.27
  5260.7 1934.08  7265.9 1934.41  7939.0 1939.51  9385.8 1938.66 11025.0 1949.19
#Mann=20,-1,0
 -1769.7   0.035       0 -1743.7    0.07       0 -1532.1   0.035       0
 -1221.8   0.035       0  -400.9   0.063       0  -196.1   0.045       0
   782.2   0.045       0   992.6    0.07       0  1271.3    0.07       0
  2445.2    0.07       0  2865.2   0.045       0  3172.7    0.07       0
  3494.2    0.07       0  3524.5    0.07       0  3658.8   0.035       0
  3800.3    0.07       0  4206.2    0.16       0  4930.2    0.16       0
  5088.1    0.07       0  5260.7   0.045       0
Bank Sta=3494.2,3524.5
Exp/Cntr=0.3,0.1

Type RM Length L Ch R = 1,25872,681,681,681
BEGIN DESCRIPTION:
UCFB HW Trib 04 25.9
END DESCRIPTION:
XS GIS Cut Line= 6
      1367408.13      6997888.47      1367482.78      6996723.67
      1367706.30      6991542.14      1367930.26      6991520.44
      1367930.00      6991163.00      1367232.18      6984805.87
#Sta/Elev= 30
 -1452.3 1961.33 -1411.0 1960.44 -1007.8 1956.85  -847.9 1955.58   418.5 1941.09
  1125.0 1938.49  1446.6 1937.31  1646.0 1937.32  2690.3 1935.84  3236.4 1935.56
  3472.1 1935.46  3654.2 1938.37  3704.3 1932.52  3877.8 1930.77  3878.4 1930.27
  3911.1 1930.77  4130.1 1932.36  4650.5 1936.25  5009.0 1933.51  5235.5 1935.23
  5700.0 1933.49  5750.3 1941.22  5770.4 1935.04  5804.6 1934.45  5830.8 1931.27
  6122.0 1933.81  6714.5 1933.38  8466.5 1938.87  9972.4 1936.66 11879.0 1945.34
#Mann=20,-1,0
 -1452.3   0.035       0 -1411.0    0.07       0 -1007.8    0.07       0
  -847.9   0.035       0   418.5   0.045       0  1125.0   0.045       0
  1446.6    0.07       0  1646.0    0.07       0  2690.3    0.07       0
  3236.4   0.045       0  3472.1    0.07       0  3877.8    0.07       0
  3911.1   0.035       0  4130.1    0.07       0  4650.5    0.16       0
  5009.0   0.035       0  5235.5    0.07       0  5804.6    0.16       0
  6122.0   0.035       0  6714.5   0.045       0
Bank Sta=3877.8,3911.1
Exp/Cntr=0.3,0.1

Type RM Length L Ch R = 1,25191,251,251,251
BEGIN DESCRIPTION:
UCFB HW Trib 04 25.8
END DESCRIPTION:
XS GIS Cut Line= 6
      1367457.61      6997893.66      1367587.46      6996692.41
      1367863.32      6995364.93      1368270.06      6991738.15
      1368252.15      6991522.50      1368436.62      6984285.04
#Sta/Elev= 30
 -1213.6 1961.68 -1184.2 1960.90  -489.7 1953.69   597.3 1941.30   818.7 1940.73
  1364.7 1938.36  2083.7 1937.40  2338.7 1936.14  2962.5 1935.45  3257.0 1936.59
  3944.2 1935.67  4336.8 1935.08  4817.0 1933.56  4879.4 1941.68  5024.1 1930.37
  5220.9 1939.82  5921.5 1942.30  6297.0 1933.18  6763.3 1933.72  7169.6 1933.19
  7491.7 1933.62  7601.7 1922.48  7814.4 1920.89  7815.1 1920.39  7849.0 1920.89
  8021.8 1925.34  8051.8 1937.75  8111.8 1923.92  8275.4 1936.77 12456.2 1942.06
#Mann=20,-1,0
 -1213.6   0.035       0 -1184.2    0.07       0  -489.7    0.07       0
   597.3    0.07       0   818.7   0.045       0  1364.7    0.07       0
  2083.7   0.035       0  2338.7    0.07       0  2962.5    0.07       0
  3257.0    0.07       0  3944.2   0.035       0  4336.8   0.035       0
  5024.1   0.035       0  5220.9    0.12       0  6297.0    0.16       0
  6763.3    0.16       0  7169.6    0.16       0  7814.4    0.07       0
  7849.0    0.07       0  8275.4   0.045       0
Bank Sta=7814.4,7849
Exp/Cntr=0.3,0.1

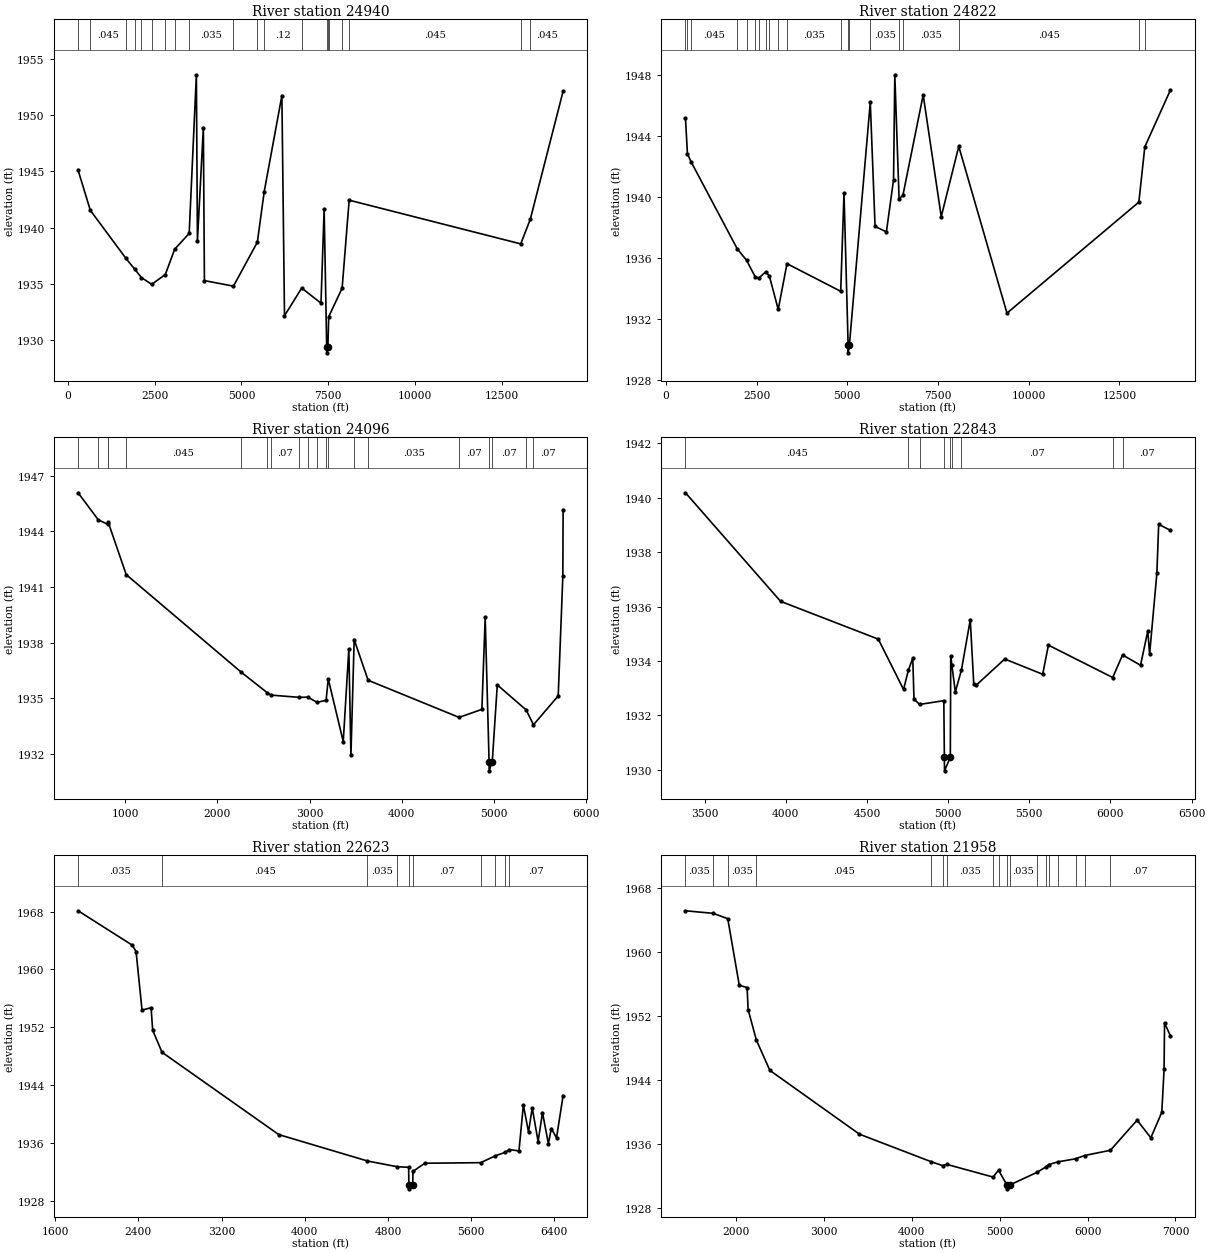
Type RM Length L Ch R = 1,24940,118,118,118
BEGIN DESCRIPTION:
UCFB HW Trib 04 25.76
END DESCRIPTION:
XS GIS Cut Line= 5
      1367980.00      6996363.01      1368437.20      6992374.26
      1368506.06      6991700.45      1368427.93      6990624.06
      1369455.00      6982488.04
#Sta/Elev= 30
   294.9 1945.11   647.1 1941.55  1671.3 1937.29  1923.5 1936.33  2120.5 1935.58
  2414.5 1934.98  2807.2 1935.85  3075.7 1938.09  3494.6 1939.50  3702.1 1953.58
  3732.3 1938.84  3903.4 1948.90  3933.6 1935.31  4770.6 1934.82  5458.3 1938.72
  5654.9 1943.18  6165.4 1951.73  6240.6 1932.19  6736.2 1934.65  7292.0 1933.31
  7382.7 1941.67  7456.1 1929.40  7456.8 1928.90  7490.7 1929.40  7515.0 1932.11
  7900.8 1934.64  8103.4 1942.45 13045.8 1938.57 13322.0 1940.76 14266.9 1952.12
#Mann=20,-1,0
   294.9   0.035       0   647.1   0.045       0  1671.3    0.07       0
  1923.5   0.045       0  2120.5    0.07       0  2414.5    0.07       0
  2807.2    0.07       0  3075.7   0.063       0  3494.6   0.035       0
  4770.6   0.063       0  5458.3    0.07       0  5654.9    0.12       0
  6736.2   0.035       0  7456.1   0.063       0  7490.7    0.16       0
  7515.0   0.035       0  7900.8   0.035       0  8103.4   0.045       0
 13045.8   0.035       0 13322.0   0.045       0
Bank Sta=7456.1,7490.7
Exp/Cntr=0.3,0.1

Type RM Length L Ch R = 1,24822,726,726,726
BEGIN DESCRIPTION:
UCFB HW Trib 04 25.77
END DESCRIPTION:
XS GIS Cut Line= 3
      1368059.44      6996166.19      1369012.29      6988421.28
      1370825.48      6983156.25
#Sta/Elev= 30
   537.4 1945.18   591.8 1942.83   690.0 1942.32  1967.4 1936.60  2220.1 1935.87
  2458.7 1934.78  2557.0 1934.69  2753.5 1935.11  2851.8 1934.82  3094.8 1932.64
  3336.2 1935.64  4817.0 1933.83  4908.3 1940.28  5022.0 1930.30  5022.7 1929.80
  5056.6 1930.30  5632.8 1946.21  5764.7 1938.08  6077.0 1937.72  6274.1 1941.13
  6308.8 1948.01  6426.7 1939.89  6531.8 1940.11  7091.6 1946.69  7589.2 1938.72
  8072.3 1943.32  9401.8 1932.40 13037.6 1939.67 13202.0 1943.29 13909.2 1947.02
#Mann=20,-1,0
   537.4   0.063       0   591.8   0.035       0   690.0   0.045       0
  1967.4   0.045       0  2220.1    0.07       0  2458.7   0.063       0
  2557.0    0.07       0  2753.5   0.035       0  2851.8    0.07       0
  3094.8   0.063       0  3336.2   0.035       0  4817.0    0.07       0
  5022.0    0.07       0  5056.6    0.07       0  5632.8   0.035       0
  6426.7    0.07       0  6531.8   0.035       0  8072.3   0.045       0
 13037.6   0.035       0 13202.0   0.045       0
Bank Sta=5022,5056.6
Exp/Cntr=0.3,0.1

Type RM Length L Ch R = 1,24096,1253,1253,1253
BEGIN DESCRIPTION:
UCFB HW Trib 04 25.71
END DESCRIPTION:
XS GIS Cut Line= 6
      1367979.99      6996513.02      1368110.19      6996165.62
      1368646.68      6992552.88      1369125.85      6992240.38
      1369030.00      6992063.00      1368869.68      6991628.15
#Sta/Elev= 30
   490.2 1946.07   709.5 1944.61   812.9 1944.37   816.9 1944.48  1012.2 1941.66
  2253.3 1936.43  2541.3 1935.30  2582.3 1935.17  2884.3 1935.05  2982.8 1935.06
  3081.3 1934.78  3179.8 1934.89  3203.4 1936.04  3366.0 1932.66  3426.6 1937.66
  3449.4 1931.94  3484.5 1938.16  3635.6 1935.97  4622.4 1933.97  4869.7 1934.40
  4905.5 1939.36  4947.8 1931.59  4948.5 1931.09  4982.4 1931.59  5036.8 1935.72
  5350.1 1934.37  5429.4 1933.57  5697.6 1935.13  5747.7 1941.57  5750.7 1945.16
#Mann=20,-1,0
   490.2   0.035       0   709.5    0.07       0   812.9   0.063       0
   816.9   0.035       0  1012.2   0.045       0  2253.3    0.07       0
  2541.3   0.045       0  2582.3    0.07       0  2884.3   0.063       0
  2982.8    0.07       0  3081.3   0.035       0  3179.8    0.07       0
  3203.4   0.063       0  3484.5    0.07       0  3635.6   0.035       0
  4622.4    0.07       0  4947.8    0.07       0  4982.4    0.07       0
  5350.1   0.035       0  5429.4    0.07       0
Bank Sta=4947.8,4982.4
Exp/Cntr=0.3,0.1

Type RM Length L Ch R = 1,22843,220,220,220
BEGIN DESCRIPTION:
UCFB HW Trib 04 25.75
END DESCRIPTION:
XS GIS Cut Line= 3
      1370957.27      6993723.58      1369080.00      6992013.00
      1368880.02      6991613.04
#Sta/Elev= 30
  3382.6 1940.18  3968.3 1936.19  4570.3 1934.80  4725.7 1932.95  4754.9 1933.65
  4782.5 1934.10  4789.9 1932.60  4824.0 1932.40  4973.7 1932.54  4977.0 1930.46
  4977.9 1929.96  5013.7 1930.46  5016.3 1934.18  5022.8 1933.86  5044.6 1932.86
  5082.3 1933.67  5136.5 1935.51  5157.9 1933.17  5171.7 1933.10  5348.7 1934.07
  5582.5 1933.51  5617.9 1934.58  6013.7 1933.39  6074.5 1934.22  6185.1 1933.84
  6229.8 1935.10  6241.0 1934.25  6285.7 1937.22  6296.9 1939.02  6369.5 1938.80
#Mann=9,-1,0
  3382.6   0.045       0  4754.9   0.035       0  4824.0    0.07       0
  4977.0    0.07       0  5013.7    0.07       0  5022.8    0.16       0
  5082.3    0.07       0  6013.7   0.035       0  6074.5    0.07       0
Bank Sta=4977,5013.7
Exp/Cntr=0.3,0.1

Type RM Length L Ch R = 1,22623,665,665,665
BEGIN DESCRIPTION:
UCFB HW Trib 04 25.6
END DESCRIPTION:
XS GIS Cut Line= 3
      1372497.57      6994198.89      1369838.70      6992438.41
      1368830.01      6991363.01
#Sta/Elev= 30
  1820.7 1968.11  2342.0 1963.35  2378.1 1962.47  2435.4 1954.37  2522.5 1954.71
  2537.6 1951.60  2627.7 1948.54  3750.1 1937.16  4603.0 1933.51  4887.7 1932.72
  4998.6 1932.64  5001.3 1930.16  5002.2 1929.66  5038.0 1930.16  5040.7 1932.07
  5154.0 1933.20  5692.3 1933.28  5830.1 1934.21  5924.1 1934.69  5967.8 1935.09
  6059.5 1934.90  6102.0 1941.25  6151.4 1937.51  6187.0 1940.85  6243.7 1936.20
  6285.7 1940.20  6342.4 1935.92  6370.7 1938.00  6420.5 1936.70  6484.0 1942.55
#Mann=10,-1,0
  1820.7   0.035       0  2627.7   0.045       0  4603.0   0.035       0
  4887.7    0.07       0  5001.3    0.07       0  5038.0    0.07       0
  5692.3   0.035       0  5830.1    0.07       0  5924.1    0.16       0
  5967.8    0.07       0
Bank Sta=5001.3,5038
Exp/Cntr=0.3,0.1

Type RM Length L Ch R = 1,21958,101,101,101
BEGIN DESCRIPTION:
UCFB HW Trib 04 25.2
END DESCRIPTION:
XS GIS Cut Line= 5
      1372642.78      6994062.78      1369989.81      6992435.41
      1370102.65      6991979.68      1370217.67      6991445.82
      1368880.00      6991063.00
#Sta/Elev= 30
  1424.0 1965.15  1739.8 1964.83  1905.3 1964.16  2036.4 1955.85  2125.3 1955.57
  2137.0 1952.82  2231.0 1949.01  2384.5 1945.23  3404.0 1937.27  4221.1 1933.83
  4350.7 1933.35  4398.1 1933.50  4925.1 1931.92  4986.3 1932.78  5081.2 1930.95
  5082.1 1930.45  5118.0 1930.95  5423.2 1932.50  5526.0 1933.19  5556.8 1933.47
  5659.0 1933.81  5863.3 1934.20  5965.5 1934.61  6259.6 1935.26  6563.6 1939.02
  6719.7 1936.82  6844.5 1940.00  6870.5 1945.35  6875.8 1951.15  6943.3 1949.53
#Mann=18,-1,0
  1424.0   0.035       0  1739.8    0.07       0  1905.3   0.035       0
  2231.0   0.045       0  4221.1   0.035       0  4350.7    0.07       0
  4398.1   0.035       0  4925.1    0.07       0  4986.3   0.035       0
  5081.2   0.035       0  5118.0   0.035       0  5423.2    0.07       0
  5526.0   0.035       0  5556.8    0.07       0  5659.0    0.16       0
  5863.3   0.035       0  5965.5    0.16       0  6259.6    0.07       0
Bank Sta=5081.2,5118
Exp/Cntr=0.3,0.1

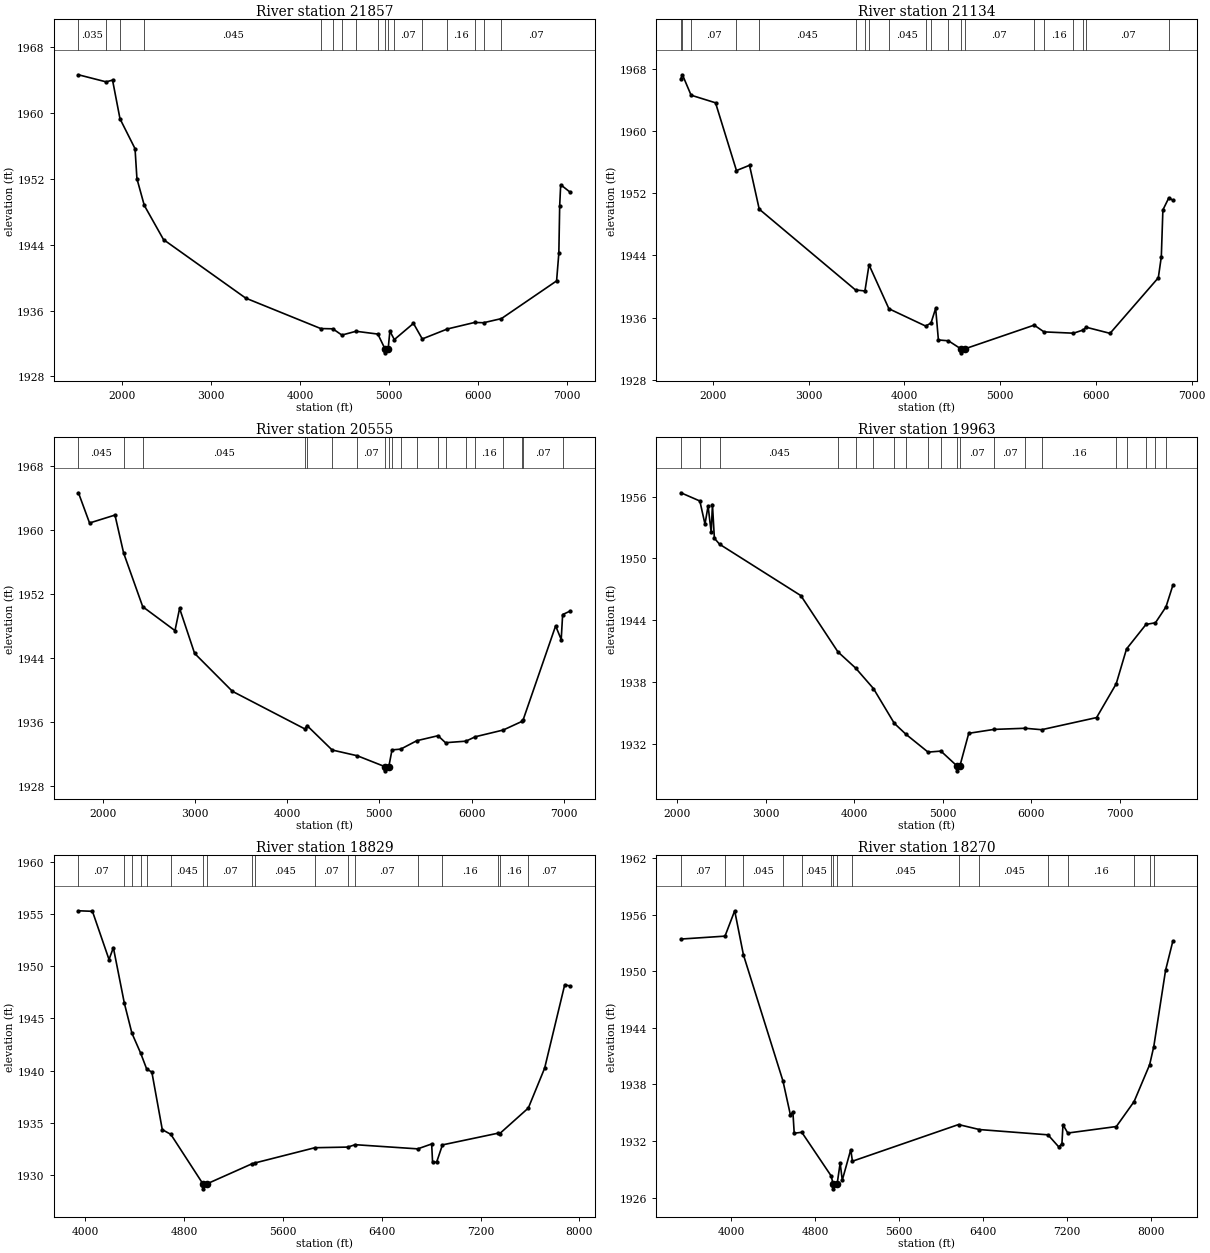
Type RM Length L Ch R = 1,21857,723,723,723
BEGIN DESCRIPTION:
UCFB HW Trib 04 25.1
END DESCRIPTION:
XS GIS Cut Line= 4
      1372623.64      6993996.12      1370074.44      6992418.05
      1370313.16      6991398.08      1368880.03      6991013.01
#Sta/Elev= 30
  1508.4 1964.66  1819.2 1963.80  1891.7 1964.01  1975.5 1959.31  2144.5 1955.68
  2165.8 1952.03  2248.4 1948.79  2464.8 1944.63  3388.6 1937.52  4232.4 1933.82
  4367.6 1933.79  4469.6 1933.03  4628.9 1933.49  4874.1 1933.15  4953.4 1931.37
  4954.3 1930.87  4990.2 1931.37  5009.1 1933.51  5059.4 1932.48  5274.3 1934.45
  5373.4 1932.56  5655.6 1933.77  5960.9 1934.56  6062.7 1934.53  6263.0 1935.03
  6883.3 1939.61  6908.6 1942.99  6918.1 1948.75  6929.3 1951.30  7038.0 1950.37
#Mann=17,-1,0
  1508.4   0.035       0  1819.2    0.07       0  1975.5   0.035       0
  2248.4   0.045       0  4232.4   0.035       0  4367.6    0.07       0
  4469.6   0.035       0  4628.9    0.07       0  4874.1   0.035       0
  4953.4   0.035       0  4990.2   0.035       0  5059.4    0.07       0
  5373.4   0.035       0  5655.6    0.16       0  5960.9   0.035       0
  6062.7    0.16       0  6263.0    0.07       0
Bank Sta=4953.4,4990.2
Exp/Cntr=0.3,0.1

Type RM Length L Ch R = 1,21134,579,579,579
BEGIN DESCRIPTION:
UCFB HW Trib 04 25.0
END DESCRIPTION:
XS GIS Cut Line= 3
      1372812.13      6993980.81      1370655.00      6991438.00
      1368930.04      6990913.01
#Sta/Elev= 30
  1665.7 1966.80  1681.6 1967.28  1772.0 1964.65  2027.3 1963.67  2245.8 1954.94
  2382.1 1955.62  2483.7 1949.97  3489.2 1939.56  3587.7 1939.43  3630.4 1942.80
  3838.1 1937.14  4221.7 1934.91  4277.7 1935.30  4326.3 1937.19  4354.9 1933.12
  4460.0 1933.01  4591.3 1931.96  4592.2 1931.46  4628.2 1931.96  5355.4 1935.03
  5458.0 1934.16  5765.9 1933.99  5868.6 1934.41  5898.2 1934.76  6147.8 1933.97
  6651.8 1941.13  6683.1 1943.83  6699.6 1949.87  6760.9 1951.41  6803.3 1951.14
#Mann=20,-1,0
  1665.7    0.07       0  1681.6   0.035       0  1772.0    0.07       0
  2245.8   0.035       0  2483.7   0.045       0  3489.2    0.07       0
  3587.7   0.045       0  3630.4   0.035       0  3838.1   0.045       0
  4221.7    0.07       0  4277.7   0.035       0  4460.0    0.07       0
  4591.3    0.07       0  4628.2    0.07       0  5355.4   0.035       0
  5458.0    0.16       0  5765.9   0.035       0  5868.6    0.16       0
  5898.2    0.07       0  6760.9   0.035       0
Bank Sta=4591.3,4628.2
Exp/Cntr=0.3,0.1

Type RM Length L Ch R = 1,20555,592,592,592
BEGIN DESCRIPTION:
UCFB HW Trib 04 24.0
END DESCRIPTION:
XS GIS Cut Line= 3
      1373254.99      6993437.99      1371055.00      6991038.00
      1369029.41      6990561.21
#Sta/Elev= 30
  1735.5 1964.61  1856.0 1960.84  2131.7 1961.83  2225.3 1957.11  2432.9 1950.40
  2782.8 1947.42  2832.8 1950.19  2995.6 1944.58  3405.6 1939.85  4193.0 1935.15
  4215.1 1935.58  4487.5 1932.53  4760.9 1931.81  5065.3 1930.43  5066.2 1929.93
  5102.2 1930.43  5137.3 1932.54  5232.1 1932.64  5406.7 1933.69  5636.4 1934.31
  5717.7 1933.44  5939.6 1933.63  6040.6 1934.18  6343.8 1935.02  6546.0 1936.09
  6561.2 1936.33  6912.4 1948.01  6973.0 1946.31  6988.5 1949.42  7072.2 1949.87
#Mann=20,-1,0
  1735.5   0.045       0  2225.3   0.035       0  2432.9   0.045       0
  4193.0    0.07       0  4215.1   0.035       0  4487.5    0.07       0
  4760.9    0.07       0  5065.3    0.07       0  5102.2    0.07       0
  5137.3    0.07       0  5232.1    0.16       0  5406.7    0.07       0
  5636.4   0.035       0  5717.7    0.07       0  5939.6   0.035       0
  6040.6    0.16       0  6343.8    0.07       0  6546.0    0.16       0
  6561.2    0.07       0  6988.5   0.035       0
Bank Sta=5065.3,5102.2
Exp/Cntr=0.3,0.1

Type RM Length L Ch R = 1,19963,1134,1134,1134
BEGIN DESCRIPTION:
UCFB HW Trib 04 23.0
END DESCRIPTION:
XS GIS Cut Line= 3
      1373463.20      6992913.13      1371505.00      6990688.00
      1369080.01      6989763.00
#Sta/Elev= 30
  2040.6 1956.39  2254.6 1955.59  2312.6 1953.34  2347.7 1955.11  2382.8 1952.54
  2397.0 1955.25  2418.8 1951.97  2477.0 1951.39  3396.1 1946.39  3815.1 1940.92
  4015.6 1939.34  4216.8 1937.35  4452.3 1933.97  4584.7 1932.90  4834.0 1931.17
  4979.2 1931.27  5157.5 1929.85  5158.4 1929.35  5194.4 1929.85  5293.7 1933.00
  5579.2 1933.38  5929.9 1933.49  6117.5 1933.35  6738.5 1934.53  6960.1 1937.81
  7076.7 1941.20  7297.3 1943.59  7403.8 1943.75  7523.1 1945.30  7600.1 1947.38
#Mann=20,-1,0
  2040.6   0.045       0  2254.6   0.035       0  2477.0   0.045       0
  3815.1   0.035       0  4015.6    0.16       0  4216.8   0.035       0
  4452.3    0.07       0  4584.7    0.16       0  4834.0    0.16       0
  4979.2    0.07       0  5157.5    0.07       0  5194.4    0.07       0
  5579.2    0.07       0  5929.9   0.035       0  6117.5    0.16       0
  6960.1    0.16       0  7076.7    0.07       0  7297.3    0.07       0
  7403.8    0.16       0  7523.1    0.07       0
Bank Sta=5157.5,5194.4
Exp/Cntr=0.3,0.1

Type RM Length L Ch R = 1,18829,559,559,559
BEGIN DESCRIPTION:
UCFB HW Trib 04 22.0
END DESCRIPTION:
XS GIS Cut Line= 3
      1373179.96      6990962.97      1372405.00      6990238.00
      1369530.04      6989713.01
#Sta/Elev= 30
  3943.9 1955.31  4057.2 1955.26  4191.5 1950.64  4226.7 1951.78  4315.7 1946.45
  4376.9 1943.58  4447.7 1941.67  4496.8 1940.14  4538.3 1939.86  4622.9 1934.34
  4692.0 1933.89  4950.7 1929.17  4951.7 1928.67  4988.7 1929.17  5345.5 1931.05
  5376.5 1931.16  5858.8 1932.61  6125.5 1932.67  6184.9 1932.90  6691.6 1932.50
  6804.4 1932.97  6811.9 1931.20  6845.0 1931.24  6891.7 1932.88  7341.3 1934.00
  7356.4 1933.97  7587.1 1936.41  7719.3 1940.23  7881.9 1948.22  7927.6 1948.10
#Mann=18,-1,0
  3943.9    0.07       0  4315.7    0.16       0  4376.9    0.07       0
  4447.7    0.16       0  4496.8   0.035       0  4692.0   0.045       0
  4950.7   0.045       0  4988.7    0.07       0  5345.5    0.07       0
  5376.5   0.045       0  5858.8    0.07       0  6125.5   0.045       0
  6184.9    0.07       0  6691.6   0.035       0  6891.7    0.16       0
  7341.3    0.07       0  7356.4    0.16       0  7587.1    0.07       0
Bank Sta=4950.7,4988.7
Exp/Cntr=0.3,0.1

Type RM Length L Ch R = 1,18270,566,566,566
BEGIN DESCRIPTION:
UCFB HW Trib 04 21.0
END DESCRIPTION:
XS GIS Cut Line= 3
      1373630.01      6991113.02      1372805.00      6989888.00
      1369629.96      6989412.99
#Sta/Elev= 30
  3522.8 1953.42  3942.9 1953.73  4035.2 1956.42  4118.6 1951.74  4495.0 1938.37
  4566.4 1934.75  4589.8 1935.08  4602.4 1932.82  4674.7 1932.92  4954.5 1928.29
  4973.2 1927.42  4974.2 1926.92  5011.2 1927.42  5040.2 1929.66  5060.4 1927.84
  5141.3 1931.08  5157.0 1929.85  6168.1 1933.74  6367.5 1933.21  7020.7 1932.65
  7123.1 1931.37  7153.4 1931.69  7163.5 1933.72  7209.3 1932.84  7671.8 1933.53
  7841.2 1936.18  7989.3 1940.09  8028.8 1942.02  8140.9 1950.10  8210.1 1953.19
#Mann=16,-1,0
  3522.8    0.07       0  3942.9   0.035       0  4118.6   0.045       0
  4495.0   0.035       0  4674.7   0.045       0  4954.5    0.07       0
  4973.2    0.07       0  5011.2    0.07       0  5157.0   0.045       0
  6168.1   0.035       0  6367.5   0.045       0  7020.7   0.035       0
  7209.3    0.16       0  7841.2    0.07       0  7989.3    0.16       0
  8028.8    0.07       0
Bank Sta=4973.2,5011.2
Exp/Cntr=0.3,0.1