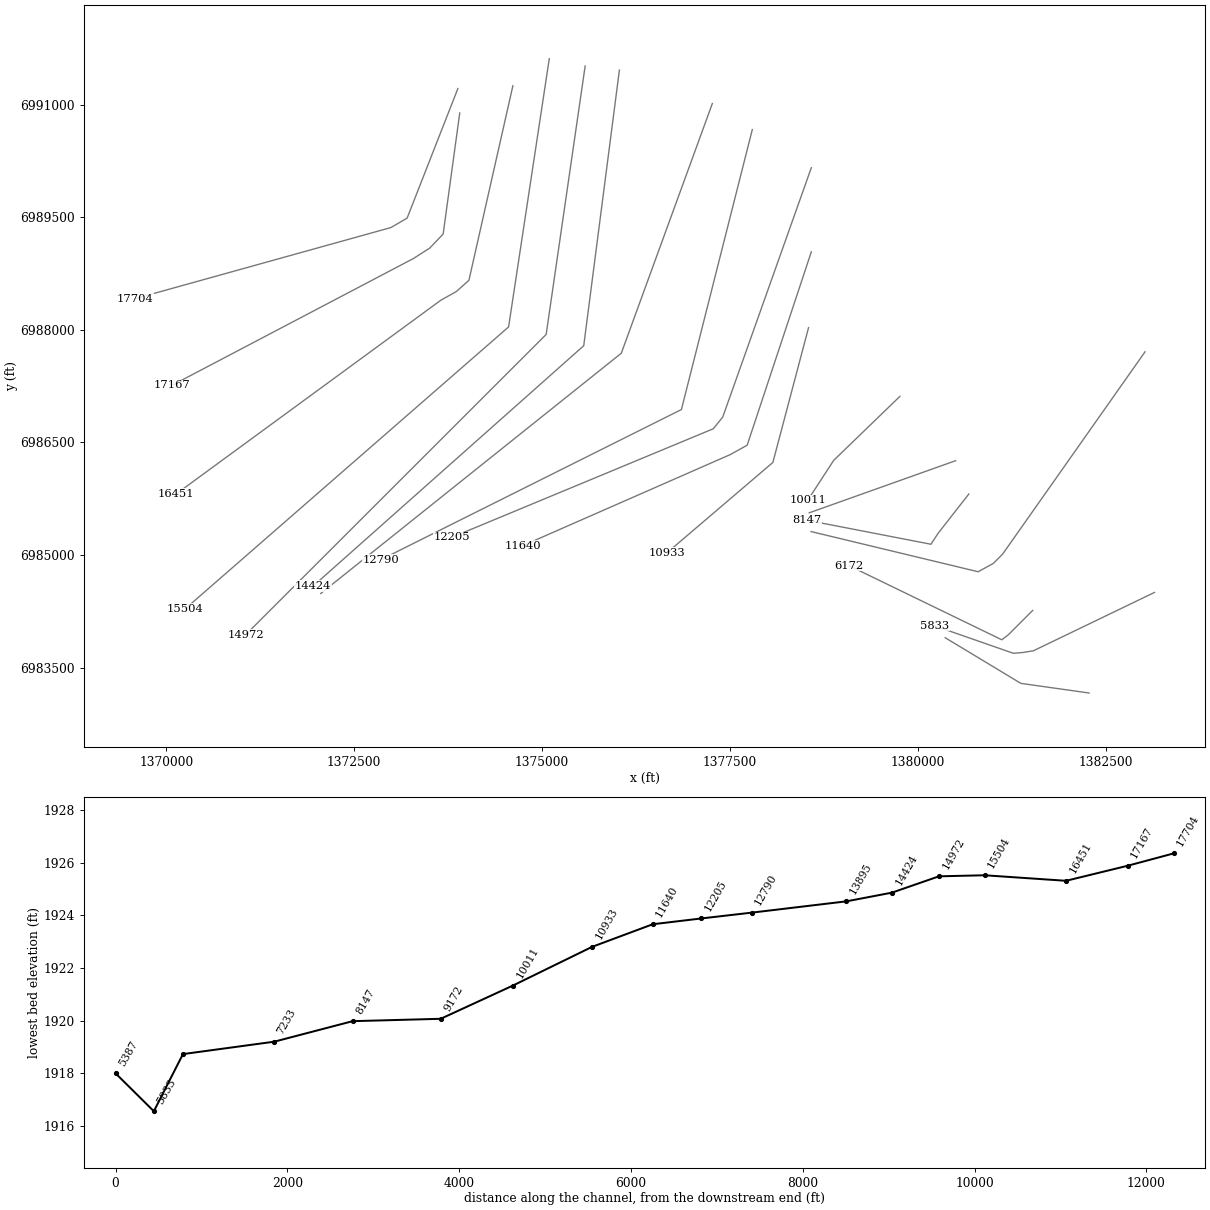
HEC-RAS study UCFB HW Trib 04.prj: UCFB HW Trib 04 Base Level Engineering

--- UCFB HW Trib 04.g01 (geometry) --- (continued)

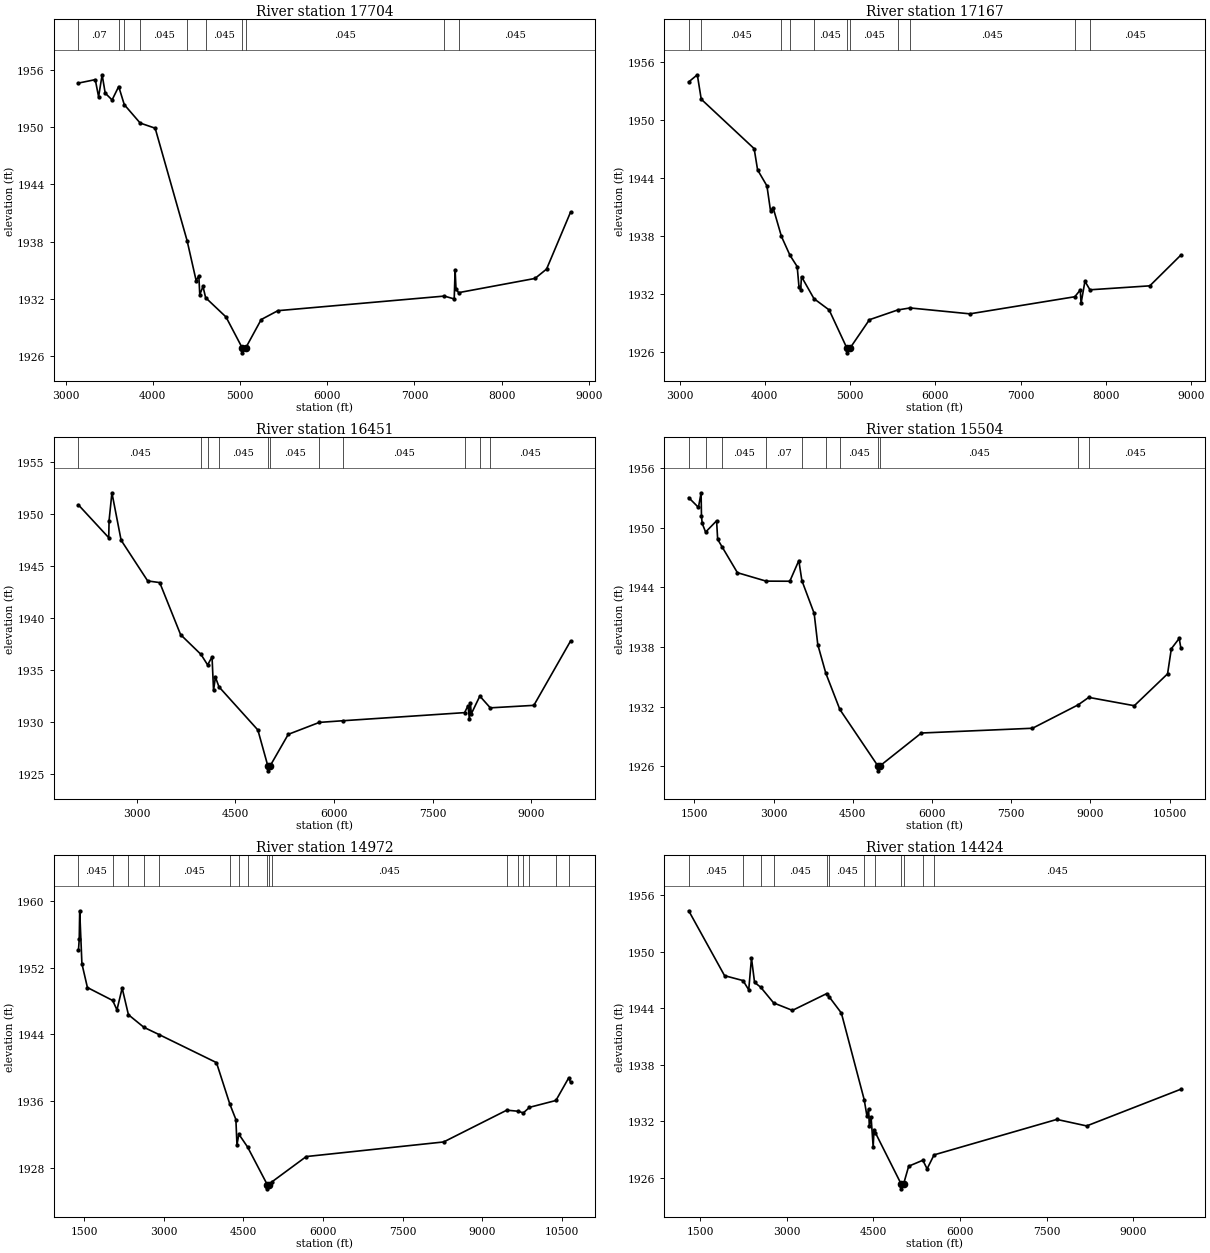
Type RM Length L Ch R = 1,17704,537,537,537
BEGIN DESCRIPTION:
UCFB HW Trib 04 20.0
END DESCRIPTION:
XS GIS Cut Line= 4
      1373879.99      6991212.98      1373205.00      6989488.00
      1372989.51      6989361.80      1369580.03      6988413.01
#Sta/Elev= 30
  3147.9 1954.63  3340.6 1954.99  3378.8 1953.19  3419.3 1955.50  3454.5 1953.58
  3533.3 1952.86  3609.2 1954.27  3673.1 1952.37  3855.3 1950.44  4027.2 1949.90
  4393.0 1938.12  4496.7 1933.93  4527.8 1934.42  4538.5 1932.45  4575.5 1933.31
  4605.6 1932.13  4839.2 1930.11  5026.3 1926.85  5027.3 1926.35  5064.3 1926.85
  5242.7 1929.84  5434.1 1930.77  7341.9 1932.30  7455.2 1932.00  7465.6 1935.07
  7476.0 1933.04  7506.0 1932.66  8381.5 1934.15  8514.0 1935.13  8789.0 1941.10
#Mann=10,-1,0
  3147.9    0.07       0  3609.2   0.045       0  3673.1   0.035       0
  3855.3   0.045       0  4393.0   0.035       0  4605.6   0.045       0
  5026.3   0.045       0  5064.3   0.045       0  7341.9   0.035       0
  7506.0   0.045       0
Bank Sta=5026.3,5064.3
Exp/Cntr=0.3,0.1

Type RM Length L Ch R = 1,17167,716,716,716
BEGIN DESCRIPTION:
UCFB HW Trib 04 19.0
END DESCRIPTION:
XS GIS Cut Line= 5
      1373904.99      6990887.95      1373683.96      6989275.00
      1373505.00      6989088.00      1373288.99      6988949.48
      1370080.03      6987263.02
#Sta/Elev= 30
  3107.6 1953.94  3208.5 1954.68  3254.4 1952.15  3874.7 1947.03  3915.0 1944.83
  4024.6 1943.17  4066.4 1940.60  4096.7 1940.92  4194.5 1937.94  4293.6 1936.00
  4379.3 1934.81  4400.5 1932.68  4419.7 1932.43  4429.8 1933.77  4576.0 1931.49
  4754.0 1930.32  4961.3 1926.38  4962.3 1925.88  4999.6 1926.38  5226.1 1929.31
  5557.6 1930.32  5702.4 1930.53  6403.2 1929.92  7633.5 1931.69  7697.7 1932.39
  7707.0 1931.00  7752.2 1933.29  7811.3 1932.41  8512.8 1932.82  8876.2 1936.00
#Mann=11,-1,0
  3107.6    0.07       0  3254.4   0.045       0  4194.5    0.07       0
  4293.6   0.035       0  4576.0   0.045       0  4961.3   0.045       0
  4999.6   0.045       0  5557.6   0.035       0  5702.4   0.045       0
  7633.5   0.035       0  7811.3   0.045       0
Bank Sta=4961.3,4999.6
Exp/Cntr=0.3,0.1

Type RM Length L Ch R = 1,16451,947,947,947
BEGIN DESCRIPTION:
UCFB HW Trib 04 18.5
END DESCRIPTION:
XS GIS Cut Line= 5
      1374611.99      6991249.66      1374026.84      6988658.68
      1373858.79      6988509.08      1373653.57      6988393.92
      1370130.03      6985813.02
#Sta/Elev= 30
  2115.1 1950.89  2575.6 1947.74  2580.7 1949.37  2623.9 1952.06  2763.7 1947.50
  3167.9 1943.58  3351.0 1943.42  3668.7 1938.41  3978.5 1936.51  4079.5 1935.50
  4146.7 1936.27  4169.6 1933.05  4197.9 1934.33  4252.2 1933.39  4843.7 1929.24
  4994.1 1925.81  4995.1 1925.31  5032.5 1925.81  5305.7 1928.82  5778.1 1929.97
  6136.7 1930.13  7987.9 1930.91  8040.0 1931.58  8060.8 1930.25  8075.5 1931.81
  8090.1 1930.80  8219.4 1932.50  8378.6 1931.37  9041.2 1931.61  9599.3 1937.80
#Mann=11,-1,0
  2115.1   0.045       0  3978.5    0.07       0  4079.5   0.035       0
  4252.2   0.045       0  4994.1   0.045       0  5032.5   0.045       0
  5778.1   0.035       0  6136.7   0.045       0  7987.9   0.035       0
  8219.4    0.07       0  8378.6   0.045       0
Bank Sta=4994.1,5032.5
Exp/Cntr=0.3,0.1

Type RM Length L Ch R = 1,15504,532,532,532
BEGIN DESCRIPTION:
UCFB HW Trib 04 18.0
END DESCRIPTION:
XS GIS Cut Line= 3
      1375096.41      6991610.10      1374555.00      6988038.00
      1370253.62      6984285.89
#Sta/Elev= 30
  1391.4 1953.04  1575.6 1952.06  1626.1 1953.53  1632.8 1951.22  1646.4 1950.45
  1711.5 1949.57  1919.5 1950.71  1939.7 1948.84  2024.9 1948.07  2313.9 1945.48
  2857.6 1944.63  3306.4 1944.62  3477.0 1946.70  3535.1 1944.68  3767.5 1941.38
  3836.3 1938.23  3987.8 1935.36  4254.4 1931.70  4974.1 1926.02  4975.1 1925.52
  5014.2 1926.02  5798.4 1929.33  7903.0 1929.81  8768.7 1932.17  8968.6 1932.92
  9831.1 1932.08 10461.4 1935.29 10532.6 1937.82 10681.7 1938.86 10712.2 1937.92
#Mann=11,-1,0
  1391.4   0.045       0  1711.5   0.035       0  2024.9   0.045       0
  2857.6    0.07       0  3535.1   0.045       0  3987.8   0.035       0
  4254.4   0.045       0  4974.1   0.045       0  5014.2   0.045       0
  8768.7   0.035       0  8968.6   0.045       0
Bank Sta=4974.1,5014.2
Exp/Cntr=0.3,0.1

Type RM Length L Ch R = 1,14972,548,548,548
BEGIN DESCRIPTION:
UCFB HW Trib 04 17.0
END DESCRIPTION:
XS GIS Cut Line= 3
      1375573.85      6991512.53      1375055.00      6987938.00
      1371055.03      6983938.03
#Sta/Elev= 30
  1392.4 1954.08  1407.1 1955.41  1415.7 1958.81  1457.6 1952.46  1561.1 1949.61
  2036.6 1948.06  2117.4 1946.93  2215.5 1949.54  2333.4 1946.35  2625.2 1944.84
  2907.9 1943.98  3991.9 1940.61  4243.9 1935.63  4357.7 1933.79  4377.9 1930.75
  4413.5 1932.03  4577.1 1930.50  4949.0 1925.98  4950.0 1925.48  4989.5 1925.98
  5028.8 1926.28  5683.2 1929.35  8271.2 1931.10  9460.1 1934.91  9674.6 1934.78
  9771.7 1934.58  9887.4 1935.25 10385.1 1936.07 10628.0 1938.80 10661.2 1938.24
#Mann=17,-1,0
  1392.4   0.045       0  2036.6   0.035       0  2333.4   0.045       0
  2625.2    0.07       0  2907.9   0.045       0  4243.9   0.035       0
  4413.5   0.045       0  4577.1   0.035       0  4949.0   0.035       0
  4989.5   0.035       0  5028.8   0.045       0  9460.1   0.035       0
  9674.6   0.045       0  9771.7    0.07       0  9887.4   0.045       0
 10385.1   0.035       0 10628.0    0.07       0
Bank Sta=4949,4989.5
Exp/Cntr=0.3,0.1

Type RM Length L Ch R = 1,14424,529,529,529
BEGIN DESCRIPTION:
UCFB HW Trib 04 16.0
END DESCRIPTION:
XS GIS Cut Line= 3
      1376029.58      6991458.28      1375555.00      6987788.00
      1371954.98      6984587.98
#Sta/Elev= 30
  1303.5 1954.34  1924.0 1947.46  2243.3 1946.94  2342.4 1945.96  2389.8 1949.32
  2443.2 1946.75  2548.5 1946.24  2773.6 1944.57  3098.7 1943.78  3692.4 1945.56
  3731.9 1945.24  3945.6 1943.50  4341.4 1934.30  4389.3 1932.54  4417.0 1933.34
  4429.6 1931.49  4459.8 1932.50  4496.3 1929.30  4510.3 1931.05  4532.7 1930.83
  4981.5 1925.36  4982.5 1924.86  5022.1 1925.36  5110.9 1927.26  5355.8 1927.89
  5429.6 1926.98  5550.2 1928.46  7674.8 1932.22  8191.6 1931.53  9821.0 1935.42
#Mann=12,-1,0
  1303.5   0.045       0  2243.3   0.035       0  2548.5    0.07       0
  2773.6   0.045       0  3692.4   0.035       0  3731.9   0.045       0
  4341.4   0.035       0  4532.7   0.045       0  4981.5   0.045       0
  5022.1   0.045       0  5355.8   0.035       0  5550.2   0.045       0
Bank Sta=4981.5,5022.1
Exp/Cntr=0.3,0.1

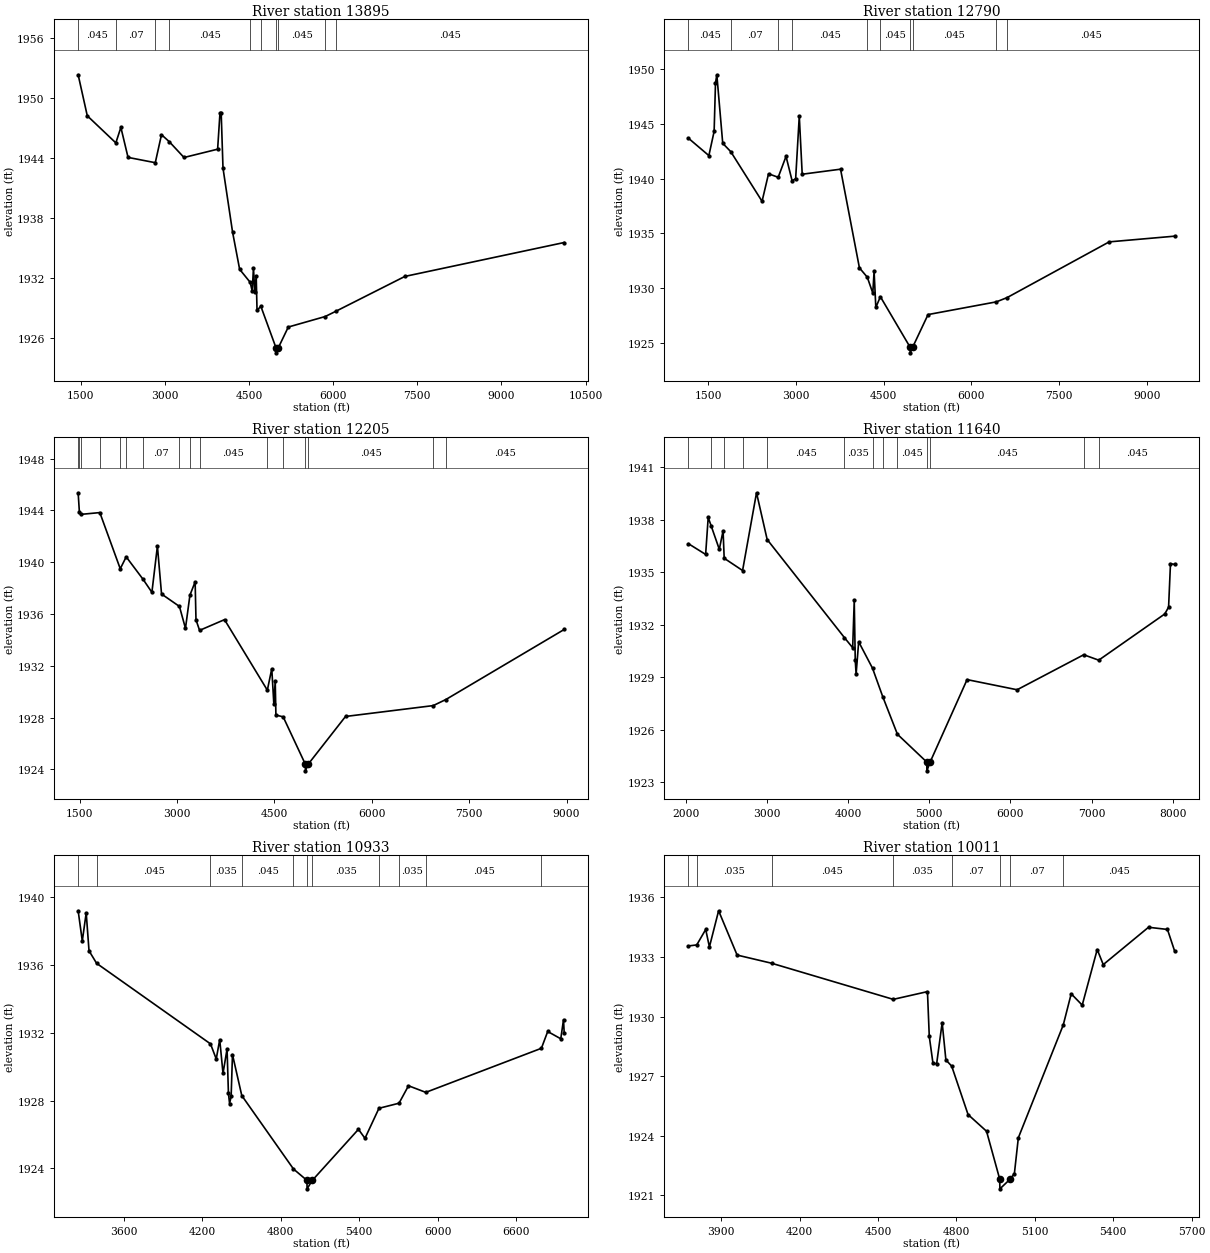
Type RM Length L Ch R = 1,13895,1105,1105,1105
BEGIN DESCRIPTION:
UCFB HW Trib 04 15.0
END DESCRIPTION:
XS GIS Cut Line= 3
      1377266.54      6991013.32      1376055.00      6987688.00
      1372054.96      6984487.97
#Sta/Elev= 30
  1456.3 1952.33  1618.9 1948.23  2127.9 1945.52  2217.6 1947.07  2345.3 1944.07
  2830.9 1943.54  2941.3 1946.34  3080.2 1945.64  3342.7 1944.06  3941.8 1944.89
  3983.3 1948.47  4005.6 1948.48  4037.6 1943.00  4207.9 1936.61  4334.2 1932.88
  4522.2 1931.58  4559.1 1930.68  4580.4 1933.04  4604.0 1930.60  4629.3 1932.22
  4644.2 1928.77  4711.8 1929.19  4982.4 1925.03  4983.4 1924.53  5023.0 1925.03
  5201.2 1927.11  5858.8 1928.16  6046.9 1928.68  7279.0 1932.17 10118.0 1935.56
#Mann=10,-1,0
  1456.3   0.045       0  2127.9    0.07       0  2830.9   0.035       0
  3080.2   0.045       0  4522.2   0.035       0  4711.8   0.045       0
  4982.4   0.045       0  5023.0   0.045       0  5858.8   0.035       0
  6046.9   0.045       0
Bank Sta=4982.4,5023
Exp/Cntr=0.3,0.1

Type RM Length L Ch R = 1,12790,585,585,585
BEGIN DESCRIPTION:
UCFB HW Trib 04 14.0
END DESCRIPTION:
XS GIS Cut Line= 3
      1377798.25      6990666.18      1376855.00      6986938.00
      1372854.99      6984938.00
#Sta/Elev= 30
  1158.5 1943.67  1507.3 1942.09  1597.4 1944.30  1620.8 1948.71  1643.6 1949.46
  1744.6 1943.21  1881.8 1942.45  2417.7 1937.92  2528.5 1940.43  2693.8 1940.11
  2827.9 1942.02  2932.4 1939.78  2992.7 1939.99  3054.6 1945.69  3104.7 1940.39
  3760.9 1940.85  4083.9 1931.85  4218.3 1931.00  4313.0 1929.55  4335.1 1931.53
  4364.6 1928.24  4442.4 1929.22  4952.8 1924.60  4953.8 1924.10  4993.7 1924.60
  5258.5 1927.59  6427.8 1928.75  6612.0 1929.14  8358.3 1934.22  9476.3 1934.74
#Mann=10,-1,0
  1158.5   0.045       0  1881.8    0.07       0  2693.8   0.035       0
  2932.4   0.045       0  4218.3   0.035       0  4442.4   0.045       0
  4952.8   0.045       0  4993.7   0.045       0  6427.8   0.035       0
  6612.0   0.045       0
Bank Sta=4952.8,4993.7
Exp/Cntr=0.3,0.1

Type RM Length L Ch R = 1,12205,565,565,565
BEGIN DESCRIPTION:
UCFB HW Trib 04 13.0
END DESCRIPTION:
XS GIS Cut Line= 4
      1378583.83      6990158.34      1377405.00      6986838.00
      1377279.44      6986682.11      1373804.96      6985237.99
#Sta/Elev= 30
  1476.9 1945.36  1496.0 1943.85  1515.0 1943.69  1810.6 1943.83  2125.3 1939.49
  2216.9 1940.41  2477.5 1938.67  2612.7 1937.67  2697.6 1941.24  2761.3 1937.54
  3036.9 1936.58  3129.8 1934.89  3198.5 1937.45  3278.8 1938.48  3291.8 1935.55
  3347.1 1934.73  3731.1 1935.56  4390.9 1930.11  4459.1 1931.77  4490.9 1929.06
  4512.3 1930.82  4522.8 1928.19  4634.8 1928.05  4977.2 1924.38  4978.2 1923.88
  5018.1 1924.38  5595.1 1928.08  6946.2 1928.92  7141.2 1929.39  8963.1 1934.80
#Mann=16,-1,0
  1476.9    0.07       0  1496.0   0.035       0  1515.0   0.045       0
  1810.6    0.07       0  2125.3   0.035       0  2216.9   0.045       0
  2477.5    0.07       0  3036.9   0.035       0  3198.5   0.063       0
  3347.1   0.045       0  4390.9   0.035       0  4634.8   0.045       0
  4977.2   0.045       0  5018.1   0.045       0  6946.2   0.035       0
  7141.2   0.045       0
Bank Sta=4977.2,5018.1
Exp/Cntr=0.3,0.1

Type RM Length L Ch R = 1,11640,707,707,707
BEGIN DESCRIPTION:
UCFB HW Trib 04 12.0
END DESCRIPTION:
XS GIS Cut Line= 4
      1378583.83      6989038.54      1377730.00      6986463.00
      1377505.00      6986338.00      1374741.67      6985124.29
#Sta/Elev= 30
  2033.1 1936.63  2244.4 1936.02  2276.0 1938.13  2311.9 1937.66  2412.9 1936.31
  2459.4 1937.37  2473.0 1935.80  2699.7 1935.10  2871.4 1939.54  3002.6 1936.87
  3954.3 1931.27  4056.4 1930.69  4075.7 1933.39  4088.0 1929.98  4098.6 1929.18
  4130.2 1931.03  4300.9 1929.52  4427.2 1927.89  4607.6 1925.75  4969.6 1924.16
  4970.6 1923.66  5010.6 1924.16  5466.0 1928.87  6082.6 1928.29  6903.3 1930.29
  7088.2 1929.98  7902.3 1932.62  7949.0 1933.01  7972.3 1935.49  8022.0 1935.45
#Mann=13,-1,0
  2033.1    0.07       0  2311.9   0.035       0  2473.0    0.07       0
  2699.7   0.035       0  3002.6   0.045       0  3954.3   0.035       0
  4300.9   0.045       0  4427.2   0.035       0  4607.6   0.045       0
  4969.6   0.045       0  5010.6   0.045       0  6903.3   0.035       0
  7088.2   0.045       0
Bank Sta=4969.6,5010.6
Exp/Cntr=0.3,0.1

Type RM Length L Ch R = 1,10933,922,922,922
BEGIN DESCRIPTION:
UCFB HW Trib 04 11.3
END DESCRIPTION:
XS GIS Cut Line= 3
      1378546.84      6988028.20      1378072.08      6986233.37
      1376659.20      6985027.00
#Sta/Elev= 30
  3251.4 1939.20  3283.0 1937.42  3312.9 1939.08  3334.4 1936.84  3392.5 1936.10
  4262.8 1931.35  4306.7 1930.46  4333.3 1931.60  4358.4 1929.61  4389.4 1931.05
  4399.8 1928.44  4408.6 1927.83  4420.5 1928.25  4430.8 1930.72  4501.9 1928.30
  4896.9 1923.97  4999.9 1923.30  5000.9 1922.80  5040.9 1923.30  5393.4 1926.31
  5443.4 1925.78  5550.2 1927.55  5703.5 1927.85  5776.0 1928.88  5908.1 1928.49
  6791.7 1931.09  6839.9 1932.08  6939.8 1931.65  6960.7 1932.78  6965.8 1932.00
#Mann=11,-1,0
  3251.4   0.035       0  3392.5   0.045       0  4262.8   0.035       0
  4501.9   0.045       0  4896.9   0.035       0  4999.9   0.035       0
  5040.9   0.035       0  5550.2   0.045       0  5703.5   0.035       0
  5908.1   0.045       0  6791.7   0.035       0
Bank Sta=4999.9,5040.9
Exp/Cntr=0.3,0.1

Type RM Length L Ch R = 1,10011,839,839,839
BEGIN DESCRIPTION:
UCFB HW Trib 04 11.2
END DESCRIPTION:
XS GIS Cut Line= 3
      1379762.66      6987113.40      1378881.64      6986261.27
      1378535.94      6985729.33
#Sta/Elev= 30
  3774.3 1933.56  3805.9 1933.61  3840.2 1934.39  3854.4 1933.51  3889.6 1935.33
  3960.4 1933.10  4092.1 1932.69  4558.1 1930.87  4688.9 1931.26  4695.8 1929.01
  4710.0 1927.65  4724.1 1927.63  4745.2 1929.70  4759.4 1927.82  4781.6 1927.51
  4844.3 1925.07  4915.0 1924.23  4965.2 1921.83  4966.2 1921.33  5006.3 1921.83
  5021.6 1922.10  5036.7 1923.90  5208.6 1929.58  5239.0 1931.15  5281.2 1930.58
  5338.6 1933.38  5361.7 1932.62  5534.9 1934.50  5607.4 1934.39  5634.4 1933.32
#Mann=8,-1,0
  3774.3    0.07       0  3805.9   0.035       0  4092.1   0.045       0
  4558.1   0.035       0  4781.6    0.07       0  4965.2    0.07       0
  5006.3    0.07       0  5208.6   0.045       0
Bank Sta=4965.2,5006.3
Exp/Cntr=0.3,0.1

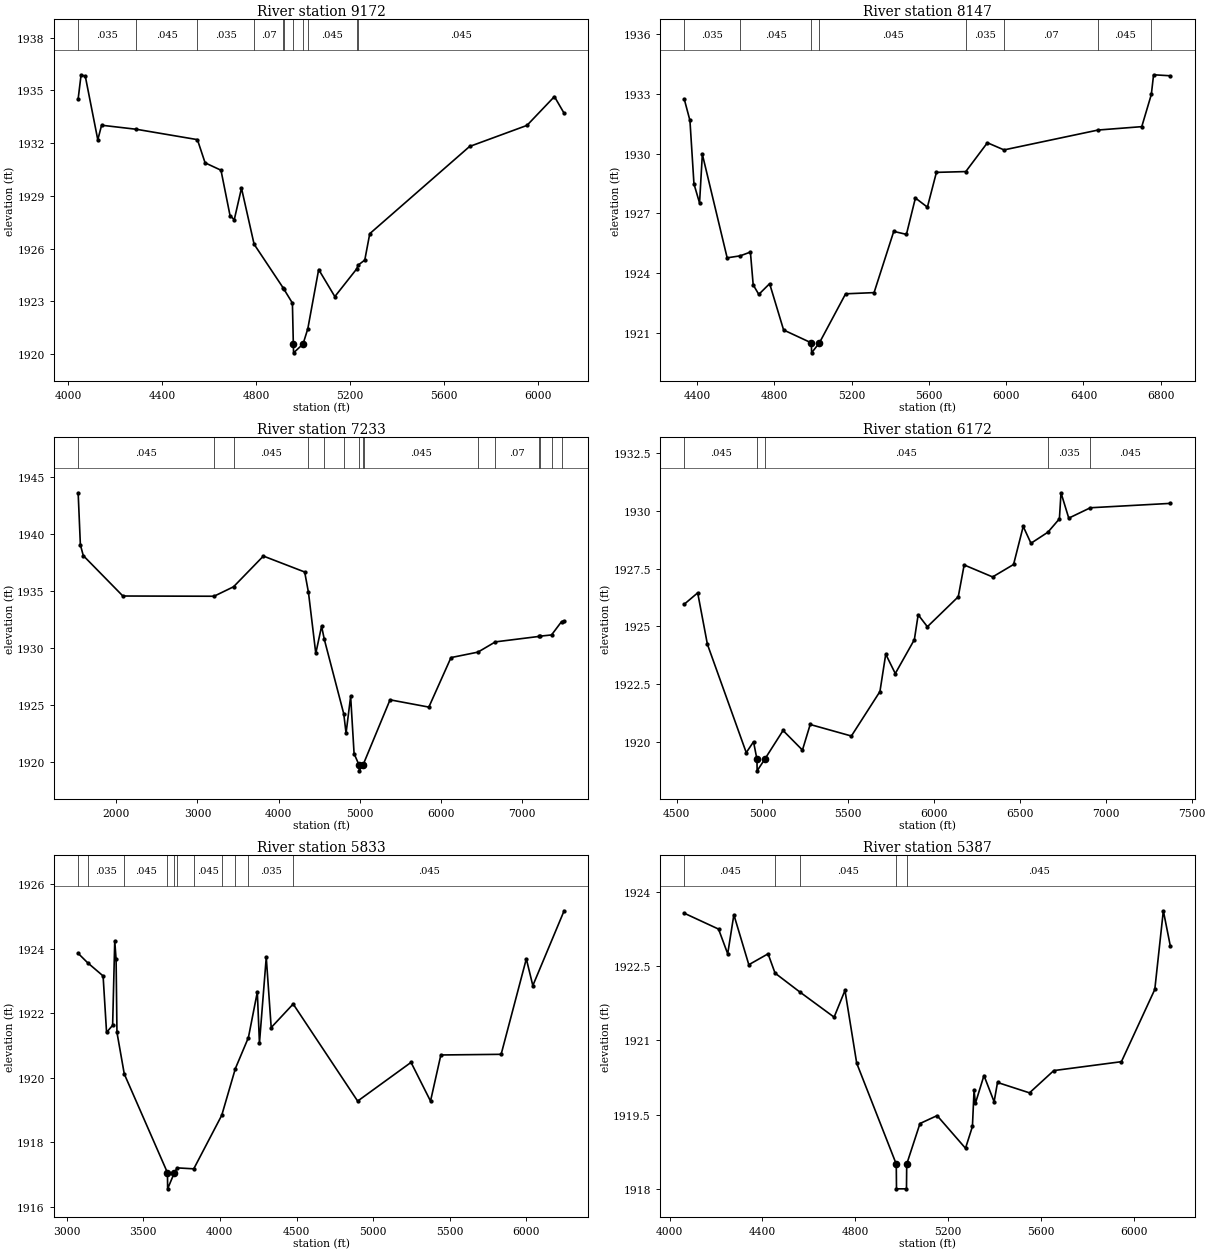
Type RM Length L Ch R = 1,9172,1025,1025,1025
BEGIN DESCRIPTION:
UCFB HW Trib 04 11.1
END DESCRIPTION:
XS GIS Cut Line= 2
      1380503.73      6986256.53      1378556.08      6985562.54
#Sta/Elev= 30
  4042.3 1934.52  4054.8 1935.89  4072.8 1935.80  4125.9 1932.19  4142.0 1933.02
  4289.7 1932.79  4549.7 1932.20  4582.4 1930.88  4650.0 1930.46  4688.5 1927.88
  4706.4 1927.64  4737.2 1929.44  4790.9 1926.25  4915.3 1923.75  4917.5 1923.70
  4953.9 1922.90  4957.8 1920.57  4958.8 1920.07  4999.0 1920.57  5019.4 1921.44
  5065.6 1924.81  5134.4 1923.27  5227.6 1924.85  5233.6 1925.06  5261.8 1925.35
  5283.0 1926.85  5707.6 1931.81  5951.8 1933.01  6068.6 1934.65  6109.9 1933.70
#Mann=11,-1,0
  4042.3   0.035       0  4289.7   0.045       0  4549.7   0.035       0
  4790.9    0.07       0  4915.3   0.045       0  4917.5    0.07       0
  4957.8    0.07       0  4999.0    0.07       0  5019.4   0.045       0
  5227.6    0.07       0  5233.6   0.045       0
Bank Sta=4957.8,4999
Exp/Cntr=0.3,0.1

Type RM Length L Ch R = 1,8147,914,914,914
BEGIN DESCRIPTION:
UCFB HW Trib 04 11.0
END DESCRIPTION:
XS GIS Cut Line= 4
      1380680.01      6985813.01      1380270.22      6985288.52
      1380176.14      6985143.92      1378529.99      6985463.00
#Sta/Elev= 30
  4334.4 1932.73  4363.4 1931.67  4384.2 1928.48  4413.1 1927.52  4427.6 1929.97
  4556.0 1924.76  4623.4 1924.86  4676.3 1925.05  4690.7 1923.40  4719.7 1922.92
  4775.8 1923.46  4848.1 1921.13  4991.9 1920.48  4992.9 1919.98  5033.2 1920.48
  5169.0 1922.95  5316.3 1923.01  5418.1 1926.09  5483.7 1925.94  5530.2 1927.77
  5592.2 1927.31  5638.9 1929.06  5791.0 1929.10  5902.7 1930.55  5988.8 1930.19
  6475.5 1931.19  6701.6 1931.36  6751.1 1932.98  6762.7 1933.97  6849.3 1933.92
#Mann=8,-1,0
  4334.4   0.035       0  4623.4   0.045       0  4991.9   0.045       0
  5033.2   0.045       0  5791.0   0.035       0  5988.8    0.07       0
  6475.5   0.045       0  6751.1   0.035       0
Bank Sta=4991.9,5033.2
Exp/Cntr=0.3,0.1

Type RM Length L Ch R = 1,7233,1061,1061,1061
BEGIN DESCRIPTION:
UCFB HW Trib 04 10.0
END DESCRIPTION:
XS GIS Cut Line= 5
      1383024.91      6987706.62      1381130.00      6985013.00
      1381005.00      6984888.00      1380803.75      6984777.77
      1378579.96      6985313.01
#Sta/Elev= 30
  1530.1 1943.63  1557.5 1939.06  1593.2 1938.11  2081.1 1934.56  3204.1 1934.54
  3444.2 1935.37  3812.0 1938.07  4320.8 1936.67  4367.6 1934.87  4457.6 1929.52
  4529.0 1931.91  4562.7 1930.75  4802.5 1924.20  4830.5 1922.51  4887.1 1925.74
  4929.5 1920.71  4991.5 1919.70  4992.5 1919.20  5036.5 1919.70  5045.8 1919.82
  5372.4 1925.44  5850.5 1924.80  6123.3 1929.15  6455.4 1929.63  6669.9 1930.53
  7208.4 1931.01  7218.4 1931.03  7362.1 1931.14  7485.3 1932.31  7517.0 1932.36
#Mann=15,-1,0
  1530.1   0.045       0  3204.1   0.035       0  3444.2   0.045       0
  4367.6   0.035       0  4562.7    0.07       0  4802.5   0.035       0
  4991.5   0.035       0  5036.5   0.035       0  5045.8   0.045       0
  6455.4   0.035       0  6669.9    0.07       0  7208.4   0.045       0
  7218.4    0.07       0  7362.1   0.045       0  7485.3   0.035       0
Bank Sta=4991.5,5036.5
Exp/Cntr=0.3,0.1

Type RM Length L Ch R = 1,6172,339,339,339
BEGIN DESCRIPTION:
UCFB HW Trib 04 9.0
END DESCRIPTION:
XS GIS Cut Line= 4
      1381529.99      6984262.99      1381205.00      6983938.00
      1381118.85      6983871.52      1379083.98      6984859.37
#Sta/Elev= 30
  4545.2 1925.96  4623.0 1926.45  4679.5 1924.22  4905.8 1919.52  4948.2 1919.99
  4968.2 1919.23  4969.2 1918.73  5013.2 1919.23  5120.2 1920.48  5233.1 1919.63
  5278.2 1920.74  5518.1 1920.24  5684.4 1922.17  5718.2 1923.79  5773.8 1922.95
  5884.9 1924.42  5907.1 1925.50  5960.7 1924.98  6140.6 1926.28  6174.9 1927.66
  6340.7 1927.14  6462.7 1927.68  6518.9 1929.33  6564.1 1928.60  6662.7 1929.08
  6729.7 1929.66  6739.0 1930.79  6784.2 1929.69  6910.0 1930.14  7375.6 1930.33
#Mann=5,-1,0
  4545.2   0.045       0  4968.2   0.045       0  5013.2   0.045       0
  6662.7   0.035       0  6910.0   0.045       0
Bank Sta=4968.2,5013.2
Exp/Cntr=0.3,0.1

Type RM Length L Ch R = 1,5833,446,446,446
BEGIN DESCRIPTION:
UCFB HW Trib 04 8.8
END DESCRIPTION:
XS GIS Cut Line= 5
      1383150.03      6984501.96      1381540.73      6983725.69
      1381405.15      6983703.06      1381272.50      6983691.84
      1380222.26      6984058.41
#Sta/Elev= 30
  3075.8 1923.86  3137.4 1923.57  3238.5 1923.16  3261.1 1921.41  3300.7 1921.63
  3314.5 1924.25  3323.3 1923.67  3328.9 1921.41  3376.7 1920.12  3658.4 1917.06
  3659.4 1916.56  3703.4 1917.06  3721.5 1917.21  3829.8 1917.18  4012.4 1918.84
  4101.3 1920.29  4186.3 1921.25  4244.4 1922.66  4258.3 1921.08  4302.7 1923.74
  4334.9 1921.56  4478.3 1922.29  4898.8 1919.28  5247.0 1920.48  5374.1 1919.28
  5441.5 1920.71  5834.7 1920.73  5999.0 1923.69  6041.4 1922.86  6245.5 1925.18
#Mann=11,-1,0
  3075.8   0.045       0  3137.4   0.035       0  3376.7   0.045       0
  3658.4   0.045       0  3703.4   0.045       0  3721.5    0.07       0
  3829.8   0.045       0  4012.4   0.035       0  4101.3   0.045       0
  4186.3   0.035       0  4478.3   0.045       0
Bank Sta=3658.4,3703.4
Exp/Cntr=0.3,0.1

Type RM Length L Ch R = 1,5387,1041,1041,1041
BEGIN DESCRIPTION:
UCFB HW Trib 04 8.6
END DESCRIPTION:
XS GIS Cut Line= 3
      1382280.01      6983163.00      1381372.63      6983291.13
      1380365.38      6983899.11
#Sta/Elev= 30
  4063.8 1923.57  4211.1 1923.25  4250.6 1922.75  4277.1 1923.54  4341.5 1922.53
  4424.4 1922.75  4454.5 1922.36  4560.8 1921.98  4708.8 1921.47  4755.6 1922.01
  4806.1 1920.54  4976.5 1918.50  4977.5 1918.00  5020.5 1918.00  5021.5 1918.50
  5078.6 1919.32  5152.4 1919.48  5274.7 1918.82  5304.5 1919.26  5311.5 1919.99
  5317.4 1919.73  5354.2 1920.29  5397.9 1919.76  5412.5 1920.15  5550.3 1919.94
  5654.9 1920.39  5946.2 1920.57  6089.9 1922.03  6126.7 1923.62  6156.7 1922.91
#Mann=5,-1,0
  4063.8   0.045       0  4454.5   0.035       0  4560.8   0.045       0
  4976.5   0.045       0  5021.5   0.045       0
Bank Sta=4976.5,5021.5
Exp/Cntr=0.3,0.1