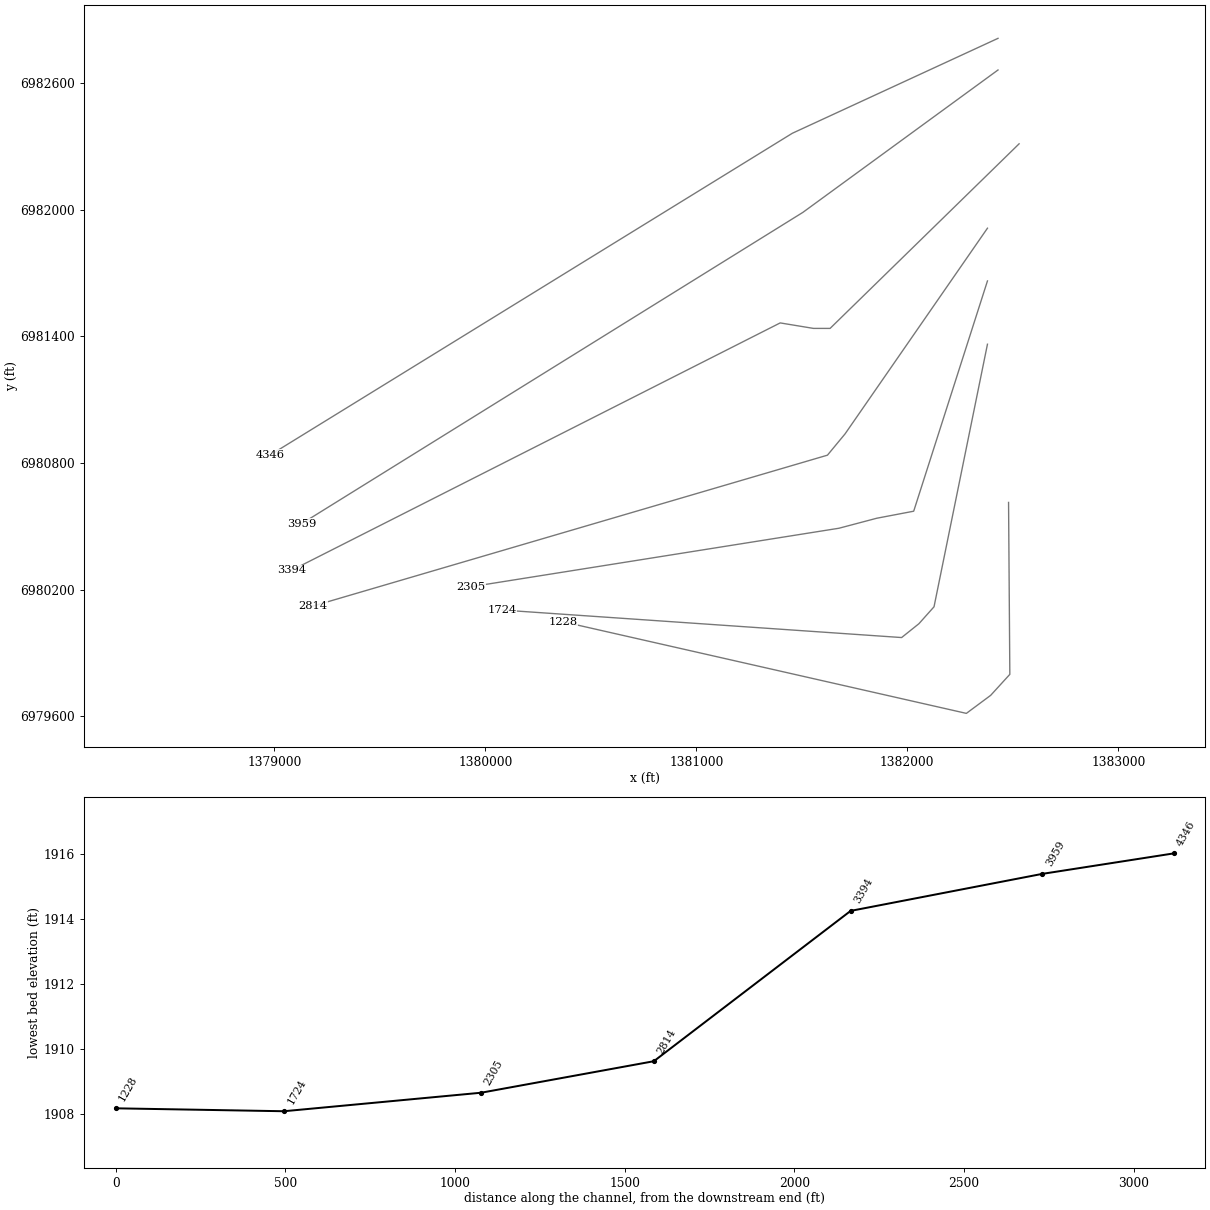
HEC-RAS study UCFB HW Trib 04.prj: UCFB HW Trib 04 Base Level Engineering

--- UCFB HW Trib 04.g01 (geometry) --- (continued)

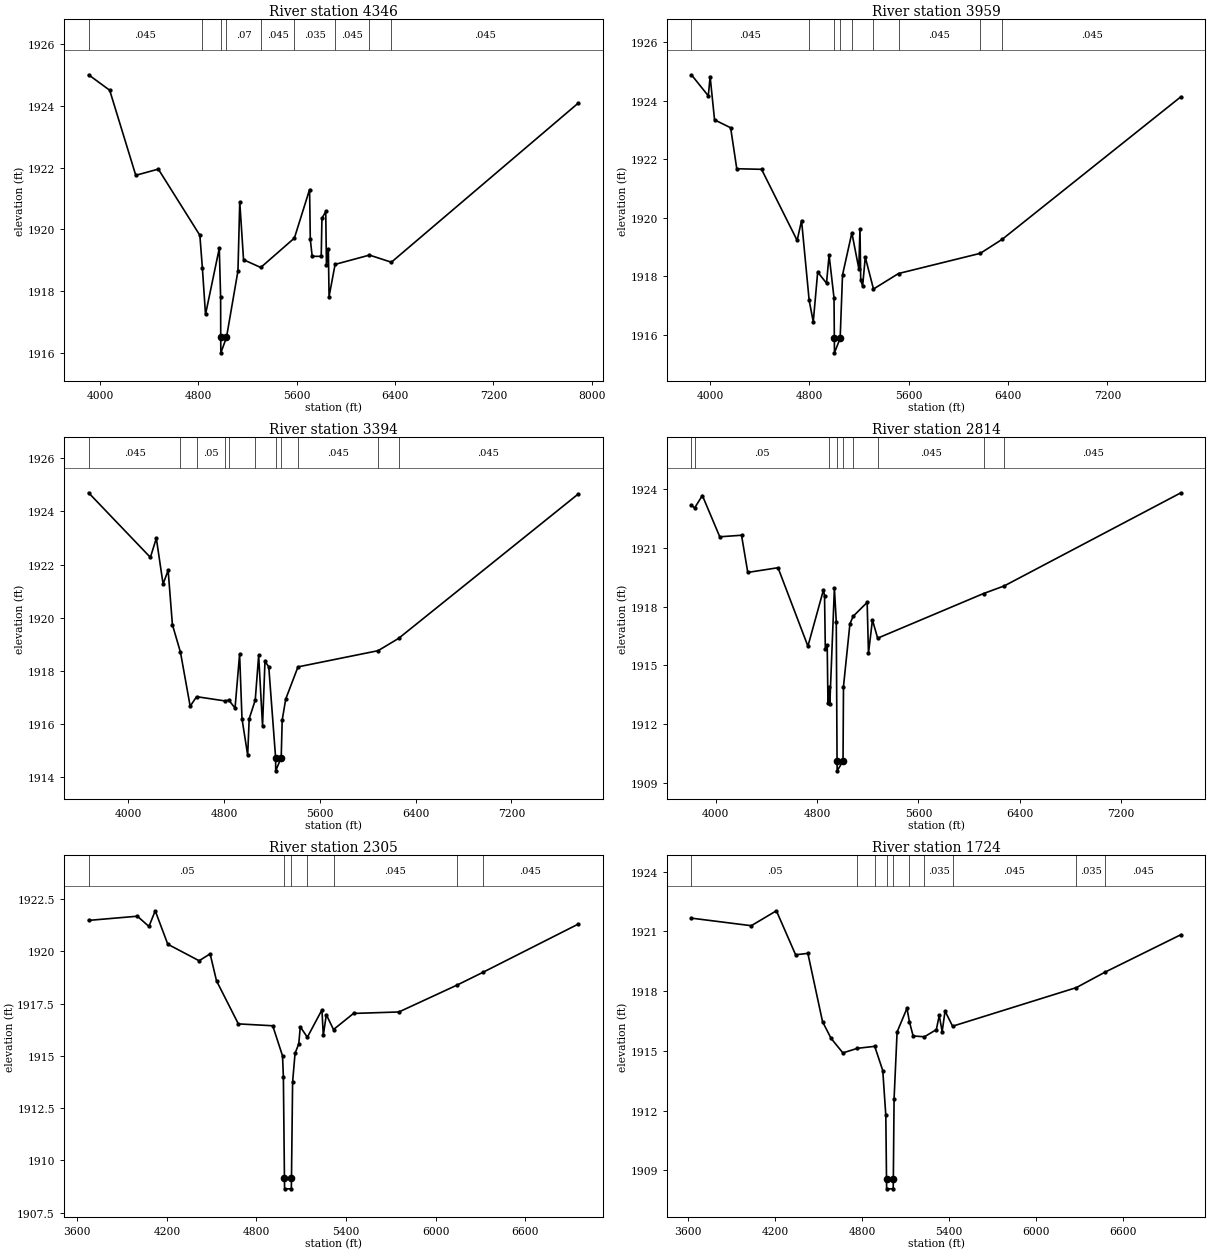
Type RM Length L Ch R = 1,4346,387,387,387
BEGIN DESCRIPTION:
UCFB HW Trib 04 8.0
END DESCRIPTION:
XS GIS Cut Line= 3
      1382430.03      6982813.02      1381455.00      6982363.00
      1378979.98      6980837.99
#Sta/Elev= 30
  3907.7 1925.00  4079.4 1924.50  4291.4 1921.75  4474.9 1921.95  4812.7 1919.81
  4833.4 1918.74  4858.6 1917.25  4970.6 1919.39  4981.6 1917.80  4982.3 1916.51
  4983.3 1916.01  5029.2 1916.51  5122.5 1918.66  5137.1 1920.89  5167.9 1919.02
  5307.9 1918.77  5581.4 1919.72  5705.0 1921.29  5710.8 1919.68  5726.2 1919.13
  5799.6 1919.13  5805.5 1920.36  5836.3 1920.58  5842.2 1918.84  5857.6 1919.36
  5863.4 1917.83  5912.5 1918.87  6192.0 1919.17  6370.1 1918.94  7888.7 1924.08
#Mann=9,-1,0
  3907.7   0.045       0  4833.4    0.07       0  4982.3    0.07       0
  5029.2    0.07       0  5307.9   0.045       0  5581.4   0.035       0
  5912.5   0.045       0  6192.0   0.035       0  6370.1   0.045       0
Bank Sta=4982.3,5029.2
Exp/Cntr=0.3,0.1

Type RM Length L Ch R = 1,3959,565,565,565
BEGIN DESCRIPTION:
UCFB HW Trib 04 7.0
END DESCRIPTION:
XS GIS Cut Line= 3
      1382430.01      6982663.01      1381505.00      6981988.00
      1379129.97      6980512.98
#Sta/Elev= 30
  3850.7 1924.88  3986.7 1924.16  4001.3 1924.82  4036.9 1923.34  4166.4 1923.07
  4215.9 1921.67  4415.4 1921.65  4701.9 1919.22  4737.4 1919.90  4798.7 1917.17
  4831.7 1916.44  4867.2 1918.14  4938.3 1917.76  4959.1 1918.72  4998.8 1917.25
  5001.3 1915.88  5002.3 1915.38  5048.2 1915.88  5067.2 1918.04  5142.4 1919.48
  5198.3 1918.26  5207.7 1919.62  5213.7 1917.87  5229.0 1917.66  5250.3 1918.65
  5316.4 1917.56  5518.0 1918.09  6176.6 1918.78  6353.1 1919.26  7791.6 1924.13
#Mann=9,-1,0
  3850.7   0.045       0  4798.7    0.07       0  5001.3    0.07       0
  5048.2    0.07       0  5142.4   0.035       0  5316.4    0.07       0
  5518.0   0.045       0  6176.6   0.035       0  6353.1   0.045       0
Bank Sta=5001.3,5048.2
Exp/Cntr=0.3,0.1

Type RM Length L Ch R = 1,3394,580,580,580
BEGIN DESCRIPTION:
UCFB HW Trib 04 6.0
END DESCRIPTION:
XS GIS Cut Line= 5
      1382529.97      6982312.97      1381633.99      6981437.95
      1381555.00      6981438.00      1381397.45      6981463.99
      1379079.97      6980290.49
#Sta/Elev= 30
  3668.6 1924.70  4184.8 1922.27  4234.4 1922.99  4290.8 1921.27  4333.2 1921.78
  4368.7 1919.74  4436.1 1918.70  4517.1 1916.67  4570.8 1917.03  4807.2 1916.87
  4840.1 1916.90  4891.9 1916.60  4930.0 1918.63  4950.0 1916.20  4997.5 1914.83
  5010.1 1916.20  5060.6 1916.90  5089.1 1918.58  5121.6 1915.93  5141.9 1918.36
  5173.6 1918.15  5230.6 1914.74  5231.6 1914.24  5277.5 1914.74  5285.7 1916.15
  5315.2 1916.94  5417.5 1918.15  6086.9 1918.76  6257.2 1919.22  7757.3 1924.65
#Mann=11,-1,0
  3668.6   0.045       0  4436.1    0.07       0  4570.8    0.05       0
  4807.2    0.07       0  4840.1    0.05       0  5060.6   0.035       0
  5230.6    0.05       0  5277.5   0.035       0  5417.5   0.045       0
  6086.9   0.035       0  6257.2   0.045       0
Bank Sta=5230.6,5277.5
Exp/Cntr=0.3,0.1

Type RM Length L Ch R = 1,2814,509,509,509
BEGIN DESCRIPTION:
UCFB HW Trib 04 5.0
END DESCRIPTION:
XS GIS Cut Line= 4
      1382380.02      6981913.03      1381705.00      6980938.00
      1381621.46      6980837.02      1379179.99      6980120.80
#Sta/Elev= 30
  3809.6 1923.19  3834.3 1923.04  3896.1 1923.68  4033.3 1921.57  4204.9 1921.65
  4254.2 1919.75  4492.8 1919.99  4728.6 1915.98  4850.9 1918.85  4859.7 1918.57
  4865.8 1915.86  4880.6 1916.05  4886.7 1913.06  4896.4 1913.91  4901.6 1913.05
  4937.4 1918.95  4952.2 1917.23  4958.4 1910.11  4959.4 1909.61  5005.5 1910.11
  5009.1 1913.92  5060.0 1917.13  5085.9 1917.51  5195.8 1918.22  5206.2 1915.61
  5237.5 1917.32  5278.7 1916.39  6113.6 1918.67  6277.0 1919.06  7670.9 1923.82
#Mann=9,-1,0
  3809.6   0.045       0  3834.3    0.05       0  4896.4    0.07       0
  4958.4    0.07       0  5005.5    0.07       0  5085.9   0.035       0
  5278.7   0.045       0  6113.6   0.035       0  6277.0   0.045       0
Bank Sta=4958.4,5005.5
Exp/Cntr=0.3,0.1

Type RM Length L Ch R = 1,2305,581,581,581
BEGIN DESCRIPTION:
UCFB HW Trib 04 4.0
END DESCRIPTION:
XS GIS Cut Line= 5
      1382380.00      6981662.99      1382030.31      6980571.39
      1381855.00      6980538.00      1381676.14      6980490.66
      1379930.00      6980213.00
#Sta/Elev= 30
  3675.8 1921.48  4002.4 1921.68  4080.1 1921.19  4122.1 1921.94  4206.1 1920.34
  4416.1 1919.55  4489.6 1919.88  4532.4 1918.59  4678.6 1916.53  4908.9 1916.44
  4974.4 1915.00  4980.1 1914.01  4987.3 1909.14  4988.3 1908.64  5033.4 1908.64
  5034.4 1909.14  5041.9 1913.75  5058.3 1915.12  5083.3 1915.58  5093.3 1916.39
  5140.6 1915.89  5238.3 1917.20  5247.4 1915.98  5267.7 1916.97  5315.8 1916.26
  5449.9 1917.03  5753.7 1917.10  6144.3 1918.39  6314.6 1918.99  6953.6 1921.30
#Mann=7,-1,0
  3675.8    0.05       0  4987.3    0.07       0  5034.4    0.05       0
  5140.6   0.035       0  5315.8   0.045       0  6144.3   0.035       0
  6314.6   0.045       0
Bank Sta=4987.3,5034.4
Exp/Cntr=0.3,0.1

Type RM Length L Ch R = 1,1724,496,496,496
BEGIN DESCRIPTION:
UCFB HW Trib 04 3.0
END DESCRIPTION:
XS GIS Cut Line= 5
      1382380.00      6981363.02      1382126.67      6980118.27
      1382055.00      6980038.00      1381973.02      6979972.44
      1380079.96      6980102.84
#Sta/Elev= 30
  3622.1 1921.67  4035.4 1921.29  4208.9 1922.04  4341.6 1919.83  4426.3 1919.90
  4527.5 1916.47  4586.5 1915.63  4668.1 1914.90  4768.7 1915.13  4887.9 1915.23
  4943.5 1914.01  4964.5 1911.76  4969.3 1908.57  4970.3 1908.07  5015.5 1908.07
  5016.5 1908.57  5021.6 1912.59  5042.4 1915.95  5110.6 1917.14  5127.5 1916.47
  5153.1 1915.75  5231.4 1915.71  5313.5 1916.07  5333.5 1916.78  5353.6 1915.97
  5373.6 1917.00  5425.6 1916.24  6280.3 1918.18  6476.5 1918.95  7002.5 1920.84
#Mann=10,-1,0
  3622.1    0.05       0  4768.7   0.045       0  4887.9    0.07       0
  4969.3    0.05       0  5016.5    0.05       0  5127.5    0.05       0
  5231.4   0.035       0  5425.6   0.045       0  6280.3   0.035       0
  6476.5   0.045       0
Bank Sta=4969.3,5016.5
Exp/Cntr=0.3,0.1

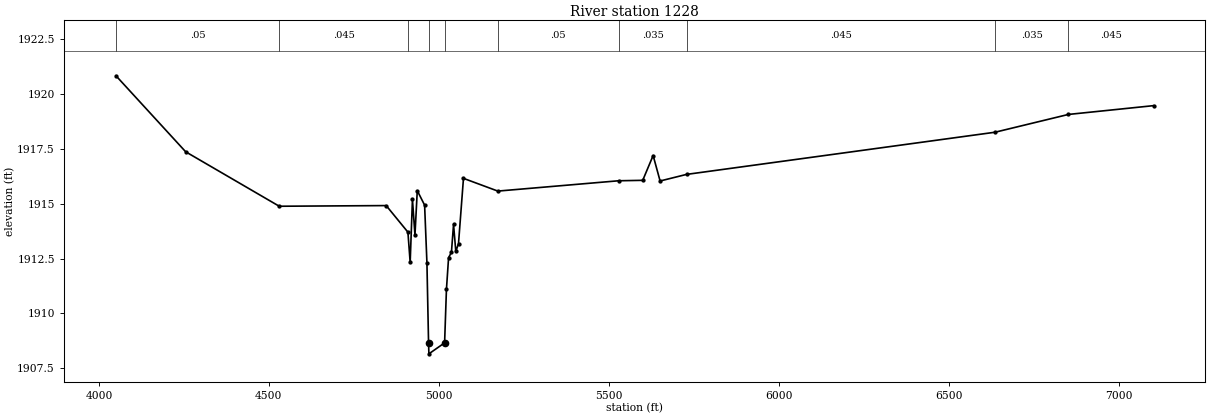
Type RM Length L Ch R = 1,1228,0,0,0
BEGIN DESCRIPTION:
UCFB HW Trib 04 2.0
END DESCRIPTION:
XS GIS Cut Line= 5
      1382480.00      6980613.00      1382486.04      6979797.96
      1382395.26      6979698.54      1382280.00      6979613.00
      1380369.37      6980046.87
#Sta/Elev= 30
  4050.3 1920.82  4255.3 1917.36  4530.6 1914.88  4845.3 1914.91  4909.2 1913.70
  4915.8 1912.32  4922.5 1915.19  4929.9 1913.57  4936.7 1915.59  4958.3 1914.93
  4965.1 1912.31  4969.9 1908.66  4970.9 1908.16  5017.1 1908.66  5022.5 1911.09
  5028.8 1912.54  5037.2 1912.78  5043.4 1914.05  5050.1 1912.82  5058.0 1913.18
  5072.6 1916.15  5173.7 1915.57  5529.2 1916.04  5600.0 1916.06  5630.6 1917.19
  5651.1 1916.03  5729.0 1916.33  6636.6 1918.25  6852.4 1919.06  7102.8 1919.46
#Mann=10,-1,0
  4050.3    0.05       0  4530.6   0.045       0  4909.2    0.07       0
  4969.9    0.07       0  5017.1    0.07       0  5173.7    0.05       0
  5529.2   0.035       0  5729.0   0.045       0  6636.6   0.035       0
  6852.4   0.045       0
Bank Sta=4969.9,5017.1
Exp/Cntr=0.3,0.1

Chan Stop Cuts=-1