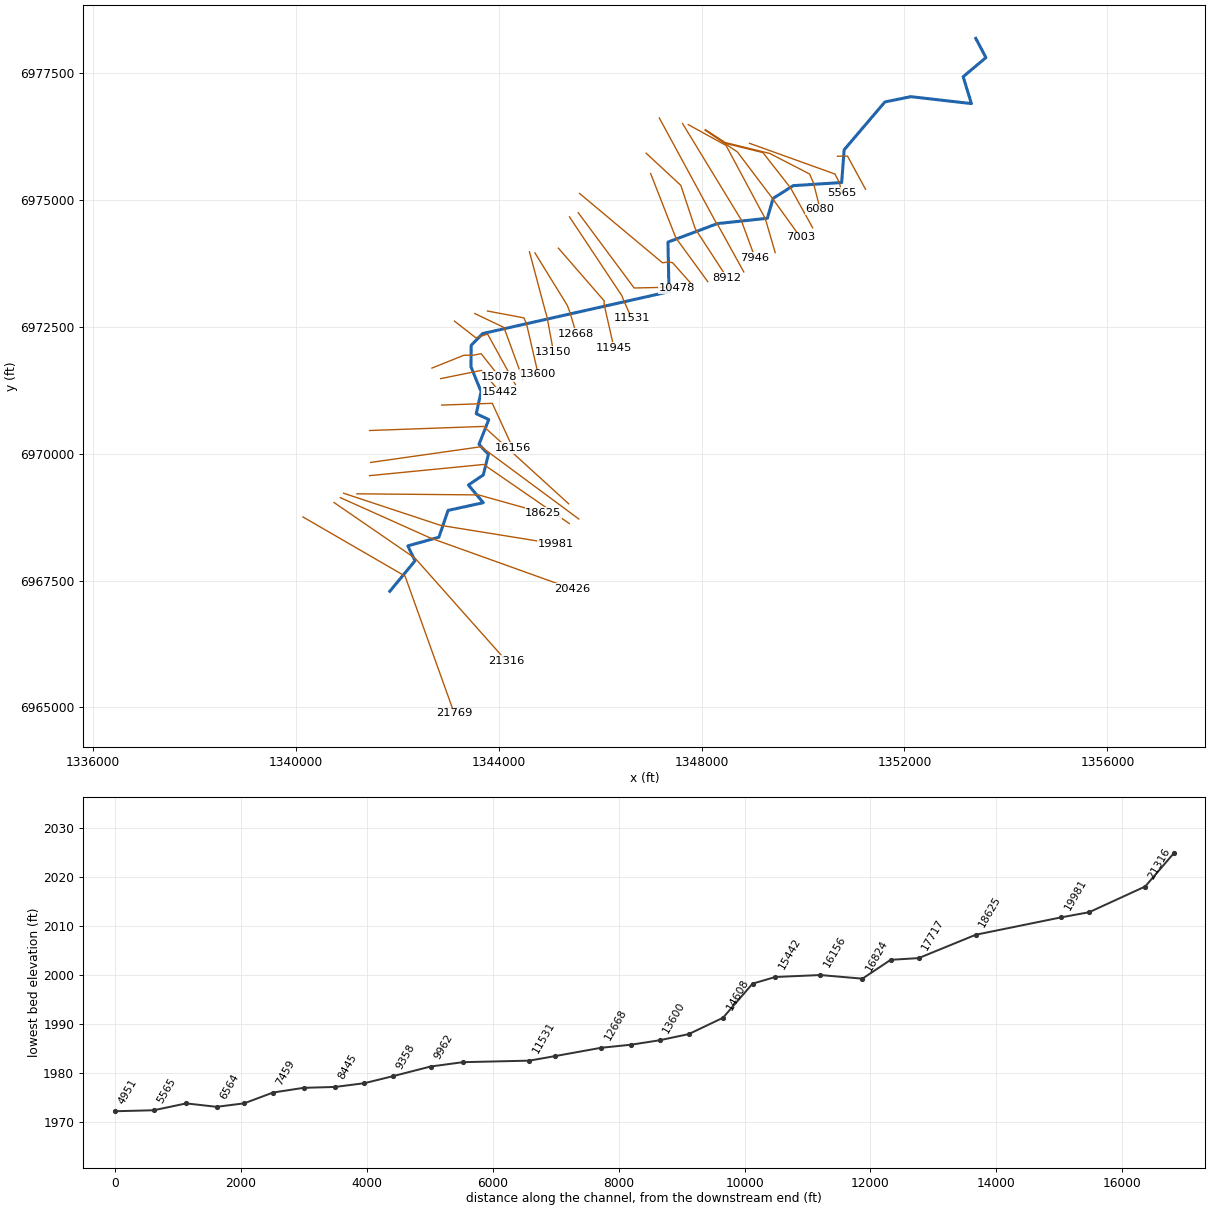
--- UCFB HW Trib 06.prj (project) ---

Proj Title=UCFB HW Trib 06 Base Level Engineering
Current Plan=p01
Default Exp/Contr=0.3,0.1
English Units
Geom File=g01
Flow File=f01
Plan File=p01
BEGIN DESCRIPTION:
UCFB HW Trib 06
END DESCRIPTION:

--- UCFB HW Trib 06.p01 (plan) ---

Plan Title=Multiple Run
Short Identifier=Multiple
Geom File=g01
Flow File=f01
Subcritical Flow
K Sum by GR= 0
Std Step Tol= 0.01
Critical Tol= 0.01
Num of Std Step Trials= 20
Max Error Tol= 0.3
Flow Tol Ratio= 0.001
Split Flow NTrial= 30
Split Flow Tol= 0.02
Split Flow Ratio= 0.02
Log Output Level= 0
Friction Slope Method= 1
Unsteady Friction Slope Method= 2
Unsteady Bridges Friction Slope Method= 1
Parabolic Critical Depth
Global Vel Dist=  1 , 1 , 1
Global Log Level= 0
CheckData=True
Encroach Param= -1, 0, 0, 0
BEGIN DESCRIPTION:
Multiple Run
END DESCRIPTION:

--- UCFB HW Trib 06.f01 (steady flow) ---

Flow Title=Multiple
Number of Profiles=7
Profile Names=10-year,25-year,50-year,1pct_min,100-year,1pct_plu,500-year
River Rch & RM= UCFB HW Trib 06,Reach-1,21769
     471     687     873     551    1099    2193    1768
River Rch & RM= UCFB HW Trib 06,Reach-1,18625
     547     802    1023     648    1292    2578    2090
River Rch & RM= UCFB HW Trib 06,Reach-1,16156
     595     873    1115     706    1409    2811    2280
River Rch & RM= UCFB HW Trib 06,Reach-1,11531
     691    1020    1307     831    1657    3307    2701
River Rch & RM= UCFB HW Trib 06,Reach-1,9358
     752    1111    1424     905    1805    3602    2941
River Rch & RM= UCFB HW Trib 06,Reach-1,4353
     739    1090    1395     884    1765    3521    2864
Boundary for River Rch & Prof#=UCFB HW Trib 06,Reach-1,1
Up Type=0
Dn Type=3
Dn Slope=0.005
Boundary for River Rch & Prof#=UCFB HW Trib 06,Reach-1,2
Up Type=0
Dn Type=3
Dn Slope=0.005
Boundary for River Rch & Prof#=UCFB HW Trib 06,Reach-1,3
Up Type=0
Dn Type=3
Dn Slope=0.005
Boundary for River Rch & Prof#=UCFB HW Trib 06,Reach-1,4
Up Type=0
Dn Type=3
Dn Slope=0.005
Boundary for River Rch & Prof#=UCFB HW Trib 06,Reach-1,5
Up Type=0
Dn Type=3
Dn Slope=0.005
Boundary for River Rch & Prof#=UCFB HW Trib 06,Reach-1,6
Up Type=0
Dn Type=3
Dn Slope=0.005
Boundary for River Rch & Prof#=UCFB HW Trib 06,Reach-1,7
Up Type=0
Dn Type=3
Dn Slope=0.005

--- UCFB HW Trib 06.g01 (geometry) ---

Geom Title=Existing Conditions

River Reach=UCFB HW Trib 06,Reach-1
Reach XY= 30
      1341855.00      6967288.00      1342351.91      6967889.64
      1342209.62      6968182.91      1342822.65      6968354.42
      1343002.56      6968882.48      1343697.33      6969034.34
      1343404.12      6969382.99      1343697.62      6969581.67
      1343797.92      6969988.01      1343612.79      6970184.58
      1343805.17      6970672.78      1343558.43      6970789.22
      1343654.62      6971222.72      1343454.76      6971712.92
      1343458.37      6972136.72      1343684.80      6972368.39
      1347357.74      6973193.34      1347337.86      6974171.55
      1348310.94      6974535.74      1349296.72      6974641.06
      1349410.59      6975032.39      1349806.58      6975284.17
      1350761.52      6975345.67      1350810.47      6975990.45
      1351613.62      6976934.16      1352125.15      6977038.36
      1353318.64      6976901.44      1353156.96      6977432.11
      1353605.06      6977807.99      1353405.00      6978188.00

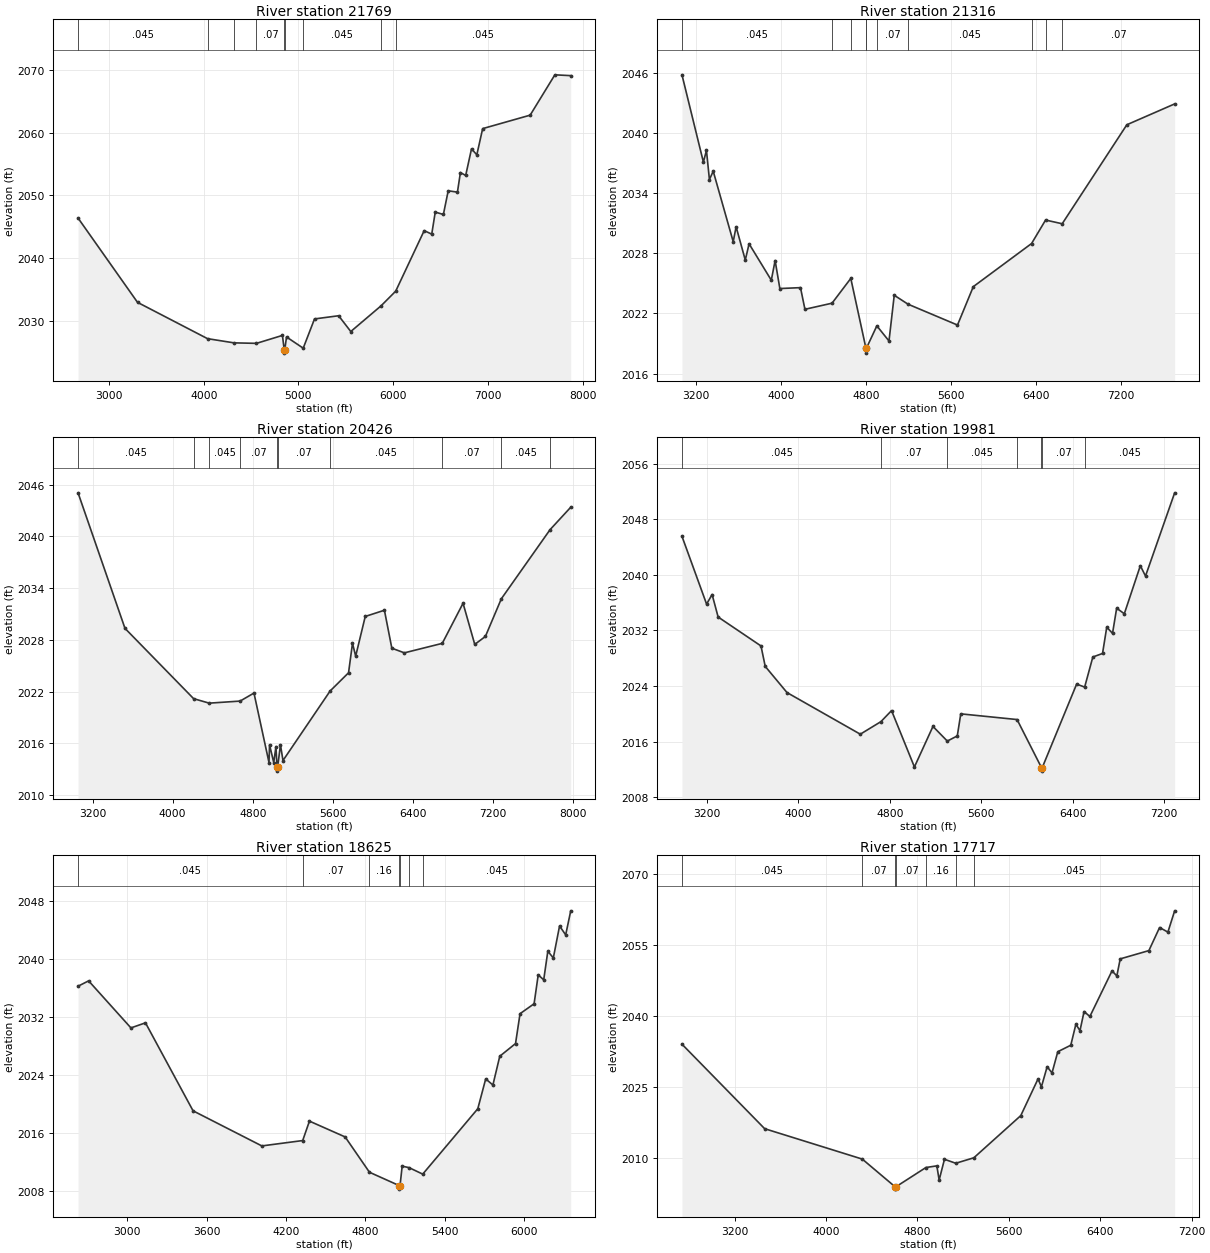
Type RM Length L Ch R = 1,21769,453,453,453
BEGIN DESCRIPTION:
UCFB HW Trib 06 26.0
END DESCRIPTION:
XS GIS Cut Line= 3
      1340141.79      6968753.86      1342155.00      6967588.00
      1343125.25      6964881.58
#Sta/Elev= 30
  2673.3 2046.37  3301.0 2032.91  4040.3 2027.11  4319.9 2026.44  4556.9 2026.36
  4831.1 2027.63  4850.2 2025.30  4850.5 2024.80  4855.2 2025.30  4874.2 2027.38
  5050.5 2025.59  5169.7 2030.26  5424.4 2030.77  5552.7 2028.25  5872.1 2032.35
  6026.7 2034.69  6327.6 2044.36  6407.3 2043.80  6444.5 2047.32  6530.3 2046.94
  6581.2 2050.72  6678.7 2050.51  6710.1 2053.64  6765.7 2053.17  6827.2 2057.42
  6883.4 2056.47  6944.9 2060.65  7446.4 2062.80  7707.2 2069.24  7874.8 2069.11
#Mann=9,-1,0
  2673.3   0.045       0  4040.3    0.07       0  4319.9   0.045       0
  4556.9    0.07       0  4850.2    0.07       0  4855.2    0.07       0
  5050.5   0.045       0  5872.1   0.035       0  6026.7   0.045       0
Bank Sta=4850.2,4855.2
Exp/Cntr=0.3,0.1

Type RM Length L Ch R = 1,21316,890,890,890
BEGIN DESCRIPTION:
UCFB HW Trib 06 25.0
END DESCRIPTION:
XS GIS Cut Line= 3
      1340755.01      6969037.99      1342355.00      6967938.00
      1344145.23      6965922.37
#Sta/Elev= 30
  3066.2 2045.79  3267.8 2037.09  3296.8 2038.25  3324.6 2035.35  3360.5 2036.18
  3548.6 2029.15  3575.9 2030.64  3662.2 2027.32  3698.0 2028.94  3907.1 2025.31
  3943.0 2027.27  3987.6 2024.48  4181.8 2024.57  4223.7 2022.41  4478.8 2023.02
  4655.3 2025.49  4797.7 2018.54  4798.0 2018.04  4802.7 2018.54  4900.6 2020.76
  5014.9 2019.25  5064.3 2023.81  5193.9 2022.92  5659.7 2020.84  5808.6 2024.67
  6357.1 2028.97  6488.8 2031.31  6645.2 2030.94  7253.6 2040.81  7703.7 2042.89
#Mann=10,-1,0
  3066.2   0.045       0  4478.8    0.07       0  4655.3    0.16       0
  4797.7    0.07       0  4802.7    0.16       0  4900.6    0.07       0
  5193.9   0.045       0  6357.1   0.035       0  6488.8   0.045       0
  6645.2    0.07       0
Bank Sta=4797.7,4802.7
Exp/Cntr=0.3,0.1

Type RM Length L Ch R = 1,20426,445,445,445
BEGIN DESCRIPTION:
UCFB HW Trib 06 24.0
END DESCRIPTION:
XS GIS Cut Line= 3
      1340879.64      6969133.63      1342655.00      6968338.00
      1345457.78      6967332.72
#Sta/Elev= 30
  3054.5 2045.05  3523.4 2029.34  4209.3 2021.19  4365.2 2020.67  4673.9 2020.91
  4812.4 2021.84  4962.5 2013.79  4967.9 2015.84  5010.0 2013.78  5031.9 2015.64
  5042.9 2013.29  5043.4 2012.79  5049.4 2013.29  5076.9 2015.85  5102.3 2014.02
  5573.3 2022.08  5757.4 2024.19  5796.8 2027.61  5828.6 2026.12  5924.3 2030.72
  6115.8 2031.44  6189.9 2027.04  6315.0 2026.50  6693.9 2027.60  6901.6 2032.25
  7018.5 2027.48  7124.7 2028.40  7284.2 2032.77  7771.0 2040.78  7977.6 2043.38
#Mann=10,-1,0
  3054.5   0.045       0  4209.3    0.07       0  4365.2   0.045       0
  4673.9    0.07       0  5042.9    0.07       0  5049.4    0.07       0
  5573.3   0.045       0  6693.9    0.07       0  7284.2   0.045       0
  7771.0   0.035       0
Bank Sta=5042.9,5049.4
Exp/Cntr=0.3,0.1

Type RM Length L Ch R = 1,19981,1356,1356,1356
BEGIN DESCRIPTION:
UCFB HW Trib 06 23.0
END DESCRIPTION:
XS GIS Cut Line= 3
      1340944.80      6969220.41      1342855.00      6968588.00
      1345121.12      6968222.35
#Sta/Elev= 30
  2983.1 2045.57  3198.4 2035.80  3246.7 2037.18  3299.3 2033.94  3674.1 2029.77
  3711.0 2026.83  3901.3 2023.06  4542.3 2017.06  4722.7 2018.87  4815.6 2020.46
  5015.5 2012.34  5177.6 2018.18  5302.9 2016.07  5390.3 2016.81  5420.7 2019.99
  5913.0 2019.17  6126.5 2012.24  6127.0 2011.74  6133.0 2012.24  6433.6 2024.27
  6503.9 2023.85  6575.4 2028.18  6660.2 2028.69  6697.0 2032.47  6747.6 2031.59
  6783.7 2035.21  6850.6 2034.41  6990.7 2041.33  7035.9 2039.84  7290.7 2051.83
#Mann=7,-1,0
  2983.1   0.045       0  4722.7    0.07       0  5302.9   0.045       0
  5913.0    0.07       0  6126.5    0.07       0  6133.0    0.07       0
  6503.9   0.045       0
Bank Sta=6126.5,6133
Exp/Cntr=0.3,0.1

Type RM Length L Ch R = 1,18625,908,908,908
BEGIN DESCRIPTION:
UCFB HW Trib 06 22.0
END DESCRIPTION:
XS GIS Cut Line= 3
      1341205.15      6969209.57      1343605.00      6969188.00
      1344881.79      6968830.30
#Sta/Elev= 30
  2627.3 2036.18  2707.2 2036.92  3027.2 2030.43  3137.2 2031.13  3497.2 2018.99
  4017.2 2014.15  4326.1 2014.89  4377.2 2017.57  4647.2 2015.39  4831.0 2010.52
  5054.4 2008.69  5054.9 2008.19  5062.4 2008.69  5078.4 2011.36  5131.1 2011.15
  5233.9 2010.26  5650.4 2019.28  5710.2 2023.40  5764.6 2022.55  5816.5 2026.52
  5935.7 2028.27  5969.8 2032.39  6076.1 2033.76  6107.3 2037.75  6148.8 2037.06
  6180.0 2041.01  6221.5 2040.08  6268.7 2044.49  6315.0 2043.26  6353.2 2046.58
#Mann=7,-1,0
  2627.3   0.045       0  4326.1    0.07       0  4831.0    0.16       0
  5054.4    0.07       0  5062.4    0.16       0  5131.1    0.07       0
  5233.9   0.045       0
Bank Sta=5054.4,5062.4
Exp/Cntr=0.3,0.1

Type RM Length L Ch R = 1,17717,444,444,444
BEGIN DESCRIPTION:
UCFB HW Trib 06 21.0
END DESCRIPTION:
XS GIS Cut Line= 3
      1341454.79      6969567.65      1343705.00      6969788.00
      1345393.58      6968623.61
#Sta/Elev= 30
  2738.7 2034.07  3462.4 2016.20  4317.0 2009.77  4603.8 2003.92  4604.3 2003.42
  4611.8 2003.92  4873.8 2007.99  4969.5 2008.34  4989.6 2005.34  5036.1 2009.73
  5135.2 2008.89  5293.4 2010.05  5704.2 2018.97  5855.0 2026.72  5884.8 2025.06
  5935.0 2029.31  5977.4 2027.99  6028.1 2032.48  6141.7 2033.85  6186.4 2038.29
  6222.2 2036.93  6258.0 2040.97  6308.8 2039.93  6502.8 2049.58  6544.7 2048.50
  6574.5 2052.11  6825.3 2053.86  6918.9 2058.74  6991.8 2057.77  7050.8 2062.27
#Mann=7,-1,0
  2738.7   0.045       0  4317.0    0.07       0  4603.8    0.07       0
  4611.8    0.07       0  4873.8    0.16       0  5135.2    0.07       0
  5293.4   0.045       0
Bank Sta=4603.8,4611.8
Exp/Cntr=0.3,0.1

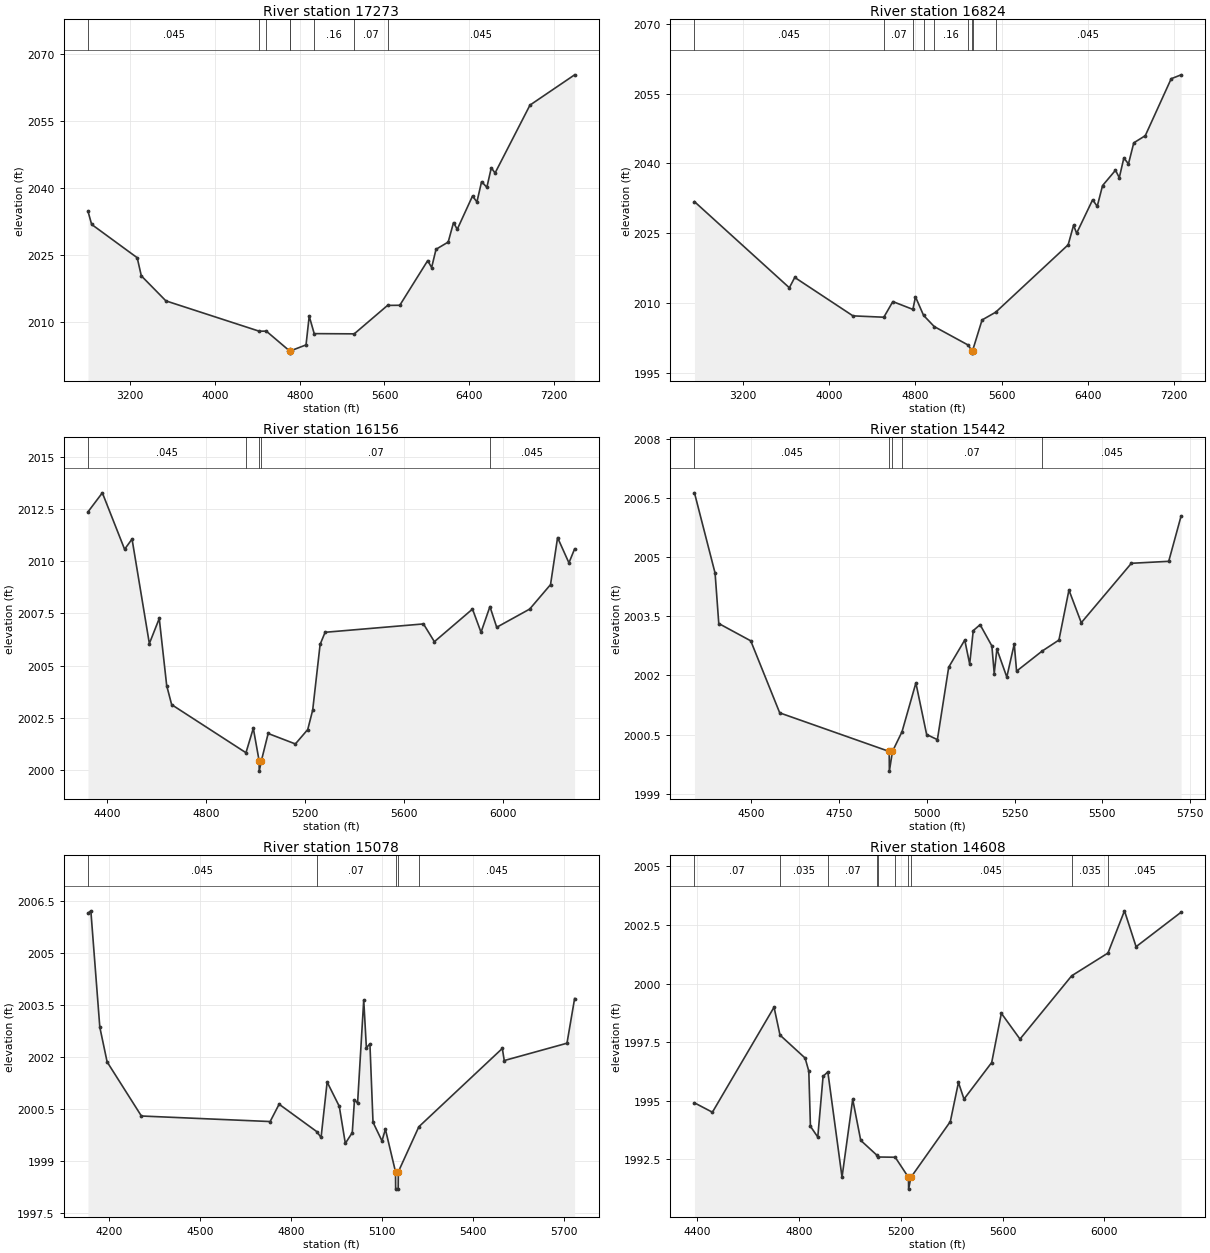
Type RM Length L Ch R = 1,17273,449,449,449
BEGIN DESCRIPTION:
UCFB HW Trib 06 20.0
END DESCRIPTION:
XS GIS Cut Line= 3
      1341476.50      6969828.07      1343655.00      6970138.00
      1345580.02      6968712.99
#Sta/Elev= 30
  2800.0 2034.78  2834.4 2031.85  3264.6 2024.40  3303.5 2020.35  3535.8 2014.75
  4417.0 2007.97  4483.8 2007.99  4703.5 2003.57  4704.0 2003.07  4711.6 2003.57
  4859.0 2004.91  4889.1 2011.33  4936.3 2007.43  5314.4 2007.38  5628.9 2013.74
  5744.5 2013.77  6008.2 2023.76  6045.1 2022.20  6086.8 2026.29  6201.6 2027.90
  6251.7 2032.24  6287.2 2030.76  6431.2 2038.19  6472.9 2036.88  6516.8 2041.39
  6566.9 2040.15  6608.6 2044.51  6644.1 2043.33  6973.9 2058.52  7395.5 2065.29
#Mann=8,-1,0
  2800.0   0.045       0  4417.0    0.07       0  4483.8   0.035       0
  4703.5    0.07       0  4711.6   0.035       0  4936.3    0.16       0
  5314.4    0.07       0  5628.9   0.045       0
Bank Sta=4703.5,4711.6
Exp/Cntr=0.3,0.1

Type RM Length L Ch R = 1,16824,668,668,668
BEGIN DESCRIPTION:
UCFB HW Trib 06 19.0
END DESCRIPTION:
XS GIS Cut Line= 3
      1341454.74      6970457.40      1343705.00      6970538.00
      1345379.98      6969013.02
#Sta/Elev= 30
  2748.7 2031.78  3629.5 2013.27  3679.6 2015.49  4219.9 2007.23  4506.5 2006.94
  4590.1 2010.30  4776.2 2008.62  4800.3 2011.32  4875.2 2007.34  4974.2 2004.93
  5291.9 2000.92  5321.7 1999.72  5322.2 1999.22  5329.8 1999.72  5418.3 2006.35
  5545.0 2008.02  6217.6 2022.51  6267.6 2026.71  6296.0 2024.99  6444.7 2032.19
  6487.2 2030.77  6536.6 2035.23  6656.8 2038.53  6692.0 2036.93  6734.5 2041.18
  6777.1 2039.89  6826.4 2044.42  6933.2 2045.96  7173.7 2058.20  7265.6 2059.04
#Mann=9,-1,0
  2748.7   0.045       0  4506.5    0.07       0  4776.2   0.035       0
  4875.2    0.07       0  4974.2    0.16       0  5291.9    0.07       0
  5321.7    0.07       0  5329.8    0.07       0  5545.0   0.045       0
Bank Sta=5321.7,5329.8
Exp/Cntr=0.3,0.1

Type RM Length L Ch R = 1,16156,714,714,714
BEGIN DESCRIPTION:
UCFB HW Trib 06 18.2
END DESCRIPTION:
XS GIS Cut Line= 3
      1342877.05      6970958.22      1343874.38      6970993.58
      1344280.01      6970112.97
#Sta/Elev= 30
  4322.0 2012.36  4380.0 2013.27  4470.0 2010.57  4500.1 2011.06  4570.1 2006.06
  4610.1 2007.26  4640.2 2004.05  4660.2 2003.14  4960.7 2000.84  4990.4 2002.01
  5013.8 2000.46  5014.3 1999.96  5023.1 2000.46  5050.4 2001.76  5160.5 2001.26
  5210.5 2001.95  5230.5 2002.88  5260.5 2006.02  5280.6 2006.60  5678.4 2007.00
  5722.5 2006.15  5876.6 2007.71  5911.1 2006.60  5947.1 2007.83  5974.5 2006.84
  6107.8 2007.71  6192.1 2008.88  6220.6 2011.13  6266.5 2009.92  6289.5 2010.59
#Mann=5,-1,0
  4322.0   0.045       0  4960.7    0.07       0  5013.8    0.07       0
  5023.1    0.07       0  5947.1   0.045       0
Bank Sta=5013.8,5023.1
Exp/Cntr=0.3,0.1

Type RM Length L Ch R = 1,15442,364,364,364
BEGIN DESCRIPTION:
UCFB HW Trib 06 18.5
END DESCRIPTION:
XS GIS Cut Line= 3
      1342857.14      6971480.45      1343658.34      6971642.24
      1344030.02      6971212.97
#Sta/Elev= 30
  4338.9 2006.64  4397.6 2004.60  4408.1 2003.32  4499.1 2002.88  4581.6 2001.05
  4893.2 2000.07  4893.7 1999.57  4902.5 2000.07  4929.7 2000.57  4969.2 2001.81
  4999.8 2000.50  5030.4 2000.37  5062.6 2002.21  5108.3 2002.90  5122.3 2002.29
  5132.5 2003.14  5152.0 2003.29  5185.5 2002.75  5192.2 2002.05  5199.8 2002.67
  5228.0 2001.96  5249.2 2002.80  5255.8 2002.11  5328.6 2002.62  5376.4 2002.90
  5404.9 2004.17  5440.0 2003.34  5582.6 2004.85  5688.9 2004.90  5724.1 2006.05
#Mann=5,-1,0
  4338.9   0.045       0  4893.2    0.07       0  4902.5   0.045       0
  4929.7    0.07       0  5328.6   0.045       0
Bank Sta=4893.2,4902.5
Exp/Cntr=0.3,0.1

Type RM Length L Ch R = 1,15078,470,470,470
BEGIN DESCRIPTION:
UCFB HW Trib 06 18.1
END DESCRIPTION:
XS GIS Cut Line= 5
      1342685.25      6971687.91      1343314.59      6971940.86
      1343505.81      6971943.03      1343654.87      6971972.11
      1344016.00      6971513.75
#Sta/Elev= 30
  4130.5 2006.16  4139.9 2006.23  4169.5 2002.87  4193.6 2001.87  4306.6 2000.31
  4731.2 2000.15  4760.8 2000.65  4884.9 1999.86  4899.2 1999.69  4919.2 2001.29
  4959.2 2000.59  4979.2 1999.52  5002.1 1999.83  5009.4 2000.78  5019.6 2000.68
  5039.9 2003.66  5048.6 2002.28  5060.3 2002.39  5070.5 2000.13  5100.1 1999.59
  5111.3 1999.93  5144.7 1998.70  5145.2 1998.20  5153.5 1998.20  5154.0 1998.70
  5221.7 2000.00  5497.0 2002.26  5503.3 2001.91  5710.2 2002.41  5735.4 2003.70
#Mann=5,-1,0
  4130.5   0.045       0  4884.9    0.07       0  5144.7    0.07       0
  5154.0    0.07       0  5221.7   0.045       0
Bank Sta=5144.7,5154
Exp/Cntr=0.3,0.1

Type RM Length L Ch R = 1,14608,544,544,544
BEGIN DESCRIPTION:
UCFB HW Trib 06 18.0
END DESCRIPTION:
XS GIS Cut Line= 4
      1343130.03      6972612.97      1343551.08      6972284.48
      1343782.85      6972358.26      1344329.99      6971363.01
#Sta/Elev= 30
  4388.8 1994.91  4459.3 1994.51  4701.7 1998.99  4725.1 1997.80  4823.8 1996.82
  4838.3 1996.26  4844.7 1993.91  4873.6 1993.45  4894.4 1996.04  4913.1 1996.23
  4968.9 1991.74  5010.9 1995.06  5042.4 1993.31  5105.6 1992.68  5110.2 1992.60
  5178.0 1992.59  5230.2 1991.73  5230.7 1991.23  5239.5 1991.73  5394.6 1994.11
  5426.6 1995.78  5448.4 1995.07  5557.3 1996.63  5595.2 1998.73  5668.5 1997.63
  5871.8 2000.33  6014.4 2001.30  6079.3 2003.10  6124.9 2001.57  6301.8 2003.04
#Mann=10,-1,0
  4388.8    0.07       0  4725.1   0.035       0  4913.1    0.07       0
  5105.6   0.045       0  5110.2   0.035       0  5178.0   0.045       0
  5230.2    0.07       0  5239.5   0.045       0  5871.8   0.035       0
  6014.4   0.045       0
Bank Sta=5230.2,5239.5
Exp/Cntr=0.3,0.1

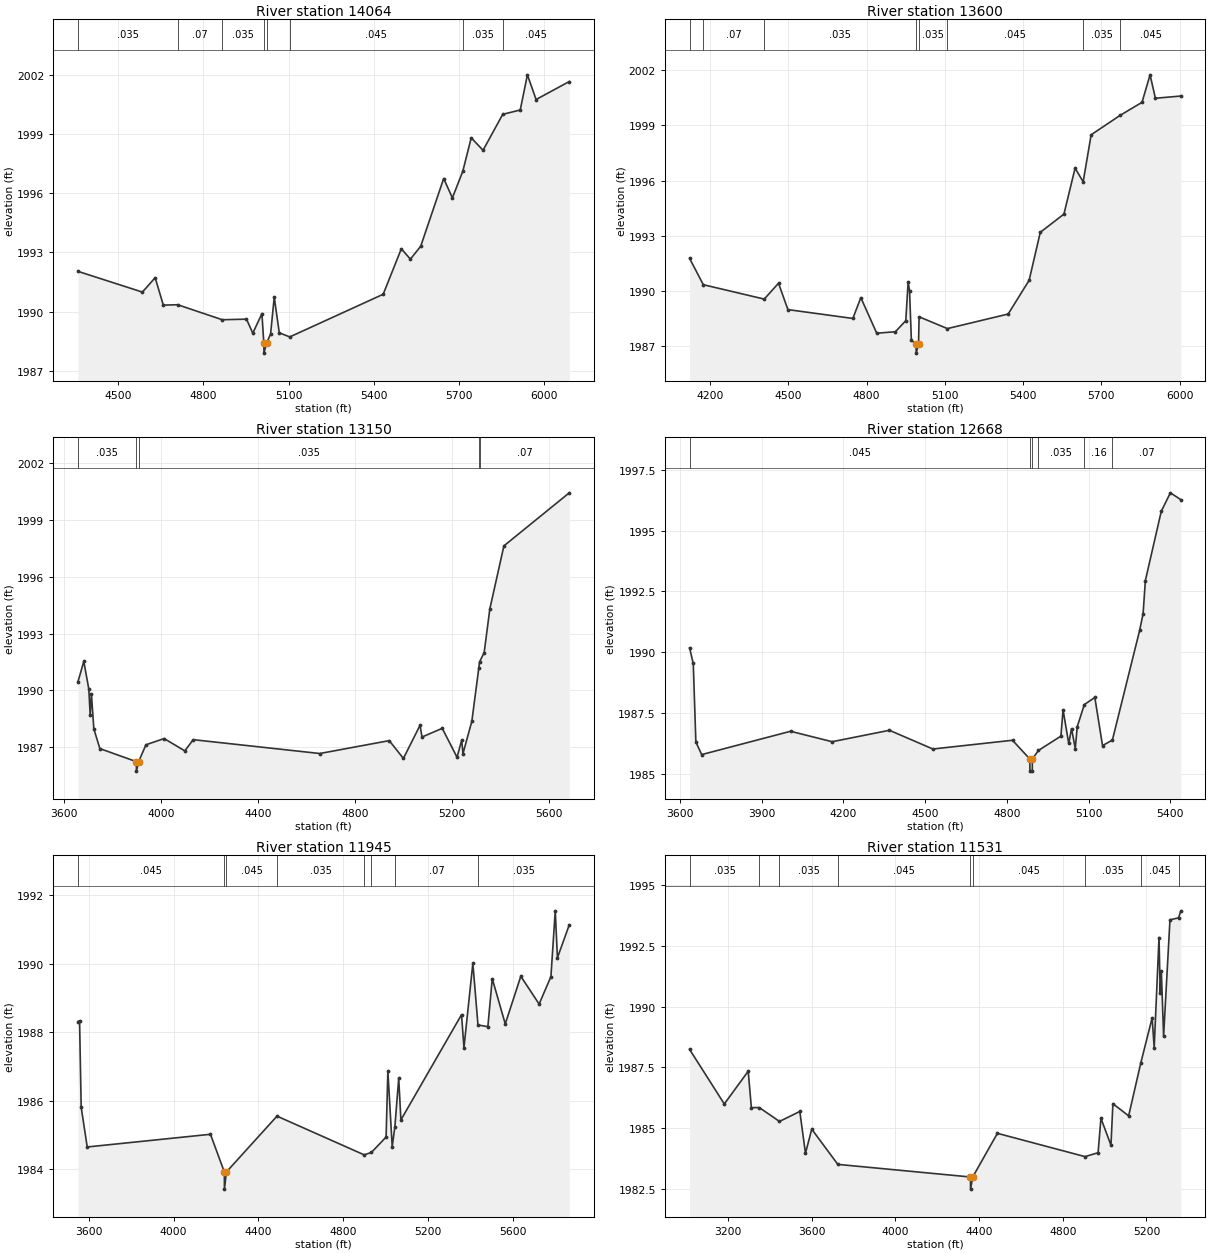
Type RM Length L Ch R = 1,14064,464,464,464
BEGIN DESCRIPTION:
UCFB HW Trib 06 17.0
END DESCRIPTION:
XS GIS Cut Line= 3
      1343530.00      6972763.00      1344105.00      6972488.00
      1344479.99      6971463.03
#Sta/Elev= 30
  4358.5 1992.04  4585.2 1990.99  4630.1 1991.72  4658.8 1990.33  4709.4 1990.35
  4866.3 1989.59  4951.5 1989.62  4973.7 1988.91  5005.8 1989.90  5012.5 1988.40
  5013.0 1987.90  5021.9 1988.40  5036.3 1988.87  5049.1 1990.73  5066.9 1988.93
  5103.7 1988.72  5432.5 1990.88  5496.3 1993.18  5528.3 1992.66  5564.5 1993.31
  5645.4 1996.74  5676.0 1995.76  5712.7 1997.11  5742.3 1998.80  5783.9 1998.17
  5853.2 1999.99  5914.8 2000.21  5940.0 2001.99  5970.6 2000.74  6087.3 2001.65
#Mann=8,-1,0
  4358.5   0.035       0  4709.4    0.07       0  4866.3   0.035       0
  5012.5   0.035       0  5021.9   0.035       0  5103.7   0.045       0
  5712.7   0.035       0  5853.2   0.045       0
Bank Sta=5012.5,5021.9
Exp/Cntr=0.3,0.1

Type RM Length L Ch R = 1,13600,450,450,450
BEGIN DESCRIPTION:
UCFB HW Trib 06 16.0
END DESCRIPTION:
XS GIS Cut Line= 4
      1343780.02      6972813.00      1344500.35      6972676.97
      1344555.00      6972538.00      1344780.00      6971563.02
#Sta/Elev= 30
  4121.7 1991.78  4174.4 1990.35  4407.9 1989.57  4462.6 1990.43  4498.6 1989.00
  4747.6 1988.52  4778.1 1989.65  4839.1 1987.72  4910.6 1987.80  4950.4 1988.40
  4959.4 1990.49  4964.8 1990.03  4971.9 1987.33  4989.8 1987.14  4990.3 1986.64
  4999.3 1987.14  5001.4 1988.61  5109.9 1987.97  5342.8 1988.76  5423.2 1990.59
  5465.9 1993.19  5556.6 1994.18  5599.3 1996.67  5630.3 1995.93  5660.9 1998.48
  5771.7 1999.53  5855.9 2000.24  5886.7 2001.73  5907.2 2000.46  6004.7 2000.58
#Mann=8,-1,0
  4121.7   0.035       0  4174.4    0.07       0  4407.9   0.035       0
  4989.8   0.035       0  4999.3   0.035       0  5109.9   0.045       0
  5630.3   0.035       0  5771.7   0.045       0
Bank Sta=4989.8,4999.3
Exp/Cntr=0.3,0.1

Type RM Length L Ch R = 1,13150,482,482,482
BEGIN DESCRIPTION:
UCFB HW Trib 06 15.0
END DESCRIPTION:
XS GIS Cut Line= 4
      1344606.97      6973981.22      1344922.23      6972801.97
      1344955.00      6972688.00      1345080.00      6972013.02
#Sta/Elev= 30
  3656.5 1990.46  3680.5 1991.53  3701.2 1990.07  3706.7 1988.71  3711.9 1989.81
  3721.9 1987.97  3746.7 1986.93  3897.1 1986.24  3897.6 1985.74  3906.6 1986.24
  3936.7 1987.13  4011.6 1987.46  4096.9 1986.81  4131.8 1987.40  4653.5 1986.67
  4940.0 1987.35  4998.3 1986.41  5066.9 1988.16  5075.1 1987.54  5158.5 1988.00
  5219.5 1986.47  5238.8 1987.38  5243.9 1986.66  5280.5 1988.37  5309.0 1991.16
  5312.2 1991.50  5331.4 1992.00  5354.8 1994.31  5412.7 1997.63  5682.2 2000.43
#Mann=5,-1,0
  3656.5   0.035       0  3897.1   0.035       0  3906.6   0.035       0
  5309.0    0.16       0  5312.2    0.07       0
Bank Sta=3897.1,3906.6
Exp/Cntr=0.3,0.1

Type RM Length L Ch R = 1,12668,723,723,723
BEGIN DESCRIPTION:
UCFB HW Trib 06 14.0
END DESCRIPTION:
XS GIS Cut Line= 4
      1344715.13      6973958.29      1345354.52      6972921.76
      1345405.00      6972788.00      1345529.99      6972363.04
#Sta/Elev= 30
  3635.0 1990.17  3648.6 1989.53  3658.1 1986.30  3679.4 1985.78  4005.8 1986.74
  4158.4 1986.31  4368.9 1986.78  4528.3 1986.01  4820.7 1986.37  4884.2 1985.60
  4884.7 1985.10  4893.2 1985.10  4893.7 1985.60  4915.8 1985.95  4998.4 1986.54
  5006.3 1987.62  5027.1 1986.24  5037.5 1986.85  5051.1 1986.03  5058.4 1986.93
  5084.5 1987.84  5123.0 1988.13  5151.2 1986.15  5187.5 1986.38  5287.7 1990.90
  5300.2 1991.58  5308.5 1992.94  5366.9 1995.79  5400.3 1996.55  5438.8 1996.27
#Mann=6,-1,0
  3635.0   0.045       0  4884.2   0.035       0  4893.7   0.045       0
  4915.8   0.035       0  5084.5    0.16       0  5187.5    0.07       0
Bank Sta=4884.2,4893.7
Exp/Cntr=0.3,0.1

Type RM Length L Ch R = 1,11945,414,414,414
BEGIN DESCRIPTION:
UCFB HW Trib 06 13.4
END DESCRIPTION:
XS GIS Cut Line= 4
      1345177.91      6974051.87      1346080.00      6973013.00
      1346079.04      6972943.26      1346271.19      6972093.63
#Sta/Elev= 30
  3549.2 1988.31  3556.7 1988.33  3564.3 1985.81  3592.8 1984.65  4173.9 1985.02
  4239.4 1983.92  4239.9 1983.42  4249.0 1983.92  4487.7 1985.55  4898.8 1984.42
  4932.8 1984.49  5002.2 1984.94  5010.5 1986.87  5031.0 1984.66  5043.4 1985.23
  5061.7 1986.65  5072.0 1985.44  5357.9 1988.51  5369.3 1987.55  5411.3 1990.01
  5435.4 1988.21  5482.1 1988.16  5502.8 1989.56  5564.1 1988.24  5637.4 1989.63
  5723.8 1988.82  5779.4 1989.62  5799.9 1991.54  5810.1 1990.17  5865.9 1991.13
#Mann=8,-1,0
  3549.2   0.045       0  4239.4   0.035       0  4249.0   0.045       0
  4487.7   0.035       0  4898.8   0.045       0  4932.8   0.035       0
  5043.4    0.07       0  5435.4   0.035       0
Bank Sta=4239.4,4249
Exp/Cntr=0.3,0.1

Type RM Length L Ch R = 1,11531,1053,1053,1053
BEGIN DESCRIPTION:
UCFB HW Trib 06 13.2
END DESCRIPTION:
XS GIS Cut Line= 4
      1345396.29      6974668.39      1346430.00      6973113.00
      1346465.94      6973020.64      1346619.78      6972672.59
#Sta/Elev= 30
  3017.1 1988.24  3183.0 1985.99  3297.3 1987.34  3312.3 1985.84  3350.5 1985.84
  3446.7 1985.27  3543.8 1985.68  3570.8 1983.96  3600.9 1984.95  3725.4 1983.50
  4359.1 1982.98  4359.6 1982.48  4369.9 1982.98  4487.8 1984.78  4906.3 1983.82
  4968.9 1983.98  4982.5 1985.40  5030.4 1984.29  5039.6 1986.00  5114.9 1985.50
  5173.2 1987.69  5227.2 1989.54  5236.9 1988.31  5260.0 1992.85  5265.7 1990.56
  5271.1 1991.45  5281.9 1988.78  5312.3 1993.58  5353.2 1993.66  5364.3 1993.95
#Mann=9,-1,0
  3017.1   0.035       0  3350.5    0.07       0  3446.7   0.035       0
  3725.4   0.045       0  4359.1   0.035       0  4369.9   0.045       0
  4906.3   0.035       0  5173.2   0.045       0  5353.2    0.07       0
Bank Sta=4359.1,4369.9
Exp/Cntr=0.3,0.1

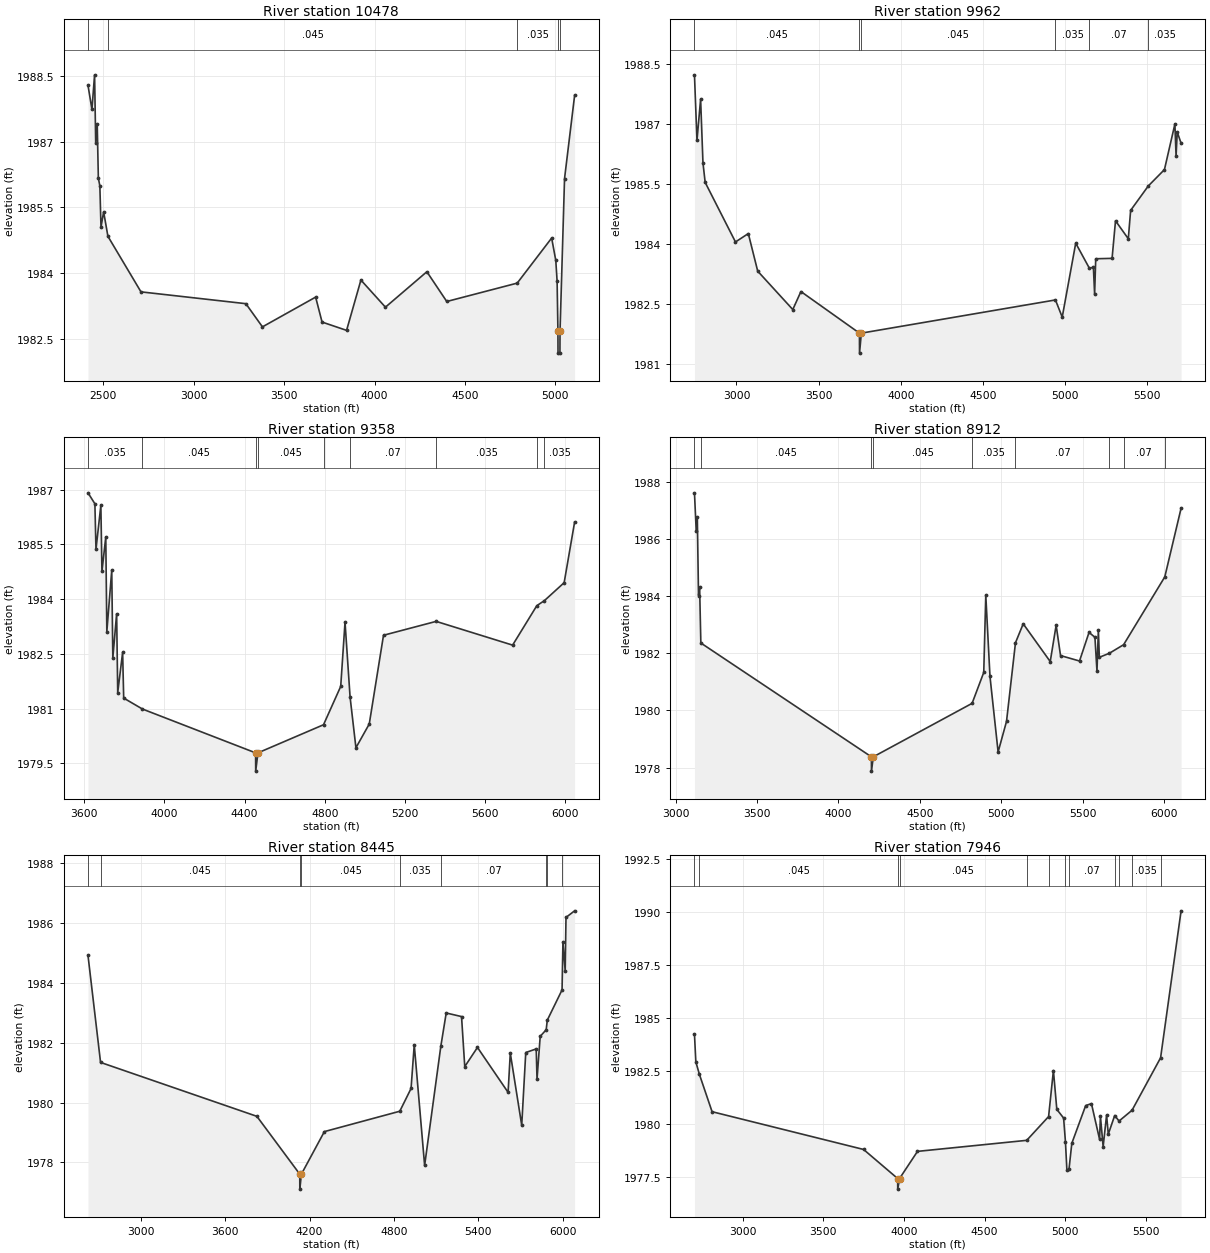
Type RM Length L Ch R = 1,10478,516,516,516
BEGIN DESCRIPTION:
UCFB HW Trib 06 13.0
END DESCRIPTION:
XS GIS Cut Line= 4
      1345568.13      6974752.01      1346670.72      6973266.67
      1347405.50      6973282.76      1347509.56      6973260.11
#Sta/Elev= 30
  2415.2 1988.29  2437.0 1987.74  2451.6 1988.53  2457.8 1986.98  2466.2 1987.41
  2472.5 1986.17  2480.8 1985.99  2487.1 1985.05  2501.7 1985.40  2525.3 1984.84
  2708.2 1983.57  3288.3 1983.30  3380.0 1982.77  3674.2 1983.45  3709.7 1982.88
  3845.3 1982.69  3924.6 1983.84  4060.2 1983.22  4289.3 1984.03  4399.4 1983.35
  4789.0 1983.77  4979.5 1984.80  5002.3 1984.29  5009.7 1983.81  5014.2 1982.67
  5014.7 1982.17  5025.3 1982.17  5025.8 1982.67  5050.8 1986.16  5106.5 1988.06
#Mann=5,-1,0
  2415.2    0.07       0  2525.3   0.045       0  4789.0   0.035       0
  5014.2   0.035       0  5025.8   0.035       0
Bank Sta=5014.2,5025.8
Exp/Cntr=0.3,0.1

Type RM Length L Ch R = 1,9962,604,604,604
BEGIN DESCRIPTION:
UCFB HW Trib 06 12.0
END DESCRIPTION:
XS GIS Cut Line= 5
      1345595.07      6975130.10      1347230.00      6973763.00
      1347352.74      6973782.06      1347430.00      6973763.00
      1347845.26      6973295.20
#Sta/Elev= 30
  2744.6 1988.24  2759.9 1986.60  2782.0 1987.63  2796.3 1986.04  2809.7 1985.55
  2994.1 1984.06  3072.2 1984.27  3129.4 1983.33  3342.8 1982.37  3392.3 1982.82
  3748.3 1981.78  3748.8 1981.28  3759.9 1981.78  4940.8 1982.61  4982.0 1982.18
  5064.1 1984.03  5147.6 1983.40  5171.6 1983.43  5179.1 1982.75  5185.8 1983.64
  5285.3 1983.65  5306.2 1984.59  5384.0 1984.14  5398.2 1984.85  5505.5 1985.46
  5603.9 1985.87  5667.5 1987.01  5674.6 1986.21  5681.7 1986.81  5705.1 1986.53
#Mann=6,-1,0
  2744.6   0.045       0  3748.3   0.035       0  3759.9   0.045       0
  4940.8   0.035       0  5147.6    0.07       0  5505.5   0.035       0
Bank Sta=3748.3,3759.9
Exp/Cntr=0.3,0.1

Type RM Length L Ch R = 1,9358,446,446,446
BEGIN DESCRIPTION:
UCFB HW Trib 06 11.0
END DESCRIPTION:
XS GIS Cut Line= 4
      1346996.30      6975522.11      1347476.40      6974296.56
      1347505.00      6974238.00      1348121.94      6973392.44
#Sta/Elev= 30
  3618.6 1986.91  3653.0 1986.61  3658.4 1985.36  3682.8 1986.57  3688.2 1984.76
  3707.3 1985.70  3712.6 1983.11  3737.1 1984.79  3742.5 1982.39  3761.5 1983.60
  3766.9 1981.44  3791.4 1982.54  3796.7 1981.29  3890.3 1980.99  4454.9 1979.79
  4455.4 1979.29  4466.5 1979.79  4793.8 1980.56  4879.6 1981.61  4901.1 1983.37
  4926.3 1981.32  4955.5 1979.93  5022.0 1980.58  5093.1 1983.01  5355.7 1983.39
  5737.3 1982.74  5858.1 1983.82  5896.3 1983.96  5994.5 1984.45  6046.7 1986.11
#Mann=9,-1,0
  3618.6   0.035       0  3890.3   0.045       0  4454.9    0.07       0
  4466.5   0.045       0  4793.8   0.035       0  4926.3    0.07       0
  5355.7   0.035       0  5858.1    0.07       0  5896.3   0.035       0
Bank Sta=4454.9,4466.5
Exp/Cntr=0.3,0.1

Type RM Length L Ch R = 1,8912,467,467,467
BEGIN DESCRIPTION:
UCFB HW Trib 06 10.0
END DESCRIPTION:
XS GIS Cut Line= 5
      1346906.70      6975924.46      1347591.61      6975289.03
      1347869.63      6974450.20      1347905.00      6974388.00
      1348505.99      6973464.71
#Sta/Elev= 30
  3114.7 1987.61  3125.4 1986.29  3132.2 1986.77  3139.6 1984.02  3146.4 1984.31
  3153.9 1982.36  4202.3 1978.38  4202.8 1977.88  4213.9 1978.38  4821.3 1980.25
  4892.9 1981.33  4905.4 1984.03  4931.2 1981.19  4981.2 1978.55  5032.9 1979.62
  5088.0 1982.37  5135.5 1983.03  5301.6 1981.71  5337.9 1982.98  5364.9 1981.92
  5481.5 1981.73  5540.1 1982.73  5576.3 1982.56  5588.9 1981.37  5597.4 1982.82
  5603.4 1981.86  5664.8 1982.00  5752.6 1982.30  6005.7 1984.67  6105.9 1987.07
#Mann=9,-1,0
  3114.7   0.035       0  3153.9   0.045       0  4202.3   0.035       0
  4213.9   0.045       0  4821.3   0.035       0  5088.0    0.07       0
  5664.8   0.035       0  5752.6    0.07       0  6005.7   0.035       0
Bank Sta=4202.3,4213.9
Exp/Cntr=0.3,0.1

Type RM Length L Ch R = 1,8445,499,499,499
BEGIN DESCRIPTION:
UCFB HW Trib 06 9.0
END DESCRIPTION:
XS GIS Cut Line= 4
      1347166.69      6976618.91      1348276.84      6974571.68
      1348305.00      6974538.00      1348832.08      6973583.63
#Sta/Elev= 30
  2623.1 1984.91  2712.5 1981.34  3825.0 1979.54  4130.1 1977.61  4130.6 1977.11
  4141.8 1977.61  4305.2 1979.03  4841.9 1979.71  4922.2 1980.47  4944.8 1981.93
  5018.7 1977.90  5134.0 1981.88  5172.3 1982.99  5281.4 1982.87  5304.3 1981.20
  5394.6 1981.84  5612.7 1980.34  5628.3 1981.65  5709.7 1979.24  5738.4 1981.67
  5812.8 1981.79  5818.5 1980.78  5841.2 1982.21  5883.8 1982.43  5891.6 1982.75
  5996.7 1983.76  6003.0 1985.37  6019.0 1984.39  6024.7 1986.18  6086.1 1986.40
#Mann=9,-1,0
  2623.1    0.07       0  2712.5   0.045       0  4130.1   0.035       0
  4141.8   0.045       0  4841.9   0.035       0  5134.0    0.07       0
  5883.8   0.035       0  5891.6    0.07       0  5996.7   0.035       0
Bank Sta=4130.1,4141.8
Exp/Cntr=0.3,0.1

Type RM Length L Ch R = 1,7946,487,487,487
BEGIN DESCRIPTION:
UCFB HW Trib 06 8.0
END DESCRIPTION:
XS GIS Cut Line= 4
      1347624.59      6976508.66      1348780.00      6974613.00
      1348805.00      6974538.00      1349053.37      6973864.62
#Sta/Elev= 30
  2700.9 1984.24  2709.4 1982.93  2731.5 1982.34  2810.1 1980.58  3749.3 1978.80
  3960.6 1977.43  3961.1 1976.93  3972.3 1977.43  4083.6 1978.71  4760.7 1979.23
  4896.3 1980.35  4926.2 1982.52  4947.3 1980.69  4989.4 1980.28  5000.8 1979.16
  5009.9 1977.81  5022.7 1977.86  5040.3 1979.09  5126.3 1980.87  5162.0 1980.96
  5212.3 1979.28  5217.6 1980.37  5234.5 1978.93  5255.8 1980.42  5266.4 1979.52
  5306.1 1980.40  5333.2 1980.14  5413.8 1980.65  5590.6 1983.12  5717.7 1990.05
#Mann=12,-1,0
  2700.9    0.07       0  2731.5   0.045       0  3960.6    0.07       0
  3972.3   0.045       0  4760.7   0.035       0  4896.3    0.07       0
  5000.8   0.035       0  5022.7    0.07       0  5306.1   0.035       0
  5333.2    0.07       0  5413.8   0.035       0  5590.6    0.07       0
Bank Sta=3960.6,3972.3
Exp/Cntr=0.3,0.1

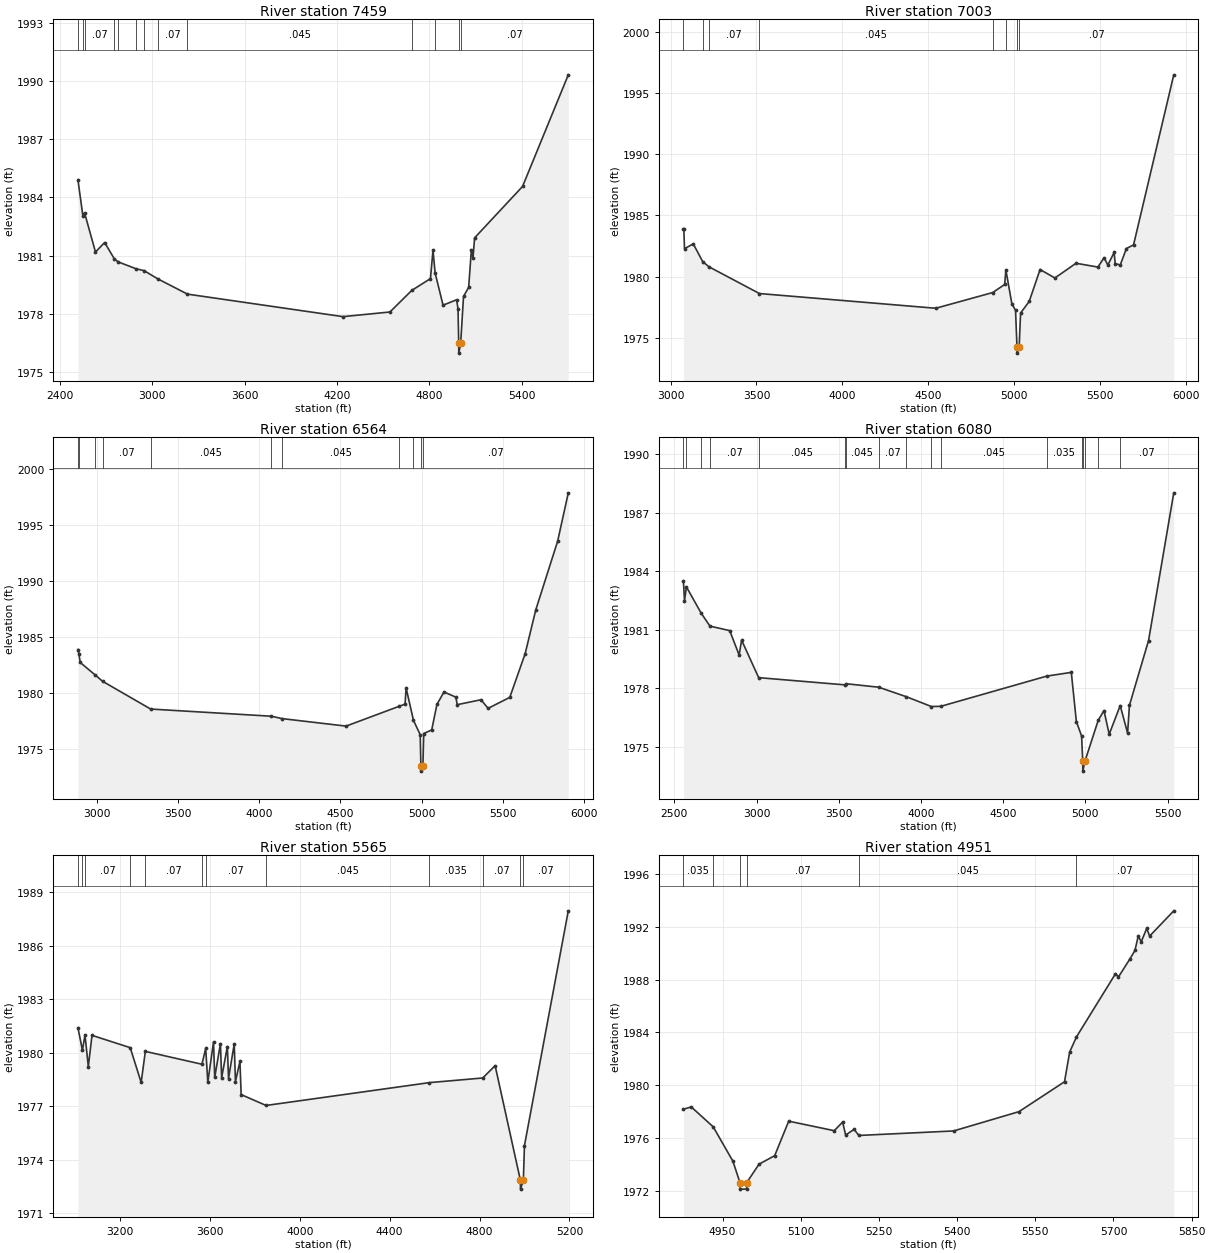
Type RM Length L Ch R = 1,7459,456,456,456
BEGIN DESCRIPTION:
UCFB HW Trib 06 7.0
END DESCRIPTION:
XS GIS Cut Line= 5
      1347737.90      6976486.71      1348482.69      6976076.99
      1349186.57      6974760.91      1349255.00      6974638.00
      1349451.93      6973963.47
#Sta/Elev= 30
  2516.2 1984.90  2548.2 1983.05  2559.2 1983.20  2630.2 1981.18  2689.8 1981.67
  2752.5 1980.83  2777.9 1980.67  2892.8 1980.32  2945.8 1980.22  3034.3 1979.80
  3227.9 1979.01  4238.3 1977.85  4543.4 1978.09  4684.9 1979.20  4806.7 1979.81
  4823.0 1981.28  4836.9 1980.10  4888.5 1978.44  4976.5 1978.72  4985.7 1978.25
  4990.2 1976.47  4990.7 1975.97  5002.8 1976.47  5021.4 1978.89  5054.8 1979.36
  5072.3 1981.28  5082.7 1980.86  5093.5 1981.91  5405.1 1984.56  5702.1 1990.31
#Mann=13,-1,0
  2516.2    0.07       0  2548.2   0.035       0  2559.2    0.07       0
  2752.5   0.045       0  2777.9    0.07       0  2892.8   0.035       0
  2945.8   0.045       0  3034.3    0.07       0  3227.9   0.045       0
  4684.9   0.035       0  4836.9    0.07       0  4990.2    0.07       0
  5002.8    0.07       0
Bank Sta=4990.2,5002.8
Exp/Cntr=0.3,0.1

Type RM Length L Ch R = 1,7003,439,439,439
BEGIN DESCRIPTION:
UCFB HW Trib 06 6.0
END DESCRIPTION:
XS GIS Cut Line= 4
      1348073.70      6976375.88      1348705.93      6975948.51
      1349373.63      6975065.17      1349949.58      6974266.75
#Sta/Elev= 30
  3074.5 1983.88  3077.0 1983.88  3080.9 1982.29  3131.8 1982.68  3186.7 1981.24
  3222.3 1980.82  3517.0 1978.63  4543.7 1977.43  4875.0 1978.71  4944.9 1979.37
  4951.9 1980.55  4987.3 1977.76  5008.2 1977.27  5016.6 1974.27  5017.1 1973.77
  5029.2 1974.27  5037.6 1977.04  5087.9 1977.99  5151.0 1980.59  5237.4 1979.90
  5360.3 1981.10  5487.9 1980.79  5523.5 1981.55  5545.6 1980.96  5582.3 1981.98
  5588.5 1981.07  5617.9 1980.96  5653.5 1982.30  5695.3 1982.60  5929.4 1996.47
#Mann=8,-1,0
  3074.5   0.035       0  3186.7    0.12       0  3222.3    0.07       0
  3517.0   0.045       0  4875.0   0.035       0  4951.9    0.07       0
  5016.6    0.07       0  5029.2    0.07       0
Bank Sta=5016.6,5029.2
Exp/Cntr=0.3,0.1

Type RM Length L Ch R = 1,6564,484,484,484
BEGIN DESCRIPTION:
UCFB HW Trib 06 5.0
END DESCRIPTION:
XS GIS Cut Line= 5
      1348076.93      6976379.80      1348475.83      6976116.42
      1349209.17      6975935.84      1349755.00      6975238.00
      1350190.12      6974453.14
#Sta/Elev= 30
  2885.6 1983.88  2891.4 1983.50  2899.6 1982.73  2992.9 1981.60  3037.4 1981.05
  3333.0 1978.58  4076.2 1977.94  4140.3 1977.73  4535.1 1977.06  4860.8 1978.82
  4898.1 1979.02  4904.4 1980.46  4949.9 1977.57  4991.2 1976.30  4995.3 1973.55
  4995.8 1973.05  5007.9 1973.55  5012.8 1976.40  5062.0 1976.72  5094.1 1978.99
  5137.6 1980.10  5210.6 1979.64  5218.8 1978.97  5365.3 1979.41  5408.8 1978.64
  5542.2 1979.62  5636.6 1983.50  5702.3 1987.42  5836.9 1993.54  5902.2 1997.84
#Mann=11,-1,0
  2885.6    0.12       0  2891.4   0.035       0  2992.9    0.12       0
  3037.4    0.07       0  3333.0   0.045       0  4076.2    0.07       0
  4140.3   0.045       0  4860.8   0.035       0  4949.9    0.07       0
  4995.3    0.07       0  5007.9    0.07       0
Bank Sta=4995.3,5007.9
Exp/Cntr=0.3,0.1

Type RM Length L Ch R = 1,6080,515,515,515
BEGIN DESCRIPTION:
UCFB HW Trib 06 4.0
END DESCRIPTION:
XS GIS Cut Line= 6
      1348074.74      6976386.76      1348463.85      6976134.65
      1349344.94      6975918.72      1350130.00      6975513.00
      1350205.00      6975338.00      1350338.73      6974816.79
#Sta/Elev= 30
  2555.1 1983.50  2561.7 1982.48  2573.3 1983.19  2664.2 1981.83  2716.6 1981.18
  2836.7 1980.95  2894.0 1979.70  2909.2 1980.46  3012.9 1978.54  3537.6 1978.17
  3542.8 1978.23  3743.0 1978.05  3912.1 1977.56  4063.8 1977.06  4120.7 1977.07
  4765.8 1978.62  4914.8 1978.81  4945.6 1976.29  4977.4 1975.55  4984.4 1974.25
  4984.9 1973.75  4997.5 1974.25  5078.8 1976.36  5113.6 1976.85  5145.3 1975.64
  5212.3 1977.11  5257.2 1975.70  5268.4 1977.12  5384.7 1980.44  5538.1 1988.01
#Mann=17,-1,0
  2555.1    0.12       0  2573.3   0.035       0  2664.2    0.12       0
  2716.6    0.07       0  3012.9   0.045       0  3537.6    0.07       0
  3542.8   0.045       0  3743.0    0.07       0  3912.1   0.045       0
  4063.8    0.07       0  4120.7   0.045       0  4765.8   0.035       0
  4977.4    0.07       0  4984.4    0.07       0  4997.5    0.07       0
  5078.8   0.035       0  5212.3    0.07       0
Bank Sta=4984.4,4997.5
Exp/Cntr=0.3,0.1

Type RM Length L Ch R = 1,5565,614,614,614
BEGIN DESCRIPTION:
UCFB HW Trib 06 3.0
END DESCRIPTION:
XS GIS Cut Line= 4
      1348946.11      6976118.47      1350630.00      6975513.00
      1350720.26      6975337.48      1350758.87      6975146.65
#Sta/Elev= 30
  3013.2 1981.40  3033.1 1980.14  3044.6 1980.99  3059.4 1979.22  3075.8 1980.97
  3245.8 1980.28  3294.5 1978.33  3313.1 1980.07  3564.9 1979.35  3581.6 1980.24
  3591.0 1978.34  3616.4 1980.60  3621.8 1978.61  3647.2 1980.51  3652.5 1978.59
  3677.9 1980.34  3683.2 1978.55  3708.6 1980.50  3713.9 1978.38  3734.0 1979.51
  3739.3 1977.65  3850.1 1977.04  4576.9 1978.32  4814.0 1978.58  4869.2 1979.27
  4981.6 1972.85  4982.1 1972.35  4994.8 1972.85  4999.7 1974.79  5194.7 1987.95
#Mann=12,-1,0
  3013.2    0.07       0  3033.1    0.12       0  3044.6    0.07       0
  3245.8    0.12       0  3313.1    0.07       0  3564.9    0.12       0
  3581.6    0.07       0  3850.1   0.045       0  4576.9   0.035       0
  4814.0    0.07       0  4981.6    0.07       0  4994.8    0.07       0
Bank Sta=4981.6,4994.8
Exp/Cntr=0.3,0.1

Type RM Length L Ch R = 1,4951,598,598,598
BEGIN DESCRIPTION:
UCFB HW Trib 06 2.9
END DESCRIPTION:
XS GIS Cut Line= 4
      1350680.02      6975863.00      1350809.22      6975867.56
      1350876.71      6975866.04      1351232.21      6975212.57
#Sta/Elev= 30
  4875.0 1978.19  4890.0 1978.37  4932.2 1976.86  4970.0 1974.26  4983.4 1972.65
  4983.9 1972.15  4996.1 1972.15  4996.6 1972.65  5020.1 1974.04  5050.1 1974.68
  5077.0 1977.29  5164.3 1976.57  5180.5 1977.22  5186.2 1976.24  5202.3 1976.67
  5211.7 1976.21  5393.3 1976.55  5518.7 1978.01  5606.1 1980.27  5616.0 1982.52
  5629.0 1983.66  5703.9 1988.44  5709.6 1988.20  5731.4 1989.55  5741.2 1990.20
  5747.6 1991.30  5753.3 1990.86  5763.8 1991.87  5769.4 1991.29  5815.7 1993.20
#Mann=6,-1,0
  4875.0   0.035       0  4932.2    0.07       0  4983.4    0.07       0
  4996.6    0.07       0  5211.7   0.045       0  5629.0    0.07       0
Bank Sta=4983.4,4996.6
Exp/Cntr=0.3,0.1