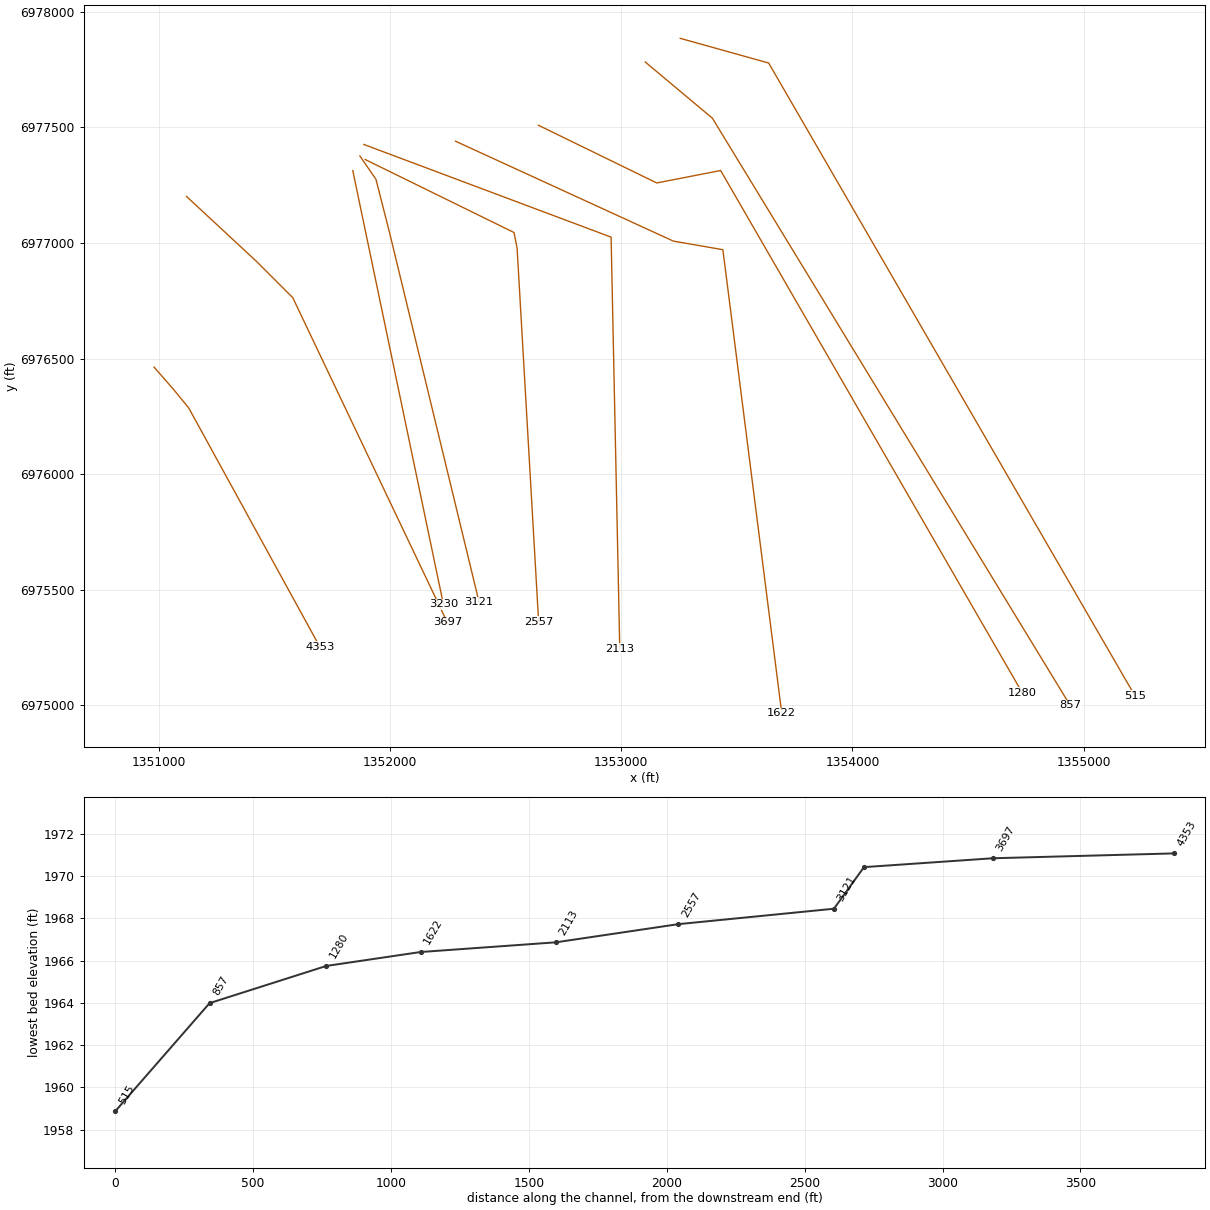
HEC-RAS study UCFB HW Trib 06.prj: UCFB HW Trib 06 Base Level Engineering

--- UCFB HW Trib 06.g01 (geometry) --- (continued)

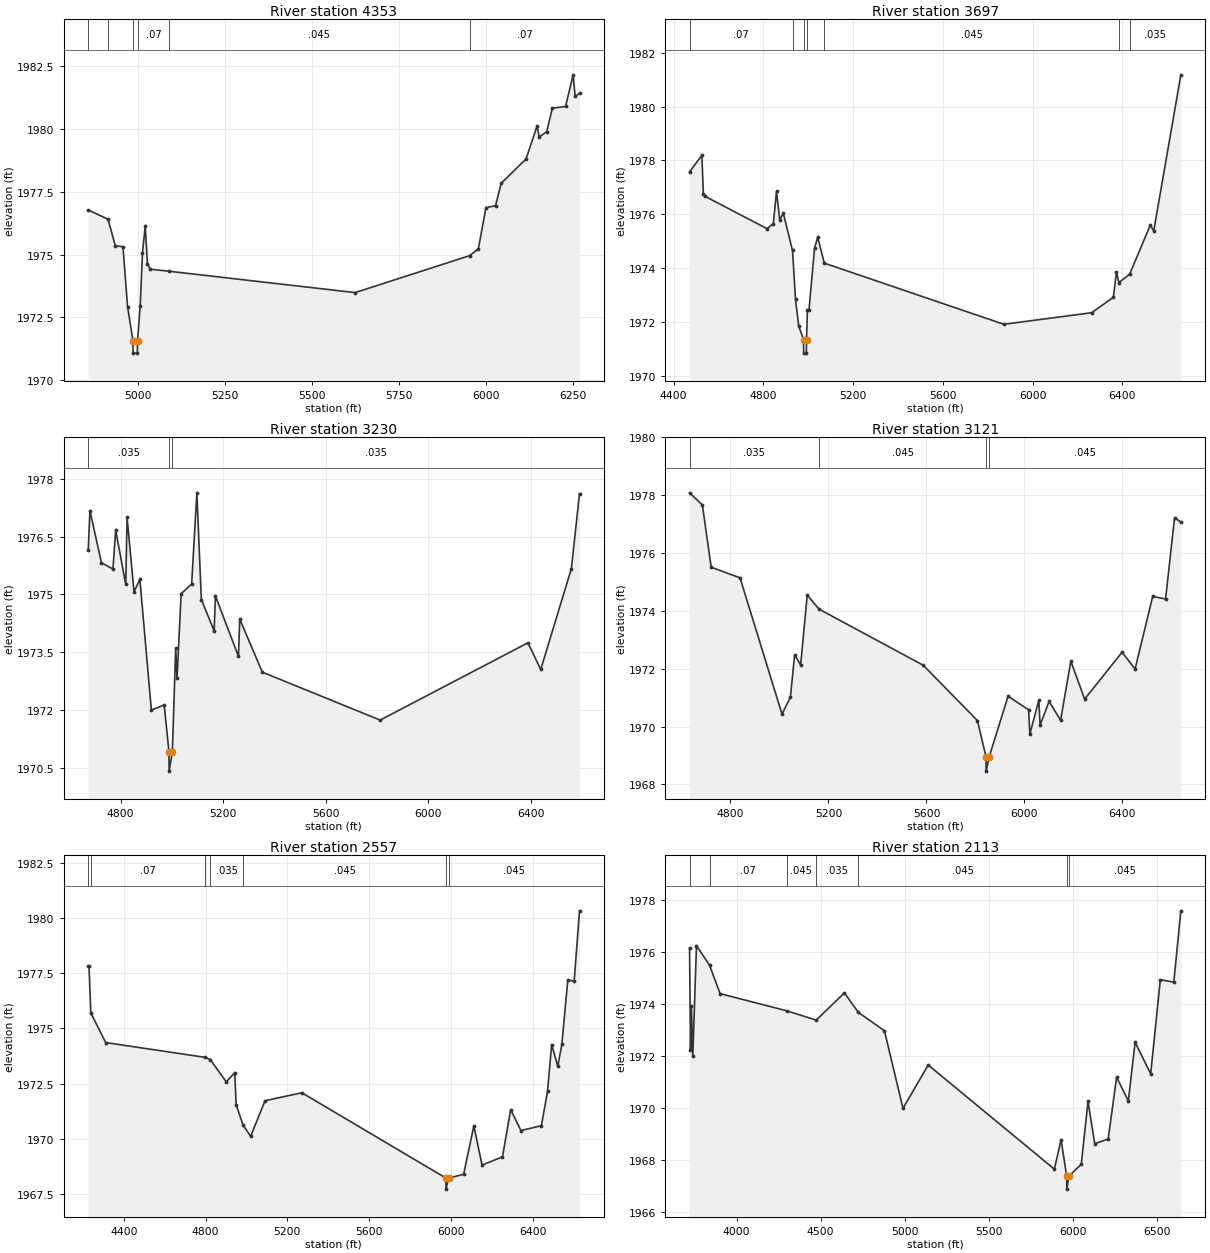
Type RM Length L Ch R = 1,4353,656,656,656
BEGIN DESCRIPTION:
UCFB HW Trib 06 2.8
END DESCRIPTION:
XS GIS Cut Line= 4
      1350980.02      6976462.98      1351062.64      6976368.55
      1351130.00      6976286.38      1351696.84      6975253.40
#Sta/Elev= 30
  4857.8 1976.78  4914.7 1976.41  4935.6 1975.35  4957.4 1975.32  4970.7 1972.93
  4986.1 1971.58  4986.6 1971.08  4998.8 1971.08  4999.3 1971.58  5007.0 1972.96
  5013.5 1975.08  5021.4 1976.14  5027.8 1974.64  5035.7 1974.42  5089.9 1974.34
  5623.8 1973.49  5952.3 1974.96  5977.4 1975.23  5999.3 1976.87  6026.8 1976.95
  6042.9 1977.84  6114.3 1978.81  6146.2 1980.13  6151.9 1979.68  6173.7 1979.90
  6189.8 1980.83  6227.7 1980.90  6249.5 1982.16  6255.2 1981.30  6267.8 1981.42
#Mann=6,-1,0
  4857.8   0.035       0  4914.7    0.07       0  4986.1    0.07       0
  4999.3    0.07       0  5089.9   0.045       0  5952.3    0.07       0
Bank Sta=4986.1,4999.3
Exp/Cntr=0.3,0.1

Type RM Length L Ch R = 1,3697,467,467,467
BEGIN DESCRIPTION:
UCFB HW Trib 06 2.0
END DESCRIPTION:
XS GIS Cut Line= 5
      1351120.45      6977200.88      1351423.17      6976919.83
      1351505.00      6976838.00      1351580.00      6976763.00
      1352248.05      6975358.88
#Sta/Elev= 30
  4471.4 1977.58  4526.2 1978.19  4533.0 1976.76  4540.4 1976.67  4816.5 1975.47
  4844.8 1975.66  4859.0 1976.85  4873.2 1975.80  4889.3 1976.04  4930.2 1974.66
  4943.6 1972.85  4957.8 1971.86  4979.4 1971.35  4979.9 1970.85  4992.1 1970.85
  4992.6 1971.35  4996.7 1972.45  5003.7 1972.45  5028.5 1974.75  5042.6 1975.15
  5071.9 1974.19  5872.4 1971.92  6263.5 1972.35  6360.4 1972.92  6374.2 1973.86
  6385.1 1973.47  6433.0 1973.78  6524.9 1975.60  6540.4 1975.39  6661.2 1981.18
#Mann=7,-1,0
  4471.4    0.07       0  4930.2   0.035       0  4979.4   0.035       0
  4992.6   0.035       0  5071.9   0.045       0  6385.1    0.07       0
  6433.0   0.035       0
Bank Sta=4979.4,4992.6
Exp/Cntr=0.3,0.1

Type RM Length L Ch R = 1,3230,109,109,109
BEGIN DESCRIPTION:
UCFB HW Trib 06 1.35
END DESCRIPTION:
XS GIS Cut Line= 2
      1351839.34      6977312.84      1352231.34      6975436.96
#Sta/Elev= 30
  4673.4 1976.14  4680.0 1977.17  4724.9 1975.82  4769.8 1975.66  4780.5 1976.66
  4819.8 1975.26  4824.9 1977.00  4852.0 1975.07  4874.9 1975.39  4919.7 1972.01
  4969.7 1972.14  4988.4 1970.93  4988.9 1970.43  5001.6 1970.93  5014.6 1973.62
  5019.7 1972.83  5035.9 1975.02  5076.8 1975.27  5097.2 1977.63  5114.6 1974.87
  5164.6 1974.06  5169.7 1974.96  5259.4 1973.40  5264.5 1974.36  5352.6 1972.99
  5812.3 1971.75  6388.6 1973.75  6438.6 1973.06  6558.1 1975.67  6589.8 1977.61
#Mann=3,-1,0
  4673.4   0.035       0  4988.4   0.035       0  5001.6   0.035       0
Bank Sta=4988.4,5001.6
Exp/Cntr=0.3,0.1

Type RM Length L Ch R = 1,3121,564,564,564
BEGIN DESCRIPTION:
UCFB HW Trib 06 1.3
END DESCRIPTION:
XS GIS Cut Line= 4
      1351870.14      6977375.78      1351939.74      6977274.72
      1351999.82      6977038.45      1352385.64      6975446.43
#Sta/Elev= 30
  4633.5 1978.08  4685.8 1977.66  4721.6 1975.51  4839.5 1975.14  5010.7 1970.43
  5045.0 1971.02  5062.2 1972.48  5086.8 1972.13  5113.6 1974.55  5161.6 1974.06
  5587.0 1972.12  5807.8 1970.21  5843.0 1968.96  5843.5 1968.46  5856.2 1968.96
  5933.2 1971.05  6016.9 1970.58  6022.0 1969.74  6058.7 1970.91  6063.8 1970.05
  6100.5 1970.87  6147.4 1970.22  6189.2 1972.26  6245.5 1970.95  6398.3 1972.57
  6451.3 1971.99  6523.3 1974.50  6575.8 1974.41  6612.5 1977.22  6638.1 1977.07
#Mann=4,-1,0
  4633.5   0.035       0  5161.6   0.045       0  5843.0   0.035       0
  5856.2   0.045       0
Bank Sta=5843,5856.2
Exp/Cntr=0.3,0.1

Type RM Length L Ch R = 1,2557,444,444,444
BEGIN DESCRIPTION:
UCFB HW Trib 06 1.2
END DESCRIPTION:
XS GIS Cut Line= 4
      1351893.16      6977360.59      1352536.58      6977044.85
      1352549.94      6976977.00      1352643.05      6975361.85
#Sta/Elev= 30
  4225.7 1977.83  4229.5 1977.83  4238.4 1975.70  4311.2 1974.36  4798.6 1973.69
  4822.8 1973.59  4901.4 1972.58  4942.4 1973.00  4949.4 1971.55  4983.1 1970.63
  5020.6 1970.12  5090.7 1971.73  5271.0 1972.09  5975.6 1968.23  5976.1 1967.73
  5988.8 1968.23  6062.3 1968.40  6112.4 1970.59  6152.5 1968.82  6252.6 1969.19
  6292.7 1971.33  6342.8 1970.38  6442.9 1970.60  6473.0 1972.16  6493.0 1974.27
  6523.1 1973.29  6543.1 1974.28  6572.2 1977.20  6603.2 1977.13  6629.4 1980.32
#Mann=7,-1,0
  4225.7   0.035       0  4238.4    0.07       0  4798.6   0.045       0
  4822.8   0.035       0  4983.1   0.045       0  5975.6   0.045       0
  5988.8   0.045       0
Bank Sta=5975.6,5988.8
Exp/Cntr=0.3,0.1

Type RM Length L Ch R = 1,2113,491,491,491
BEGIN DESCRIPTION:
UCFB HW Trib 06 3.15
END DESCRIPTION:
XS GIS Cut Line= 3
      1351887.00      6977425.72      1352956.37      6977024.90
      1352993.82      6975246.01
#Sta/Elev= 30
  3720.8 1976.16  3726.3 1972.22  3731.6 1973.91  3740.0 1972.00  3761.9 1976.25
  3839.7 1975.49  3902.5 1974.40  4298.0 1973.74  4473.9 1973.38  4641.4 1974.43
  4724.0 1973.68  4879.7 1972.97  4989.7 1969.98  5139.8 1971.65  5889.9 1967.64
  5929.9 1968.77  5963.4 1967.37  5963.9 1966.87  5976.6 1967.37  6050.0 1967.83
  6090.0 1970.25  6130.0 1968.62  6210.0 1968.80  6260.0 1971.18  6330.0 1970.27
  6370.0 1972.53  6462.8 1971.31  6520.1 1974.94  6600.1 1974.84  6642.1 1977.59
#Mann=7,-1,0
  3720.8   0.035       0  3839.7    0.07       0  4298.0   0.045       0
  4473.9   0.035       0  4724.0   0.045       0  5963.4   0.045       0
  5976.6   0.045       0
Bank Sta=5963.4,5976.6
Exp/Cntr=0.3,0.1

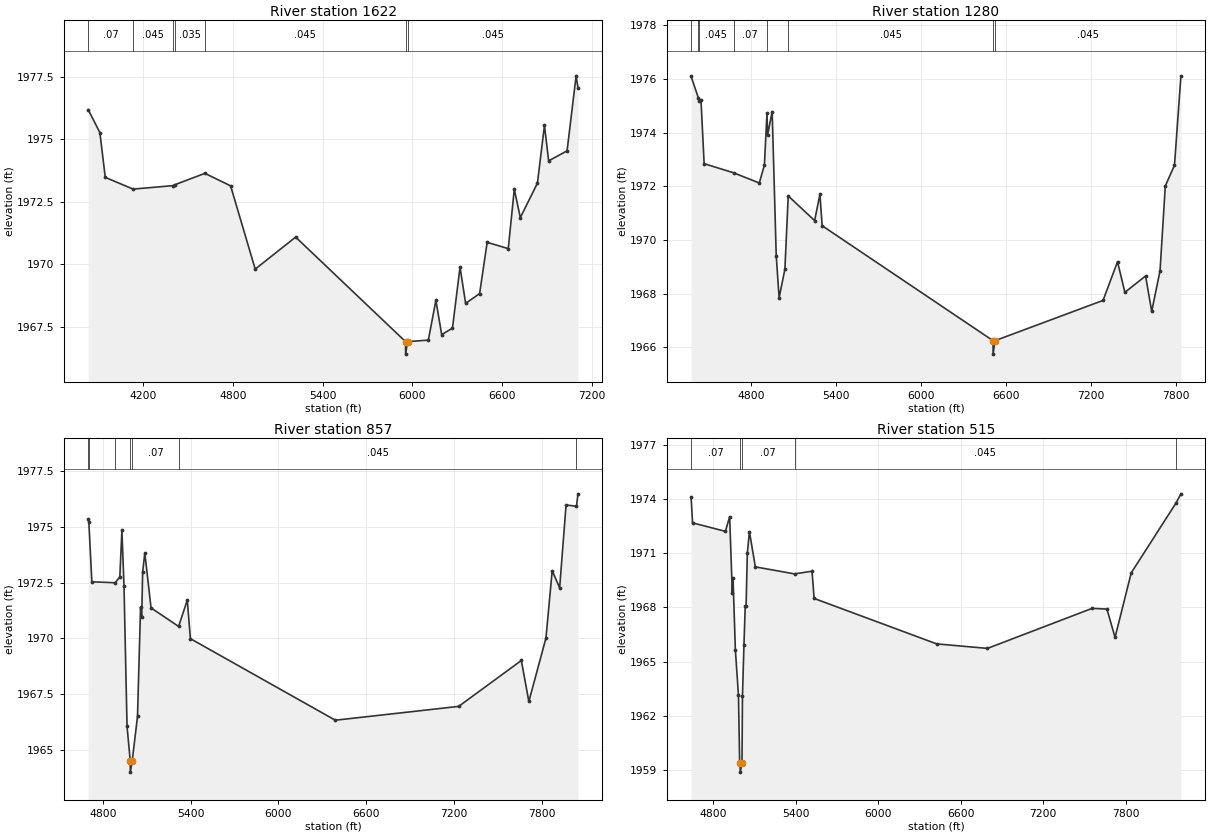
Type RM Length L Ch R = 1,1622,342,342,342
BEGIN DESCRIPTION:
UCFB HW Trib 06 1.1
END DESCRIPTION:
XS GIS Cut Line= 4
      1352283.77      6977439.59      1353225.59      6977007.74
      1353439.72      6976970.60      1353694.34      6974965.64
#Sta/Elev= 30
  3832.0 1976.19  3910.4 1975.27  3946.3 1973.48  4132.3 1973.01  4402.2 1973.15
  4413.8 1973.19  4612.5 1973.64  4784.2 1973.14  4948.7 1969.81  5219.1 1971.09
  5953.8 1966.91  5954.3 1966.41  5967.0 1966.91  6106.2 1966.97  6156.6 1968.56
  6195.4 1967.19  6267.5 1967.45  6317.9 1969.89  6355.4 1968.44  6448.9 1968.83
  6499.3 1970.88  6640.4 1970.63  6680.7 1973.00  6721.1 1971.87  6835.5 1973.25
  6882.4 1975.56  6910.4 1974.14  7033.6 1974.54  7094.0 1977.54  7106.5 1977.06
#Mann=7,-1,0
  3832.0    0.07       0  4132.3   0.045       0  4402.2    0.07       0
  4413.8   0.035       0  4612.5   0.045       0  5953.8   0.045       0
  5967.0   0.045       0
Bank Sta=5953.8,5967
Exp/Cntr=0.3,0.1

Type RM Length L Ch R = 1,1280,423,423,423
BEGIN DESCRIPTION:
UCFB HW Trib 06 2.15
END DESCRIPTION:
XS GIS Cut Line= 4
      1352642.29      6977508.59      1353153.69      6977259.18
      1353430.00      6977313.00      1354733.85      6975055.45
#Sta/Elev= 30
  4379.4 1976.09  4430.0 1975.30  4435.3 1975.19  4449.2 1975.21  4471.4 1972.84
  4679.6 1972.50  4860.8 1972.12  4896.9 1972.79  4915.0 1974.73  4919.4 1973.91
  4951.6 1974.78  4980.3 1969.42  5000.7 1967.85  5041.4 1968.91  5065.0 1971.64
  5251.4 1970.72  5288.7 1971.70  5304.5 1970.53  6510.8 1966.25  6511.3 1965.75
  6524.1 1966.25  7287.4 1967.75  7389.3 1969.19  7441.3 1968.05  7587.5 1968.66
  7630.6 1967.34  7689.4 1968.85  7726.7 1972.01  7791.4 1972.78  7836.9 1976.11
#Mann=8,-1,0
  4379.4   0.045       0  4430.0    0.07       0  4435.3   0.045       0
  4679.6    0.07       0  4915.0   0.035       0  5065.0   0.045       0
  6510.8   0.035       0  6524.1   0.045       0
Bank Sta=6510.8,6524.1
Exp/Cntr=0.3,0.1

Type RM Length L Ch R = 1,857,342,342,342
BEGIN DESCRIPTION:
UCFB HW Trib 06 1.15
END DESCRIPTION:
XS GIS Cut Line= 3
      1353104.11      6977782.15      1353394.38      6977539.16
      1354940.89      6975000.94
#Sta/Elev= 30
  4698.4 1975.34  4703.0 1975.23  4723.7 1972.53  4882.9 1972.49  4915.0 1972.75
  4929.3 1974.84  4943.6 1972.35  4964.4 1966.05  4986.4 1964.49  4986.9 1963.99
  4999.7 1964.49  5036.0 1966.49  5056.8 1971.39  5064.6 1970.93  5071.1 1972.96
  5086.0 1973.83  5128.6 1971.36  5317.2 1970.53  5376.5 1971.71  5397.8 1969.98
  6389.3 1966.32  7232.9 1966.94  7661.7 1969.00  7713.1 1967.16  7830.2 1970.01
  7872.8 1973.03  7923.8 1972.26  7967.7 1975.98  8038.9 1975.92  8049.2 1976.48
#Mann=7,-1,0
  4698.4    0.07       0  4703.0   0.045       0  4882.9    0.07       0
  4986.4    0.07       0  4999.7    0.07       0  5317.2   0.045       0
  8038.9   0.035       0
Bank Sta=4986.4,4999.7
Exp/Cntr=0.3,0.1

Type RM Length L Ch R = 1,515,0,0,0
BEGIN DESCRIPTION:
UCFB HW Trib 06 1.0
END DESCRIPTION:
XS GIS Cut Line= 3
      1353255.20      6977884.53      1353637.62      6977777.84
      1355221.40      6975041.68
#Sta/Elev= 30
  4641.2 1974.12  4651.7 1972.69  4890.2 1972.22  4921.3 1973.03  4940.7 1968.79
  4945.9 1969.63  4962.8 1965.65  4985.3 1963.13  4994.0 1959.39  4997.7 1959.37
  4998.2 1958.87  5011.0 1959.37  5014.3 1963.07  5025.1 1965.90  5034.3 1968.06
  5040.6 1968.06  5049.6 1971.00  5064.9 1972.20  5108.0 1970.25  5392.9 1969.86
  5519.8 1970.01  5534.9 1968.50  6425.3 1965.98  6794.1 1965.73  7554.6 1967.95
  7662.3 1967.91  7721.1 1966.34  7838.8 1969.92  8163.1 1973.78  8199.7 1974.30
#Mann=5,-1,0
  4641.2    0.07       0  4997.7    0.07       0  5011.0    0.07       0
  5392.9   0.045       0  8163.1   0.035       0
Bank Sta=4997.7,5011
Exp/Cntr=0.3,0.1

Chan Stop Cuts=-1