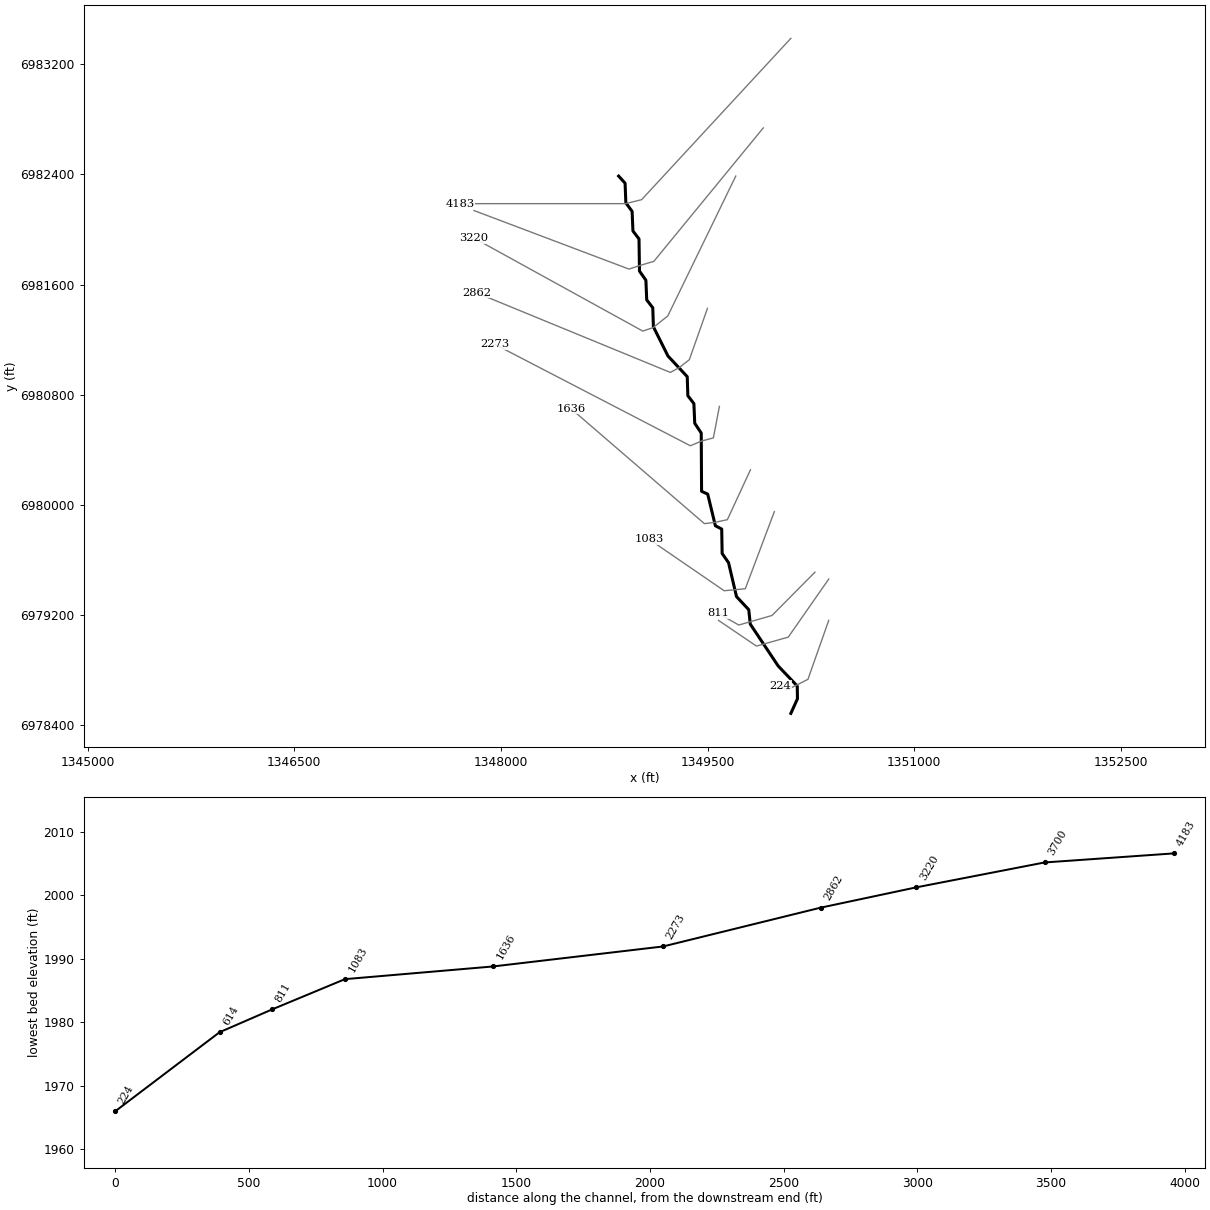
--- UCFB HW Trib 07-01.prj (project) ---

Proj Title=UCFB HW Trib 07-01 Base Level Engineering
Current Plan=p01
Default Exp/Contr=0.3,0.1
English Units
Geom File=g01
Flow File=f01
Plan File=p01
BEGIN DESCRIPTION:
UCFB HW Trib 07-01
END DESCRIPTION:

--- UCFB HW Trib 07-01.p01 (plan) ---

Plan Title=Multiple Run
Short Identifier=Multiple
Geom File=g01
Flow File=f01
Subcritical Flow
K Sum by GR= 0
Std Step Tol= 0.01
Critical Tol= 0.01
Num of Std Step Trials= 20
Max Error Tol= 0.3
Flow Tol Ratio= 0.001
Split Flow NTrial= 30
Split Flow Tol= 0.02
Split Flow Ratio= 0.02
Log Output Level= 0
Friction Slope Method= 1
Unsteady Friction Slope Method= 2
Unsteady Bridges Friction Slope Method= 1
Parabolic Critical Depth
Global Vel Dist=  1 , 1 , 1
Global Log Level= 0
CheckData=True
Encroach Param= -1, 0, 0, 0
BEGIN DESCRIPTION:
Multiple Run
END DESCRIPTION:

--- UCFB HW Trib 07-01.f01 (steady flow) ---

Flow Title=Multiple
Number of Profiles=7
Profile Names=10-year,25-year,50-year,1pct_min,100-year,1pct_plu,500-year
River Rch & RM= UCFB HW Trib 07-,Reach-1,4183
     307     437     547     340     679    1355    1062
Boundary for River Rch & Prof#=UCFB HW Trib 07-,Reach-1,1
Up Type=0
Dn Type=3
Dn Slope=0.005
Boundary for River Rch & Prof#=UCFB HW Trib 07-,Reach-1,2
Up Type=0
Dn Type=3
Dn Slope=0.005
Boundary for River Rch & Prof#=UCFB HW Trib 07-,Reach-1,3
Up Type=0
Dn Type=3
Dn Slope=0.005
Boundary for River Rch & Prof#=UCFB HW Trib 07-,Reach-1,4
Up Type=0
Dn Type=3
Dn Slope=0.005
Boundary for River Rch & Prof#=UCFB HW Trib 07-,Reach-1,5
Up Type=0
Dn Type=3
Dn Slope=0.005
Boundary for River Rch & Prof#=UCFB HW Trib 07-,Reach-1,6
Up Type=0
Dn Type=3
Dn Slope=0.005
Boundary for River Rch & Prof#=UCFB HW Trib 07-,Reach-1,7
Up Type=0
Dn Type=3
Dn Slope=0.005

--- UCFB HW Trib 07-01.g01 (geometry) ---

Geom Title=Existing Conditions

River Reach=UCFB HW Trib 07-,Reach-1
Reach XY= 30
      1348855.00      6982388.00      1348901.70      6982336.63
      1348907.27      6982193.94      1348952.73      6982132.06
      1348958.79      6981989.57      1349002.74      6981932.06
      1349006.22      6981698.50      1349052.73      6981632.06
      1349058.79      6981489.57      1349102.73      6981432.06
      1349107.25      6981293.93      1349213.14      6981081.94
      1349352.93      6980932.14      1349357.27      6980793.94
      1349401.21      6980736.43      1349407.27      6980593.94
      1349454.48      6980522.78      1349456.96      6980099.97
      1349501.44      6980079.50      1349557.08      6979850.02
      1349603.04      6979826.03      1349606.22      6979648.51
      1349652.64      6979582.02      1349710.54      6979335.58
      1349799.46      6979240.42      1349810.54      6979135.58
      1350013.16      6978831.95      1350151.54      6978686.51
      1350152.98      6978593.92      1350105.00      6978488.00

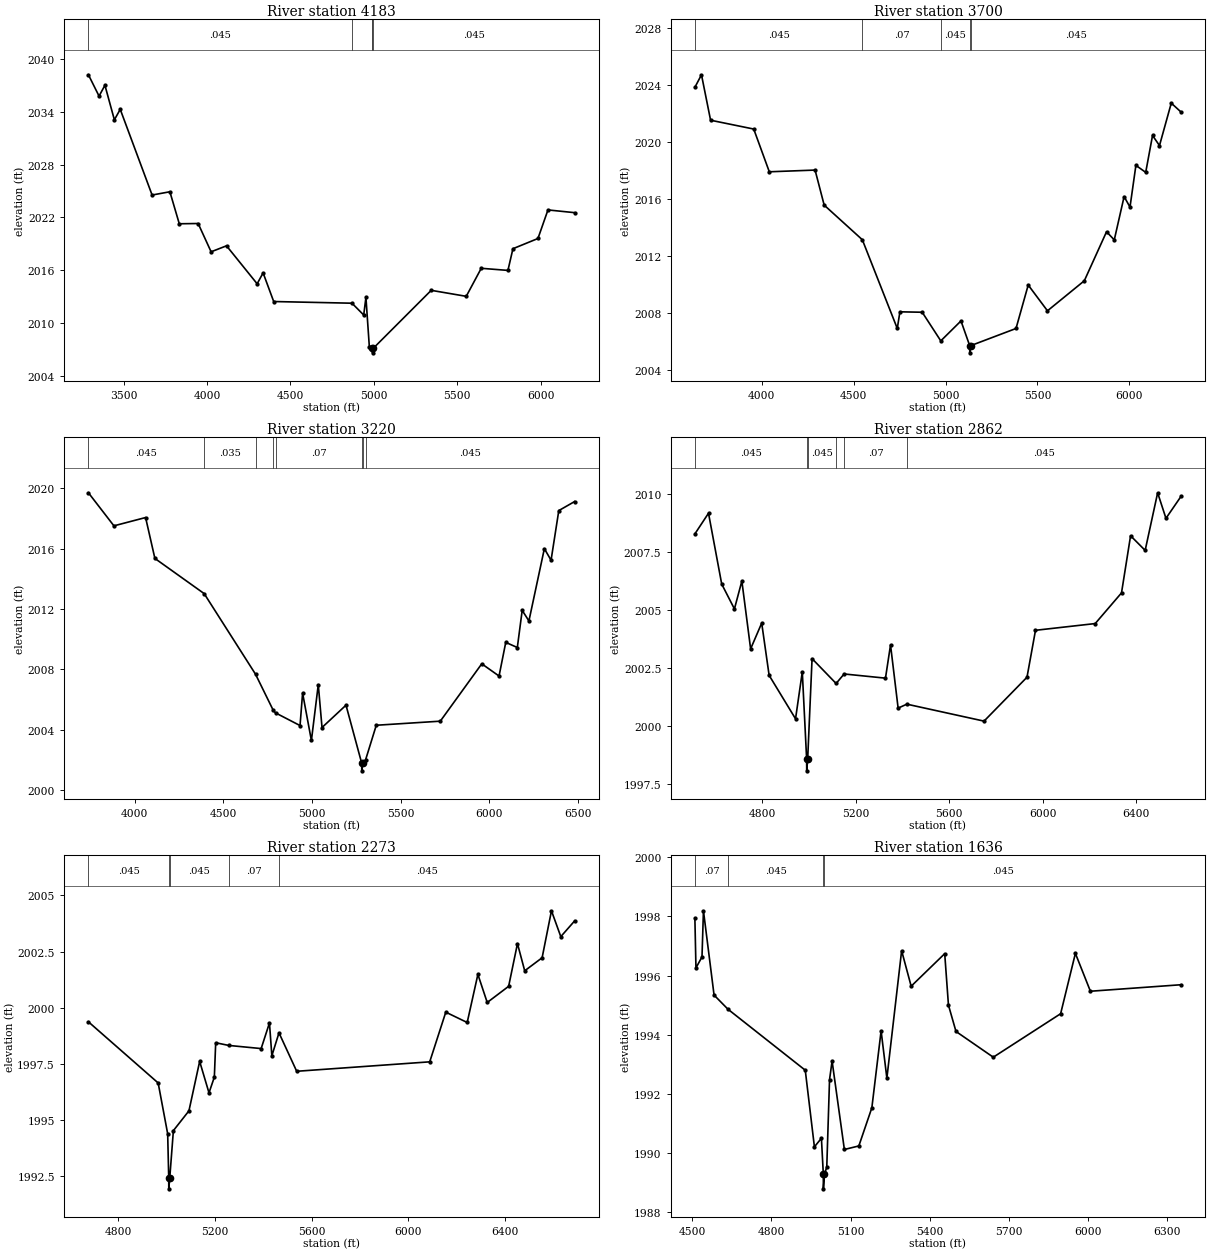
Type RM Length L Ch R = 1,4183,483,483,483
BEGIN DESCRIPTION:
UCFB HW Trib 07-01 3.0
END DESCRIPTION:
XS GIS Cut Line= 4
      1350105.01      6983388.01      1349021.71      6982216.82
      1348905.00      6982188.00      1347704.99      6982188.00
#Sta/Elev= 30
  3288.6 2038.18  3352.4 2035.76  3387.6 2036.99  3444.3 2033.07  3479.4 2034.26
  3670.5 2024.54  3777.1 2024.91  3833.5 2021.28  3946.6 2021.31  4024.3 2018.10
  4116.7 2018.78  4300.4 2014.47  4336.1 2015.71  4399.6 2012.46  4869.0 2012.27
  4939.4 2010.93  4952.7 2012.93  4973.3 2007.28  4987.5 2007.18  4991.9 2007.14
  4992.1 2006.64  4995.9 2007.14  5344.2 2013.73  5554.2 2013.05  5644.2 2016.23
  5804.2 2015.99  5834.2 2018.45  5984.2 2019.61  6044.2 2022.85  6204.2 2022.54
#Mann=5,-1,0
  3288.6   0.045       0  4869.0    0.07       0  4987.5   0.045       0
  4991.9   0.045       0  4995.9   0.045       0
Bank Sta=4991.9,4995.9
Exp/Cntr=0.3,0.1

Type RM Length L Ch R = 1,3700,480,480,480
BEGIN DESCRIPTION:
UCFB HW Trib 07-01 2.0
END DESCRIPTION:
XS GIS Cut Line= 5
      1349905.00      6982738.00      1349110.25      6981768.90
      1349005.00      6981738.00      1348930.00      6981713.00
      1347804.96      6982138.02
#Sta/Elev= 30
  3636.6 2023.85  3672.5 2024.73  3722.0 2021.54  3956.7 2020.92  4041.4 2017.92
  4290.4 2018.04  4339.9 2015.58  4547.4 2013.15  4737.5 2006.92  4751.8 2008.09
  4873.1 2008.06  4974.2 2006.05  5084.0 2007.45  5131.5 2005.71  5131.8 2005.21
  5135.9 2005.71  5383.3 2006.92  5449.7 2009.97  5554.4 2008.16  5754.9 2010.27
  5875.7 2013.71  5917.8 2013.14  5971.3 2016.18  6003.3 2015.44  6035.4 2018.37
  6088.8 2017.88  6125.9 2020.47  6163.7 2019.76  6227.8 2022.74  6281.3 2022.11
#Mann=5,-1,0
  3636.6   0.045       0  4547.4    0.07       0  4974.2   0.045       0
  5131.5   0.045       0  5135.9   0.045       0
Bank Sta=5131.5,5135.9
Exp/Cntr=0.3,0.1

Type RM Length L Ch R = 1,3220,358,358,358
BEGIN DESCRIPTION:
UCFB HW Trib 07-01 1.0
END DESCRIPTION:
XS GIS Cut Line= 5
      1349705.02      6982388.04      1349211.81      6981373.07
      1349105.00      6981288.00      1349030.00      6981263.00
      1347805.02      6981937.99
#Sta/Elev= 30
  3739.3 2019.70  3883.2 2017.51  4061.8 2018.06  4114.3 2015.35  4392.3 2013.02
  4682.0 2007.68  4782.3 2005.28  4794.7 2005.12  4933.0 2004.28  4947.5 2006.43
  4997.1 2003.29  5035.9 2006.99  5057.0 2004.15  5192.3 2005.63  5281.0 2001.78
  5281.3 2001.28  5285.4 2001.78  5302.8 2002.01  5363.1 2004.30  5724.2 2004.57
  5958.1 2008.37  6055.6 2007.56  6093.4 2009.79  6158.7 2009.45  6186.2 2011.91
  6224.1 2011.21  6311.2 2016.00  6349.0 2015.23  6392.6 2018.52  6482.0 2019.12
#Mann=8,-1,0
  3739.3   0.045       0  4392.3   0.035       0  4682.0    0.07       0
  4782.3   0.045       0  4794.7    0.07       0  5281.0    0.07       0
  5285.4    0.07       0  5302.8   0.045       0
Bank Sta=5281,5285.4
Exp/Cntr=0.3,0.1

Type RM Length L Ch R = 1,2862,589,589,589
BEGIN DESCRIPTION:
UCFB HW Trib 07-01 0.9
END DESCRIPTION:
XS GIS Cut Line= 5
      1349499.56      6981427.56      1349368.06      6981055.36
      1349295.12      6980998.05      1349230.00      6980963.00
      1347825.05      6981540.33
#Sta/Elev= 30
  4512.5 2008.27  4570.8 2009.16  4627.3 2006.11  4681.7 2005.04  4713.5 2006.24
  4751.0 2003.32  4798.4 2004.43  4830.2 2002.18  4943.2 2000.31  4972.1 2002.33
  4990.7 1998.57  4991.0 1998.07  4995.1 1998.57  5013.9 2002.90  5116.8 2001.83
  5151.0 2002.24  5328.0 2002.06  5349.6 2003.49  5382.1 2000.77  5419.4 2000.94
  5749.7 2000.21  5933.5 2002.10  5969.9 2004.12  6225.4 2004.41  6337.9 2005.73
  6376.7 2008.19  6439.1 2007.56  6492.5 2010.04  6528.1 2008.94  6592.9 2009.89
#Mann=6,-1,0
  4512.5   0.045       0  4990.7    0.07       0  4995.1   0.045       0
  5116.8    0.16       0  5151.0    0.07       0  5419.4   0.045       0
Bank Sta=4990.7,4995.1
Exp/Cntr=0.3,0.1

Type RM Length L Ch R = 1,2273,637,637,637
BEGIN DESCRIPTION:
UCFB HW Trib 07-01 0.8
END DESCRIPTION:
XS GIS Cut Line= 5
      1349586.31      6980716.13      1349542.54      6980487.65
      1349455.22      6980464.40      1349375.88      6980430.36
      1347955.25      6981167.24
#Sta/Elev= 30
  4677.0 1999.38  4965.3 1996.66  5004.6 1994.40  5008.9 1992.45  5009.2 1991.95
  5013.3 1992.45  5028.2 1994.54  5092.5 1995.42  5136.8 1997.62  5175.4 1996.22
  5197.5 1996.92  5203.1 1998.45  5256.8 1998.33  5391.0 1998.19  5425.3 1999.33
  5435.2 1997.87  5464.7 1998.89  5537.9 1997.18  6087.7 1997.60  6154.1 1999.81
  6242.6 1999.35  6286.8 2001.49  6325.4 2000.24  6413.9 2000.96  6450.4 2002.86
  6480.3 2001.65  6552.3 2002.23  6590.9 2004.32  6629.5 2003.17  6686.7 2003.87
#Mann=5,-1,0
  4677.0   0.045       0  5008.9   0.045       0  5013.3   0.045       0
  5256.8    0.07       0  5464.7   0.045       0
Bank Sta=5008.9,5013.3
Exp/Cntr=0.3,0.1

Type RM Length L Ch R = 1,1636,553,553,553
BEGIN DESCRIPTION:
UCFB HW Trib 07-01 0.7
END DESCRIPTION:
XS GIS Cut Line= 5
      1349811.89      6980256.31      1349644.11      6979893.90
      1349551.60      6979874.54      1349477.44      6979865.26
      1348510.50      6980698.74
#Sta/Elev= 30
  4509.4 1997.94  4513.5 1996.26  4536.4 1996.63  4541.9 1998.19  4582.2 1995.34
  4635.2 1994.86  4928.3 1992.80  4963.0 1990.21  4989.6 1990.50  4996.8 1989.29
  4997.1 1988.79  5001.2 1989.29  5009.9 1989.52  5020.4 1992.48  5030.1 1993.11
  5076.7 1990.12  5131.6 1990.24  5181.0 1991.53  5216.1 1994.13  5238.0 1992.53
  5294.0 1996.84  5330.2 1995.64  5457.5 1996.74  5471.7 1995.00  5500.3 1994.11
  5641.8 1993.24  5897.4 1994.71  5953.4 1996.75  6010.4 1995.47  6354.6 1995.69
#Mann=4,-1,0
  4509.4    0.07       0  4635.2   0.045       0  4996.8   0.045       0
  5001.2   0.045       0
Bank Sta=4996.8,5001.2
Exp/Cntr=0.3,0.1

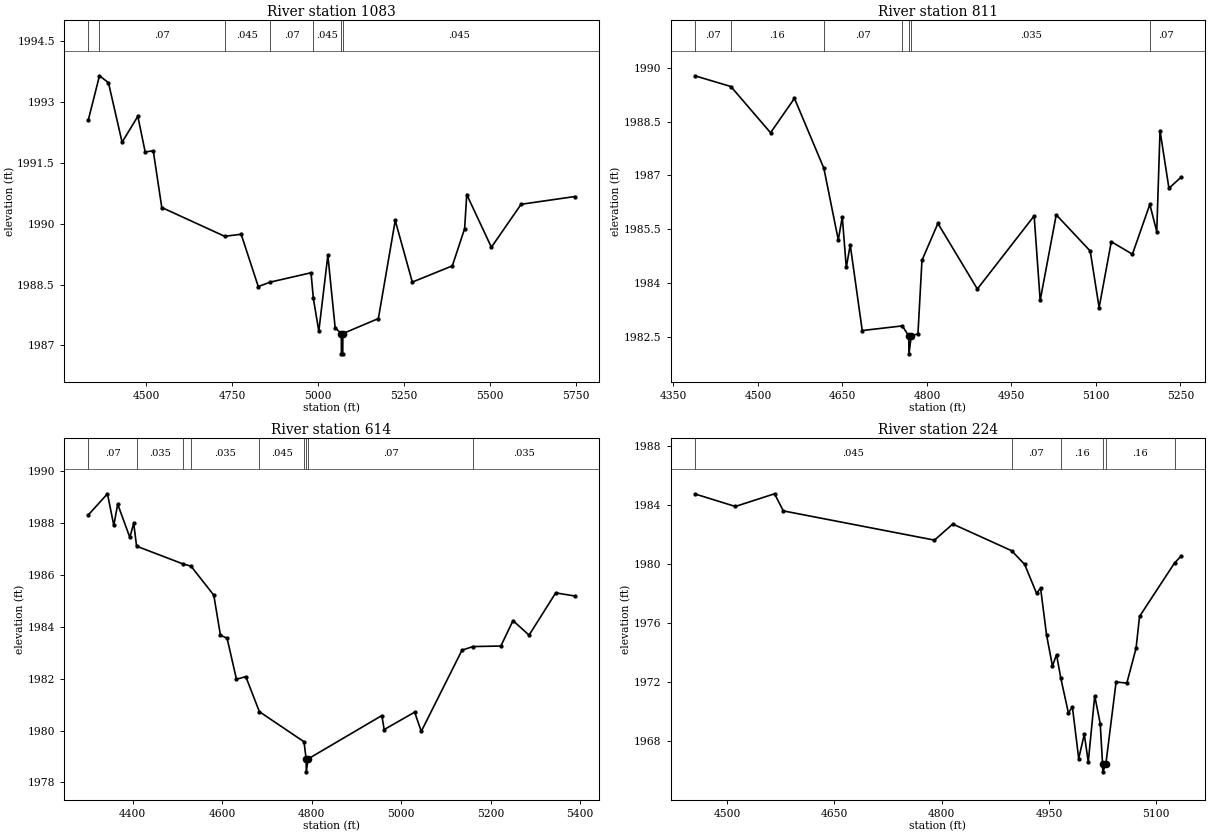
Type RM Length L Ch R = 1,1083,272,272,272
BEGIN DESCRIPTION:
UCFB HW Trib 07-01 0.6
END DESCRIPTION:
XS GIS Cut Line= 5
      1349985.38      6979952.59      1349774.49      6979392.90
      1349704.94      6979385.94      1349620.67      6979378.28
      1349074.49      6979753.03
#Sta/Elev= 30
  4332.0 1992.57  4364.2 1993.65  4390.3 1993.48  4430.0 1992.01  4475.8 1992.65
  4497.2 1991.77  4520.7 1991.80  4545.5 1990.40  4728.5 1989.69  4776.5 1989.74
  4826.3 1988.45  4861.4 1988.56  4979.8 1988.79  4986.6 1988.16  5002.5 1987.35
  5028.8 1989.22  5050.1 1987.43  5068.0 1987.29  5068.3 1986.79  5072.1 1986.79
  5072.5 1987.29  5175.8 1987.66  5224.9 1990.08  5274.6 1988.56  5391.0 1988.96
  5426.9 1989.88  5433.0 1990.72  5504.7 1989.42  5591.3 1990.48  5747.0 1990.67
#Mann=7,-1,0
  4332.0   0.045       0  4364.2    0.07       0  4728.5   0.045       0
  4861.4    0.07       0  4986.6   0.045       0  5068.0   0.045       0
  5072.5   0.045       0
Bank Sta=5068,5072.5
Exp/Cntr=0.3,0.1

Type RM Length L Ch R = 1,811,197,197,197
BEGIN DESCRIPTION:
UCFB HW Trib 07-01 0.5
END DESCRIPTION:
XS GIS Cut Line= 4
      1350279.97      6979512.97      1349968.24      6979198.67
      1349726.92      6979129.22      1349580.01      6979212.99
#Sta/Elev= 30
  4388.2 1989.78  4452.1 1989.48  4522.5 1988.19  4564.9 1989.15  4617.1 1987.20
  4642.7 1985.20  4649.8 1985.84  4656.9 1984.43  4663.9 1985.06  4685.2 1982.67
  4756.3 1982.80  4767.8 1982.52  4768.1 1982.02  4772.3 1982.52  4784.1 1982.58
  4791.2 1984.63  4819.5 1985.66  4889.5 1983.83  4990.3 1985.87  5001.0 1983.51
  5029.5 1985.90  5089.8 1984.89  5105.6 1983.31  5127.2 1985.15  5164.7 1984.80
  5195.6 1986.19  5207.9 1985.43  5213.7 1988.25  5229.5 1986.64  5251.1 1986.95
#Mann=7,-1,0
  4388.2    0.07       0  4452.1    0.16       0  4617.1    0.07       0
  4756.3   0.035       0  4767.8   0.035       0  4772.3   0.035       0
  5195.6    0.07       0
Bank Sta=4767.8,4772.3
Exp/Cntr=0.3,0.1

Type RM Length L Ch R = 1,614,390,390,390
BEGIN DESCRIPTION:
UCFB HW Trib 07-01 0.4
END DESCRIPTION:
XS GIS Cut Line= 4
      1350379.99      6979462.99      1350086.29      6979041.55
      1349855.39      6978976.45      1349580.02      6979162.99
#Sta/Elev= 30
  4301.5 1988.32  4344.1 1989.13  4358.2 1987.91  4366.9 1988.73  4394.0 1987.45
  4402.7 1987.99  4409.1 1987.11  4512.1 1986.43  4530.7 1986.34  4581.6 1985.22
  4596.4 1983.68  4611.3 1983.56  4632.2 1981.98  4653.1 1982.08  4683.4 1980.73
  4783.1 1979.57  4787.9 1978.91  4788.2 1978.41  4792.4 1978.91  4957.0 1980.58
  4962.2 1980.04  5030.2 1980.71  5045.1 1979.97  5136.1 1983.10  5160.5 1983.24
  5222.9 1983.26  5250.0 1984.24  5285.9 1983.68  5345.4 1985.31  5387.7 1985.19
#Mann=9,-1,0
  4301.5    0.07       0  4409.1   0.035       0  4512.1    0.16       0
  4530.7   0.035       0  4683.4   0.045       0  4783.1    0.07       0
  4787.9    0.07       0  4792.4    0.07       0  5160.5   0.035       0
Bank Sta=4787.9,4792.4
Exp/Cntr=0.3,0.1

Type RM Length L Ch R = 1,224,0,0,0
BEGIN DESCRIPTION:
UCFB HW Trib 07-01 0.3
END DESCRIPTION:
XS GIS Cut Line= 4
      1350380.00      6979163.00      1350229.06      6978735.26
      1350078.25      6978658.49      1350030.02      6978689.03
#Sta/Elev= 30
  4454.9 1984.77  4511.5 1983.92  4566.3 1984.78  4578.6 1983.62  4789.9 1981.64
  4815.5 1982.73  4897.9 1980.92  4916.1 1979.99  4932.7 1978.03  4938.3 1978.39
  4946.7 1975.20  4954.9 1973.11  4960.6 1973.88  4966.6 1972.28  4977.2 1969.93
  4982.8 1970.34  4991.6 1966.84  4999.4 1968.48  5005.0 1966.62  5014.0 1971.09
  5021.7 1969.21  5025.0 1966.44  5025.3 1965.94  5029.5 1966.44  5043.9 1972.03
  5058.9 1971.95  5071.8 1974.31  5076.7 1976.47  5125.6 1980.09  5134.8 1980.56
#Mann=6,-1,0
  4454.9   0.045       0  4897.9    0.07       0  4966.6    0.16       0
  5025.0    0.07       0  5029.5    0.16       0  5125.6    0.07       0
Bank Sta=5025,5029.5
Exp/Cntr=0.3,0.1

Chan Stop Cuts=-1