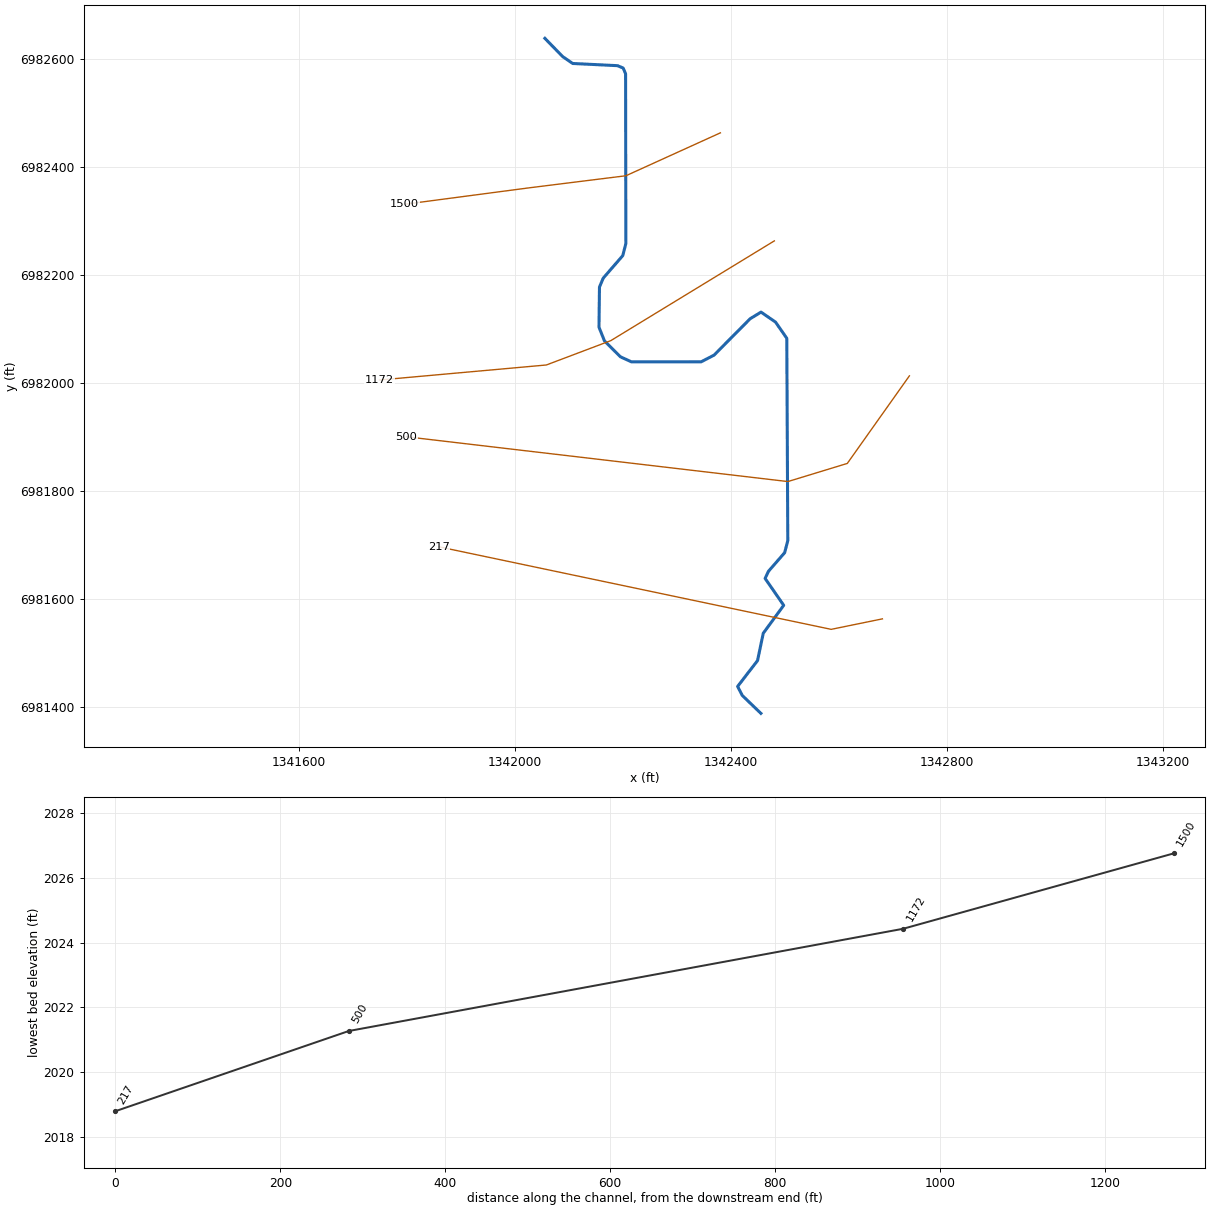
--- UCFB HW Trib 07-02.prj (project) ---

Proj Title=UCFB HW Trib 07-02 Base Level Engineering
Current Plan=p01
Default Exp/Contr=0.3,0.1
English Units
Geom File=g01
Flow File=f01
Plan File=p01
BEGIN DESCRIPTION:
UCFB HW Trib 07-02
END DESCRIPTION:

--- UCFB HW Trib 07-02.p01 (plan) ---

Plan Title=Multiple Run
Short Identifier=Multiple
Geom File=g01
Flow File=f01
Subcritical Flow
K Sum by GR= 0
Std Step Tol= 0.01
Critical Tol= 0.01
Num of Std Step Trials= 20
Max Error Tol= 0.3
Flow Tol Ratio= 0.001
Split Flow NTrial= 30
Split Flow Tol= 0.02
Split Flow Ratio= 0.02
Log Output Level= 0
Friction Slope Method= 1
Unsteady Friction Slope Method= 2
Unsteady Bridges Friction Slope Method= 1
Parabolic Critical Depth
Global Vel Dist=  1 , 1 , 1
Global Log Level= 0
CheckData=True
Encroach Param= -1, 0, 0, 0
BEGIN DESCRIPTION:
Multiple Run
END DESCRIPTION:

--- UCFB HW Trib 07-02.f01 (steady flow) ---

Flow Title=Multiple
Number of Profiles=7
Profile Names=10-year,25-year,50-year,1pct_min,100-year,1pct_plu,500-year
River Rch & RM= UCFB HW Trib 07-,Reach-1,1500
     304     433     543     338     675    1347    1058
Boundary for River Rch & Prof#=UCFB HW Trib 07-,Reach-1,1
Up Type=0
Dn Type=3
Dn Slope=0.005
Boundary for River Rch & Prof#=UCFB HW Trib 07-,Reach-1,2
Up Type=0
Dn Type=3
Dn Slope=0.005
Boundary for River Rch & Prof#=UCFB HW Trib 07-,Reach-1,3
Up Type=0
Dn Type=3
Dn Slope=0.005
Boundary for River Rch & Prof#=UCFB HW Trib 07-,Reach-1,4
Up Type=0
Dn Type=3
Dn Slope=0.005
Boundary for River Rch & Prof#=UCFB HW Trib 07-,Reach-1,5
Up Type=0
Dn Type=3
Dn Slope=0.005
Boundary for River Rch & Prof#=UCFB HW Trib 07-,Reach-1,6
Up Type=0
Dn Type=3
Dn Slope=0.005
Boundary for River Rch & Prof#=UCFB HW Trib 07-,Reach-1,7
Up Type=0
Dn Type=3
Dn Slope=0.005

--- UCFB HW Trib 07-02.g01 (geometry) ---

Geom Title=Existing Conditions

River Reach=UCFB HW Trib 07-,Reach-1
Reach XY= 30
      1342055.00      6982638.00      1342088.00      6982604.14
      1342106.51      6982591.44      1342189.46      6982587.39
      1342200.00      6982582.96      1342204.46      6982572.44
      1342204.93      6982258.03      1342199.25      6982235.66
      1342163.09      6982194.03      1342156.10      6982177.44
      1342155.18      6982103.07      1342165.28      6982077.84
      1342194.82      6982048.32      1342215.27      6982038.96
      1342344.56      6982039.05      1342368.32      6982051.43
      1342435.10      6982118.78      1342455.25      6982131.02
      1342482.14      6982112.53      1342502.94      6982082.56
      1342504.82      6981707.98      1342499.00      6981685.55
      1342469.07      6981651.16      1342462.80      6981637.90
      1342497.24      6981588.08      1342459.38      6981536.36
      1342448.76      6981485.69      1342411.87      6981437.88
      1342420.53      6981421.17      1342455.00      6981388.00

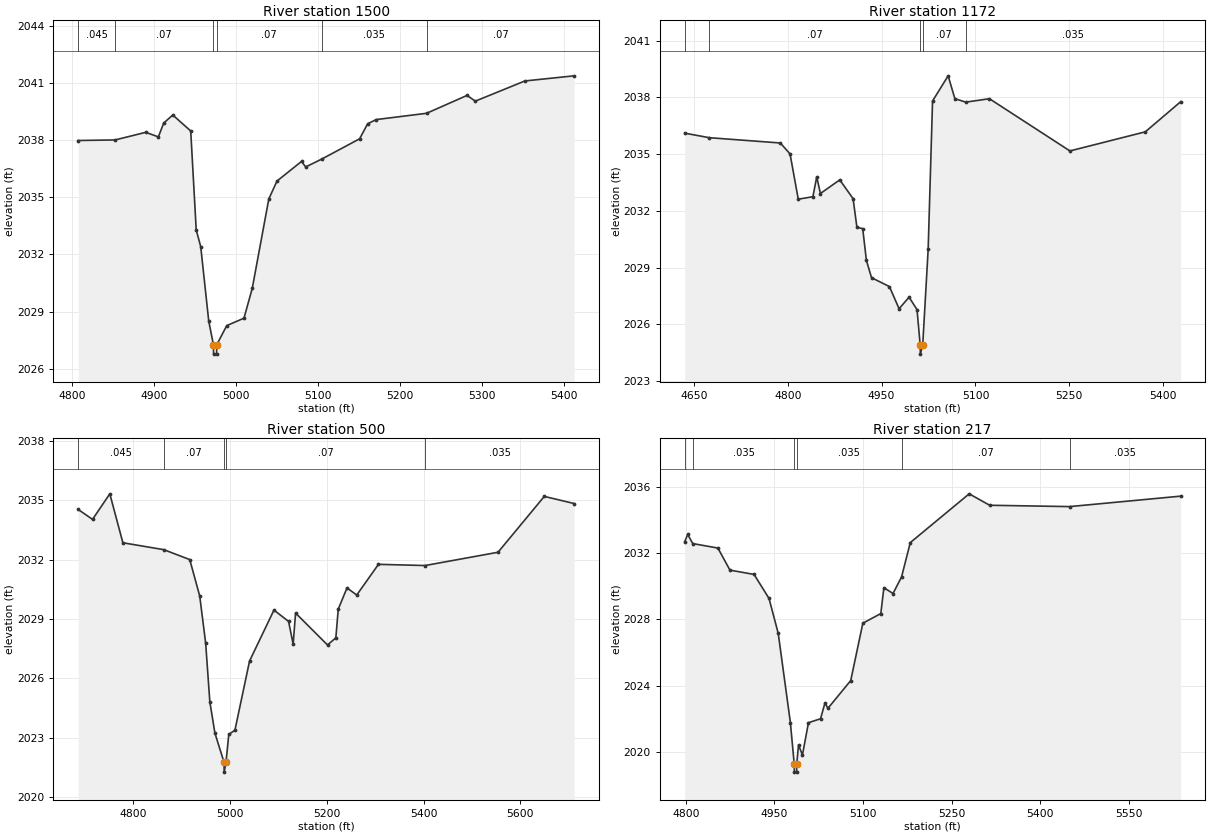
Type RM Length L Ch R = 1,1500,328,328,328
BEGIN DESCRIPTION:
UCFB HW Trib 07-02 2.0
END DESCRIPTION:
XS GIS Cut Line= 4
      1342380.04      6982463.02      1342205.04      6982383.52
      1342026.47      6982361.25      1341795.44      6982330.73
#Sta/Elev= 30
  4807.8 2037.99  4852.9 2038.02  4890.2 2038.42  4905.6 2038.18  4912.2 2038.91
  4923.2 2039.33  4945.1 2038.49  4951.8 2033.29  4957.3 2032.41  4967.1 2028.49
  4972.8 2027.26  4973.0 2026.76  4976.6 2026.76  4976.9 2027.26  4989.1 2028.26
  5010.1 2028.65  5020.2 2030.22  5040.4 2034.92  5050.4 2035.86  5080.3 2036.89
  5085.4 2036.60  5104.8 2037.01  5151.2 2038.08  5161.0 2038.87  5171.4 2039.09
  5232.9 2039.42  5282.3 2040.36  5292.4 2040.06  5352.9 2041.12  5413.0 2041.39
#Mann=6,-1,0
  4807.8   0.045       0  4852.9    0.07       0  4972.8    0.07       0
  4976.9    0.07       0  5104.8   0.035       0  5232.9    0.07       0
Bank Sta=4972.8,4976.9
Exp/Cntr=0.3,0.1

Type RM Length L Ch R = 1,1172,672,672,672
BEGIN DESCRIPTION:
UCFB HW Trib 07-02 1.5
END DESCRIPTION:
XS GIS Cut Line= 4
      1342479.96      6982262.98      1342177.07      6982078.22
      1342057.72      6982033.13      1341748.84      6982005.31
#Sta/Elev= 30
  4635.3 2036.11  4674.7 2035.87  4788.2 2035.59  4803.7 2035.01  4816.8 2032.62
  4840.2 2032.75  4846.3 2033.80  4852.2 2032.92  4883.1 2033.64  4904.4 2032.65
  4910.5 2031.14  4919.8 2031.06  4925.7 2029.38  4933.9 2028.47  4962.5 2028.00
  4977.9 2026.83  4993.9 2027.44  5006.6 2026.78  5011.6 2024.93  5011.9 2024.43
  5015.7 2024.93  5024.4 2029.98  5031.4 2037.81  5056.3 2039.14  5067.1 2037.93
  5084.6 2037.75  5122.3 2037.93  5250.9 2035.17  5371.4 2036.18  5427.8 2037.77
#Mann=5,-1,0
  4635.3   0.045       0  4674.7    0.07       0  5011.6    0.07       0
  5015.7    0.07       0  5084.6   0.035       0
Bank Sta=5011.6,5015.7
Exp/Cntr=0.3,0.1

Type RM Length L Ch R = 1,500,283,283,283
BEGIN DESCRIPTION:
UCFB HW Trib 07-02 1.0
END DESCRIPTION:
XS GIS Cut Line= 5
      1342730.02      6982013.02      1342615.01      6981850.84
      1342505.04      6981817.27      1342329.47      6981837.89
      1341798.79      6981900.20
#Sta/Elev= 30
  4686.2 2034.53  4715.8 2034.03  4751.5 2035.32  4778.5 2032.85  4863.2 2032.50
  4916.7 2032.00  4937.3 2030.16  4949.6 2027.78  4958.2 2024.82  4968.7 2023.24
  4987.5 2021.77  4987.8 2021.27  4991.6 2021.77  4997.4 2023.17  5010.1 2023.39
  5040.3 2026.88  5090.7 2029.45  5120.9 2028.88  5130.4 2027.73  5135.4 2029.30
  5201.4 2027.69  5218.6 2028.05  5223.6 2029.50  5241.7 2030.57  5261.8 2030.21
  5306.7 2031.76  5402.9 2031.70  5553.8 2032.37  5649.4 2035.19  5711.1 2034.83
#Mann=5,-1,0
  4686.2   0.045       0  4863.2    0.07       0  4987.5    0.07       0
  4991.6    0.07       0  5402.9   0.035       0
Bank Sta=4987.5,4991.6
Exp/Cntr=0.3,0.1

Type RM Length L Ch R = 1,217,0,0,0
BEGIN DESCRIPTION:
UCFB HW Trib 07-02 0.5
END DESCRIPTION:
XS GIS Cut Line= 3
      1342680.04      6981563.01      1342585.18      6981543.60
      1341858.91      6981696.41
#Sta/Elev= 30
  4798.2 2032.68  4803.3 2033.12  4811.9 2032.57  4854.4 2032.30  4874.8 2030.97
  4915.6 2030.71  4940.9 2029.26  4956.5 2027.15  4977.0 2021.78  4983.5 2019.29
  4983.8 2018.79  4987.6 2018.79  4987.8 2019.29  4990.8 2020.43  4997.4 2019.82
  5007.6 2021.77  5028.1 2022.01  5035.5 2022.96  5040.6 2022.64  5079.1 2024.31
  5099.6 2027.77  5130.0 2028.35  5135.2 2029.91  5150.7 2029.56  5165.1 2030.56
  5179.9 2032.63  5279.5 2035.57  5314.2 2034.88  5449.4 2034.80  5637.2 2035.43
#Mann=6,-1,0
  4798.2    0.07       0  4811.9   0.035       0  4983.5   0.035       0
  4987.8   0.035       0  5165.1    0.07       0  5449.4   0.035       0
Bank Sta=4983.5,4987.8
Exp/Cntr=0.3,0.1

Chan Stop Cuts=-1