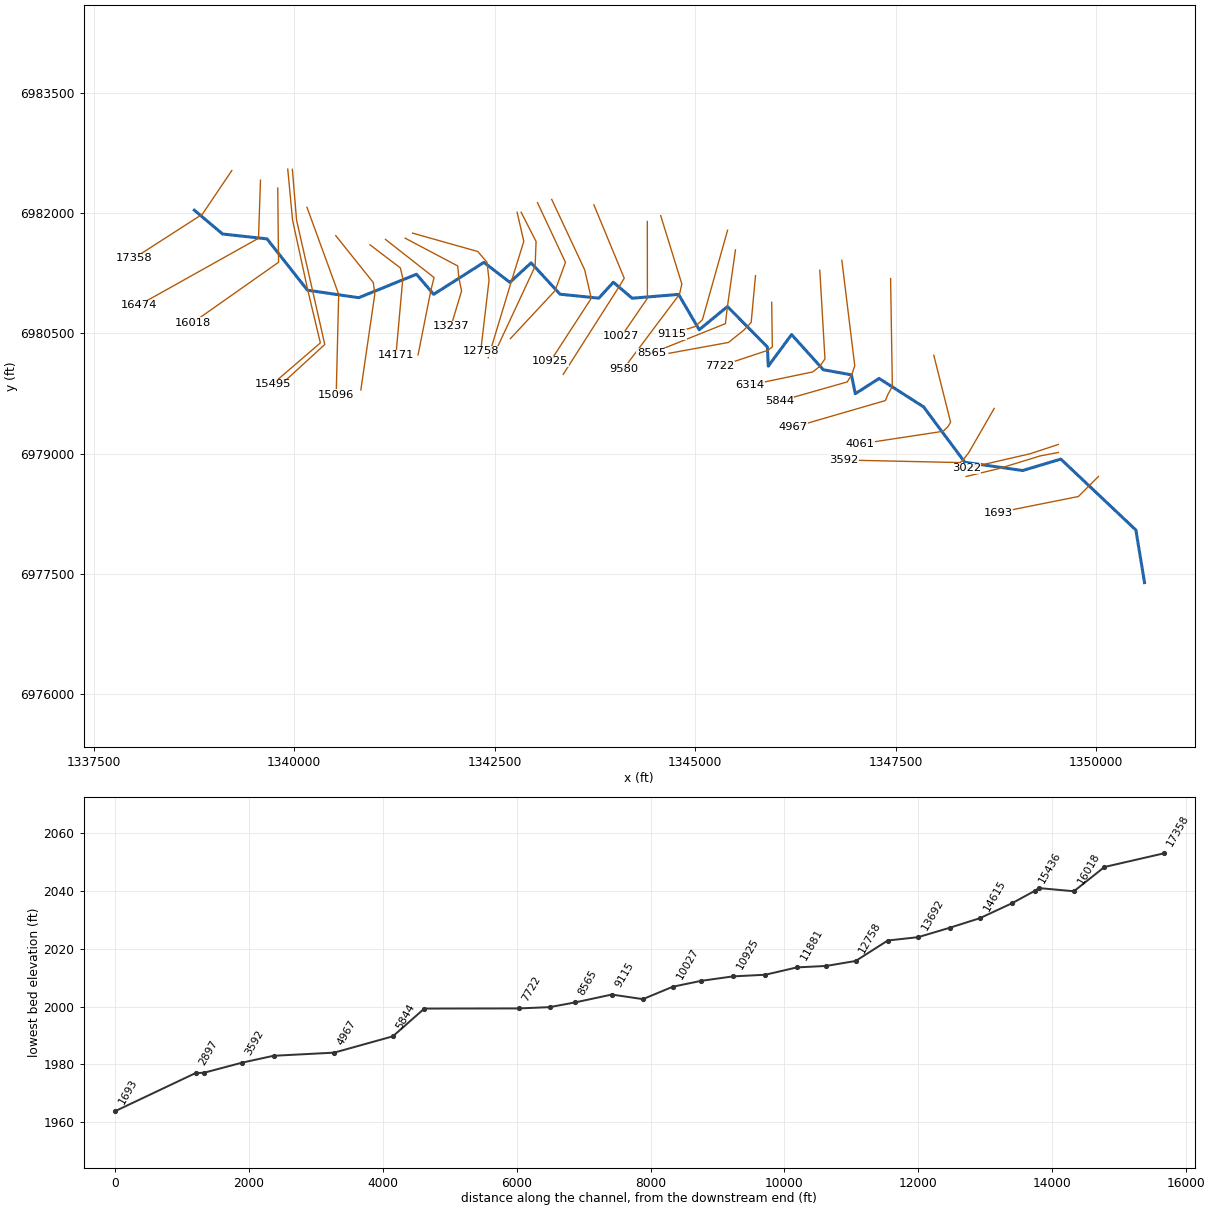
--- UCFB HW Trib 07.prj (project) ---

Proj Title=UCFB HW Trib 07 Base Level Engineering
Current Plan=p01
Default Exp/Contr=0.3,0.1
English Units
Geom File=g01
Flow File=f01
Plan File=p01
BEGIN DESCRIPTION:
UCFB HW Trib 07
END DESCRIPTION:

--- UCFB HW Trib 07.p01 (plan) ---

Plan Title=Multiple Run
Short Identifier=Multiple
Geom File=g01
Flow File=f01
Subcritical Flow
K Sum by GR= 0
Std Step Tol= 0.01
Critical Tol= 0.01
Num of Std Step Trials= 20
Max Error Tol= 0.3
Flow Tol Ratio= 0.001
Split Flow NTrial= 30
Split Flow Tol= 0.02
Split Flow Ratio= 0.02
Log Output Level= 0
Friction Slope Method= 1
Unsteady Friction Slope Method= 2
Unsteady Bridges Friction Slope Method= 1
Parabolic Critical Depth
Global Vel Dist=  1 , 1 , 1
Global Log Level= 0
CheckData=True
Encroach Param= -1, 0, 0, 0
BEGIN DESCRIPTION:
Multiple Run
END DESCRIPTION:

--- UCFB HW Trib 07.f01 (steady flow) ---

Flow Title=Multiple
Number of Profiles=7
Profile Names=10-year,25-year,50-year,1pct_min,100-year,1pct_plu,500-year
River Rch & RM= UCFB HW Trib 07,Reach-1,17358
     311     442     553     344     686    1369    1070
River Rch & RM= UCFB HW Trib 07,Reach-1,12318
     543     793    1008     636    1269    2532    2039
River Rch & RM= UCFB HW Trib 07,Reach-1,1693
     583     853    1088     688    1372    2737    2214
River Rch & RM= UCFB HW Trib 07,Reach-1,1166
     744    1103    1417     902    1800    3591    2946
Boundary for River Rch & Prof#=UCFB HW Trib 07,Reach-1,1
Up Type=0
Dn Type=3
Dn Slope=0.005
Boundary for River Rch & Prof#=UCFB HW Trib 07,Reach-1,2
Up Type=0
Dn Type=3
Dn Slope=0.005
Boundary for River Rch & Prof#=UCFB HW Trib 07,Reach-1,3
Up Type=0
Dn Type=3
Dn Slope=0.005
Boundary for River Rch & Prof#=UCFB HW Trib 07,Reach-1,4
Up Type=0
Dn Type=3
Dn Slope=0.005
Boundary for River Rch & Prof#=UCFB HW Trib 07,Reach-1,5
Up Type=0
Dn Type=3
Dn Slope=0.005
Boundary for River Rch & Prof#=UCFB HW Trib 07,Reach-1,6
Up Type=0
Dn Type=3
Dn Slope=0.005
Boundary for River Rch & Prof#=UCFB HW Trib 07,Reach-1,7
Up Type=0
Dn Type=3
Dn Slope=0.005

--- UCFB HW Trib 07.g01 (geometry) ---

Geom Title=Existing Conditions

River Reach=UCFB HW Trib 07,Reach-1
Reach XY= 30
      1338755.00      6982038.00      1339106.98      6981741.02
      1339661.19      6981680.15      1340165.43      6981039.05
      1340805.00      6980945.56      1341525.08      6981238.67
      1341739.29      6980987.74      1342366.21      6981386.82
      1342689.93      6981137.21      1342954.90      6981380.69
      1343315.50      6980989.20      1343799.33      6980939.98
      1343980.08      6981138.62      1344215.44      6980939.05
      1344793.42      6980986.62      1345051.42      6980545.48
      1345402.99      6980835.05      1345901.65      6980329.90
      1345912.58      6980090.96      1346203.32      6980484.92
      1346598.83      6980045.76      1346949.82      6979982.56
      1346998.00      6979746.82      1347294.56      6979937.18
      1347849.39      6979582.41      1348363.28      6978891.06
      1349084.84      6978787.53      1349561.19      6978930.17
      1350497.14      6978044.19      1350605.00      6977388.00

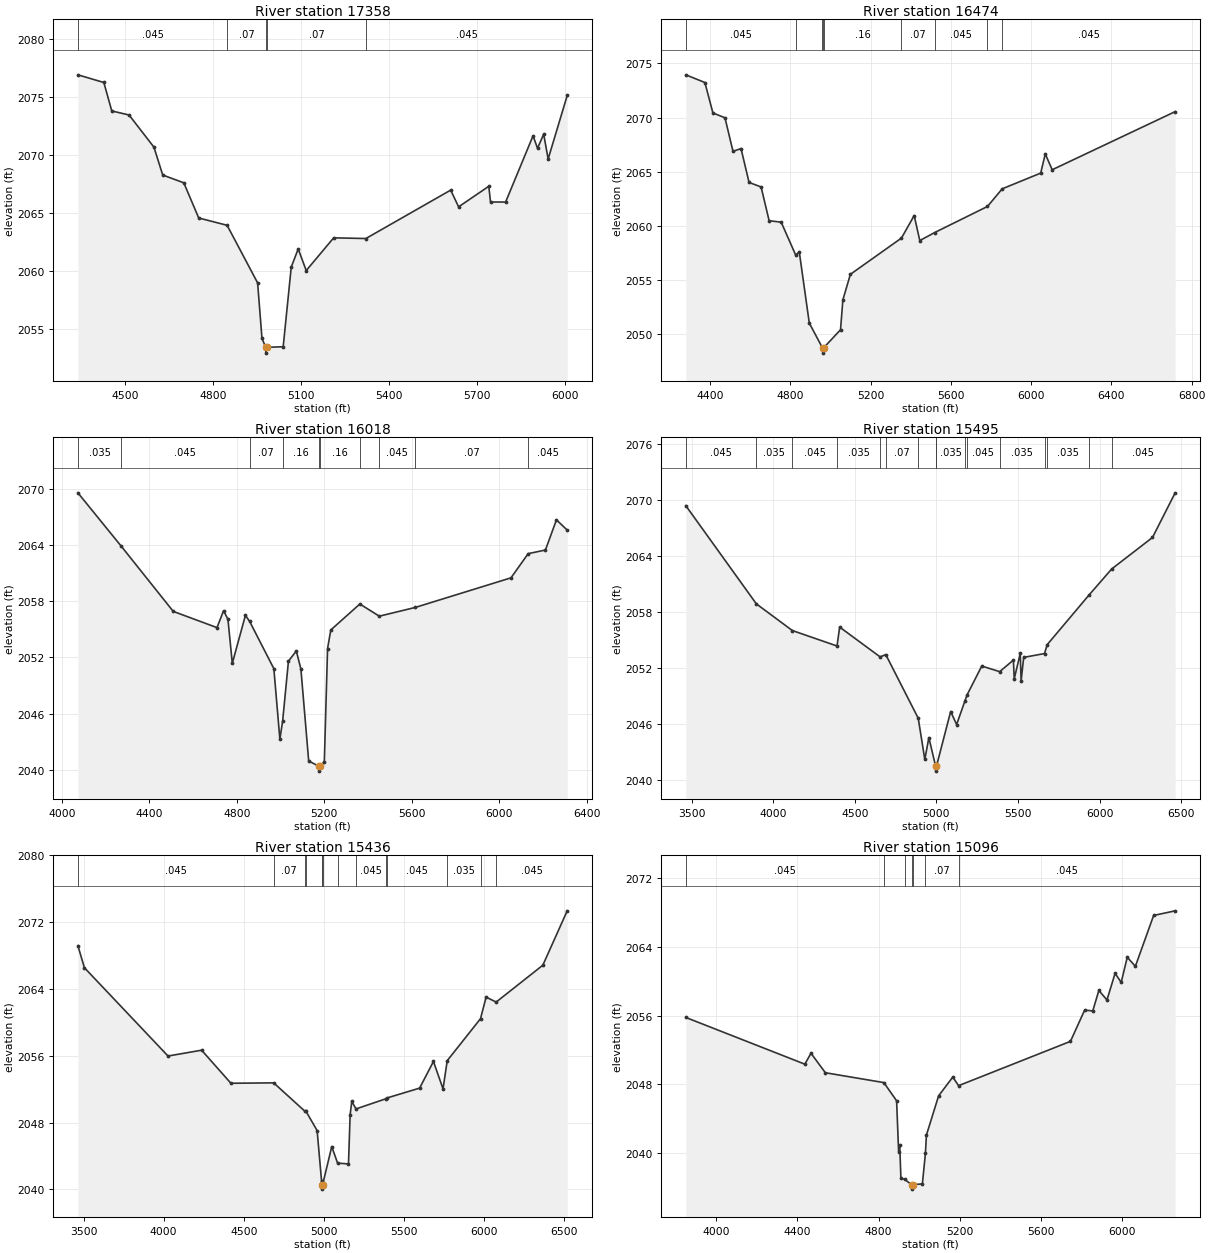
Type RM Length L Ch R = 1,17358,884,884,884
BEGIN DESCRIPTION:
UCFB HW Trib 07 30.0
END DESCRIPTION:
XS GIS Cut Line= 3
      1339221.93      6982532.91      1338855.00      6981988.00
      1338003.15      6981439.12
#Sta/Elev= 30
  4337.8 2076.91  4426.4 2076.25  4453.5 2073.80  4512.5 2073.45  4597.4 2070.68
  4627.4 2068.28  4699.3 2067.61  4750.3 2064.58  4847.2 2063.95  4951.3 2058.99
  4966.2 2054.20  4979.2 2053.44  4979.5 2052.94  4983.2 2053.44  5038.6 2053.49
  5066.1 2060.35  5089.9 2061.92  5117.2 2060.05  5210.9 2062.87  5320.8 2062.81
  5610.3 2066.98  5637.4 2065.54  5740.4 2067.31  5746.3 2065.96  5797.8 2065.95
  5891.5 2071.66  5906.7 2070.58  5927.8 2071.80  5943.0 2069.66  6008.1 2075.13
#Mann=5,-1,0
  4337.8   0.045       0  4847.2    0.07       0  4979.2    0.07       0
  4983.2    0.07       0  5320.8   0.045       0
Bank Sta=4979.2,4983.2
Exp/Cntr=0.3,0.1

Type RM Length L Ch R = 1,16474,456,456,456
BEGIN DESCRIPTION:
UCFB HW Trib 07 29.0
END DESCRIPTION:
XS GIS Cut Line= 3
      1339580.00      6982412.95      1339555.00      6981688.00
      1338060.41      6980850.56
#Sta/Elev= 30
  4279.2 2073.95  4374.2 2073.24  4414.2 2070.43  4474.3 2069.98  4514.3 2066.88
  4554.3 2067.14  4594.3 2064.01  4654.4 2063.59  4694.4 2060.47  4754.4 2060.34
  4827.2 2057.28  4844.5 2057.61  4894.5 2051.02  4958.0 2048.80  4962.6 2048.74
  4962.8 2048.24  4966.6 2048.74  5050.2 2050.40  5061.9 2053.16  5099.3 2055.52
  5353.9 2058.87  5417.2 2060.95  5445.2 2058.64  5519.5 2059.38  5782.5 2061.79
  5856.0 2063.42  6047.7 2064.87  6070.6 2066.64  6105.0 2065.18  6717.8 2070.55
#Mann=9,-1,0
  4279.2   0.045       0  4827.2    0.07       0  4958.0    0.16       0
  4962.6    0.07       0  4966.6    0.16       0  5353.9    0.07       0
  5519.5   0.045       0  5782.5   0.035       0  5856.0   0.045       0
Bank Sta=4962.6,4966.6
Exp/Cntr=0.3,0.1

Type RM Length L Ch R = 1,16018,523,523,523
BEGIN DESCRIPTION:
UCFB HW Trib 07 28.0
END DESCRIPTION:
XS GIS Cut Line= 3
      1339794.82      6982314.07      1339805.00      6981388.00
      1338733.18      6980632.43
#Sta/Elev= 30
  4073.6 2069.55  4271.4 2063.87  4509.7 2056.90  4709.7 2055.17  4739.7 2056.97
  4759.7 2056.07  4779.7 2051.36  4839.7 2056.48  4858.5 2055.85  4969.7 2050.79
  4997.2 2043.27  5010.0 2045.23  5036.4 2051.59  5072.4 2052.68  5093.3 2050.76
  5129.0 2040.94  5177.5 2040.36  5177.8 2039.86  5181.6 2040.36  5200.5 2040.87
  5215.3 2052.94  5230.1 2054.92  5362.9 2057.69  5451.8 2056.39  5615.9 2057.32
  6053.9 2060.48  6132.6 2063.06  6211.5 2063.45  6262.0 2066.67  6311.1 2065.57
#Mann=10,-1,0
  4073.6   0.035       0  4271.4   0.045       0  4858.5    0.07       0
  5010.0    0.16       0  5177.5    0.07       0  5181.6    0.16       0
  5362.9    0.07       0  5451.8   0.045       0  5615.9    0.07       0
  6132.6   0.045       0
Bank Sta=5177.5,5181.6
Exp/Cntr=0.3,0.1

Type RM Length L Ch R = 1,15495,59,59,59
BEGIN DESCRIPTION:
UCFB HW Trib 07 27.2
END DESCRIPTION:
XS GIS Cut Line= 5
      1339919.81      6982551.29      1339980.00      6981913.00
      1340170.73      6981034.85      1340326.34      6980380.96
      1339730.05      6979866.41
#Sta/Elev= 30
  3463.9 2069.43  3896.3 2058.90  4116.8 2056.04  4390.8 2054.38  4406.9 2056.41
  4655.2 2053.21  4689.5 2053.46  4888.6 2046.63  4928.8 2042.21  4953.7 2044.55
  4995.5 2041.46  4995.8 2040.96  4999.9 2041.46  5087.3 2047.35  5123.8 2045.96
  5175.5 2048.52  5188.6 2049.16  5277.9 2052.23  5387.8 2051.63  5471.9 2052.87
  5477.0 2050.87  5514.0 2053.58  5519.2 2050.62  5534.9 2053.16  5662.6 2053.57
  5679.3 2054.53  5934.5 2059.83  6074.2 2062.64  6324.5 2066.02  6463.4 2070.81
#Mann=16,-1,0
  3463.9   0.045       0  3896.3   0.035       0  4116.8   0.045       0
  4390.8   0.035       0  4655.2   0.045       0  4689.5    0.07       0
  4888.6   0.035       0  4995.5   0.035       0  4999.9   0.035       0
  5175.5    0.07       0  5188.6   0.045       0  5387.8   0.035       0
  5662.6   0.045       0  5679.3   0.035       0  5934.5    0.07       0
  6074.2   0.045       0
Bank Sta=4995.5,4999.9
Exp/Cntr=0.3,0.1

Type RM Length L Ch R = 1,15436,340,340,340
BEGIN DESCRIPTION:
UCFB HW Trib 07 27.0
END DESCRIPTION:
XS GIS Cut Line= 4
      1339977.10      6982548.53      1340030.00      6981913.00
      1340381.78      6980361.13      1339773.96      6979803.68
#Sta/Elev= 30
  3464.8 2069.17  3505.5 2066.53  4027.3 2055.96  4237.0 2056.66  4419.8 2052.70
  4686.6 2052.75  4881.7 2049.35  4886.0 2049.42  4957.8 2047.04  4985.7 2040.96
  4987.3 2040.53  4987.6 2040.03  4991.7 2040.53  5049.2 2045.13  5085.5 2043.14
  5153.5 2043.05  5163.8 2048.92  5174.0 2050.53  5200.4 2049.63  5384.6 2050.83
  5395.3 2050.95  5597.4 2052.12  5683.7 2055.31  5743.5 2052.03  5769.8 2055.41
  5977.4 2060.43  6012.4 2063.01  6075.1 2062.42  6366.3 2066.83  6518.5 2073.34
#Mann=14,-1,0
  3464.8   0.045       0  4686.6    0.07       0  4881.7   0.045       0
  4886.0   0.035       0  4985.7    0.16       0  4987.3    0.07       0
  4991.7    0.16       0  5085.5    0.07       0  5200.4   0.045       0
  5384.6   0.035       0  5395.3   0.045       0  5769.8   0.035       0
  5977.4    0.07       0  6075.1   0.045       0
Bank Sta=4987.3,4991.7
Exp/Cntr=0.3,0.1

Type RM Length L Ch R = 1,15096,481,481,481
BEGIN DESCRIPTION:
UCFB HW Trib 07 26.0
END DESCRIPTION:
XS GIS Cut Line= 3
      1340159.38      6982074.58      1340555.00      6980988.00
      1340524.01      6979731.94
#Sta/Elev= 30
  3849.6 2055.78  4436.3 2050.33  4466.9 2051.60  4537.7 2049.33  4826.1 2048.18
  4888.9 2046.06  4898.9 2040.13  4904.3 2040.88  4910.2 2037.00  4929.3 2036.89
  4963.2 2036.25  4963.5 2035.75  4967.7 2036.25  5016.0 2036.37  5031.0 2039.91
  5036.0 2042.06  5096.0 2046.63  5166.0 2048.83  5194.4 2047.82  5746.2 2052.99
  5816.2 2056.64  5856.2 2056.54  5886.2 2058.93  5926.2 2057.82  5966.3 2060.93
  5996.3 2059.87  6026.3 2062.80  6066.3 2061.75  6156.3 2067.68  6262.4 2068.22
#Mann=7,-1,0
  3849.6   0.045       0  4826.1   0.035       0  4929.3    0.16       0
  4963.2    0.07       0  4967.7    0.16       0  5031.0    0.07       0
  5194.4   0.045       0
Bank Sta=4963.2,4967.7
Exp/Cntr=0.3,0.1

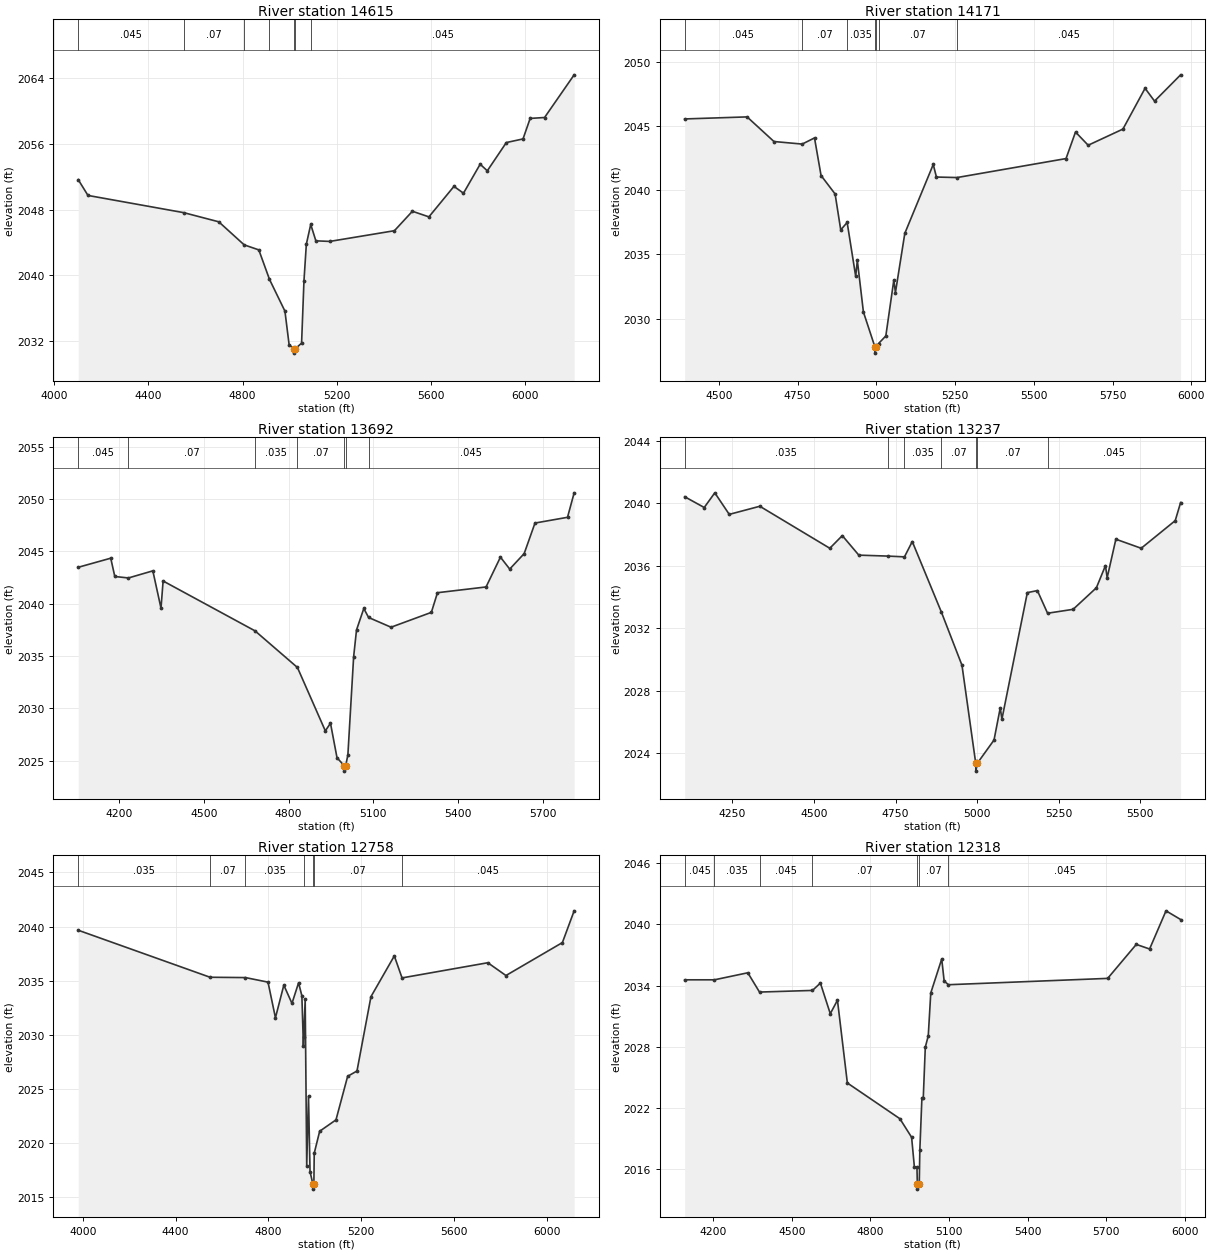
Type RM Length L Ch R = 1,14615,444,444,444
BEGIN DESCRIPTION:
UCFB HW Trib 07 25.0
END DESCRIPTION:
XS GIS Cut Line= 4
      1340518.77      6981720.37      1340987.09      6981133.70
      1341005.00      6980988.00      1340831.27      6979793.24
#Sta/Elev= 30
  4102.1 2051.63  4143.5 2049.71  4550.2 2047.62  4698.6 2046.51  4806.5 2043.71
  4868.6 2043.10  4913.9 2039.52  4979.4 2035.67  4997.1 2031.61  5017.5 2031.07
  5017.8 2030.57  5022.0 2031.07  5050.1 2031.78  5060.2 2039.34  5070.3 2043.79
  5088.9 2046.19  5110.7 2044.20  5169.8 2044.13  5444.2 2045.43  5520.4 2047.79
  5590.5 2047.11  5696.8 2050.81  5737.2 2049.98  5808.0 2053.50  5838.3 2052.70
  5919.1 2056.13  5989.9 2056.57  6020.2 2059.06  6081.3 2059.17  6206.9 2064.35
#Mann=7,-1,0
  4102.1   0.045       0  4550.2    0.07       0  4806.5   0.035       0
  4913.9    0.07       0  5017.5    0.07       0  5022.0    0.07       0
  5088.9   0.045       0
Bank Sta=5017.5,5022
Exp/Cntr=0.3,0.1

Type RM Length L Ch R = 1,14171,479,479,479
BEGIN DESCRIPTION:
UCFB HW Trib 07 24.0
END DESCRIPTION:
XS GIS Cut Line= 4
      1340945.84      6981605.80      1341323.89      6981317.73
      1341355.00      6981188.00      1341268.77      6980225.56
#Sta/Elev= 30
  4391.3 2045.56  4589.5 2045.72  4674.8 2043.80  4764.4 2043.60  4803.6 2044.08
  4824.4 2041.15  4869.0 2039.71  4886.9 2036.91  4907.3 2037.49  4934.4 2033.29
  4939.6 2034.53  4958.9 2030.51  4995.2 2027.80  4995.5 2027.30  4999.7 2027.80
  5007.1 2028.05  5030.1 2028.64  5055.6 2033.01  5060.6 2032.02  5090.4 2036.64
  5180.7 2042.01  5190.8 2041.03  5256.1 2040.99  5602.4 2042.47  5632.5 2044.54
  5672.7 2043.51  5783.1 2044.77  5853.4 2047.95  5883.5 2046.95  5966.3 2049.00
#Mann=7,-1,0
  4391.3   0.045       0  4764.4    0.07       0  4907.3   0.035       0
  4995.2   0.035       0  4999.7   0.035       0  5007.1    0.07       0
  5256.1   0.045       0
Bank Sta=4995.2,4999.7
Exp/Cntr=0.3,0.1

Type RM Length L Ch R = 1,13692,455,455,455
BEGIN DESCRIPTION:
UCFB HW Trib 07 23.0
END DESCRIPTION:
XS GIS Cut Line= 4
      1341138.58      6981673.48      1341744.47      6981197.24
      1341705.00      6981038.00      1341545.04      6980231.92
#Sta/Elev= 30
  4054.7 2043.49  4169.9 2044.36  4184.3 2042.61  4232.5 2042.47  4319.0 2043.15
  4347.9 2039.58  4355.4 2042.18  4681.0 2037.41  4831.1 2033.91  4929.9 2027.85
  4948.2 2028.58  4971.3 2025.28  4997.4 2024.50  4997.7 2024.00  5001.9 2024.50
  5009.8 2025.55  5030.2 2034.94  5040.4 2037.50  5066.2 2039.55  5083.2 2038.69
  5162.7 2037.76  5305.5 2039.18  5327.1 2041.06  5499.2 2041.61  5550.1 2044.46
  5583.0 2043.32  5634.2 2044.80  5672.5 2047.72  5787.7 2048.27  5811.2 2050.61
#Mann=7,-1,0
  4054.7   0.045       0  4232.5    0.07       0  4681.0   0.035       0
  4831.1    0.07       0  4997.4    0.07       0  5001.9    0.07       0
  5083.2   0.045       0
Bank Sta=4997.4,5001.9
Exp/Cntr=0.3,0.1

Type RM Length L Ch R = 1,13237,479,479,479
BEGIN DESCRIPTION:
UCFB HW Trib 07 22.0
END DESCRIPTION:
XS GIS Cut Line= 5
      1341383.39      6981689.10      1342039.17      6981342.03
      1342055.00      6981188.00      1342087.78      6981029.53
      1341955.00      6980588.00
#Sta/Elev= 30
  4103.6 2040.41  4163.5 2039.72  4195.9 2040.66  4240.2 2039.28  4333.9 2039.80
  4548.3 2037.11  4586.6 2037.92  4637.2 2036.67  4725.2 2036.61  4777.1 2036.56
  4801.0 2037.54  4889.9 2033.04  4953.3 2029.62  4995.5 2023.34  4995.9 2022.84
  5000.2 2023.34  5051.5 2024.83  5070.6 2026.89  5075.7 2026.17  5153.6 2034.27
  5184.4 2034.40  5215.6 2032.95  5293.9 2033.20  5365.2 2034.58  5393.0 2036.00
  5398.2 2035.22  5424.9 2037.69  5502.5 2037.11  5606.8 2038.88  5623.3 2040.04
#Mann=7,-1,0
  4103.6   0.035       0  4725.2    0.07       0  4777.1   0.035       0
  4889.9    0.07       0  4995.5    0.07       0  5000.2    0.07       0
  5215.6   0.045       0
Bank Sta=4995.5,5000.2
Exp/Cntr=0.3,0.1

Type RM Length L Ch R = 1,12758,440,440,440
BEGIN DESCRIPTION:
UCFB HW Trib 07 21.0
END DESCRIPTION:
XS GIS Cut Line= 5
      1341477.15      6981751.60      1342289.17      6981522.59
      1342405.00      6981388.00      1342430.00      6981163.00
      1342326.06      6980277.63
#Sta/Elev= 30
  3980.0 2039.66  4548.7 2035.32  4701.4 2035.29  4798.6 2034.87  4830.7 2031.58
  4866.8 2034.59  4902.0 2032.91  4930.5 2034.81  4944.7 2033.61  4951.3 2028.99
  4952.8 2029.82  4959.0 2033.27  4965.6 2017.95  4973.3 2024.33  4979.9 2017.39
  4991.8 2016.27  4992.1 2015.77  4996.5 2016.27  4998.0 2019.08  5021.4 2021.11
  5091.8 2022.16  5142.1 2026.18  5182.4 2026.67  5242.7 2033.53  5343.4 2037.29
  5376.7 2035.26  5746.7 2036.66  5824.9 2035.48  6068.4 2038.52  6119.1 2041.45
#Mann=7,-1,0
  3980.0   0.035       0  4548.7    0.07       0  4701.4   0.035       0
  4952.8    0.07       0  4991.8    0.07       0  4996.5    0.07       0
  5376.7   0.045       0
Bank Sta=4991.8,4996.5
Exp/Cntr=0.3,0.1

Type RM Length L Ch R = 1,12318,437,437,437
BEGIN DESCRIPTION:
UCFB HW Trib 07 20.0
END DESCRIPTION:
XS GIS Cut Line= 4
      1342780.00      6982013.00      1342863.69      6981649.07
      1342705.00      6981138.00      1342419.90      6980194.61
#Sta/Elev= 30
  4090.5 2034.56  4204.1 2034.56  4331.6 2035.25  4376.3 2033.36  4578.6 2033.52
  4608.8 2034.24  4646.6 2031.24  4674.0 2032.56  4711.8 2024.45  4912.4 2020.95
  4957.2 2019.13  4967.7 2016.24  4977.6 2016.22  4979.1 2014.55  4979.6 2014.05
  4986.4 2014.55  4988.6 2017.86  4996.5 2022.96  5001.7 2022.96  5009.5 2027.96
  5020.8 2029.07  5030.4 2033.27  5072.2 2036.60  5081.5 2034.44  5098.0 2034.08
  5706.0 2034.70  5815.3 2038.03  5866.1 2037.58  5928.8 2041.32  5984.6 2040.47
#Mann=7,-1,0
  4090.5   0.045       0  4204.1   0.035       0  4376.3   0.045       0
  4578.6    0.07       0  4979.1    0.07       0  4986.4    0.07       0
  5098.0   0.045       0
Bank Sta=4979.1,4986.4
Exp/Cntr=0.3,0.1

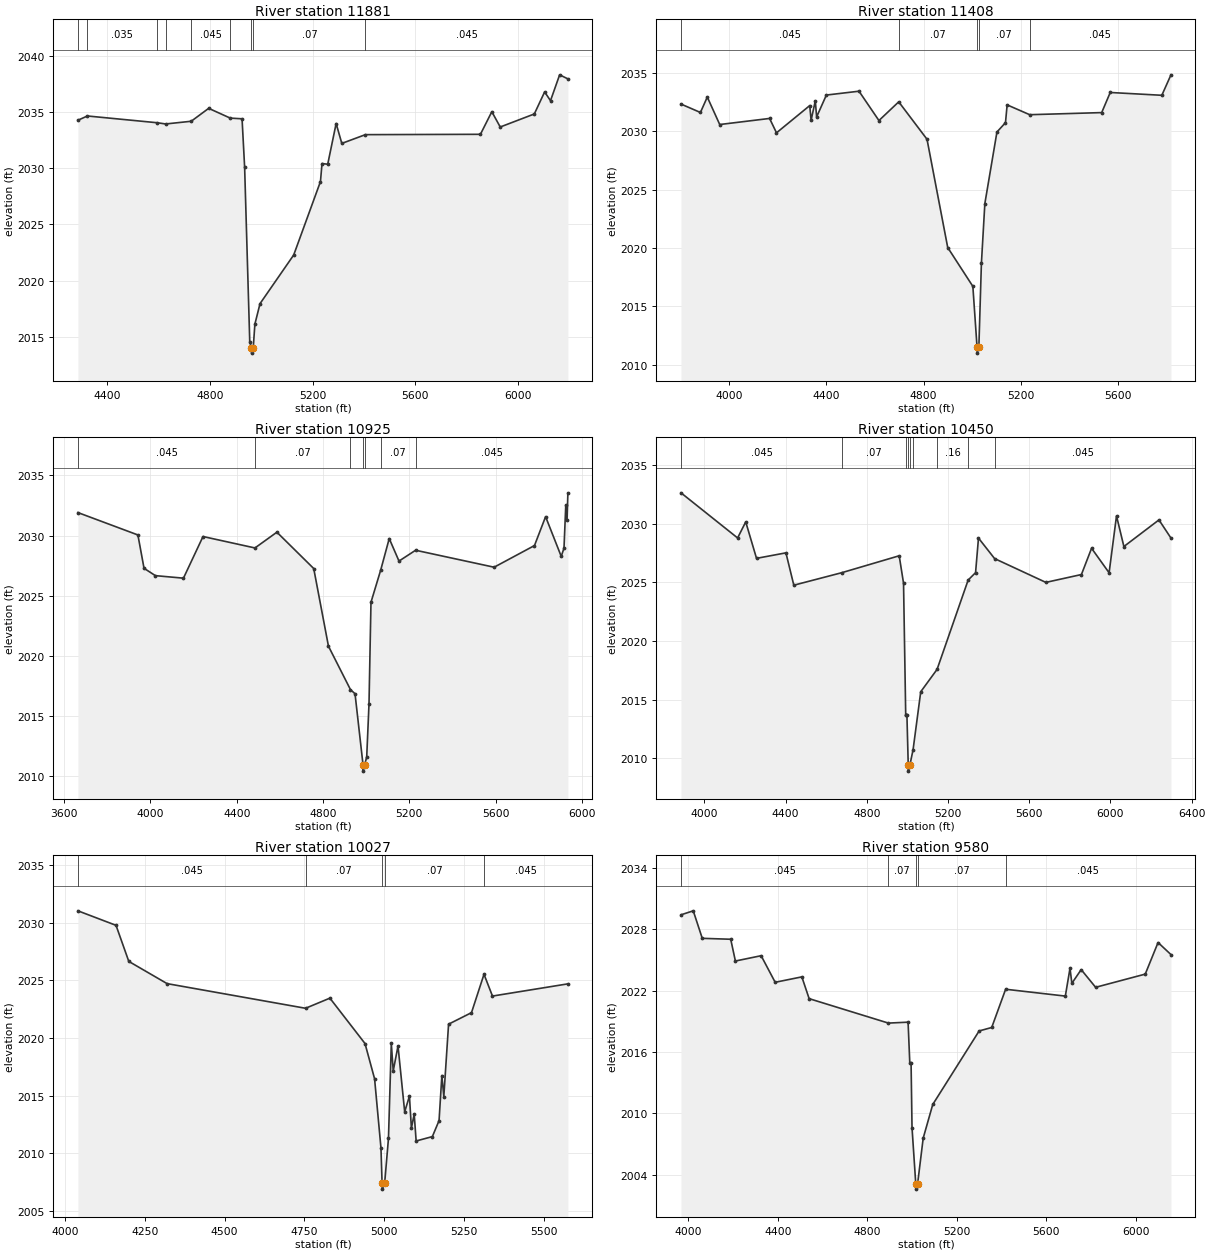
Type RM Length L Ch R = 1,11881,473,473,473
BEGIN DESCRIPTION:
UCFB HW Trib 07 19.0
END DESCRIPTION:
XS GIS Cut Line= 4
      1342830.02      6982012.96      1343016.53      6981647.73
      1343005.00      6981338.00      1342502.64      6980258.84
#Sta/Elev= 30
  4284.8 2034.26  4321.8 2034.64  4593.4 2034.04  4626.9 2033.93  4726.5 2034.17
  4794.7 2035.32  4878.9 2034.45  4924.8 2034.39  4934.8 2030.09  4954.8 2014.55
  4961.2 2014.05  4961.7 2013.55  4968.5 2014.05  4974.8 2016.13  4994.8 2017.95
  5126.2 2022.28  5230.5 2028.81  5236.5 2030.41  5258.8 2030.35  5291.6 2033.97
  5313.7 2032.20  5405.7 2032.98  5854.2 2033.01  5898.6 2035.02  5931.4 2033.66
  6064.3 2034.82  6104.5 2036.78  6127.4 2036.00  6163.0 2038.30  6195.2 2037.94
#Mann=9,-1,0
  4284.8   0.045       0  4321.8   0.035       0  4593.4   0.045       0
  4626.9   0.035       0  4726.5   0.045       0  4878.9    0.07       0
  4961.2    0.07       0  4968.5    0.07       0  5405.7   0.045       0
Bank Sta=4961.2,4968.5
Exp/Cntr=0.3,0.1

Type RM Length L Ch R = 1,11408,483,483,483
BEGIN DESCRIPTION:
UCFB HW Trib 07 18.0
END DESCRIPTION:
XS GIS Cut Line= 4
      1343034.40      6982131.83      1343383.36      6981387.03
      1343253.54      6981033.61      1342695.88      6980433.93
#Sta/Elev= 30
  3801.0 2032.31  3881.0 2031.59  3909.3 2032.91  3960.5 2030.56  4165.9 2031.08
  4194.3 2029.85  4331.3 2032.18  4336.8 2030.92  4354.1 2032.58  4359.6 2031.21
  4399.7 2033.08  4534.1 2033.41  4616.2 2030.90  4697.7 2032.50  4814.2 2029.30
  4899.5 2020.04  5003.0 2016.72  5020.3 2011.51  5020.8 2011.01  5027.7 2011.51
  5038.2 2018.68  5052.4 2023.80  5102.2 2029.92  5137.4 2030.72  5144.2 2032.24
  5237.1 2031.40  5533.6 2031.58  5568.8 2033.30  5781.3 2033.06  5818.9 2034.81
#Mann=5,-1,0
  3801.0   0.045       0  4697.7    0.07       0  5020.3    0.07       0
  5027.7    0.07       0  5237.1   0.045       0
Bank Sta=5020.3,5027.7
Exp/Cntr=0.3,0.1

Type RM Length L Ch R = 1,10925,475,475,475
BEGIN DESCRIPTION:
UCFB HW Trib 07 17.0
END DESCRIPTION:
XS GIS Cut Line= 4
      1343211.46      6982173.53      1343622.94      6981293.28
      1343705.00      6980938.00      1343195.94      6980152.79
#Sta/Elev= 30
  3663.5 2031.92  3941.7 2030.06  3970.1 2027.29  4022.8 2026.68  4152.9 2026.47
  4243.6 2029.93  4484.5 2028.98  4586.2 2030.29  4757.0 2027.27  4825.3 2020.82
  4927.4 2017.21  4948.5 2016.87  4985.8 2010.94  4986.3 2010.44  4993.3 2010.94
  5002.8 2011.65  5013.3 2016.02  5022.5 2024.47  5067.7 2027.15  5107.1 2029.76
  5152.4 2027.89  5229.4 2028.79  5593.5 2027.38  5780.7 2029.18  5832.2 2031.58
  5904.7 2028.28  5917.5 2028.96  5925.8 2032.53  5931.7 2031.30  5935.6 2033.56
#Mann=7,-1,0
  3663.5   0.045       0  4484.5    0.07       0  4927.4    0.16       0
  4985.8    0.07       0  4993.3    0.16       0  5067.7    0.07       0
  5229.4   0.045       0
Bank Sta=4985.8,4993.3
Exp/Cntr=0.3,0.1

Type RM Length L Ch R = 1,10450,423,423,423
BEGIN DESCRIPTION:
UCFB HW Trib 07 16.0
END DESCRIPTION:
XS GIS Cut Line= 4
      1343737.51      6982105.82      1344116.04      6981189.04
      1344055.00      6981088.00      1343355.02      6979988.03
#Sta/Elev= 30
  3884.4 2032.64  4163.3 2028.79  4203.3 2030.16  4256.5 2027.05  4401.3 2027.52
  4440.2 2024.76  4677.0 2025.83  4959.3 2027.27  4980.7 2024.93  4991.4 2013.72
  4993.3 2013.72  4997.3 2013.72  5003.9 2009.40  5004.4 2008.90  5011.8 2009.40
  5027.8 2010.74  5065.4 2015.67  5145.9 2017.58  5299.0 2025.20  5335.5 2025.83
  5349.9 2028.78  5429.3 2027.03  5681.8 2025.00  5857.0 2025.67  5907.0 2027.91
  5993.3 2025.82  6029.8 2030.67  6066.2 2028.06  6238.9 2030.33  6298.1 2028.78
#Mann=9,-1,0
  3884.4   0.045       0  4677.0    0.07       0  4993.3    0.16       0
  5003.9    0.07       0  5011.8    0.16       0  5027.8    0.07       0
  5145.9    0.16       0  5299.0    0.07       0  5429.3   0.045       0
Bank Sta=5003.9,5011.8
Exp/Cntr=0.3,0.1

Type RM Length L Ch R = 1,10027,447,447,447
BEGIN DESCRIPTION:
UCFB HW Trib 07 15.0
END DESCRIPTION:
XS GIS Cut Line= 3
      1344404.19      6981897.41      1344405.00      6980938.00
      1344079.97      6980462.96
#Sta/Elev= 30
  4040.6 2031.04  4160.0 2029.78  4200.0 2026.65  4320.0 2024.72  4753.7 2022.58
  4830.0 2023.46  4940.0 2019.52  4970.0 2016.46  4990.0 2010.45  4993.5 2007.38
  4994.0 2006.88  5001.5 2007.38  5013.5 2011.28  5022.4 2019.53  5028.4 2017.14
  5043.4 2019.31  5064.3 2013.59  5079.2 2014.96  5085.3 2012.17  5094.1 2013.39
  5100.2 2011.06  5151.0 2011.44  5172.0 2012.83  5180.8 2016.74  5186.9 2014.92
  5201.8 2021.20  5273.6 2022.20  5312.8 2025.53  5339.3 2023.64  5575.6 2024.70
#Mann=5,-1,0
  4040.6   0.045       0  4753.7    0.07       0  4993.5    0.07       0
  5001.5    0.07       0  5312.8   0.045       0
Bank Sta=4993.5,5001.5
Exp/Cntr=0.3,0.1

Type RM Length L Ch R = 1,9580,465,465,465
BEGIN DESCRIPTION:
UCFB HW Trib 07 14.0
END DESCRIPTION:
XS GIS Cut Line= 4
      1344570.86      6981970.35      1344834.79      6981116.13
      1344805.00      6980988.00      1344106.01      6980056.01
#Sta/Elev= 30
  3967.0 2029.41  4021.8 2029.80  4062.1 2027.11  4189.3 2027.02  4210.2 2024.89
  4325.3 2025.41  4388.1 2022.81  4507.3 2023.34  4539.9 2021.21  4894.2 2018.82
  4982.3 2018.91  4990.0 2014.88  4995.7 2014.88  4999.9 2008.59  5016.7 2003.08
  5017.2 2002.58  5024.7 2003.08  5049.9 2007.57  5092.6 2010.86  5299.9 2018.05
  5356.2 2018.39  5418.4 2022.13  5685.3 2021.46  5706.2 2024.18  5714.5 2022.71
  5756.2 2024.05  5820.7 2022.32  6042.6 2023.61  6099.9 2026.70  6157.6 2025.52
#Mann=5,-1,0
  3967.0   0.045       0  4894.2    0.07       0  5016.7    0.07       0
  5024.7    0.07       0  5418.4   0.045       0
Bank Sta=5016.7,5024.7
Exp/Cntr=0.3,0.1

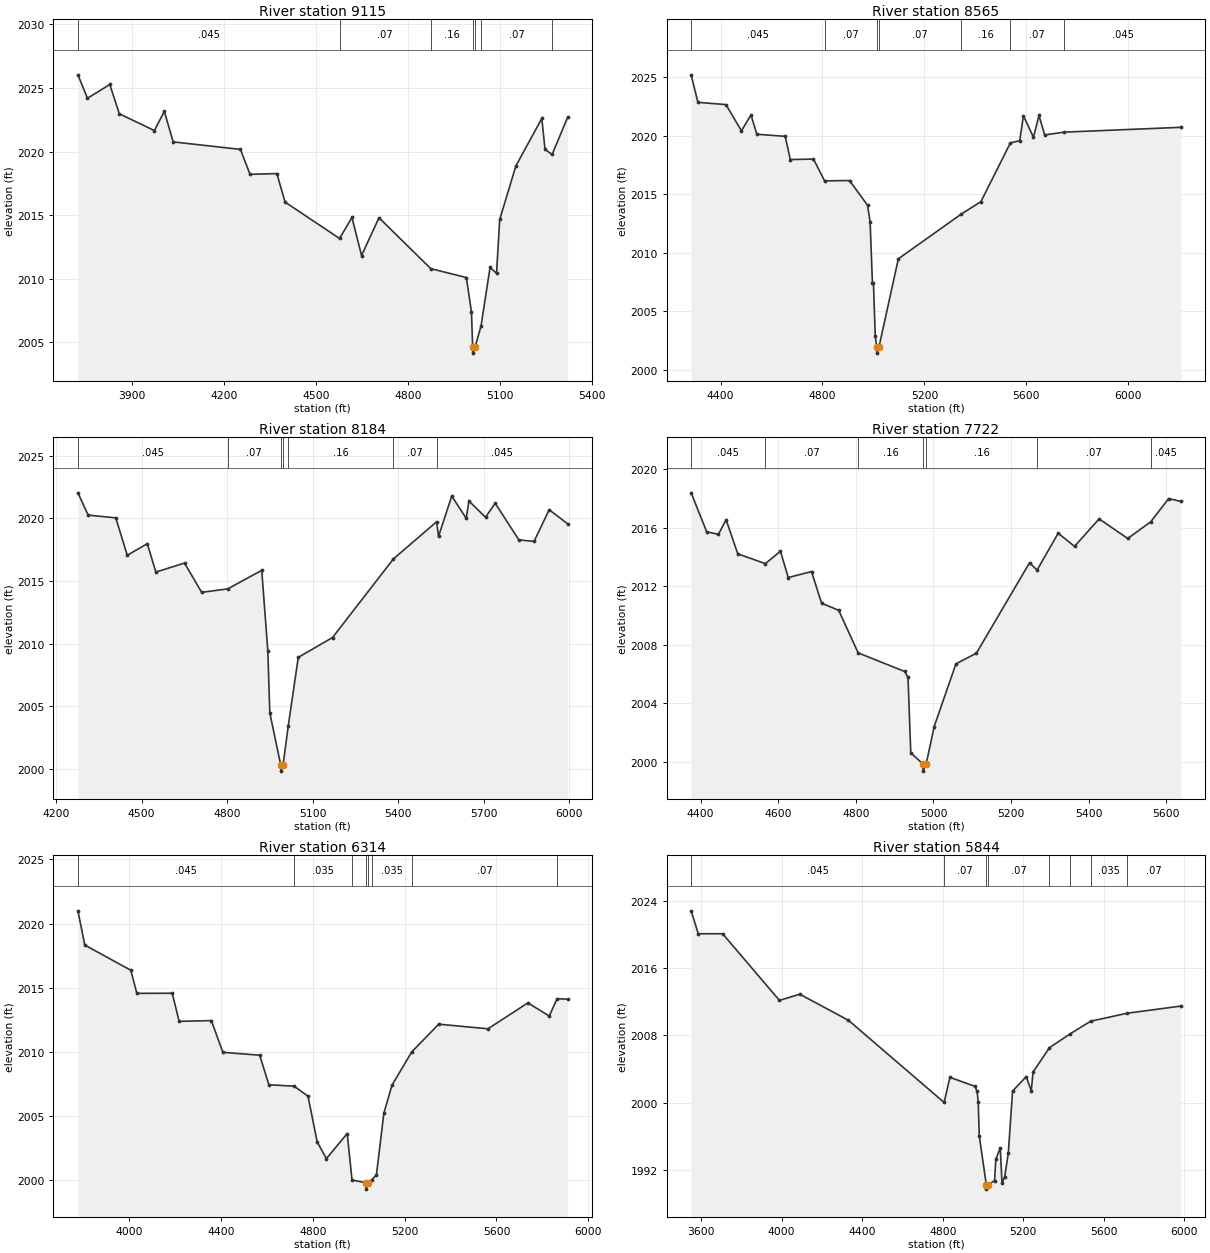
Type RM Length L Ch R = 1,9115,550,550,550
BEGIN DESCRIPTION:
UCFB HW Trib 07 13.0
END DESCRIPTION:
XS GIS Cut Line= 4
      1345405.00      6981788.01      1345091.73      6980671.68
      1345005.00      6980588.00      1344705.00      6980488.00
#Sta/Elev= 30
  3724.6 2026.03  3755.8 2024.19  3828.5 2025.27  3859.6 2022.97  3973.9 2021.65
  4006.2 2023.16  4035.1 2020.76  4254.3 2020.17  4285.5 2018.21  4373.0 2018.27
  4399.7 2016.03  4577.3 2013.17  4617.8 2014.82  4649.0 2011.83  4705.8 2014.80
  4874.5 2010.80  4990.5 2010.10  5007.2 2007.41  5011.1 2004.66  5011.6 2004.16
  5019.2 2004.66  5038.3 2006.28  5067.8 2010.89  5088.9 2010.43  5099.4 2014.67
  5152.1 2018.88  5236.5 2022.60  5247.0 2020.17  5270.0 2019.77  5320.8 2022.70
#Mann=7,-1,0
  3724.6   0.045       0  4577.3    0.07       0  4874.5    0.16       0
  5011.1    0.07       0  5019.2    0.16       0  5038.3    0.07       0
  5270.0   0.045       0
Bank Sta=5011.1,5019.2
Exp/Cntr=0.3,0.1

Type RM Length L Ch R = 1,8565,381,381,381
BEGIN DESCRIPTION:
UCFB HW Trib 07 12.0
END DESCRIPTION:
XS GIS Cut Line= 4
      1345503.15      6981543.31      1345402.99      6980835.05
      1345378.15      6980621.41      1344458.00      6980252.31
#Sta/Elev= 30
  4284.7 2025.19  4311.3 2022.84  4421.4 2022.65  4482.0 2020.41  4519.4 2021.77
  4542.5 2020.12  4653.6 2019.94  4673.8 2017.96  4764.7 2018.00  4808.3 2016.14
  4906.1 2016.17  4976.8 2014.06  4986.9 2012.65  4996.0 2007.42  5000.0 2007.42
  5007.1 2002.89  5013.0 2001.94  5013.5 2001.44  5021.4 2001.94  5097.7 2009.49
  5342.9 2013.28  5421.8 2014.37  5537.3 2019.38  5574.0 2019.57  5588.5 2021.70
  5627.9 2019.86  5649.5 2021.72  5671.9 2020.06  5748.4 2020.30  6206.5 2020.71
#Mann=7,-1,0
  4284.7   0.045       0  4808.3    0.07       0  5013.0    0.07       0
  5021.4    0.07       0  5342.9    0.16       0  5537.3    0.07       0
  5748.4   0.045       0
Bank Sta=5013,5021.4
Exp/Cntr=0.3,0.1

Type RM Length L Ch R = 1,8184,462,462,462
BEGIN DESCRIPTION:
UCFB HW Trib 07 11.0
END DESCRIPTION:
XS GIS Cut Line= 5
      1345753.15      6981220.37      1345699.37      6980636.96
      1345605.00      6980538.00      1345415.90      6980386.72
      1344675.01      6980251.62
#Sta/Elev= 30
  4276.9 2022.04  4312.8 2020.26  4409.8 2020.04  4450.0 2017.05  4520.3 2017.98
  4550.4 2015.71  4650.8 2016.43  4711.1 2014.09  4802.7 2014.37  4921.7 2015.85
  4943.1 2009.40  4950.0 2004.47  4988.2 2000.31  4988.7 1999.81  4996.6 2000.31
  5014.5 2003.39  5049.9 2008.90  5170.0 2010.48  5383.5 2016.76  5535.1 2019.73
  5541.8 2018.56  5588.2 2021.78  5639.0 2020.00  5648.4 2021.39  5706.7 2020.09
  5740.7 2021.21  5823.5 2018.28  5876.8 2018.16  5930.0 2020.69  5994.8 2019.56
#Mann=7,-1,0
  4276.9   0.045       0  4802.7    0.07       0  4988.2    0.07       0
  4996.6    0.07       0  5014.5    0.16       0  5383.5    0.07       0
  5535.1   0.045       0
Bank Sta=4988.2,4996.6
Exp/Cntr=0.3,0.1

Type RM Length L Ch R = 1,7722,1408,1408,1408
BEGIN DESCRIPTION:
UCFB HW Trib 07 10.0
END DESCRIPTION:
XS GIS Cut Line= 4
      1345955.00      6980888.04      1345963.26      6980331.40
      1345905.00      6980288.00      1345305.01      6980088.00
#Sta/Elev= 30
  4375.8 2018.39  4415.8 2015.73  4445.9 2015.55  4465.9 2016.55  4495.9 2014.22
  4567.1 2013.55  4605.9 2014.40  4625.9 2012.60  4685.9 2013.01  4711.8 2010.85
  4755.9 2010.36  4806.1 2007.45  4925.9 2006.18  4934.5 2005.77  4941.6 2000.61
  4972.8 1999.87  4973.3 1999.37  4981.3 1999.87  5002.0 2002.42  5057.9 2006.70
  5110.6 2007.43  5247.6 2013.61  5267.0 2013.11  5321.4 2015.63  5363.5 2014.73
  5426.8 2016.61  5500.6 2015.27  5559.8 2016.41  5606.0 2018.00  5637.6 2017.80
#Mann=7,-1,0
  4375.8   0.045       0  4567.1    0.07       0  4806.1    0.16       0
  4972.8    0.07       0  4981.3    0.16       0  5267.0    0.07       0
  5559.8   0.045       0
Bank Sta=4972.8,4981.3
Exp/Cntr=0.3,0.1

Type RM Length L Ch R = 1,6314,470,470,470
BEGIN DESCRIPTION:
UCFB HW Trib 07 9.0
END DESCRIPTION:
XS GIS Cut Line= 5
      1346555.00      6981287.97      1346619.51      6980182.10
      1346555.00      6980088.00      1346466.73      6980018.90
      1345685.41      6979855.78
#Sta/Elev= 30
  3777.9 2021.00  3807.9 2018.33  4008.3 2016.37  4034.4 2014.57  4188.6 2014.58
  4218.6 2012.39  4358.9 2012.45  4408.9 2009.98  4569.2 2009.75  4609.3 2007.45
  4719.2 2007.34  4779.6 2006.56  4819.6 2002.99  4859.7 2001.70  4950.4 2003.65
  4971.1 2000.03  5031.6 1999.82  5032.1 1999.32  5040.1 1999.82  5058.4 2000.07
  5077.5 2000.43  5109.8 2005.23  5145.0 2007.41  5231.2 2010.01  5348.6 2012.17
  5563.1 2011.81  5736.8 2013.83  5829.8 2012.80  5863.8 2014.15  5910.0 2014.12
#Mann=8,-1,0
  3777.9   0.045       0  4719.2   0.035       0  4971.1    0.16       0
  5031.6    0.07       0  5040.1    0.16       0  5058.4   0.035       0
  5231.2    0.07       0  5863.8    0.16       0
Bank Sta=5031.6,5040.1
Exp/Cntr=0.3,0.1

Type RM Length L Ch R = 1,5844,877,877,877
BEGIN DESCRIPTION:
UCFB HW Trib 07 8.0
END DESCRIPTION:
XS GIS Cut Line= 5
      1346830.00      6981413.02      1346991.04      6980095.29
      1346955.00      6979988.00      1346897.29      6979893.90
      1346050.64      6979652.84
#Sta/Elev= 30
  3551.3 2022.78  3586.6 2020.06  3707.5 2020.06  3989.6 2012.14  4090.3 2012.88
  4332.1 2009.78  4807.2 2000.02  4835.8 2003.01  4960.4 2001.93  4970.9 2001.33
  4976.3 2000.13  4981.5 1996.07  5016.7 1990.23  5017.2 1989.73  5025.3 1990.23
  5057.7 1990.75  5063.6 1993.25  5085.9 1994.63  5094.5 1990.40  5107.8 1991.21
  5125.6 1993.97  5146.9 2001.37  5214.6 2003.09  5239.9 2001.42  5248.5 2003.63
  5330.1 2006.53  5432.2 2008.16  5534.3 2009.67  5716.0 2010.62  5982.7 2011.47
#Mann=8,-1,0
  3551.3   0.045       0  4807.2    0.07       0  5016.7    0.07       0
  5025.3    0.07       0  5330.1   0.045       0  5432.2    0.07       0
  5534.3   0.035       0  5716.0    0.07       0
Bank Sta=5016.7,5025.3
Exp/Cntr=0.3,0.1

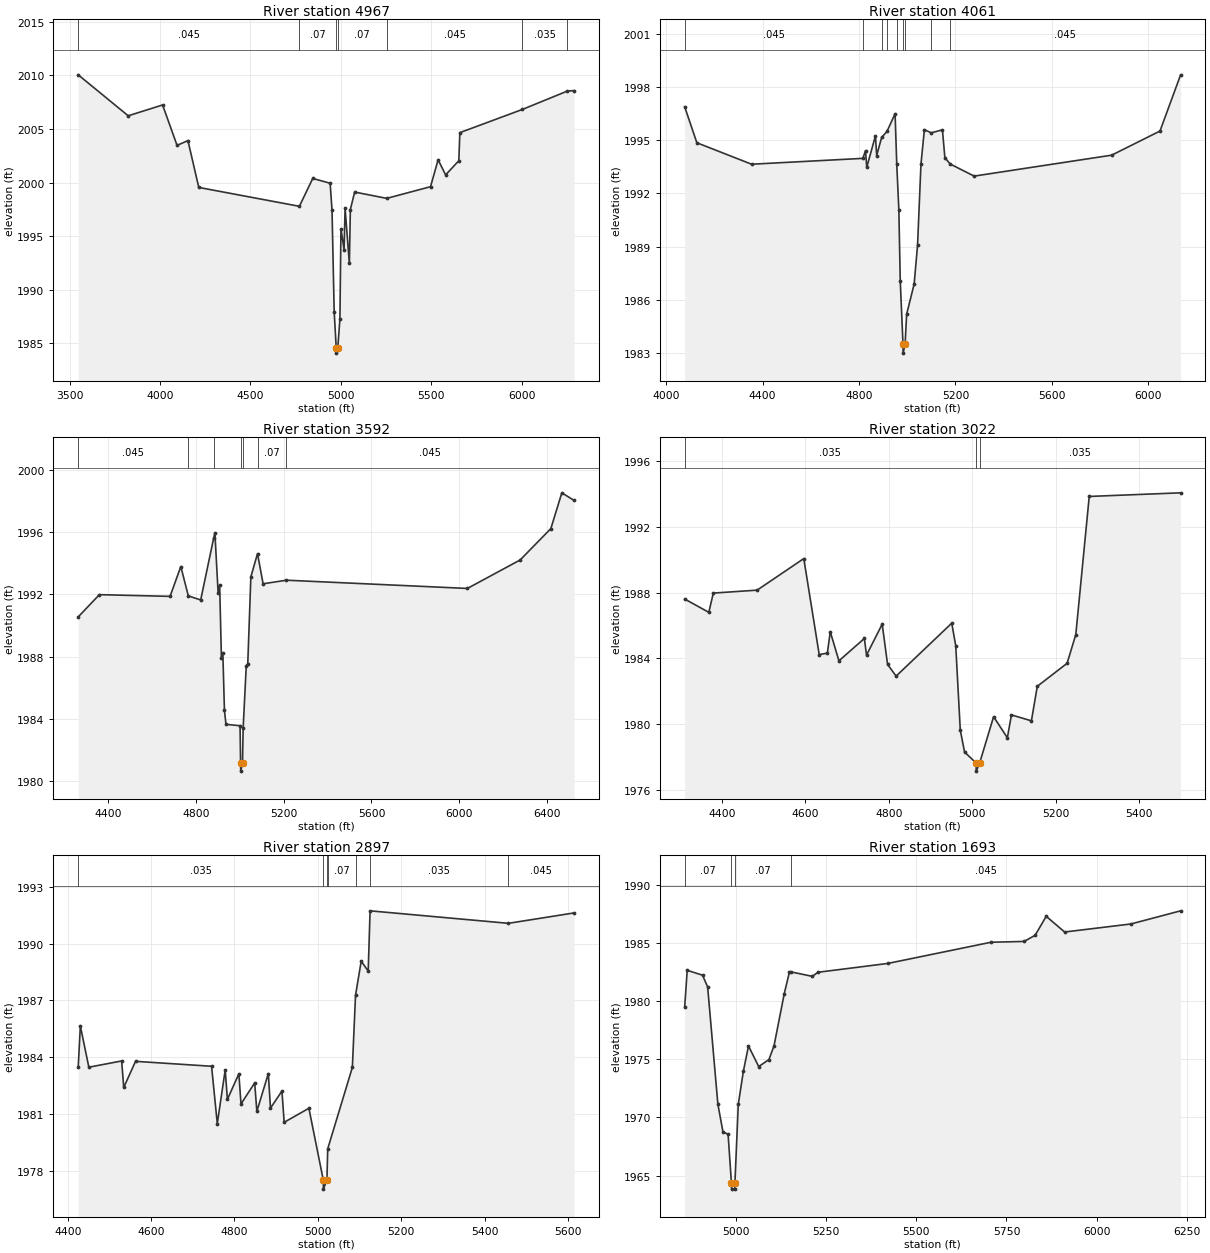
Type RM Length L Ch R = 1,4967,906,906,906
BEGIN DESCRIPTION:
UCFB HW Trib 07 7.0
END DESCRIPTION:
XS GIS Cut Line= 5
      1347438.04      6981184.38      1347459.79      6979838.35
      1347405.00      6979738.00      1347372.98      6979661.26
      1346222.74      6979326.70
#Sta/Elev= 30
  3548.1 2010.04  3824.5 2006.22  4014.5 2007.23  4094.6 2003.46  4154.6 2003.91
  4214.6 1999.54  4770.8 1997.78  4844.6 2000.38  4940.8 1999.93  4951.2 1997.42
  4963.1 1987.97  4974.4 1984.59  4974.9 1984.09  4983.1 1984.59  4994.9 1987.30
  5000.6 1995.68  5017.8 1993.74  5023.3 1997.63  5047.1 1992.45  5052.5 1997.48
  5076.3 1999.11  5253.7 1998.52  5495.8 1999.61  5537.5 2002.12  5579.2 2000.71
  5652.1 2002.03  5657.9 2004.65  6003.1 2006.81  6251.4 2008.52  6289.7 2008.57
#Mann=7,-1,0
  3548.1   0.045       0  4770.8    0.07       0  4974.4    0.07       0
  4983.1    0.07       0  5253.7   0.045       0  6003.1   0.035       0
  6251.4    0.07       0
Bank Sta=4974.4,4983.1
Exp/Cntr=0.3,0.1

Type RM Length L Ch R = 1,4061,469,469,469
BEGIN DESCRIPTION:
UCFB HW Trib 07 6.0
END DESCRIPTION:
XS GIS Cut Line= 5
      1347976.51      6980227.25      1348186.31      6979391.53
      1348155.00      6979338.00      1348094.80      6979277.80
      1347058.20      6979119.67
#Sta/Elev= 30
  4076.8 1996.89  4127.3 1994.86  4354.4 1993.65  4815.9 1993.98  4827.0 1994.42
  4832.1 1993.47  4868.1 1995.25  4873.3 1994.14  4893.9 1995.16  4916.1 1995.50
  4949.7 1996.50  4956.6 1993.64  4965.3 1991.08  4971.1 1987.07  4982.5 1983.50
  4983.0 1983.00  4991.2 1983.50  4997.6 1985.19  5028.8 1986.90  5042.9 1989.09
  5057.0 1993.65  5071.2 1995.60  5099.5 1995.42  5146.1 1995.59  5156.2 1994.02
  5178.5 1993.66  5277.6 1992.98  5848.0 1994.16  6048.6 1995.52  6134.2 1998.69
#Mann=9,-1,0
  4076.8   0.045       0  4815.9    0.07       0  4893.9   0.045       0
  4916.1    0.07       0  4956.6    0.16       0  4982.5    0.07       0
  4991.2    0.16       0  5099.5    0.07       0  5178.5   0.045       0
Bank Sta=4982.5,4991.2
Exp/Cntr=0.3,0.1

Type RM Length L Ch R = 1,3592,570,570,570
BEGIN DESCRIPTION:
UCFB HW Trib 07 5.0
END DESCRIPTION:
XS GIS Cut Line= 5
      1348730.01      6979563.02      1348411.18      6979008.49
      1348355.00      6978938.00      1348307.01      6978886.96
      1346848.91      6978918.69
#Sta/Elev= 30
  4264.7 1990.55  4361.0 1991.98  4683.0 1991.87  4731.9 1993.79  4766.1 1991.90
  4822.4 1991.64  4881.3 1995.60  4887.1 1995.96  4901.8 1992.09  4908.8 1992.60
  4916.8 1987.91  4923.2 1988.25  4930.6 1984.53  4937.6 1983.64  5001.6 1983.55
  5004.1 1981.13  5004.6 1980.63  5012.8 1981.13  5015.7 1983.38  5029.9 1987.39
  5036.8 1987.54  5050.9 1993.13  5081.2 1994.62  5106.6 1992.68  5213.0 1992.91
  6036.8 1992.38  6276.9 1994.21  6416.9 1996.23  6466.9 1998.53  6523.0 1998.04
#Mann=7,-1,0
  4264.7   0.045       0  4766.1    0.07       0  4881.3    0.16       0
  5004.1    0.07       0  5012.8    0.16       0  5081.2    0.07       0
  5213.0   0.045       0
Bank Sta=5004.1,5012.8
Exp/Cntr=0.3,0.1

Type RM Length L Ch R = 1,3022,125,125,125
BEGIN DESCRIPTION:
UCFB HW Trib 07 3.2
END DESCRIPTION:
XS GIS Cut Line= 3
      1349530.00      6979113.00      1349177.36      6978996.56
      1348379.98      6978813.00
#Sta/Elev= 30
  4310.3 1987.61  4368.2 1986.80  4379.0 1987.97  4484.1 1988.15  4596.0 1990.07
  4633.0 1984.23  4652.6 1984.32  4659.5 1985.62  4680.3 1983.85  4741.3 1985.21
  4746.5 1984.20  4784.1 1986.08  4797.0 1983.63  4817.5 1982.92  4950.9 1986.14
  4960.5 1984.77  4971.4 1979.63  4981.7 1978.30  5009.2 1977.64  5009.7 1977.14
  5017.9 1977.64  5051.3 1980.45  5084.3 1979.17  5094.1 1980.56  5142.0 1980.20
  5156.1 1982.30  5227.6 1983.70  5248.5 1985.45  5280.7 1993.85  5499.9 1994.07
#Mann=3,-1,0
  4310.3   0.035       0  5009.2   0.035       0  5017.9   0.035       0
Bank Sta=5009.2,5017.9
Exp/Cntr=0.3,0.1

Type RM Length L Ch R = 1,2897,1204,1204,1204
BEGIN DESCRIPTION:
UCFB HW Trib 07 3.5
END DESCRIPTION:
XS GIS Cut Line= 4
      1349530.01      6979013.00      1349302.91      6978969.57
      1348790.78      6978812.35      1348379.96      6978712.99
#Sta/Elev= 30
  4425.2 1983.46  4430.3 1985.65  4450.7 1983.47  4529.4 1983.80  4534.4 1982.40
  4562.7 1983.78  4745.1 1983.52  4758.8 1980.49  4777.8 1983.33  4783.0 1981.77
  4810.5 1983.12  4815.7 1981.53  4848.5 1982.64  4853.7 1981.14  4881.2 1983.13
  4886.4 1981.31  4913.9 1982.21  4919.2 1980.56  4978.5 1981.30  5012.9 1977.53
  5013.4 1977.03  5021.8 1977.53  5023.7 1979.16  5082.8 1983.46  5090.4 1987.27
  5104.0 1989.07  5120.8 1988.55  5125.3 1991.73  5457.1 1991.07  5614.8 1991.62
#Mann=7,-1,0
  4425.2   0.035       0  5012.9   0.035       0  5021.8   0.035       0
  5023.7    0.07       0  5090.4   0.045       0  5125.3   0.035       0
  5457.1   0.045       0
Bank Sta=5012.9,5021.8
Exp/Cntr=0.3,0.1

Type RM Length L Ch R = 1,1693,527,527,527
BEGIN DESCRIPTION:
UCFB HW Trib 07 3.0
END DESCRIPTION:
XS GIS Cut Line= 3
      1350029.97      6978712.97      1349780.00      6978463.00
      1348780.01      6978263.00
#Sta/Elev= 30
  4858.9 1979.45  4865.9 1982.64  4908.3 1982.22  4922.5 1981.21  4950.8 1971.14
  4964.9 1968.76  4979.1 1968.55  4988.4 1964.34  4988.9 1963.84  4997.5 1963.84
  4998.0 1964.34  5007.3 1971.12  5021.5 1973.98  5035.6 1976.14  5063.9 1974.37
  5092.2 1974.97  5106.3 1976.15  5134.6 1980.63  5148.8 1982.47  5152.2 1982.51
  5212.4 1982.12  5227.7 1982.47  5421.5 1983.23  5707.0 1985.05  5798.8 1985.12
  5829.4 1985.65  5860.0 1987.28  5911.0 1985.93  6094.5 1986.62  6232.2 1987.75
#Mann=4,-1,0
  4858.9    0.07       0  4988.4    0.07       0  4998.0    0.07       0
  5152.2   0.045       0
Bank Sta=4988.4,4998
Exp/Cntr=0.3,0.1