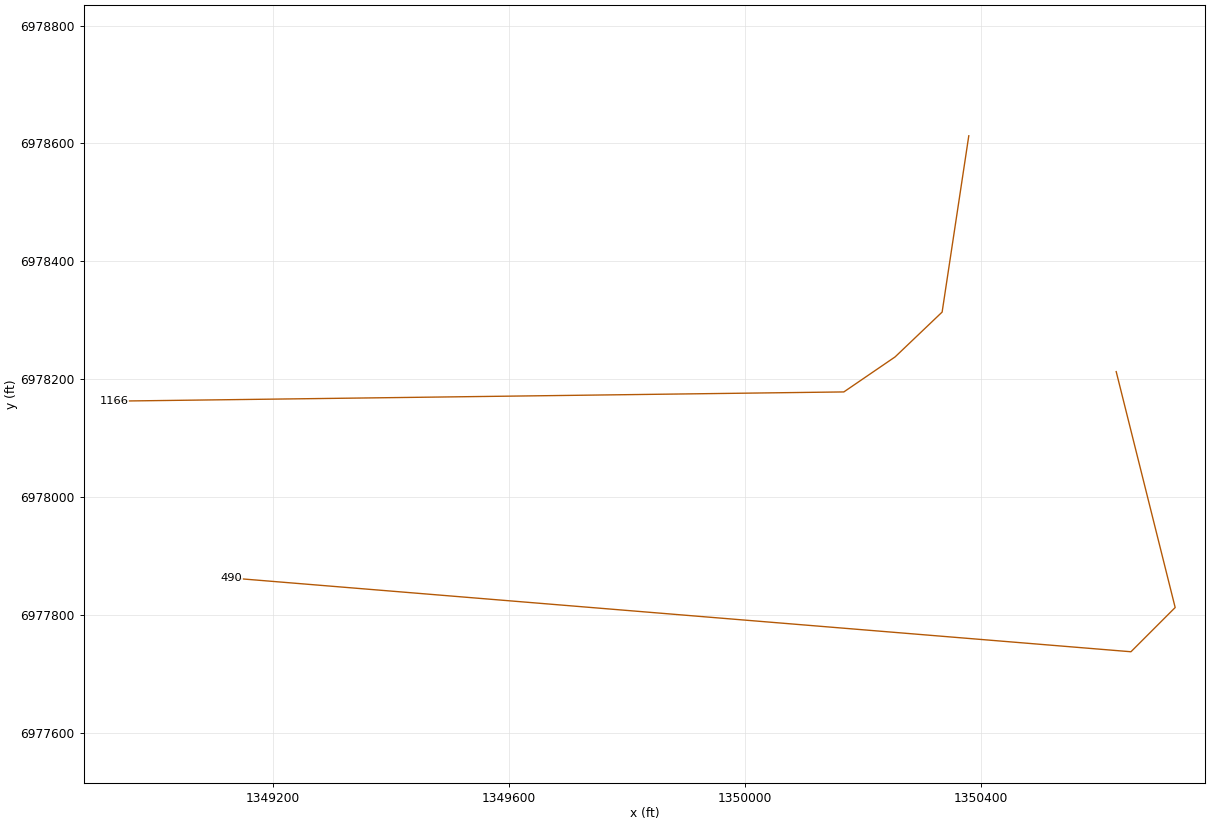
HEC-RAS study UCFB HW Trib 07.prj: UCFB HW Trib 07 Base Level Engineering

--- UCFB HW Trib 07.g01 (geometry) --- (continued)

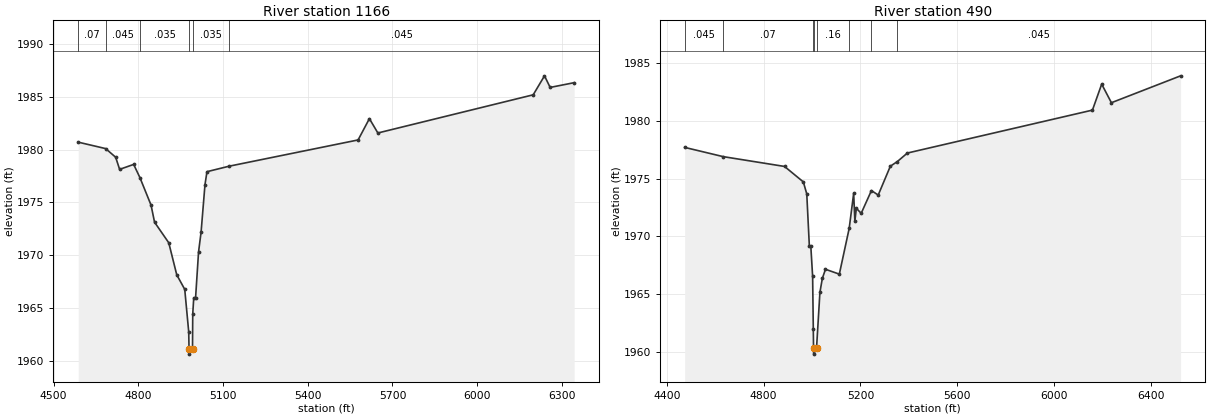
Type RM Length L Ch R = 1,1166,676,676,676
BEGIN DESCRIPTION:
UCFB HW Trib 07 2.0
END DESCRIPTION:
XS GIS Cut Line= 5
      1350380.00      6978613.00      1350334.79      6978314.04
      1350254.98      6978237.98      1350168.12      6978178.63
      1348930.03      6978163.00
#Sta/Elev= 30
  4587.4 1980.71  4684.5 1980.10  4720.0 1979.28  4734.0 1978.13  4783.8 1978.60
  4806.0 1977.34  4845.3 1974.74  4857.7 1973.12  4908.0 1971.17  4936.3 1968.13
  4964.6 1966.75  4978.7 1962.71  4979.8 1961.11  4980.3 1960.61  4992.1 1961.11
  4992.9 1964.40  4996.5 1965.96  5003.0 1965.96  5013.5 1970.30  5022.4 1972.16
  5036.3 1976.69  5043.3 1977.91  5121.6 1978.43  5578.4 1980.92  5618.4 1982.94
  5648.4 1981.58  6198.4 1985.20  6238.4 1987.00  6258.4 1985.90  6343.4 1986.35
#Mann=6,-1,0
  4587.4    0.07       0  4684.5   0.045       0  4806.0   0.035       0
  4979.8   0.035       0  4992.1   0.035       0  5121.6   0.045       0
Bank Sta=4979.8,4992.1
Exp/Cntr=0.3,0.1

Type RM Length L Ch R = 1,490,0,0,0
BEGIN DESCRIPTION:
UCFB HW Trib 07 1.0
END DESCRIPTION:
XS GIS Cut Line= 5
      1350629.99      6978213.05      1350730.00      6977813.00
      1350655.00      6977738.00      1350522.92      6977748.83
      1349130.04      6977863.00
#Sta/Elev= 30
  4474.2 1977.70  4633.2 1976.90  4886.6 1976.05  4964.3 1974.71  4978.5 1973.67
  4989.1 1969.18  4995.1 1969.18  5002.7 1966.52  5005.5 1961.93  5006.5 1960.29
  5007.0 1959.79  5018.8 1960.29  5032.8 1965.14  5042.8 1966.35  5055.8 1967.14
  5113.0 1966.72  5153.7 1970.68  5172.2 1973.71  5177.2 1971.32  5183.3 1972.42
  5203.3 1971.99  5245.6 1973.96  5273.6 1973.57  5323.7 1976.07  5352.5 1976.47
  5394.0 1977.21  6158.5 1980.93  6196.7 1983.18  6236.8 1981.57  6522.7 1983.90
#Mann=8,-1,0
  4474.2   0.045       0  4633.2    0.07       0  5005.5    0.16       0
  5006.5    0.07       0  5018.8    0.16       0  5153.7    0.07       0
  5245.6   0.035       0  5352.5   0.045       0
Bank Sta=5006.5,5018.8
Exp/Cntr=0.3,0.1

Chan Stop Cuts=-1