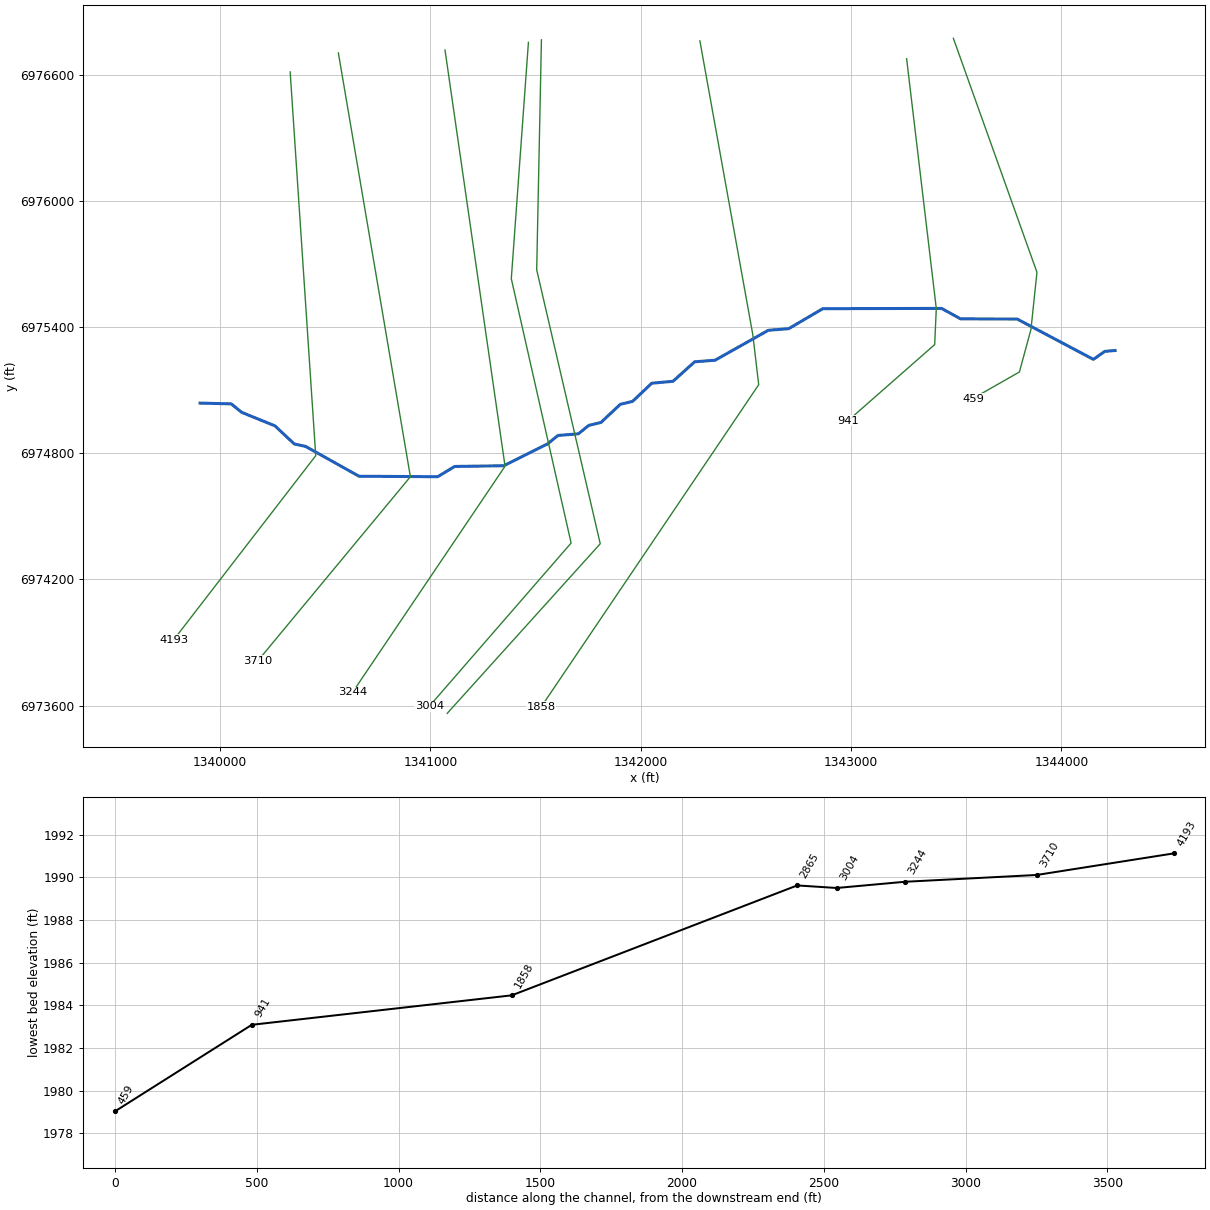
--- UCFB HW Trib 08.prj (project) ---

Proj Title=UCFB HW Trib 08 Base Level Engineering
Current Plan=p01
Default Exp/Contr=0.3,0.1
English Units
Geom File=g01
Flow File=f01
Plan File=p01
BEGIN DESCRIPTION:
UCFB HW Trib 08
END DESCRIPTION:

--- UCFB HW Trib 08.p01 (plan) ---

Plan Title=Multiple Run
Short Identifier=Multiple
Geom File=g01
Flow File=f01
Subcritical Flow
K Sum by GR= 0
Std Step Tol= 0.01
Critical Tol= 0.01
Num of Std Step Trials= 20
Max Error Tol= 0.3
Flow Tol Ratio= 0.001
Split Flow NTrial= 30
Split Flow Tol= 0.02
Split Flow Ratio= 0.02
Log Output Level= 0
Friction Slope Method= 1
Unsteady Friction Slope Method= 2
Unsteady Bridges Friction Slope Method= 1
Parabolic Critical Depth
Global Vel Dist=  1 , 1 , 1
Global Log Level= 0
CheckData=True
Encroach Param= -1, 0, 0, 0
BEGIN DESCRIPTION:
Multiple Run
END DESCRIPTION:

--- UCFB HW Trib 08.f01 (steady flow) ---

Flow Title=Multiple
Number of Profiles=7
Profile Names=10-year,25-year,50-year,1pct_min,100-year,1pct_plu,500-year
River Rch & RM= UCFB HW Trib 08,Reach-1,4193
     395     570     719     451     900    1795    1426
Boundary for River Rch & Prof#=UCFB HW Trib 08,Reach-1,1
Up Type=0
Dn Type=3
Dn Slope=0.005
Boundary for River Rch & Prof#=UCFB HW Trib 08,Reach-1,2
Up Type=0
Dn Type=3
Dn Slope=0.005
Boundary for River Rch & Prof#=UCFB HW Trib 08,Reach-1,3
Up Type=0
Dn Type=3
Dn Slope=0.005
Boundary for River Rch & Prof#=UCFB HW Trib 08,Reach-1,4
Up Type=0
Dn Type=3
Dn Slope=0.005
Boundary for River Rch & Prof#=UCFB HW Trib 08,Reach-1,5
Up Type=0
Dn Type=3
Dn Slope=0.005
Boundary for River Rch & Prof#=UCFB HW Trib 08,Reach-1,6
Up Type=0
Dn Type=3
Dn Slope=0.005
Boundary for River Rch & Prof#=UCFB HW Trib 08,Reach-1,7
Up Type=0
Dn Type=3
Dn Slope=0.005

--- UCFB HW Trib 08.g01 (geometry) ---

Geom Title=Existing Conditions

River Reach=UCFB HW Trib 08,Reach-1
Reach XY= 30
      1339905.00      6975038.00      1340053.46      6975034.28
      1340102.82      6974994.12      1340261.05      6974929.84
      1340352.71      6974843.85      1340407.19      6974831.90
      1340660.93      6974690.24      1341034.97      6974688.07
      1341115.50      6974736.78      1341349.07      6974740.24
      1341557.18      6974844.12      1341606.58      6974884.17
      1341703.42      6974891.83      1341752.83      6974931.86
      1341811.05      6974946.16      1341902.72      6975032.13
      1341961.04      6975046.18      1342052.58      6975132.46
      1342153.50      6975141.63      1342256.50      6975234.38
      1342353.41      6975241.83      1342606.58      6975384.17
      1342703.42      6975391.83      1342865.50      6975486.80
      1343430.08      6975488.20      1343520.22      6975438.52
      1343789.79      6975437.49      1344151.72      6975245.85
      1344206.36      6975284.00      1344255.00      6975288.00

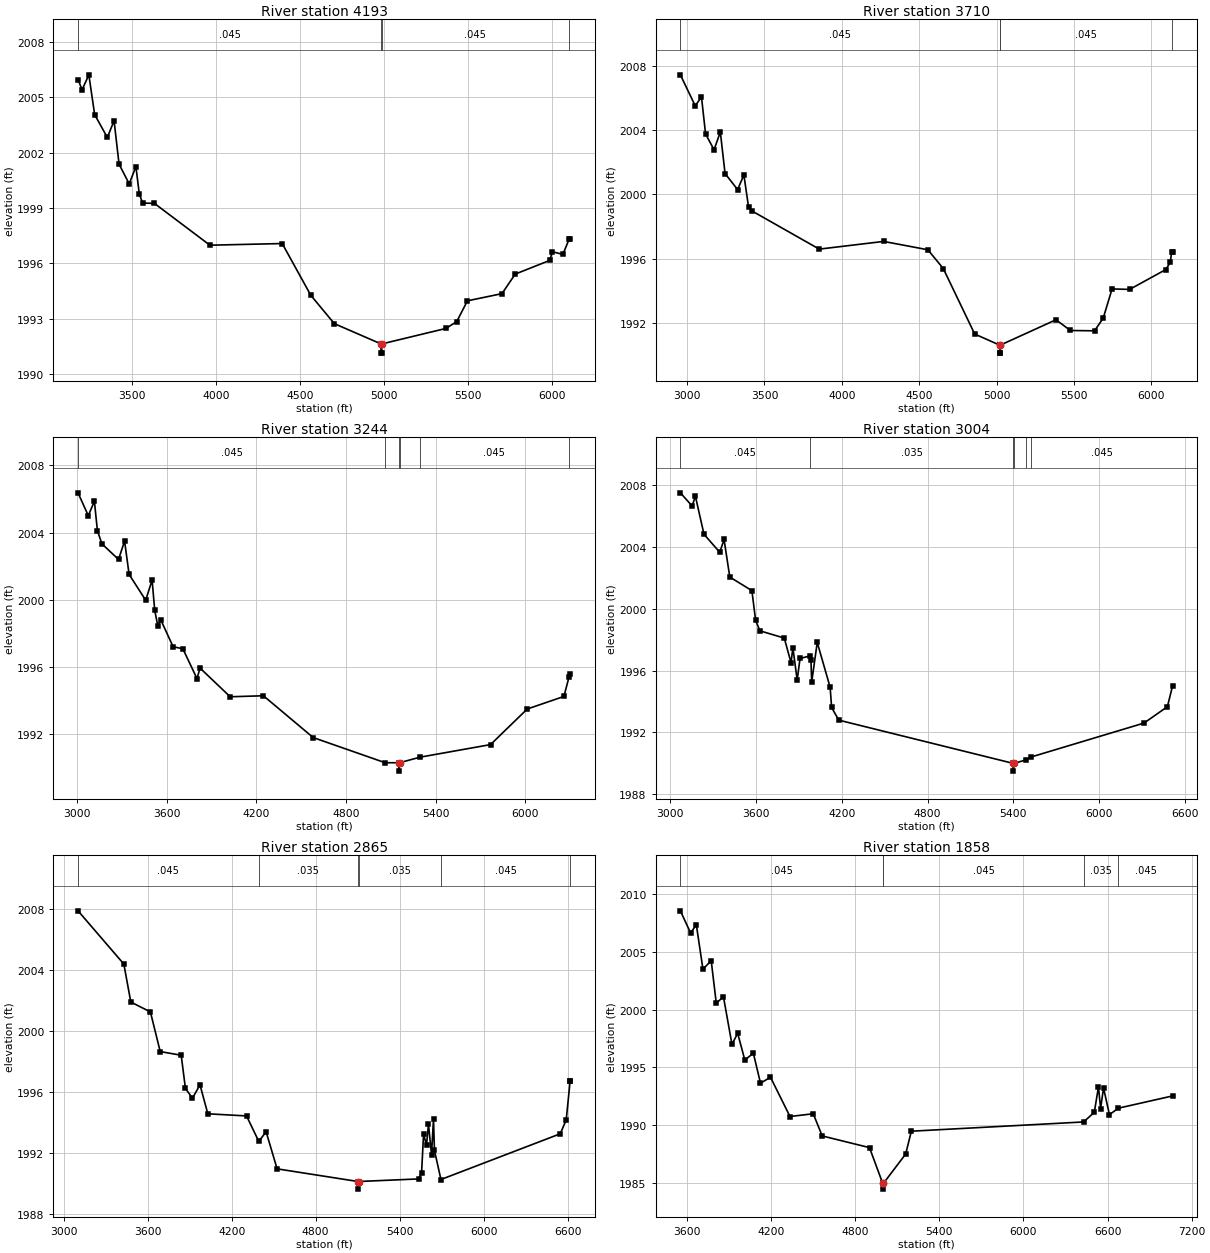
Type RM Length L Ch R = 1,4193,483,483,483
BEGIN DESCRIPTION:
UCFB HW Trib 08 6.0
END DESCRIPTION:
XS GIS Cut Line= 3
      1340333.44      6976612.34      1340455.00      6974788.00
      1339779.99      6973912.99
#Sta/Elev= 30
  3176.8 2005.97  3201.2 2005.42  3241.3 2006.23  3275.9 2004.07  3351.5 2002.83
  3391.6 2003.74  3421.3 2001.38  3481.8 2000.31  3521.9 2001.25  3541.9 1999.76
  3562.0 1999.27  3632.1 1999.25  3962.9 1996.98  4393.8 1997.07  4564.2 1994.26
  4704.5 1992.72  4982.9 1991.62  4983.2 1991.12  4987.0 1991.12  4987.3 1991.62
  5369.3 1992.46  5433.7 1992.83  5497.7 1993.96  5703.6 1994.35  5782.4 1995.41
  5989.8 1996.16  6002.9 1996.63  6066.8 1996.48  6103.3 1997.30  6110.3 1997.32
#Mann=4,-1,0
  3176.8   0.045       0  4982.9   0.045       0  4987.3   0.045       0
  6103.3    0.07       0
Bank Sta=4982.9,4987.3
Exp/Cntr=0.3,0.1

Type RM Length L Ch R = 1,3710,466,466,466
BEGIN DESCRIPTION:
UCFB HW Trib 08 5.0
END DESCRIPTION:
XS GIS Cut Line= 3
      1340562.61      6976702.57      1340905.00      6974688.00
      1340179.99      6973812.99
#Sta/Elev= 30
  2956.5 2007.45  3052.4 2005.52  3093.0 2006.07  3119.2 2003.77  3174.1 2002.78
  3214.7 2003.89  3245.2 2001.30  3326.3 2000.30  3366.9 2001.21  3397.3 1999.19
  3420.5 1998.96  3853.8 1996.59  4269.6 1997.07  4555.5 1996.55  4655.1 1995.38
  4858.0 1991.30  5019.2 1990.61  5019.6 1990.11  5023.4 1990.11  5023.7 1990.61
  5383.5 1992.19  5476.0 1991.52  5632.3 1991.50  5688.3 1992.29  5745.6 1994.11
  5858.9 1994.08  6093.3 1995.32  6122.0 1995.78  6130.4 1996.43  6136.3 1996.43
#Mann=4,-1,0
  2956.5   0.045       0  5019.2   0.045       0  5023.7   0.045       0
  6130.4    0.07       0
Bank Sta=5019.2,5023.7
Exp/Cntr=0.3,0.1

Type RM Length L Ch R = 1,3244,240,240,240
BEGIN DESCRIPTION:
UCFB HW Trib 08 4.0
END DESCRIPTION:
XS GIS Cut Line= 3
      1341069.55      6976716.48      1341355.00      6974738.00
      1340630.00      6973663.00
#Sta/Elev= 30
  3005.3 2006.37  3074.0 2005.01  3114.9 2005.87  3135.1 2004.11  3165.4 2003.33
  3276.6 2002.40  3317.0 2003.50  3347.3 2001.51  3458.4 1999.97  3501.3 2001.17
  3519.0 1999.36  3539.3 1998.46  3559.5 1998.80  3642.0 1997.20  3707.3 1997.08
  3801.9 1995.30  3822.2 1995.93  4024.2 1994.22  4246.5 1994.28  4579.9 1991.79
  5062.2 1990.29  5153.4 1990.29  5153.7 1989.79  5158.0 1990.29  5294.5 1990.62
  5767.3 1991.37  6013.1 1993.49  6258.7 1994.24  6292.4 1995.38  6300.9 1995.55
#Mann=6,-1,0
  3005.3   0.045       0  5062.2    0.07       0  5153.4   0.045       0
  5158.0    0.07       0  5294.5   0.045       0  6292.4    0.07       0
Bank Sta=5153.4,5158
Exp/Cntr=0.3,0.1

Type RM Length L Ch R = 1,3004,139,139,139
BEGIN DESCRIPTION:
UCFB HW Trib 08 3.1
END DESCRIPTION:
XS GIS Cut Line= 4
      1341466.08      6976752.82      1341384.70      6975629.26
      1341668.99      6974372.75      1340995.17      6973596.99
#Sta/Elev= 30
  3071.5 2007.51  3153.6 2006.66  3176.6 2007.29  3236.7 2004.83  3347.0 2003.66
  3377.1 2004.49  3417.2 2002.06  3571.8 2001.18  3597.7 1999.26  3627.8 1998.58
  3798.2 1998.11  3845.5 1996.52  3858.4 1997.48  3888.4 1995.40  3908.5 1996.79
  3975.8 1996.95  3984.9 1996.67  3989.9 1995.26  4028.8 1997.83  4119.1 1994.92
  4129.3 1993.62  4179.2 1992.80  5399.8 1990.00  5400.2 1989.50  5404.4 1990.00
  5486.1 1990.22  5522.9 1990.41  6314.3 1992.61  6477.6 1993.67  6513.8 1995.01
#Mann=6,-1,0
  3071.5   0.045       0  3975.8   0.035       0  5399.8   0.035       0
  5404.4   0.035       0  5486.1    0.07       0  5522.9   0.045       0
Bank Sta=5399.8,5404.4
Exp/Cntr=0.3,0.1

Type RM Length L Ch R = 1,2865,1007,1007,1007
BEGIN DESCRIPTION:
UCFB HW Trib 08 3.0
END DESCRIPTION:
XS GIS Cut Line= 4
      1341527.89      6976765.09      1341505.42      6975671.34
      1341807.50      6974369.26      1341080.00      6973563.00
#Sta/Elev= 30
  3102.3 2007.87  3429.5 2004.38  3479.5 2001.89  3619.5 2001.24  3689.5 1998.64
  3839.5 1998.40  3869.6 1996.23  3919.6 1995.58  3973.8 1996.46  4029.6 1994.56
  4306.3 1994.42  4393.8 1992.75  4446.1 1993.38  4524.7 1990.95  5102.3 1990.12
  5102.7 1989.62  5107.4 1990.12  5537.2 1990.29  5557.0 1990.70  5571.2 1993.24
  5592.1 1992.50  5606.3 1993.88  5627.9 1991.89  5642.1 1994.20  5648.9 1992.16
  5695.2 1990.25  6547.9 1993.25  6590.5 1994.17  6618.3 1996.72  6618.9 1996.72
#Mann=6,-1,0
  3102.3   0.045       0  4393.8   0.035       0  5102.3   0.035       0
  5107.4   0.035       0  5695.2   0.045       0  6618.3    0.07       0
Bank Sta=5102.3,5107.4
Exp/Cntr=0.3,0.1

Type RM Length L Ch R = 1,1858,917,917,917
BEGIN DESCRIPTION:
UCFB HW Trib 08 2.5
END DESCRIPTION:
XS GIS Cut Line= 4
      1342281.17      6976759.92      1342532.78      6975363.06
      1342560.80      6975125.38      1341526.36      6973593.14
#Sta/Elev= 30
  3556.0 2008.54  3629.1 2006.62  3669.7 2007.34  3717.0 2003.49  3775.7 2004.23
  3812.0 2000.54  3862.8 2001.12  3923.7 1996.99  3964.4 1997.95  4015.2 1995.64
  4076.2 1996.22  4127.0 1993.63  4198.1 1994.15  4337.2 1990.75  4502.9 1990.99
  4566.9 1989.07  4903.8 1988.06  4997.9 1984.97  4998.3 1984.47  5003.2 1984.97
  5161.7 1987.51  5202.0 1989.48  6429.3 1990.28  6505.7 1991.11  6535.6 1993.32
  6550.6 1991.44  6571.6 1993.22  6613.6 1990.91  6677.0 1991.47  7063.4 1992.53
#Mann=5,-1,0
  3556.0   0.045       0  4997.9   0.045       0  5003.2   0.045       0
  6429.3   0.035       0  6677.0   0.045       0
Bank Sta=4997.9,5003.2
Exp/Cntr=0.3,0.1

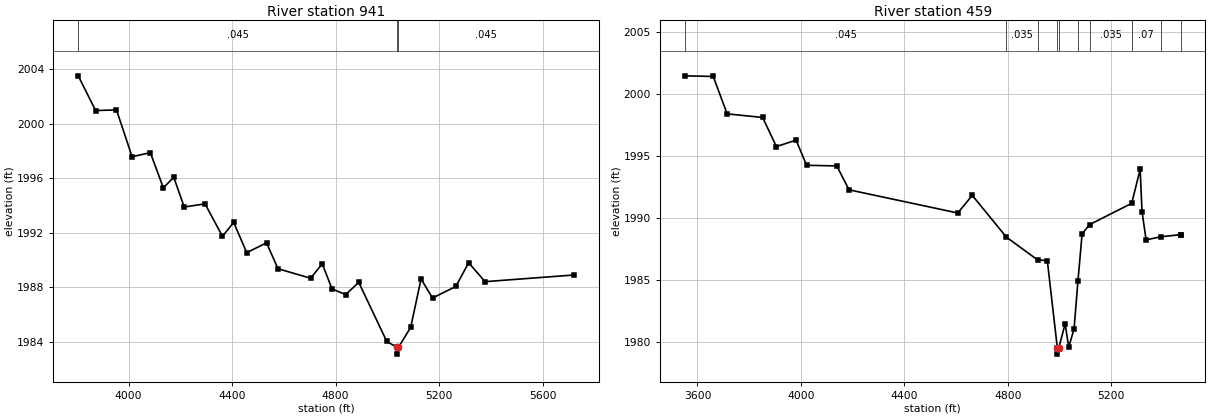
Type RM Length L Ch R = 1,941,482,482,482
BEGIN DESCRIPTION:
UCFB HW Trib 08 2.0
END DESCRIPTION:
XS GIS Cut Line= 4
      1343263.99      6976674.84      1343405.00      6975488.00
      1343397.39      6975316.14      1342984.21      6974953.30
#Sta/Elev= 30
  3805.2 2003.52  3872.5 2000.97  3953.1 2001.02  4013.5 1997.58  4084.0 1997.88
  4134.3 1995.30  4174.6 1996.07  4214.9 1993.89  4295.5 1994.12  4362.8 1991.74
  4406.2 1992.76  4456.6 1990.54  4533.2 1991.26  4577.4 1989.36  4703.5 1988.66
  4748.6 1989.72  4786.2 1987.88  4839.3 1987.46  4889.6 1988.36  4997.9 1984.02
  5037.6 1983.59  5038.1 1983.09  5043.2 1983.59  5090.5 1985.06  5130.5 1988.61
  5174.8 1987.21  5265.1 1988.06  5314.4 1989.80  5378.0 1988.41  5722.3 1988.90
#Mann=3,-1,0
  3805.2   0.045       0  5037.6   0.045       0  5043.2   0.045       0
Bank Sta=5037.6,5043.2
Exp/Cntr=0.3,0.1

Type RM Length L Ch R = 1,459,0,0,0
BEGIN DESCRIPTION:
UCFB HW Trib 08 1.0
END DESCRIPTION:
XS GIS Cut Line= 5
      1343486.23      6976772.01      1343883.50      6975659.89
      1343855.00      6975388.00      1343800.17      6975185.93
      1343579.01      6975059.80
#Sta/Elev= 30
  3550.5 2001.50  3660.9 2001.45  3714.8 1998.43  3852.1 1998.14  3905.2 1995.79
  3981.4 1996.31  4022.0 1994.28  4138.8 1994.23  4186.3 1992.30  4606.7 1990.43
  4663.0 1991.85  4795.0 1988.48  4915.8 1986.64  4953.2 1986.59  4991.9 1979.54
  4992.4 1979.04  4997.6 1979.54  5022.1 1981.49  5035.9 1979.61  5056.6 1981.06
  5071.8 1984.98  5087.7 1988.74  5117.0 1989.50  5279.6 1991.21  5312.3 1993.95
  5319.5 1990.54  5335.3 1988.26  5391.8 1988.51  5468.5 1988.68  5468.8 1988.69
#Mann=10,-1,0
  3550.5   0.045       0  4795.0   0.035       0  4915.8    0.16       0
  4991.9    0.07       0  4997.6    0.16       0  5071.8    0.07       0
  5117.0   0.035       0  5279.6    0.07       0  5391.8   0.045       0
  5468.5    0.07       0
Bank Sta=4991.9,4997.6
Exp/Cntr=0.3,0.1

Chan Stop Cuts=-1