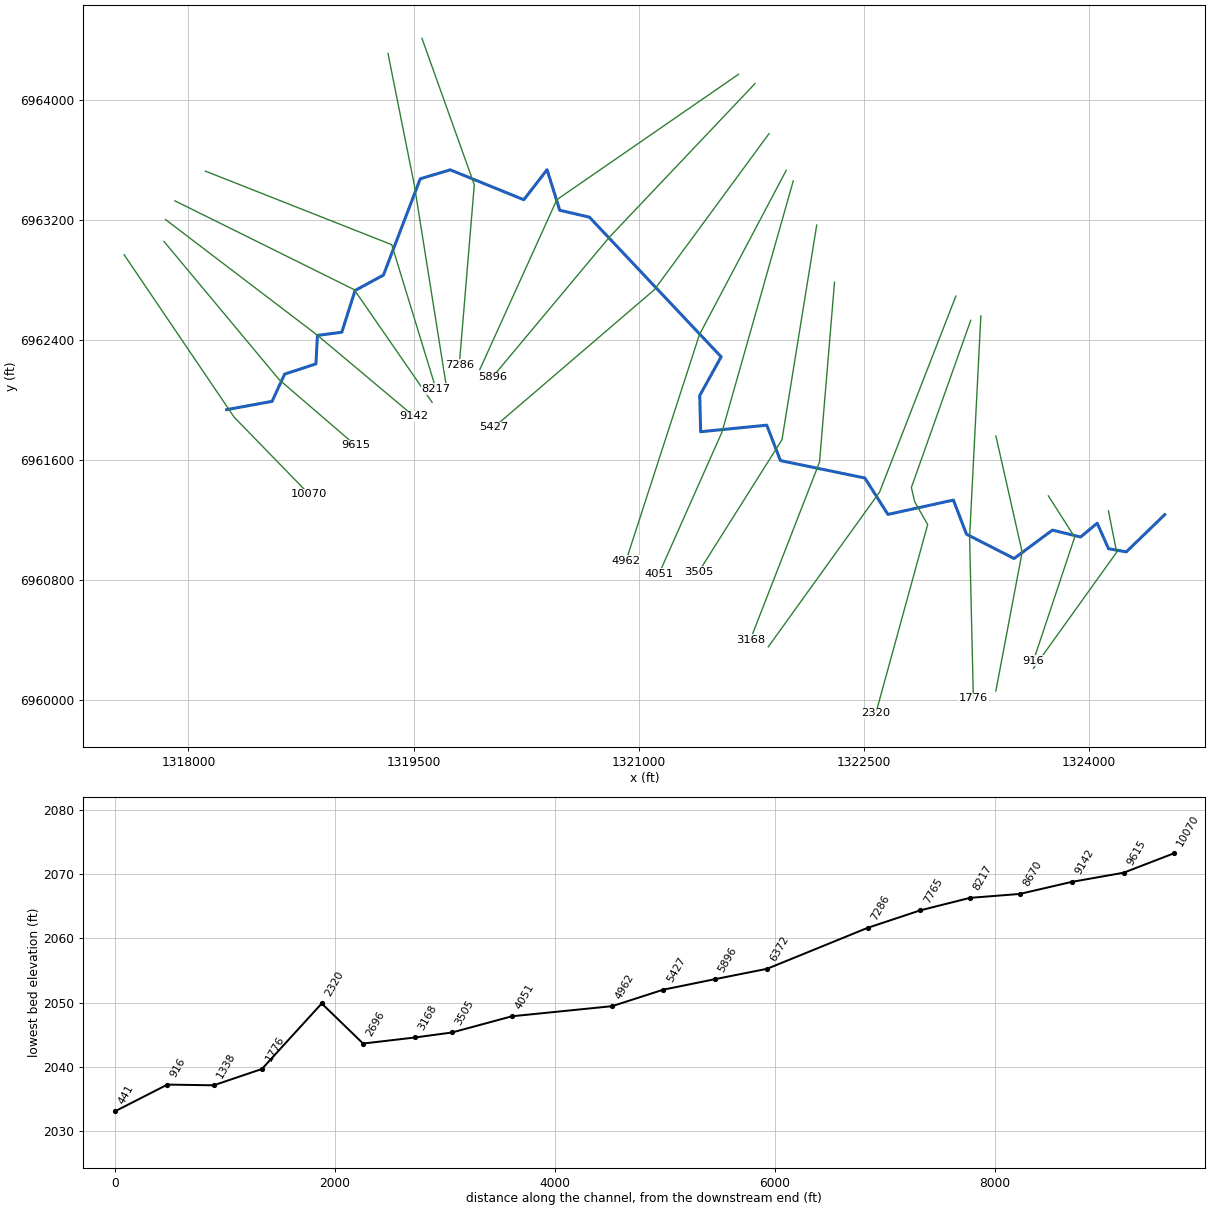
--- UCFB HW Trib 09.prj (project) ---

Proj Title=UCFB HW Trib 09 Base Level Engineering
Current Plan=p01
Default Exp/Contr=0.3,0.1
English Units
Geom File=g01
Flow File=f01
Plan File=p01
BEGIN DESCRIPTION:
UCFB HW Trib 09
END DESCRIPTION:

--- UCFB HW Trib 09.p01 (plan) ---

Plan Title=Multiple Run
Short Identifier=Multiple
Geom File=g01
Flow File=f01
Subcritical Flow
K Sum by GR= 0
Std Step Tol= 0.01
Critical Tol= 0.01
Num of Std Step Trials= 20
Max Error Tol= 0.3
Flow Tol Ratio= 0.001
Split Flow NTrial= 30
Split Flow Tol= 0.02
Split Flow Ratio= 0.02
Log Output Level= 0
Friction Slope Method= 1
Unsteady Friction Slope Method= 2
Unsteady Bridges Friction Slope Method= 1
Parabolic Critical Depth
Global Vel Dist=  1 , 1 , 1
Global Log Level= 0
CheckData=True
Encroach Param= -1, 0, 0, 0
BEGIN DESCRIPTION:
Multiple Run
END DESCRIPTION:

--- UCFB HW Trib 09.f01 (steady flow) ---

Flow Title=Multiple
Number of Profiles=7
Profile Names=10-year,25-year,50-year,1pct_min,100-year,1pct_plu,500-year
River Rch & RM= UCFB HW Trib 09,Reach-1,10070
     353     509     641     402     803    1601    1273
River Rch & RM= UCFB HW Trib 09,Reach-1,4051
     536     787    1006     638    1273    2539    2066
Boundary for River Rch & Prof#=UCFB HW Trib 09,Reach-1,1
Up Type=0
Dn Type=3
Dn Slope=0.005
Boundary for River Rch & Prof#=UCFB HW Trib 09,Reach-1,2
Up Type=0
Dn Type=3
Dn Slope=0.005
Boundary for River Rch & Prof#=UCFB HW Trib 09,Reach-1,3
Up Type=0
Dn Type=3
Dn Slope=0.005
Boundary for River Rch & Prof#=UCFB HW Trib 09,Reach-1,4
Up Type=0
Dn Type=3
Dn Slope=0.005
Boundary for River Rch & Prof#=UCFB HW Trib 09,Reach-1,5
Up Type=0
Dn Type=3
Dn Slope=0.005
Boundary for River Rch & Prof#=UCFB HW Trib 09,Reach-1,6
Up Type=0
Dn Type=3
Dn Slope=0.005
Boundary for River Rch & Prof#=UCFB HW Trib 09,Reach-1,7
Up Type=0
Dn Type=3
Dn Slope=0.005

--- UCFB HW Trib 09.g01 (geometry) ---

Geom Title=Existing Conditions

River Reach=UCFB HW Trib 09,Reach-1
Reach XY= 30
      1318255.00      6961938.00      1318557.73      6961993.35
      1318641.28      6962174.77      1318849.83      6962243.41
      1318860.00      6962432.99      1319022.22      6962454.24
      1319110.58      6962732.42      1319299.63      6962835.31
      1319544.94      6963477.39      1319744.52      6963537.06
      1320235.06      6963337.73      1320389.78      6963537.88
      1320474.40      6963267.34      1320671.76      6963221.57
      1321549.60      6962290.43      1321407.06      6962032.15
      1321412.91      6961790.91      1321853.53      6961834.54
      1321944.76      6961598.34      1322507.31      6961482.18
      1322660.83      6961239.53      1323097.03      6961335.07
      1323184.45      6961107.44      1323501.43      6960945.53
      1323756.64      6961134.86      1323944.52      6961088.95
      1324055.03      6961180.92      1324130.59      6961010.84
      1324249.10      6960989.96      1324505.00      6961238.00

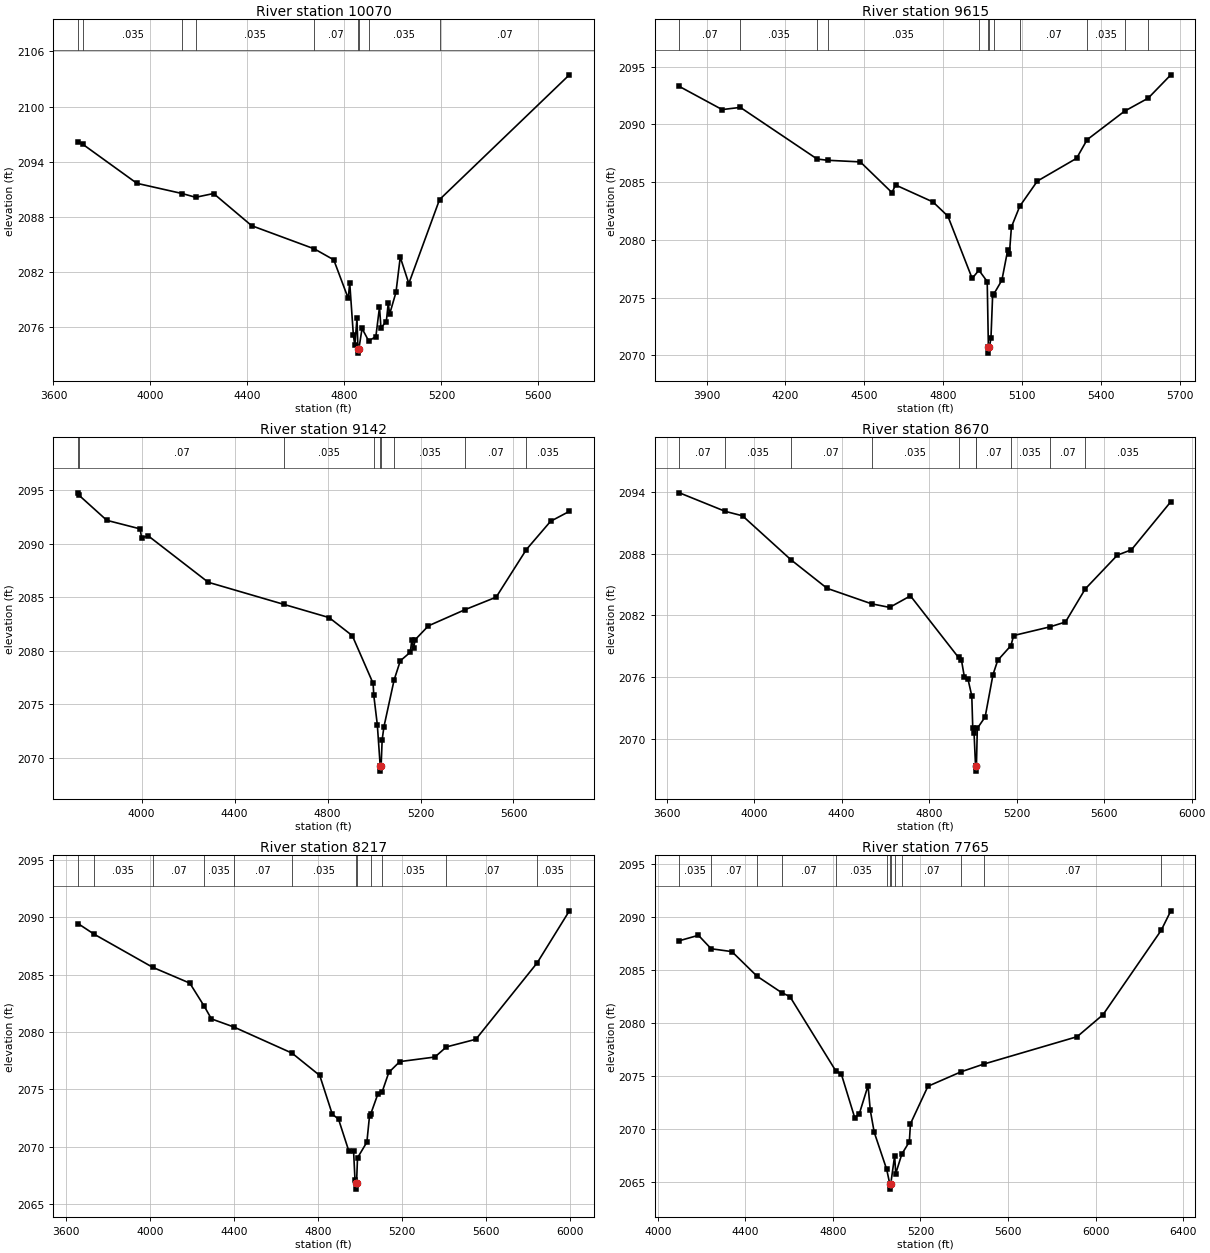
Type RM Length L Ch R = 1,10070,455,455,455
BEGIN DESCRIPTION:
UCFB HW Trib 09 20.0
END DESCRIPTION:
XS GIS Cut Line= 3
      1317571.83      6962971.11      1318305.00      6961888.00
      1318805.81      6961372.56
#Sta/Elev= 30
  3701.3 2096.20  3721.9 2095.89  3944.2 2091.66  4130.6 2090.55  4186.5 2090.14
  4260.5 2090.55  4417.6 2087.05  4676.0 2084.53  4756.1 2083.34  4815.9 2079.14
  4822.0 2080.85  4836.9 2075.19  4843.0 2074.02  4851.9 2076.96  4855.9 2073.69
  4856.2 2073.19  4859.9 2073.69  4872.9 2075.87  4900.3 2074.51  4929.8 2074.99
  4944.8 2078.19  4950.8 2075.95  4973.0 2076.63  4980.8 2078.60  4986.8 2077.45
  5012.7 2079.80  5030.4 2083.63  5065.7 2080.76  5192.4 2089.89  5727.9 2103.46
#Mann=9,-1,0
  3701.3    0.07       0  3721.9   0.035       0  4130.6    0.07       0
  4186.5   0.035       0  4676.0    0.07       0  4855.9   0.035       0
  4859.9    0.07       0  4900.3   0.035       0  5192.4    0.07       0
Bank Sta=4855.9,4859.9
Exp/Cntr=0.3,0.1

Type RM Length L Ch R = 1,9615,473,473,473
BEGIN DESCRIPTION:
UCFB HW Trib 09 19.0
END DESCRIPTION:
XS GIS Cut Line= 3
      1317837.48      6963059.61      1318605.00      6962138.00
      1319113.49      6961700.28
#Sta/Elev= 30
  3796.6 2093.28  3959.1 2091.28  4028.3 2091.47  4320.5 2087.00  4360.4 2086.89
  4485.0 2086.75  4605.5 2084.09  4619.1 2084.75  4761.7 2083.28  4818.3 2082.05
  4910.7 2076.66  4936.4 2077.37  4968.0 2076.39  4972.5 2070.69  4972.7 2070.19
  4976.5 2070.69  4982.3 2071.52  4988.8 2075.30  4992.1 2075.26  5023.9 2076.51
  5045.9 2079.10  5052.5 2078.81  5060.1 2081.11  5091.9 2082.91  5158.9 2085.09
  5308.1 2087.06  5348.2 2088.67  5490.6 2091.14  5580.7 2092.27  5666.9 2094.29
#Mann=12,-1,0
  3796.6    0.07       0  4028.3   0.035       0  4320.5    0.07       0
  4360.4   0.035       0  4936.4    0.07       0  4972.5   0.035       0
  4976.5    0.07       0  4992.1   0.035       0  5091.9    0.07       0
  5348.2   0.035       0  5490.6    0.07       0  5580.7   0.035       0
Bank Sta=4972.5,4976.5
Exp/Cntr=0.3,0.1

Type RM Length L Ch R = 1,9142,472,472,472
BEGIN DESCRIPTION:
UCFB HW Trib 09 18.0
END DESCRIPTION:
XS GIS Cut Line= 3
      1317847.90      6963205.46      1318855.00      6962438.00
      1319504.14      6961892.97
#Sta/Elev= 30
  3726.6 2094.77  3730.7 2094.55  3850.6 2092.20  3993.9 2091.40  4000.2 2090.57
  4029.3 2090.74  4287.0 2086.41  4612.9 2084.34  4806.8 2083.11  4906.6 2081.42
  4996.1 2076.96  4999.0 2075.85  5014.2 2073.10  5026.6 2069.26  5026.8 2068.76
  5030.6 2069.26  5035.1 2071.71  5042.9 2072.93  5086.6 2077.29  5113.1 2079.07
  5156.0 2079.87  5162.6 2081.01  5170.3 2080.27  5176.9 2081.04  5234.1 2082.34
  5392.6 2083.86  5525.5 2085.02  5655.4 2089.47  5759.6 2092.11  5840.4 2093.04
#Mann=9,-1,0
  3726.6   0.035       0  3730.7    0.07       0  4612.9   0.035       0
  4999.0    0.07       0  5026.6    0.07       0  5030.6    0.07       0
  5086.6   0.035       0  5392.6    0.07       0  5655.4   0.035       0
Bank Sta=5026.6,5030.6
Exp/Cntr=0.3,0.1

Type RM Length L Ch R = 1,8670,453,453,453
BEGIN DESCRIPTION:
UCFB HW Trib 09 17.0
END DESCRIPTION:
XS GIS Cut Line= 3
      1317910.41      6963330.46      1319105.00      6962738.00
      1319623.92      6961986.73
#Sta/Elev= 30
  3658.3 2093.90  3867.9 2092.10  3946.6 2091.67  4168.2 2087.40  4333.3 2084.63
  4536.6 2083.13  4619.1 2082.78  4714.3 2083.90  4934.1 2077.92  4947.1 2077.72
  4960.9 2076.03  4977.7 2075.79  4994.8 2074.19  4999.2 2071.10  5005.2 2070.57
  5012.0 2067.39  5012.3 2066.89  5016.0 2067.39  5020.1 2071.04  5055.9 2072.15
  5091.8 2076.26  5113.3 2077.64  5173.7 2079.07  5186.2 2080.05  5351.8 2080.89
  5423.0 2081.36  5513.4 2084.57  5660.2 2087.85  5724.5 2088.37  5904.8 2093.04
#Mann=10,-1,0
  3658.3    0.07       0  3867.9   0.035       0  4168.2    0.07       0
  4536.6   0.035       0  4934.1    0.07       0  5012.0    0.07       0
  5016.0    0.07       0  5173.7   0.035       0  5351.8    0.07       0
  5513.4   0.035       0
Bank Sta=5012,5016
Exp/Cntr=0.3,0.1

Type RM Length L Ch R = 1,8217,452,452,452
BEGIN DESCRIPTION:
UCFB HW Trib 09 16.0
END DESCRIPTION:
XS GIS Cut Line= 3
      1318113.51      6963528.39      1319355.00      6963038.00
      1319649.95      6962075.30
#Sta/Elev= 30
  3656.8 2089.46  3732.9 2088.54  4012.9 2085.64  4189.6 2084.26  4259.2 2082.22
  4292.5 2081.14  4398.3 2080.44  4676.8 2078.15  4808.9 2076.20  4868.6 2072.82
  4898.3 2072.39  4947.0 2069.63  4970.1 2069.61  4976.8 2067.11  4980.1 2066.78
  4980.3 2066.28  4984.2 2066.78  4988.9 2069.01  5033.5 2070.38  5046.0 2072.66
  5051.9 2072.84  5085.8 2074.58  5106.3 2074.77  5138.1 2076.47  5190.3 2077.41
  5357.7 2077.81  5412.3 2078.69  5553.0 2079.36  5845.1 2086.03  5998.5 2090.57
#Mann=12,-1,0
  3656.8    0.07       0  3732.9   0.035       0  4012.9    0.07       0
  4259.2   0.035       0  4398.3    0.07       0  4676.8   0.035       0
  4980.1   0.035       0  4984.2   0.035       0  5051.9    0.07       0
  5106.3   0.035       0  5412.3    0.07       0  5845.1   0.035       0
Bank Sta=4980.1,4984.2
Exp/Cntr=0.3,0.1

Type RM Length L Ch R = 1,7765,479,479,479
BEGIN DESCRIPTION:
UCFB HW Trib 09 15.0
END DESCRIPTION:
XS GIS Cut Line= 3
      1319330.00      6964312.98      1319505.00      6963438.00
      1319717.54      6962102.11
#Sta/Elev= 30
  4099.0 2087.79  4185.7 2088.30  4243.8 2087.03  4338.6 2086.76  4453.4 2084.44
  4565.8 2082.89  4603.8 2082.51  4813.3 2075.50  4838.3 2075.22  4899.5 2071.10
  4919.9 2071.40  4960.7 2074.11  4970.9 2071.78  4988.8 2069.71  5045.7 2066.21
  5059.9 2064.84  5060.2 2064.34  5064.5 2064.84  5082.2 2067.49  5087.1 2065.80
  5114.8 2067.64  5149.3 2068.81  5154.4 2070.51  5234.3 2074.05  5386.3 2075.42
  5488.7 2076.14  5916.0 2078.73  6034.3 2080.81  6299.9 2088.77  6344.0 2090.61
#Mann=13,-1,0
  4099.0   0.035       0  4243.8    0.07       0  4453.4   0.035       0
  4565.8    0.07       0  4813.3   0.035       0  5045.7    0.07       0
  5059.9   0.035       0  5064.5    0.07       0  5082.2   0.035       0
  5114.8    0.07       0  5386.3   0.035       0  5488.7    0.07       0
  6299.9   0.035       0
Bank Sta=5059.9,5064.5
Exp/Cntr=0.3,0.1

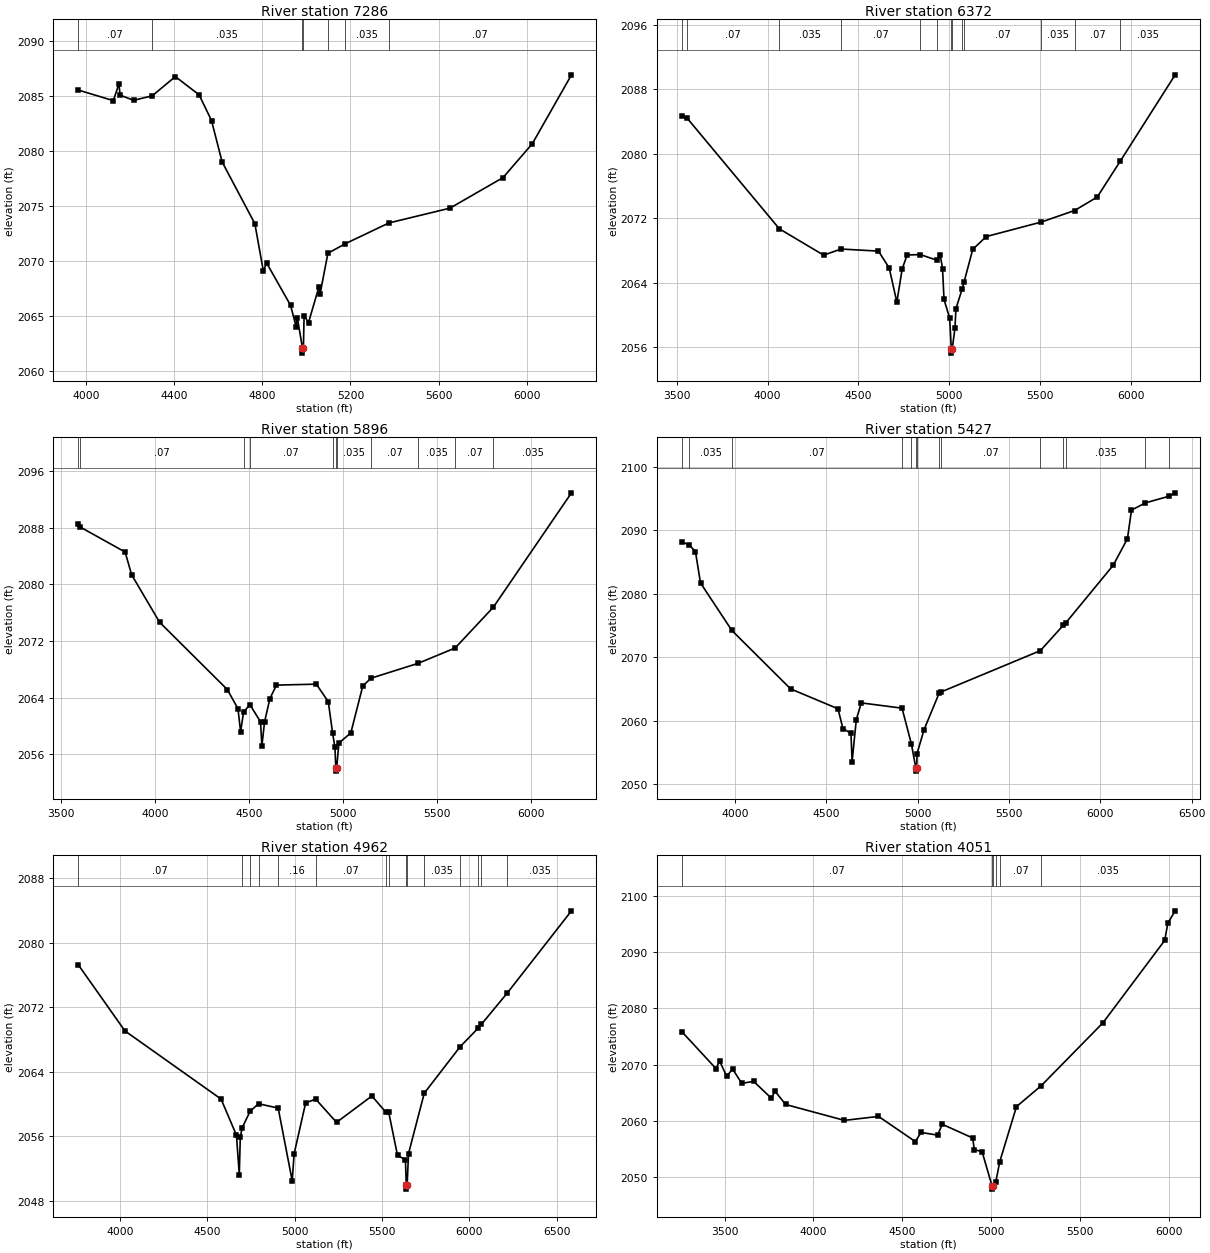
Type RM Length L Ch R = 1,7286,914,914,914
BEGIN DESCRIPTION:
UCFB HW Trib 09 14.0
END DESCRIPTION:
XS GIS Cut Line= 3
      1319556.21      6964413.81      1319905.00      6963438.00
      1319805.00      6962238.03
#Sta/Elev= 30
  3963.3 2085.58  4123.3 2084.61  4148.8 2086.13  4154.1 2085.11  4215.6 2084.64
  4300.0 2085.05  4404.9 2086.80  4512.9 2085.14  4569.1 2082.80  4617.3 2079.03
  4765.9 2073.41  4804.8 2069.07  4819.0 2069.84  4927.9 2065.98  4953.4 2064.04
  4958.7 2064.86  4981.9 2062.12  4982.2 2061.62  4986.5 2062.12  4989.5 2065.04
  5009.6 2064.40  5057.3 2067.68  5062.3 2067.02  5097.6 2070.71  5177.4 2071.59
  5374.3 2073.47  5651.8 2074.82  5892.7 2077.60  6025.6 2080.68  6203.7 2086.96
#Mann=7,-1,0
  3963.3    0.07       0  4300.0   0.035       0  4981.9   0.035       0
  4986.5   0.035       0  5097.6    0.07       0  5177.4   0.035       0
  5374.3    0.07       0
Bank Sta=4981.9,4986.5
Exp/Cntr=0.3,0.1

Type RM Length L Ch R = 1,6372,476,476,476
BEGIN DESCRIPTION:
UCFB HW Trib 09 13.0
END DESCRIPTION:
XS GIS Cut Line= 3
      1321665.60      6964174.24      1320455.00      6963338.00
      1319941.62      6962205.47
#Sta/Elev= 30
  3527.6 2084.71  3554.3 2084.50  4064.5 2070.69  4308.1 2067.42  4404.2 2068.18
  4610.0 2067.92  4669.1 2065.83  4711.0 2061.58  4740.7 2065.75  4768.0 2067.44
  4840.5 2067.49  4932.3 2066.78  4949.6 2067.44  4962.5 2065.76  4970.6 2061.92
  5001.7 2059.60  5010.9 2055.76  5011.2 2055.26  5015.6 2055.76  5030.8 2058.35
  5036.3 2060.78  5070.0 2063.19  5081.5 2064.14  5128.7 2068.14  5203.4 2069.73
  5506.1 2071.53  5689.1 2072.96  5813.6 2074.63  5939.7 2079.06  6242.4 2089.80
#Mann=13,-1,0
  3527.6   0.035       0  3554.3    0.07       0  4064.5   0.035       0
  4404.2    0.07       0  4840.5   0.035       0  4932.3    0.07       0
  5010.9    0.07       0  5015.6    0.07       0  5070.0   0.035       0
  5081.5    0.07       0  5506.1   0.035       0  5689.1    0.07       0
  5939.7   0.035       0
Bank Sta=5010.9,5015.6
Exp/Cntr=0.3,0.1

Type RM Length L Ch R = 1,5896,469,469,469
BEGIN DESCRIPTION:
UCFB HW Trib 09 12.0
END DESCRIPTION:
XS GIS Cut Line= 3
      1321774.93      6964111.70      1320805.00      6963088.00
      1320024.94      6962153.38
#Sta/Elev= 30
  3589.8 2088.58  3602.4 2088.09  3840.1 2084.58  3875.3 2081.35  4023.7 2074.67
  4384.6 2065.16  4441.2 2062.46  4455.3 2059.21  4471.0 2061.96  4504.7 2063.03
  4561.3 2060.61  4568.6 2057.19  4582.8 2060.58  4611.1 2063.88  4646.3 2065.79
  4858.6 2065.92  4922.2 2063.45  4945.3 2059.01  4957.7 2056.99  4962.2 2054.14
  4962.6 2053.64  4967.0 2054.14  4978.8 2057.60  5042.3 2059.04  5106.1 2065.68
  5150.7 2066.77  5400.5 2068.86  5598.0 2071.03  5801.9 2076.81  6217.4 2092.94
#Mann=11,-1,0
  3589.8   0.035       0  3602.4    0.07       0  4471.0   0.035       0
  4504.7    0.07       0  4945.3   0.035       0  4962.2   0.035       0
  4967.0   0.035       0  5150.7    0.07       0  5400.5   0.035       0
  5598.0    0.07       0  5801.9   0.035       0
Bank Sta=4962.2,4967
Exp/Cntr=0.3,0.1

Type RM Length L Ch R = 1,5427,465,465,465
BEGIN DESCRIPTION:
UCFB HW Trib 09 11.0
END DESCRIPTION:
XS GIS Cut Line= 3
      1321868.72      6963778.41      1321105.00      6962738.00
      1320035.40      6961820.08
#Sta/Elev= 30
  3709.6 2088.22  3751.1 2087.70  3784.5 2086.66  3812.2 2081.71  3983.9 2074.21
  4305.5 2064.99  4564.6 2061.85  4591.6 2058.73  4635.6 2057.97  4641.8 2053.52
  4664.9 2060.15  4691.9 2062.78  4915.1 2061.95  4966.5 2056.27  4990.5 2052.51
  4990.8 2052.01  4995.3 2052.51  4997.1 2054.77  5035.9 2058.58  5117.4 2064.27
  5129.8 2064.52  5672.2 2071.03  5796.5 2075.00  5810.3 2075.38  6070.8 2084.51
  6148.7 2088.70  6170.7 2093.21  6246.9 2094.35  6374.2 2095.39  6409.7 2095.94
#Mann=14,-1,0
  3709.6    0.07       0  3751.1   0.035       0  3983.9    0.07       0
  4915.1   0.035       0  4966.5    0.07       0  4990.5    0.07       0
  4995.3    0.07       0  5117.4   0.035       0  5129.8    0.07       0
  5672.2   0.035       0  5796.5    0.07       0  5810.3   0.035       0
  6246.9    0.07       0  6374.2   0.035       0
Bank Sta=4990.5,4995.3
Exp/Cntr=0.3,0.1

Type RM Length L Ch R = 1,4962,911,911,911
BEGIN DESCRIPTION:
UCFB HW Trib 09 10.0
END DESCRIPTION:
XS GIS Cut Line= 3
      1321983.31      6963533.64      1321405.00      6962438.00
      1320916.16      6960931.21
#Sta/Elev= 30
  3760.9 2077.28  4029.0 2069.05  4578.9 2060.61  4667.0 2056.13  4683.2 2051.26
  4689.0 2055.89  4699.3 2057.03  4744.7 2059.08  4793.4 2060.03  4905.7 2059.49
  4986.0 2050.48  4997.0 2053.83  5062.9 2060.14  5120.5 2060.60  5239.6 2057.72
  5441.9 2060.99  5521.4 2058.99  5537.5 2059.05  5588.5 2053.62  5633.8 2053.10
  5638.7 2049.95  5639.0 2049.45  5643.5 2049.95  5651.6 2053.86  5741.6 2061.34
  5946.6 2067.09  6050.2 2069.40  6067.8 2069.85  6217.7 2073.78  6583.9 2083.93
#Mann=15,-1,0
  3760.9    0.07       0  4699.3    0.16       0  4744.7   0.035       0
  4793.4    0.07       0  4905.7    0.16       0  5120.5    0.07       0
  5521.4   0.035       0  5537.5    0.07       0  5638.7    0.07       0
  5643.5    0.07       0  5741.6   0.035       0  5946.6    0.07       0
  6050.2   0.035       0  6067.8    0.07       0  6217.7   0.035       0
Bank Sta=5638.7,5643.5
Exp/Cntr=0.3,0.1

Type RM Length L Ch R = 1,4051,546,546,546
BEGIN DESCRIPTION:
UCFB HW Trib 09 9.0
END DESCRIPTION:
XS GIS Cut Line= 3
      1322030.00      6963463.00      1321555.00      6961788.00
      1321134.81      6960841.97
#Sta/Elev= 30
  3258.9 2075.89  3451.2 2069.32  3472.0 2070.64  3511.9 2067.93  3544.7 2069.24
  3596.7 2066.68  3663.2 2067.04  3763.0 2064.05  3783.8 2065.29  3843.2 2062.93
  4174.4 2060.10  4365.9 2060.81  4573.5 2056.33  4605.0 2057.96  4698.5 2057.48
  4724.8 2059.41  4896.0 2056.97  4904.8 2054.92  4949.1 2054.51  5005.4 2048.38
  5005.9 2047.88  5012.2 2048.38  5026.1 2049.19  5048.4 2052.78  5142.2 2062.54
  5282.1 2066.29  5628.6 2077.44  5976.2 2092.09  5993.9 2095.16  6035.1 2097.36
#Mann=6,-1,0
  3258.9    0.07       0  5005.4    0.07       0  5012.2    0.07       0
  5026.1    0.16       0  5048.4    0.07       0  5282.1   0.035       0
Bank Sta=5005.4,5012.2
Exp/Cntr=0.3,0.1

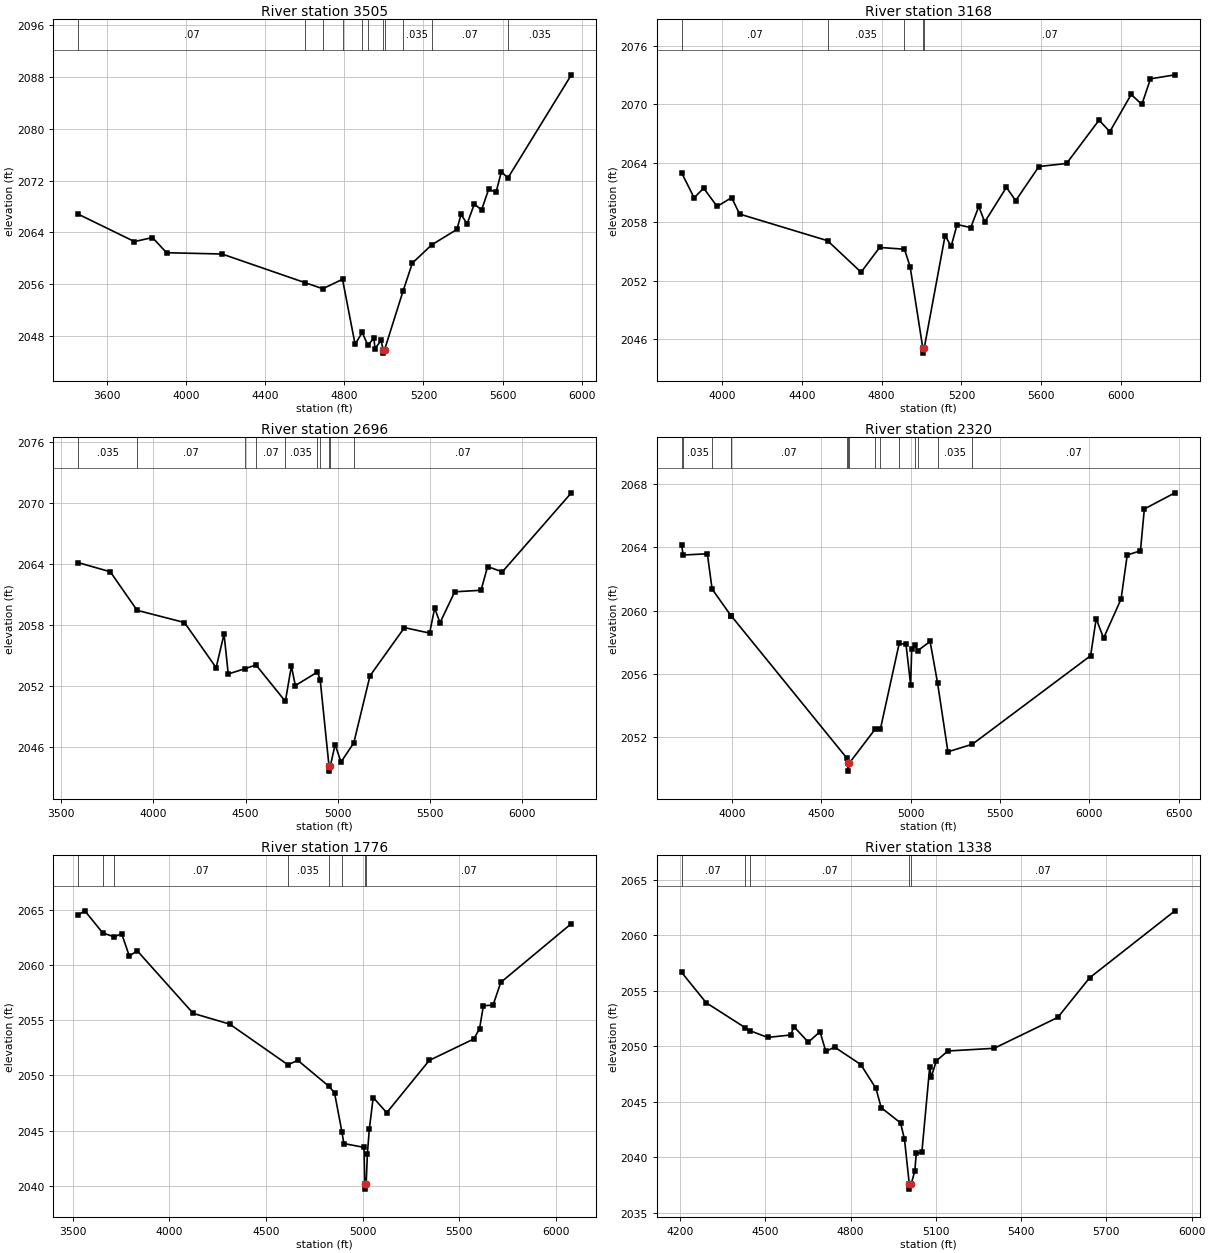
Type RM Length L Ch R = 1,3505,337,337,337
BEGIN DESCRIPTION:
UCFB HW Trib 09 8.0
END DESCRIPTION:
XS GIS Cut Line= 3
      1322186.41      6963168.98      1321955.00      6961738.00
      1321399.98      6960856.56
#Sta/Elev= 30
  3455.9 2066.82  3740.5 2062.58  3831.7 2063.20  3902.6 2060.86  4183.1 2060.66
  4603.5 2056.22  4691.7 2055.30  4791.3 2056.76  4854.8 2046.73  4890.9 2048.55
  4919.7 2046.55  4949.6 2047.69  4955.5 2046.05  4986.1 2047.33  4996.6 2045.86
  4997.1 2045.36  5003.5 2045.86  5097.4 2054.97  5143.9 2059.25  5241.5 2062.07
  5368.8 2064.45  5390.0 2066.76  5420.6 2065.32  5457.0 2068.38  5493.5 2067.46
  5530.0 2070.70  5566.5 2070.16  5593.6 2073.37  5626.5 2072.39  5947.1 2088.32
#Mann=11,-1,0
  3455.9    0.07       0  4603.5   0.035       0  4691.7    0.07       0
  4791.3   0.035       0  4890.9    0.07       0  4919.7    0.16       0
  4996.6    0.07       0  5003.5    0.16       0  5097.4   0.035       0
  5241.5    0.07       0  5626.5   0.035       0
Bank Sta=4996.6,5003.5
Exp/Cntr=0.3,0.1

Type RM Length L Ch R = 1,3168,472,472,472
BEGIN DESCRIPTION:
UCFB HW Trib 09 7.0
END DESCRIPTION:
XS GIS Cut Line= 3
      1322305.00      6962788.03      1322205.00      6961588.00
      1321743.72      6960403.43
#Sta/Elev= 30
  3796.2 2063.01  3858.9 2060.45  3906.6 2061.44  3974.3 2059.57  4047.1 2060.47
  4087.2 2058.79  4528.4 2056.07  4696.8 2052.85  4789.7 2055.38  4914.2 2055.20
  4942.7 2053.42  5006.5 2045.08  5007.0 2044.58  5013.4 2045.08  5118.4 2056.60
  5148.6 2055.49  5178.5 2057.72  5247.2 2057.41  5287.3 2059.57  5317.1 2057.98
  5425.9 2061.52  5472.6 2060.16  5589.1 2063.65  5727.7 2063.96  5890.9 2068.39
  5944.8 2067.21  6052.1 2071.01  6105.7 2070.00  6149.0 2072.61  6271.6 2073.02
#Mann=5,-1,0
  3796.2    0.07       0  4528.4   0.035       0  4914.2    0.07       0
  5006.5    0.07       0  5013.4    0.07       0
Bank Sta=5006.5,5013.4
Exp/Cntr=0.3,0.1

Type RM Length L Ch R = 1,2696,376,376,376
BEGIN DESCRIPTION:
UCFB HW Trib 09 6.0
END DESCRIPTION:
XS GIS Cut Line= 3
      1323113.50      6962695.06      1322605.00      6961388.00
      1321863.52      6960356.55
#Sta/Elev= 30
  3592.7 2064.14  3767.2 2063.24  3912.5 2059.45  4169.0 2058.25  4340.7 2053.81
  4383.6 2057.12  4406.3 2053.19  4495.3 2053.70  4556.7 2054.08  4715.8 2050.50
  4748.4 2053.96  4769.9 2052.05  4889.6 2053.38  4904.4 2052.63  4952.3 2044.14
  4952.8 2043.64  4959.2 2044.14  4985.6 2046.25  5017.3 2044.53  5086.6 2046.42
  5174.4 2053.01  5361.0 2057.75  5497.3 2057.21  5524.8 2059.66  5553.8 2058.23
  5633.5 2061.27  5776.0 2061.42  5811.6 2063.75  5891.4 2063.23  6265.5 2071.00
#Mann=10,-1,0
  3592.7   0.035       0  3912.5    0.07       0  4495.3   0.035       0
  4556.7    0.07       0  4715.8   0.035       0  4889.6    0.07       0
  4904.4    0.16       0  4952.3    0.07       0  4959.2    0.16       0
  5086.6    0.07       0
Bank Sta=4952.3,4959.2
Exp/Cntr=0.3,0.1

Type RM Length L Ch R = 1,2320,544,544,544
BEGIN DESCRIPTION:
UCFB HW Trib 09 5.0
END DESCRIPTION:
XS GIS Cut Line= 5
      1323212.46      6962533.63      1322817.06      6961419.00
      1322839.64      6961322.64      1322925.57      6961171.61
      1322580.00      6959913.00
#Sta/Elev= 30
  3718.1 2064.15  3726.5 2063.52  3862.0 2063.60  3888.6 2061.37  3993.6 2059.70
  3994.2 2059.70  4641.2 2050.71  4649.1 2050.37  4649.6 2049.87  4656.1 2050.37
  4802.3 2052.54  4829.9 2052.50  4935.7 2057.94  4973.7 2057.87  4999.6 2055.33
  5005.7 2057.60  5022.8 2057.82  5039.5 2057.48  5108.6 2058.06  5150.3 2055.44
  5208.4 2051.09  5345.1 2051.57  6006.9 2057.16  6038.0 2059.50  6079.5 2058.27
  6177.3 2060.74  6211.7 2063.52  6285.8 2063.79  6307.6 2066.43  6478.7 2067.45
#Mann=15,-1,0
  3718.1   0.045       0  3726.5   0.035       0  3888.6    0.07       0
  3993.6   0.035       0  3994.2    0.07       0  4641.2   0.035       0
  4649.1    0.07       0  4656.1   0.035       0  4802.3    0.07       0
  4829.9   0.035       0  4935.7    0.07       0  5022.8   0.035       0
  5039.5    0.07       0  5150.3   0.035       0  5345.1    0.07       0
Bank Sta=4649.1,4656.1
Exp/Cntr=0.3,0.1

Type RM Length L Ch R = 1,1776,438,438,438
BEGIN DESCRIPTION:
UCFB HW Trib 09 4.0
END DESCRIPTION:
XS GIS Cut Line= 3
      1323280.00      6962562.96      1323205.00      6961088.00
      1323230.00      6960012.96
#Sta/Elev= 30
  3527.1 2064.52  3562.1 2064.90  3654.4 2062.90  3714.1 2062.54  3752.4 2062.84
  3792.4 2060.79  3832.5 2061.29  4122.8 2055.61  4311.4 2054.64  4613.2 2050.95
  4663.5 2051.36  4823.9 2049.02  4853.8 2048.42  4891.8 2044.91  4902.2 2043.82
  5006.5 2043.47  5010.3 2040.19  5010.8 2039.69  5017.7 2040.19  5024.0 2042.91
  5034.0 2045.14  5054.0 2047.99  5124.0 2046.61  5344.1 2051.35  5574.1 2053.29
  5604.1 2054.21  5624.1 2056.30  5674.1 2056.36  5714.2 2058.42  6079.3 2063.74
#Mann=8,-1,0
  3527.1   0.045       0  3654.4   0.035       0  3714.1    0.07       0
  4613.2   0.035       0  4823.9    0.16       0  4891.8    0.07       0
  5010.3    0.07       0  5017.7    0.07       0
Bank Sta=5010.3,5017.7
Exp/Cntr=0.3,0.1

Type RM Length L Ch R = 1,1338,422,422,422
BEGIN DESCRIPTION:
UCFB HW Trib 09 3.0
END DESCRIPTION:
XS GIS Cut Line= 3
      1323380.01      6961762.96      1323555.00      6960988.00
      1323380.00      6960062.98
#Sta/Elev= 30
  4205.3 2056.65  4291.7 2053.92  4428.1 2051.69  4445.2 2051.41  4507.7 2050.80
  4589.7 2051.02  4599.9 2051.78  4651.2 2050.37  4692.2 2051.32  4712.7 2049.54
  4743.5 2049.93  4835.7 2048.36  4889.2 2046.21  4907.5 2044.48  4975.6 2043.11
  4989.5 2041.64  5006.2 2037.65  5006.7 2037.15  5013.7 2037.65  5025.9 2038.80
  5031.0 2040.38  5050.7 2040.47  5078.3 2048.14  5083.4 2047.20  5101.5 2048.69
  5142.2 2049.58  5305.1 2049.82  5529.0 2052.60  5640.9 2056.16  5941.2 2062.19
#Mann=5,-1,0
  4205.3    0.07       0  4428.1   0.035       0  4445.2    0.07       0
  5006.2    0.07       0  5013.7    0.07       0
Bank Sta=5006.2,5013.7
Exp/Cntr=0.3,0.1

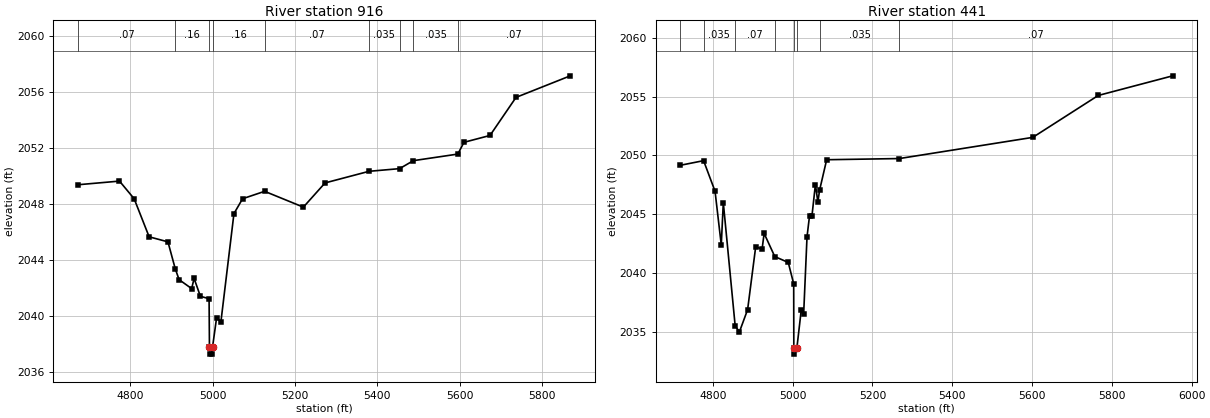
Type RM Length L Ch R = 1,916,475,475,475
BEGIN DESCRIPTION:
UCFB HW Trib 09 2.0
END DESCRIPTION:
XS GIS Cut Line= 3
      1323730.01      6961362.99      1323905.00      6961088.00
      1323629.99      6960262.97
#Sta/Elev= 30
  4673.2 2049.36  4773.9 2049.62  4809.5 2048.36  4845.9 2045.64  4891.6 2045.28
  4909.3 2043.36  4918.7 2042.58  4949.2 2041.94  4955.1 2042.67  4970.4 2041.39
  4991.5 2041.22  4992.4 2037.76  4992.9 2037.26  4999.4 2037.26  4999.9 2037.76
  5009.7 2039.85  5020.2 2039.56  5051.9 2047.30  5072.9 2048.36  5126.4 2048.89
  5220.5 2047.76  5273.2 2049.49  5380.1 2050.32  5454.2 2050.51  5487.6 2051.08
  5595.7 2051.55  5610.5 2052.39  5673.8 2052.88  5737.0 2055.60  5868.8 2057.14
#Mann=9,-1,0
  4673.2    0.07       0  4909.3    0.16       0  4992.4    0.07       0
  4999.9    0.16       0  5126.4    0.07       0  5380.1   0.035       0
  5454.2    0.07       0  5487.6   0.035       0  5595.7    0.07       0
Bank Sta=4992.4,4999.9
Exp/Cntr=0.3,0.1

Type RM Length L Ch R = 1,441,0,0,0
BEGIN DESCRIPTION:
UCFB HW Trib 09 1.0
END DESCRIPTION:
XS GIS Cut Line= 3
      1324129.99      6961263.03      1324184.78      6960987.32
      1323630.03      6960213.04
#Sta/Elev= 30
  4718.9 2049.17  4776.9 2049.56  4805.6 2046.96  4821.2 2042.40  4826.3 2045.99
  4856.1 2035.50  4866.8 2035.02  4887.2 2036.90  4907.5 2042.25  4923.5 2042.04
  4928.6 2043.38  4955.3 2041.41  4989.1 2040.91  5002.7 2039.09  5003.0 2033.62
  5003.5 2033.12  5010.6 2033.62  5021.5 2036.83  5027.6 2036.49  5036.1 2043.09
  5042.4 2044.88  5048.5 2044.88  5057.1 2047.53  5063.3 2046.04  5067.5 2047.04
  5085.3 2049.64  5267.4 2049.74  5601.9 2051.54  5765.8 2055.10  5952.5 2056.77
#Mann=8,-1,0
  4718.9    0.07       0  4776.9   0.035       0  4856.1    0.07       0
  4955.3    0.16       0  5003.0    0.07       0  5010.6    0.16       0
  5067.5   0.035       0  5267.4    0.07       0
Bank Sta=5003,5010.6
Exp/Cntr=0.3,0.1

Chan Stop Cuts=-1