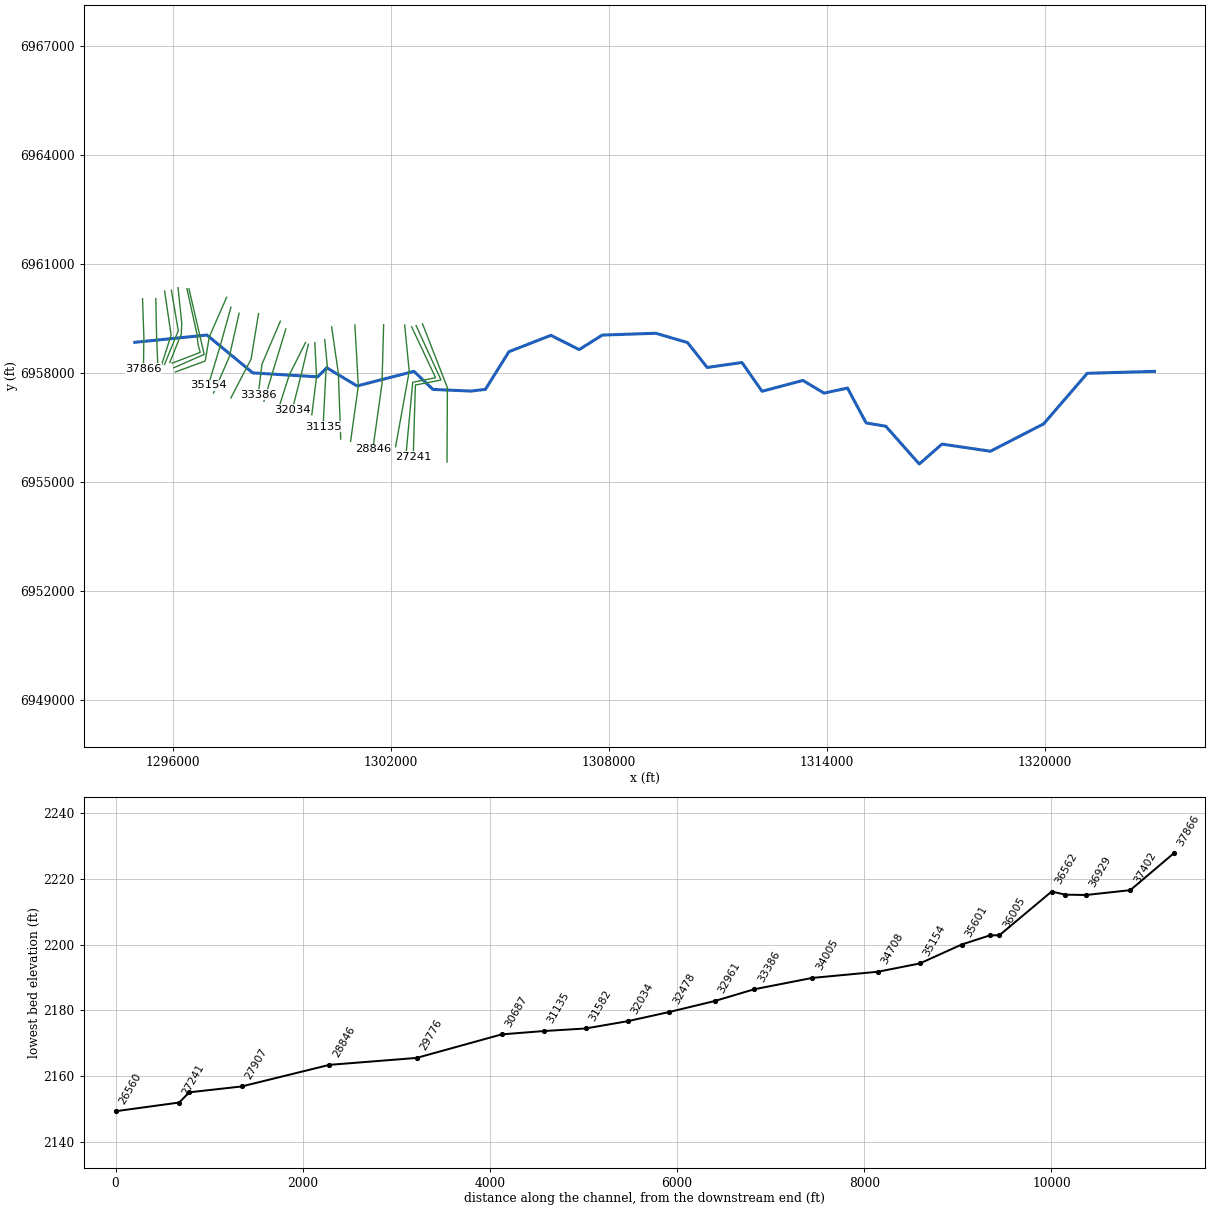
--- UCFB HW Trib 10.prj (project) ---

Proj Title=UCFB HW Trib 10 Base Level Engineering
Current Plan=p01
Default Exp/Contr=0.3,0.1
English Units
Geom File=g01
Flow File=f01
Plan File=p01
Y Axis Title=Elevation
X Axis Title(PF)=Main Channel Distance
X Axis Title(XS)=Station
BEGIN DESCRIPTION:
UCFB HW Trib 10
END DESCRIPTION:
DSS Export Rating Curves= 0
DSS Export Rating Curve Sorted= 0
DSS Export Volume Flow Curves= 0
DXF OffsetX= 0
DXF OffsetY= 0
DXF ScaleX= 1
DXF ScaleY= 10

--- UCFB HW Trib 10.p01 (plan) ---

Plan Title=Multiple Run
Short Identifier=Multiple
Geom File=g01
Flow File=f01
Subcritical Flow
K Sum by GR= 0
Std Step Tol= 0.01
Critical Tol= 0.01
Num of Std Step Trials= 20
Max Error Tol= 0.3
Flow Tol Ratio= 0.001
Split Flow NTrial= 30
Split Flow Tol= 0.02
Split Flow Ratio= 0.02
Log Output Level= 0
Friction Slope Method= 1
Unsteady Friction Slope Method= 2
Unsteady Bridges Friction Slope Method= 1
Parabolic Critical Depth
Global Vel Dist=  1 , 1 , 1
Global Log Level= 0
CheckData=True
Encroach Param= -1, 0, 0, 0
BEGIN DESCRIPTION:
Multiple Run
END DESCRIPTION:

--- UCFB HW Trib 10.f01 (steady flow) ---

Flow Title=Multiple
Program Version=4.10
Number of Profiles= 7
Profile Names=10-year,25-year,50-year,1pct_min,100-year,1pct_plu,500-year
River Rch & RM=UCFB HW Trib 10,Reach-1         ,37866
     313     451     568     357     712    1420    1131
River Rch & RM=UCFB HW Trib 10,Reach-1         ,35154
     451     659     839     531    1060    2114    1712
River Rch & RM=UCFB HW Trib 10,Reach-1         ,28846
     559     825    1058     674    1344    2681    2197
River Rch & RM=UCFB HW Trib 10,Reach-1         ,25186
     629     932    1198     765    1525    3044    2506
River Rch & RM=UCFB HW Trib 10,Reach-1         ,22404
     732    1091    1407     900    1796    3584    2968
River Rch & RM=UCFB HW Trib 10,Reach-1         ,18878
     780    1163    1501     961    1917    3824    3168
River Rch & RM=UCFB HW Trib 10,Reach-1         ,13779
     866    1296    1676    1074    2143    4275    3553
River Rch & RM=UCFB HW Trib 10,Reach-1         ,8739
    1044    1573    2043    1315    2623    5233    4384
River Rch & RM=UCFB HW Trib 10,Reach-1         ,4665
    1078    1623    2108    1356    2705    5397    4517
Boundary for River Rch & Prof#=UCFB HW Trib 10,Reach-1         , 1
Up Type= 0
Dn Type= 3
Dn Slope=0.002
Boundary for River Rch & Prof#=UCFB HW Trib 10,Reach-1         , 2
Up Type= 0
Dn Type= 3
Dn Slope=0.002
Boundary for River Rch & Prof#=UCFB HW Trib 10,Reach-1         , 3
Up Type= 0
Dn Type= 3
Dn Slope=0.002
Boundary for River Rch & Prof#=UCFB HW Trib 10,Reach-1         , 4
Up Type= 0
Dn Type= 3
Dn Slope=0.002
Boundary for River Rch & Prof#=UCFB HW Trib 10,Reach-1         , 5
Up Type= 0
Dn Type= 3
Dn Slope=0.002
Boundary for River Rch & Prof#=UCFB HW Trib 10,Reach-1         , 6
Up Type= 0
Dn Type= 3
Dn Slope=0.002
Boundary for River Rch & Prof#=UCFB HW Trib 10,Reach-1         , 7
Up Type= 0
Dn Type= 3
Dn Slope=0.002
DSS Import GetInterval= 0
DSS Import GetPeak= 0
DSS Import FillOption= 0

--- UCFB HW Trib 10.g01 (geometry) ---

Geom Title=Existing Conditions
Program Version=4.10

River Reach=UCFB HW Trib 10 ,Reach-1
Reach XY= 30
        1294955.        6958838.      1296939.78      6959037.76
      1298201.65      6957995.59      1299984.98      6957887.55
      1300234.85      6958138.48      1301070.32      6957637.51
      1302634.97      6958037.93      1303156.43      6957541.01
       1304205.1      6957495.28      1304599.97      6957542.92
      1305248.55      6958580.26      1306401.78      6959030.13
        1307180.      6958637.59      1307815.42      6959037.17
      1309289.16      6959087.35      1310161.38      6958830.63
      1310701.31       6958145.7      1311657.73      6958282.65
      1312210.93      6957490.24      1313334.95       6957788.6
       1313915.5       6957439.2      1314561.74      6957578.87
      1315074.44      6956617.45      1315614.81      6956527.57
      1316534.85      6955487.64      1317160.93      6956035.76
       1318494.5       6955839.2      1319957.71      6956593.28
      1321156.46      6957984.46        1323005.        6958038.

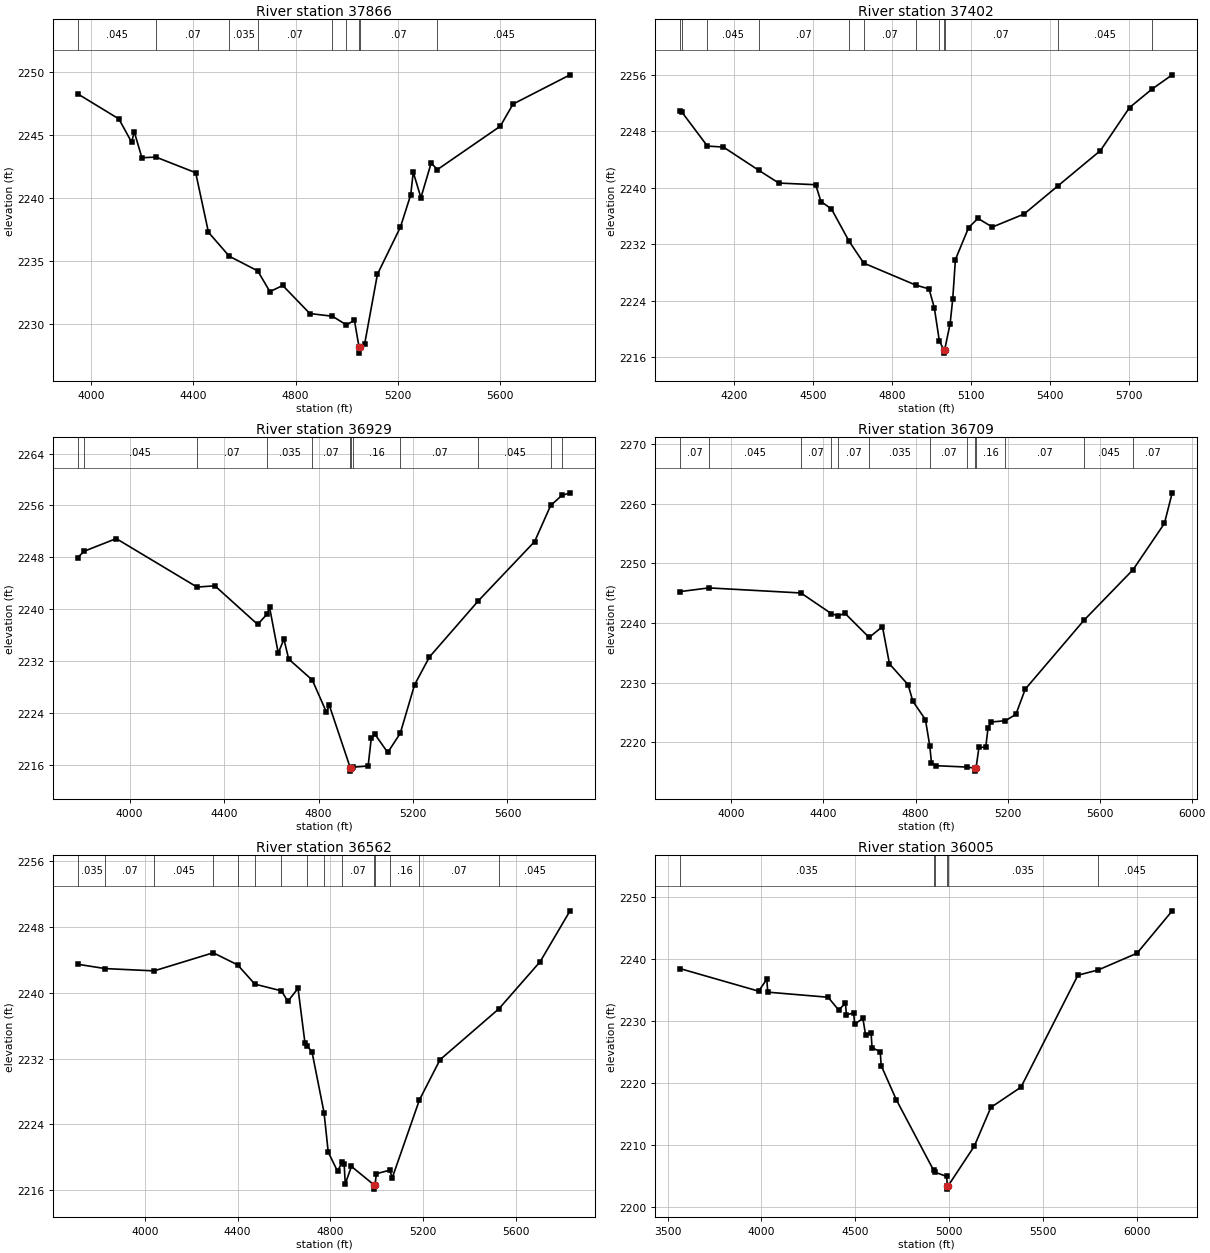
Type RM Length L Ch R = 1 ,37866   ,464,464,464
BEGIN DESCRIPTION:
UCFB HW Trib 10 65.0
END DESCRIPTION:
XS GIS Cut Line= 3
      1295168.25      6960037.97        1295205.        6958988.
      1295194.29      6958115.28
#Sta/Elev= 30
  3949.5 2248.29  4109.6 2246.31  4159.6 2244.46  4169.6  2245.3  4199.6 2243.23
  4254.6 2243.28  4409.8 2242.04  4459.8 2237.31  4541.2 2235.41  4652.2 2234.25
  4699.9  2232.6    4750 2233.09  4856.1 2230.86  4944.1 2230.65    4999 2229.96
  5030.1 2230.33  5048.1 2228.22  5048.4 2227.72  5052.1 2228.22  5070.1 2228.44
  5120.1 2233.98  5210.1 2237.73  5250.1 2240.28  5260.1 2242.08  5290.1 2240.06
  5330.1 2242.81  5354.6 2242.29  5600.2 2245.73  5650.2 2247.49  5872.9 2249.81
#Mann= 9 ,-1 , 0
  3949.5    .045       0  4254.6     .07       0  4541.2    .035       0
  4652.2     .07       0  4944.1    .035       0    4999     .07       0
  5048.1     .07       0  5052.1     .07       0  5354.6    .045       0
Bank Sta=5048.1,5052.1
XS Rating Curve= 0 ,0
Exp/Cntr=0.3,0.1

Type RM Length L Ch R = 1 ,37402   ,473,473,473
BEGIN DESCRIPTION:
UCFB HW Trib 10 64.0
END DESCRIPTION:
XS GIS Cut Line= 3
      1295532.83      6960042.36        1295555.        6959038.
      1295589.25      6958176.08
#Sta/Elev= 30
  3995.3 2250.84  4001.1 2250.77    4099  2245.9  4159.7 2245.76  4294.6 2242.45
  4369.7 2240.66  4509.8 2240.42  4529.8 2238.04  4569.8 2236.98  4636.7  2232.4
  4692.2 2229.31  4889.2  2226.2  4939.9 2225.65  4959.9 2222.99  4978.9 2218.29
  4995.4 2217.05  4995.7 2216.55  4999.4 2217.05  5019.9 2220.74  5029.9 2224.26
  5039.9 2229.81    5090 2234.34  5125.4 2235.65    5180 2234.42  5300.1 2236.26
  5427.7 2240.22  5590.4 2245.27  5700.5 2251.36  5785.9 2253.98  5862.5    2256
#Mann= 12 ,-1 , 0
  3995.3    .035       0  4001.1     .07       0    4099    .045       0
  4294.6     .07       0  4636.7    .035       0  4692.2     .07       0
  4889.2    .035       0  4978.9     .07       0  4995.4     .07       0
  4999.4     .07       0  5427.7    .045       0  5785.9    .035       0
Bank Sta=4995.4,4999.4
XS Rating Curve= 0 ,0
Exp/Cntr=0.3,0.1

Type RM Length L Ch R = 1 ,36929   ,220,220,220
BEGIN DESCRIPTION:
UCFB HW Trib 10 63.0
END DESCRIPTION:
XS GIS Cut Line= 3
      1295775.88       6960250.7        1295955.        6959038.
        1295694.      6958221.24
#Sta/Elev= 30
  3781.5 2247.98  3806.5 2248.93  3943.7  2250.9  4285.9 2243.43  4361.3 2243.63
  4542.4 2237.68  4581.4 2239.23  4592.9  2240.3  4629.6 2233.27  4653.6  2235.4
  4673.8 2232.34  4773.8 2229.11  4833.4 2224.17  4845.6 2225.24  4934.6 2215.58
  4934.8 2215.08  4938.6 2215.58  4944.1 2215.68    5010 2215.87  5023.4 2220.14
  5038.8 2220.76    5093 2217.95    5146  2220.9  5206.8 2228.39  5269.8 2232.67
    5477 2241.33  5714.8 2250.44  5782.9 2256.01  5829.9 2257.54  5864.8 2257.95
#Mann= 12 ,-1 , 0
  3781.5     .07       0  3806.5    .045       0  4285.9     .07       0
  4581.4    .035       0  4773.8     .07       0  4934.6     .07       0
  4938.6     .07       0  4944.1     .16       0    5146     .07       0
    5477    .045       0  5782.9     .07       0  5829.9    .035       0
Bank Sta=4934.6,4938.6
XS Rating Curve= 0 ,0
Exp/Cntr=0.3,0.1

Type RM Length L Ch R = 1 ,36709   ,147,147,147
BEGIN DESCRIPTION:
UCFB HW Trib 10 61.5
END DESCRIPTION:
XS GIS Cut Line= 3
      1295961.78      6960275.15      1296151.51      6959156.83
      1295772.97      6958226.49
#Sta/Elev= 30
  3776.8 2245.26  3902.1 2245.88    4302 2245.03  4433.7 2241.58  4462.2 2241.21
  4494.1  2241.6  4598.4 2237.58  4656.3 2239.39  4686.8 2233.15  4767.9 2229.64
  4788.2 2226.91  4843.1  2223.8    4862  2219.4  4869.3 2216.59  4889.6 2216.09
  5023.7 2215.86    5059 2215.68  5059.2 2215.18    5063 2215.68  5075.7 2219.18
  5105.2 2219.18    5115  2222.4  5129.3 2223.41    5191 2223.63  5236.3  2224.7
  5276.9 2228.92  5531.8 2240.45  5745.5 2248.94  5881.5 2256.68  5915.5 2261.81
#Mann= 13 ,-1 , 0
  3776.8     .07       0  3902.1    .045       0    4302     .07       0
  4433.7    .045       0  4462.2     .07       0  4598.4    .035       0
    4862     .07       0  5023.7     .16       0    5059     .07       0
    5063     .16       0    5191     .07       0  5531.8    .045       0
  5745.5     .07       0
Bank Sta=5059,5063
XS Rating Curve= 0 ,0
Exp/Cntr=0.3,0.1

Type RM Length L Ch R = 1 ,36562   ,557,557,557
BEGIN DESCRIPTION:
UCFB HW Trib 10 62.0
END DESCRIPTION:
XS GIS Cut Line= 5
      1296144.81      6960341.81      1296246.77      6959376.33
      1296234.84       6959058.5      1296187.74      6958957.93
      1295920.54      6958287.25
#Sta/Elev= 30
  3711.1 2243.46  3828.7 2242.94  4039.5 2242.66  4294.4 2244.86  4399.7 2243.39
  4474.1 2241.05  4588.8 2240.23  4616.2 2238.96  4660.2 2240.53  4690.3 2233.85
  4698.3 2233.56  4720.3 2232.84  4772.3 2225.44  4790.4 2220.63  4830.4 2218.31
  4850.8 2219.42  4858.9 2219.22  4863.9 2216.76  4890.4 2218.89  4988.5 2216.63
  4988.7 2216.13  4992.5 2216.63  4997.7    2218    5055 2218.43  5066.8 2217.53
  5183.7 2226.98  5272.4 2231.86  5526.2 2238.05  5703.9 2243.77    5833 2249.96
#Mann= 15 ,-1 , 0
  3711.1    .035       0  3828.7     .07       0  4039.5    .045       0
  4294.4     .07       0  4399.7    .045       0  4474.1     .07       0
  4588.8    .035       0  4698.3     .07       0  4772.3    .035       0
  4850.8     .07       0  4988.5     .07       0  4992.5     .07       0
    5055     .16       0  5183.7     .07       0  5526.2    .045       0
Bank Sta=4988.5,4992.5
XS Rating Curve= 0 ,0
Exp/Cntr=0.3,0.1

Type RM Length L Ch R = 1 ,36005   ,106,106,106
BEGIN DESCRIPTION:
UCFB HW Trib 10 61.0
END DESCRIPTION:
XS GIS Cut Line= 5
      1296390.44      6960313.49      1296664.75      6959066.69
      1296695.13      6958780.23       1296755.9      6958561.21
      1295980.02      6958263.01
#Sta/Elev= 30
    3566 2238.39  3984.6 2234.76  4028.3 2236.67  4033.4  2234.6    4355 2233.78
  4411.2 2231.72  4447.6 2232.82  4452.8 2230.92  4491.4 2231.27  4496.5  2229.4
  4540.3  2230.4  4554.6 2227.75    4584  2228.1  4589.1 2225.68  4632.9 2224.98
    4638 2222.77  4718.4 2217.28  4917.5  2205.9  4922.8 2205.62  4987.2 2204.91
  4990.2 2203.37  4990.4 2202.87  4994.2 2203.37  5134.4  2209.8  5222.5 2216.03
  5383.3  2219.3  5686.6 2237.33  5794.3 2238.17  6001.7 2240.87  6189.2  2247.7
#Mann= 6 ,-1 , 0
    3566    .035       0  4917.5     .07       0  4922.8    .035       0
  4990.2    .035       0  4994.2    .035       0  5794.3    .045       0
Bank Sta=4990.2,4994.2
XS Rating Curve= 0 ,0
Exp/Cntr=0.3,0.1

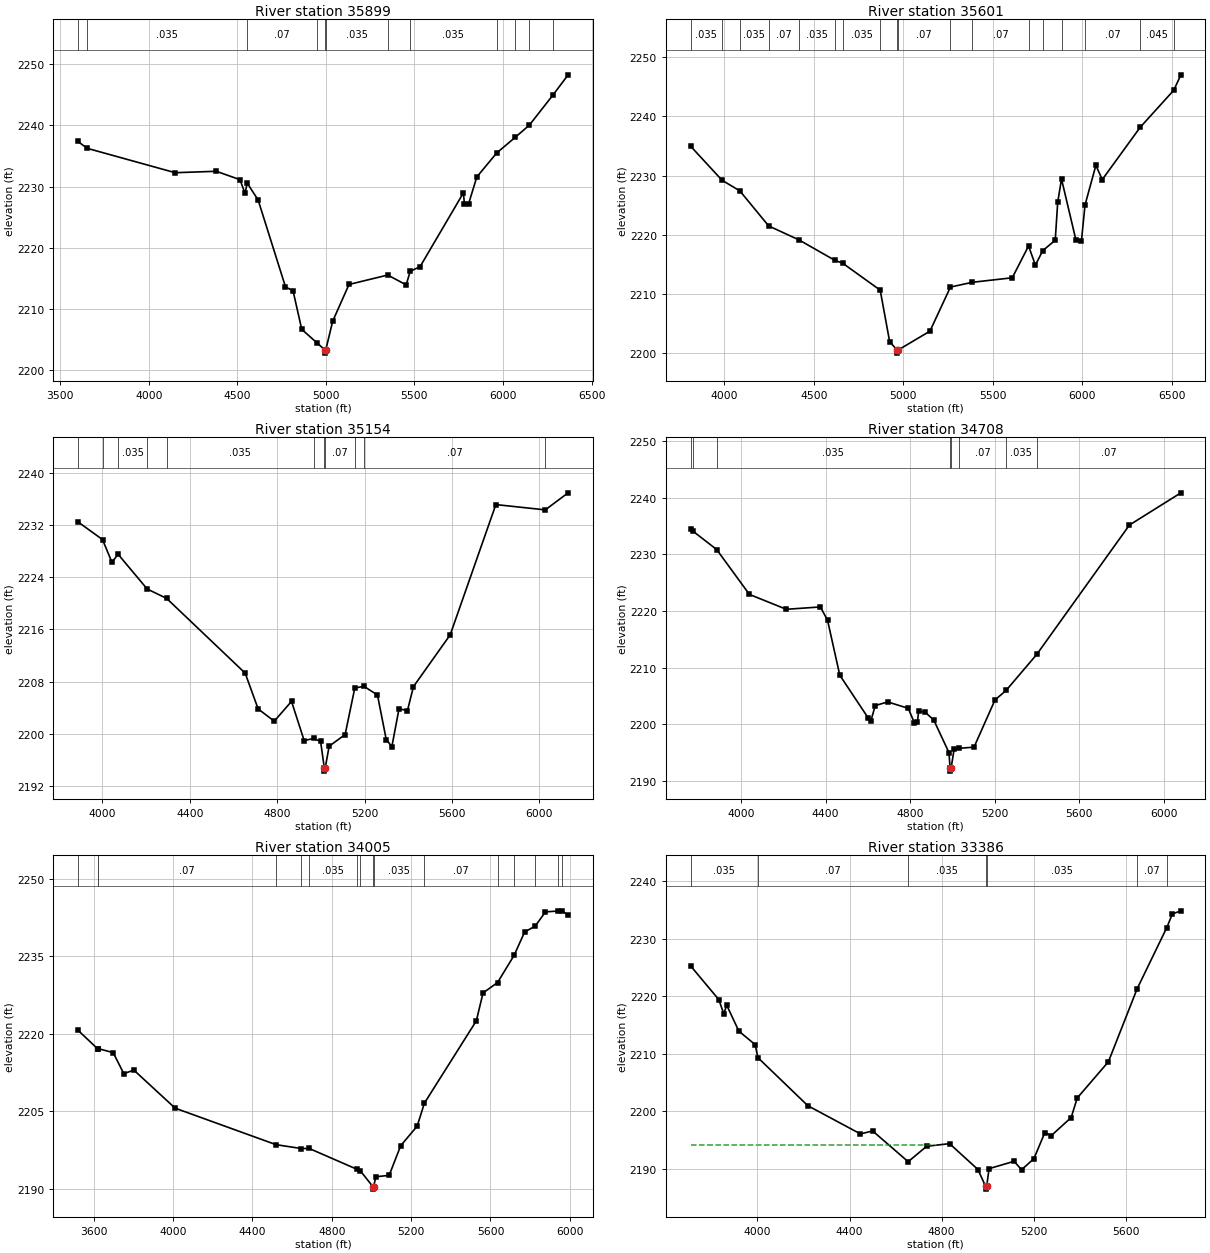
Type RM Length L Ch R = 1 ,35899   ,298,298,298
BEGIN DESCRIPTION:
UCFB HW Trib 10 60.5
END DESCRIPTION:
XS GIS Cut Line= 3
      1296446.28      6960310.04      1296864.39      6958505.61
      1296025.26       6958136.4
#Sta/Elev= 30
    3599 2237.37  3652.3 2236.24  4148.7 2232.26  4381.2 2232.49  4514.7 2231.12
  4543.1 2228.91  4555.9 2230.55  4617.3  2227.8  4771.9  2213.6  4814.5 2212.96
  4863.7 2206.66    4950 2204.45  4995.1 2203.28  4995.4 2202.78  4999.1 2203.28
  5038.2 2207.98  5130.6    2214  5349.3 2215.54  5453.6 2213.93  5475.8 2216.13
  5532.4 2216.93  5776.7 2228.97  5782.2 2227.15  5805.5 2227.13  5852.2 2231.56
  5964.6 2235.48  6069.2 2238.04  6148.7 2240.02  6282.9 2244.97    6368 2248.25
#Mann= 12 ,-1 , 0
    3599     .07       0  3652.3    .035       0  4555.9     .07       0
    4950    .035       0  4995.1    .035       0  4999.1    .035       0
  5349.3     .07       0  5475.8    .035       0  5964.6     .07       0
  6069.2    .035       0  6148.7    .045       0  6282.9    .035       0
Bank Sta=4995.1,4999.1
XS Rating Curve= 0 ,0
Exp/Cntr=0.3,0.1

Type RM Length L Ch R = 1 ,35601   ,447,447,447
BEGIN DESCRIPTION:
UCFB HW Trib 10 60.0
END DESCRIPTION:
XS GIS Cut Line= 4
      1297481.15      6960076.84        1297005.        6958988.
      1296893.03      6958325.04      1296069.82       6958019.6
#Sta/Elev= 30
  3811.9 2234.97  3987.5 2229.22    4087 2227.42  4248.2  2221.5  4416.4 2219.16
    4617 2215.71  4661.5 2215.21  4871.1 2210.66  4923.9 2201.96  4965.9 2200.53
  4966.2 2200.03  4969.9 2200.53  5148.9 2203.74  5263.4 2211.18    5386 2211.99
  5608.8 2212.75  5699.8 2218.12  5737.9 2214.89  5779.3 2217.34  5848.8 2219.09
  5862.5 2225.47  5883.8 2229.42  5964.9 2219.05  5995.3 2219.03  6015.1 2225.03
  6075.7 2231.72  6111.5 2229.33  6323.2 2238.15  6510.9 2244.41  6550.7 2247.01
#Mann= 18 ,-1 , 0
  3811.9    .035       0  3987.5     .07       0    4087    .035       0
  4248.2     .07       0  4416.4    .035       0    4617     .07       0
  4661.5    .035       0  4871.1     .07       0  4965.9     .07       0
  4969.9     .07       0  5263.4    .035       0    5386     .07       0
  5699.8    .035       0  5779.3     .07       0  5883.8    .035       0
  6015.1     .07       0  6323.2    .045       0  6510.9    .035       0
Bank Sta=4965.9,4969.9
XS Rating Curve= 0 ,0
Exp/Cntr=0.3,0.1

Type RM Length L Ch R = 1 ,35154   ,446,446,446
BEGIN DESCRIPTION:
UCFB HW Trib 10 59.0
END DESCRIPTION:
XS GIS Cut Line= 3
      1297600.94      6959805.99        1297305.        6958738.
      1296976.44      6957651.42
#Sta/Elev= 30
  3887.6 2232.46  4000.7 2229.73  4043.6 2226.26    4072 2227.48  4204.9 2222.17
  4294.2 2220.72  4653.4 2209.28  4712.7  2203.8  4786.5 2201.93  4865.4 2204.96
  4923.2 2198.96  4966.5 2199.28  4998.4 2198.82  5015.4 2194.78  5015.7 2194.28
  5019.6 2194.78  5037.6  2198.1  5110.7 2199.88  5154.9 2207.01  5196.7 2207.26
  5258.6 2205.94  5298.8 2199.12  5324.5 2198.03  5357.4 2203.85  5395.6 2203.52
  5423.3 2207.22  5591.3 2215.14  5800.3 2235.09  6026.5 2234.28    6131 2236.89
#Mann= 11 ,-1 , 0
  3887.6    .035       0  4000.7     .07       0    4072    .035       0
  4204.9     .07       0  4294.2    .035       0  4966.5     .07       0
  5015.4     .07       0  5019.6     .07       0  5154.9    .035       0
  5196.7     .07       0  6026.5    .035       0
Bank Sta=5015.4,5019.6
XS Rating Curve= 0 ,0
Exp/Cntr=0.3,0.1

Type RM Length L Ch R = 1 ,34708   ,703,703,703
BEGIN DESCRIPTION:
UCFB HW Trib 10 58.0
END DESCRIPTION:
XS GIS Cut Line= 3
       1297824.9      6959639.35        1297555.        6958438.
      1297122.12      6957442.22
#Sta/Elev= 30
  3762.4 2234.48  3775.5 2234.05  3885.8 2230.86  4040.5 2222.94  4214.8 2220.32
  4375.7 2220.73  4409.5 2218.41  4467.5 2208.69  4602.5  2201.1  4614.5 2200.62
    4635 2203.33  4694.3 2203.97  4791.1 2202.84  4819.5 2200.33  4834.4 2200.39
    4840 2202.29  4870.7 2202.17  4911.7 2200.77  4983.4 2195.03  4988.9 2192.26
  4989.2 2191.76  4993.4 2192.26  5008.1 2195.71    5029 2195.78  5101.9 2195.99
  5200.9 2204.32  5253.2 2205.99  5398.4 2212.36  5836.4 2235.19  6079.5 2240.87
#Mann= 8 ,-1 , 0
  3762.4    .035       0  3775.5     .07       0  3885.8    .035       0
  4988.9    .035       0  4993.4    .035       0    5029     .07       0
  5253.2    .035       0  5398.4     .07       0
Bank Sta=4988.9,4993.4
XS Rating Curve= 0 ,0
Exp/Cntr=0.3,0.1

Type RM Length L Ch R = 1 ,34005   ,619,619,619
BEGIN DESCRIPTION:
UCFB HW Trib 10 57.5
END DESCRIPTION:
XS GIS Cut Line= 3
      1298359.01      6959626.93      1298155.44      6958378.38
       1297599.5      6957307.18
#Sta/Elev= 30
  3519.5 2220.68    3620 2217.03  3621.5 2217.09  3697.7 2216.32  3751.4 2212.24
  3802.1 2212.93  4010.1 2205.56  4518.7 2198.49  4646.7 2197.74  4686.4 2197.75
  4927.8 2193.71    4944 2193.42  5006.7 2190.38  5007.1 2189.88  5011.3 2190.38
  5021.6 2192.27  5089.2 2192.55  5147.4  2198.3  5230.3 2202.07  5266.8 2206.53
  5528.6 2222.47  5562.4 2227.87  5635.4 2229.88  5718.9 2235.14    5772 2239.66
  5826.3 2240.84    5877 2243.57  5938.2 2243.72  5961.9 2243.77  5991.4  2242.9
#Mann= 16 ,-1 , 0
  3519.5     .07       0    3620    .035       0  3621.5     .07       0
  4518.7    .035       0  4646.7     .07       0  4686.4    .035       0
  4927.8     .07       0    4944    .035       0  5006.7    .035       0
  5011.3    .035       0  5266.8     .07       0  5635.4    .035       0
  5718.9     .07       0  5826.3    .035       0  5938.2     .07       0
  5961.9    .035       0
Bank Sta=5006.7,5011.3
XS Rating Curve= 0 ,0
Exp/Cntr=0.3,0.1

Type RM Length L Ch R = 1 ,33386   ,425,425,425
BEGIN DESCRIPTION:
UCFB HW Trib 10 57.0
END DESCRIPTION:
XS GIS Cut Line= 3
      1298960.31      6959420.58        1298455.        6958238.
      1298351.14      6957401.33
#Sta/Elev= 30
  3709.7 2225.27  3832.1 2219.41  3853.9 2216.94  3866.7 2218.42  3919.3 2213.92
  3990.1 2211.57    4002 2209.31  4218.8 2200.95  4447.5 2196.04  4500.2 2196.56
  4654.6 2191.21  4734.7 2193.89  4834.2 2194.35  4957.6 2189.85  4990.5 2186.94
  4990.9 2186.44  4995.5 2186.94  5005.8    2190  5114.5 2191.28  5146.9 2189.81
  5200.5 2191.74  5247.6 2196.24  5276.3 2195.76  5362.3 2198.89  5388.7 2202.29
    5524 2208.59  5648.4 2221.25  5777.7 2231.94  5801.9  2234.3  5838.8 2234.84
#Mann= 7 ,-1 , 0
  3709.7    .035       0    4002     .07       0  4654.6    .035       0
  4990.5    .035       0  4995.5    .035       0  5648.4     .07       0
  5777.7    .035       0
#XS Ineff= 2 , 0
       0  4781.5 2194.18               0
Permanent Ineff=
       F       F
Bank Sta=4990.5,4995.5
XS Rating Curve= 0 ,0
Exp/Cntr=0.3,0.1

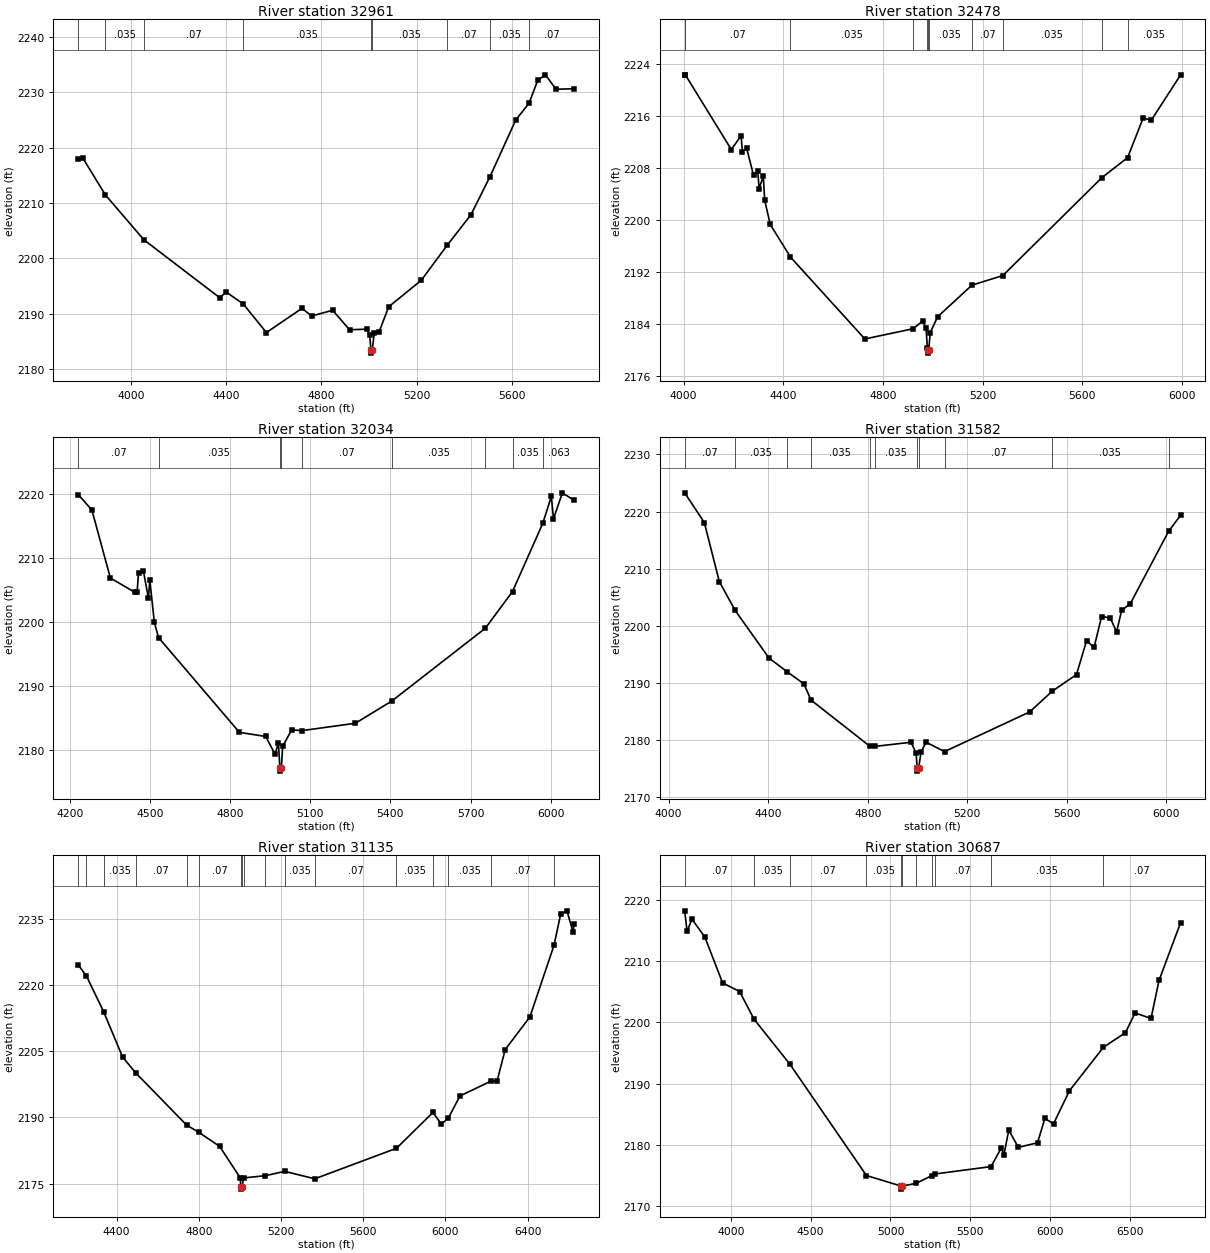
Type RM Length L Ch R = 1 ,32961   ,483,483,483
BEGIN DESCRIPTION:
UCFB HW Trib 10 56.0
END DESCRIPTION:
XS GIS Cut Line= 3
      1299111.35      6959207.01        1298755.        6958038.
      1298507.29      6957212.59
#Sta/Elev= 30
  3777.8 2217.93  3797.7 2218.09  3891.9 2211.47  4054.1 2203.33  4372.7 2192.86
  4399.3  2193.9  4471.3 2191.74  4568.6 2186.57  4717.7 2190.94  4759.5 2189.57
    4847 2190.61  4917.8 2187.08  4989.5 2187.18  5002.5 2186.04  5007.9 2183.35
  5008.2 2182.85  5012.9 2183.35  5021.7 2186.45  5041.7 2186.65  5082.6 2191.24
  5219.2 2196.02  5328.4 2202.37    5428 2207.88  5507.8 2214.74  5615.9 2224.98
  5672.7 2228.09  5708.9 2232.22  5741.2 2233.18  5785.4 2230.57  5861.7 2230.67
#Mann= 9 ,-1 , 0
  3777.8     .07       0  3891.9    .035       0  4054.1     .07       0
  4471.3    .035       0  5007.9    .035       0  5012.9    .035       0
  5328.4     .07       0  5507.8    .035       0  5672.7     .07       0
#XS Ineff= 2 , 0
       0  4717.7 2190.94               0
Permanent Ineff=
       F       F
Bank Sta=5007.9,5012.9
XS Rating Curve= 0 ,0
Exp/Cntr=0.3,0.1

Type RM Length L Ch R = 1 ,32478   ,444,444,444
BEGIN DESCRIPTION:
UCFB HW Trib 10 55.0
END DESCRIPTION:
XS GIS Cut Line= 3
      1299653.04      6958832.07        1299205.        6957938.
      1298903.04      6956993.55
#Sta/Elev= 30
    4004 2222.37  4006.7 2222.37  4191.2 2210.88  4230.3 2212.99  4235.9 2210.57
  4252.7 2211.12  4280.6  2206.9  4297.4 2207.55    4303 2204.87  4319.7 2206.78
  4325.3 2203.08  4347.6 2199.34  4428.9 2194.32  4727.5 2181.71    4922 2183.29
  4959.3 2184.47  4973.3 2183.36  4978.8 2180.26  4979.2 2180.03  4979.5 2179.53
  4984.2 2180.03  4990.1  2182.7  5020.1 2185.14  5157.4 2189.99  5281.8 2191.48
  5679.2 2206.54  5782.8 2209.63  5845.3 2215.75  5877.5 2215.37  5995.6 2222.38
#Mann= 11 ,-1 , 0
    4004    .035       0  4006.7     .07       0  4428.9    .035       0
    4922     .07       0  4978.8    .035       0  4979.2    .035       0
  4984.2    .035       0  5157.4     .07       0  5281.8    .035       0
  5679.2     .07       0  5782.8    .035       0
Bank Sta=4979.2,4984.2
XS Rating Curve= 0 ,0
Exp/Cntr=0.3,0.1

Type RM Length L Ch R = 1 ,32034   ,452,452,452
BEGIN DESCRIPTION:
UCFB HW Trib 10 54.0
END DESCRIPTION:
XS GIS Cut Line= 3
      1299731.16      6958785.21        1299555.        6958038.
      1299288.43      6956983.05
#Sta/Elev= 30
  4231.9  2219.9    4283 2217.51  4352.3 2206.88  4444.8 2204.63  4452.4 2204.72
  4457.5 2207.71  4475.6 2208.01  4494.7 2203.74  4499.9 2206.55  4516.7 2199.99
  4532.4 2197.59  4835.2 2182.79  4933.5 2182.15  4968.8 2179.35    4981  2181.2
  4986.6 2177.24    4987 2176.74  4992.1 2177.24    4997 2180.61  5030.5 2183.17
  5070.3 2183.07  5268.9 2184.21  5405.6 2187.69  5755.3 2199.04    5857 2204.77
  5970.2 2215.41  6002.4 2219.62  6010.4 2216.12  6043.5 2220.18  6087.7 2219.01
#Mann= 9 ,-1 , 0
  4231.9     .07       0  4532.4    .035       0  4986.6    .035       0
  4992.1    .035       0  5070.3     .07       0  5405.6    .035       0
  5755.3     .07       0    5857    .035       0  5970.2    .063       0
Bank Sta=4986.6,4992.1
XS Rating Curve= 0 ,0
Exp/Cntr=0.3,0.1

Type RM Length L Ch R = 1 ,31582   ,447,447,447
BEGIN DESCRIPTION:
UCFB HW Trib 10 53.0
END DESCRIPTION:
XS GIS Cut Line= 3
      1299908.23      6958826.89        1299955.        6957888.
      1299824.93      6956842.71
#Sta/Elev= 30
  4064.3 2223.28  4143.3 2218.07  4203.4 2207.74  4267.1 2202.67  4403.6 2194.31
  4476.6 2191.91  4543.8 2189.79  4572.2 2186.96  4807.3 2178.91  4828.1 2178.84
  4974.3 2179.57  4994.3 2177.66  4999.1 2175.01  4999.5 2174.51  5004.6 2175.01
  5014.4 2177.87  5034.6 2179.58  5108.7 2177.93  5451.3 2184.89  5541.3 2188.51
  5639.2 2191.43  5679.5 2197.35  5709.8  2196.2    5740 2201.59  5774.5 2201.38
  5800.4 2198.91  5820.6 2202.68  5855.3 2203.84  6009.7 2216.56  6057.7 2219.34
#Mann= 11 ,-1 , 0
  4064.3     .07       0  4267.1    .035       0  4476.6     .07       0
  4572.2    .035       0  4807.3     .07       0  4828.1    .035       0
  4999.1    .035       0  5004.6    .035       0  5108.7     .07       0
  5541.3    .035       0  6009.7     .07       0
Bank Sta=4999.1,5004.6
XS Rating Curve= 0 ,0
Exp/Cntr=0.3,0.1

Type RM Length L Ch R = 1 ,31135   ,448,448,448
BEGIN DESCRIPTION:
UCFB HW Trib 10 52.0
END DESCRIPTION:
XS GIS Cut Line= 4
        1300180.      6958912.98        1300255.        6958138.
      1300213.91      6958029.67      1300134.62        6956513.
#Sta/Elev= 30
  4212.9 2224.48  4252.3 2222.06  4336.6 2213.91  4428.9 2203.64    4493 2200.04
    4740 2188.25  4798.9 2186.62  4901.1 2183.41  5001.2  2176.3  5003.8 2174.23
  5004.2 2173.73  5009.3 2174.23  5018.5 2176.27  5123.1 2176.77  5217.5 2177.75
  5364.1 2176.07  5761.6 2182.98  5938.9 2191.09  5980.2 2188.45  6014.5 2189.85
  6070.3 2194.82  6221.4 2198.19  6250.6 2198.12  6290.6 2205.34  6410.8 2212.73
  6528.1 2228.94    6561 2236.11  6591.1 2236.75  6621.1 2231.88  6626.1 2233.87
#Mann= 17 ,-1 , 0
  4212.9    .035       0  4252.3     .07       0  4336.6    .035       0
    4493     .07       0    4740    .035       0  4798.9     .07       0
  5003.8     .07       0  5009.3     .07       0  5018.5    .035       0
  5123.1     .07       0  5217.5    .035       0  5364.1     .07       0
  5761.6    .035       0  5938.9    .063       0  6014.5    .035       0
  6221.4     .07       0  6528.1    .035       0
Bank Sta=5003.8,5009.3
XS Rating Curve= 0 ,0
Exp/Cntr=0.3,0.1

Type RM Length L Ch R = 1 ,30687   ,911,911,911
BEGIN DESCRIPTION:
UCFB HW Trib 10 51.0
END DESCRIPTION:
XS GIS Cut Line= 3
      1300370.73      6959262.95        1300555.        6957988.
      1300620.73      6956172.88
#Sta/Elev= 30
  3711.8 2218.28  3726.9 2214.91  3757.2 2216.92    3838 2213.99  3949.2 2206.48
  4055.7 2205.07  4145.5 2200.56  4370.5 2193.17  4849.5 2174.95  5067.2 2173.22
  5067.6 2172.72  5072.9 2173.22  5160.2 2173.66    5258 2174.92  5278.5  2175.2
  5629.6 2176.41  5693.2 2179.44  5710.5 2178.37  5740.5 2182.38  5800.5 2179.56
  5920.6 2180.31  5966.4 2184.29  6020.7 2183.42  6120.7 2188.84  6333.1 2195.94
    6471 2198.33    6531 2201.57  6631.1 2200.66  6681.1 2206.89  6816.3 2216.35
#Mann= 11 ,-1 , 0
  3711.8     .07       0  4145.5    .035       0  4370.5     .07       0
  4849.5    .035       0  5067.2    .035       0  5072.9    .035       0
  5160.2     .07       0    5258    .035       0  5278.5     .07       0
  5629.6    .035       0  6333.1     .07       0
Bank Sta=5067.2,5072.9
XS Rating Curve= 0 ,0
Exp/Cntr=0.3,0.1

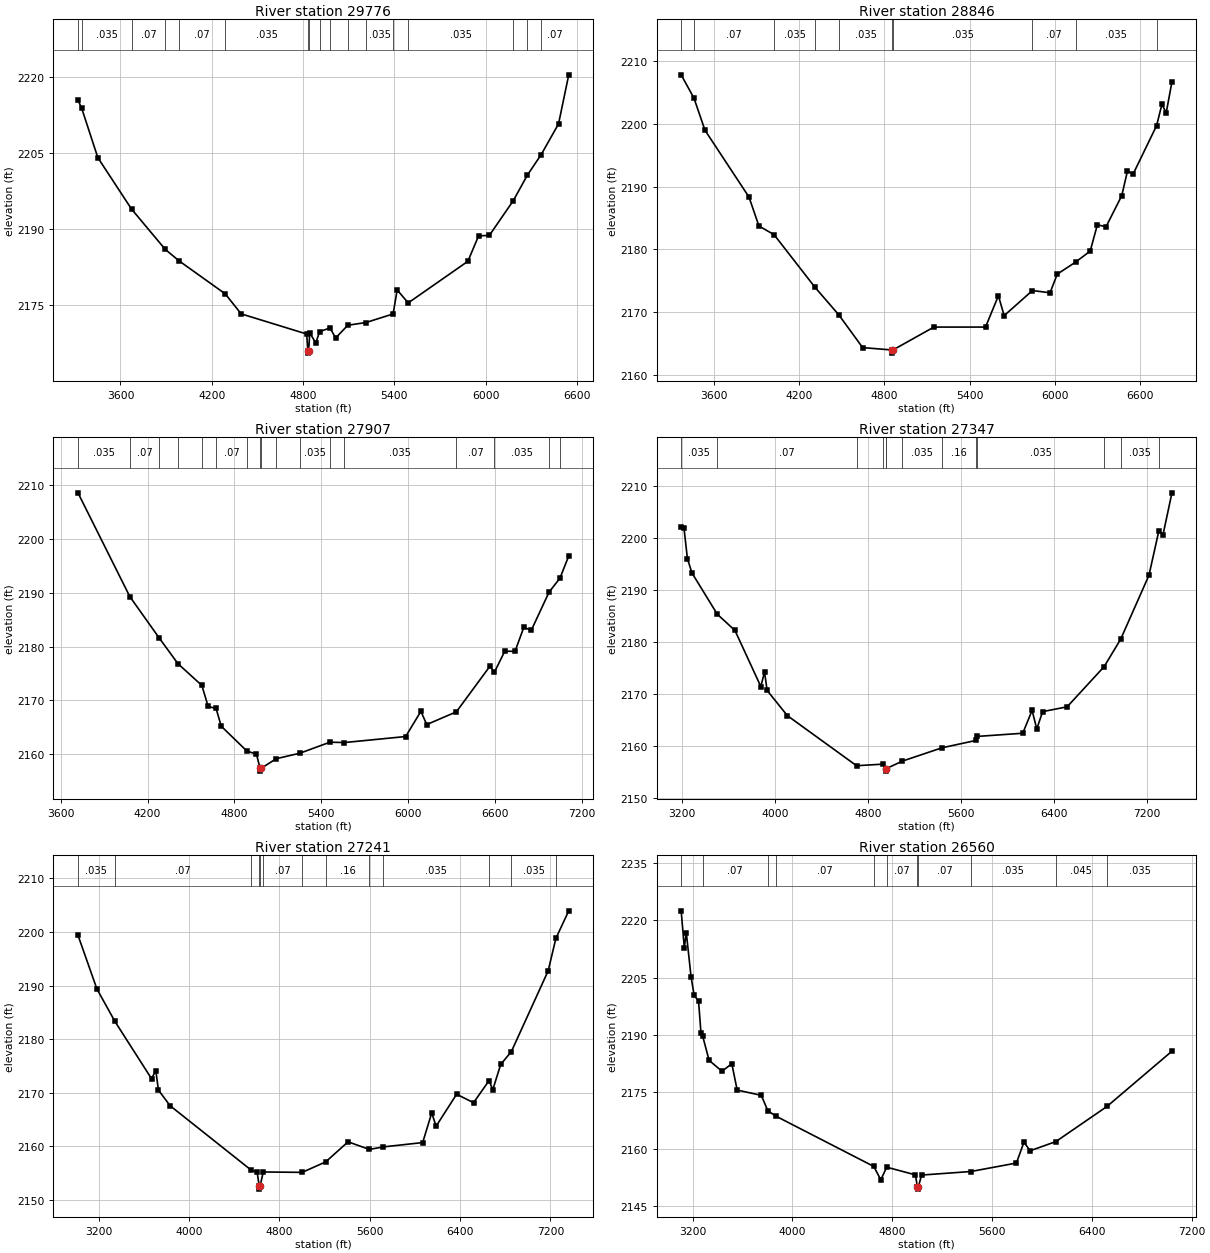
Type RM Length L Ch R = 1 ,29776   ,930,930,930
BEGIN DESCRIPTION:
UCFB HW Trib 10 50.0
END DESCRIPTION:
XS GIS Cut Line= 3
      1301009.62      6959318.51        1301105.        6957638.
      1300891.76      6956111.54
#Sta/Elev= 30
  3320.7 2215.49  3345.1  2213.9  3451.4 2204.13  3672.9 2193.98    3894 2186.04
  3985.3 2183.76  4288.3 2177.26  4392.9 2173.31  4823.6 2169.33  4830.7 2166.06
  4831.2 2165.56  4836.5 2166.06  4843.7 2169.55  4883.7 2167.55  4908.1 2169.81
  4976.4 2170.52    5014 2168.56  5093.6 2171.06  5212.9  2171.6  5391.3 2173.29
  5417.9 2178.03  5490.5 2175.47  5882.4 2183.68    5953  2188.7  6023.7 2188.79
  6180.7 2195.64  6273.9 2200.71  6364.4 2204.75  6478.1 2210.79  6545.2 2220.48
#Mann= 17 ,-1 , 0
  3320.7     .07       0  3345.1    .035       0  3672.9     .07       0
    3894    .035       0  3985.3     .07       0  4288.3    .035       0
  4830.7    .035       0  4836.5    .035       0  4908.1     .07       0
  4976.4    .035       0  5093.6     .07       0  5212.9    .035       0
  5391.3    .063       0  5490.5    .035       0  6180.7     .07       0
  6273.9    .035       0  6364.4     .07       0
Bank Sta=4830.7,4836.5
XS Rating Curve= 0 ,0
Exp/Cntr=0.3,0.1

Type RM Length L Ch R = 1 ,28846   ,939,939,939
BEGIN DESCRIPTION:
UCFB HW Trib 10 49.0
END DESCRIPTION:
XS GIS Cut Line= 3
      1301801.29      6959325.42        1301755.        6957688.
      1301502.68      6955887.97
#Sta/Elev= 30
  3368.9 2207.79  3459.4 2204.06  3536.4 2198.97  3846.5 2188.32  3916.5 2183.71
  4023.1 2182.33  4310.3 2173.97  4479.4 2169.54  4646.8 2164.34  4853.8 2163.96
  4854.3 2163.46  4860.1 2163.96  5148.3 2167.61  5511.9 2167.61  5602.7  2172.6
  5643.1 2169.43  5842.2 2173.43  5966.3 2173.07  6016.8 2176.04  6145.5 2177.95
    6249 2179.71  6299.5 2183.91  6360.1 2183.58  6471.2 2188.54  6511.5 2192.49
  6551.3 2191.99  6716.5 2199.69  6753.9 2203.09  6784.2 2201.74  6824.6 2206.68
#Mann= 10 ,-1 , 0
  3368.9    .035       0  3459.4     .07       0  4023.1    .035       0
  4310.3     .07       0  4479.4    .035       0  4853.8    .035       0
  4860.1    .035       0  5842.2     .07       0  6145.5    .035       0
  6716.5     .07       0
Bank Sta=4853.8,4860.1
XS Rating Curve= 0 ,0
Exp/Cntr=0.3,0.1

Type RM Length L Ch R = 1 ,27907   ,560,560,560
BEGIN DESCRIPTION:
UCFB HW Trib 10 48.0
END DESCRIPTION:
XS GIS Cut Line= 3
        1302380.      6959313.02        1302505.        6958038.
      1302130.01      6955963.05
#Sta/Elev= 30
  3718.9 2208.52  4077.3 2189.26  4281.4 2181.54  4409.7 2176.82  4574.8 2172.78
  4618.2 2168.88  4672.8 2168.52  4708.6 2165.22  4885.7 2160.61  4951.8 2160.05
  4976.7 2157.39  4977.2 2156.89  4983.1 2157.39  5088.1 2159.19  5252.5 2160.22
    5459 2162.26    5559 2162.19  5982.4 2163.31  6087.4 2167.98    6128 2165.53
  6332.5 2167.89    6565 2176.38  6594.7 2175.21  6666.6 2179.13  6737.7 2179.12
  6798.7 2183.59  6849.5 2182.99  6972.8  2190.1    7048 2192.69  7108.6 2196.81
#Mann= 17 ,-1 , 0
  3718.9    .035       0  4077.3     .07       0  4281.4    .035       0
  4409.7     .07       0  4574.8    .035       0  4672.8     .07       0
  4885.7    .035       0  4976.7    .035       0  4983.1    .035       0
  5088.1     .07       0  5252.5    .035       0    5459     .07       0
    5559    .035       0  6332.5     .07       0  6594.7    .035       0
  6972.8     .07       0    7048    .035       0
Bank Sta=4976.7,4983.1
XS Rating Curve= 0 ,0
Exp/Cntr=0.3,0.1

Type RM Length L Ch R = 1 ,27347   ,106,106,106
BEGIN DESCRIPTION:
UCFB HW Trib 10 47.2
END DESCRIPTION:
XS GIS Cut Line= 4
      1302570.69      6959266.49        1303230.        6957863.
      1302600.91      6957738.64      1302414.22      6955721.26
#Sta/Elev= 30
  3194.1 2202.17    3218 2201.97  3247.7 2196.02  3286.5 2193.26  3504.8  2185.3
  3656.5 2182.18  3878.7 2171.39  3910.6 2174.21  3932.7 2170.64  4106.8 2165.79
  4701.7 2156.15  4932.6 2156.46  4951.6 2155.61  4952.1 2155.11  4958.1 2155.61
  5095.6 2157.04  5435.8  2159.6  5728.3 2161.02  5739.6 2161.79  6129.8  2162.4
  6210.1  2166.8  6250.3 2163.22  6300.5 2166.56  6511.4 2167.49  6829.1 2175.22
  6971.4  2180.5  7214.4  2192.8  7299.6 2201.37  7334.9 2200.58    7412 2208.67
#Mann= 13 ,-1 , 0
  3194.1    .035       0  3504.8     .07       0  4701.7    .035       0
  4932.6     .07       0  4951.6     .07       0  4958.1     .07       0
  5095.6    .035       0  5435.8     .16       0  5728.3     .07       0
  5739.6    .035       0  6829.1     .07       0  6971.4    .035       0
  7299.6     .07       0
Bank Sta=4951.6,4958.1
XS Rating Curve= 0 ,0
Exp/Cntr=0.3,0.1

Type RM Length L Ch R = 1 ,27241   ,681,681,681
BEGIN DESCRIPTION:
UCFB HW Trib 10 47.1
END DESCRIPTION:
XS GIS Cut Line= 4
      1302693.78      6959300.04      1303378.69      6957801.14
      1302673.82      6957662.25      1302615.46        6955686.
#Sta/Elev= 30
    3018 2199.41  3185.2 2189.39  3344.5 2183.33  3668.9 2172.63    3707 2174.12
  3730.1  2170.5  3833.8 2167.57  4551.5 2155.55  4603.5 2155.23  4622.7 2152.51
  4623.2 2152.01  4629.2 2152.51  4657.7 2155.21  5002.7 2155.14  5210.1 2157.09
  5408.6 2160.84  5596.9 2159.42  5720.9 2159.89  6068.9  2160.7    6149 2166.24
  6187.7 2163.75  6369.1 2169.72  6519.1 2168.14  6656.6 2172.27  6689.2 2170.55
  6759.2 2175.27  6853.7 2177.68  7179.4 2192.75  7247.8 2198.81  7361.5 2203.95
#Mann= 13 ,-1 , 0
    3018    .035       0  3344.5     .07       0  4551.5    .035       0
  4622.7     .07       0  4629.2    .035       0  4657.7     .07       0
  5002.7    .035       0  5210.1     .16       0  5596.9     .07       0
  5720.9    .035       0  6656.6     .07       0  6853.7    .035       0
  7247.8     .07       0
Bank Sta=4622.7,4629.2
XS Rating Curve= 0 ,0
Exp/Cntr=0.3,0.1

Type RM Length L Ch R = 1 ,26560   ,471,471,471
BEGIN DESCRIPTION:
UCFB HW Trib 10 47.0
END DESCRIPTION:
XS GIS Cut Line= 3
      1302870.74      6959346.26        1303555.        6957588.
      1303544.35      6955541.84
#Sta/Elev= 30
  3108.7 2222.53  3133.9 2212.85  3149.8 2216.79  3188.3 2205.12  3212.9 2200.27
  3248.1 2198.81  3267.3 2190.46  3280.5 2189.67  3332.4 2183.22  3435.8 2180.35
  3514.6 2182.33  3557.5  2175.4  3750.7 2174.02  3803.4 2169.95  3870.3 2168.51
    4652 2155.33  4708.5 2151.81  4755.9 2155.13  4985.8 2153.11  5002.1 2149.86
  5002.6 2149.36  5008.7 2149.86  5035.4 2153.06  5430.1 2153.99  5795.4 2156.22
  5855.4  2161.7  5905.4 2159.45  6111.3 2161.86  6520.8 2171.09  7041.6 2185.63
#Mann= 11 ,-1 , 0
  3108.7    .035       0  3280.5     .07       0  3803.4    .035       0
  3870.3     .07       0    4652    .035       0  4755.9     .07       0
  5002.1     .07       0  5008.7     .07       0  5430.1    .035       0
  6111.3    .045       0  6520.8    .035       0
Bank Sta=5002.1,5008.7
XS Rating Curve= 0 ,0
Exp/Cntr=0.3,0.1