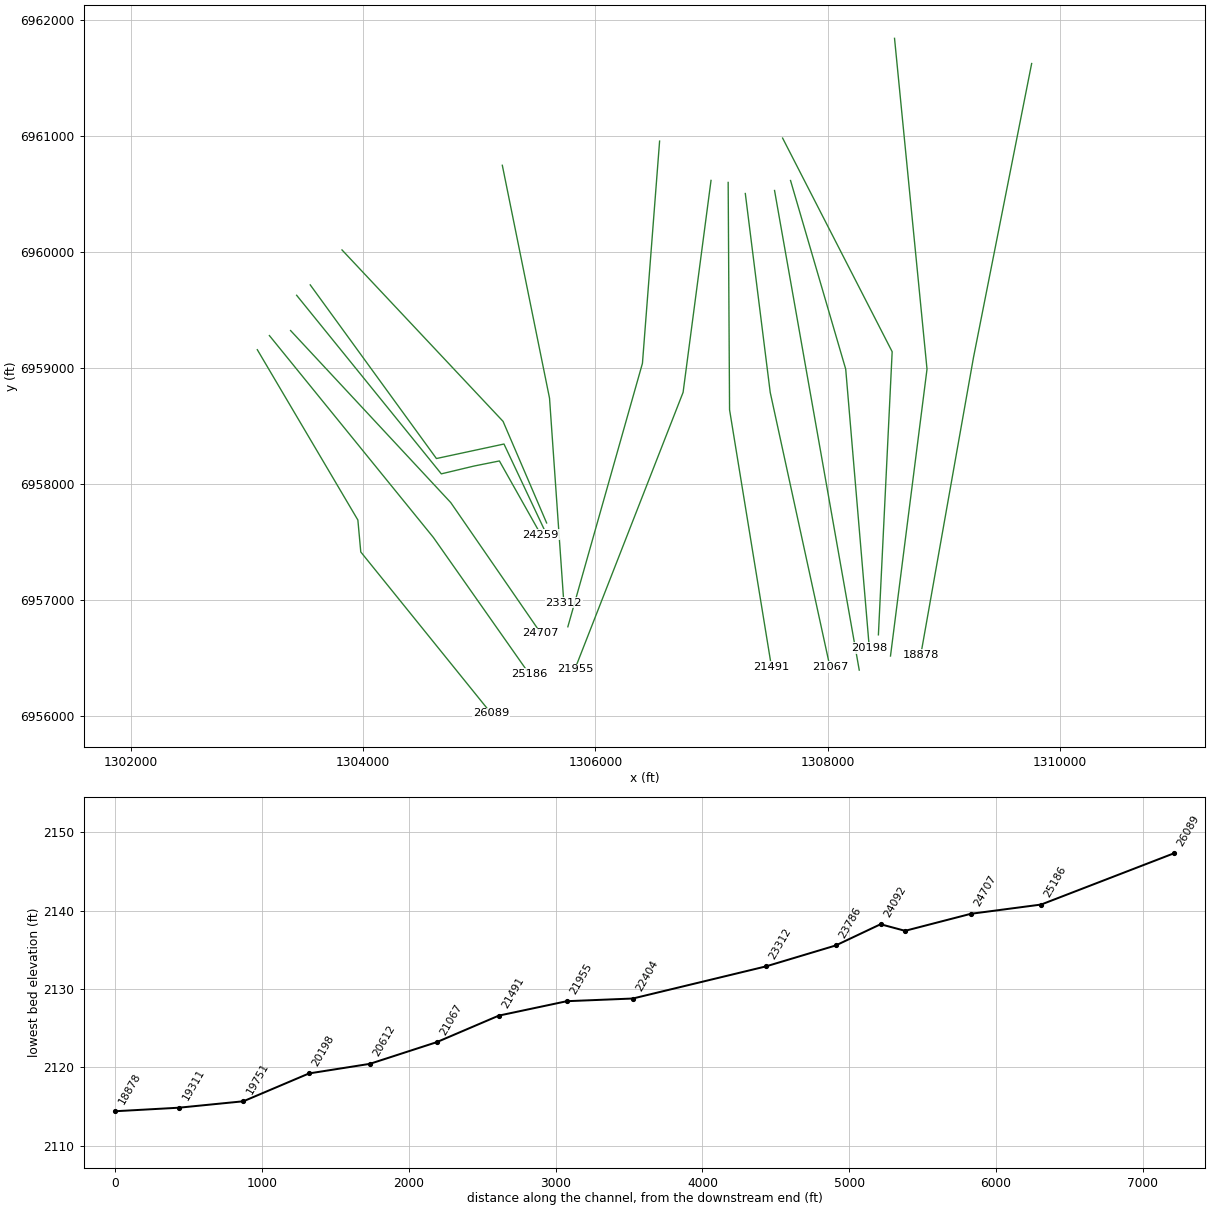
HEC-RAS study UCFB HW Trib 10.prj: UCFB HW Trib 10 Base Level Engineering

--- UCFB HW Trib 10.g01 (geometry) --- (continued)

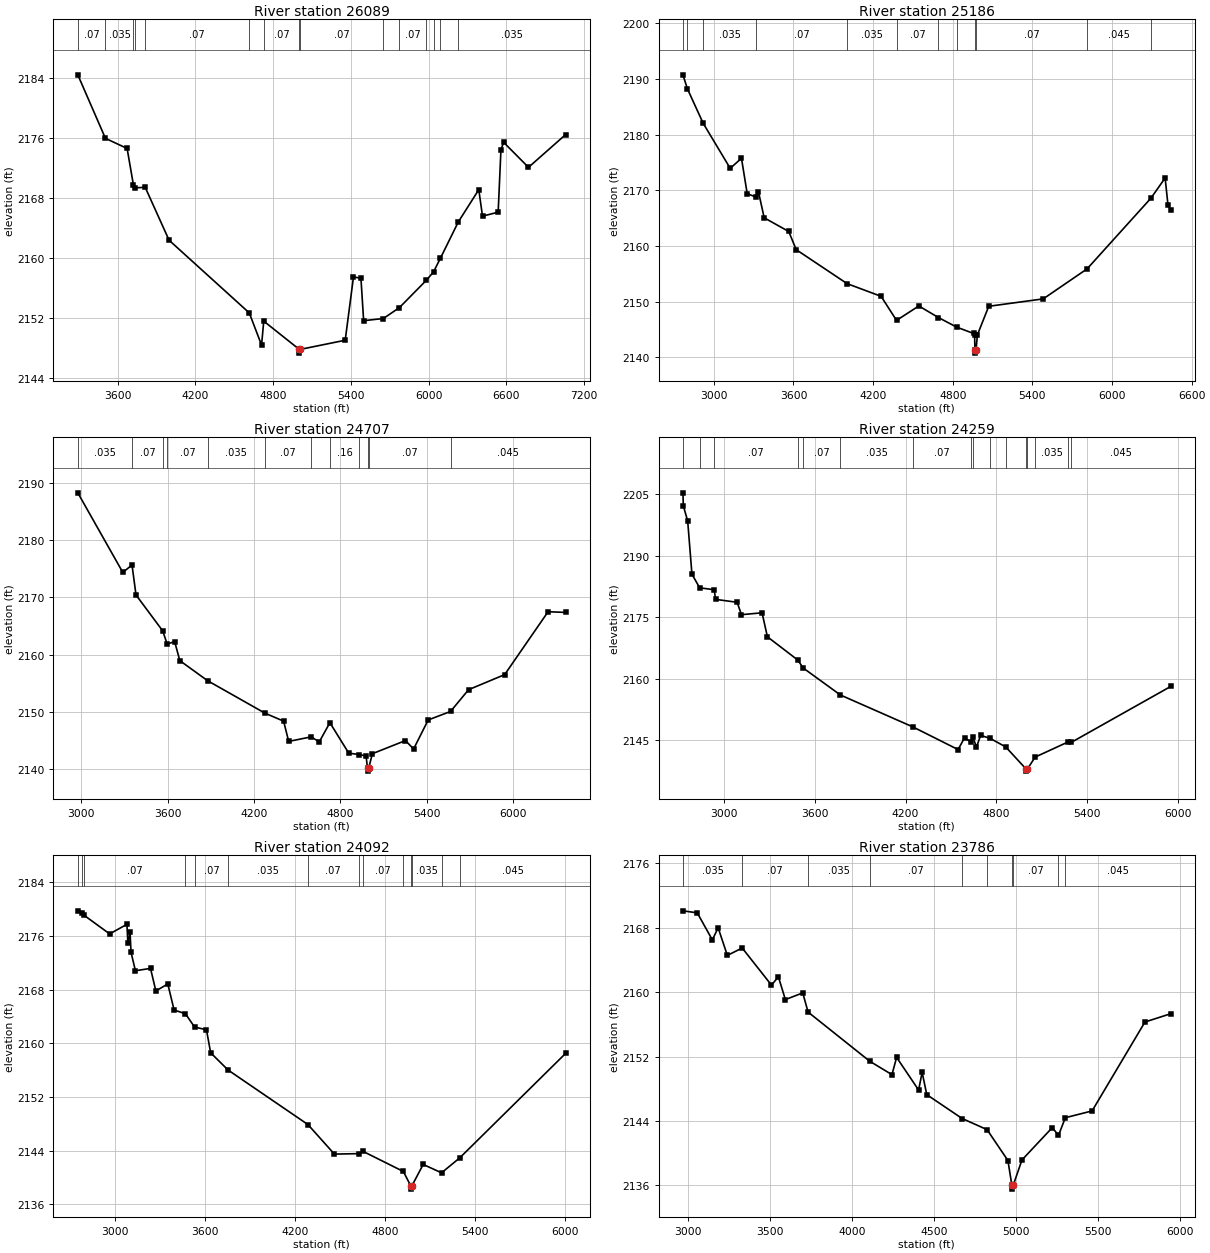
Type RM Length L Ch R = 1 ,26089   ,903,903,903
BEGIN DESCRIPTION:
UCFB HW Trib 10 46.0
END DESCRIPTION:
XS GIS Cut Line= 4
      1303089.19      6959155.47        1303955.        6957688.
        1303980.        6957413.      1305102.61      6956022.36
#Sta/Elev= 30
    3292 2184.44  3505.3 2175.96  3672.8 2174.61  3721.6 2169.72    3737 2169.36
  3812.5 2169.42  3996.8 2162.36    4616 2152.66  4710.9 2148.36  4727.8 2151.56
  5002.1 2147.79  5002.6 2147.29  5009.6 2147.79  5356.8 2149.01  5420.7 2157.47
  5478.3 2157.28  5499.1 2151.62  5651.5 2151.91  5775.5 2153.37  5983.7 2157.02
  6038.6 2158.13  6091.2 2159.93  6229.7 2164.79  6388.2 2169.11    6417 2165.57
  6537.9 2166.11  6559.3 2174.44  6580.2 2175.43  6772.1 2172.09  7059.2 2176.47
#Mann= 15 ,-1 , 0
    3292     .07       0  3505.3    .035       0  3721.6     .07       0
    3737    .035       0  3812.5     .07       0    4616    .035       0
  4727.8     .07       0  5002.1     .07       0  5009.6     .07       0
  5651.5    .035       0  5775.5     .07       0  5983.7     .16       0
  6038.6     .07       0  6091.2     .16       0  6229.7    .035       0
Bank Sta=5002.1,5009.6
XS Rating Curve= 0 ,0
Exp/Cntr=0.3,0.1

Type RM Length L Ch R = 1 ,25186   ,479,479,479
BEGIN DESCRIPTION:
UCFB HW Trib 10 45.0
END DESCRIPTION:
XS GIS Cut Line= 3
      1303193.37      6959276.98        1304605.        6957538.
      1305429.99      6956363.01
#Sta/Elev= 30
  2767.4 2190.74  2800.7 2188.25  2919.6 2182.05  3123.6 2173.95  3208.4 2175.76
  3251.5  2169.4    3317  2168.8  3336.3 2169.75  3379.4 2165.07  3564.6 2162.61
  3620.7 2159.35  4003.9 2153.25  4260.2 2150.97  4376.6 2146.65  4544.6 2149.24
  4692.3 2147.16  4829.6 2145.44  4956.9  2144.3  4964.8 2143.97  4967.2 2141.27
  4967.7 2140.77  4975.4 2141.27  4985.6 2144.03  5071.3 2149.18  5481.7 2150.51
  5812.3  2155.9  6293.5  2168.6  6400.1 2172.22    6422 2167.28  6442.9  2166.5
#Mann= 12 ,-1 , 0
  2767.4    .035       0  2800.7     .07       0  2919.6    .035       0
    3317     .07       0  4003.9    .035       0  4376.6     .07       0
  4692.3     .16       0  4829.6     .07       0  4967.2     .07       0
  4975.4     .07       0  5812.3    .045       0  6293.5    .035       0
Bank Sta=4967.2,4975.4
XS Rating Curve= 0 ,0
Exp/Cntr=0.3,0.1

Type RM Length L Ch R = 1 ,24707   ,448,448,448
BEGIN DESCRIPTION:
UCFB HW Trib 10 44.0
END DESCRIPTION:
XS GIS Cut Line= 3
      1303375.64      6959320.41        1304755.        6957838.
        1305530.        6956713.
#Sta/Elev= 30
    2975 2188.32  3287.7 2174.39  3351.8 2175.68  3379.5 2170.44  3565.2 2164.14
  3596.2 2161.84  3648.2 2162.27  3683.9 2158.94  3876.7 2155.43  4275.9 2149.74
  4405.5 2148.34  4440.7 2144.79  4596.8 2145.59  4653.2 2144.71  4727.1 2148.07
  4858.4 2142.73  4930.8  2142.5  4978.6 2142.24  4988.7 2140.09  4989.2 2139.59
  4996.9 2140.09  5022.2 2142.64  5252.2 2144.94    5309 2143.47  5410.4 2148.55
  5565.8 2150.04  5691.1 2153.85    5942 2156.49  6243.6  2167.5    6366 2167.38
#Mann= 12 ,-1 , 0
    2975    .035       0  3351.8     .07       0  3565.2    .035       0
  3596.2     .07       0  3876.7    .035       0  4275.9     .07       0
  4596.8    .035       0  4727.1     .16       0  4930.8     .07       0
  4988.7     .07       0  4996.9     .07       0  5565.8    .045       0
Bank Sta=4988.7,4996.9
XS Rating Curve= 0 ,0
Exp/Cntr=0.3,0.1

Type RM Length L Ch R = 1 ,24259   ,167,167,167
BEGIN DESCRIPTION:
UCFB HW Trib 10 43.0
END DESCRIPTION:
XS GIS Cut Line= 5
      1303427.75      6959624.19      1304673.44      6958085.82
      1304954.84      6958153.06      1305173.44      6958196.93
      1305530.01      6957562.99
#Sta/Elev= 30
  2731.2 2205.31  2733.8 2202.13  2762.5 2198.44  2790.6 2185.46  2841.6 2182.14
  2937.5 2181.67  2946.4 2179.32  3088.7 2178.61  3117.4 2175.59  3253.3 2176.04
  3288.5 2170.19  3487.8 2164.55    3526 2162.54  3770.3 2155.99  4248.8  2148.2
  4546.7 2142.68  4589.8 2145.59    4633 2144.47  4644.4 2145.72  4668.1 2143.27
  4695.4 2146.15    4760 2145.38  4861.1 2143.32  4995.7 2137.92  4996.2 2137.42
  5004.1 2137.92  5054.8 2140.84  5273.2 2144.55  5294.9 2144.46  5950.3 2158.09
#Mann= 16 ,-1 , 0
  2731.2     .07       0  2841.6    .035       0  2937.5     .07       0
  3487.8    .035       0    3526     .07       0  3770.3    .035       0
  4248.8     .07       0    4633    .035       0  4644.4     .07       0
    4760     .16       0  4861.1     .07       0  4995.7     .07       0
  5004.1     .07       0  5054.8    .035       0  5273.2     .07       0
  5294.9    .045       0
Bank Sta=4995.7,5004.1
XS Rating Curve= 0 ,0
Exp/Cntr=0.3,0.1

Type RM Length L Ch R = 1 ,24092   ,306,306,306
BEGIN DESCRIPTION:
UCFB HW Trib 10 42.5
END DESCRIPTION:
XS GIS Cut Line= 4
      1303544.85      6959713.85      1304631.32      6958217.77
      1305212.91      6958342.77      1305555.89      6957614.42
#Sta/Elev= 30
  2755.1 2179.74  2782.7 2179.42    2796 2179.09  2967.2  2176.3  3082.3 2177.73
  3088.5 2174.91  3103.2 2176.52  3109.4 2173.56  3138.8 2170.81  3239.3 2171.16
  3274.8  2167.8  3354.4 2168.84  3396.2 2164.96    3472  2164.4  3532.4 2162.42
  3611.8 2162.01  3639.8 2158.58  3755.9 2156.01  4287.8 2147.88  4463.7 2143.48
  4625.3 2143.55    4656 2143.87  4923.1 2140.89  4971.9 2138.76  4972.4 2138.26
  4980.3 2138.76    5055 2141.94  5177.3 2140.69  5298.6 2142.92    6004  2158.5
#Mann= 14 ,-1 , 0
  2755.1     .07       0  2782.7    .035       0    2796     .07       0
    3472    .035       0  3532.4     .07       0  3755.9    .035       0
  4287.8     .07       0  4625.3    .035       0    4656     .07       0
  4923.1    .035       0  4971.9    .035       0  4980.3    .035       0
  5177.3     .07       0  5298.6    .045       0
Bank Sta=4971.9,4980.3
XS Rating Curve= 0 ,0
Exp/Cntr=0.3,0.1

Type RM Length L Ch R = 1 ,23786   ,474,474,474
BEGIN DESCRIPTION:
UCFB HW Trib 10 42.0
END DESCRIPTION:
XS GIS Cut Line= 3
      1303818.34      6960014.86        1305205.        6958538.
        1305580.      6957662.99
#Sta/Elev= 30
  2967.9 2170.07  3055.4 2169.82  3147.2 2166.47  3182.8 2167.96    3239 2164.54
  3329.6 2165.46  3508.1 2160.86  3550.6 2161.88  3593.1 2159.06  3699.1 2159.89
  3731.8 2157.51  4108.3 2151.41  4243.7 2149.75  4272.1 2151.89  4406.4 2147.84
  4427.9 2150.04  4456.2 2147.27    4672 2144.31  4824.1 2142.93  4951.5  2139.1
  4975.4 2136.05  4975.9 2135.55  4984.1 2136.05  5037.2 2139.17  5222.2 2143.18
  5260.1 2142.22  5302.1 2144.41  5465.2 2145.25  5787.9 2156.28  5945.7 2157.31
#Mann= 10 ,-1 , 0
  2967.9    .035       0  3329.6     .07       0  3731.8    .035       0
  4108.3     .07       0    4672    .035       0  4824.1     .07       0
  4975.4     .07       0  4984.1     .07       0  5260.1    .035       0
  5302.1    .045       0
Bank Sta=4975.4,4984.1
XS Rating Curve= 0 ,0
Exp/Cntr=0.3,0.1

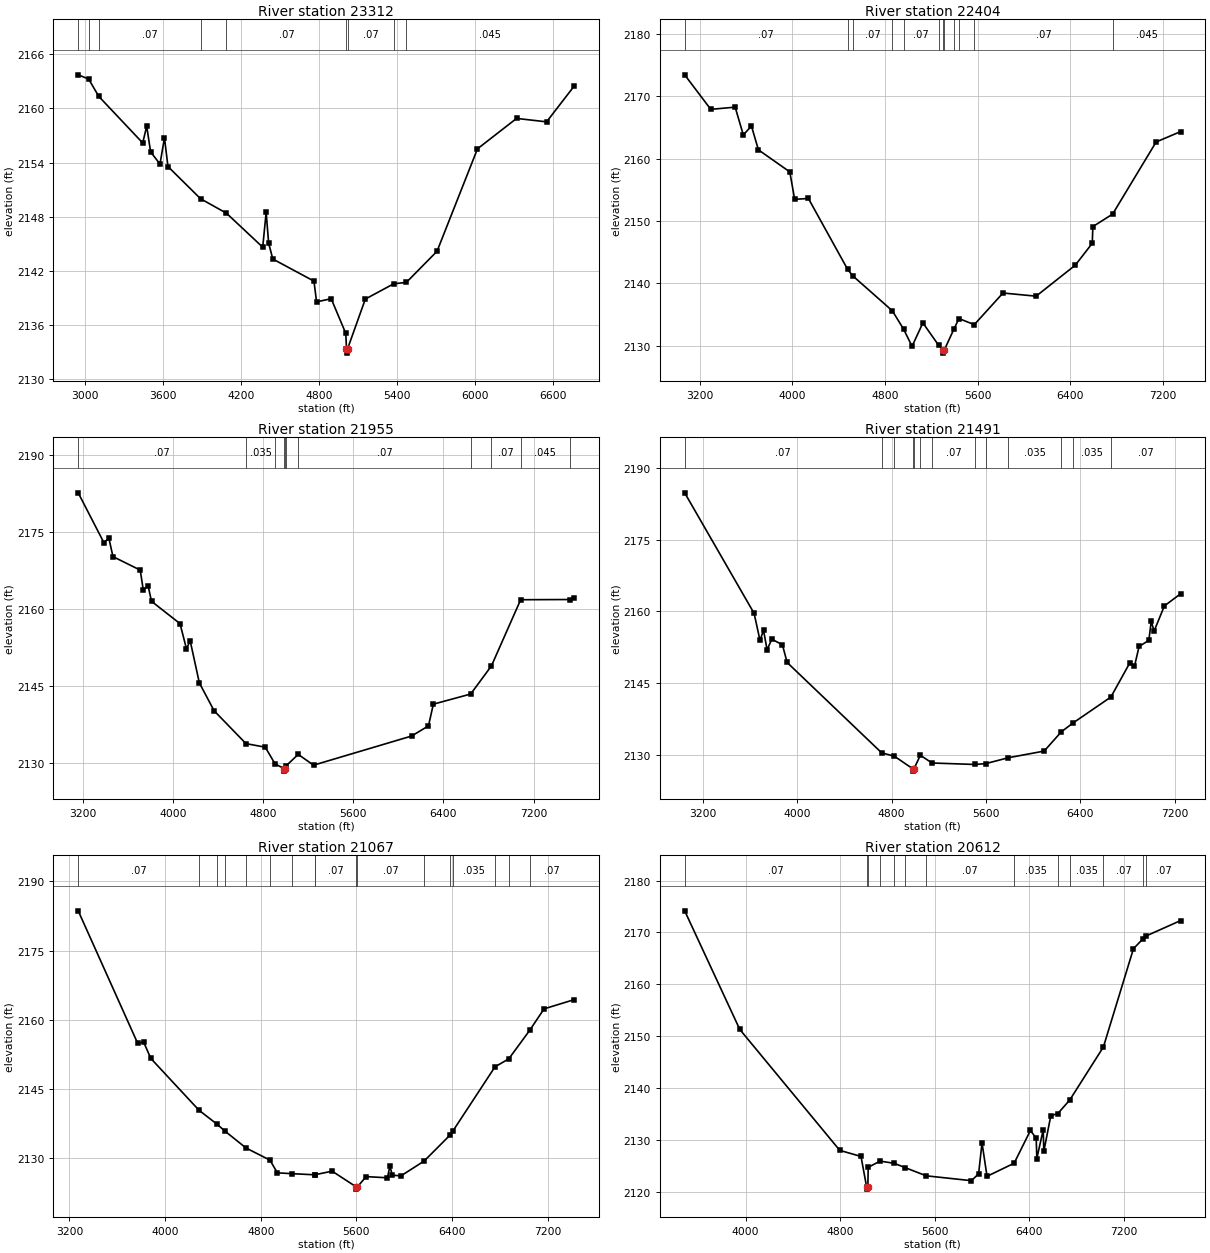
Type RM Length L Ch R = 1 ,23312   ,908,908,908
BEGIN DESCRIPTION:
UCFB HW Trib 10 41.0
END DESCRIPTION:
XS GIS Cut Line= 3
      1305198.56      6960744.04        1305605.        6958738.
      1305728.09      6956976.59
#Sta/Elev= 30
  2948.6 2163.73  3028.8 2163.26  3106.6 2161.34  3444.5 2156.18  3475.1 2158.04
  3505.2 2155.19  3577.2 2153.84  3611.7 2156.75  3638.4 2153.57  3889.1    2150
  4087.8  2148.4  4366.9 2144.63  4393.4 2148.49  4412.5 2145.08  4444.4 2143.32
  4760.7 2140.87  4781.1 2138.57  4893.4 2138.92  5005.4 2135.08    5011 2133.39
  5011.5 2132.89  5019.9 2133.39  5155.8 2138.88  5373.4 2140.57  5471.3 2140.73
  5707.1 2144.18  6017.9 2155.53  6318.6  2158.9  6549.2 2158.52  6761.1 2162.48
#Mann= 9 ,-1 , 0
  2948.6     .07       0  3028.8    .035       0  3106.6     .07       0
  3889.1    .035       0  4087.8     .07       0    5011     .07       0
  5019.9     .07       0  5373.4    .035       0  5471.3    .045       0
Bank Sta=5011,5019.9
XS Rating Curve= 0 ,0
Exp/Cntr=0.3,0.1

Type RM Length L Ch R = 1 ,22404   ,449,449,449
BEGIN DESCRIPTION:
UCFB HW Trib 10 40.0
END DESCRIPTION:
XS GIS Cut Line= 3
      1306552.73      6960952.31        1306405.        6959038.
       1305762.8      6956768.31
#Sta/Elev= 30
    3072 2173.46    3297 2167.92  3507.6 2168.27  3577.8 2163.81    3648 2165.24
  3708.2 2161.42    3979 2157.88  4020.7 2153.48  4139.5 2153.61  4477.8 2142.24
  4522.5 2141.19  4863.8 2135.58  4962.2 2132.59  5033.6 2129.88  5127.1 2133.64
  5261.9 2130.08  5301.2 2129.29  5301.7 2128.79  5311.9 2129.29  5395.7 2132.68
  5438.4 2134.34  5570.6 2133.36  5818.3 2138.44    6104 2137.93  6442.3 2142.91
  6588.5 2146.42  6593.7  2149.1  6764.3 2151.11  7139.4 2162.68  7350.8 2164.35
#Mann= 12 ,-1 , 0
    3072     .07       0  4477.8    .035       0  4522.5     .07       0
  4863.8    .035       0  4962.2     .07       0  5261.9    .035       0
  5301.2     .07       0  5311.9    .035       0  5395.7     .07       0
  5438.4    .035       0  5570.6     .07       0  6764.3    .045       0
Bank Sta=5301.2,5311.9
XS Rating Curve= 0 ,0
Exp/Cntr=0.3,0.1

Type RM Length L Ch R = 1 ,21955   ,464,464,464
BEGIN DESCRIPTION:
UCFB HW Trib 10 39.0
END DESCRIPTION:
XS GIS Cut Line= 3
      1306995.44      6960613.77        1306755.        6958788.
      1305823.57      6956403.72
#Sta/Elev= 30
  3158.5  2182.6  3386.2 2172.91  3430.8 2173.75  3466.9 2170.19    3709 2167.56
  3735.3 2163.77  3779.6 2164.43  3808.9 2161.49    4062 2157.15  4118.4 2152.31
  4152.8 2153.75  4233.5 2145.62  4364.6 2140.19  4647.5  2133.8  4818.5 2133.11
  4905.2 2129.86  4984.6 2128.95  4985.1 2128.45  4995.4 2128.95  5004.6  2129.5
  5110.8 2131.71    5247 2129.61  6117.5 2135.28  6266.9 2137.26  6310.3 2141.48
  6641.4 2143.45  6825.6 2148.92  7085.1  2161.8  7524.6 2161.84  7559.8 2162.21
#Mann= 11 ,-1 , 0
  3158.5     .07       0  4647.5    .035       0  4905.2     .07       0
  4984.6     .07       0  4995.4     .07       0  5004.6    .035       0
  5110.8     .07       0  6641.4    .045       0  6825.6     .07       0
  7085.1    .045       0  7524.6    .035       0
Bank Sta=4984.6,4995.4
XS Rating Curve= 0 ,0
Exp/Cntr=0.3,0.1

Type RM Length L Ch R = 1 ,21491   ,424,424,424
BEGIN DESCRIPTION:
UCFB HW Trib 10 38.0
END DESCRIPTION:
XS GIS Cut Line= 3
      1307143.01       6960596.4        1307155.        6958638.
      1307516.12      6956422.06
#Sta/Elev= 30
  3045.8 2184.78  3634.2 2159.59  3684.2 2153.94  3714.2 2156.05  3744.2 2151.96
  3784.2 2154.19  3874.2 2153.02  3914.2 2149.32  4715.2 2130.44  4823.5 2129.72
  4978.8 2127.11  4979.3 2126.61  4989.6 2127.11  5043.3 2129.93  5142.1 2128.31
  5508.6    2128  5599.3 2128.19  5789.2 2129.41  6092.8  2130.8  6238.8 2134.84
    6340 2136.72  6658.6  2142.1  6817.8 2149.19  6858.4 2148.53  6897.2 2152.66
    6980 2153.95  7000.2  2157.9  7024.8 2155.89  7111.7 2161.14  7249.4 2163.68
#Mann= 13 ,-1 , 0
  3045.8     .07       0  4715.2    .035       0  4823.5     .07       0
  4978.8     .07       0  4989.6     .07       0  5043.3    .035       0
  5142.1     .07       0  5508.6    .035       0  5599.3     .07       0
  5789.2    .035       0  6238.8     .07       0    6340    .035       0
  6658.6     .07       0
Bank Sta=4978.8,4989.6
XS Rating Curve= 0 ,0
Exp/Cntr=0.3,0.1

Type RM Length L Ch R = 1 ,21067   ,455,455,455
BEGIN DESCRIPTION:
UCFB HW Trib 10 37.0
END DESCRIPTION:
XS GIS Cut Line= 3
      1307290.59      6960500.91        1307505.        6958788.
      1308019.53      6956422.08
#Sta/Elev= 30
  3273.8 2183.63  3770.6  2154.9    3821 2155.13  3881.4 2151.58  4284.9 2140.32
  4432.5 2137.36  4504.5 2135.74  4677.2 2132.15  4877.1 2129.52  4939.6 2126.75
  5058.7 2126.58  5251.5 2126.33  5252.3 2126.33  5397.1 2127.12  5598.4 2123.72
  5598.9 2123.22  5609.3 2123.72  5681.5 2125.94  5859.7 2125.68  5880.2 2128.21
  5900.7 2126.25  5972.3 2126.09  6166.9 2129.32  6386.2 2135.02    6405 2135.75
  6759.4 2149.77  6874.7  2151.5  7050.1 2157.71  7169.6 2162.35  7421.3 2164.35
#Mann= 17 ,-1 , 0
  3273.8     .07       0  4284.9    .035       0  4432.5     .07       0
  4504.5    .035       0  4677.2     .07       0  4877.1    .035       0
  5058.7     .07       0  5251.5    .035       0  5252.3     .07       0
  5598.4    .035       0  5609.3     .07       0  6166.9    .035       0
  6386.2     .07       0    6405    .035       0  6759.4     .07       0
  6874.7    .035       0  7050.1     .07       0
Bank Sta=5598.4,5609.3
XS Rating Curve= 0 ,0
Exp/Cntr=0.3,0.1

Type RM Length L Ch R = 1 ,20612   ,414,414,414
BEGIN DESCRIPTION:
UCFB HW Trib 10 36.0
END DESCRIPTION:
XS GIS Cut Line= 3
      1307542.32      6960526.99        1307805.        6959038.
      1308271.49      6956395.03
#Sta/Elev= 30
  3484.3 2174.18  3950.4 2151.29  4796.5 2127.94    4976 2126.77    5023 2120.96
  5023.5 2120.46  5033.9 2120.96  5036.9 2124.67    5138 2125.87  5257.2 2125.44
  5348.6 2124.62  5527.7 2123.03  5910.2 2122.09  5971.1 2123.42  5999.8  2129.4
  6042.2 2122.93  6271.6 2125.46  6409.3 2131.78  6458.4 2130.29  6463.5 2126.36
  6517.6 2131.93  6522.7 2127.75  6581.9 2134.63  6641.3 2135.05  6742.1 2137.66
  7026.6 2147.89  7281.1 2166.87  7364.1 2168.83  7387.5 2169.32  7680.1  2172.3
#Mann= 13 ,-1 , 0
  3484.3     .07       0    5023     .07       0  5033.9     .07       0
    5138    .035       0  5257.2     .07       0  5348.6    .035       0
  5527.7     .07       0  6271.6    .035       0  6641.3     .07       0
  6742.1    .035       0  7026.6     .07       0  7364.1    .035       0
  7387.5     .07       0
Bank Sta=5023,5033.9
XS Rating Curve= 0 ,0
Exp/Cntr=0.3,0.1

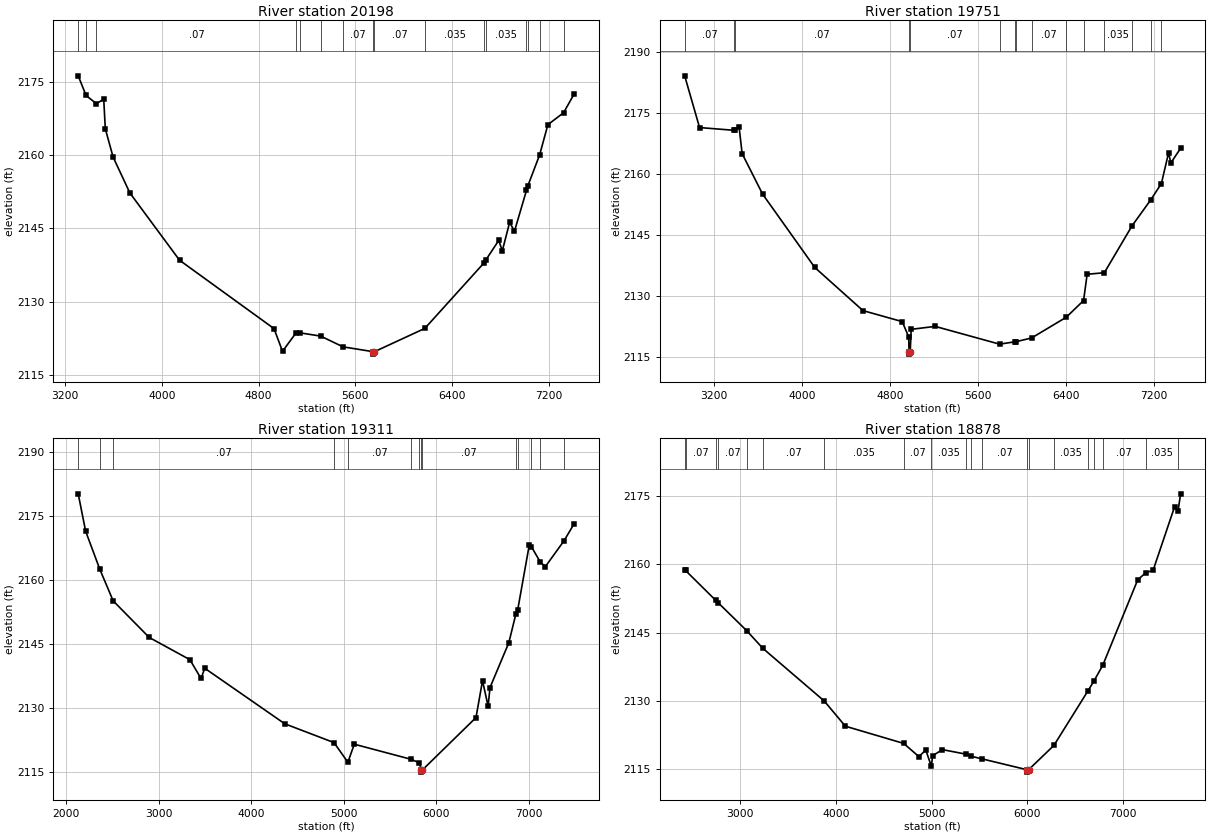
Type RM Length L Ch R = 1 ,20198   ,447,447,447
BEGIN DESCRIPTION:
UCFB HW Trib 10 35.0
END DESCRIPTION:
XS GIS Cut Line= 3
      1307679.99      6960613.04        1308155.        6958988.
      1308358.29      6956586.03
#Sta/Elev= 30
  3307.3 2176.19  3372.2 2172.17  3458.1 2170.49  3518.5 2171.41  3531.3 2165.38
  3595.8 2159.58  3734.8 2152.22    4146 2138.45  4927.4 2124.46  4997.7 2119.82
  5111.3 2123.63  5138.4 2123.61  5313.6 2122.93  5498.4 2120.73  5747.5 2119.74
    5748 2119.24  5758.5 2119.74  6175.6 2124.51  6666.9 2137.96  6677.8 2138.42
  6786.7  2142.5  6816.8  2140.4    6877 2146.21  6917.2  2144.4  7016.2 2152.73
  7027.6 2153.66  7125.6 2160.04  7193.6  2166.2  7323.3 2168.63  7410.9 2172.48
#Mann= 16 ,-1 , 0
  3307.3     .07       0  3372.2    .035       0  3458.1     .07       0
  5111.3    .035       0  5138.4     .07       0  5313.6    .035       0
  5498.4     .07       0  5747.5     .07       0  5758.5     .07       0
  6175.6    .035       0  6666.9     .07       0  6677.8    .035       0
  7016.2     .07       0  7027.6    .035       0  7125.6     .07       0
  7323.3    .035       0
Bank Sta=5747.5,5758.5
XS Rating Curve= 0 ,0
Exp/Cntr=0.3,0.1

Type RM Length L Ch R = 1 ,19751   ,440,440,440
BEGIN DESCRIPTION:
UCFB HW Trib 10 34.0
END DESCRIPTION:
XS GIS Cut Line= 3
      1307611.77      6960978.36        1308555.        6959138.
      1308436.42      6956698.88
#Sta/Elev= 30
  2933.1 2184.24  3068.4  2171.5  3386.1 2170.81  3386.3 2170.83  3427.9  2171.6
  3455.7 2165.07  3641.4 2155.12  4116.1 2137.04  4554.4 2126.41  4911.2  2123.7
  4970.6 2119.92  4973.1 2116.19  4973.6 2115.69  4984.1 2116.19  4992.8  2121.8
  5211.3 2122.52  5796.5 2118.15  5938.6 2118.73  5947.2 2118.76  6087.9 2119.67
  6403.4 2124.78  6560.6 2128.89    6593 2135.36  6749.4 2135.74  7001.4  2147.3
  7170.2 2153.64  7268.3 2157.71  7333.9 2165.32  7353.9 2162.76  7443.1  2166.4
#Mann= 15 ,-1 , 0
  2933.1     .07       0  3386.1    .035       0  3386.3     .07       0
  4973.1     .07       0  4984.1     .07       0  5796.5    .035       0
  5938.6     .07       0  5947.2    .035       0  6087.9     .07       0
  6403.4    .035       0  6560.6     .07       0  6749.4    .035       0
  7001.4     .07       0  7170.2    .035       0  7268.3     .07       0
Bank Sta=4973.1,4984.1
XS Rating Curve= 0 ,0
Exp/Cntr=0.3,0.1

Type RM Length L Ch R = 1 ,19311   ,433,433,433
BEGIN DESCRIPTION:
UCFB HW Trib 10 33.0
END DESCRIPTION:
XS GIS Cut Line= 3
      1308575.31      6961837.75        1308855.        6958988.
      1308540.58      6956516.56
#Sta/Elev= 30
  2131.6 2180.17  2211.7  2171.4    2364 2162.51    2509 2155.05  2898.2 2146.47
  3337.1 2141.26  3457.7 2136.84  3497.9 2139.24    4362 2126.21  4893.1  2121.8
  5043.3 2117.19  5112.4 2121.42  5727.6 2117.87  5815.7 2117.04  5836.3 2115.37
  5836.8 2114.87  5847.4 2115.37  6426.5 2127.67    6497 2136.32  6557.5 2130.33
  6577.7 2134.71  6781.1 2145.24  6855.8 2151.86  6875.7  2152.8  7001.1 2168.08
  7023.6 2167.81  7122.7 2164.09  7175.8  2163.1  7378.6  2169.2  7486.4 2173.16
#Mann= 14 ,-1 , 0
  2131.6     .07       0    2364    .035       0    2509     .07       0
  4893.1    .035       0  5043.3     .07       0  5727.6    .035       0
  5815.7     .07       0  5836.3    .035       0  5847.4     .07       0
  6855.8    .035       0  6875.7     .07       0  7023.6    .035       0
  7122.7     .07       0  7378.6    .035       0
Bank Sta=5836.3,5847.4
XS Rating Curve= 0 ,0
Exp/Cntr=0.3,0.1

Type RM Length L Ch R = 1 ,18878   ,478,478,478
BEGIN DESCRIPTION:
UCFB HW Trib 10 32.0
END DESCRIPTION:
XS GIS Cut Line= 3
      1309755.86      6961620.73        1309255.        6959088.
        1308801.      6956525.28
#Sta/Elev= 30
  2418.9 2158.75  2427.7 2158.59  2743.4 2152.05  2772.4 2151.45  3066.1 2145.43
  3236.3 2141.53  3877.4 2130.01  4098.6 2124.48  4708.2 2120.71  4867.4 2117.82
  4939.5 2119.26    4997 2115.72  5010.8    2118  5112.4 2119.35  5361.7 2118.35
    5413  2117.9  5525.8 2117.33    6002 2114.92  6002.5 2114.42  6013.1 2114.92
  6278.7 2120.27  6635.2 2132.24  6697.8  2134.4    6790 2137.85  7154.6 2156.53
  7237.8 2158.08  7316.2 2158.65  7539.6 2172.51  7576.1 2171.64  7603.3 2175.38
#Mann= 20 ,-1 , 0
  2418.9    .035       0  2427.7     .07       0  2743.4    .035       0
  2772.4     .07       0  3066.1    .035       0  3236.3     .07       0
  3877.4    .035       0  4708.2     .07       0    4997    .035       0
  5361.7     .07       0    5413    .035       0  5525.8     .07       0
    6002    .035       0  6013.1     .07       0  6278.7    .035       0
  6635.2     .07       0  6697.8    .035       0    6790     .07       0
  7237.8    .035       0  7576.1     .07       0
Bank Sta=6002,6013.1
XS Rating Curve= 0 ,0
Exp/Cntr=0.3,0.1