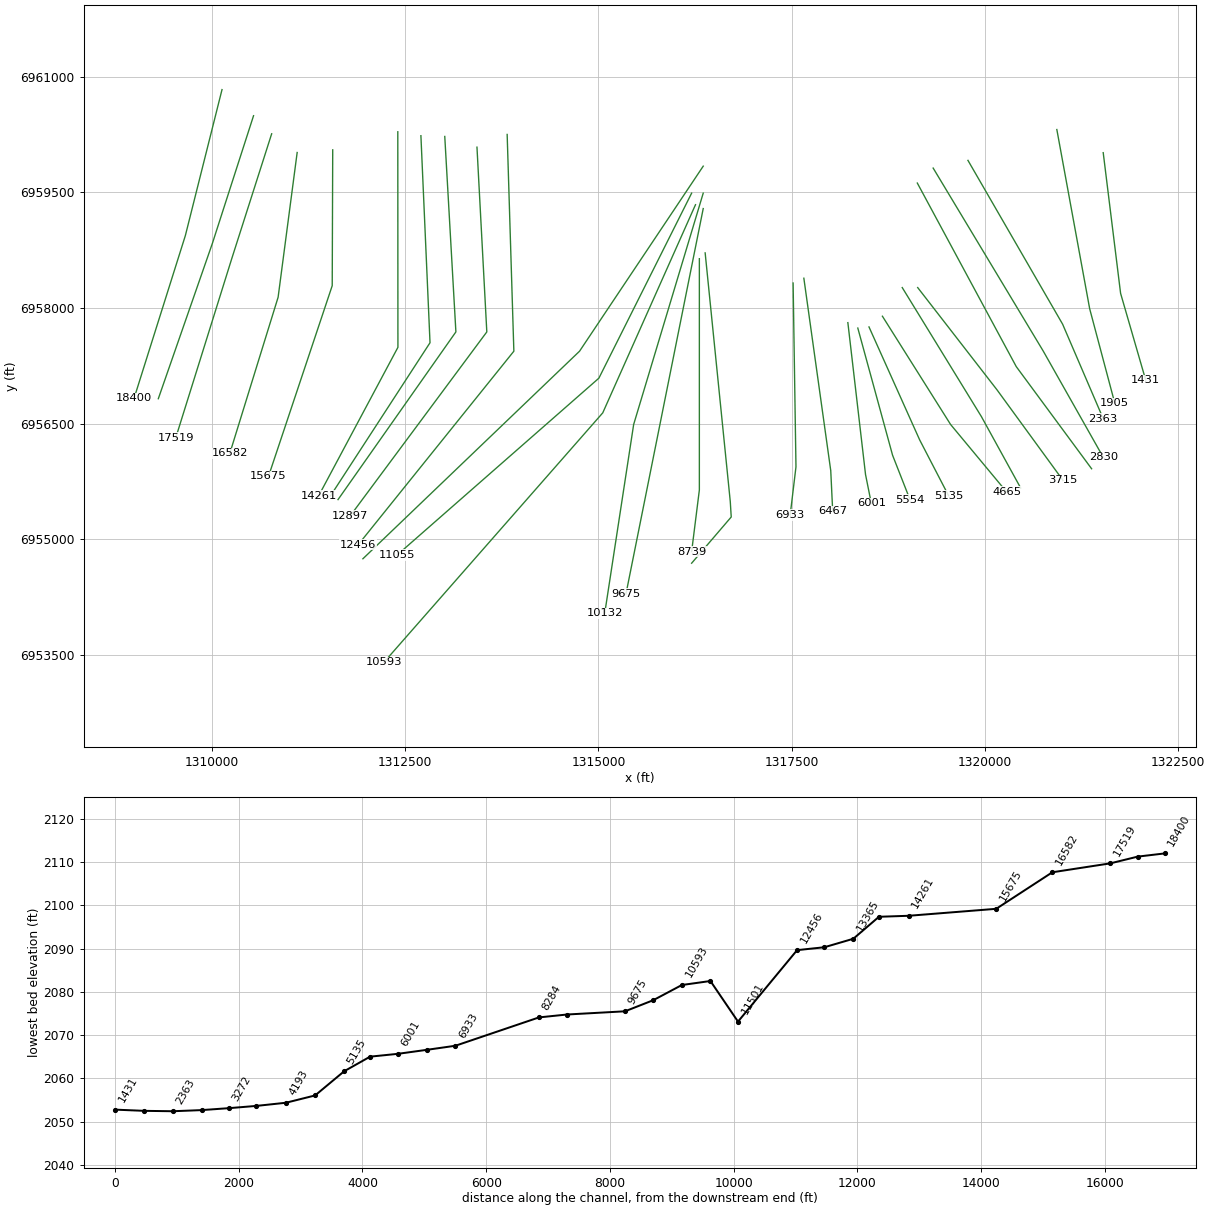
HEC-RAS study UCFB HW Trib 10.prj: UCFB HW Trib 10 Base Level Engineering

--- UCFB HW Trib 10.g01 (geometry) --- (continued)

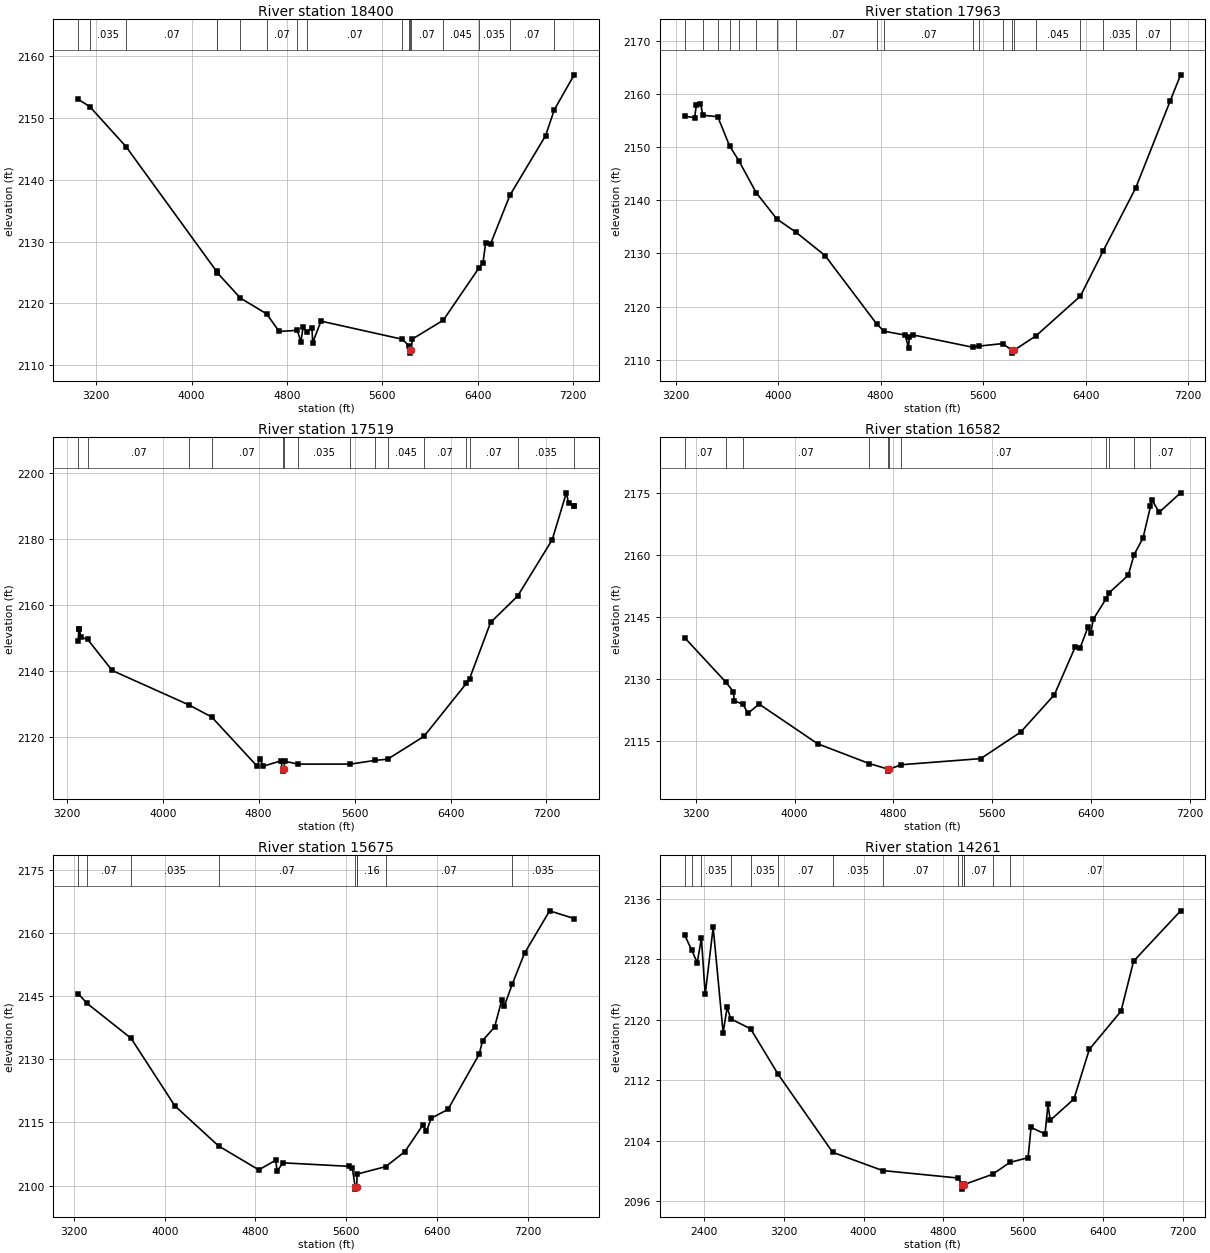
Type RM Length L Ch R = 1 ,18400   ,437,437,437
BEGIN DESCRIPTION:
UCFB HW Trib 10 31.0
END DESCRIPTION:
XS GIS Cut Line= 3
      1310129.12      6960830.79        1309655.        6958938.
      1308991.96      6956829.03
#Sta/Elev= 30
  3048.7 2152.98  3145.5 2151.81  3450.3 2145.33  4210.2 2125.18  4215.1 2124.98
  4410.1 2120.87  4630.1 2118.32  4734.8 2115.48  4887.5 2115.66  4917.5  2113.8
  4935.6 2116.13  4968.5 2115.45  5010.4 2116.11  5016.2 2113.66  5086.2 2117.15
  5768.8 2114.22  5828.9 2113.06    5833 2112.48  5833.5 2111.98  5844.1 2112.48
  5852.2 2114.25  6112.5  2117.3  6410.4  2125.7  6445.8  2126.6  6467.5  2129.7
  6509.5 2129.64    6672  2137.5  6970.7  2147.1  7044.1 2151.29  7210.7 2156.94
#Mann= 17 ,-1 , 0
  3048.7     .07       0  3145.5    .035       0  3450.3     .07       0
  4210.2    .035       0  4215.1     .07       0  4410.1    .035       0
  4630.1     .07       0  4887.5    .035       0  4968.5     .07       0
  5768.8    .035       0  5828.9     .07       0    5833     .07       0
  5844.1     .07       0  6112.5    .045       0  6410.4    .035       0
    6672     .07       0  7044.1    .035       0
Bank Sta=5833,5844.1
XS Rating Curve= 0 ,0
Exp/Cntr=0.3,0.1

Type RM Length L Ch R = 1 ,17963   ,444,444,444
BEGIN DESCRIPTION:
UCFB HW Trib 10 30.0
END DESCRIPTION:
XS GIS Cut Line= 3
       1310537.1      6960492.22        1310005.        6958838.
      1309304.92      6956821.67
#Sta/Elev= 30
  3269.7 2155.76  3347.7 2155.53  3360.8 2157.91  3392.9 2158.16  3412.6 2155.96
  3527.8  2155.7  3620.1 2150.21  3692.5 2147.42  3827.5 2141.43  3989.2 2136.46
  4138.8 2133.97    4366 2129.58  4771.8 2116.63  4826.6 2115.36  4991.3 2114.63
  5017.7 2112.21  5022.9 2114.29  5054.1 2114.65  5521.7 2112.33  5569.3 2112.57
  5752.3 2113.03  5827.1 2111.74  5827.6 2111.24  5839.1 2111.74  6014.6 2114.53
  6359.3 2121.96  6537.7 2130.48  6790.9 2142.28  7060.8 2158.69  7141.8 2163.57
#Mann= 20 ,-1 , 0
  3269.7     .07       0  3412.6     .07       0  3527.8    .035       0
  3620.1     .07       0  3692.5    .035       0  3827.5     .07       0
  3989.2    .035       0  4138.8     .07       0  4771.8    .035       0
  4826.6     .07       0  5521.7    .035       0  5569.3     .07       0
  5752.3    .035       0  5827.1     .07       0  5839.1    .035       0
  6014.6    .045       0  6359.3     .07       0  6537.7    .035       0
  6790.9     .07       0  7060.8    .035       0
Bank Sta=5827.1,5839.1
XS Rating Curve= 0 ,0
Exp/Cntr=0.3,0.1

Type RM Length L Ch R = 1 ,17519   ,937,937,937
BEGIN DESCRIPTION:
UCFB HW Trib 10 29.0
END DESCRIPTION:
XS GIS Cut Line= 3
      1310771.48      6960257.86        1310255.        6958638.
      1309530.01      6956313.02
#Sta/Elev= 30
  3295.1 2148.95  3300.1 2152.55  3305.5 2152.75  3315.9 2150.22  3374.3 2149.52
  3578.3 2140.14  4219.2  2129.7  4407.6 2126.08    4786 2111.22  4812.9  2113.4
  4837.9 2111.17  4984.8 2112.78  4999.7 2110.18  5000.2 2109.68  5011.8 2110.18
  5016.8 2112.69  5127.4  2111.8  5565.4 2111.81  5772.3 2112.94  5875.7  2113.3
  6178.1 2120.19  6532.4 2136.26  6558.7 2137.68  6734.1 2154.69  6959.2 2162.66
  7247.4 2179.68  7365.7 2193.91  7383.6 2190.94  7427.1 2189.94  7430.7 2189.94
#Mann= 15 ,-1 , 0
  3295.1    .035       0  3374.3     .07       0  4219.2    .035       0
  4407.6     .07       0  4999.7     .07       0  5011.8     .07       0
  5127.4    .035       0  5565.4     .07       0  5772.3    .035       0
  5875.7    .045       0  6178.1     .07       0  6532.4    .035       0
  6558.7     .07       0  6959.2    .035       0  7427.1     .07       0
Bank Sta=4999.7,5011.8
XS Rating Curve= 0 ,0
Exp/Cntr=0.3,0.1

Type RM Length L Ch R = 1 ,16582   ,907,907,907
BEGIN DESCRIPTION:
UCFB HW Trib 10 28.0
END DESCRIPTION:
XS GIS Cut Line= 3
      1311101.35      6960014.85        1310855.        6958138.
        1310230.        6956113.
#Sta/Elev= 30
  3111.4 2139.91  3442.2 2129.24  3506.3 2126.83  3511.7 2124.63  3583.6 2123.83
  3622.6  2121.6  3713.4 2123.85  4187.4 2114.24  4605.3 2109.44  4756.2 2108.12
  4756.7 2107.62  4768.3 2108.12  4863.4 2109.17  5506.7 2110.65  5830.5 2117.09
  6102.2  2126.1  6270.7 2137.66  6308.6 2137.34  6373.9 2142.46  6396.3 2140.96
  6417.2 2144.39  6519.3 2149.28  6546.9 2150.84  6699.8 2155.03  6747.7 2160.05
  6819.3 2164.03  6879.9  2171.7  6889.8 2173.37  6949.9 2170.27  7123.6 2174.99
#Mann= 11 ,-1 , 0
  3111.4     .07       0  3442.2    .035       0  3583.6     .07       0
  4605.3    .035       0  4756.2     .07       0  4768.3    .035       0
  4863.4     .07       0  6519.3    .035       0  6546.9     .07       0
  6747.7    .035       0  6879.9     .07       0
Bank Sta=4756.2,4768.3
XS Rating Curve= 0 ,0
Exp/Cntr=0.3,0.1

Type RM Length L Ch R = 1 ,15675   ,1414,1414,1414
BEGIN DESCRIPTION:
UCFB HW Trib 10 27.0
END DESCRIPTION:
XS GIS Cut Line= 3
      1311561.42      6960049.58        1311555.        6958288.
      1310729.99      6955812.98
#Sta/Elev= 30
  3237.9 2145.56  3313.7 2143.29  3703.6 2134.96  4089.5 2118.93  4475.5 2109.41
  4829.5 2103.75  4979.5 2106.06  4989.5 2103.41  5041.7 2105.42  5621.4 2104.59
    5653 2104.29  5678.6 2099.68  5679.1 2099.18  5690.7 2099.68    5697 2102.75
  5947.6 2104.52  6116.8 2108.08  6274.9 2114.37  6306.6 2112.89  6348.7    2116
  6496.3 2118.09  6770.4 2131.13    6802 2134.42  6907.4 2137.65  6970.6 2144.01
  6991.7 2142.53  7064.9 2147.95  7170.9 2155.12  7392.3  2165.2  7608.4 2163.37
#Mann= 9 ,-1 , 0
  3237.9    .035       0  3313.7     .07       0  3703.6    .035       0
  4475.5     .07       0  5678.6     .07       0  5690.7     .07       0
    5697     .16       0  5947.6     .07       0  7064.9    .035       0
Bank Sta=5678.6,5690.7
XS Rating Curve= 0 ,0
Exp/Cntr=0.3,0.1

Type RM Length L Ch R = 1 ,14261   ,482,482,482
BEGIN DESCRIPTION:
UCFB HW Trib 10 26.0
END DESCRIPTION:
XS GIS Cut Line= 3
      1312403.43       6960283.9        1312405.        6957488.
      1311379.99      6955562.99
#Sta/Elev= 30
    2204 2131.22  2274.2 2129.23  2329.9 2127.57    2372  2130.8  2409.9 2123.35
  2489.9 2132.24  2589.9 2118.27  2629.9 2121.64  2665.7 2120.13  2865.6  2118.8
  3142.5 2112.77    3689 2102.45  4190.6 2100.03  4947.5 2099.04  4991.4 2098.07
  4991.9 2097.57  5003.5 2098.07  5010.2 2098.19  5294.7 2099.54  5467.1 2101.11
  5650.1 2101.73  5679.7 2105.75  5820.2 2104.87  5849.6 2108.78  5872.3 2106.69
  6110.2  2109.5  6264.5 2116.08  6582.7 2121.14  6708.8 2127.76  7180.8 2134.43
#Mann= 14 ,-1 , 0
    2204    .035       0  2274.2     .07       0    2372    .035       0
  2665.7     .07       0  2865.6    .035       0  3142.5     .07       0
    3689    .035       0  4190.6     .07       0  4947.5    .035       0
  4991.4    .035       0  5003.5    .035       0  5010.2     .07       0
  5294.7    .035       0  5467.1     .07       0
Bank Sta=4991.4,5003.5
XS Rating Curve= 0 ,0
Exp/Cntr=0.3,0.1

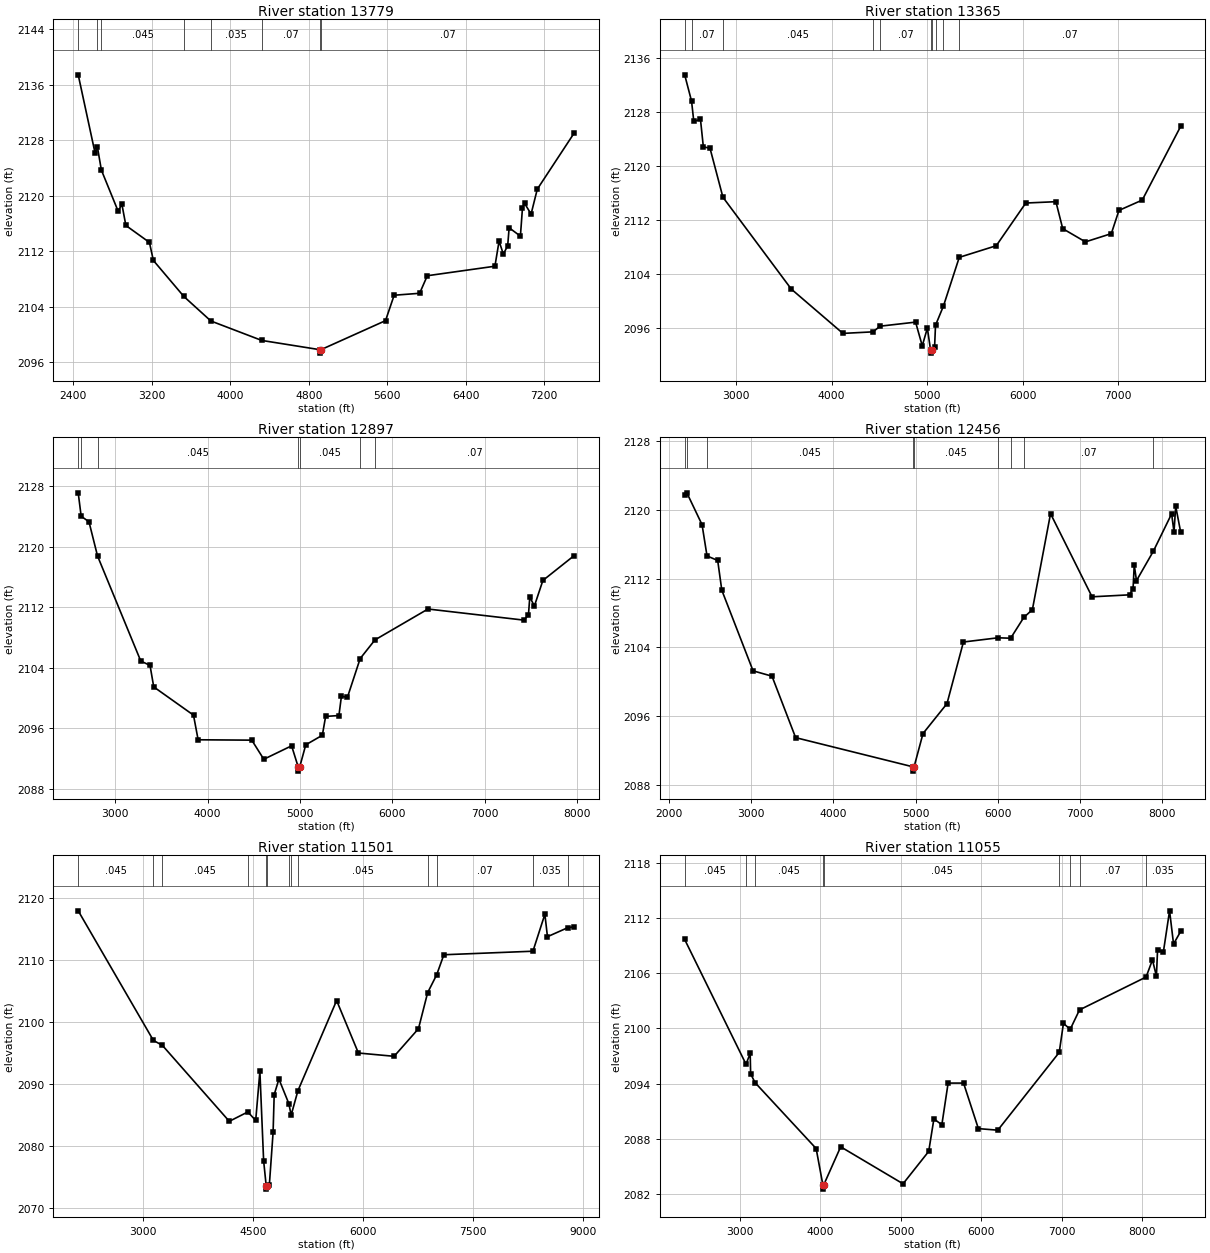
Type RM Length L Ch R = 1 ,13779   ,414,414,414
BEGIN DESCRIPTION:
UCFB HW Trib 10 26.5
END DESCRIPTION:
XS GIS Cut Line= 3
      1312702.38      6960233.14      1312820.24      6957547.69
       1311532.9        6955562.
#Sta/Elev= 30
  2450.6 2137.43  2622.6 2126.15  2645.6 2127.08  2686.6 2123.71  2856.8 2117.81
  2896.2 2118.76  2936.2 2115.73  3176.4 2113.29  3216.5 2110.69  3527.4  2105.5
  3802.6 2101.97  4320.8 2099.17  4911.4 2097.84  4911.9 2097.34  4924.9 2097.84
  5582.7 2102.02  5670.4 2105.68  5930.2 2105.96  6008.6 2108.49  6697.6 2109.86
  6739.8 2113.47  6782.9 2111.62  6827.4 2112.77  6842.5  2115.4  6957.3 2114.19
  6978.4 2118.25  6999.5 2118.92  7066.1 2117.37  7129.4 2120.96  7505.1 2129.04
#Mann= 8 ,-1 , 0
  2450.6    .035       0  2645.6     .07       0  2686.6    .045       0
  3527.4     .07       0  3802.6    .035       0  4320.8     .07       0
  4911.4     .07       0  4924.9     .07       0
Bank Sta=4911.4,4924.9
XS Rating Curve= 0 ,0
Exp/Cntr=0.3,0.1

Type RM Length L Ch R = 1 ,13365   ,468,468,468
BEGIN DESCRIPTION:
UCFB HW Trib 10 25.0
END DESCRIPTION:
XS GIS Cut Line= 3
      1313011.07      6960223.21        1313155.        6957688.
      1311629.97      6955512.96
#Sta/Elev= 30
  2460.4 2133.46  2532.5 2129.56  2555.8 2126.57  2625.9 2126.86  2655.9 2122.81
    2726 2122.58    2861 2115.34  3577.4 2101.74  4118.3 2095.18    4433 2095.41
  4508.4 2096.25  4879.5 2096.85  4949.6 2093.34  5002.7 2095.96  5036.1 2092.76
  5036.6 2092.26  5049.6 2092.76  5078.6 2093.16  5088.2 2096.38  5171.5 2099.24
  5337.1 2106.44  5724.5 2108.16  6033.9 2114.48  6349.4 2114.68  6420.9 2110.69
  6658.9 2108.73    6930 2109.95  7010.2 2113.39  7254.2 2114.92  7656.1 2125.82
#Mann= 10 ,-1 , 0
  2460.4    .035       0  2532.5     .07       0    2861    .045       0
    4433    .035       0  4508.4     .07       0  5036.1     .07       0
  5049.6     .07       0  5088.2    .045       0  5171.5    .035       0
  5337.1     .07       0
Bank Sta=5036.1,5049.6
XS Rating Curve= 0 ,0
Exp/Cntr=0.3,0.1

Type RM Length L Ch R = 1 ,12897   ,441,441,441
BEGIN DESCRIPTION:
UCFB HW Trib 10 24.0
END DESCRIPTION:
XS GIS Cut Line= 3
      1313427.73      6960084.31        1313555.        6957688.
      1311787.73      6955302.13
#Sta/Elev= 30
  2600.3 2127.14  2632.2 2124.04  2716.8 2123.31  2809.4 2118.78  3277.6 2104.87
  3377.7  2104.3  3417.8 2101.45  3848.4 2097.71  3898.4 2094.45  4479.3  2094.4
  4609.4 2091.87  4910.3 2093.65  4983.2  2090.8  4983.7  2090.3  4996.8  2090.8
  5063.6 2093.78  5243.1 2095.05  5278.6 2097.54  5422.6 2097.66  5449.7 2100.22
  5514.4 2100.06  5652.6  2105.2  5812.7 2107.67  6386.8 2111.76  7424.1 2110.29
  7474.2 2110.96  7488.8 2113.34  7538.7 2112.16  7630.6 2115.54  7969.1 2118.83
#Mann= 7 ,-1 , 0
  2600.3    .035       0  2632.2     .07       0  2809.4    .045       0
  4983.2    .045       0  4996.8    .045       0  5652.6    .035       0
  5812.7     .07       0
Bank Sta=4983.2,4996.8
XS Rating Curve= 0 ,0
Exp/Cntr=0.3,0.1

Type RM Length L Ch R = 1 ,12456   ,955,955,955
BEGIN DESCRIPTION:
UCFB HW Trib 10 23.0
END DESCRIPTION:
XS GIS Cut Line= 3
      1313818.36      6960249.17        1313905.        6957438.
      1311891.29      6954928.05
#Sta/Elev= 30
  2192.1 2121.72  2218.5 2121.96  2403.4 2118.26  2463.7 2114.63  2593.5  2114.1
  2643.5 2110.65  3023.7 2101.28  3253.8 2100.66  3541.3 2093.52  4967.8 2090.13
  4968.3 2089.63  4981.4 2090.13  5090.2    2094  5381.5 2097.47  5581.5 2104.63
    6003 2105.12  6155.7 2105.07  6315.4 2107.48  6420.1 2108.39  6640.9 2119.54
  7145.6 2109.88  7601.1 2110.11  7644.3 2110.83  7658.5 2113.58  7685.9 2111.76
  7891.6 2115.19  8113.1 2119.52  8141.9 2117.41  8162.8 2120.39  8222.5 2117.43
#Mann= 9 ,-1 , 0
  2192.1    .035       0  2218.5     .07       0  2463.7    .045       0
  4967.8    .045       0  4981.4    .045       0    6003    .035       0
  6155.7    .045       0  6315.4     .07       0  7891.6    .035       0
Bank Sta=4967.8,4981.4
XS Rating Curve= 0 ,0
Exp/Cntr=0.3,0.1

Type RM Length L Ch R = 1 ,11501   ,446,446,446
BEGIN DESCRIPTION:
UCFB HW Trib 10 22.0
END DESCRIPTION:
XS GIS Cut Line= 3
        1316355.        6959838.        1314755.        6957438.
      1311952.07      6954745.76
#Sta/Elev= 30
  2110.7 2117.98  3137.1 2097.09  3259.3  2096.3  4173.4 2084.05  4426.4 2085.56
  4533.9 2084.19    4591 2092.09  4642.1 2077.69  4677.4 2073.62  4677.9 2073.12
    4691 2073.62  4720.2 2073.79  4771.3 2082.26  4786.3 2088.35  4850.9 2090.85
  4985.7 2086.92  5018.2 2085.06  5110.2 2088.98  5638.7 2103.52  5935.9 2095.06
  6423.7 2094.53  6756.1 2098.98  6881.4 2104.79    7004 2107.65  7102.7  2110.9
    8319 2111.47  8481.9 2117.43  8517.1 2113.81  8791.9 2115.25  8881.6 2115.41
#Mann= 13 ,-1 , 0
  2110.7    .045       0  3137.1    .035       0  3259.3    .045       0
  4426.4     .07       0  4677.4    .045       0    4691     .07       0
  4985.7    .045       0  5018.2     .07       0  5110.2    .045       0
  6881.4    .035       0    7004     .07       0    8319    .035       0
  8791.9    .045       0
Bank Sta=4677.4,4691
XS Rating Curve= 0 ,0
Exp/Cntr=0.3,0.1

Type RM Length L Ch R = 1 ,11055   ,462,462,462
BEGIN DESCRIPTION:
UCFB HW Trib 10 21.0
END DESCRIPTION:
XS GIS Cut Line= 3
      1316205.02      6959488.03        1315005.        6957088.
      1312394.77      6954794.36
#Sta/Elev= 30
  2317.6 2109.69  3079.4  2096.1    3131 2097.29  3136.6 2095.06  3191.3  2094.1
    3950 2086.92  4032.6    2083  4033.1  2082.5  4046.2    2083  4254.6 2087.11
  5028.9 2083.08  5347.7 2086.61  5412.2 2090.15  5510.9 2089.51  5588.7 2094.05
  5780.4 2094.05  5964.5 2089.09  6205.5 2088.92  6968.4 2097.39  7020.6 2100.55
    7105 2099.91  7220.1 2102.02  8047.1  2105.6    8126 2107.47  8175.3 2105.69
  8189.5 2108.58  8260.7 2108.28  8338.5 2112.81  8387.9  2109.2  8475.7 2110.56
#Mann= 9 ,-1 , 0
  2317.6    .045       0  3079.4    .035       0  3191.3    .045       0
  4032.6    .045       0  4046.2    .045       0  6968.4     .07       0
    7105    .035       0  7220.1     .07       0  8047.1    .035       0
Bank Sta=4032.6,4046.2
XS Rating Curve= 0 ,0
Exp/Cntr=0.3,0.1

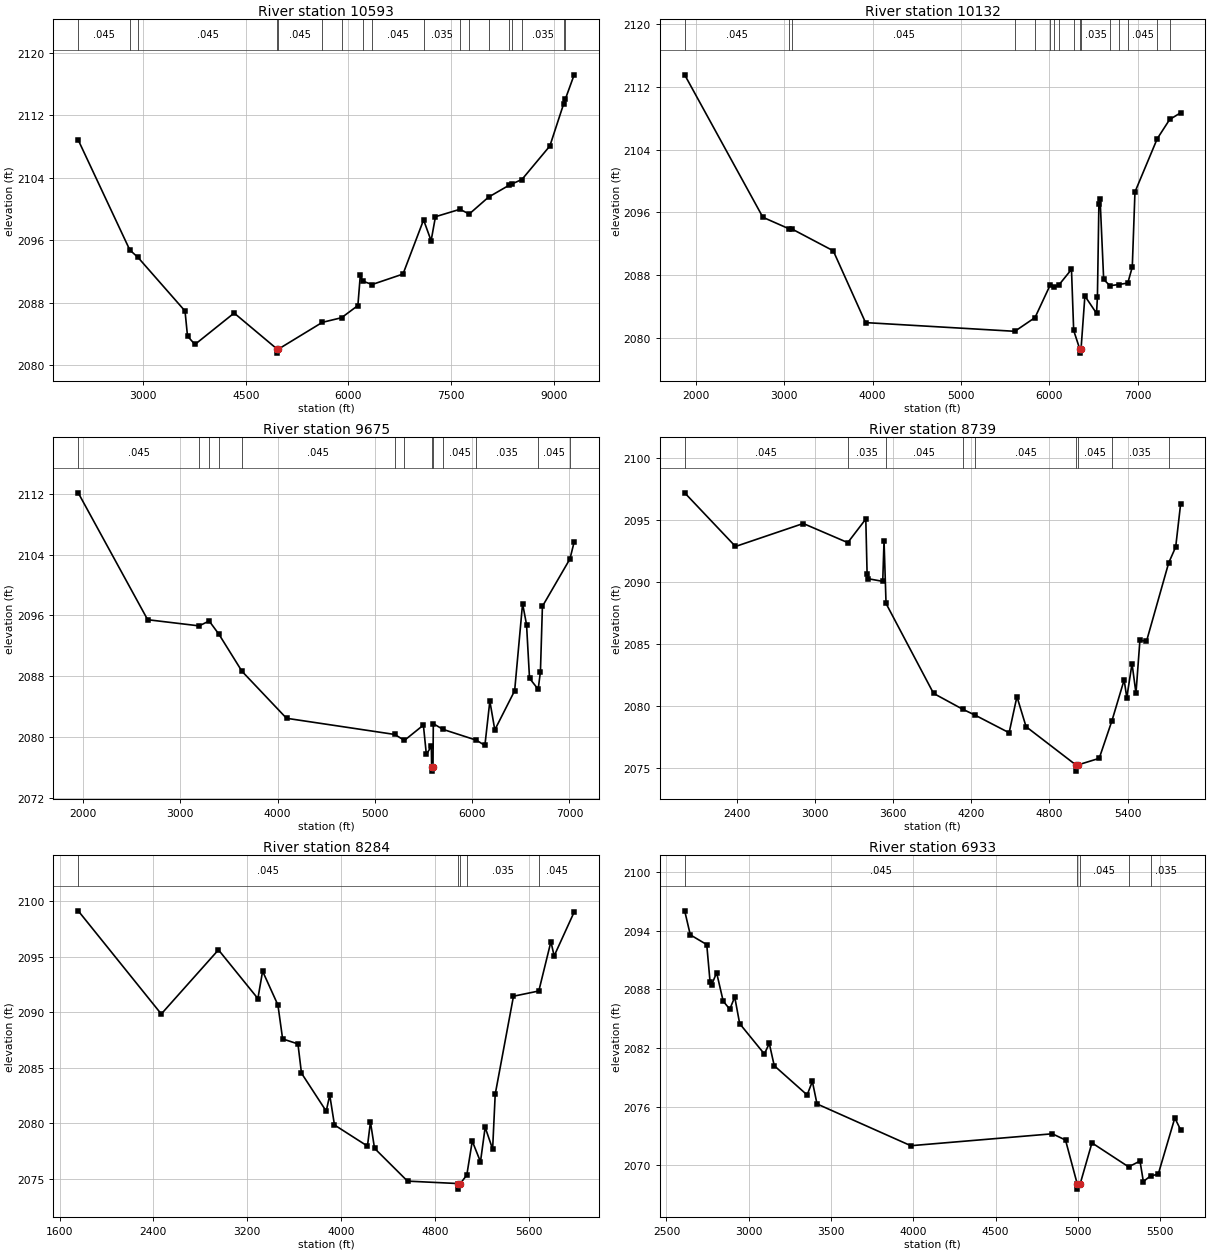
Type RM Length L Ch R = 1 ,10593   ,461,461,461
BEGIN DESCRIPTION:
UCFB HW Trib 10 20.0
END DESCRIPTION:
XS GIS Cut Line= 3
        1316255.      6959337.99        1315055.        6956638.
      1312226.32      6953405.43
#Sta/Elev= 30
  2050.8 2108.85  2805.1 2094.77  2925.8 2093.81  3612.2 2086.96  3648.5 2083.75
  3757.2 2082.68  4330.4  2086.7    4961 2082.07  4961.5 2081.57  4974.7 2082.07
  5619.6 2085.51  5900.1  2086.1  6139.2 2087.66  6174.8 2091.55  6209.9 2090.79
  6346.5 2090.35  6798.8 2091.69  7099.9 2098.62  7209.8 2095.95  7273.4 2099.03
  7631.9 2099.98  7766.5 2099.37  8049.7 2101.54  8354.2 2103.08  8394.7 2103.24
  8536.8 2103.79  8945.7 2108.08  9148.3  2113.5  9172.2 2114.08  9300.9 2117.19
#Mann= 18 ,-1 , 0
  2050.8    .045       0  2805.1    .035       0  2925.8    .045       0
    4961    .045       0  4974.7    .045       0  5619.6     .07       0
  5900.1     .16       0  6209.9     .07       0  6346.5    .045       0
  7099.9    .035       0  7631.9    .045       0  7766.5    .035       0
  8049.7     .07       0  8354.2    .035       0  8394.7     .07       0
  8536.8    .035       0  9148.3     .07       0  9172.2    .035       0
Bank Sta=4961,4974.7
XS Rating Curve= 0 ,0
Exp/Cntr=0.3,0.1

Type RM Length L Ch R = 1 ,10132   ,457,457,457
BEGIN DESCRIPTION:
UCFB HW Trib 10 19.0
END DESCRIPTION:
XS GIS Cut Line= 3
      1316355.01      6959488.03        1315455.        6956488.
      1315080.51      6954037.37
#Sta/Elev= 30
  1873.5 2113.53  2758.3 2095.38  3054.4 2093.91  3091.6 2093.86  3554.4 2091.11
  3919.8 2081.96  5608.7 2080.85  5837.4  2082.6  6006.4 2086.69  6057.6  2086.5
  6105.8 2086.73  6249.9 2088.74  6274.7 2080.96  6344.2 2078.57  6344.7 2078.07
  6357.9 2078.57  6401.6 2085.35  6533.2 2083.14  6543.3 2085.18  6559.9 2097.02
  6573.6 2097.69  6614.1 2087.46    6685 2086.66  6783.6 2086.81  6886.6    2087
  6937.8 2089.03  6968.1  2098.6  7220.1 2105.39  7360.8 2107.84  7484.7 2108.69
#Mann= 16 ,-1 , 0
  1873.5    .045       0  3054.4    .035       0  3091.6    .045       0
  5608.7    .035       0  5837.4     .07       0  6006.4    .045       0
  6057.6    .035       0  6105.8    .045       0  6274.7    .035       0
  6344.2    .045       0  6357.9    .035       0    6685     .07       0
  6783.6    .035       0  6886.6    .045       0  7220.1    .035       0
  7360.8    .045       0
Bank Sta=6344.2,6357.9
XS Rating Curve= 0 ,0
Exp/Cntr=0.3,0.1

Type RM Length L Ch R = 1 ,9675    ,936,936,936
BEGIN DESCRIPTION:
UCFB HW Trib 10 18.0
END DESCRIPTION:
XS GIS Cut Line= 3
        1316355.      6959288.01        1315755.        6956288.
      1315355.01      6954288.03
#Sta/Elev= 30
  1949.7 2112.15  2663.6 2095.44  3192.2 2094.63  3296.3 2095.27  3396.7 2093.52
  3633.2 2088.65  4091.3 2082.46  5203.4 2080.33  5303.8 2079.55  5498.6 2081.56
  5529.2  2077.7  5580.2 2078.78  5583.6    2076  5584.1  2075.5  5597.3    2076
  5600.6 2081.75  5699.9    2081  6044.6 2079.57  6130.9 2078.88  6181.9 2084.73
  6232.9 2080.93  6436.8 2086.08  6518.4 2097.56  6559.2  2094.8  6589.8 2087.73
  6678.7 2086.28    6702 2088.59  6722.4  2097.2  7005.6 2103.45  7048.7 2105.68
#Mann= 13 ,-1 , 0
  1949.7    .045       0  3192.2    .035       0  3296.3    .045       0
  3396.7    .035       0  3633.2    .045       0  5203.4    .035       0
  5303.8     .07       0  5583.6    .045       0  5597.3     .07       0
  5699.9    .045       0  6044.6    .035       0  6678.7    .045       0
  7005.6    .035       0
Bank Sta=5583.6,5597.3
XS Rating Curve= 0 ,0
Exp/Cntr=0.3,0.1

Type RM Length L Ch R = 1 ,8739    ,455,455,455
BEGIN DESCRIPTION:
UCFB HW Trib 10 17.0
END DESCRIPTION:
XS GIS Cut Line= 3
        1316305.      6958637.99        1316305.        6955638.
        1316205.      6954838.02
#Sta/Elev= 30
  2000.3 2097.17  2390.3 2092.85  2910.3  2094.7    3252 2093.16  3390.3 2095.06
  3400.3 2090.66  3410.3 2090.25  3520.3 2090.04  3530.3 2093.32  3545.7 2088.26
  3910.3 2081.02  4132.9 2079.75  4230.8 2079.26  4490.3 2077.85  4550.3 2080.76
  4620.3 2078.34  5002.6 2075.26  5003.1 2074.76  5018.1 2075.26  5181.7 2075.79
  5279.8 2078.83  5373.2 2082.11  5393.3 2080.67  5433.6 2083.42  5463.9 2081.03
  5494.1  2085.3  5544.5 2085.21  5714.9 2091.53  5768.7 2092.81  5806.5 2096.27
#Mann= 9 ,-1 , 0
  2000.3    .045       0    3252    .035       0  3545.7    .045       0
  4132.9    .035       0  4230.8    .045       0  5002.6    .045       0
  5018.1    .045       0  5279.8    .035       0  5714.9    .045       0
Bank Sta=5002.6,5018.1
XS Rating Curve= 0 ,0
Exp/Cntr=0.3,0.1

Type RM Length L Ch R = 1 ,8284    ,1351,1351,1351
BEGIN DESCRIPTION:
UCFB HW Trib 10 16.0
END DESCRIPTION:
XS GIS Cut Line= 4
        1316380.      6958713.02        1316705.        6955488.
      1316717.28      6955287.52      1316204.99      6954687.99
#Sta/Elev= 30
  1758.6 2099.12  2467.2 2089.84    2955 2095.61  3291.3 2091.23  3331.6 2093.69
  3462.2 2090.65  3502.4  2087.6  3633.1 2087.15  3663.2 2084.52  3874.3  2081.1
  3904.4 2082.55  3944.6 2079.86  4226.1 2077.96  4251.6 2080.13  4286.4 2077.76
  4567.8 2074.81  5001.7 2074.59  5002.2 2074.09  5018.3 2074.59  5073.7 2075.36
  5120.2 2078.41  5190.3 2076.55  5230.2 2079.65  5293.9 2077.69  5315.9 2082.62
  5471.8 2091.44  5687.9 2091.91  5791.2 2096.35  5818.7 2095.06  5989.4 2099.01
#Mann= 5 ,-1 , 0
  1758.6    .045       0  5001.7    .045       0  5018.3    .045       0
  5073.7    .035       0  5687.9    .045       0
Bank Sta=5001.7,5018.3
XS Rating Curve= 0 ,0
Exp/Cntr=0.3,0.1

Type RM Length L Ch R = 1 ,6933    ,466,466,466
BEGIN DESCRIPTION:
UCFB HW Trib 10 15.0
END DESCRIPTION:
XS GIS Cut Line= 3
      1317518.01      6958322.11        1317555.        6955938.
        1317480.      6955312.98
#Sta/Elev= 30
  2610.8 2096.06  2644.9  2093.6  2744.9  2092.6  2764.9 2088.81  2774.9 2088.49
  2804.9 2089.72  2844.9  2086.8  2884.9 2085.98    2915 2087.22    2945  2084.5
    3095 2081.39    3125 2082.47    3155 2080.19    3355 2077.19  3386.8 2078.58
    3415 2076.27  3985.1 2071.99  4845.2 2073.21  4925.2 2072.57  4996.9 2068.04
  4997.4 2067.54  5013.6 2068.04  5085.8 2072.28  5308.7 2069.82  5377.9 2070.42
  5398.1 2068.32  5441.9 2068.89  5488.7 2069.07  5589.4 2074.83  5624.7 2073.62
#Mann= 5 ,-1 , 0
  2610.8    .045       0  4996.9    .045       0  5013.6    .045       0
  5308.7     .07       0  5441.9    .035       0
Bank Sta=4996.9,5013.6
XS Rating Curve= 0 ,0
Exp/Cntr=0.3,0.1

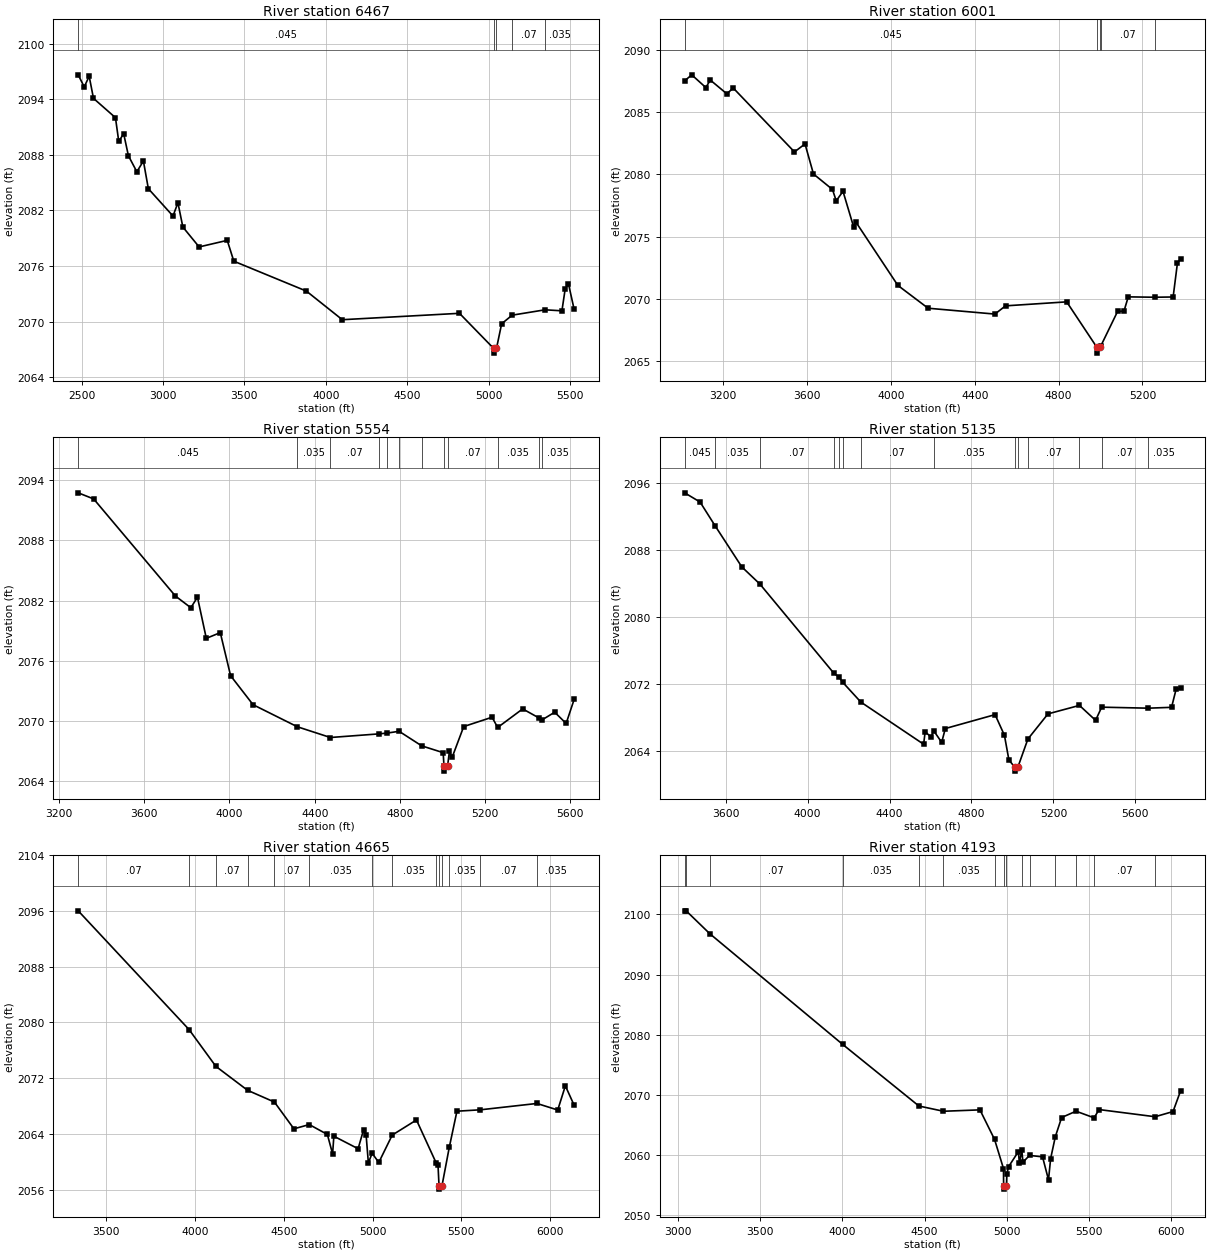
Type RM Length L Ch R = 1 ,6467    ,466,466,466
BEGIN DESCRIPTION:
UCFB HW Trib 10 14.0
END DESCRIPTION:
XS GIS Cut Line= 3
       1317656.9      6958384.65        1318005.        6955888.
        1318030.        6955363.
#Sta/Elev= 30
  2479.2 2096.65  2516.2 2095.34  2546.5  2096.5  2572.9 2094.11    2708 2092.02
  2728.2 2089.46  2758.5 2090.29  2787.5 2087.91  2839.3 2086.18  2879.7 2087.34
    2910 2084.35  3061.4  2081.4  3091.7 2082.83    3122 2080.21  3221.9 2078.06
  3394.6 2078.77    3435 2076.52  3880.9 2073.29  4101.4  2070.2  4821.1 2070.89
  5031.6 2067.09  5032.1 2066.59  5048.4 2067.09  5080.1 2069.76  5144.9 2070.69
  5347.1 2071.27  5450.5 2071.16  5470.5 2073.52  5490.6 2074.08  5525.6 2071.31
#Mann= 5 ,-1 , 0
  2479.2    .045       0  5031.6    .045       0  5048.4    .045       0
  5144.9     .07       0  5347.1    .035       0
Bank Sta=5031.6,5048.4
XS Rating Curve= 0 ,0
Exp/Cntr=0.3,0.1

Type RM Length L Ch R = 1 ,6001    ,447,447,447
BEGIN DESCRIPTION:
UCFB HW Trib 10 13.0
END DESCRIPTION:
XS GIS Cut Line= 3
      1318226.34      6957808.26        1318455.        6955838.
        1318530.      6955463.01
#Sta/Elev= 30
  3016.1  2087.5  3049.7 2087.98    3117 2086.96  3138.4 2087.56    3217 2086.46
  3247.9 2086.92  3539.8  2081.8  3590.2 2082.44  3630.5 2080.03  3721.1 2078.79
    3739 2077.88  3771.4 2078.64  3821.7 2075.81  3832.7 2076.18  4033.1  2071.1
  4177.3 2069.27  4496.2  2068.8  4546.6 2069.46  4838.5 2069.78  4981.1 2066.17
  4981.6 2065.67  4997.9 2066.17  5001.5 2066.25  5081.2 2069.01  5111.8 2069.04
  5132.2 2070.18  5257.8 2070.15  5346.3 2070.17  5366.7 2072.88    5382 2073.24
#Mann= 5 ,-1 , 0
  3016.1    .045       0  4981.1    .045       0  4997.9    .045       0
  5001.5     .07       0  5257.8    .035       0
Bank Sta=4981.1,4997.9
XS Rating Curve= 0 ,0
Exp/Cntr=0.3,0.1

Type RM Length L Ch R = 1 ,5554    ,419,419,419
BEGIN DESCRIPTION:
UCFB HW Trib 10 12.0
END DESCRIPTION:
XS GIS Cut Line= 3
        1318355.      6957737.99        1318805.        6956088.
        1319030.      6955513.01
#Sta/Elev= 30
    3290 2092.75  3362.6 2092.14  3746.1 2082.47  3818.6  2081.3  3849.7 2082.35
  3891.2 2078.25  3956.8 2078.82  4005.2 2074.53  4110.6 2071.64  4318.5 2069.44
  4473.6 2068.37  4700.6 2068.73  4739.7 2068.81    4796 2068.99    4902 2067.54
  5002.9 2066.86  5006.8 2065.52  5007.3 2065.02  5023.6 2065.52  5032.5 2067.03
    5045 2066.39  5099.3 2069.46  5232.3 2070.39  5258.8 2069.37  5376.1 2071.22
  5453.4 2070.31  5466.6 2070.12  5526.4 2070.89  5580.1 2069.77  5617.7 2072.17
#Mann= 12 ,-1 , 0
    3290    .045       0  4318.5    .035       0  4473.6     .07       0
  4700.6    .045       0  4739.7     .07       0    4796    .035       0
    4902     .07       0  5006.8     .07       0  5023.6     .07       0
  5258.8    .035       0  5453.4     .07       0  5466.6    .035       0
Bank Sta=5006.8,5023.6
XS Rating Curve= 0 ,0
Exp/Cntr=0.3,0.1

Type RM Length L Ch R = 1 ,5135    ,470,470,470
BEGIN DESCRIPTION:
UCFB HW Trib 10 11.0
END DESCRIPTION:
XS GIS Cut Line= 3
      1318499.79      6957752.67        1319155.        6956288.
      1319530.01      6955562.99
#Sta/Elev= 30
    3400 2094.85  3475.2 2093.75  3548.9  2090.9    3679 2086.01    3767 2083.97
  4128.1 2073.33  4153.9 2072.86  4171.7 2072.24  4259.8 2069.89  4566.3 2064.86
  4573.9 2066.35  4602.6 2065.71  4615.5 2066.47  4654.5 2065.08  4672.2 2066.73
  4915.1 2068.39  4960.7 2065.93  4982.6 2062.99    5010 2062.15  5010.5 2061.65
  5026.8 2062.15  5075.3 2065.48  5173.4 2068.48  5326.9 2069.49  5405.7 2067.71
  5435.5 2069.28  5662.7 2069.16  5776.5 2069.26  5798.6  2071.4  5820.8 2071.53
#Mann= 14 ,-1 , 0
    3400    .045       0  3548.9    .035       0    3767     .07       0
  4128.1    .035       0  4153.9     .07       0  4171.7    .035       0
  4259.8     .07       0  4615.5    .035       0    5010    .035       0
  5026.8    .035       0  5075.3     .07       0  5326.9    .035       0
  5435.5     .07       0  5662.7    .035       0
Bank Sta=5010,5026.8
XS Rating Curve= 0 ,0
Exp/Cntr=0.3,0.1

Type RM Length L Ch R = 1 ,4665    ,472,472,472
BEGIN DESCRIPTION:
UCFB HW Trib 10 10.0
END DESCRIPTION:
XS GIS Cut Line= 3
      1318673.41      6957891.54        1319555.        6956488.
      1320280.02      6955612.98
#Sta/Elev= 30
  3342.1 2096.02  3966.5 2078.97  4117.5 2073.69  4296.2 2070.25  4447.5 2068.56
  4557.2 2064.72  4643.8 2065.33  4745.7 2063.91  4775.2 2061.11  4782.2 2063.66
  4918.9 2061.86  4949.5 2064.57  4964.1 2063.78  4976.6 2059.83  4997.9 2061.21
  5035.4 2059.89    5111 2063.82  5247.6 2065.99  5359.5 2059.77  5368.8 2059.57
  5374.7 2056.56  5375.2 2056.06  5391.5 2056.56  5432.4 2062.06  5475.6 2067.25
    5608 2067.45  5926.4 2068.36  6043.4 2067.42  6086.4 2070.89  6135.9  2068.1
#Mann= 14 ,-1 , 0
  3342.1     .07       0  3966.5    .035       0  4117.5     .07       0
  4296.2    .035       0  4447.5     .07       0  4643.8    .035       0
  4997.9     .16       0    5111    .035       0  5359.5     .07       0
  5374.7     .07       0  5391.5     .07       0  5432.4    .035       0
    5608     .07       0  5926.4    .035       0
Bank Sta=5374.7,5391.5
XS Rating Curve= 0 ,0
Exp/Cntr=0.3,0.1

Type RM Length L Ch R = 1 ,4193    ,478,478,478
BEGIN DESCRIPTION:
UCFB HW Trib 10 9.0
END DESCRIPTION:
XS GIS Cut Line= 3
      1318929.98      6958263.04        1319955.        6956588.
      1320462.52      6955662.96
#Sta/Elev= 30
  3039.9 2100.55    3049 2100.58  3192.8 2096.78  4001.7  2078.4  4465.8 2068.17
  4615.2  2067.3  4837.3 2067.53  4926.1 2062.63  4980.5 2057.79  4981.4 2054.87
  4981.9 2054.37  4998.8 2054.87  5000.7 2056.89  5011.7  2058.1  5071.4 2060.61
  5077.1 2058.71  5092.2 2060.79  5098.9 2058.84  5139.1 2059.97  5218.3 2059.73
  5254.6 2055.91  5267.6 2059.45  5296.1 2063.07  5334.5 2066.26  5422.1 2067.31
    5532 2066.21  5562.6 2067.58  5903.4 2066.39  6012.6 2067.25  6058.8  2070.7
#Mann= 15 ,-1 , 0
  3039.9     .07       0    3049    .035       0  3192.8     .07       0
  4001.7    .035       0  4465.8     .07       0  4615.2    .035       0
  4926.1     .16       0  4981.4     .07       0  4998.8     .16       0
  5092.2     .07       0  5139.1     .16       0  5296.1     .07       0
  5422.1    .035       0    5532     .07       0  5903.4    .035       0
Bank Sta=4981.4,4998.8
XS Rating Curve= 0 ,0
Exp/Cntr=0.3,0.1

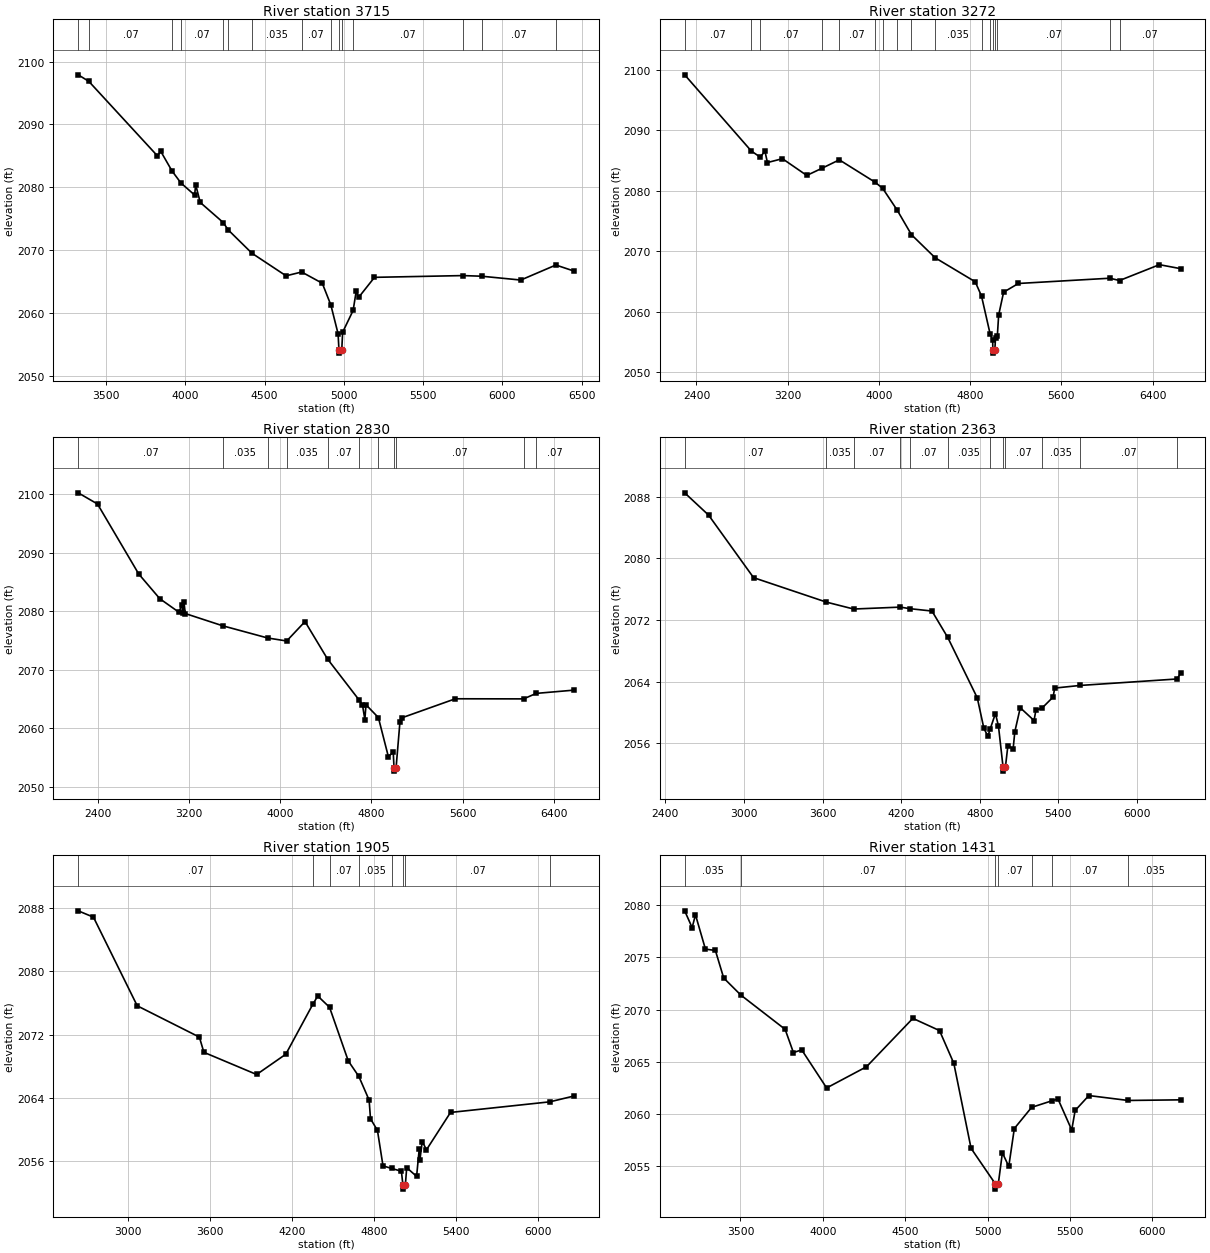
Type RM Length L Ch R = 1 ,3715    ,443,443,443
BEGIN DESCRIPTION:
UCFB HW Trib 10 8.0
END DESCRIPTION:
XS GIS Cut Line= 3
      1319129.98      6958263.03        1320155.        6956938.
      1321009.54        6955763.
#Sta/Elev= 30
  3324.9 2097.89  3391.4 2096.86  3824.3 2085.01  3845.6 2085.72  3916.4 2082.61
  3972.6  2080.7  4059.3 2078.77  4065.6 2080.43  4094.6  2077.6  4239.8  2074.4
  4270.3 2073.25  4420.8 2069.52  4636.1 2065.93  4734.3 2066.54  4864.3 2064.75
  4918.2 2061.31  4963.9 2056.73  4969.6 2054.14  4970.1 2053.64  4987.1 2054.14
  4992.9 2056.97  5058.9 2060.43  5078.6 2063.53  5093.2 2062.49  5193.7 2065.69
  5750.3 2065.97  5868.9 2065.87  6116.4 2065.26  6337.7 2067.65    6453 2066.68
#Mann= 15 ,-1 , 0
  3324.9    .035       0  3391.4     .07       0  3916.4    .035       0
  3972.6     .07       0  4239.8    .035       0  4270.3     .07       0
  4420.8    .035       0  4734.3     .07       0  4918.2     .16       0
  4969.6     .07       0  4987.1     .16       0  5058.9     .07       0
  5750.3    .035       0  5868.9     .07       0  6337.7    .035       0
Bank Sta=4969.6,4987.1
XS Rating Curve= 0 ,0
Exp/Cntr=0.3,0.1

Type RM Length L Ch R = 1 ,3272    ,442,442,442
BEGIN DESCRIPTION:
UCFB HW Trib 10 7.0
END DESCRIPTION:
XS GIS Cut Line= 3
       1319124.8      6959618.98        1320405.        6957238.
        1321380.        6955913.
#Sta/Elev= 30
  2296.6 2099.15  2880.3 2086.56  2958.9 2085.53  3000.2 2086.52  3022.1 2084.64
  3153.6 2085.28    3367 2082.51  3501.9 2083.71  3652.4 2085.09  3964.2 2081.41
  4032.1 2080.39  4158.9  2076.8  4285.3  2072.7  4492.8 2068.89  4844.1 2064.92
  4899.2 2062.56  4975.3 2056.25  4997.1 2055.25  4998.5 2053.62    4999 2053.12
    5016 2053.62  5021.9 2055.59  5037.8 2055.92  5049.6 2059.42  5092.9  2063.2
  5222.5 2064.64  6024.3 2065.51  6109.5 2065.13  6459.1 2067.75    6645 2067.09
#Mann= 17 ,-1 , 0
  2296.6     .07       0  2880.3    .035       0  2958.9     .07       0
  3501.9    .035       0  3652.4     .07       0  3964.2    .035       0
  4032.1     .07       0  4158.9    .035       0  4285.3     .07       0
  4492.8    .035       0  4899.2     .07       0  4975.3     .16       0
  4998.5     .07       0    5016     .16       0  5037.8     .07       0
  6024.3    .035       0  6109.5     .07       0
Bank Sta=4998.5,5016
XS Rating Curve= 0 ,0
Exp/Cntr=0.3,0.1

Type RM Length L Ch R = 1 ,2830    ,467,467,467
BEGIN DESCRIPTION:
UCFB HW Trib 10 6.0
END DESCRIPTION:
XS GIS Cut Line= 3
      1319329.98      6959813.03        1320755.        6957438.
        1321530.      6956063.01
#Sta/Elev= 30
  2230.2 2100.25  2399.3 2098.34  2760.9 2086.37  2945.5 2082.15  3110.7 2079.87
  3141.8 2081.06  3147.6 2079.73  3157.4 2081.53    3169 2079.61  3498.4 2077.51
  3891.7 2075.43    4058 2074.92  4218.6 2078.24  4415.9 2071.84  4695.2 2064.77
    4722 2064.04  4743.4 2061.47  4753.1 2064.02  4861.8 2061.83  4949.4 2055.15
  4992.2 2055.92  4999.1 2053.17  4999.6 2052.67  5016.7 2053.17  5051.2 2061.13
  5067.1 2061.78  5536.7 2065.04    6135 2065.02  6245.7 2065.96  6578.3 2066.52
#Mann= 11 ,-1 , 0
  2230.2     .07       0  3498.4    .035       0  3891.7     .07       0
    4058    .035       0  4415.9     .07       0  4695.2    .035       0
  4861.8     .07       0  4999.1     .07       0  5016.7     .07       0
    6135    .035       0  6245.7     .07       0
Bank Sta=4999.1,5016.7
XS Rating Curve= 0 ,0
Exp/Cntr=0.3,0.1

Type RM Length L Ch R = 1 ,2363    ,458,458,458
BEGIN DESCRIPTION:
UCFB HW Trib 10 5.0
END DESCRIPTION:
XS GIS Cut Line= 3
      1319779.99      6959913.02        1321005.        6957788.
        1321530.      6956562.99
#Sta/Elev= 30
  2547.2  2088.5  2729.7 2085.61    3073  2077.5  3628.2 2074.33    3837 2073.43
    4194 2073.68  4264.7 2073.48  4434.8 2073.17  4555.3 2069.74  4780.7 2061.91
  4831.3 2057.94  4861.5 2056.95  4878.1 2057.82  4919.2 2059.88  4942.3 2058.27
  4977.6 2052.91  4978.1 2052.41  4995.2 2052.91  5014.5 2055.73  5054.4 2055.29
  5067.1 2057.51  5108.8 2060.63    5214 2058.97  5228.5 2060.36  5272.9 2060.55
  5359.1 2062.01  5371.8 2063.18  5564.6 2063.52  6305.4 2064.36  6332.8 2065.09
#Mann= 12 ,-1 , 0
  2547.2     .07       0  3628.2    .035       0    3837     .07       0
    4194    .035       0  4264.7     .07       0  4555.3    .035       0
  4878.1     .07       0  4977.6     .07       0  4995.2     .07       0
  5272.9    .035       0  5564.6     .07       0  6305.4    .035       0
Bank Sta=4977.6,4995.2
XS Rating Curve= 0 ,0
Exp/Cntr=0.3,0.1

Type RM Length L Ch R = 1 ,1905    ,474,474,474
BEGIN DESCRIPTION:
UCFB HW Trib 10 4.0
END DESCRIPTION:
XS GIS Cut Line= 3
      1320929.99      6960313.04        1321355.        6957988.
      1321679.99      6956763.04
#Sta/Elev= 30
    2636 2087.63  2747.6 2086.83  3068.1 2075.64  3523.1 2071.69    3556 2069.77
  3942.3 2066.97  4155.8 2069.53    4353 2075.81  4389.6 2076.88  4475.9 2075.46
  4613.3 2068.68  4690.7 2066.72  4765.8 2063.74  4775.9 2061.38  4826.7 2059.92
  4867.4 2055.44  4930.6 2055.11  5002.1 2054.76  5013.4    2053  5013.9  2052.5
    5031    2053  5040.9 2055.21  5113.4 2054.11  5132.5 2057.52  5137.6  2056.2
  5154.8 2058.51  5185.8 2057.47  5361.7 2062.18    6089 2063.52  6266.9 2064.26
#Mann= 8 ,-1 , 0
    2636     .07       0    4353    .035       0  4475.9     .07       0
  4690.7    .035       0  4930.6     .07       0  5013.4     .07       0
    5031     .07       0    6089    .035       0
Bank Sta=5013.4,5031
XS Rating Curve= 0 ,0
Exp/Cntr=0.3,0.1

Type RM Length L Ch R = 1 ,1431    ,0,0,0
BEGIN DESCRIPTION:
UCFB HW Trib 10 3.0
END DESCRIPTION:
XS GIS Cut Line= 3
        1321530.        6960013.        1321755.        6958188.
        1322080.      6957063.02
#Sta/Elev= 30
  3161.6 2079.46  3206.9 2077.85  3227.1 2079.08  3287.5 2075.79    3348 2075.66
  3398.4 2073.02  3502.7 2071.38  3771.2  2068.1  3821.6 2065.87  3871.9 2066.13
  4023.1 2062.48  4264.9 2064.51  4546.4 2069.15  4708.2 2067.98    4795 2064.84
  4899.7 2056.69  5047.2 2053.28  5047.7 2052.78  5064.9 2053.28  5089.7 2056.26
  5128.5 2054.96  5162.2 2058.59  5267.2 2060.62  5388.7 2061.24  5427.2 2061.42
  5510.5 2058.45  5531.3 2060.32  5614.5 2061.75  5852.9 2061.28  6171.4 2061.34
#Mann= 7 ,-1 , 0
  3161.6    .035       0  3502.7     .07       0  5047.2     .07       0
  5064.9     .07       0  5267.2    .035       0  5388.7     .07       0
  5852.9    .035       0
Bank Sta=5047.2,5064.9
XS Rating Curve= 0 ,0
Exp/Cntr=0.3,0.1

Chan Stop Cuts=-1
Use User Specified Reach Order=0
Composite Channel Slope=5