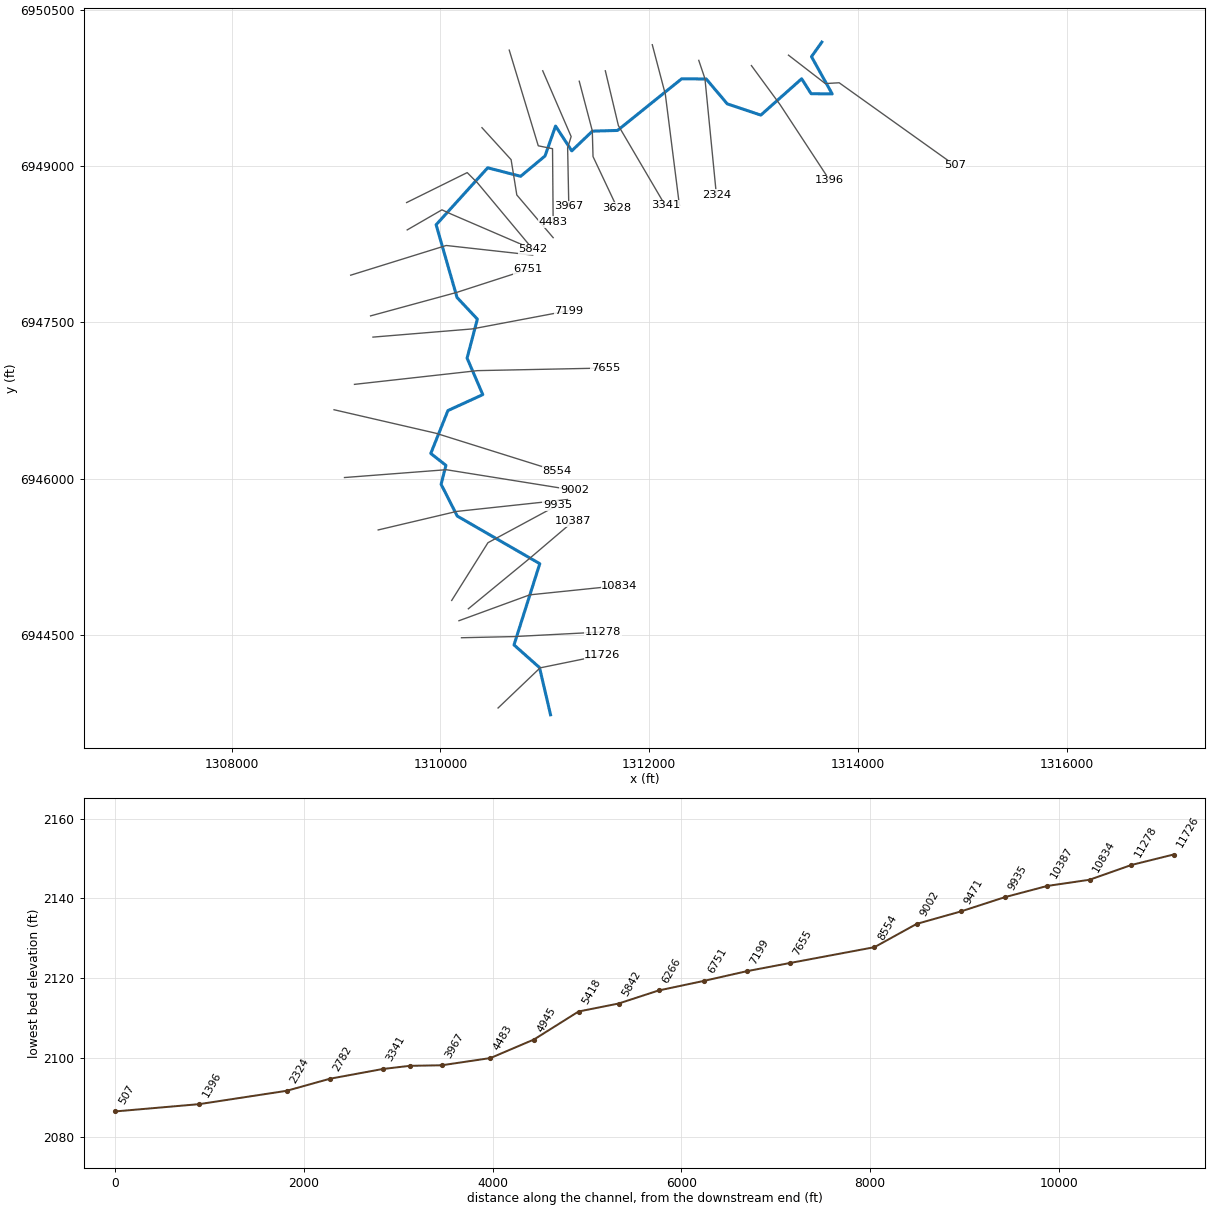
--- UCFB HW Trib 12.prj (project) ---

Proj Title=UCFB HW Trib 12 Base Level Engineering
Current Plan=p01
Default Exp/Contr=0.3,0.1
English Units
Geom File=g01
Flow File=f01
Plan File=p01
Y Axis Title=Elevation
X Axis Title(PF)=Main Channel Distance
X Axis Title(XS)=Station
BEGIN DESCRIPTION:
UCFB HW Trib 12
END DESCRIPTION:
DSS Export Rating Curves= 0
DSS Export Rating Curve Sorted= 0
DSS Export Volume Flow Curves= 0
DXF OffsetX= 0
DXF OffsetY= 0
DXF ScaleX= 1
DXF ScaleY= 10

--- UCFB HW Trib 12.p01 (plan) ---

Plan Title=Multiple Run
Short Identifier=Multiple
Geom File=g01
Flow File=f01
Subcritical Flow
K Sum by GR= 0
Std Step Tol= 0.01
Critical Tol= 0.01
Num of Std Step Trials= 20
Max Error Tol= 0.3
Flow Tol Ratio= 0.001
Split Flow NTrial= 30
Split Flow Tol= 0.02
Split Flow Ratio= 0.02
Log Output Level= 0
Friction Slope Method= 1
Unsteady Friction Slope Method= 2
Unsteady Bridges Friction Slope Method= 1
Parabolic Critical Depth
Global Vel Dist=  1 , 1 , 1
Global Log Level= 0
CheckData=True
Encroach Param= -1, 0, 0, 0
BEGIN DESCRIPTION:
Multiple Run
END DESCRIPTION:

--- UCFB HW Trib 12.f01 (steady flow) ---

Flow Title=Multiple
Number of Profiles=7
Profile Names=10-year,25-year,50-year,1pct_min,100-year,1pct_plu,500-year
River Rch & RM= UCFB HW Trib 12,Reach-1,11726
     374     540     683     429     856    1708    1364
River Rch & RM= UCFB HW Trib 12,Reach-1,3628
     515     757     967     614    1224    2443    1990
River Rch & RM= UCFB HW Trib 12,Reach-1,1396
     530     780     996     632    1261    2517    2050
Boundary for River Rch & Prof#=UCFB HW Trib 12,Reach-1,1
Up Type=0
Dn Type=3
Dn Slope=0.005
Boundary for River Rch & Prof#=UCFB HW Trib 12,Reach-1,2
Up Type=0
Dn Type=3
Dn Slope=0.005
Boundary for River Rch & Prof#=UCFB HW Trib 12,Reach-1,3
Up Type=0
Dn Type=3
Dn Slope=0.005
Boundary for River Rch & Prof#=UCFB HW Trib 12,Reach-1,4
Up Type=0
Dn Type=3
Dn Slope=0.005
Boundary for River Rch & Prof#=UCFB HW Trib 12,Reach-1,5
Up Type=0
Dn Type=3
Dn Slope=0.005
Boundary for River Rch & Prof#=UCFB HW Trib 12,Reach-1,6
Up Type=0
Dn Type=3
Dn Slope=0.005
Boundary for River Rch & Prof#=UCFB HW Trib 12,Reach-1,7
Up Type=0
Dn Type=3
Dn Slope=0.005

--- UCFB HW Trib 12.g01 (geometry) ---

Geom Title=Existing Conditions
Program Version=4.10

River Reach=UCFB HW Trib 12 ,Reach-1
Reach XY= 30
        1311055.        6943738.      1310949.28      6944190.58
      1310704.79      6944408.05      1310951.63      6945186.72
      1310160.58      6945643.58      1310005.94      6945948.48
      1310052.37      6946129.52      1309907.04      6946243.85
      1310071.45      6946655.14      1310405.44      6946808.03
      1310254.96      6947157.98      1310353.42      6947531.95
      1310158.54      6947739.47      1309958.37      6948436.72
      1310452.46      6948983.04      1310768.32      6948901.37
      1311001.92      6949096.31      1311102.85       6949383.2
      1311258.15      6949145.52      1311456.26      6949334.52
       1311696.7      6949341.07      1312310.84      6949835.95
      1312546.62      6949834.62      1312748.81      6949595.81
      1313070.22      6949488.24      1313461.52      6949836.61
      1313552.27      6949693.35      1313754.03      6949691.53
      1313555.69       6950048.7        1313655.        6950188.

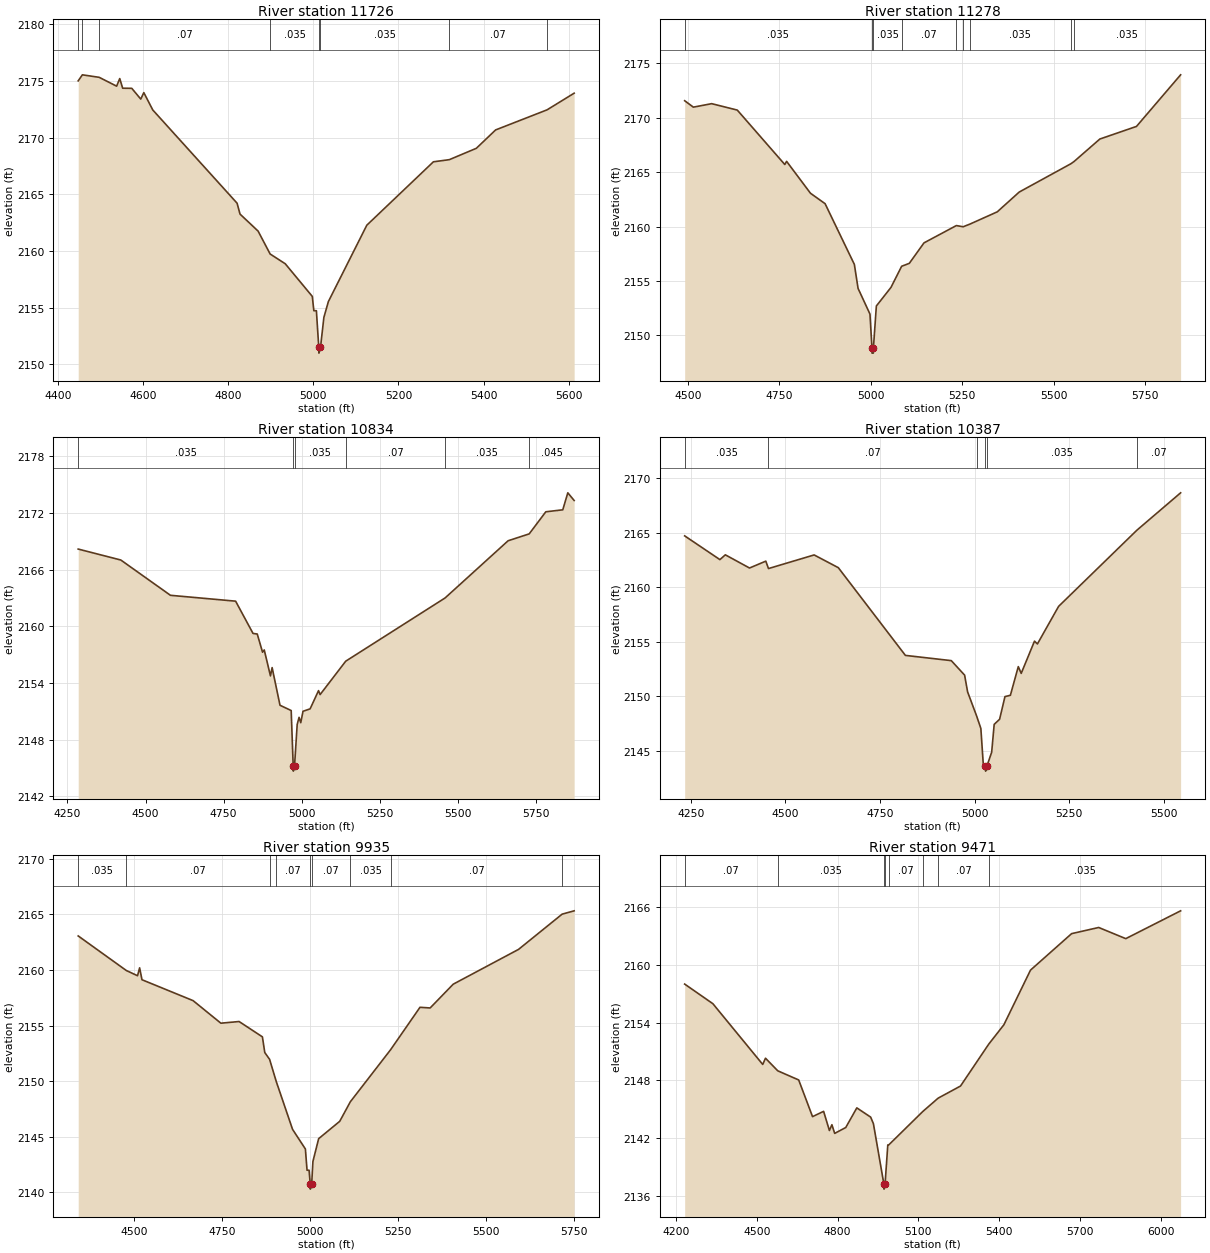
Type RM Length L Ch R = 1 ,11726   ,448,448,448
BEGIN DESCRIPTION:
UCFB HW Trib 12 23.0
END DESCRIPTION:
XS GIS Cut Line= 3
      1310551.97      6943803.19        1310955.        6944188.
      1311551.01      6944309.96
#Sta/Elev= 30
  4447.3 2175.01  4457.1 2175.54  4496.6 2175.32  4537.6 2174.54  4544.9 2175.21
  4551.8 2174.36  4573.2 2174.35  4594.3  2173.4  4601.5 2173.97  4622.6 2172.44
  4820.7 2164.22  4827.6 2163.26  4870.1 2161.76  4898.4 2159.74  4933.9 2158.88
  4997.5    2156  5001.1 2154.74  5007.1 2154.74  5012.7  2151.5    5013    2151
  5016.7  2151.5  5024.7 2154.15  5035.2 2155.54  5125.6 2162.28  5282.1 2167.87
  5319.6 2168.06    5383 2169.06  5428.3 2170.68  5549.1 2172.45  5612.9 2173.92
#Mann= 8 ,-1 , 0
  4447.3     .07       0  4457.1    .035       0  4496.6     .07       0
  4898.4    .035       0  5012.7    .035       0  5016.7    .035       0
  5319.6     .07       0  5549.1    .035       0
Bank Sta=5012.7,5016.7
XS Rating Curve= 0 ,0
Exp/Cntr=0.3,0.1

Type RM Length L Ch R = 1 ,11278   ,444,444,444
BEGIN DESCRIPTION:
UCFB HW Trib 12 22.0
END DESCRIPTION:
XS GIS Cut Line= 3
      1310201.27      6944476.83        1310705.        6944488.
      1311555.48      6944532.38
#Sta/Elev= 30
  4491.5 2171.56  4515.2 2170.97  4565.3 2171.29  4635.3  2170.7  4765.1  2165.7
  4770.1 2165.99  4835.3 2163.06  4875.3  2162.1  4955.3 2156.52  4965.4 2154.32
  4997.9 2151.96  5003.4 2148.87  5003.6 2148.37  5007.1 2148.37  5007.4 2148.87
  5015.4  2152.7  5055.4 2154.41  5084.5 2156.35  5105.5 2156.62  5145.6  2158.5
  5234.1 2160.09  5252.6 2159.98  5270.8 2160.22  5345.8 2161.35  5405.9 2163.17
  5547.1 2165.77  5555.9 2165.98  5626.2 2168.04  5726.4  2169.2    5847 2173.94
#Mann= 9 ,-1 , 0
  4491.5    .035       0  5003.4    .035       0  5007.4    .035       0
  5084.5     .07       0  5234.1    .035       0  5252.6     .07       0
  5270.8    .035       0  5547.1     .07       0  5555.9    .035       0
Bank Sta=5003.4,5007.4
XS Rating Curve= 0 ,0
Exp/Cntr=0.3,0.1

Type RM Length L Ch R = 1 ,10834   ,447,447,447
BEGIN DESCRIPTION:
UCFB HW Trib 12 21.0
END DESCRIPTION:
XS GIS Cut Line= 3
      1310177.02      6944640.03        1310855.        6944888.
      1311715.23      6944976.83
#Sta/Elev= 30
  4284.6 2168.19  4420.9 2167.03  4579.8 2163.29  4788.2 2162.67  4843.9 2159.25
  4857.4 2159.19  4874.4 2157.26  4879.8  2157.5  4899.7 2154.75    4905 2155.63
  4930.2 2151.64    4966 2151.08  4972.5 2145.16  4972.8 2144.66  4976.6 2145.16
  4985.2 2149.61  4991.2 2150.36  4996.6 2149.79  5003.8    2151  5026.6 2151.26
  5053.5 2153.19  5058.5 2152.77  5140.5 2156.31  5458.4 2163.01    5660 2169.07
  5727.5  2169.8  5780.6 2172.14  5834.9 2172.35    5851 2174.15  5871.3 2173.34
#Mann= 6 ,-1 , 0
  4284.6    .035       0  4972.5    .035       0  4976.6    .035       0
  5140.5     .07       0  5458.4    .035       0  5727.5    .045       0
#XS Ineff= 2 , 0
       0    4966 2151.08               0
Permanent Ineff=
       F       F
Bank Sta=4972.5,4976.6
XS Rating Curve= 0 ,0
Exp/Cntr=0.3,0.1

Type RM Length L Ch R = 1 ,10387   ,452,452,452
BEGIN DESCRIPTION:
UCFB HW Trib 12 20.0
END DESCRIPTION:
XS GIS Cut Line= 3
      1310267.24      6944754.58        1310855.        6945238.
      1311273.09      6945593.92
#Sta/Elev= 30
  4233.9  2164.7    4327 2162.52  4341.3 2162.96  4405.2 2161.75  4448.2 2162.38
  4455.3  2161.7  4575.9 2162.95  4639.8 2161.78    4817 2153.73  4938.2 2153.25
  4973.4 2151.92  4981.3 2150.38    5005 2148.18  5016.3 2147.03  5022.9 2143.64
  5028.5 2143.61  5028.8 2143.11  5032.7 2143.61  5044.9 2144.85  5051.5  2147.4
  5065.8 2147.87    5080 2149.95  5094.3 2150.07  5115.2  2152.7  5122.9 2152.08
    5158 2155.04  5165.7 2154.78  5221.7 2158.23  5428.5 2165.22    5544 2168.65
#Mann= 6 ,-1 , 0
  4233.9    .035       0  4455.3     .07       0    5005    .035       0
  5028.5     .07       0  5032.7    .035       0  5428.5     .07       0
Bank Sta=5028.5,5032.7
XS Rating Curve= 0 ,0
Exp/Cntr=0.3,0.1

Type RM Length L Ch R = 1 ,9935    ,464,464,464
BEGIN DESCRIPTION:
UCFB HW Trib 12 19.0
END DESCRIPTION:
XS GIS Cut Line= 3
      1310107.54      6944834.46        1310455.        6945388.
      1311120.69      6945747.26
#Sta/Elev= 30
  4341.1 2163.06  4477.9 2159.95  4509.8 2159.48  4515.7 2160.19  4522.4 2159.12
  4667.7 2157.24  4746.7 2155.21  4798.5 2155.36  4864.8 2153.98  4871.5 2152.57
  4885.2 2151.96  4904.3 2149.95  4950.5 2145.66    4987 2143.89  4991.7 2141.98
  4997.5 2141.98  5000.7 2140.78    5001 2140.28  5004.9 2140.78  5008.4 2142.77
  5024.7 2144.82  5084.6 2146.38  5114.8 2148.14  5229.2 2152.82  5312.8 2156.64
  5341.7 2156.58  5407.3 2158.72    5593 2161.85  5716.9 2165.02  5751.1 2165.32
#Mann= 9 ,-1 , 0
  4341.1    .035       0  4477.9     .07       0  4885.2    .035       0
  4904.3     .07       0  5000.7     .07       0  5004.9     .07       0
  5114.8    .035       0  5229.2     .07       0  5716.9    .035       0
Bank Sta=5000.7,5004.9
XS Rating Curve= 0 ,0
Exp/Cntr=0.3,0.1

Type RM Length L Ch R = 1 ,9471    ,469,469,469
BEGIN DESCRIPTION:
UCFB HW Trib 12 18.0
END DESCRIPTION:
XS GIS Cut Line= 3
      1309402.99      6945510.54        1310155.        6945688.
      1311217.41       6945802.2
#Sta/Elev= 30
  4232.3 2158.01  4337.1 2155.97  4522.1 2149.66  4532.3 2150.31  4577.9    2149
  4655.6 2148.05    4707 2144.24  4748.1 2144.79  4769.6  2142.8  4778.9  2143.4
  4789.2  2142.5  4830.3 2143.11  4871.4 2145.15  4922.8 2144.19    4933 2143.51
    4972 2137.21  4972.3 2136.71  4976.2 2137.21  4986.4  2141.3  4989.8  2141.3
  5116.5 2144.78  5173.3 2146.16  5256.4 2147.42  5361.1 2151.77  5417.3 2153.78
  5516.2 2159.46  5668.8 2163.25  5769.3 2163.89  5869.9 2162.73  6073.5 2165.62
#Mann= 8 ,-1 , 0
  4232.3     .07       0  4577.9    .035       0    4972     .07       0
  4976.2    .035       0  4989.8     .07       0  5116.5    .035       0
  5173.3     .07       0  5361.1    .035       0
Bank Sta=4972,4976.2
XS Rating Curve= 0 ,0
Exp/Cntr=0.3,0.1

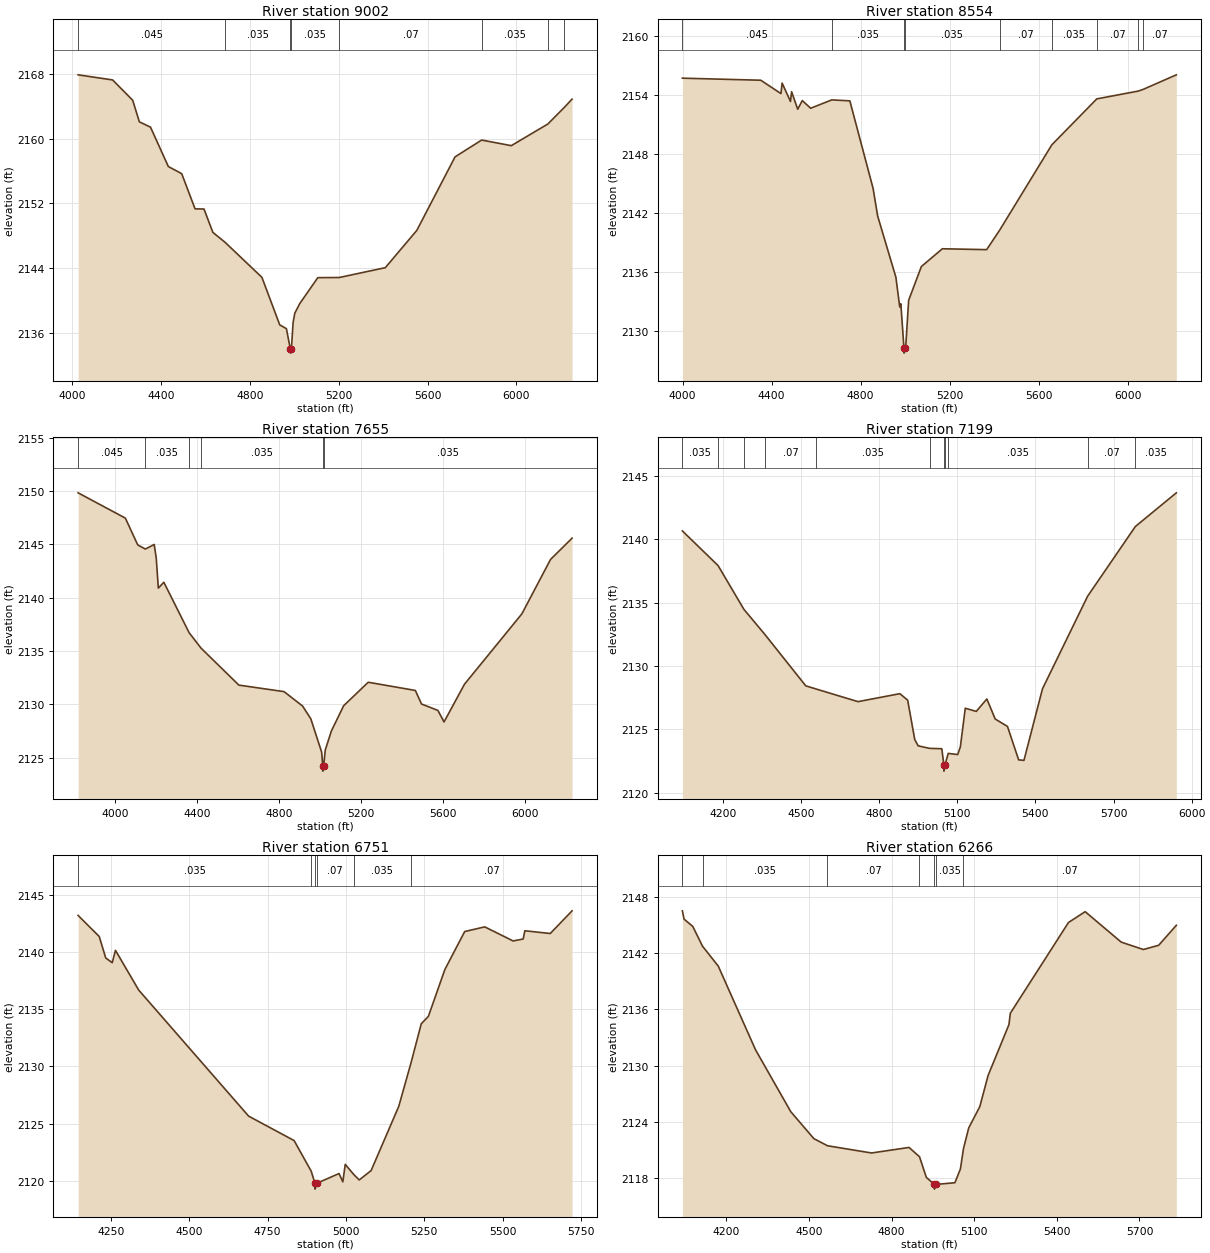
Type RM Length L Ch R = 1 ,9002    ,448,448,448
BEGIN DESCRIPTION:
UCFB HW Trib 12 17.0
END DESCRIPTION:
XS GIS Cut Line= 3
      1309080.02        6946013.        1310055.        6946088.
      1311285.12      6945890.75
#Sta/Elev= 30
  4026.6 2167.84    4182 2167.21  4272.3 2164.71  4302.4 2162.05  4352.5  2161.4
  4432.8 2156.55    4493 2155.67  4553.1 2151.34  4593.3 2151.32  4633.4 2148.44
  4687.9 2147.23    4854 2142.91  4934.3 2137.06  4964.3 2136.59  4982.2 2134.08
  4982.5 2133.58  4986.7 2134.08  4994.4 2137.33    5002 2138.49  5024.7 2139.69
  5105.7 2142.87  5202.5 2142.89  5409.6  2144.1  5551.4 2148.69  5723.5 2157.74
  5843.3 2159.81  5976.7 2159.12  6141.5 2161.79  6215.1 2163.82  6250.3 2164.85
#Mann= 8 ,-1 , 0
  4026.6    .045       0  4687.9    .035       0  4982.2    .035       0
  4986.7    .035       0  5202.5     .07       0  5843.3    .035       0
  6141.5     .07       0  6215.1    .035       0
Bank Sta=4982.2,4986.7
XS Rating Curve= 0 ,0
Exp/Cntr=0.3,0.1

Type RM Length L Ch R = 1 ,8554    ,899,899,899
BEGIN DESCRIPTION:
UCFB HW Trib 12 16.0
END DESCRIPTION:
XS GIS Cut Line= 3
      1308979.99        6946663.        1309955.        6946438.
      1311118.47      6946073.04
#Sta/Elev= 30
  3999.4 2155.71  4351.8  2155.5  4442.4 2154.14  4447.6 2155.21  4485.2 2153.34
  4490.3 2154.33  4517.7 2152.55  4538.2 2153.43  4575.8 2152.65  4670.9  2153.5
    4752  2153.4  4856.4  2144.5  4876.9 2141.69    4959 2135.45  4976.1 2132.43
  4981.2 2132.75  4995.2 2128.23  4995.5 2127.73  4999.7 2128.23  5002.7 2128.23
  5016.2  2133.1  5073.4 2136.54  5167.7 2138.35  5366.8 2138.26  5425.5 2140.25
  5659.9 2148.93  5861.8  2153.6    6049  2154.4  6071.5 2154.58  6219.4 2156.05
#Mann= 9 ,-1 , 0
  3999.4    .045       0  4670.9    .035       0  4995.2    .035       0
  4999.7    .035       0  5425.5     .07       0  5659.9    .035       0
  5861.8     .07       0    6049    .035       0  6071.5     .07       0
Bank Sta=4995.2,4999.7
XS Rating Curve= 0 ,0
Exp/Cntr=0.3,0.1

Type RM Length L Ch R = 1 ,7655    ,456,456,456
BEGIN DESCRIPTION:
UCFB HW Trib 12 15.0
END DESCRIPTION:
XS GIS Cut Line= 3
      1309175.74      6946906.37        1310355.        6947038.
      1311579.96        6947063.
#Sta/Elev= 30
  3817.5 2149.82  4048.2 2147.45  4108.6 2144.94  4145.8 2144.55  4189.1 2144.98
  4199.1 2143.68  4209.2 2140.89  4236.1 2141.44  4359.6 2136.71    4418 2135.26
  4602.5  2131.8    4823 2131.19  4913.5 2129.84  4953.8 2128.64  5006.6 2125.52
  5011.8 2124.24  5012.1 2123.74  5016.4 2124.24  5024.1 2125.71  5054.1  2127.5
  5114.1 2129.87  5234.1 2132.07  5464.2  2131.3  5494.2 2130.03  5574.2 2129.43
  5604.2 2128.35  5704.2 2131.89  5984.3 2138.48  6124.3 2143.58  6229.3 2145.57
#Mann= 6 ,-1 , 0
  3817.5    .045       0  4145.8    .035       0  4359.6     .07       0
    4418    .035       0  5011.8    .035       0  5016.4    .035       0
Bank Sta=5011.8,5016.4
XS Rating Curve= 0 ,0
Exp/Cntr=0.3,0.1

Type RM Length L Ch R = 1 ,7199    ,448,448,448
BEGIN DESCRIPTION:
UCFB HW Trib 12 14.0
END DESCRIPTION:
XS GIS Cut Line= 3
      1309352.89       6947359.5        1310305.        6947438.
      1311229.95      6947612.99
#Sta/Elev= 30
  4044.6 2140.67  4181.7 2137.93  4280.9 2134.47  4360.1 2132.52  4518.3 2128.43
  4557.9 2128.18    4719 2127.18  4879.5 2127.81  4909.6  2127.3  4936.9 2124.18
  4949.8 2123.69  4993.5 2123.49  5040.7 2123.46  5048.5 2122.19  5048.8 2121.69
  5053.1 2122.19  5065.3 2123.09  5101.7    2123  5111.9  2123.6  5130.8 2126.66
    5173 2126.41  5213.7 2127.39  5245.7 2125.81  5292.9 2125.22  5335.8 2122.58
  5356.1 2122.54  5427.4  2128.2  5600.6 2135.51    5784 2141.02  5941.3 2143.68
#Mann= 11 ,-1 , 0
  4044.6    .035       0  4181.7     .07       0  4280.9    .035       0
  4360.1     .07       0  4557.9    .035       0  4993.5     .07       0
  5048.5     .07       0  5053.1     .07       0  5065.3    .035       0
  5600.6     .07       0    5784    .035       0
Bank Sta=5048.5,5053.1
XS Rating Curve= 0 ,0
Exp/Cntr=0.3,0.1

Type RM Length L Ch R = 1 ,6751    ,485,485,485
BEGIN DESCRIPTION:
UCFB HW Trib 12 13.0
END DESCRIPTION:
XS GIS Cut Line= 3
        1309330.        6947563.        1310155.        6947788.
      1310841.21      6948010.14
#Sta/Elev= 30
  4145.2 2143.18  4212.6 2141.34  4233.3 2139.47    4254 2139.05  4264.4 2140.13
  4338.7 2136.66  4689.4 2125.66  4834.5 2123.53  4889.2 2120.85  4901.1 2119.79
  4901.5 2119.29    4906 2119.79  4977.9 2120.65    4990 2119.93  4997.7 2121.45
  5024.4 2120.58  5042.4 2120.09  5080.3 2120.91  5168.5 2126.51    5208 2130.35
  5240.3 2133.72  5263.1 2134.37  5315.7 2138.46  5378.9 2141.77  5442.9 2142.18
  5533.6 2140.95  5565.6 2141.12  5570.9 2141.84    5652  2141.6  5721.6 2143.58
#Mann= 6 ,-1 , 0
  4145.2    .035       0  4889.2     .07       0  4901.1     .07       0
    4906     .07       0  5024.4    .035       0    5208     .07       0
Bank Sta=4901.1,4906
XS Rating Curve= 0 ,0
Exp/Cntr=0.3,0.1

Type RM Length L Ch R = 1 ,6266    ,424,424,424
BEGIN DESCRIPTION:
UCFB HW Trib 12 12.0
END DESCRIPTION:
XS GIS Cut Line= 3
      1309139.34      6947953.26        1310055.        6948238.
      1310884.09      6948145.95
#Sta/Elev= 30
  4040.7  2146.5  4046.6 2145.62  4078.4 2144.84  4113.8 2142.73  4170.8 2140.62
  4306.2  2131.7  4434.1 2125.11  4517.9 2122.24  4567.3 2121.48  4727.3 2120.71
  4863.5  2121.3  4901.4 2120.31  4926.3 2118.11  4955.3 2117.36  4955.6 2116.86
  4960.2 2117.36  5029.8 2117.54  5049.9    2119  5060.9 2121.15  5080.1 2123.38
  5120.4 2125.65  5150.5 2128.97  5226.1 2134.38  5231.1 2135.59  5442.3 2145.26
  5502.9 2146.41  5633.5 2143.17    5714 2142.38  5769.6 2142.83  5833.8 2144.96
#Mann= 7 ,-1 , 0
  4040.7     .07       0  4113.8    .035       0  4567.3     .07       0
  4901.4    .035       0  4955.3    .035       0  4960.2    .035       0
  5060.9     .07       0
Bank Sta=4955.3,4960.2
XS Rating Curve= 0 ,0
Exp/Cntr=0.3,0.1

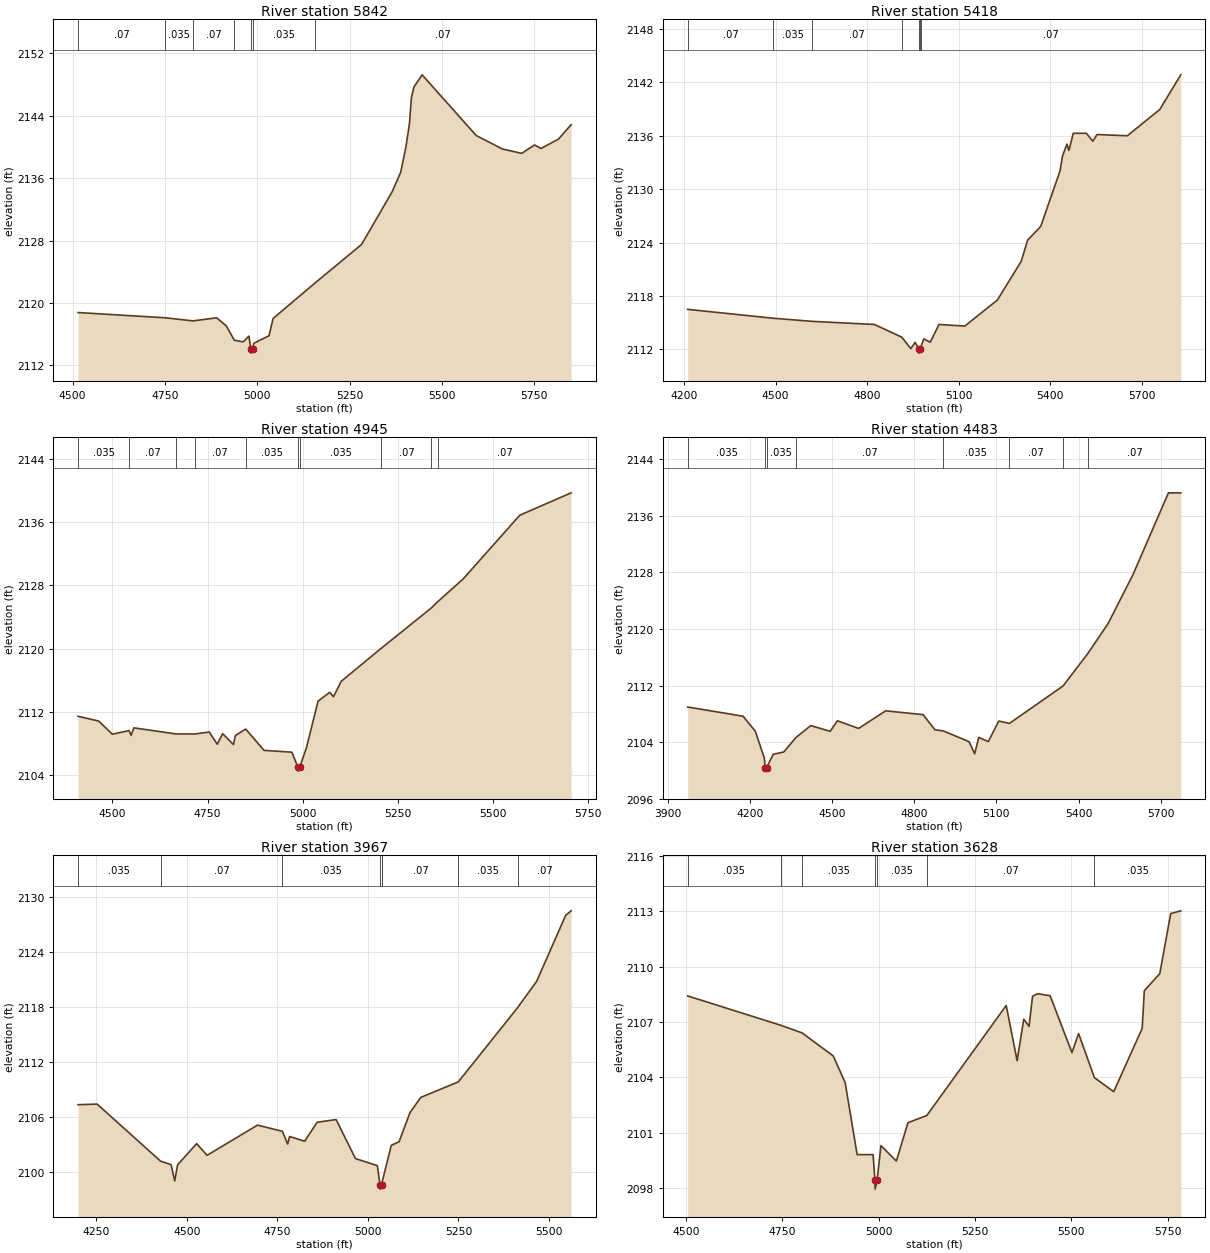
Type RM Length L Ch R = 1 ,5842    ,424,424,424
BEGIN DESCRIPTION:
UCFB HW Trib 12 11.0
END DESCRIPTION:
XS GIS Cut Line= 4
      1309681.13      6948387.51      1310013.79      6948579.81
        1310105.        6948538.      1310886.05      6948201.32
#Sta/Elev= 30
  4514.9 2118.78    4751 2118.11  4826.2 2117.71  4890.1 2118.11  4916.2 2117.07
    4938 2115.23  4962.2 2115.03  4977.5 2115.76  4982.8 2114.08  4983.1 2113.58
  4987.7 2114.08  4990.7 2114.84    5032 2115.81    5043 2118.02  5157.1 2122.59
  5282.6 2127.51    5365 2134.23  5388.5 2136.76  5402.4 2139.95  5412.1 2142.94
  5417.5  2146.3  5424.2 2147.68  5446.5 2149.25    5593 2141.47  5663.6 2139.75
  5716.1 2139.18  5750.9 2140.26  5768.6 2139.81  5815.6 2141.01    5850 2142.86
#Mann= 7 ,-1 , 0
  4514.9     .07       0    4751    .035       0  4826.2     .07       0
    4938    .035       0  4982.8    .035       0  4987.7    .035       0
  5157.1     .07       0
Bank Sta=4982.8,4987.7
XS Rating Curve= 0 ,0
Exp/Cntr=0.3,0.1

Type RM Length L Ch R = 1 ,5418    ,473,473,473
BEGIN DESCRIPTION:
UCFB HW Trib 12 10.0
END DESCRIPTION:
XS GIS Cut Line= 4
      1309675.47      6948649.66      1310256.11      6948936.89
        1310355.        6948838.      1310885.31      6948202.18
#Sta/Elev= 30
  4212.1  2116.5  4492.8  2115.5  4620.3 2115.15  4824.1  2114.8  4913.4 2113.38
  4943.2 2112.08  4957.3 2112.79    4969 2112.08  4969.4 2111.58  4973.9 2112.08
  4975.3 2112.21  4985.6 2113.18  5006.9 2112.81  5035.5  2114.8  5120.2 2114.62
  5226.9 2117.55    5305  2121.9  5325.8 2124.27  5368.8 2125.82  5432.5  2132.1
  5440.3 2133.75  5454.7 2135.07  5461.2 2134.36  5475.5 2136.29  5518.4 2136.29
  5539.3  2135.4  5553.6 2136.15  5652.5 2136.01  5759.2 2138.97  5827.7 2142.86
#Mann= 7 ,-1 , 0
  4212.1     .07       0  4492.8    .035       0  4620.3     .07       0
  4913.4    .035       0    4969     .07       0  4973.9    .035       0
  4975.3     .07       0
Bank Sta=4969,4973.9
XS Rating Curve= 0 ,0
Exp/Cntr=0.3,0.1

Type RM Length L Ch R = 1 ,4945    ,462,462,462
BEGIN DESCRIPTION:
UCFB HW Trib 12 9.0
END DESCRIPTION:
XS GIS Cut Line= 5
      1310397.62      6949367.53      1310676.81      6949061.01
        1310705.        6948888.       1310731.5      6948722.47
      1311079.97      6948313.03
#Sta/Elev= 30
  4409.6 2111.47  4463.8 2110.87  4499.6 2109.21  4543.5 2109.67  4548.9 2109.07
  4556.3 2110.01  4667.3 2109.24  4716.4 2109.24  4754.3 2109.48  4775.2 2107.95
  4789.4 2109.28  4817.8  2107.9  4822.9 2109.04  4849.9 2109.86  4898.2 2107.17
  4971.3 2106.94  4986.9 2105.05  4987.3 2104.55  4991.8 2105.05  5009.6 2107.52
    5040 2113.38  5070.4 2114.49  5080.5 2113.94  5100.8 2115.88  5206.5 2120.07
  5337.3 2125.13  5355.8 2125.99  5421.5 2128.82  5569.8 2136.84  5704.8 2139.67
#Mann= 10 ,-1 , 0
  4409.6    .035       0  4543.5     .07       0  4667.3    .035       0
  4716.4     .07       0  4849.9    .035       0  4986.9    .035       0
  4991.8    .035       0  5206.5     .07       0  5337.3    .035       0
  5355.8     .07       0
Bank Sta=4986.9,4991.8
XS Rating Curve= 0 ,0
Exp/Cntr=0.3,0.1

Type RM Length L Ch R = 1 ,4483    ,516,516,516
BEGIN DESCRIPTION:
UCFB HW Trib 12 8.0
END DESCRIPTION:
XS GIS Cut Line= 4
      1310659.02      6950111.48      1310937.23      6949193.82
      1311073.94      6949166.03        1311080.      6948462.97
#Sta/Elev= 30
  3972.1 2108.96  4174.3 2107.66    4219 2105.55  4251.9 2101.76  4255.4 2100.39
  4255.8 2099.89  4260.4 2100.39  4284.8 2102.27    4323  2102.6  4367.8 2104.65
  4421.7 2106.33  4492.7 2105.52  4519.1 2107.01  4596.7 2105.93  4695.4 2108.42
  4832.3 2107.88  4875.6 2105.73  4905.1 2105.59  5000.2 2104.06  5020.6 2102.34
  5035.7 2104.66  5070.5 2104.07  5108.5 2106.97  5147.6 2106.64  5343.6 2111.94
  5434.3 2116.54  5508.6  2120.8  5598.6 2127.65  5728.6 2139.26  5773.6 2139.25
#Mann= 8 ,-1 , 0
  3972.1    .035       0  4255.4    .035       0  4260.4    .035       0
  4367.8     .07       0  4905.1    .035       0  5147.6     .07       0
  5343.6    .035       0  5434.3     .07       0
Bank Sta=4255.4,4260.4
XS Rating Curve= 0 ,0
Exp/Cntr=0.3,0.1

Type RM Length L Ch R = 1 ,3967    ,339,339,339
BEGIN DESCRIPTION:
UCFB HW Trib 12 7.0
END DESCRIPTION:
XS GIS Cut Line= 4
      1310979.99      6949913.03      1311252.33      6949282.36
      1311218.62      6949173.94        1311230.      6948612.95
#Sta/Elev= 30
  4199.5 2107.31    4252 2107.38  4427.4 2101.14  4456.4 2100.75  4466.4 2098.98
  4474.4 2100.74  4526.9 2103.05  4555.8 2101.78  4695.1 2105.08  4763.8  2104.4
  4778.3 2103.01  4783.7 2103.83  4825.3 2103.32  4859.7 2105.39    4912 2105.69
  4965.6 2101.42  5025.9 2100.65  5033.4 2098.58  5033.8 2098.08  5038.4 2098.58
  5039.8 2098.96  5064.5 2102.87    5086 2103.26    5116 2106.44    5146 2108.11
  5249.6 2109.81    5413 2117.91    5466 2120.81  5546.1 2128.02  5561.1 2128.51
#Mann= 8 ,-1 , 0
  4199.5    .035       0  4427.4     .07       0  4763.8    .035       0
  5033.4    .035       0  5038.4    .035       0  5039.8     .07       0
  5249.6    .035       0    5413     .07       0
Bank Sta=5033.4,5038.4
XS Rating Curve= 0 ,0
Exp/Cntr=0.3,0.1

Type RM Length L Ch R = 1 ,3628    ,287,287,287
BEGIN DESCRIPTION:
UCFB HW Trib 12 6.0
END DESCRIPTION:
XS GIS Cut Line= 4
        1311330.      6949812.99        1311455.        6949338.
      1311462.03      6949090.59      1311692.41      6948602.06
#Sta/Elev= 30
  4504.8 2108.41  4745.9 2106.82  4801.1 2106.41  4882.2 2105.16  4913.2 2103.71
  4944.3 2099.81  4985.6 2099.81  4990.5 2098.44    4991 2097.94  4996.2 2098.44
    5006  2100.3    5046 2099.46    5076 2101.54    5125 2101.93  5330.9 2107.89
  5359.2  2104.9  5376.4 2107.15  5390.1 2106.76  5399.2 2108.39  5412.2 2108.53
  5444.8 2108.42  5501.4 2105.34  5518.6 2106.37  5559.7 2103.98  5609.7 2103.22
  5683.6 2106.65  5689.1 2108.69  5729.2 2109.62  5757.5 2112.87  5783.6 2113.02
#Mann= 7 ,-1 , 0
  4504.8    .035       0  4745.9     .07       0  4801.1    .035       0
  4990.5    .035       0  4996.2    .035       0    5125     .07       0
  5559.7    .035       0
Bank Sta=4990.5,4996.2
XS Rating Curve= 0 ,0
Exp/Cntr=0.3,0.1

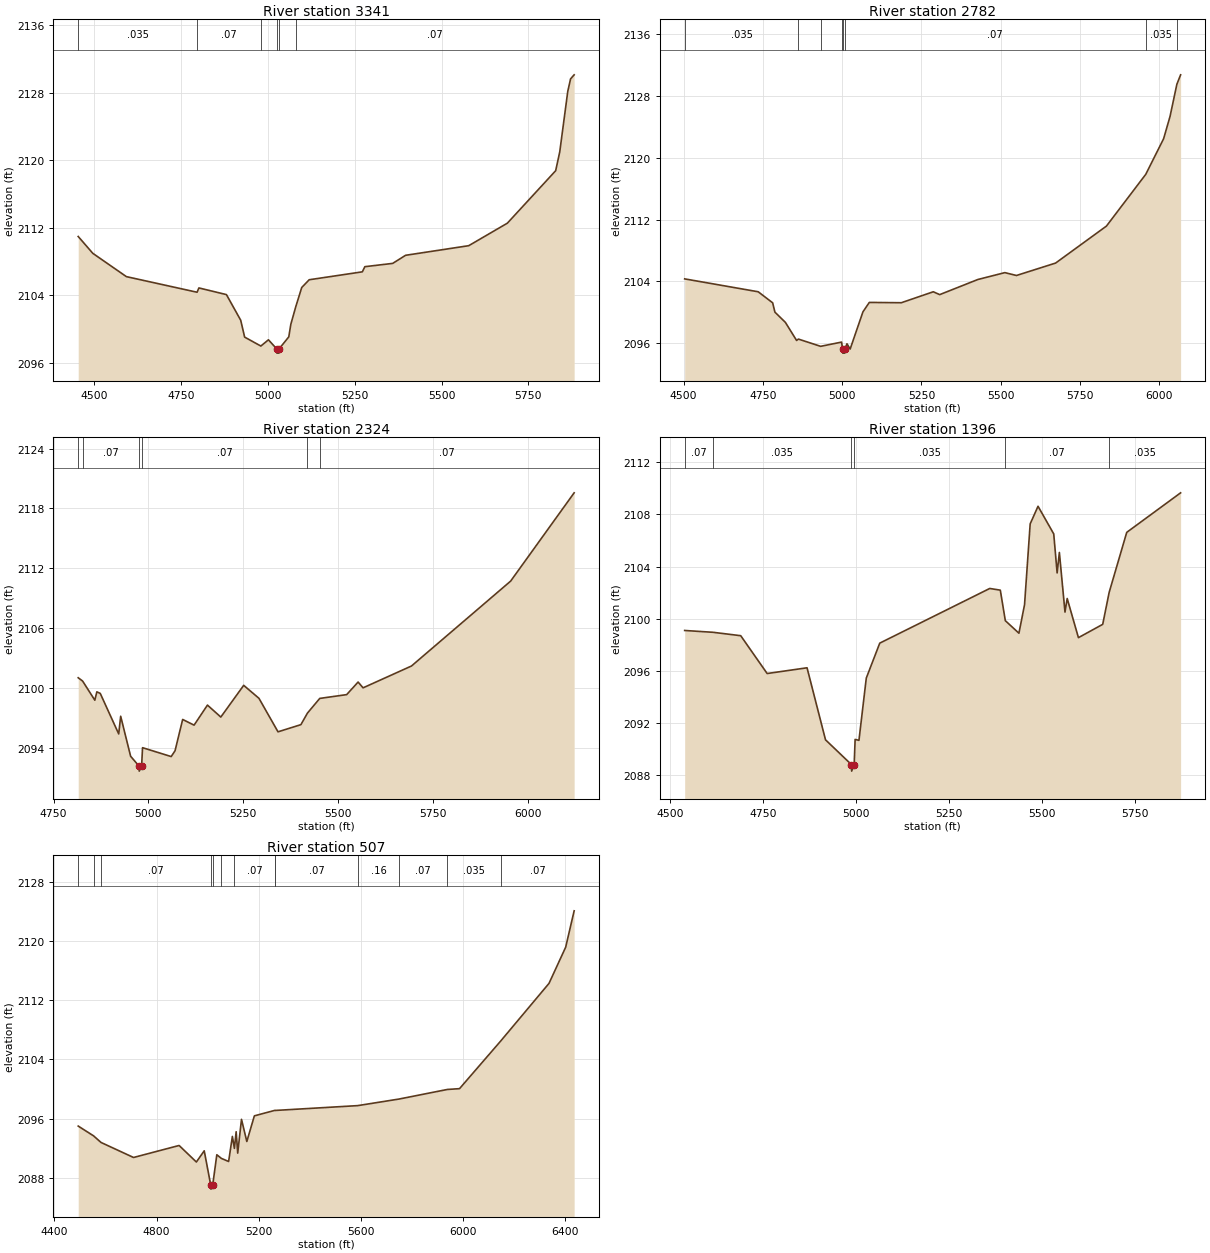
Type RM Length L Ch R = 1 ,3341    ,559,559,559
BEGIN DESCRIPTION:
UCFB HW Trib 12 5.0
END DESCRIPTION:
XS GIS Cut Line= 3
      1311580.01      6949912.96        1311705.        6949388.
      1312154.02      6948622.17
#Sta/Elev= 30
  4454.2 2110.97  4496.3 2108.97  4592.9 2106.21  4796.3 2104.36  4801.6 2104.87
  4880.8 2104.08  4921.9 2101.04  4933.2 2099.04  4979.9 2097.98  5001.7 2098.72
  5025.6 2097.64  5026.1 2097.14  5031.8 2097.14  5032.3 2097.64  5060.3 2099.07
  5066.1 2100.55  5080.2 2102.62  5097.5 2104.92    5119 2105.84    5272 2106.78
  5279.2 2107.39  5359.3 2107.78  5396.5 2108.74  5578.2 2109.88  5689.4 2112.55
  5828.4 2118.77  5840.1 2120.99  5863.2 2128.17  5871.3 2129.66  5881.6 2130.14
#Mann= 6 ,-1 , 0
  4454.2    .035       0  4796.3     .07       0  4979.9    .035       0
  5025.6    .035       0  5032.3    .035       0  5080.2     .07       0
Bank Sta=5025.6,5032.3
XS Rating Curve= 0 ,0
Exp/Cntr=0.3,0.1

Type RM Length L Ch R = 1 ,2782    ,458,458,458
BEGIN DESCRIPTION:
UCFB HW Trib 12 4.0
END DESCRIPTION:
XS GIS Cut Line= 3
      1312029.99      6950163.04        1312155.        6949688.
      1312289.91      6948624.84
#Sta/Elev= 30
  4503.7 2104.32  4735.4 2102.65  4780.9 2101.22  4788.1 2100.01  4821.2 2098.68
  4856.4 2096.34  4862.1 2096.52  4932.2 2095.58  4998.1 2096.13  5001.6  2095.2
  5002.1  2094.7  5007.8  2094.7  5008.3  2095.2  5015.1 2095.91  5025.2 2095.23
  5065.5 2100.05  5085.6 2101.27  5186.4 2101.23  5287.2 2102.65  5307.4 2102.28
  5427.6 2104.24  5512.7 2105.13  5549.3 2104.76  5672.7 2106.37  5832.8 2111.16
  5956.8 2117.87    6013 2122.48  6033.2 2125.36  6054.8 2129.54  6066.6 2130.76
#Mann= 8 ,-1 , 0
  4503.7    .035       0  4862.1     .07       0  4932.2    .035       0
  4998.1     .07       0  5001.6     .07       0  5008.3     .07       0
  5956.8    .035       0  6054.8     .07       0
Bank Sta=5001.6,5008.3
XS Rating Curve= 0 ,0
Exp/Cntr=0.3,0.1

Type RM Length L Ch R = 1 ,2324    ,928,928,928
BEGIN DESCRIPTION:
UCFB HW Trib 12 3.0
END DESCRIPTION:
XS GIS Cut Line= 3
      1312475.46      6950012.99      1312534.75      6949837.75
      1312644.71      6948721.55
#Sta/Elev= 30
    4815 2101.03  4826.6  2100.7  4858.8 2098.78  4864.1 2099.62  4873.1 2099.46
  4921.7  2095.4  4926.9 2097.17  4953.1 2093.16  4975.3 2092.17  4975.8 2091.67
    4982 2092.17  4984.5 2094.02    5060 2093.13  5070.1 2093.71  5090.2 2096.85
  5120.3 2096.28  5155.5 2098.29  5190.7 2097.09    5251 2100.27  5291.2 2098.97
  5341.4 2095.61  5401.7 2096.33    5419 2097.49  5451.4 2098.96  5522.3 2099.34
  5552.4  2100.6  5565.5 2100.02  5693.1 2102.21  5954.3 2110.72  6121.6 2119.57
#Mann= 6 ,-1 , 0
    4815    .035       0  4826.6     .07       0  4975.3     .07       0
    4982     .07       0    5419    .035       0  5451.4     .07       0
Bank Sta=4975.3,4982
XS Rating Curve= 0 ,0
Exp/Cntr=0.3,0.1

Type RM Length L Ch R = 1 ,1396    ,889,889,889
BEGIN DESCRIPTION:
UCFB HW Trib 12 2.0
END DESCRIPTION:
XS GIS Cut Line= 3
        1312980.        6949963.        1313255.        6949588.
      1313730.01      6948862.98
#Sta/Elev= 30
  4540.2  2099.1  4616.4 2098.96  4690.7  2098.7  4761.7  2095.8  4868.8 2096.24
  4918.4 2090.72  4988.1 2088.82  4988.6 2088.32  4995.4 2088.82  4997.9 2090.75
  5008.2 2090.68  5027.9 2095.45  5064.1 2098.13  5359.5 2102.32  5387.8 2102.19
  5401.3 2099.85  5437.8 2098.89  5452.9 2101.08    5468 2107.27  5489.1 2108.62
  5531.3  2106.5  5540.4 2103.51  5546.4 2105.08  5561.5 2100.51  5567.4 2101.55
  5597.6 2098.55  5662.8 2099.57  5680.1 2102.02  5727.3 2106.62    5872 2109.65
#Mann= 6 ,-1 , 0
  4540.2     .07       0  4616.4    .035       0  4988.1    .035       0
  4995.4    .035       0  5401.3     .07       0  5680.1    .035       0
Bank Sta=4988.1,4995.4
XS Rating Curve= 0 ,0
Exp/Cntr=0.3,0.1

Type RM Length L Ch R = 1 ,507     ,0,0,0
BEGIN DESCRIPTION:
UCFB HW Trib 12 1.0
END DESCRIPTION:
XS GIS Cut Line= 4
      1313335.29      6950062.98      1313688.25      6949790.46
      1313821.07      6949798.27      1314930.34      6949006.03
#Sta/Elev= 30
  4492.9    2095    4553 2093.68  4582.2 2092.79  4709.6 2090.76    4888 2092.38
  4955.6 2090.15  4986.4 2091.66  5012.1 2086.99  5012.6 2086.49  5019.4 2086.99
  5035.7 2091.13  5053.3 2090.64  5081.9 2090.22  5096.6  2093.6  5104.6 2091.99
  5111.4 2094.24  5117.5 2091.35  5132.3 2095.91  5153.2 2092.92  5182.7 2096.38
    5264 2097.13  5265.1 2097.11  5587.6 2097.76  5749.7 2098.65  5938.3 2099.94
  5986.1 2100.05  6146.9 2106.46  6336.6 2114.26  6401.8 2119.14    6435 2124.05
#Mann= 13 ,-1 , 0
  4492.9     .07       0    4553    .035       0  4582.2     .07       0
  5012.1     .07       0  5019.4     .07       0  5053.3    .035       0
  5104.6     .07       0    5264    .035       0  5265.1     .07       0
  5587.6     .16       0  5749.7     .07       0  5938.3    .035       0
  6146.9     .07       0
Bank Sta=5012.1,5019.4
XS Rating Curve= 0 ,0
Exp/Cntr=0.3,0.1

Chan Stop Cuts=-1
Use User Specified Reach Order=0
Composite Channel Slope=5