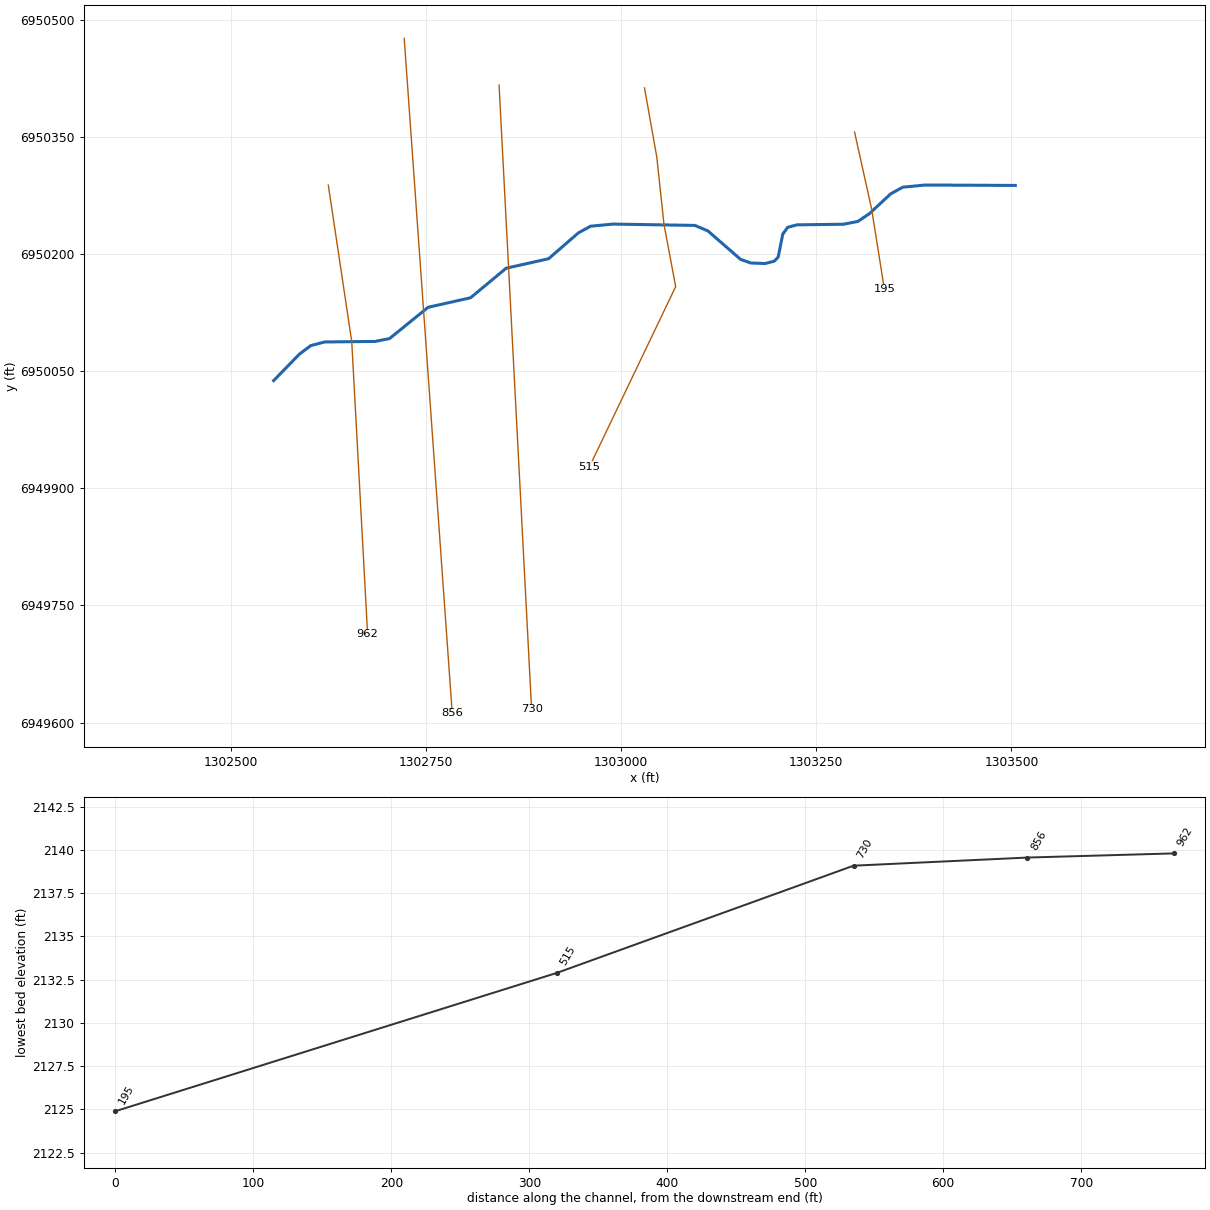
--- UCFB HW Trib 14.prj (project) ---

Proj Title=UCFB HW Trib 14 Base Level Engineering
Current Plan=p01
Default Exp/Contr=0.3,0.1
English Units
Geom File=g01
Flow File=f01
Plan File=p01
BEGIN DESCRIPTION:
UCFB HW Trib 14
END DESCRIPTION:

--- UCFB HW Trib 14.p01 (plan) ---

Plan Title=Multiple Run
Short Identifier=Multiple
Geom File=g01
Flow File=f01
Subcritical Flow
K Sum by GR= 0
Std Step Tol= 0.01
Critical Tol= 0.01
Num of Std Step Trials= 20
Max Error Tol= 0.3
Flow Tol Ratio= 0.001
Split Flow NTrial= 30
Split Flow Tol= 0.02
Split Flow Ratio= 0.02
Log Output Level= 0
Friction Slope Method= 1
Unsteady Friction Slope Method= 2
Unsteady Bridges Friction Slope Method= 1
Parabolic Critical Depth
Global Vel Dist=  1 , 1 , 1
Global Log Level= 0
CheckData=True
Encroach Param= -1, 0, 0, 0
BEGIN DESCRIPTION:
Multiple Run
END DESCRIPTION:

--- UCFB HW Trib 14.f01 (steady flow) ---

Flow Title=Multiple
Number of Profiles=7
Profile Names=10-year,25-year,50-year,1pct_min,100-year,1pct_plu,500-year
River Rch & RM= UCFB HW Trib 14,Reach-1,962
     386     561     712     449     896    1787    1438
Boundary for River Rch & Prof#=UCFB HW Trib 14,Reach-1,1
Up Type=0
Dn Type=3
Dn Slope=0.005
Boundary for River Rch & Prof#=UCFB HW Trib 14,Reach-1,2
Up Type=0
Dn Type=3
Dn Slope=0.005
Boundary for River Rch & Prof#=UCFB HW Trib 14,Reach-1,3
Up Type=0
Dn Type=3
Dn Slope=0.005
Boundary for River Rch & Prof#=UCFB HW Trib 14,Reach-1,4
Up Type=0
Dn Type=3
Dn Slope=0.005
Boundary for River Rch & Prof#=UCFB HW Trib 14,Reach-1,5
Up Type=0
Dn Type=3
Dn Slope=0.005
Boundary for River Rch & Prof#=UCFB HW Trib 14,Reach-1,6
Up Type=0
Dn Type=3
Dn Slope=0.005
Boundary for River Rch & Prof#=UCFB HW Trib 14,Reach-1,7
Up Type=0
Dn Type=3
Dn Slope=0.005

--- UCFB HW Trib 14.g01 (geometry) ---

Geom Title=Existing Conditions

River Reach=UCFB HW Trib 14,Reach-1
Reach XY= 30
      1302555.00      6950038.00      1302587.95      6950071.88
      1302602.45      6950082.78      1302620.22      6950087.47
      1302684.93      6950088.17      1302703.43      6950091.80
      1302752.82      6950131.89      1302807.20      6950144.08
      1302852.80      6950181.92      1302907.18      6950194.12
      1302945.33      6950227.21      1302960.93      6950235.77
      1302989.84      6950238.48      1303094.52      6950236.77
      1303111.12      6950229.80      1303153.14      6950193.28
      1303166.04      6950188.68      1303184.56      6950187.94
      1303196.36      6950191.02      1303201.27      6950196.21
      1303207.16      6950225.65      1303213.48      6950234.38
      1303225.35      6950237.51      1303284.75      6950238.29
      1303303.34      6950241.88      1303318.10      6950251.83
      1303345.34      6950277.16      1303360.92      6950285.78
      1303389.79      6950288.51      1303505.00      6950288.00

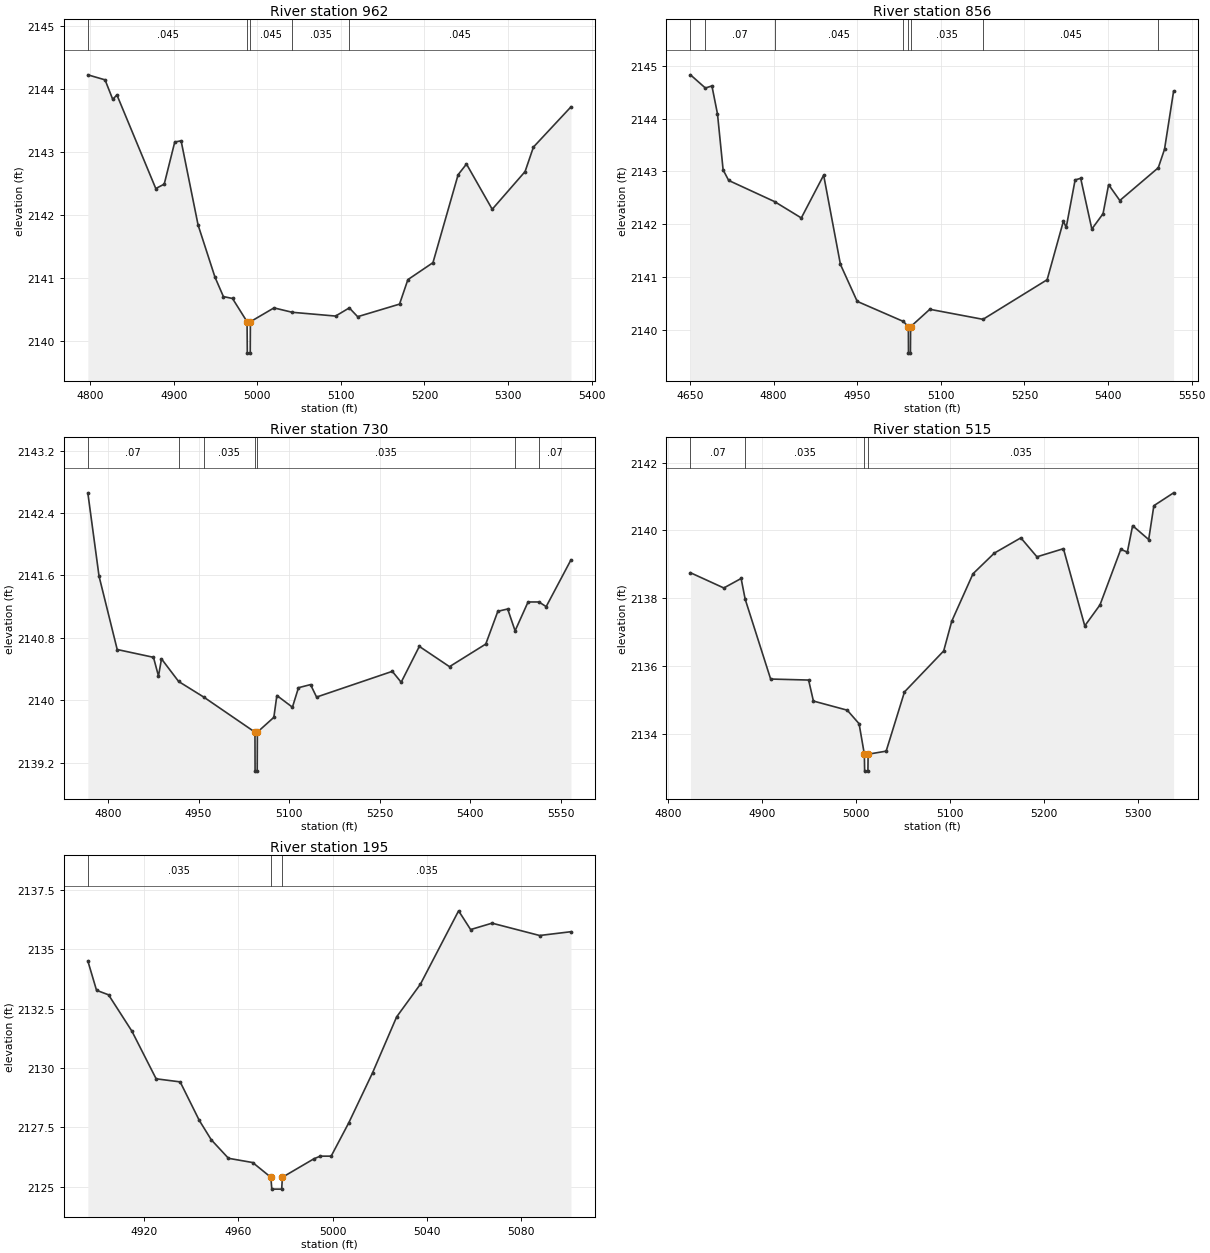
Type RM Length L Ch R = 1,962,106,106,106
BEGIN DESCRIPTION:
UCFB HW Trib 14 2.0
END DESCRIPTION:
XS GIS Cut Line= 3
      1302624.99      6950288.40      1302655.00      6950088.00
      1302675.33      6949713.19
#Sta/Elev= 30
  4797.3 2144.23  4817.9 2144.15  4827.1 2143.84  4832.1 2143.91  4878.6 2142.42
  4888.7 2142.49  4901.3 2143.16  4908.9 2143.18  4929.2 2141.84  4949.4 2141.01
  4959.5 2140.70  4970.4 2140.67  4987.8 2140.30  4988.1 2139.80  4991.6 2139.80
  4991.8 2140.30  5020.0 2140.52  5041.9 2140.45  5093.7 2140.39  5110.1 2140.52
  5120.1 2140.38  5170.2 2140.58  5180.2 2140.97  5210.2 2141.24  5240.3 2142.64
  5250.3 2142.81  5281.1 2142.09  5320.4 2142.69  5330.4 2143.08  5375.3 2143.72
#Mann=5,-1,0
  4797.3   0.045       0  4987.8   0.045       0  4991.8   0.045       0
  5041.9   0.035       0  5110.1   0.045       0
Bank Sta=4987.8,4991.8
Exp/Cntr=0.3,0.1

Type RM Length L Ch R = 1,856,126,126,126
BEGIN DESCRIPTION:
UCFB HW Trib 14 1.7
END DESCRIPTION:
XS GIS Cut Line= 2
      1302722.21      6950476.42      1302783.75      6949611.71
#Sta/Elev= 30
  4650.7 2144.83  4677.5 2144.58  4689.2 2144.62  4699.2 2144.09  4709.3 2143.03
  4719.3 2142.83  4801.5 2142.43  4849.6 2142.12  4889.7 2142.93  4919.8 2141.24
  4949.9 2140.54  5032.7 2140.16  5041.7 2140.06  5041.9 2139.56  5045.4 2139.56
  5045.7 2140.06  5080.2 2140.39  5175.6 2140.20  5290.7 2140.95  5319.9 2142.06
  5324.9 2141.94  5340.9 2142.84  5350.9 2142.87  5370.9 2141.91  5391.0 2142.20
  5401.0 2142.75  5421.1 2142.45  5490.1 2143.07  5501.3 2143.42  5517.6 2144.52
#Mann=8,-1,0
  4650.7   0.035       0  4677.5    0.07       0  4801.5   0.045       0
  5032.7   0.035       0  5041.7   0.045       0  5045.7   0.035       0
  5175.6   0.045       0  5490.1    0.07       0
Bank Sta=5041.7,5045.7
Exp/Cntr=0.3,0.1

Type RM Length L Ch R = 1,730,215,215,215
BEGIN DESCRIPTION:
UCFB HW Trib 14 1.6
END DESCRIPTION:
XS GIS Cut Line= 2
      1302843.73      6950416.61      1302885.40      6949617.00
#Sta/Elev= 30
  4766.5 2142.66  4785.1 2141.59  4815.2 2140.65  4875.3 2140.55  4883.6 2140.31
  4888.6 2140.53  4917.0 2140.24  4958.6 2140.04  5043.5 2139.59  5043.7 2139.09
  5047.2 2139.09  5047.5 2139.59  5074.8 2139.78  5079.8 2140.06  5105.6 2139.91
  5115.6 2140.16  5135.6 2140.20  5145.6 2140.04  5271.1 2140.37  5285.8 2140.23
  5315.9 2140.69  5365.9 2140.43  5426.0 2140.72  5446.0 2141.14  5462.3 2141.17
  5474.6 2140.89  5496.1 2141.26  5514.2 2141.26  5526.1 2141.20  5567.2 2141.80
#Mann=7,-1,0
  4766.5    0.07       0  4917.0   0.045       0  4958.6   0.035       0
  5043.5   0.035       0  5047.5   0.035       0  5474.6   0.045       0
  5514.2    0.07       0
Bank Sta=5043.5,5047.5
Exp/Cntr=0.3,0.1

Type RM Length L Ch R = 1,515,320,320,320
BEGIN DESCRIPTION:
UCFB HW Trib 14 1.0
END DESCRIPTION:
XS GIS Cut Line= 5
      1303030.01      6950412.96      1303045.67      6950325.00
      1303055.00      6950238.00      1303069.97      6950158.33
      1302959.38      6949927.35
#Sta/Elev= 30
  4823.6 2138.75  4859.1 2138.30  4877.5 2138.58  4881.8 2137.97  4908.9 2135.61
  4949.3 2135.58  4954.4 2134.96  4990.4 2134.69  5003.0 2134.29  5008.6 2133.39
  5008.9 2132.89  5012.4 2132.89  5012.6 2133.39  5031.8 2133.48  5051.3 2135.23
  5093.0 2136.44  5101.6 2137.32  5124.2 2138.72  5146.9 2139.33  5175.1 2139.78
  5192.2 2139.22  5220.4 2139.46  5243.1 2137.18  5259.3 2137.80  5281.4 2139.44
  5288.4 2139.36  5294.0 2140.14  5311.1 2139.73  5316.6 2140.73  5337.6 2141.11
#Mann=4,-1,0
  4823.6    0.07       0  4881.8   0.035       0  5008.6   0.035       0
  5012.6   0.035       0
Bank Sta=5008.6,5012.6
Exp/Cntr=0.3,0.1

Type RM Length L Ch R = 1,195,0,0,0
BEGIN DESCRIPTION:
UCFB HW Trib 14 0.5
END DESCRIPTION:
XS GIS Cut Line= 3
      1303299.13      6950356.30      1303320.97      6950257.73
      1303337.33      6950154.88
#Sta/Elev= 26
  4896.1 2134.51  4899.8 2133.27  4904.9 2133.08  4914.8 2131.55  4925.1 2129.54
  4935.3 2129.41  4943.4 2127.79  4948.5 2126.97  4955.8 2126.19  4966.1 2126.01
  4973.8 2125.39  4974.2 2124.89  4978.4 2124.89  4978.7 2125.39  4992.1 2126.17
  4994.8 2126.28  4999.4 2126.28  5006.9 2127.69  5017.0 2129.80  5027.2 2132.15
  5037.3 2133.53  5053.5 2136.62  5058.6 2135.83  5067.7 2136.10  5087.9 2135.58
  5101.2 2135.74
#Mann=3,-1,0
  4896.1   0.035       0  4973.8   0.035       0  4978.7   0.035       0
Bank Sta=4973.8,4978.7
Exp/Cntr=0.3,0.1

Chan Stop Cuts=-1