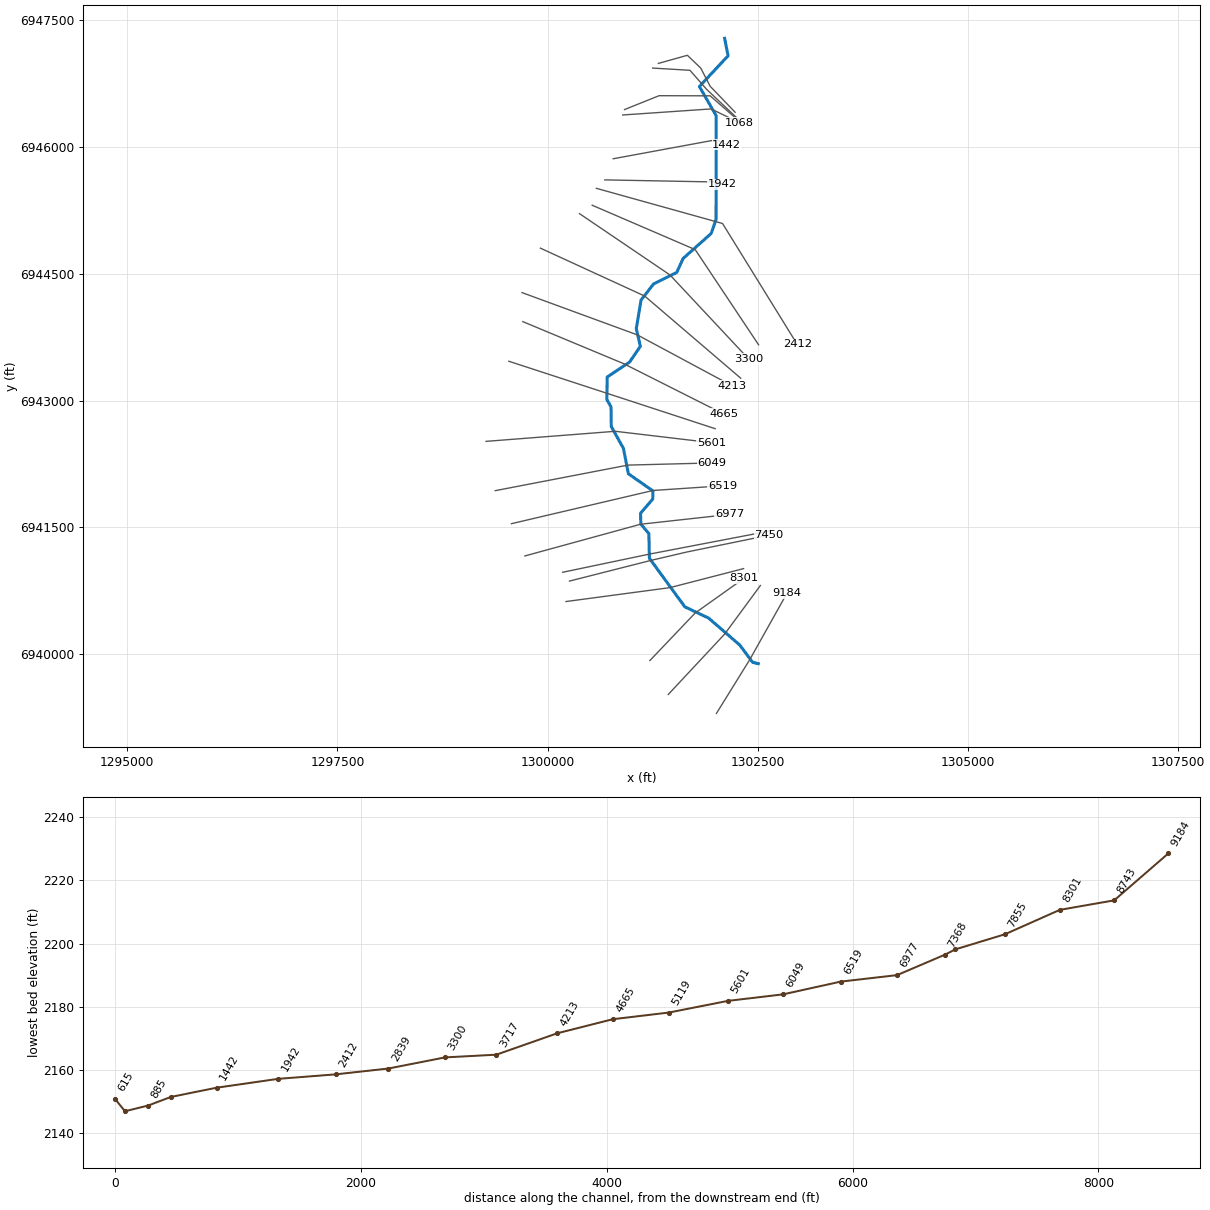
--- UCFB HW Trib 15.prj (project) ---

Proj Title=UCFB HW Trib 15 Base Level Engineering
Current Plan=p01
Default Exp/Contr=0.3,0.1
English Units
Geom File=g01
Flow File=f01
Plan File=p01
Y Axis Title=Elevation
X Axis Title(PF)=Main Channel Distance
X Axis Title(XS)=Station
BEGIN DESCRIPTION:
UCFB HW Trib 15
END DESCRIPTION:
DSS Export Rating Curves= 0
DSS Export Rating Curve Sorted= 0
DSS Export Volume Flow Curves= 0
DXF OffsetX= 0
DXF OffsetY= 0
DXF ScaleX= 1
DXF ScaleY= 10

--- UCFB HW Trib 15.p01 (plan) ---

Plan Title=Multiple Run
Short Identifier=Multiple
Geom File=g01
Flow File=f01
Subcritical Flow
K Sum by GR= 0
Std Step Tol= 0.01
Critical Tol= 0.01
Num of Std Step Trials= 20
Max Error Tol= 0.3
Flow Tol Ratio= 0.001
Split Flow NTrial= 30
Split Flow Tol= 0.02
Split Flow Ratio= 0.02
Log Output Level= 0
Friction Slope Method= 1
Unsteady Friction Slope Method= 2
Unsteady Bridges Friction Slope Method= 1
Parabolic Critical Depth
Global Vel Dist=  1 , 1 , 1
Global Log Level= 0
CheckData=True
Encroach Param= -1, 0, 0, 0
BEGIN DESCRIPTION:
Multiple Run
END DESCRIPTION:

--- UCFB HW Trib 15.f01 (steady flow) ---

Flow Title=Multiple
Number of Profiles=7
Profile Names=10-year,25-year,50-year,1pct_min,100-year,1pct_plu,500-year
River Rch & RM= UCFB HW Trib 15,Reach-1,9184
     399     583     742     470     938    1872    1519
River Rch & RM= UCFB HW Trib 15,Reach-1,6519
     441     645     821     520    1037    2069    1675
Boundary for River Rch & Prof#=UCFB HW Trib 15,Reach-1,1
Up Type=0
Dn Type=3
Dn Slope=0.005
Boundary for River Rch & Prof#=UCFB HW Trib 15,Reach-1,2
Up Type=0
Dn Type=3
Dn Slope=0.005
Boundary for River Rch & Prof#=UCFB HW Trib 15,Reach-1,3
Up Type=0
Dn Type=3
Dn Slope=0.005
Boundary for River Rch & Prof#=UCFB HW Trib 15,Reach-1,4
Up Type=0
Dn Type=3
Dn Slope=0.005
Boundary for River Rch & Prof#=UCFB HW Trib 15,Reach-1,5
Up Type=0
Dn Type=3
Dn Slope=0.005
Boundary for River Rch & Prof#=UCFB HW Trib 15,Reach-1,6
Up Type=0
Dn Type=3
Dn Slope=0.005
Boundary for River Rch & Prof#=UCFB HW Trib 15,Reach-1,7
Up Type=0
Dn Type=3
Dn Slope=0.005

--- UCFB HW Trib 15.g01 (geometry) ---

Geom Title=Existing Conditions
Program Version=4.10

River Reach=UCFB HW Trib 15 ,Reach-1
Reach XY= 30
        1302505.        6939888.      1302437.77      6939904.36
      1302285.16      6940108.39      1301914.68      6940427.24
      1301631.53      6940561.01      1301210.46      6941135.55
      1301203.94      6941427.56      1301108.54      6941539.47
      1301104.94      6941668.01      1301249.61      6941835.58
      1301253.12      6941932.29      1300960.42      6942135.33
      1300901.24      6942436.44      1300757.24      6942693.93
      1300753.78       6942927.5       1300704.8      6943012.92
      1300708.07       6943279.7      1300975.13      6943457.77
      1301102.86      6943643.97      1301054.29      6943853.06
      1301110.46      6944190.45      1301260.62      6944382.38
      1301535.42      6944517.43      1301610.59      6944682.39
      1301944.48      6944978.21      1302002.74      6945143.94
      1302004.49      6946372.79      1301804.53      6946717.84
      1302145.86      6947081.27        1302105.        6947288.

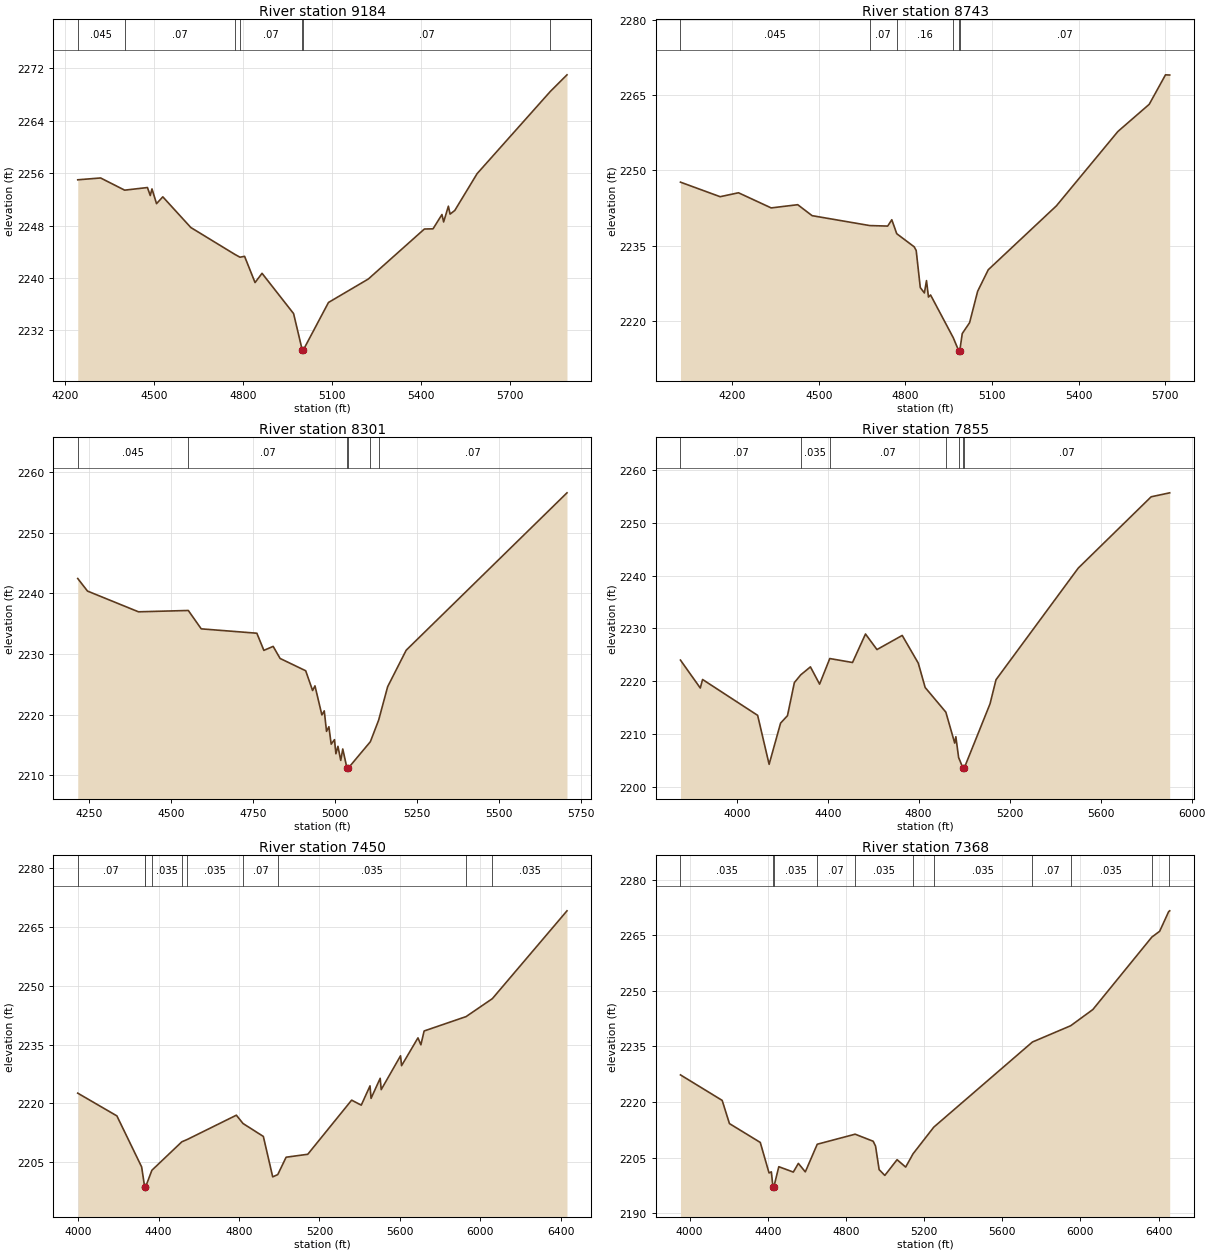
Type RM Length L Ch R = 1 ,9184    ,441,441,441
BEGIN DESCRIPTION:
UCFB HW Trib 15 19.0
END DESCRIPTION:
XS GIS Cut Line= 3
      1302007.77        6939300.        1302405.        6939938.
      1302846.36      6940721.94
#Sta/Elev= 30
  4242.8 2254.99  4319.9 2255.27  4401.1 2253.41    4478 2253.81  4487.5 2252.59
  4493.3  2253.6  4508.7 2251.35  4529.9 2252.39  4624.4 2247.71  4774.1 2243.58
  4790.4 2243.18  4805.9 2243.31  4841.2 2239.31  4864.8 2240.72  4971.3 2234.57
  5000.3 2229.04  5000.6 2228.54  5004.3 2229.04    5089 2236.27  5223.5 2239.85
  5412.7 2247.48  5441.9 2247.51    5472 2249.69  5477.7 2248.56  5493.7 2250.96
  5499.4 2249.75  5515.3 2250.31  5590.5 2255.92  5837.5 2268.46    5894 2271.01
#Mann= 7 ,-1 , 0
  4242.8    .045       0  4401.1     .07       0  4774.1     .16       0
  4790.4     .07       0  5000.3     .07       0  5004.3     .07       0
  5837.5    .035       0
Bank Sta=5000.3,5004.3
XS Rating Curve= 0 ,0
Exp/Cntr=0.3,0.1

Type RM Length L Ch R = 1 ,8743    ,442,442,442
BEGIN DESCRIPTION:
UCFB HW Trib 15 18.0
END DESCRIPTION:
XS GIS Cut Line= 3
      1301434.88      6939523.99        1302105.        6940238.
      1302529.98      6940812.97
#Sta/Elev= 30
  4020.8 2247.67  4158.2 2244.78  4221.7 2245.56    4335 2242.55  4426.9 2243.19
  4476.6 2241.01  4676.3 2239.04  4738.4 2238.94  4752.6  2240.2  4769.8 2237.42
  4830.3 2234.81  4837.1 2234.08  4851.3 2226.71  4865.5 2225.64  4872.8  2228.1
  4879.6 2224.83  4886.9 2225.24  4965.6 2216.73  4984.1 2214.18  4984.3 2213.68
  4988.1 2214.18  4996.6 2217.57    5022 2219.73  5049.8 2225.96  5086.7 2230.26
  5322.6 2242.96  5535.5 2257.74  5644.1 2263.15  5700.4 2269.01    5715 2268.97
#Mann= 6 ,-1 , 0
  4020.8    .045       0  4676.3     .07       0  4769.8     .16       0
  4965.6     .07       0  4984.1     .07       0  4988.1     .07       0
Bank Sta=4984.1,4988.1
XS Rating Curve= 0 ,0
Exp/Cntr=0.3,0.1

Type RM Length L Ch R = 1 ,8301    ,446,446,446
BEGIN DESCRIPTION:
UCFB HW Trib 15 17.0
END DESCRIPTION:
XS GIS Cut Line= 3
       1301216.1      6939925.01        1301755.        6940488.
      1302335.88      6940898.96
#Sta/Elev= 30
  4215.1 2242.43  4244.8 2240.36  4400.2 2236.94    4552 2237.16  4591.4 2234.13
  4760.9 2233.41  4782.3 2230.58  4810.6 2231.24  4831.7 2229.25  4909.7 2227.22
  4930.8 2223.96    4938 2224.73  4959.1 2219.93  4966.3 2220.61  4973.2 2217.23
  4980.4 2217.99  4987.4 2215.12  4997.5 2215.86  5001.8 2213.53    5008 2214.76
  5016.6 2212.44  5022.7 2214.32  5035.5 2211.17  5035.8 2210.67  5039.5 2211.17
  5106.8 2215.52    5132 2219.07  5159.4 2224.58    5216 2230.61    5706 2256.56
#Mann= 6 ,-1 , 0
  4215.1    .045       0    4552     .07       0  5035.5     .07       0
  5039.5     .07       0  5106.8     .16       0    5132     .07       0
Bank Sta=5035.5,5039.5
XS Rating Curve= 0 ,0
Exp/Cntr=0.3,0.1

Type RM Length L Ch R = 1 ,7855    ,405,405,405
BEGIN DESCRIPTION:
UCFB HW Trib 15 16.0
END DESCRIPTION:
XS GIS Cut Line= 3
      1300218.71      6940623.41        1301455.        6940788.
      1302330.03      6941013.01
#Sta/Elev= 30
  3752.8 2223.99  3839.9  2218.7  3849.9 2220.32  4092.1 2213.52  4142.5 2204.24
  4192.9 2212.05  4223.2 2213.46  4253.5 2219.73  4281.3 2221.19  4324.1 2222.71
  4364.4 2219.44  4409.2 2224.29  4509.1 2223.54  4566.2 2228.94  4616.6 2225.99
  4727.6 2228.67  4798.2 2223.42  4828.5  2218.8  4919.4 2214.13  4958.4 2208.26
  4963.4 2209.47  4975.5 2205.54  4995.5 2203.45  4995.7 2202.95  4999.5 2203.45
  5113.6  2215.7    5140 2220.28  5501.4 2241.43    5822 2254.95  5903.5  2255.7
#Mann= 7 ,-1 , 0
  3752.8     .07       0  4281.3    .035       0  4409.2     .07       0
  4919.4     .16       0  4975.5     .07       0  4995.5     .07       0
  4999.5     .07       0
Bank Sta=4995.5,4999.5
XS Rating Curve= 0 ,0
Exp/Cntr=0.3,0.1

Type RM Length L Ch R = 1 ,7450    ,82,82,82
BEGIN DESCRIPTION:
UCFB HW Trib 15 15.0
END DESCRIPTION:
XS GIS Cut Line= 4
      1300260.35      6940865.59      1301229.45       6941110.4
       1301655.6      6941209.51      1302631.04      6941408.01
#Sta/Elev= 30
  3998.4 2222.63    4193 2216.83  4316.1 2203.81  4331.2 2198.65  4331.5 2198.15
  4335.2 2198.65    4367 2202.96  4515.9 2210.22  4543.5 2210.83  4787.1 2217.01
  4820.1 2214.89  4921.2 2211.59  4967.7 2201.28  4992.8 2201.85  5034.4 2206.29
  5142.1 2207.04  5360.2 2220.85    5408 2219.57  5451.6 2224.49  5456.7  2221.3
  5502.1 2226.42  5507.2 2223.53  5603.3 2232.16  5608.4 2229.64    5690 2236.74
  5704.5 2234.96  5720.6 2238.49  5929.2 2242.16  6059.9 2246.74  6430.9 2269.14
#Mann= 10 ,-1 , 0
  3998.4     .07       0  4331.2    .035       0  4335.2     .07       0
    4367    .035       0  4515.9     .07       0  4543.5    .035       0
  4820.1     .07       0  4992.8    .035       0  5929.2     .07       0
  6059.9    .035       0
Bank Sta=4331.2,4335.2
XS Rating Curve= 0 ,0
Exp/Cntr=0.3,0.1

Type RM Length L Ch R = 1 ,7368    ,391,391,391
BEGIN DESCRIPTION:
UCFB HW Trib 15 14.5
END DESCRIPTION:
XS GIS Cut Line= 3
      1300179.58      6940969.75      1301203.41      6941183.31
      1302635.56      6941456.84
#Sta/Elev= 30
    3953 2227.33  4166.4 2220.45  4203.7 2214.19  4361.4 2209.11  4406.3 2200.88
  4418.2 2201.17  4426.4 2197.01  4426.7 2196.51  4430.4 2197.01  4456.3 2202.56
  4530.6 2201.11  4556.4 2203.45  4591.9 2201.16    4653 2208.62  4846.8 2211.33
  4939.2 2209.43  4951.4 2208.11  4969.8 2201.77  4998.9 2200.21  5061.6 2204.45
  5105.6 2202.46  5143.2 2206.03  5249.6 2213.24  5754.3  2236.2  5950.1 2240.59
  6063.8 2244.97  6365.4  2264.5  6405.4 2266.07  6451.5 2271.37  6456.9 2271.59
#Mann= 11 ,-1 , 0
    3953    .035       0  4426.4    .035       0  4430.4    .035       0
    4653     .07       0  4846.8    .035       0  5143.2     .07       0
  5249.6    .035       0  5754.3     .07       0  5950.1    .035       0
  6365.4     .07       0  6451.5    .035       0
Bank Sta=4426.4,4430.4
XS Rating Curve= 0 ,0
Exp/Cntr=0.3,0.1

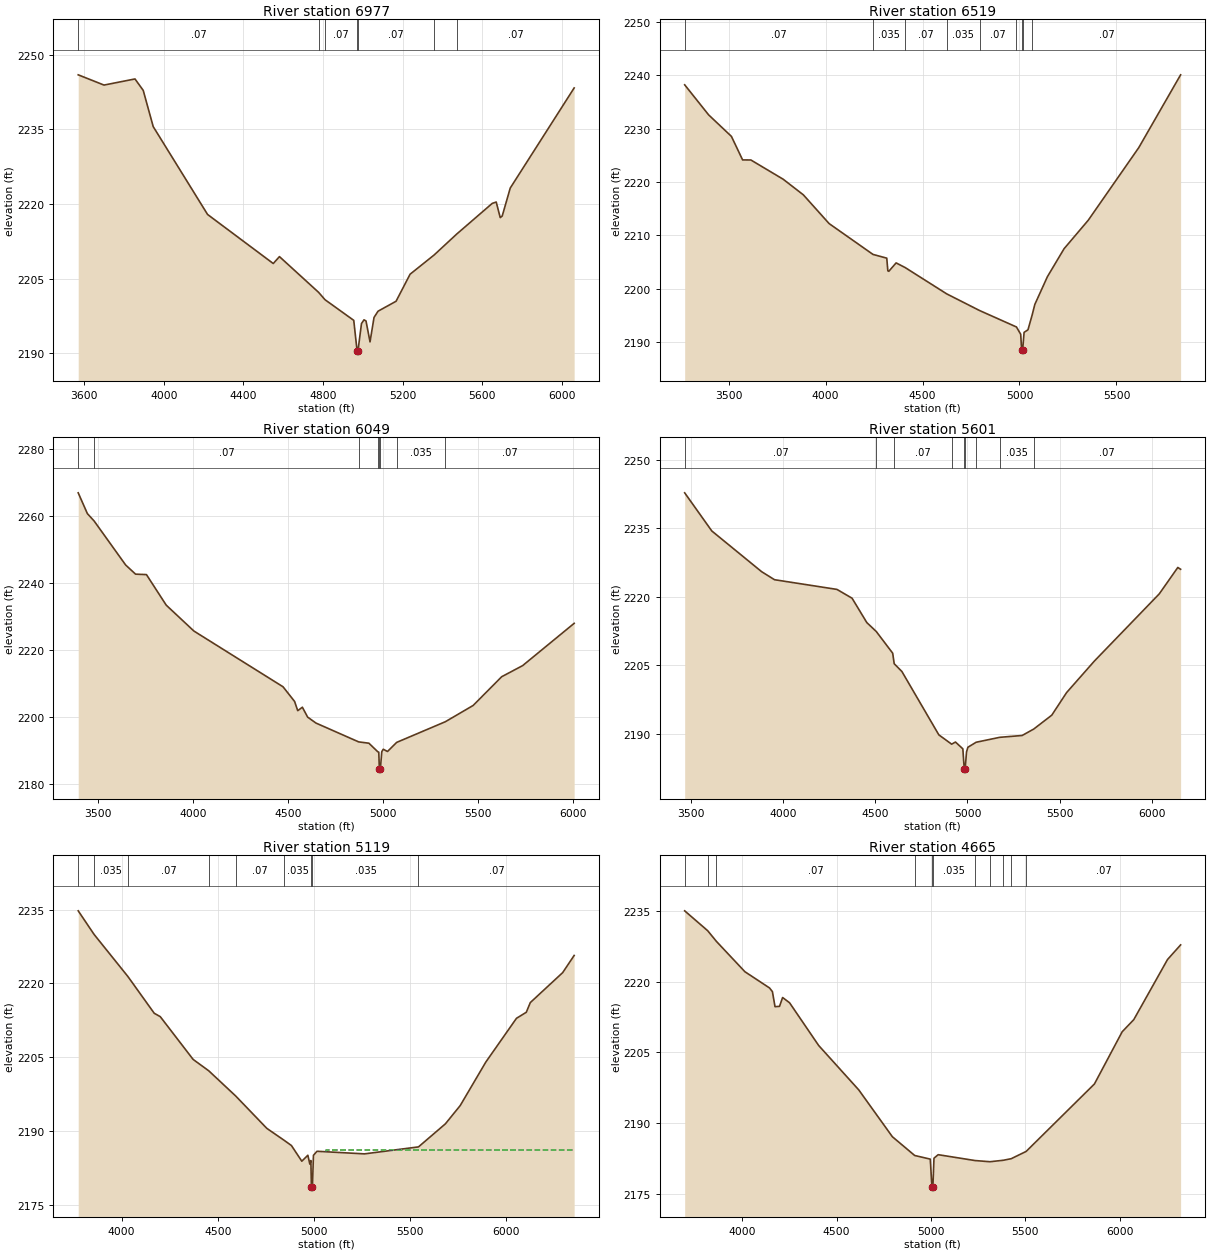
Type RM Length L Ch R = 1 ,6977    ,458,458,458
BEGIN DESCRIPTION:
UCFB HW Trib 15 14.0
END DESCRIPTION:
XS GIS Cut Line= 3
      1299729.99        6941163.        1301105.        6941538.
      1302164.02       6941654.2
#Sta/Elev= 30
  3570.7 2245.98  3700.3 2243.92  3855.8 2245.15  3897.2 2242.85  3947.3 2235.57
  4220.3  2217.9  4550.2 2208.03  4581.3 2209.42  4777.8 2202.24  4809.9 2200.76
  4954.5  2196.6  4971.1 2190.51  4971.5 2190.01  4975.8 2190.51  4993.3 2195.95
    5006 2196.71    5016 2196.48  5036.2 2192.27  5056.3 2197.19  5076.4 2198.44
  5166.9 2200.44  5237.4 2205.88  5357.9 2209.74  5471.1 2213.94  5649.8 2220.12
  5669.9  2220.4  5690.1 2217.26  5700.1 2217.59  5740.4 2223.21  6061.3 2243.34
#Mann= 7 ,-1 , 0
  3570.7     .07       0  4777.8    .035       0  4809.9     .07       0
  4971.1     .07       0  4975.8     .07       0  5357.9    .035       0
  5471.1     .07       0
Bank Sta=4971.1,4975.8
XS Rating Curve= 0 ,0
Exp/Cntr=0.3,0.1

Type RM Length L Ch R = 1 ,6519    ,470,470,470
BEGIN DESCRIPTION:
UCFB HW Trib 15 13.0
END DESCRIPTION:
XS GIS Cut Line= 3
      1299570.29      6941544.82        1301255.        6941938.
      1302080.31      6941992.71
#Sta/Elev= 30
  3273.7 2238.22  3397.2 2232.59  3514.7 2228.56  3572.4 2224.15    3615 2224.14
  3781.7 2220.53  3885.6 2217.61  4018.3 2212.23  4244.6 2206.45  4315.7 2205.75
  4321.2 2203.38  4326.4 2203.29  4363.8 2204.86  4410.4 2203.99  4624.7 2199.06
  4794.2 2195.94  4984.3 2192.86  5006.2  2191.5  5011.3 2188.46  5011.7 2187.96
  5016.1 2188.46  5023.7 2191.85  5043.8 2192.33  5065.8 2195.17  5079.1 2197.08
    5144 2202.28  5229.8 2207.51  5354.5 2212.85    5615 2226.45  5830.8 2240.09
#Mann= 9 ,-1 , 0
  3273.7     .07       0  4244.6    .035       0  4410.4     .07       0
  4624.7    .035       0  4794.2     .07       0  4984.3    .035       0
  5011.3    .035       0  5016.1    .035       0  5065.8     .07       0
Bank Sta=5011.3,5016.1
XS Rating Curve= 0 ,0
Exp/Cntr=0.3,0.1

Type RM Length L Ch R = 1 ,6049    ,448,448,448
BEGIN DESCRIPTION:
UCFB HW Trib 15 12.0
END DESCRIPTION:
XS GIS Cut Line= 3
      1299377.62      6941935.46        1300955.        6942238.
      1301955.74      6942263.58
#Sta/Elev= 30
  3398.2 2266.93  3446.4 2260.73    3482 2258.52  3647.8 2245.39  3699.8 2242.67
  3756.9 2242.54  3860.9 2233.43  4006.5  2225.7  4474.9 2209.08  4535.9 2204.69
  4552.2 2201.95  4576.7 2202.98  4604.2 2200.04    4648 2198.26  4872.6 2192.64
  4926.3 2192.25  4972.9 2189.71  4978.3 2189.58  4981.5 2184.42  4981.9 2183.92
  4986.4 2184.42  4994.1 2189.71  5001.8 2190.45  5024.3 2189.78  5072.3 2192.49
  5328.5 2198.66  5474.5 2203.51  5624.5 2212.08  5734.6 2215.39  6005.4    2228
#Mann= 8 ,-1 , 0
  3398.2    .035       0    3482     .07       0  4872.6    .035       0
  4972.9     .07       0  4981.5     .07       0  4986.4     .07       0
  5072.3    .035       0  5328.5     .07       0
Bank Sta=4981.5,4986.4
XS Rating Curve= 0 ,0
Exp/Cntr=0.3,0.1

Type RM Length L Ch R = 1 ,5601    ,482,482,482
BEGIN DESCRIPTION:
UCFB HW Trib 15 11.0
END DESCRIPTION:
XS GIS Cut Line= 3
      1299268.24      6942518.79        1300805.        6942638.
      1301950.22      6942503.19
#Sta/Elev= 30
  3463.5 2242.78  3610.7 2234.44  3881.5 2225.52  3951.7 2223.76  4290.7 2221.64
    4373 2219.71  4453.2 2214.37  4504.1 2212.44  4593.6 2207.68  4601.9 2205.37
  4643.8 2203.66  4844.4  2189.8  4914.1 2187.76  4934.7 2188.23  4974.8 2186.74
  4982.3 2182.36  4982.7 2181.86  4987.3 2182.36  4994.8 2186.06  5002.4 2187.09
  5047.1 2188.18  5175.2 2189.26  5296.9 2189.66  5360.4 2191.08    5458 2194.11
  5538.5 2199.05  5689.6 2205.96    6042 2220.66  6142.7 2226.44    6158 2226.05
#Mann= 9 ,-1 , 0
  3463.5     .07       0  4504.1    .035       0  4601.9     .07       0
  4914.1    .035       0  4982.3    .035       0  4987.3    .035       0
  5047.1     .07       0  5175.2    .035       0  5360.4     .07       0
Bank Sta=4982.3,4987.3
XS Rating Curve= 0 ,0
Exp/Cntr=0.3,0.1

Type RM Length L Ch R = 1 ,5119    ,454,454,454
BEGIN DESCRIPTION:
UCFB HW Trib 15 10.0
END DESCRIPTION:
XS GIS Cut Line= 3
      1299539.08      6943466.69        1300705.        6943088.
      1301991.73      6942669.03
#Sta/Elev= 30
  3774.2 2234.77  3856.8 2229.97    4033 2221.39  4169.4 2213.94    4201 2213.24
  4371.7 2204.55  4452.8 2202.24  4593.3  2197.1  4755.1 2190.52  4842.7 2188.16
    4883 2187.03    4937 2183.84  4968.5 2185.05  4978.8 2183.25  4984.1 2183.98
    4987 2178.66  4987.4 2178.16  4992.1 2178.66  4997.5 2185.04    5016 2185.86
    5263 2185.33  5543.8 2186.75  5683.7 2191.44  5760.8 2195.16    5894 2204.01
  6053.4 2212.91  6104.3 2214.13  6125.4 2216.11  6293.6  2222.2  6353.3 2225.69
#Mann= 9 ,-1 , 0
  3774.2     .07       0  3856.8    .035       0    4033     .07       0
  4452.8    .035       0  4593.3     .07       0  4842.7    .035       0
    4987    .035       0  4992.1    .035       0  5543.8     .07       0
#XS Ineff= 2 , 0
       0                  5063.2       0 2186.17
Permanent Ineff=
       F       F
Bank Sta=4987,4992.1
XS Rating Curve= 0 ,0
Exp/Cntr=0.3,0.1

Type RM Length L Ch R = 1 ,4665    ,452,452,452
BEGIN DESCRIPTION:
UCFB HW Trib 15 9.0
END DESCRIPTION:
XS GIS Cut Line= 3
      1299705.68      6943935.47        1300905.        6943438.
      1302093.24      6942842.53
#Sta/Elev= 30
  3695.5 2234.97  3817.2 2230.77  3863.9 2228.49  4014.6 2222.08  4144.8 2218.65
  4160.3 2217.87  4174.1 2214.68    4198 2214.75  4214.4 2216.62  4251.2 2215.51
  4405.3 2206.47  4617.9 2197.06  4795.9 2187.15  4914.1 2183.18  4996.7 2182.41
  5005.3 2176.56  5005.7 2176.06  5010.5 2176.56  5016.3 2182.61  5038.6 2183.35
  5233.8 2182.11  5313.1 2181.86  5383.7 2182.17  5425.5  2182.5  5504.6 2184.04
  5866.4 2198.32  6013.4 2209.37  6074.9 2211.94  6253.6 2224.66    6323 2227.76
#Mann= 11 ,-1 , 0
  3695.5     .07       0  3817.2    .035       0  3863.9     .07       0
  4914.1    .035       0  5005.3    .035       0  5010.5    .035       0
  5233.8     .07       0  5313.1    .035       0  5383.7     .07       0
  5425.5    .035       0  5504.6     .07       0
Bank Sta=5005.3,5010.5
XS Rating Curve= 0 ,0
Exp/Cntr=0.3,0.1

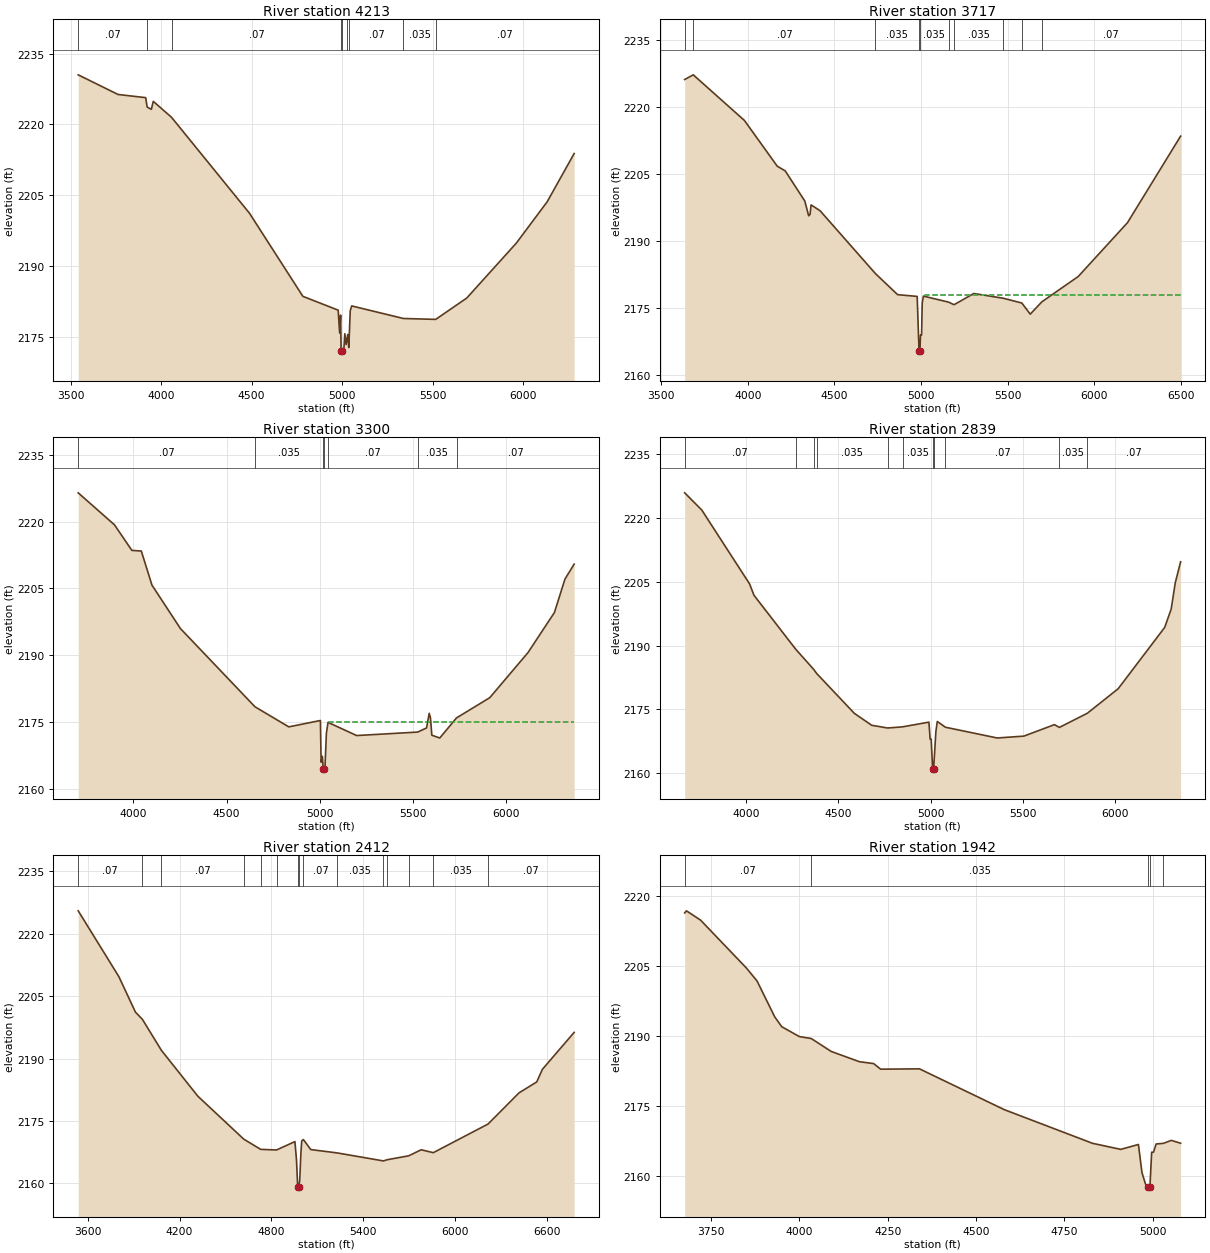
Type RM Length L Ch R = 1 ,4213    ,496,496,496
BEGIN DESCRIPTION:
UCFB HW Trib 15 8.0
END DESCRIPTION:
XS GIS Cut Line= 3
      1299695.27      6944279.21      1301065.18      6943779.35
      1302196.44      6943175.06
#Sta/Elev= 30
  3541.9 2230.51    3762 2226.35  3914.8 2225.68  3922.9 2223.69  3946.1 2223.21
  3956.8  2224.9  4057.6 2221.52  4488.6 2201.21  4783.5 2183.63  4978.7  2180.7
  4986.8 2175.85  4992.1 2179.66  4994.8 2172.11  4995.2 2171.61    5000 2172.11
  5009.6 2172.15  5015.3 2175.72  5022.6 2173.43  5029.4 2175.04  5031.6 2175.56
  5037.2 2172.78  5040.1 2175.58  5045.3 2180.59  5053.5  2181.6    5339 2178.94
  5517.6 2178.75  5689.3 2183.27  5963.3  2194.9  6133.3 2203.62  6282.7 2213.85
#Mann= 9 ,-1 , 0
  3541.9     .07       0  3922.9    .035       0  4057.6     .07       0
  4994.8     .07       0    5000     .07       0  5029.4    .035       0
  5040.1     .07       0    5339    .035       0  5517.6     .07       0
#XS Ineff= 2 , 0
       0  4992.1 2179.66  5053.5       0  2181.6
Permanent Ineff=
       F       F
Bank Sta=4994.8,5000
XS Rating Curve= 0 ,0
Exp/Cntr=0.3,0.1

Type RM Length L Ch R = 1 ,3717    ,417,417,417
BEGIN DESCRIPTION:
UCFB HW Trib 15 7.0
END DESCRIPTION:
XS GIS Cut Line= 3
      1299914.03      6944805.25        1301155.        6944238.
      1302296.33      6943266.16
#Sta/Elev= 30
  3635.8  2226.1  3685.3 2227.15  3980.6 2216.94  4170.3 2206.69  4216.3 2205.64
  4329.6 2198.88  4351.6 2195.59  4359.9 2195.89  4365.4 2198.03  4417.5 2196.72
    4737 2182.65  4865.4 2177.92  4978.3 2177.53  4988.9 2165.33  4989.3 2164.83
  4994.1 2165.33  4997.5 2168.89  5003.6 2168.89  5007.4 2176.02    5014  2177.6
  5159.8 2176.25  5191.1 2175.67    5305 2178.18  5475.1 2177.12  5582.4 2176.05
  5631.1 2173.56  5698.5 2176.33  5907.9 2181.98  6192.3 2194.03  6499.3 2213.42
#Mann= 10 ,-1 , 0
  3635.8    .035       0  3685.3     .07       0    4737    .035       0
  4988.9    .035       0  4994.1    .035       0  5159.8     .07       0
  5191.1    .035       0  5475.1     .07       0  5582.4    .035       0
  5698.5     .07       0
#XS Ineff= 2 , 0
       0                  5021.7       0 2177.78
Permanent Ineff=
       F       F
Bank Sta=4988.9,4994.1
XS Rating Curve= 0 ,0
Exp/Cntr=0.3,0.1

Type RM Length L Ch R = 1 ,3300    ,461,461,461
BEGIN DESCRIPTION:
UCFB HW Trib 15 6.0
END DESCRIPTION:
XS GIS Cut Line= 3
      1300379.96      6945213.03        1301455.        6944488.
      1302390.35      6943493.41
#Sta/Elev= 30
  3703.3 2226.47  3898.2 2219.27  3991.2 2213.55  4042.1 2213.39  4099.1 2205.75
  4251.9 2195.99  4651.9 2178.43  4833.6 2173.91  5003.4 2175.34  5007.1 2165.98
  5013.9 2167.29  5018.6 2164.47    5019 2163.97  5023.9 2164.47  5028.1 2165.06
  5035.4 2172.44  5044.1 2174.92    5198 2171.96  5525.4 2172.74  5573.1 2173.67
  5587.3 2176.95  5594.1 2175.91  5601.4 2172.04  5643.9 2171.41  5733.9 2175.92
  5912.6 2180.47  6117.7  2190.6  6259.3 2199.58    6316  2207.1  6365.3 2210.45
#Mann= 7 ,-1 , 0
  3703.3     .07       0  4651.9    .035       0  5018.6    .035       0
  5023.9    .035       0  5044.1     .07       0  5525.4    .035       0
  5733.9     .07       0
#XS Ineff= 2 , 0
       0                  5049.5       0 2175.11
Permanent Ineff=
       F       F
Bank Sta=5018.6,5023.9
XS Rating Curve= 0 ,0
Exp/Cntr=0.3,0.1

Type RM Length L Ch R = 1 ,2839    ,427,427,427
BEGIN DESCRIPTION:
UCFB HW Trib 15 5.0
END DESCRIPTION:
XS GIS Cut Line= 3
      1300529.98      6945313.01        1301755.        6944788.
      1302508.36      6943662.07
#Sta/Elev= 30
  3667.2 2225.95  3759.7 2221.91    4019 2204.51  4042.6 2201.85  4268.6 2189.16
  4365.4 2184.44  4382.7 2183.42  4586.5 2174.05  4680.8 2171.24  4767.3  2170.6
  4847.6 2170.87  4990.9 2171.98  4997.3 2167.98    5003 2167.98  5010.8 2160.95
  5011.3 2160.45  5016.1 2160.95  5028.5 2169.75  5036.1 2172.14  5080.2 2170.78
  5360.9 2168.25  5505.3 2168.69    5671 2171.39  5697.9 2170.74  5849.5 2174.08
  6016.3 2179.84  6268.5 2194.28  6303.7 2198.61  6325.6 2204.76  6354.7 2209.72
#Mann= 11 ,-1 , 0
  3667.2     .07       0  4268.6    .035       0  4365.4     .07       0
  4382.7    .035       0  4767.3     .07       0  4847.6    .035       0
  5010.8    .035       0  5016.1    .035       0  5080.2     .07       0
  5697.9    .035       0  5849.5     .07       0
#XS Ineff= 2 , 0
       0                  5036.1       0 2172.14
Permanent Ineff=
       F       F
Bank Sta=5010.8,5016.1
XS Rating Curve= 0 ,0
Exp/Cntr=0.3,0.1

Type RM Length L Ch R = 1 ,2412    ,470,470,470
BEGIN DESCRIPTION:
UCFB HW Trib 15 4.0
END DESCRIPTION:
XS GIS Cut Line= 3
      1300579.96      6945513.01        1302080.      6945097.01
      1302969.06      6943665.47
#Sta/Elev= 30
  3537.9 2225.52  3803.8 2209.69  3911.8 2201.18  3957.5 2199.43  4081.9 2191.97
    4320 2180.95  4619.9 2170.63  4730.6 2168.17  4834.2 2168.02  4954.5 2170.04
  4964.9 2165.54  4972.6 2159.11    4973 2158.61  4977.9 2159.11  4985.6 2160.58
    4994 2167.65  4999.2 2170.21  5009.6 2170.53  5058.2 2168.12  5231.6 2167.31
    5533 2165.39  5559.1 2165.69  5698.4 2166.62  5779.5 2168.07  5859.2 2167.38
    6217 2174.26  6419.5 2181.76  6535.2 2184.38  6571.9  2187.4  6779.7  2196.3
#Mann= 15 ,-1 , 0
  3537.9     .07       0  3957.5    .035       0  4081.9     .07       0
  4619.9    .035       0  4730.6     .07       0  4834.2    .035       0
  4972.6    .035       0  4977.9    .035       0  5009.6     .07       0
  5231.6    .035       0    5533     .07       0  5559.1    .035       0
  5698.4     .07       0  5859.2    .035       0    6217     .07       0
#XS Ineff= 2 , 0
       0                  5009.6       0 2170.53
Permanent Ineff=
       F       F
Bank Sta=4972.6,4977.9
XS Rating Curve= 0 ,0
Exp/Cntr=0.3,0.1

Type RM Length L Ch R = 1 ,1942    ,500,500,500
BEGIN DESCRIPTION:
UCFB HW Trib 15 3.0
END DESCRIPTION:
XS GIS Cut Line= 3
      1300680.04        6945613.        1302005.        6945588.
        1302080.      6945561.61
#Sta/Elev= 30
  3674.8 2216.38  3679.8 2216.83  3719.8 2214.84  3849.8 2204.56  3879.8 2201.79
  3929.8 2194.11  3949.8 2191.99  3999.8 2189.87  4033.3 2189.46  4089.8 2186.69
  4169.8 2184.49  4209.9 2184.09  4229.9 2182.89  4339.9 2182.96  4579.9 2174.22
    4830    2167    4910  2165.7    4960 2166.75    4970 2160.73    4980 2158.27
  4987.3 2157.68  4987.7 2157.18  4992.2 2157.18  4992.6 2157.68  4997.5 2165.09
  5002.6 2165.09  5010.2 2166.86  5030.9 2166.99    5053 2167.63  5079.5 2167.02
#Mann= 5 ,-1 , 0
  3674.8     .07       0  4033.3    .035       0  4987.3    .035       0
  4992.6    .035       0  5030.9     .07       0
Bank Sta=4987.3,4992.6
XS Rating Curve= 0 ,0
Exp/Cntr=0.3,0.1

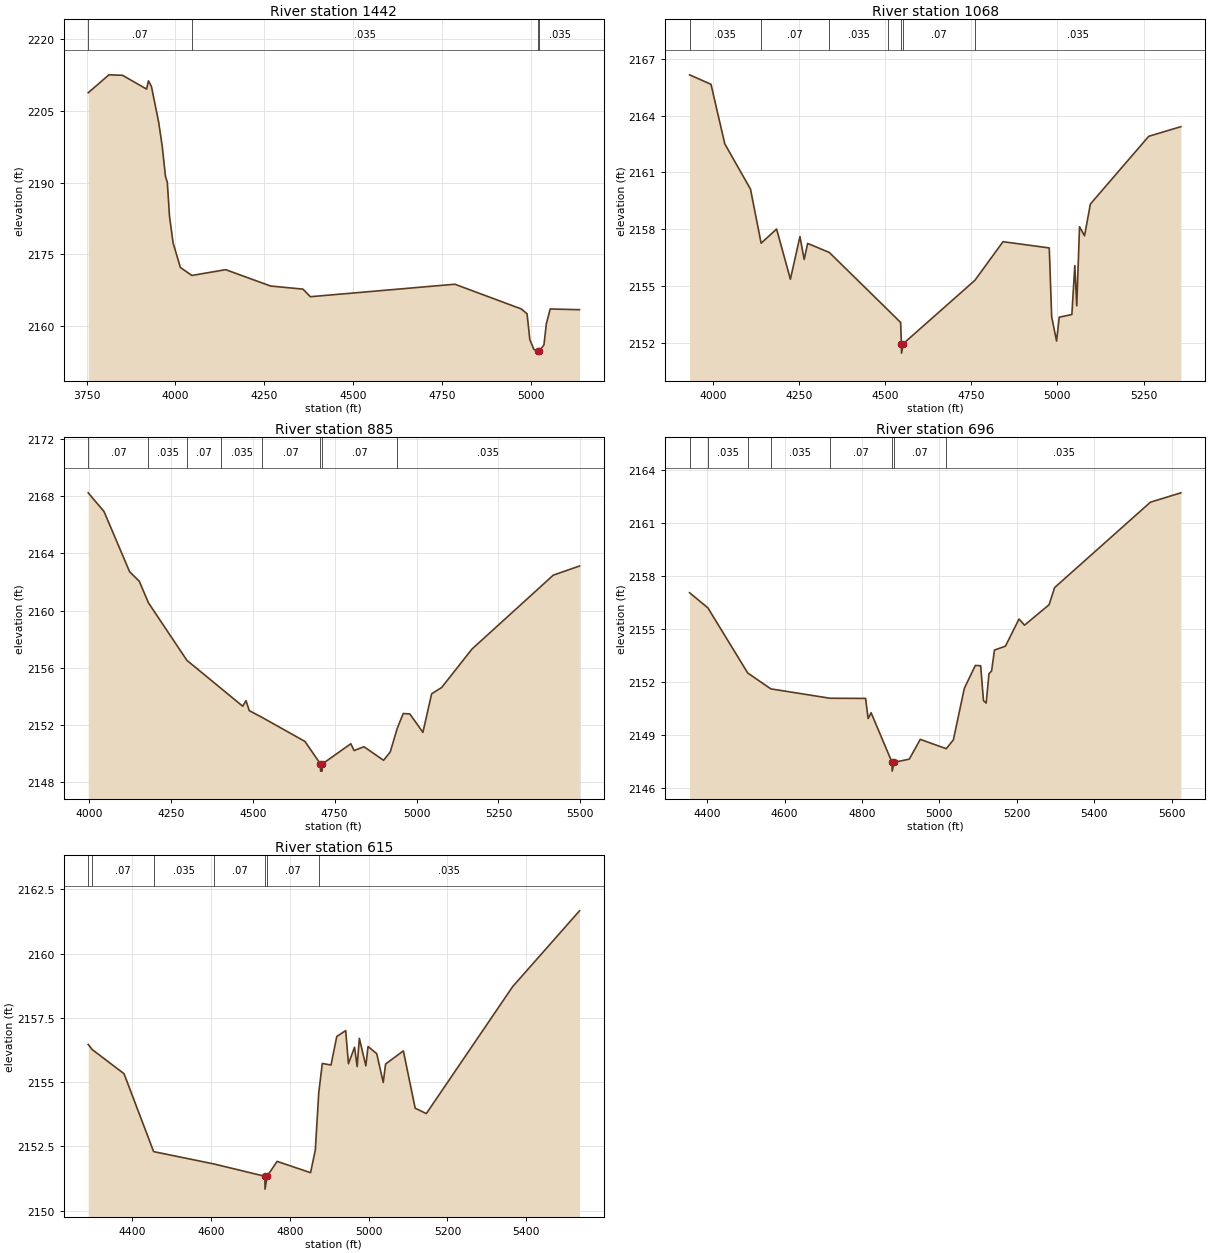
Type RM Length L Ch R = 1 ,1442    ,374,374,374
BEGIN DESCRIPTION:
UCFB HW Trib 15 2.0
END DESCRIPTION:
XS GIS Cut Line= 3
      1300779.99        6945863.        1302005.        6946088.
      1302130.02      6946030.99
#Sta/Elev= 30
  3754.5 2208.76  3812.7  2212.5  3851.1  2212.4  3918.9 2209.52    3924 2211.25
  3932.4 2210.07  3952.8 2202.61  3962.9 2197.53    3972 2191.25  3977.1 2190.07
  3983.3 2182.94  3993.4 2177.41  4013.8 2172.28  4046.2  2170.6  4141.4 2171.81
    4268 2168.39  4358.9 2167.75  4379.8 2166.16  4786.5 2168.77  4973.5 2163.61
  4989.8 2162.59  4997.5 2157.21  5008.8 2155.18  5019.3 2154.88  5019.7 2154.38
  5024.7 2154.88  5037.3  2156.1    5044 2160.49  5054.9  2163.6  5137.4 2163.45
#Mann= 4 ,-1 , 0
  3754.5     .07       0  4046.2    .035       0  5019.3    .035       0
  5024.7    .035       0
Bank Sta=5019.3,5024.7
XS Rating Curve= 0 ,0
Exp/Cntr=0.3,0.1

Type RM Length L Ch R = 1 ,1068    ,183,183,183
BEGIN DESCRIPTION:
UCFB HW Trib 15 1.5
END DESCRIPTION:
XS GIS Cut Line= 3
      1300892.93      6946381.01      1301943.94      6946452.67
      1302280.02      6946290.53
#Sta/Elev= 30
  3931.8 2166.15    3994 2165.65  4034.1  2162.5  4108.7 2160.11  4139.6 2157.25
  4184.5    2158  4224.6 2155.35  4252.3  2157.6  4264.6 2156.39  4274.7 2157.24
  4337.7 2156.76  4506.9 2153.74  4544.7 2153.06  4546.9 2151.94  4547.4 2151.44
  4552.4 2151.94  4760.4 2155.29    4842 2157.33  4976.3    2157  4983.3 2153.36
  4997.5 2152.08  5005.3 2153.34  5041.9 2153.48  5050.5 2156.07  5056.1 2153.94
  5064.2 2158.12  5078.7 2157.64  5095.7 2159.32  5265.1  2162.9  5358.4 2163.41
#Mann= 7 ,-1 , 0
  3931.8    .035       0  4139.6     .07       0  4337.7    .035       0
  4506.9     .07       0  4546.9    .035       0  4552.4     .07       0
  4760.4    .035       0
Bank Sta=4546.9,4552.4
XS Rating Curve= 0 ,0
Exp/Cntr=0.3,0.1

Type RM Length L Ch R = 1 ,885     ,189,189,189
BEGIN DESCRIPTION:
UCFB HW Trib 15 1.2
END DESCRIPTION:
XS GIS Cut Line= 4
      1300914.93      6946445.26      1301325.71      6946609.33
       1301933.2      6946607.61      1302272.64      6946312.52
#Sta/Elev= 30
  3997.9 2168.25  4046.1 2166.94  4124.2 2162.72  4153.8 2162.05  4181.7 2160.54
    4299 2156.51  4404.4 2154.52  4469.5 2153.29  4479.5 2153.68  4489.5 2152.98
  4528.4 2152.51  4659.5 2150.82  4706.8 2149.24  4707.2 2148.74  4711.8 2148.74
  4712.3 2149.24  4799.5 2150.66  4809.5 2150.18  4839.5 2150.45  4899.5  2149.5
  4919.5 2150.07  4941.3 2151.75  4959.5 2152.78  4979.5 2152.75  5019.5 2151.46
  5046.1 2154.16  5076.6  2154.6  5169.4  2157.3  5417.5 2162.48  5497.5 2163.12
#Mann= 8 ,-1 , 0
  3997.9     .07       0  4181.7    .035       0    4299     .07       0
  4404.4    .035       0  4528.4     .07       0  4706.8    .035       0
  4712.3     .07       0  4941.3    .035       0
Bank Sta=4706.8,4712.3
XS Rating Curve= 0 ,0
Exp/Cntr=0.3,0.1

Type RM Length L Ch R = 1 ,696     ,81,81,81
BEGIN DESCRIPTION:
UCFB HW Trib 15 1.1
END DESCRIPTION:
XS GIS Cut Line= 4
      1301248.76      6946936.12      1301692.44      6946909.86
      1301890.61      6946684.64      1302273.19      6946325.34
#Sta/Elev= 30
  4354.5 2157.04  4401.9 2156.18  4504.8 2152.49  4564.6 2151.59  4717.2 2151.06
  4809.3 2151.05  4815.9 2149.91  4823.5 2150.24  4877.6 2147.43    4878 2146.93
  4883.1 2147.43  4922.2 2147.61  4950.6 2148.73  5017.7  2148.2    5036  2148.7
  5064.5 2151.63  5092.9 2152.92  5106.6  2152.9  5113.9 2150.92  5120.8 2150.79
  5128.1 2152.45  5134.9 2152.61  5142.2 2153.79  5170.5 2154.01  5205.7 2155.55
  5219.9  2155.2  5283.4 2156.36  5297.6 2157.33  5545.2 2162.17  5623.8  2162.7
#Mann= 8 ,-1 , 0
  4354.5     .07       0  4401.9    .035       0  4504.8     .07       0
  4564.6    .035       0  4717.2     .07       0  4877.6     .07       0
  4883.1     .07       0  5017.7    .035       0
Bank Sta=4877.6,4883.1
XS Rating Curve= 0 ,0
Exp/Cntr=0.3,0.1

Type RM Length L Ch R = 1 ,615     ,0,0,0
BEGIN DESCRIPTION:
UCFB HW Trib 15 1.0
END DESCRIPTION:
XS GIS Cut Line= 5
      1301317.36      6946991.24      1301661.87      6947087.36
      1301820.84       6946935.9       1301932.6      6946721.06
        1302230.        6946413.
#Sta/Elev= 30
  4287.9 2156.47  4298.2 2156.27  4378.9 2155.33    4454  2152.3  4606.9 2151.82
  4736.5 2151.34  4736.9 2150.84  4742.1 2151.34  4767.6 2151.92  4852.5 2151.48
  4864.6 2152.36  4873.3 2154.59  4882.3 2155.73  4904.4 2155.67  4919.1 2156.78
  4941.7 2157.01  4948.7 2155.72  4964.2 2156.36  4970.8 2155.61  4976.4 2156.71
  4992.9 2155.64  4998.5 2156.39  5020.6 2156.11  5037.1 2154.99  5043.1 2155.71
  5088.2 2156.22  5118.2 2153.99  5146.5 2153.78  5365.7 2158.72  5535.5 2161.67
#Mann= 7 ,-1 , 0
  4287.9    .035       0  4298.2     .07       0    4454    .035       0
  4606.9     .07       0  4736.5    .035       0  4742.1     .07       0
  4873.3    .035       0
Bank Sta=4736.5,4742.1
XS Rating Curve= 0 ,0
Exp/Cntr=0.3,0.1

Chan Stop Cuts=-1
Use User Specified Reach Order=0
Composite Channel Slope=5