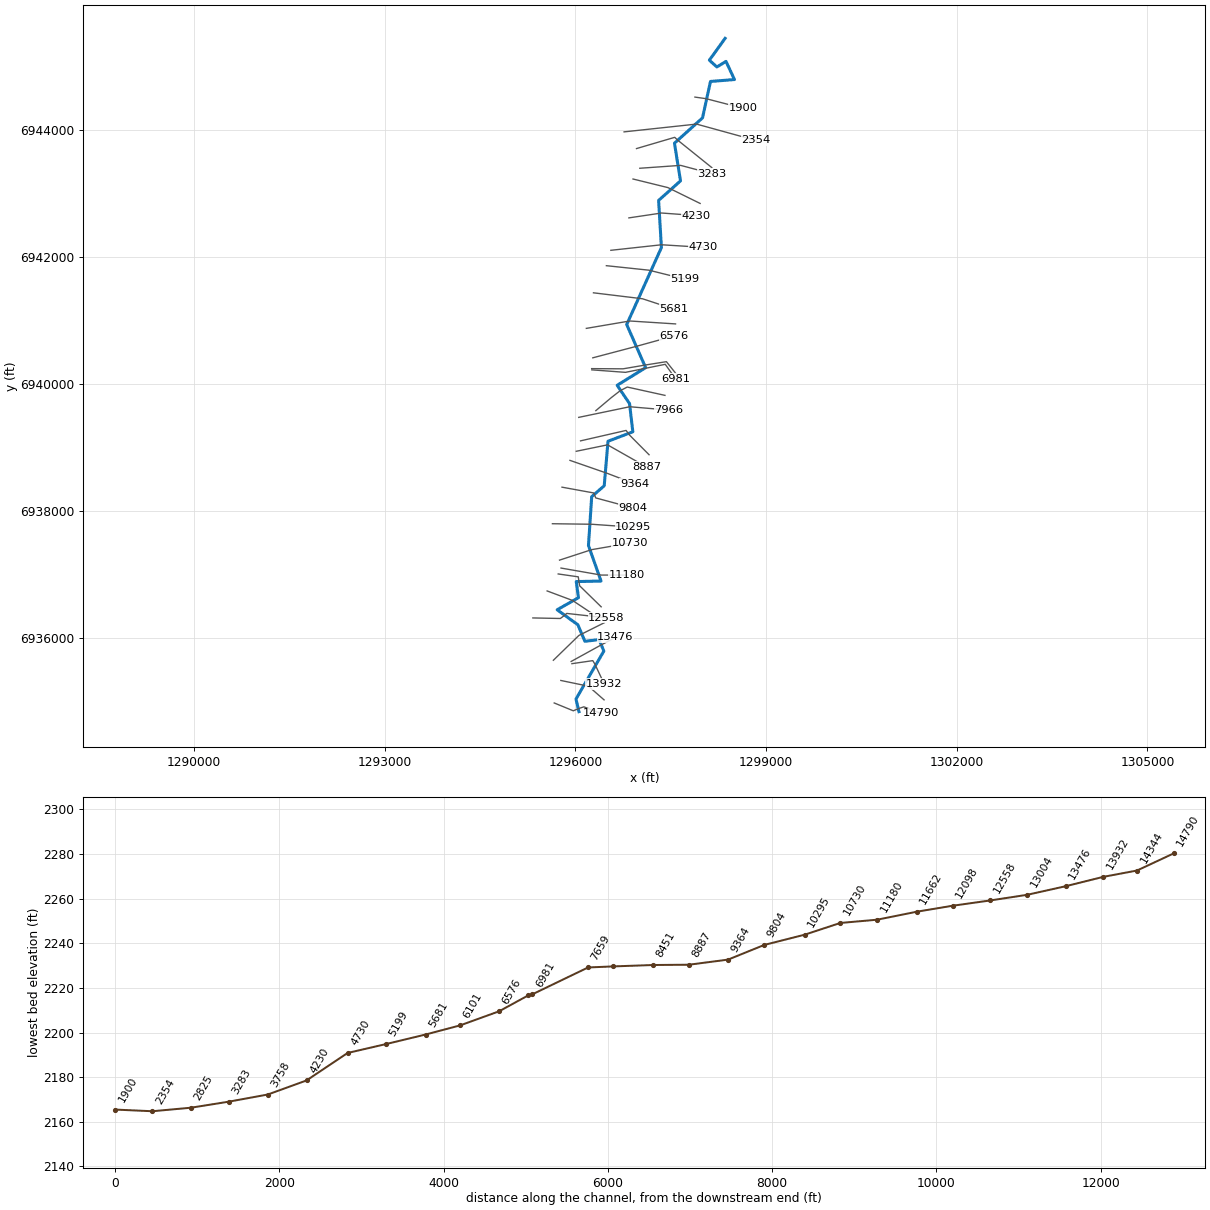
--- UCFB HW Trib 16-01.prj (project) ---

Proj Title=UCFB HW Trib 16-01 Base Level Engineering
Current Plan=p01
Default Exp/Contr=0.3,0.1
English Units
Geom File=g01
Flow File=f01
Plan File=p01
BEGIN DESCRIPTION:
UCFB HW Trib 16-01
END DESCRIPTION:

--- UCFB HW Trib 16-01.p01 (plan) ---

Plan Title=Multiple Run
Short Identifier=Multiple
Geom File=g01
Flow File=f01
Subcritical Flow
K Sum by GR= 0
Std Step Tol= 0.01
Critical Tol= 0.01
Num of Std Step Trials= 20
Max Error Tol= 0.3
Flow Tol Ratio= 0.001
Split Flow NTrial= 30
Split Flow Tol= 0.02
Split Flow Ratio= 0.02
Log Output Level= 0
Friction Slope Method= 1
Unsteady Friction Slope Method= 2
Unsteady Bridges Friction Slope Method= 1
Parabolic Critical Depth
Global Vel Dist=  1 , 1 , 1
Global Log Level= 0
CheckData=True
Encroach Param= -1, 0, 0, 0
BEGIN DESCRIPTION:
Multiple Run
END DESCRIPTION:

--- UCFB HW Trib 16-01.f01 (steady flow) ---

Flow Title=Multiple
Number of Profiles=7
Profile Names=10-year,25-year,50-year,1pct_min,100-year,1pct_plu,500-year
River Rch & RM= UCFB HW Trib 16-,Reach-1,14790
     347     502     636     400     798    1593    1276
River Rch & RM= UCFB HW Trib 16-,Reach-1,12558
     469     686     874     553    1103    2201    1782
River Rch & RM= UCFB HW Trib 16-,Reach-1,540
     476     696     887     562    1120    2235    1811
Boundary for River Rch & Prof#=UCFB HW Trib 16-,Reach-1,1
Up Type=0
Dn Type=3
Dn Slope=0.005
Boundary for River Rch & Prof#=UCFB HW Trib 16-,Reach-1,2
Up Type=0
Dn Type=3
Dn Slope=0.005
Boundary for River Rch & Prof#=UCFB HW Trib 16-,Reach-1,3
Up Type=0
Dn Type=3
Dn Slope=0.005
Boundary for River Rch & Prof#=UCFB HW Trib 16-,Reach-1,4
Up Type=0
Dn Type=3
Dn Slope=0.005
Boundary for River Rch & Prof#=UCFB HW Trib 16-,Reach-1,5
Up Type=0
Dn Type=3
Dn Slope=0.005
Boundary for River Rch & Prof#=UCFB HW Trib 16-,Reach-1,6
Up Type=0
Dn Type=3
Dn Slope=0.005
Boundary for River Rch & Prof#=UCFB HW Trib 16-,Reach-1,7
Up Type=0
Dn Type=3
Dn Slope=0.005

--- UCFB HW Trib 16-01.g01 (geometry) ---

Geom Title=Existing Conditions

River Reach=UCFB HW Trib 16-,Reach-1
Reach XY= 30
      1296055.00      6934838.00      1296008.46      6935036.51
      1296446.90      6935791.29      1296372.21      6935971.79
      1296148.92      6935945.47      1296038.72      6936205.14
      1295712.47      6936441.61      1296047.68      6936631.96
      1296013.09      6936885.53      1296403.03      6936893.65
      1296204.96      6937453.34      1296255.66      6938222.18
      1296452.76      6938393.91      1296512.35      6939094.38
      1296903.03      6939243.65      1296851.38      6939686.50
      1296656.42      6939975.85      1297104.62      6940253.15
      1296806.59      6940931.95      1297352.76      6942143.93
      1297308.53      6942886.53      1297653.02      6943193.67
      1297558.00      6943786.60      1297999.16      6944185.71
      1298124.77      6944759.03      1298501.98      6944789.39
      1298368.69      6945074.73      1298225.16      6944987.53
      1298106.95      6945093.88      1298355.00      6945438.00

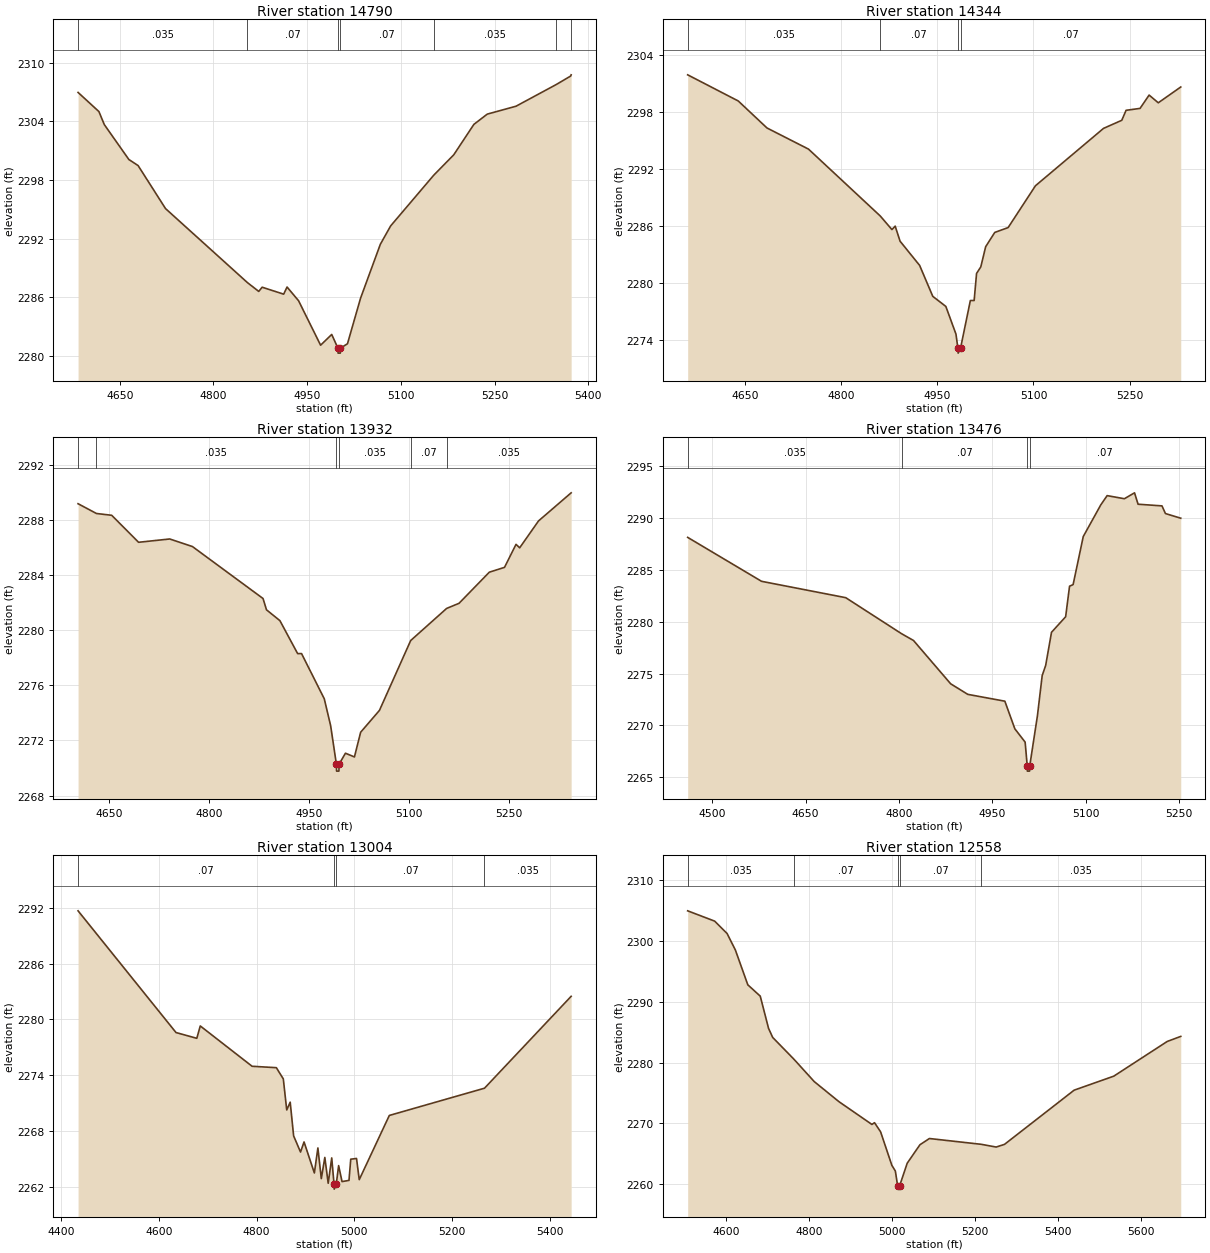
Type RM Length L Ch R = 1,14790,446,446,446
BEGIN DESCRIPTION:
UCFB HW Trib 16-01 30.0
END DESCRIPTION:
XS GIS Cut Line= 5
      1295666.14      6934974.48      1295966.28      6934851.04
      1296055.00      6934888.00      1296132.95      6934913.54
      1296400.30      6934810.50
#Sta/Elev= 30
  4583.3 2306.95  4616.7 2304.99  4625.3 2303.66  4664.6 2300.09  4679.4 2299.47
  4723.3 2295.07  4854.4 2287.50  4872.5 2286.60  4877.9 2287.03  4912.4 2286.32
  4917.8 2287.05  4936.2 2285.65  4971.5 2281.10  4989.3 2282.20  4999.2 2280.79
  4999.5 2280.29  5003.0 2280.29  5003.2 2280.79  5014.5 2281.25  5035.5 2285.92
  5067.1 2291.42  5083.6 2293.30  5152.5 2298.48  5184.6 2300.57  5216.8 2303.68
  5238.2 2304.73  5284.3 2305.54  5349.0 2307.77  5371.8 2308.63  5372.5 2308.75
#Mann=7,-1,0
  4583.3   0.035       0  4854.4    0.07       0  4999.2    0.07       0
  5003.2    0.07       0  5152.5   0.035       0  5349.0    0.07       0
  5371.8   0.035       0
Bank Sta=4999.2,5003.2
Exp/Cntr=0.3,0.1

Type RM Length L Ch R = 1,14344,412,412,412
BEGIN DESCRIPTION:
UCFB HW Trib 16-01 29.0
END DESCRIPTION:
XS GIS Cut Line= 3
      1295770.30      6935328.64      1296205.00      6935238.00
      1296450.38      6935023.30
#Sta/Elev= 30
  4559.9 2301.88  4638.9 2299.13  4683.8 2296.29  4748.6 2294.07  4860.5 2287.05
  4878.9 2285.61  4884.0 2285.97  4891.6 2284.39  4922.2 2281.84  4942.7 2278.59
  4963.1 2277.53  4978.9 2274.62  4982.0 2273.12  4982.3 2272.62  4986.0 2273.12
  5001.4 2278.15  5007.3 2278.15  5011.1 2281.00  5017.7 2281.69  5025.3 2283.81
  5039.5 2285.31  5060.4 2285.82  5103.1 2290.22  5209.4 2296.25  5237.9 2297.10
  5244.6 2298.15  5266.4 2298.35  5280.6 2299.75  5294.9 2298.94  5330.0 2300.60
#Mann=4,-1,0
  4559.9   0.035       0  4860.5    0.07       0  4982.0    0.07       0
  4986.0    0.07       0
Bank Sta=4982,4986
Exp/Cntr=0.3,0.1

Type RM Length L Ch R = 1,13932,456,456,456
BEGIN DESCRIPTION:
UCFB HW Trib 16-01 28.0
END DESCRIPTION:
XS GIS Cut Line= 4
      1295945.00      6935592.96      1296272.70      6935640.71
      1296305.00      6935588.00      1296453.17      6935273.53
#Sta/Elev= 30
  4603.1 2289.18  4630.7 2288.47  4653.6 2288.34  4694.0 2286.38  4740.8 2286.62
  4774.9 2286.07  4880.9 2282.30  4886.1 2281.48  4906.3 2280.69  4932.9 2278.30
  4938.8 2278.30  4972.9 2275.02  4982.5 2273.06  4991.1 2270.27  4991.4 2269.77
  4994.9 2269.77  4995.1 2270.27  5004.7 2271.07  5018.2 2270.80  5027.5 2272.59
  5055.8 2274.18  5102.7 2279.25  5156.7 2281.58  5175.3 2281.95  5220.8 2284.21
  5243.6 2284.56  5260.9 2286.23  5266.4 2285.98  5294.7 2287.93  5343.7 2289.97
#Mann=6,-1,0
  4603.1    0.07       0  4630.7   0.035       0  4991.1   0.035       0
  4995.1   0.035       0  5102.7    0.07       0  5156.7   0.035       0
Bank Sta=4991.1,4995.1
Exp/Cntr=0.3,0.1

Type RM Length L Ch R = 1,13476,472,472,472
BEGIN DESCRIPTION:
UCFB HW Trib 16-01 27.0
END DESCRIPTION:
XS GIS Cut Line= 3
      1295932.46      6935627.69      1296405.00      6935888.00
      1296628.61      6936006.14
#Sta/Elev= 30
  4460.4 2288.15  4579.1 2283.91  4714.4 2282.33  4804.2 2278.85  4823.3 2278.20
  4883.0 2274.02  4910.5 2273.00  4970.1 2272.34  4986.2 2269.67  5002.7 2268.39
  5006.1 2266.09  5006.3 2265.59  5009.8 2265.59  5010.1 2266.09  5022.5 2270.95
  5030.1 2274.81  5035.7 2275.79  5045.1 2278.99  5067.8 2280.49  5074.1 2283.44
  5079.8 2283.59  5096.1 2288.23  5124.3 2291.29  5134.5 2292.18  5162.2 2291.88
  5178.5 2292.45  5184.2 2291.35  5222.6 2291.19  5228.2 2290.45  5252.8 2290.00
#Mann=4,-1,0
  4460.4   0.035       0  4804.2    0.07       0  5006.1    0.07       0
  5010.1    0.07       0
Bank Sta=5006.1,5010.1
Exp/Cntr=0.3,0.1

Type RM Length L Ch R = 1,13004,446,446,446
BEGIN DESCRIPTION:
UCFB HW Trib 16-01 26.0
END DESCRIPTION:
XS GIS Cut Line= 3
      1295652.89      6935646.75      1296055.00      6936038.00
      1296455.04      6936238.02
#Sta/Elev= 30
  4435.1 2291.67  4635.4 2278.57  4677.9 2277.95  4685.0 2279.28  4791.0 2274.94
  4840.6 2274.79  4854.8 2273.58  4861.8 2270.24  4868.9 2271.08  4875.9 2267.45
  4890.0 2265.71  4897.2 2266.80  4918.3 2263.46  4925.5 2266.15  4932.5 2262.85
  4939.7 2265.13  4946.6 2262.35  4953.8 2265.08  4958.6 2262.22  4958.9 2261.72
  4963.0 2262.22  4967.9 2264.25  4974.9 2262.53  4989.1 2262.66  4992.7 2264.94
  5004.5 2265.02  5010.1 2262.74  5071.6 2269.65  5266.2 2272.58  5443.4 2282.47
#Mann=4,-1,0
  4435.1    0.07       0  4958.6    0.07       0  4963.0    0.07       0
  5266.2   0.035       0
Bank Sta=4958.6,4963
Exp/Cntr=0.3,0.1

Type RM Length L Ch R = 1,12558,460,460,460
BEGIN DESCRIPTION:
UCFB HW Trib 16-01 25.0
END DESCRIPTION:
XS GIS Cut Line= 5
      1295330.03      6936313.00      1295761.87      6936304.30
      1295811.03      6936340.53      1295863.26      6936384.16
      1296487.36      6936314.80
#Sta/Elev= 30
  4507.0 2304.91  4572.0 2303.22  4602.0 2301.19  4622.0 2298.48  4652.0 2292.76
  4682.0 2290.90  4702.0 2285.61  4712.0 2284.12  4763.4 2280.53  4812.0 2276.88
  4872.0 2273.56  4951.3 2269.83  4957.5 2270.12  4972.2 2268.62  4999.4 2263.11
  5007.8 2262.18  5013.4 2259.71  5013.7 2259.21  5017.5 2259.21  5017.8 2259.71
  5036.4 2263.47  5067.1 2266.50  5089.9 2267.52  5214.8 2266.57  5250.9 2266.12
  5271.0 2266.56  5438.9 2275.46  5534.5 2277.76  5663.4 2283.46  5696.0 2284.29
#Mann=5,-1,0
  4507.0   0.035       0  4763.4    0.07       0  5013.4    0.07       0
  5017.8    0.07       0  5214.8   0.035       0
Bank Sta=5013.4,5017.8
Exp/Cntr=0.3,0.1

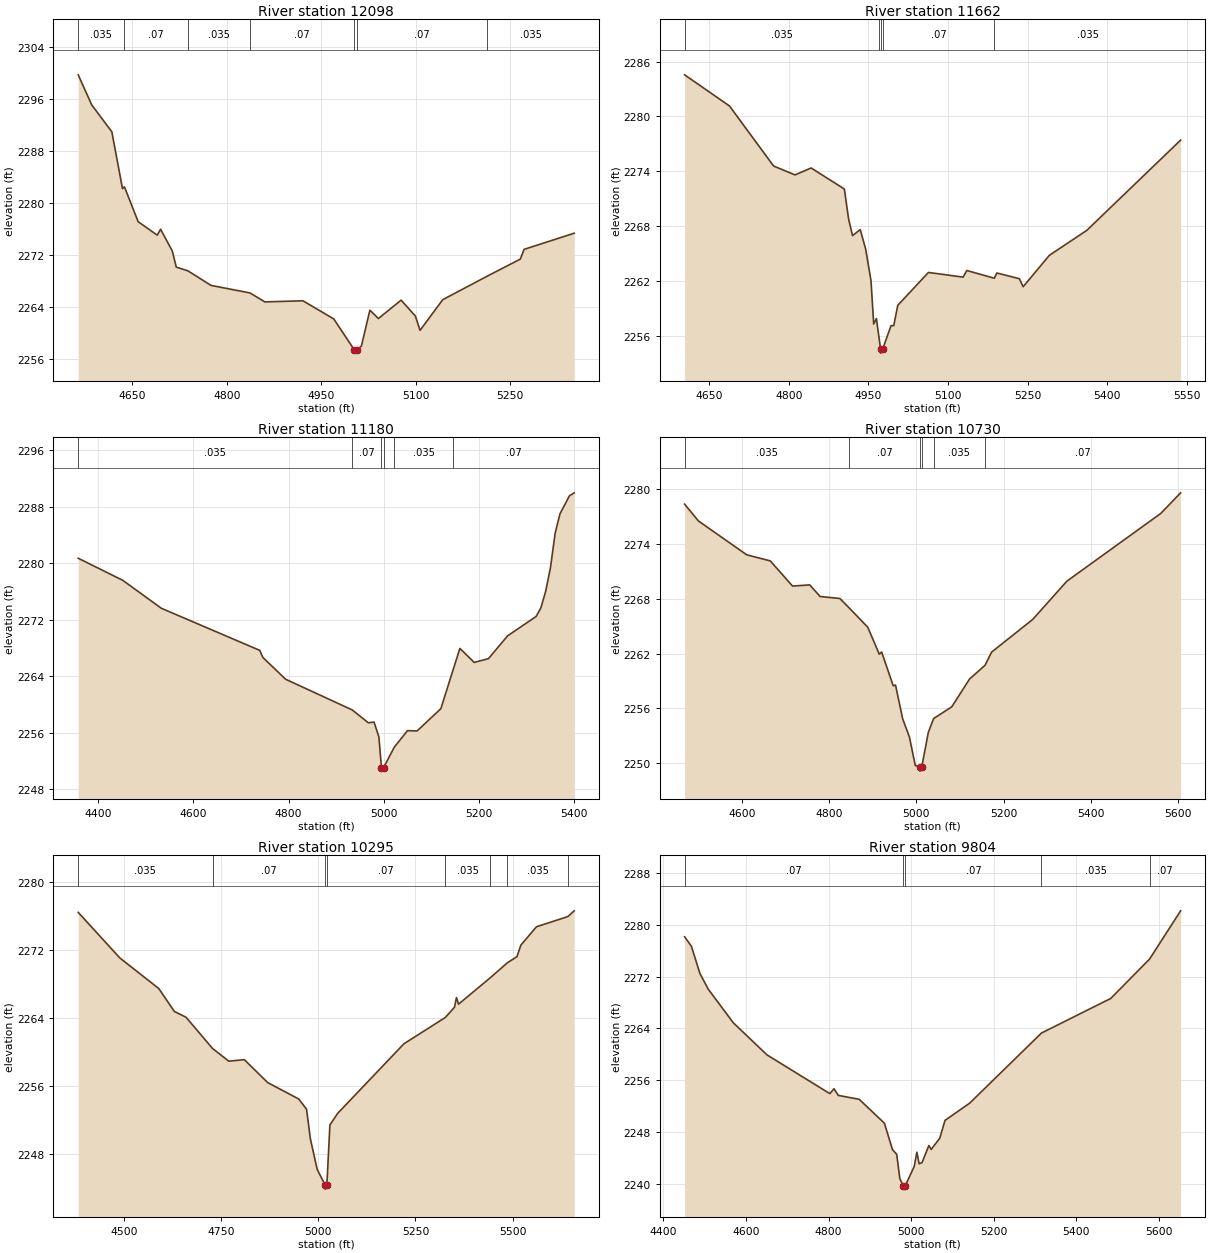
Type RM Length L Ch R = 1,12098,436,436,436
BEGIN DESCRIPTION:
UCFB HW Trib 16-01 24.0
END DESCRIPTION:
XS GIS Cut Line= 3
      1295555.01      6936738.00      1295955.00      6936588.00
      1296254.96      6936388.03
#Sta/Elev= 30
  4564.0 2299.69  4585.4 2295.07  4617.4 2290.92  4634.3 2282.17  4637.4 2282.44
  4659.2 2277.07  4689.5 2275.00  4694.8 2275.91  4713.5 2272.54  4719.7 2270.08
  4738.5 2269.49  4774.9 2267.26  4836.8 2266.10  4860.4 2264.72  4920.9 2264.89
  4969.8 2262.10  5002.5 2257.33  5002.8 2256.83  5006.9 2257.33  5013.7 2257.92
  5027.2 2263.44  5040.8 2262.16  5076.8 2264.99  5099.4 2262.55  5106.9 2260.34
  5142.9 2265.06  5213.9 2268.70  5266.1 2271.31  5272.1 2272.81  5351.7 2275.30
#Mann=7,-1,0
  4564.0   0.035       0  4637.4    0.07       0  4738.5   0.035       0
  4836.8    0.07       0  5002.5    0.07       0  5006.9    0.07       0
  5213.9   0.035       0
Bank Sta=5002.5,5006.9
Exp/Cntr=0.3,0.1

Type RM Length L Ch R = 1,11662,482,482,482
BEGIN DESCRIPTION:
UCFB HW Trib 16-01 23.0
END DESCRIPTION:
XS GIS Cut Line= 5
      1295728.92      6937005.41      1296044.65      6936960.06
      1296055.00      6936888.00      1296066.35      6936819.00
      1296404.97      6936488.03
#Sta/Elev= 30
  4603.5 2284.55  4688.1 2281.15  4771.3 2274.59  4811.7 2273.62  4842.0 2274.38
  4904.7 2272.08  4912.7 2268.80  4920.1 2266.99  4934.6 2267.65  4944.8 2265.54
  4954.9 2262.08  4960.0 2257.34  4965.1 2257.94  4969.5 2256.09  4972.9 2254.66
  4973.2 2254.16  4977.3 2254.66  4992.7 2257.16  4997.8 2257.16  5005.4 2259.38
  5063.2 2262.97  5128.6 2262.46  5135.6 2263.18  5187.4 2262.34  5192.2 2262.91
  5234.6 2262.29  5241.8 2261.41  5291.2 2264.84  5361.9 2267.57  5538.7 2277.42
#Mann=5,-1,0
  4603.5   0.035       0  4969.5    0.07       0  4972.9    0.07       0
  4977.3    0.07       0  5187.4   0.035       0
Bank Sta=4972.9,4977.3
Exp/Cntr=0.3,0.1

Type RM Length L Ch R = 1,11180,450,450,450
BEGIN DESCRIPTION:
UCFB HW Trib 16-01 22.0
END DESCRIPTION:
XS GIS Cut Line= 3
      1295773.11      6937098.31      1296405.00      6936988.00
      1296804.96      6936988.00
#Sta/Elev= 30
  4358.4 2280.71  4452.1 2277.58  4532.9 2273.63  4739.6 2267.67  4746.1 2266.67
  4794.0 2263.58  4933.8 2259.24  4967.5 2257.42  4979.5 2257.53  4989.7 2255.42
  4995.1 2251.08  4995.4 2250.58  4999.6 2251.08  5022.0 2253.97  5049.8 2256.31
  5069.8 2256.26  5119.8 2259.42  5146.1 2265.04  5159.8 2267.95  5189.8 2265.97
  5219.8 2266.50  5259.8 2269.72  5319.8 2272.47  5329.8 2273.69  5339.8 2276.01
  5349.8 2279.32  5359.8 2284.26  5369.8 2286.98  5389.8 2289.55  5399.8 2289.97
#Mann=6,-1,0
  4358.4   0.035       0  4933.8    0.07       0  4995.1    0.07       0
  4999.6    0.07       0  5022.0   0.035       0  5146.1    0.07       0
Bank Sta=4995.1,4999.6
Exp/Cntr=0.3,0.1

Type RM Length L Ch R = 1,10730,435,435,435
BEGIN DESCRIPTION:
UCFB HW Trib 16-01 21.0
END DESCRIPTION:
XS GIS Cut Line= 3
      1295749.73      6937223.30      1296255.00      6937388.00
      1296851.91      6937491.18
#Sta/Elev= 30
  4468.6 2278.37  4500.2 2276.53  4610.9 2272.82  4665.0 2272.15  4716.1 2269.39
  4755.5 2269.52  4779.2 2268.25  4824.5 2268.03  4845.4 2267.02  4888.4 2264.89
  4915.0 2261.92  4920.3 2262.17  4946.9 2258.46  4952.2 2258.54  4968.5 2254.85
  4984.1 2252.84  4997.4 2249.73  5007.9 2249.61  5008.2 2249.11  5012.4 2249.61
  5027.4 2253.36  5039.5 2254.87  5081.2 2256.16  5121.8 2259.20  5157.2 2260.70
  5172.6 2262.16  5266.6 2265.73  5345.1 2269.93  5560.5 2277.36  5605.8 2279.61
#Mann=6,-1,0
  4468.6   0.035       0  4845.4    0.07       0  5007.9    0.07       0
  5012.4    0.07       0  5039.5   0.035       0  5157.2    0.07       0
Bank Sta=5007.9,5012.4
Exp/Cntr=0.3,0.1

Type RM Length L Ch R = 1,10295,491,491,491
BEGIN DESCRIPTION:
UCFB HW Trib 16-01 20.0
END DESCRIPTION:
XS GIS Cut Line= 3
      1295637.76      6937796.21      1296255.00      6937788.00
      1296911.88      6937741.66
#Sta/Elev= 30
  4382.7 2276.46  4489.9 2271.08  4590.0 2267.48  4630.0 2264.78  4660.0 2264.10
  4728.2 2260.42  4770.0 2258.92  4810.0 2259.10  4870.0 2256.40  4950.0 2254.46
  4970.0 2253.26  4980.0 2249.74  4997.5 2246.15  5017.7 2244.34  5018.0 2243.84
  5022.3 2244.34  5030.1 2251.40  5050.1 2252.77  5220.5 2260.97  5327.2 2264.08
  5350.6 2265.28  5355.6 2266.43  5360.9 2265.64  5443.1 2268.77  5486.6 2270.52
  5511.3 2271.24  5521.3 2272.60  5561.4 2274.76  5642.0 2275.96  5658.5 2276.64
#Mann=8,-1,0
  4382.7   0.035       0  4728.2    0.07       0  5017.7    0.07       0
  5022.3    0.07       0  5327.2   0.035       0  5443.1    0.07       0
  5486.6   0.035       0  5642.0    0.07       0
Bank Sta=5017.7,5022.3
Exp/Cntr=0.3,0.1

Type RM Length L Ch R = 1,9804,440,440,440
BEGIN DESCRIPTION:
UCFB HW Trib 16-01 19.0
END DESCRIPTION:
XS GIS Cut Line= 5
      1295788.77      6938371.74      1296288.65      6938280.50
      1296305.00      6938238.00      1296319.90      6938202.38
      1296908.58      6938043.61
#Sta/Elev= 30
  4451.2 2278.12  4467.7 2276.66  4488.0 2272.52  4508.4 2270.06  4569.3 2264.87
  4650.7 2259.94  4803.1 2253.97  4813.3 2254.73  4823.5 2253.70  4874.3 2253.09
  4935.3 2249.42  4954.9 2245.35  4965.2 2244.62  4972.7 2240.90  4981.1 2239.76
  4981.4 2239.26  4985.8 2239.76  5007.6 2242.75  5014.1 2244.95  5019.5 2243.16
  5026.6 2243.34  5043.1 2245.98  5048.8 2245.37  5069.5 2247.10  5082.3 2249.85
  5142.0 2252.50  5316.0 2263.30  5483.8 2268.62  5578.1 2274.70  5653.2 2282.12
#Mann=5,-1,0
  4451.2    0.07       0  4981.1    0.07       0  4985.8    0.07       0
  5316.0   0.035       0  5578.1    0.07       0
Bank Sta=4981.1,4985.8
Exp/Cntr=0.3,0.1

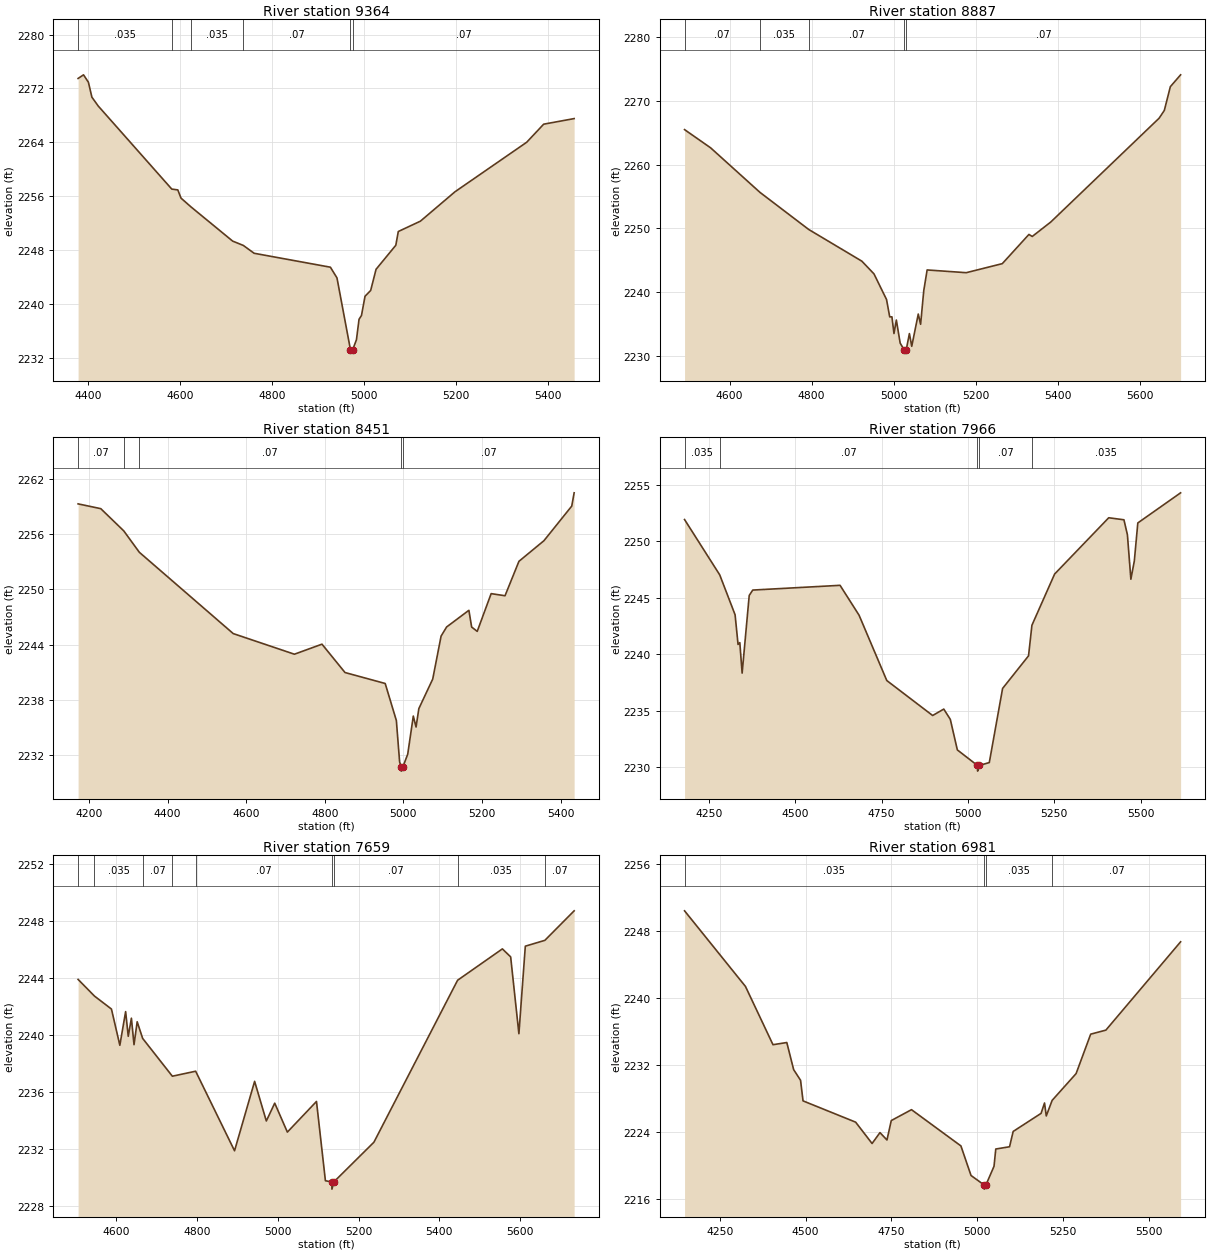
Type RM Length L Ch R = 1,9364,477,477,477
BEGIN DESCRIPTION:
UCFB HW Trib 16-01 18.0
END DESCRIPTION:
XS GIS Cut Line= 3
      1295913.83      6938793.59      1296505.00      6938588.00
      1296926.81      6938426.42
#Sta/Elev= 30
  4378.3 2273.48  4390.1 2274.02  4400.7 2272.92  4408.3 2270.70  4421.9 2269.40
  4581.8 2257.05  4594.9 2256.93  4601.9 2255.71  4623.5 2254.41  4714.0 2249.33
  4737.3 2248.68  4760.7 2247.52  4926.4 2245.45  4940.7 2243.86  4970.0 2233.19
  4970.4 2232.69  4974.8 2233.19  4983.0 2234.68  4988.6 2237.71  4993.9 2238.28
  5001.6 2241.13  5013.9 2242.00  5025.6 2245.14  5068.5 2248.71  5073.9 2250.75
  5122.0 2252.29  5197.0 2256.65  5352.9 2264.01  5389.7 2266.69  5455.9 2267.52
#Mann=6,-1,0
  4378.3   0.035       0  4581.8    0.07       0  4623.5   0.035       0
  4737.3    0.07       0  4970.0    0.07       0  4974.8    0.07       0
Bank Sta=4970,4974.8
Exp/Cntr=0.3,0.1

Type RM Length L Ch R = 1,8887,436,436,436
BEGIN DESCRIPTION:
UCFB HW Trib 16-01 17.0
END DESCRIPTION:
XS GIS Cut Line= 3
      1296012.78      6938936.85      1296505.00      6939038.00
      1297119.52      6938689.44
#Sta/Elev= 30
  4490.3 2265.52  4553.8 2262.66  4674.1 2255.66  4792.9 2249.83  4922.4 2244.85
  4952.0 2242.85  4982.6 2238.82  4990.3 2236.10  4995.7 2236.10  5000.7 2233.48
  5006.5 2235.60  5015.8 2231.97  5025.7 2230.90  5026.1 2230.40  5030.5 2230.90
  5038.3 2233.47  5044.0 2231.47  5059.9 2236.54  5065.6 2234.93  5073.3 2240.22
  5081.5 2243.47  5176.8 2243.04  5264.7 2244.46  5329.6 2249.05  5337.7 2248.73
  5383.0 2251.01  5647.0 2267.32  5659.6 2268.54  5674.3 2272.27  5699.3 2274.13
#Mann=5,-1,0
  4490.3    0.07       0  4674.1   0.035       0  4792.9    0.07       0
  5025.7    0.07       0  5030.5    0.07       0
Bank Sta=5025.7,5030.5
Exp/Cntr=0.3,0.1

Type RM Length L Ch R = 1,8451,485,485,485
BEGIN DESCRIPTION:
UCFB HW Trib 16-01 16.0
END DESCRIPTION:
XS GIS Cut Line= 4
      1296080.41      6939100.89      1296796.60      6939264.96
      1296855.00      6939188.00      1297158.16      6938882.57
#Sta/Elev= 30
  4172.5 2259.30  4230.2 2258.78  4288.6 2256.37  4328.3 2254.04  4567.1 2245.21
  4722.7 2242.97  4792.8 2244.06  4851.4 2240.98  4953.6 2239.79  4982.0 2235.77
  4990.3 2231.27  4994.1 2230.77  4994.5 2230.27  4999.0 2230.77  5010.9 2232.11
  5025.1 2236.25  5032.1 2235.06  5039.2 2237.06  5074.5 2240.27  5095.8 2244.94
  5109.9 2245.93  5166.5 2247.74  5173.5 2245.92  5187.7 2245.45  5223.1 2249.55
  5258.4 2249.32  5293.8 2253.06  5357.4 2255.30  5428.1 2259.06  5434.2 2260.50
#Mann=5,-1,0
  4172.5    0.07       0  4288.6   0.035       0  4328.3    0.07       0
  4994.1    0.07       0  4999.0    0.07       0
Bank Sta=4994.1,4999
Exp/Cntr=0.3,0.1

Type RM Length L Ch R = 1,7966,307,307,307
BEGIN DESCRIPTION:
UCFB HW Trib 16-01 15.0
END DESCRIPTION:
XS GIS Cut Line= 3
      1296051.78      6939470.69      1296855.00      6939638.00
      1297468.48      6939585.28
#Sta/Elev= 30
  4179.5 2251.94  4281.3 2247.04  4325.8 2243.50  4334.4 2240.87  4339.5 2241.03
  4346.2 2238.33  4366.7 2245.21  4376.9 2245.69  4629.7 2246.11  4684.8 2243.46
  4765.0 2237.67  4897.8 2234.57  4930.0 2235.14  4948.9 2234.23  4969.3 2231.52
  5027.6 2230.14  5028.0 2229.64  5032.5 2230.14  5061.8 2230.40  5100.3 2236.97
  5175.4 2239.86  5185.2 2242.57  5250.9 2247.11  5407.6 2252.10  5451.6 2251.92
  5461.7 2250.59  5471.7 2246.65  5481.7 2248.27  5491.8 2251.64  5615.7 2254.31
#Mann=5,-1,0
  4179.5   0.035       0  4281.3    0.07       0  5027.6    0.07       0
  5032.5    0.07       0  5185.2   0.035       0
Bank Sta=5027.6,5032.5
Exp/Cntr=0.3,0.1

Type RM Length L Ch R = 1,7659,678,678,678
BEGIN DESCRIPTION:
UCFB HW Trib 16-01 14.0
END DESCRIPTION:
XS GIS Cut Line= 5
      1296320.77      6939576.50      1296563.80      6939781.34
      1296704.42      6939890.71      1296815.53      6939948.00
      1297408.55      6939817.05
#Sta/Elev= 30
  4505.6 2243.88  4546.2 2242.71  4588.2 2241.80  4609.0 2239.26  4623.3 2241.62
  4629.8 2239.89  4637.6 2241.16  4644.1 2239.30  4651.9 2240.91  4665.5 2239.74
  4739.0 2237.09  4796.7 2237.44  4893.0 2231.86  4942.7 2236.73  4971.7 2233.95
  4992.5 2235.20  5023.8 2233.17  5095.9 2235.32  5118.0 2229.76  5133.8 2229.67
  5134.2 2229.17  5138.7 2229.67  5238.1 2232.46  5445.3 2243.82  5556.2 2246.02
  5576.7 2245.46  5597.1 2240.07  5613.0 2246.21  5661.4 2246.62  5733.9 2248.69
#Mann=9,-1,0
  4505.6    0.07       0  4546.2   0.035       0  4665.5    0.07       0
  4739.0   0.035       0  4796.7    0.07       0  5133.8    0.07       0
  5138.7    0.07       0  5445.3   0.035       0  5661.4    0.07       0
Bank Sta=5133.8,5138.7
Exp/Cntr=0.3,0.1

Type RM Length L Ch R = 1,6981,53,53,53
BEGIN DESCRIPTION:
UCFB HW Trib 16-01 13.2
END DESCRIPTION:
XS GIS Cut Line= 4
      1296258.06      6940218.70      1296787.41      6940179.43
      1297412.95      6940305.90      1297573.59      6940081.59
#Sta/Elev= 30
  4147.5 2250.39  4324.9 2241.36  4405.1 2234.40  4445.3 2234.66  4465.3 2231.42
  4485.4 2230.15  4492.6 2227.69  4645.8 2225.15  4693.7 2222.60  4716.7 2223.90
  4737.1 2223.02  4749.6 2225.34  4808.5 2226.64  4952.5 2222.31  4981.9 2218.78
  5020.1 2217.65  5020.5 2217.15  5025.4 2217.65  5048.9 2219.88  5054.0 2221.94
  5094.1 2222.21  5104.7 2224.04  5186.0 2226.20  5196.0 2227.44  5201.1 2225.89
  5218.2 2227.75  5288.0 2230.95  5330.5 2235.66  5374.7 2236.14  5592.4 2246.69
#Mann=4,-1,0
  4147.5   0.035       0  5020.1   0.035       0  5025.4   0.035       0
  5218.2    0.07       0
Bank Sta=5020.1,5025.4
Exp/Cntr=0.3,0.1

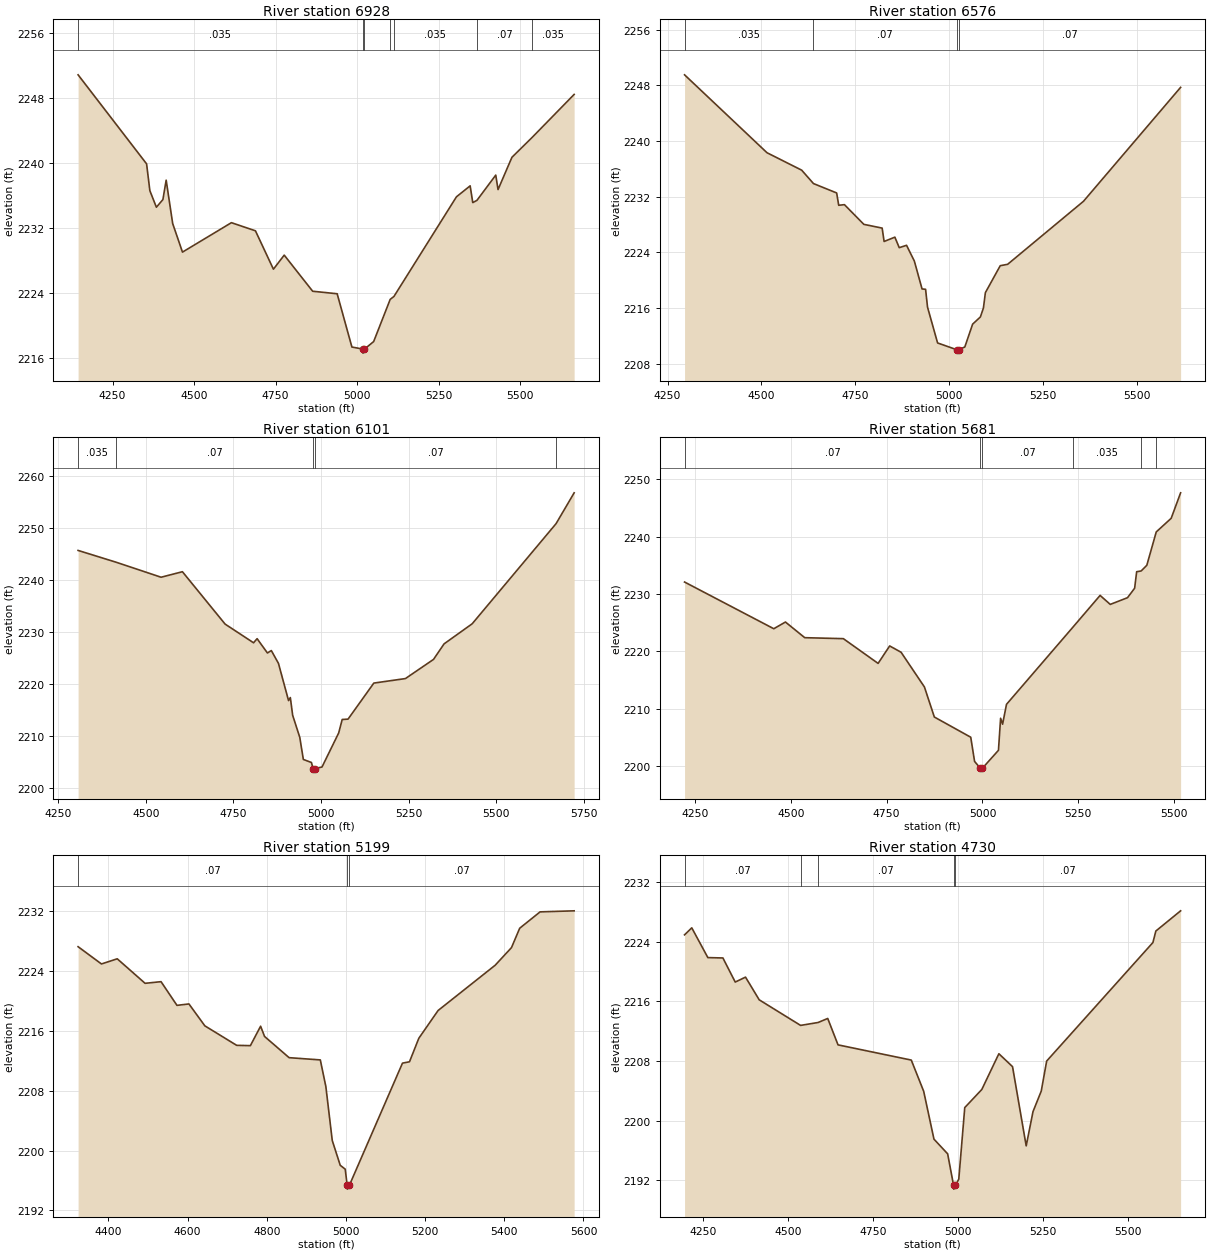
Type RM Length L Ch R = 1,6928,352,352,352
BEGIN DESCRIPTION:
UCFB HW Trib 16-01 13.0
END DESCRIPTION:
XS GIS Cut Line= 5
      1296255.05      6940238.00      1296749.21      6940234.99
      1297105.12      6940295.75      1297431.32      6940347.66
      1297640.16      6940085.51
#Sta/Elev= 30
  4144.5 2250.83  4354.5 2239.88  4364.5 2236.59  4384.5 2234.55  4404.5 2235.49
  4414.5 2237.88  4434.5 2232.54  4464.5 2229.03  4614.5 2232.65  4688.2 2231.65
  4743.3 2226.93  4776.4 2228.66  4863.6 2224.22  4938.7 2223.91  4983.9 2217.36
  5017.2 2217.11  5017.7 2216.61  5022.5 2217.11  5050.6 2218.03  5101.3 2223.22
  5112.8 2223.58  5304.4 2235.83  5346.4 2237.18  5354.4 2235.12  5367.1 2235.39
  5424.9 2238.50  5431.9 2236.72  5474.5 2240.69  5535.6 2243.10  5665.2 2248.42
#Mann=7,-1,0
  4144.5   0.035       0  5017.2   0.035       0  5022.5   0.035       0
  5101.3    0.07       0  5112.8   0.035       0  5367.1    0.07       0
  5535.6   0.035       0
Bank Sta=5017.2,5022.5
Exp/Cntr=0.3,0.1

Type RM Length L Ch R = 1,6576,475,475,475
BEGIN DESCRIPTION:
UCFB HW Trib 16-01 12.0
END DESCRIPTION:
XS GIS Cut Line= 3
      1296273.18      6940408.20      1296955.00      6940588.00
      1297549.17      6940751.93
#Sta/Elev= 30
  4295.2 2249.51  4514.8 2238.32  4607.3 2235.81  4638.6 2233.89  4700.4 2232.54
  4705.9 2230.77  4721.1 2230.86  4772.8 2228.03  4821.6 2227.49  4826.8 2225.57
  4855.5 2226.19  4867.1 2224.68  4886.6 2225.02  4907.4 2222.75  4927.9 2218.75
  4937.3 2218.70  4942.5 2216.13  4969.3 2210.99  5020.0 2210.03  5020.4 2209.53
  5025.3 2210.03  5041.8 2210.41  5062.6 2213.69  5083.3 2214.73  5091.4 2216.01
  5096.6 2218.22  5136.2 2222.09  5155.9 2222.29  5357.9 2231.34  5616.7 2247.71
#Mann=4,-1,0
  4295.2   0.035       0  4638.6    0.07       0  5020.0    0.07       0
  5025.3    0.07       0
Bank Sta=5020,5025.3
Exp/Cntr=0.3,0.1

Type RM Length L Ch R = 1,6101,420,420,420
BEGIN DESCRIPTION:
UCFB HW Trib 16-01 11.0
END DESCRIPTION:
XS GIS Cut Line= 3
      1296171.63      6940871.74      1296855.00      6940988.00
      1297575.25      6940942.05
#Sta/Elev= 30
  4306.9 2245.70  4414.4 2243.45  4543.6 2240.54  4604.5 2241.60  4726.2 2231.52
  4807.4 2227.92  4817.5 2228.71  4846.9 2225.96  4858.1 2226.42  4878.4 2223.96
  4907.2 2216.79  4912.3 2217.37  4918.9 2213.97  4939.2 2209.72  4949.4 2205.46
  4972.5 2204.87  4977.1 2203.71  4977.6 2203.21  4982.5 2203.71  5002.6 2204.00
  5050.2 2210.56  5060.2 2213.15  5076.9 2213.22  5150.4 2220.16  5240.6 2221.03
  5320.7 2224.72  5350.8 2227.71  5431.0 2231.58  5670.3 2250.86  5721.8 2256.79
#Mann=5,-1,0
  4306.9   0.035       0  4414.4    0.07       0  4977.1    0.07       0
  4982.5    0.07       0  5670.3   0.035       0
Bank Sta=4977.1,4982.5
Exp/Cntr=0.3,0.1

Type RM Length L Ch R = 1,5681,482,482,482
BEGIN DESCRIPTION:
UCFB HW Trib 16-01 10.0
END DESCRIPTION:
XS GIS Cut Line= 3
      1296283.58      6941431.63      1297055.00      6941338.00
      1297546.64      6941176.41
#Sta/Elev= 30
  4222.5 2232.08  4455.4 2223.94  4485.8 2225.11  4536.2 2222.38  4636.9 2222.21
  4727.6 2217.90  4757.8 2220.94  4787.6 2219.84  4848.5 2213.79  4874.4 2208.55
  4969.4 2205.03  4979.4 2200.81  4994.4 2199.62  4994.8 2199.12  4999.8 2199.62
  5041.7 2202.75  5047.3 2208.34  5052.5 2207.30  5062.7 2210.76  5235.5 2224.17
  5307.0 2229.75  5333.5 2228.18  5378.5 2229.35  5397.1 2231.00  5402.4 2233.88
  5414.2 2234.01  5428.9 2235.00  5453.5 2240.81  5492.5 2243.19  5517.1 2247.63
#Mann=6,-1,0
  4222.5    0.07       0  4994.4    0.07       0  4999.8    0.07       0
  5235.5   0.035       0  5414.2    0.07       0  5453.5   0.035       0
Bank Sta=4994.4,4999.8
Exp/Cntr=0.3,0.1

Type RM Length L Ch R = 1,5199,469,469,469
BEGIN DESCRIPTION:
UCFB HW Trib 16-01 9.0
END DESCRIPTION:
XS GIS Cut Line= 3
      1296486.69      6941858.71      1297155.00      6941788.00
      1297718.48      6941647.78
#Sta/Elev= 30
  4323.7 2227.28  4382.7 2224.97  4422.6 2225.66  4492.9 2222.38  4533.2 2222.60
  4573.4 2219.43  4603.6 2219.62  4643.8 2216.69  4724.2 2214.08  4758.8 2214.04
  4784.6 2216.64  4794.6 2215.27  4856.6 2212.43  4935.4 2212.13  4949.4 2208.56
  4965.6 2201.34  4985.7 2198.03  4998.3 2197.51  5003.3 2195.34  5003.7 2194.84
  5008.7 2195.34  5142.9 2211.70  5160.6 2211.88  5184.2 2215.03  5232.8 2218.74
  5377.0 2224.80  5418.2 2227.16  5438.9 2229.75  5490.4 2231.94  5576.4 2232.08
#Mann=3,-1,0
  4323.7    0.07       0  5003.3    0.07       0  5008.7    0.07       0
Bank Sta=5003.3,5008.7
Exp/Cntr=0.3,0.1

Type RM Length L Ch R = 1,4730,500,500,500
BEGIN DESCRIPTION:
UCFB HW Trib 16-01 8.0
END DESCRIPTION:
XS GIS Cut Line= 3
      1296557.05      6942100.90      1297355.00      6942188.00
      1298007.57      6942147.77
#Sta/Elev= 30
  4196.9 2224.93  4218.1 2225.87  4265.3 2221.88  4309.5 2221.83  4345.7 2218.60
  4375.9 2219.26  4416.1 2216.22  4537.6 2212.79  4589.1 2213.18  4617.3 2213.72
  4647.5 2210.18  4862.6 2208.14  4899.0 2203.96  4929.2 2197.54  4969.4 2195.57
  4986.8 2191.34  4987.2 2190.84  4992.2 2191.34  5002.1 2192.18  5019.6 2201.77
  5069.7 2204.20  5119.8 2208.99  5159.9 2207.26  5200.0 2196.64  5220.0 2201.23
  5244.2 2203.98  5260.1 2208.01  5572.1 2223.90  5580.7 2225.44  5653.4 2228.15
#Mann=5,-1,0
  4196.9    0.07       0  4537.6   0.035       0  4589.1    0.07       0
  4986.8    0.07       0  4992.2    0.07       0
Bank Sta=4986.8,4992.2
Exp/Cntr=0.3,0.1

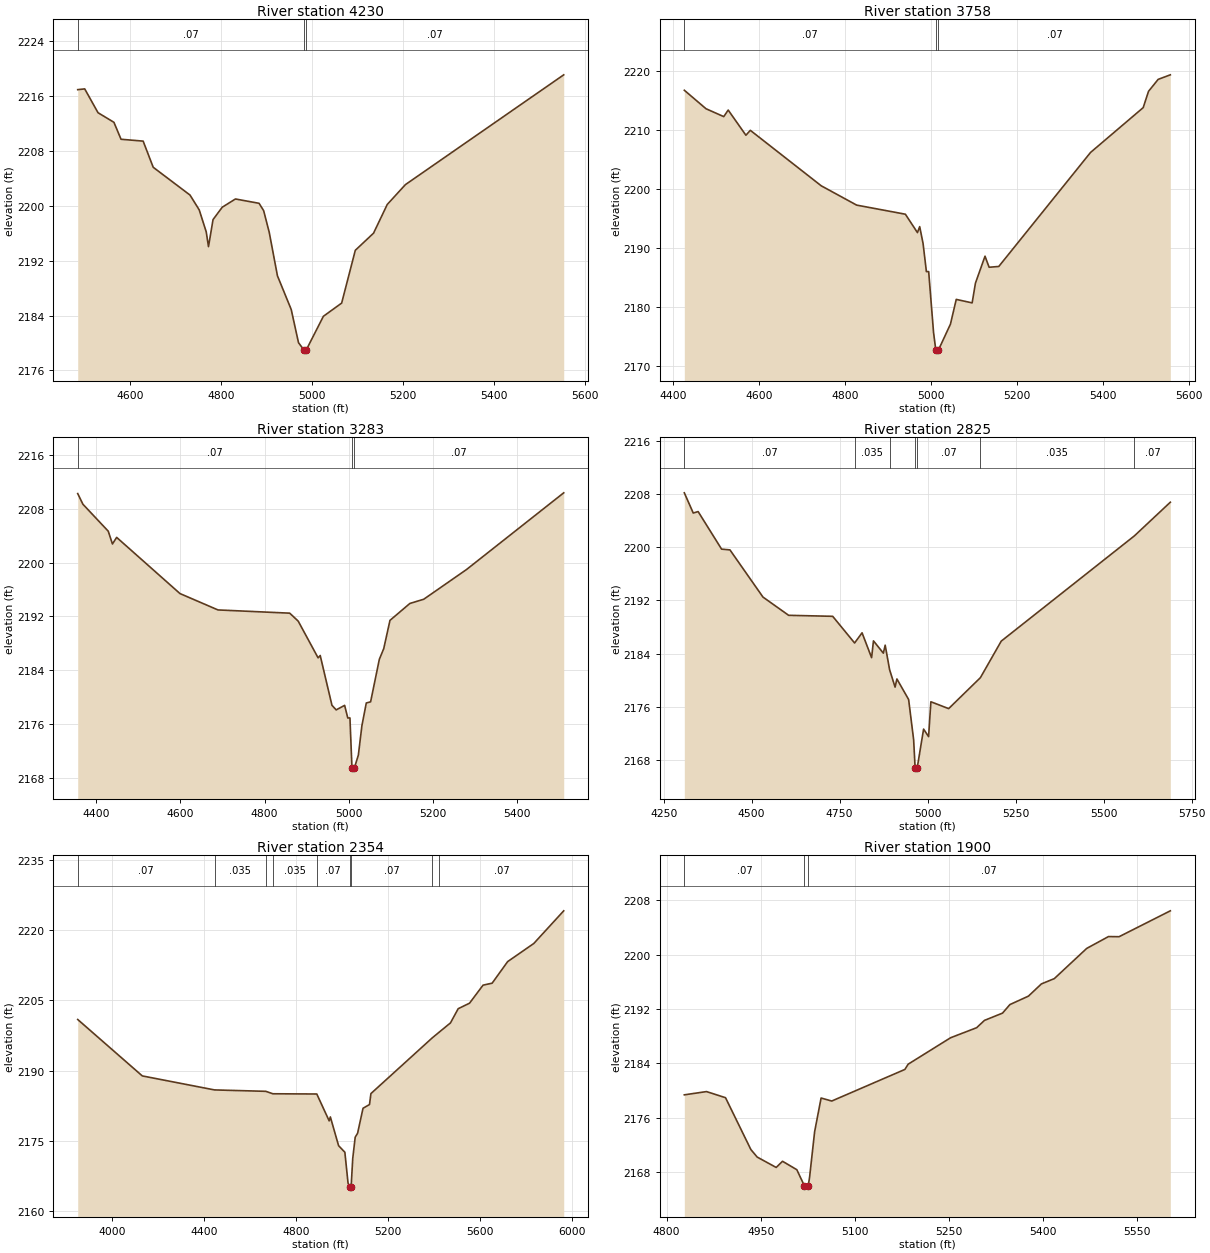
Type RM Length L Ch R = 1,4230,472,472,472
BEGIN DESCRIPTION:
UCFB HW Trib 16-01 7.0
END DESCRIPTION:
XS GIS Cut Line= 3
      1296840.89      6942611.32      1297355.00      6942688.00
      1297901.73      6942647.90
#Sta/Elev= 30
  4484.5 2216.91  4499.9 2217.02  4529.1 2213.55  4564.1 2212.15  4579.7 2209.68
  4628.3 2209.41  4650.4 2205.60  4731.3 2201.55  4751.5 2199.39  4766.9 2196.19
  4771.9 2194.04  4781.9 2197.98  4802.1 2199.78  4831.1 2200.98  4883.0 2200.35
  4893.1 2199.28  4905.4 2196.11  4923.4 2189.79  4953.7 2184.87  4969.7 2180.04
  4981.2 2179.02  4981.7 2178.52  4987.0 2179.02  5024.4 2183.89  5064.5 2185.81
  5094.5 2193.50  5134.6 2196.00  5164.7 2200.18  5204.6 2203.07  5552.5 2219.07
#Mann=3,-1,0
  4484.5    0.07       0  4981.2    0.07       0  4987.0    0.07       0
Bank Sta=4981.2,4987
Exp/Cntr=0.3,0.1

Type RM Length L Ch R = 1,3758,475,475,475
BEGIN DESCRIPTION:
UCFB HW Trib 16-01 6.0
END DESCRIPTION:
XS GIS Cut Line= 3
      1296905.97      6943223.30      1297455.00      6943088.00
      1297961.63      6942838.69
#Sta/Elev= 30
  4425.7 2216.69  4476.2 2213.56  4517.4 2212.23  4527.7 2213.34  4568.9 2209.08
  4579.2 2209.91  4744.0 2200.53  4826.4 2197.26  4939.7 2195.72  4967.8 2192.61
  4973.0 2193.62  4980.9 2190.75  4988.6 2186.01  4993.9 2186.01  5005.2 2175.74
  5010.5 2172.72  5011.0 2172.22  5016.4 2172.72  5044.5 2177.12  5058.0 2181.31
  5095.0 2180.72  5102.6 2184.05  5124.9 2188.62  5134.4 2186.75  5156.9 2186.88
  5370.3 2206.17  5492.7 2213.75  5505.1 2216.51  5527.5 2218.53  5555.8 2219.30
#Mann=3,-1,0
  4425.7    0.07       0  5010.5    0.07       0  5016.4    0.07       0
Bank Sta=5010.5,5016.4
Exp/Cntr=0.3,0.1

Type RM Length L Ch R = 1,3283,458,458,458
BEGIN DESCRIPTION:
UCFB HW Trib 16-01 5.0
END DESCRIPTION:
XS GIS Cut Line= 3
      1297012.73      6943392.57      1297655.00      6943438.00
      1298148.13      6943306.64
#Sta/Elev= 30
  4356.1 2210.25  4368.4 2208.67  4428.6 2204.66  4438.6 2202.76  4448.6 2203.74
  4599.0 2195.39  4689.2 2192.96  4859.6 2192.48  4879.7 2191.30  4927.0 2185.84
  4932.0 2186.19  4959.9 2178.79  4969.9 2178.11  4990.0 2178.78  4997.5 2176.91
  5002.6 2176.91  5007.4 2169.51  5007.9 2169.01  5013.3 2169.51  5022.6 2171.40
  5031.0 2175.75  5041.4 2179.13  5051.7 2179.31  5072.4 2185.62  5082.8 2187.20
  5097.7 2191.41  5144.9 2193.92  5177.9 2194.55  5279.4 2198.96  5510.3 2210.36
#Mann=3,-1,0
  4356.1    0.07       0  5007.4    0.07       0  5013.3    0.07       0
Bank Sta=5007.4,5013.3
Exp/Cntr=0.3,0.1

Type RM Length L Ch R = 1,2825,471,471,471
BEGIN DESCRIPTION:
UCFB HW Trib 16-01 4.0
END DESCRIPTION:
XS GIS Cut Line= 4
      1296960.64      6943702.46      1297562.22      6943879.55
      1297605.00      6943838.00      1298145.56      6943402.99
#Sta/Elev= 30
  4308.8 2208.17  4334.2 2205.13  4348.0 2205.35  4414.7 2199.70  4438.4 2199.59
  4532.3 2192.49  4605.2 2189.75  4730.3 2189.60  4792.5 2185.59  4813.7 2187.12
  4840.8 2183.38  4846.1 2185.91  4874.2 2184.06  4879.4 2185.26  4892.0 2181.56
  4907.5 2178.95  4912.7 2180.18  4946.0 2177.09  4960.2 2171.05  4964.4 2166.82
  4964.9 2166.32  4970.4 2166.82  4988.5 2172.64  5002.7 2171.51  5009.2 2176.75
  5059.7 2175.72  5149.8 2180.37  5209.1 2185.87  5587.4 2201.70  5689.4 2206.76
#Mann=7,-1,0
  4308.8    0.07       0  4792.5   0.035       0  4892.0    0.07       0
  4964.4    0.07       0  4970.4    0.07       0  5149.8   0.035       0
  5587.4    0.07       0
Bank Sta=4964.4,4970.4
Exp/Cntr=0.3,0.1

Type RM Length L Ch R = 1,2354,454,454,454
BEGIN DESCRIPTION:
UCFB HW Trib 16-01 3.0
END DESCRIPTION:
XS GIS Cut Line= 3
      1296765.39      6943965.49      1297905.00      6944088.00
      1298840.45      6943830.18
#Sta/Elev= 30
  3849.1 2200.93  4130.3 2188.89  4444.8 2185.90  4668.5 2185.60  4698.6 2185.08
  4890.3 2185.03  4944.2 2179.30  4949.3 2180.14  4985.2 2174.00  5012.5 2172.60
  5026.4 2166.00  5033.7 2165.23  5034.2 2164.73  5039.8 2165.23  5046.8 2171.27
  5057.5 2175.81  5067.9 2176.65  5091.6 2181.99  5119.8 2182.78  5126.0 2185.12
  5393.6 2197.03  5423.8 2198.25  5472.4 2200.20  5506.0 2203.23  5555.4 2204.41
  5614.4 2208.26  5653.9 2208.68  5721.4 2213.28  5835.5 2217.16  5965.6 2224.12
#Mann=9,-1,0
  3849.1    0.07       0  4444.8   0.035       0  4668.5    0.07       0
  4698.6   0.035       0  4890.3    0.07       0  5033.7    0.07       0
  5039.8    0.07       0  5393.6   0.035       0  5423.8    0.07       0
Bank Sta=5033.7,5039.8
Exp/Cntr=0.3,0.1

Type RM Length L Ch R = 1,1900,761,761,761
BEGIN DESCRIPTION:
UCFB HW Trib 16-01 2.0
END DESCRIPTION:
XS GIS Cut Line= 3
      1297879.98      6944513.00      1298055.00      6944488.00
      1298634.06      6944337.89
#Sta/Elev= 30
  4828.2 2179.35  4863.6 2179.83  4893.9 2178.93  4934.3 2171.30  4944.4 2170.19
  4974.7 2168.66  4984.8 2169.57  5007.6 2168.33  5019.6 2165.97  5020.1 2165.47
  5025.3 2165.47  5025.8 2165.97  5027.9 2167.18  5036.0 2173.93  5046.3 2178.88
  5063.3 2178.44  5179.9 2183.09  5185.1 2183.86  5252.9 2187.76  5294.3 2189.23
  5306.8 2190.31  5335.6 2191.38  5347.4 2192.64  5376.9 2193.88  5397.6 2195.68
  5418.2 2196.46  5469.9 2200.91  5504.6 2202.65  5521.5 2202.63  5603.2 2206.44
#Mann=3,-1,0
  4828.2    0.07       0  5019.6    0.07       0  5025.8    0.07       0
Bank Sta=5019.6,5025.8
Exp/Cntr=0.3,0.1