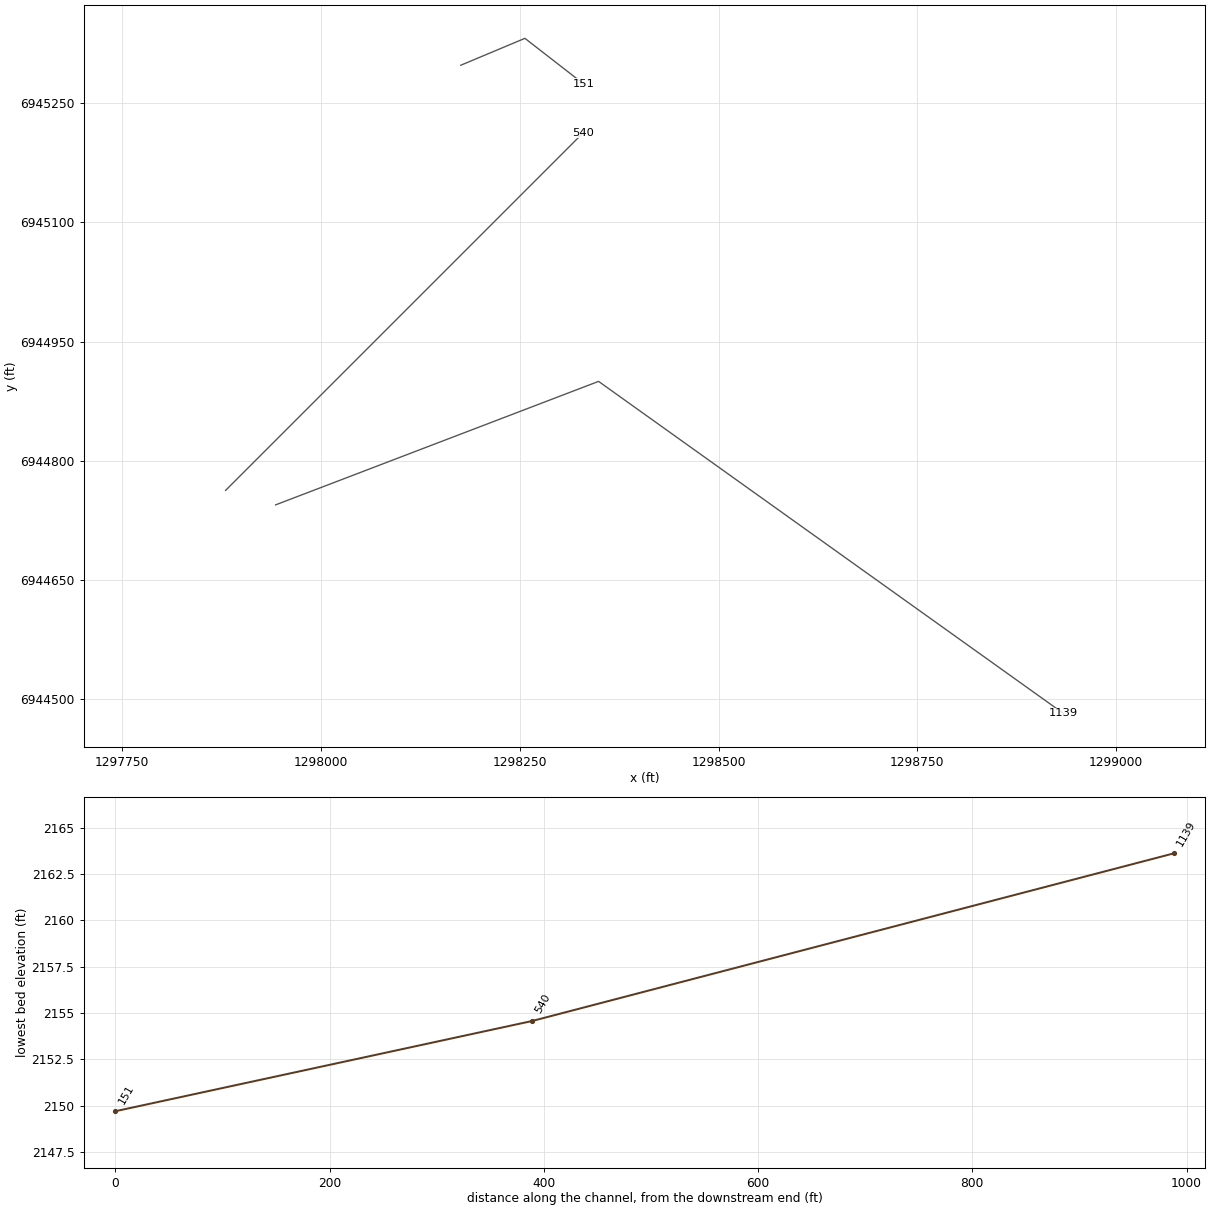
HEC-RAS study UCFB HW Trib 16-01.prj: UCFB HW Trib 16-01 Base Level Engineering

--- UCFB HW Trib 16-01.g01 (geometry) --- (continued)

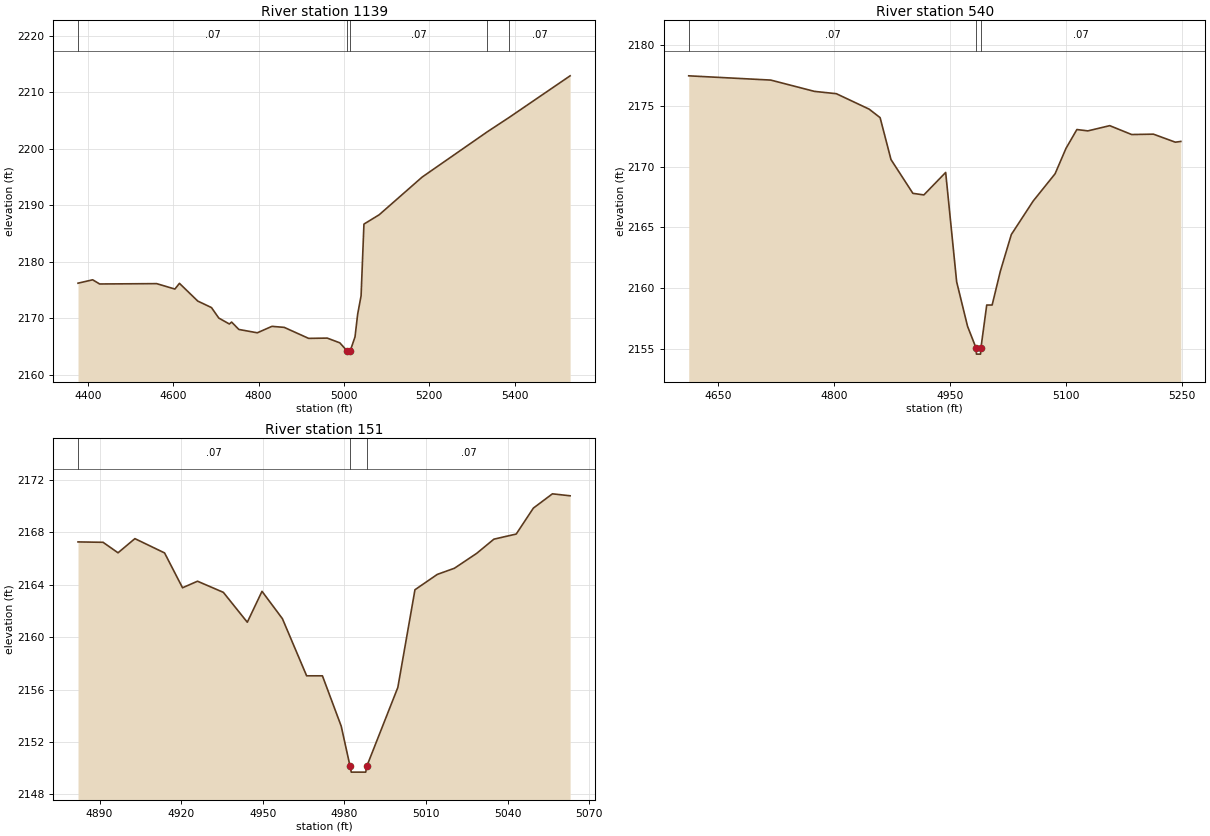
Type RM Length L Ch R = 1,1139,599,599,599
BEGIN DESCRIPTION:
UCFB HW Trib 16-01 1.5
END DESCRIPTION:
XS GIS Cut Line= 3
      1297942.93      6944744.78      1298349.04      6944900.06
      1298933.56      6944482.54
#Sta/Elev= 30
  4376.8 2176.19  4411.1 2176.79  4427.5 2176.05  4561.0 2176.11  4603.8 2175.15
  4614.5 2176.16  4657.4 2173.02  4689.5 2171.87  4706.7 2170.01  4731.4 2168.96
  4736.7 2169.30  4753.7 2167.99  4796.9 2167.40  4831.2 2168.54  4860.0 2168.36
  4917.2 2166.41  4960.8 2166.46  4990.3 2165.62  5008.1 2164.12  5008.6 2163.62
  5014.3 2164.12  5025.9 2166.68  5032.1 2170.71  5040.1 2173.95  5046.8 2186.66
  5082.5 2188.31  5183.2 2194.99  5336.0 2203.02  5386.9 2205.55  5529.9 2212.93
#Mann=5,-1,0
  4376.8    0.07       0  5008.1    0.07       0  5014.3    0.07       0
  5336.0   0.035       0  5386.9    0.07       0
Bank Sta=5008.1,5014.3
Exp/Cntr=0.3,0.1

Type RM Length L Ch R = 1,540,389,389,389
BEGIN DESCRIPTION:
UCFB HW Trib 16-01 1.0
END DESCRIPTION:
XS GIS Cut Line= 3
      1297880.00      6944763.00      1298155.00      6945038.00
      1298330.01      6945213.01
#Sta/Elev= 30
  4611.6 2177.47  4717.7 2177.12  4774.2 2176.19  4802.5 2176.00  4844.9 2174.73
  4859.1 2174.03  4873.2 2170.58  4901.5 2167.80  4915.7 2167.67  4943.9 2169.52
  4958.1 2160.52  4972.2 2156.86  4983.2 2155.07  4983.7 2154.57  4989.0 2154.57
  4989.5 2155.07  4997.0 2158.61  5004.0 2158.61  5014.6 2161.39  5028.8 2164.41
  5057.1 2167.17  5085.4 2169.41  5099.5 2171.50  5113.6 2173.05  5127.8 2172.94
  5156.1 2173.37  5184.4 2172.64  5212.6 2172.67  5240.9 2172.01  5248.0 2172.07
#Mann=3,-1,0
  4611.6    0.07       0  4983.2    0.07       0  4989.5    0.07       0
Bank Sta=4983.2,4989.5
Exp/Cntr=0.3,0.1

Type RM Length L Ch R = 1,151,0,0,0
BEGIN DESCRIPTION:
UCFB HW Trib 16-01 0.5
END DESCRIPTION:
XS GIS Cut Line= 3
      1298175.72      6945297.64      1298256.41      6945331.49
      1298330.10      6945274.27
#Sta/Elev= 28
  4882.1 2167.27  4891.3 2167.24  4896.8 2166.44  4903.0 2167.52  4913.9 2166.43
  4920.5 2163.77  4926.0 2164.27  4935.5 2163.42  4944.3 2161.14  4949.7 2163.50
  4957.2 2161.41  4966.1 2157.05  4971.9 2157.05  4978.8 2153.21  4982.0 2150.20
  4982.5 2149.70  4987.8 2149.70  4988.3 2150.20  4999.6 2156.16  5005.9 2163.62
  5014.1 2164.79  5020.4 2165.26  5028.6 2166.40  5034.9 2167.48  5043.1 2167.87
  5049.4 2169.85  5056.4 2170.94  5062.9 2170.79
#Mann=3,-1,0
  4882.1    0.07       0  4982.0    0.07       0  4988.3    0.07       0
Bank Sta=4982,4988.3
Exp/Cntr=0.3,0.1

Chan Stop Cuts=-1