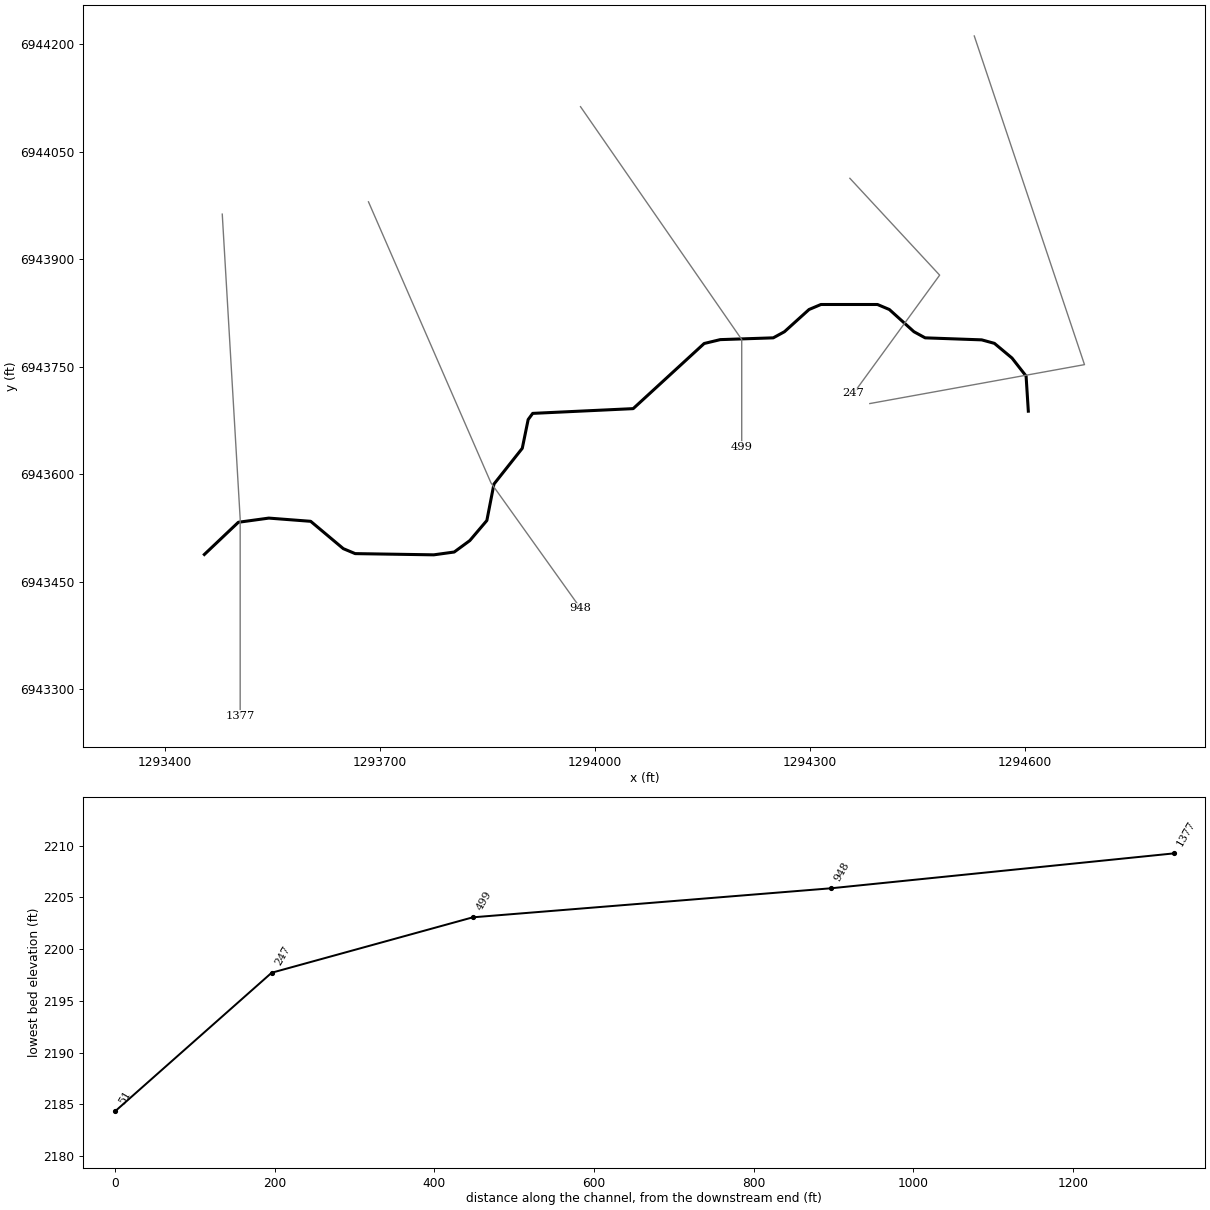
--- UCFB HW Trib 16-01A.prj (project) ---

Proj Title=UCFB HW Trib 16-01A Base Level Engineering
Current Plan=p01
Default Exp/Contr=0.3,0.1
English Units
Geom File=g01
Flow File=f01
Plan File=p01
BEGIN DESCRIPTION:
UCFB HW Trib 16-01A
END DESCRIPTION:

--- UCFB HW Trib 16-01A.p01 (plan) ---

Plan Title=Multiple Run
Short Identifier=Multiple
Geom File=g01
Flow File=f01
Subcritical Flow
K Sum by GR= 0
Std Step Tol= 0.01
Critical Tol= 0.01
Num of Std Step Trials= 20
Max Error Tol= 0.3
Flow Tol Ratio= 0.001
Split Flow NTrial= 30
Split Flow Tol= 0.02
Split Flow Ratio= 0.02
Log Output Level= 0
Friction Slope Method= 1
Unsteady Friction Slope Method= 2
Unsteady Bridges Friction Slope Method= 1
Parabolic Critical Depth
Global Vel Dist=  1 , 1 , 1
Global Log Level= 0
CheckData=True
Encroach Param= -1, 0, 0, 0
BEGIN DESCRIPTION:
Multiple Run
END DESCRIPTION:

--- UCFB HW Trib 16-01A.f01 (steady flow) ---

Flow Title=Multiple
Number of Profiles=7
Profile Names=10-year,25-year,50-year,1pct_min,100-year,1pct_plu,500-year
River Rch & RM= UCFB HW Trib 16-,Reach-1,1377
     303     435     548     344     685    1368    1087
Boundary for River Rch & Prof#=UCFB HW Trib 16-,Reach-1,1
Up Type=0
Dn Type=3
Dn Slope=0.005
Boundary for River Rch & Prof#=UCFB HW Trib 16-,Reach-1,2
Up Type=0
Dn Type=3
Dn Slope=0.005
Boundary for River Rch & Prof#=UCFB HW Trib 16-,Reach-1,3
Up Type=0
Dn Type=3
Dn Slope=0.005
Boundary for River Rch & Prof#=UCFB HW Trib 16-,Reach-1,4
Up Type=0
Dn Type=3
Dn Slope=0.005
Boundary for River Rch & Prof#=UCFB HW Trib 16-,Reach-1,5
Up Type=0
Dn Type=3
Dn Slope=0.005
Boundary for River Rch & Prof#=UCFB HW Trib 16-,Reach-1,6
Up Type=0
Dn Type=3
Dn Slope=0.005
Boundary for River Rch & Prof#=UCFB HW Trib 16-,Reach-1,7
Up Type=0
Dn Type=3
Dn Slope=0.005

--- UCFB HW Trib 16-01A.g01 (geometry) ---

Geom Title=Existing Conditions

River Reach=UCFB HW Trib 16-,Reach-1
Reach XY= 30
      1293455.00      6943488.00      1293502.45      6943532.95
      1293544.98      6943538.78      1293603.41      6943534.30
      1293648.94      6943496.14      1293665.51      6943489.21
      1293775.23      6943487.51      1293803.75      6943491.44
      1293825.55      6943507.44      1293849.29      6943535.42
      1293859.19      6943586.26      1293898.73      6943636.21
      1293906.94      6943676.32      1293913.28      6943684.93
      1294053.52      6943691.56      1294152.58      6943782.46
      1294175.05      6943787.87      1294249.02      6943790.36
      1294264.63      6943798.90      1294298.96      6943829.91
      1294315.55      6943836.90      1294394.45      6943836.90
      1294411.04      6943829.91      1294445.37      6943798.90
      1294460.98      6943790.36      1294539.89      6943787.54
      1294557.66      6943782.67      1294582.24      6943762.13
      1294601.88      6943737.01      1294605.00      6943688.00

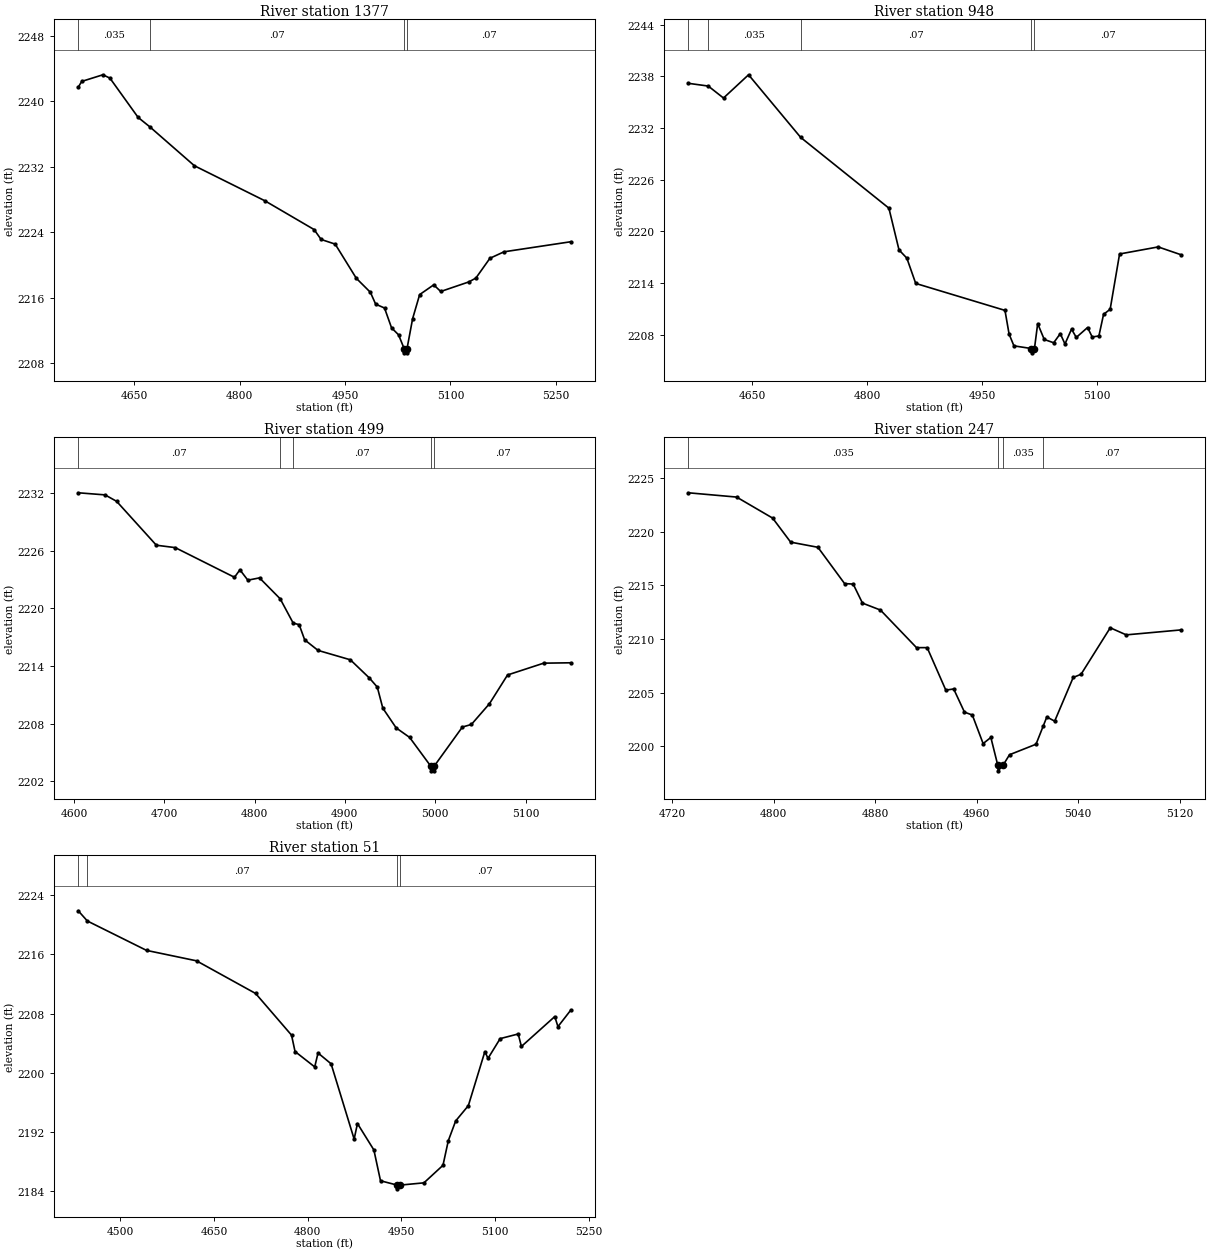
Type RM Length L Ch R = 1,1377,429,429,429
BEGIN DESCRIPTION:
UCFB HW Trib 16-01A 3.0
END DESCRIPTION:
XS GIS Cut Line= 3
      1293480.00      6943963.02      1293505.00      6943538.00
      1293505.00      6943262.95
#Sta/Elev= 30
  4570.4 2241.73  4575.4 2242.44  4605.5 2243.25  4615.5 2242.84  4655.6 2238.04
  4672.5 2236.87  4735.7 2232.13  4835.9 2227.85  4906.0 2224.33  4916.0 2223.12
  4936.0 2222.55  4966.1 2218.37  4986.1 2216.66  4993.6 2215.21  5006.2 2214.74
  5016.2 2212.32  5026.2 2211.46  5034.2 2209.76  5034.4 2209.26  5037.9 2209.26
  5038.2 2209.76  5046.2 2213.44  5056.2 2216.38  5076.2 2217.57  5086.2 2216.76
  5126.2 2217.93  5136.2 2218.40  5156.2 2220.82  5176.2 2221.61  5271.2 2222.84
#Mann=4,-1,0
  4570.4   0.035       0  4672.5    0.07       0  5034.2    0.07       0
  5038.2    0.07       0
Bank Sta=5034.2,5038.2
Exp/Cntr=0.3,0.1

Type RM Length L Ch R = 1,948,449,449,449
BEGIN DESCRIPTION:
UCFB HW Trib 16-01A 2.0
END DESCRIPTION:
XS GIS Cut Line= 3
      1293684.08      6943980.18      1293855.00      6943588.00
      1293980.02      6943412.97
#Sta/Elev= 30
  4566.6 2237.19  4592.7 2236.87  4612.6 2235.48  4645.3 2238.18  4713.3 2230.91
  4828.5 2222.69  4841.7 2217.84  4851.9 2216.89  4863.5 2213.95  4980.0 2210.82
  4985.4 2208.06  4991.7 2206.70  5014.5 2206.39  5014.8 2205.89  5018.5 2206.39
  5022.7 2209.28  5031.3 2207.44  5043.6 2207.06  5052.2 2208.12  5058.3 2206.92
  5066.9 2208.64  5073.1 2207.68  5087.8 2208.83  5093.9 2207.73  5102.6 2207.85
  5108.7 2210.36  5117.3 2210.95  5129.6 2217.37  5180.0 2218.19  5209.5 2217.29
#Mann=5,-1,0
  4566.6    0.07       0  4592.7   0.035       0  4713.3    0.07       0
  5014.5    0.07       0  5018.5    0.07       0
Bank Sta=5014.5,5018.5
Exp/Cntr=0.3,0.1

Type RM Length L Ch R = 1,499,252,252,252
BEGIN DESCRIPTION:
UCFB HW Trib 16-01A 1.0
END DESCRIPTION:
XS GIS Cut Line= 3
      1293980.01      6944112.98      1294205.00      6943788.00
      1294205.00      6943637.96
#Sta/Elev= 30
  4604.8 2232.03  4634.5 2231.81  4647.3 2231.14  4691.3 2226.57  4712.2 2226.32
  4777.8 2223.23  4783.8 2224.01  4792.6 2222.93  4805.5 2223.17  4828.4 2220.99
  4842.8 2218.46  4849.4 2218.30  4855.5 2216.72  4870.3 2215.62  4906.1 2214.64
  4927.1 2212.75  4935.9 2211.80  4942.0 2209.61  4956.8 2207.55  4971.7 2206.56
  4995.0 2203.58  4995.3 2203.08  4998.8 2203.08  4999.0 2203.58  5030.1 2207.64
  5040.1 2207.91  5060.1 2210.07  5080.1 2213.06  5120.1 2214.29  5150.1 2214.33
#Mann=5,-1,0
  4604.8    0.07       0  4828.4   0.035       0  4842.8    0.07       0
  4995.0    0.07       0  4999.0    0.07       0
Bank Sta=4995,4999
Exp/Cntr=0.3,0.1

Type RM Length L Ch R = 1,247,196,196,196
BEGIN DESCRIPTION:
UCFB HW Trib 16-01A 0.5
END DESCRIPTION:
XS GIS Cut Line= 3
      1294355.96      6944013.00      1294481.23      6943877.86
      1294361.18      6943713.02
#Sta/Elev= 30
  4732.7 2223.63  4770.8 2223.23  4799.2 2221.27  4813.4 2219.03  4834.9 2218.55
  4855.9 2215.17  4862.7 2215.12  4870.0 2213.35  4884.2 2212.70  4912.6 2209.20
  4921.0 2209.20  4935.7 2205.24  4941.9 2205.35  4950.4 2203.19  4956.6 2202.92
  4965.1 2200.26  4971.2 2200.83  4976.7 2198.22  4976.9 2197.72  4980.7 2198.22
  4985.9 2199.22  5006.8 2200.20  5012.6 2201.93  5015.3 2202.74  5021.5 2202.35
  5036.1 2206.42  5042.3 2206.72  5065.3 2211.05  5077.9 2210.39  5120.9 2210.85
#Mann=4,-1,0
  4732.7   0.035       0  4976.7   0.035       0  4980.7   0.035       0
  5012.6    0.07       0
Bank Sta=4976.7,4980.7
Exp/Cntr=0.3,0.1

Type RM Length L Ch R = 1,51,0,0,0
BEGIN DESCRIPTION:
UCFB HW Trib 16-01A 0.3
END DESCRIPTION:
XS GIS Cut Line= 3
      1294529.57      6944211.66      1294683.39      6943752.97
      1294383.78      6943698.64
#Sta/Elev= 30
  4432.8 2221.89  4447.4 2220.51  4542.1 2216.54  4622.1 2215.13  4716.7 2210.72
  4774.2 2205.09  4779.8 2202.88  4811.3 2200.80  4816.6 2202.68  4837.5 2201.22
  4874.4 2191.05  4879.7 2193.15  4906.0 2189.58  4916.6 2185.42  4943.5 2184.83
  4943.7 2184.33  4947.5 2184.83  4986.1 2185.14  5016.6 2187.51  5025.1 2190.83
  5036.9 2193.50  5057.2 2195.57  5083.6 2202.86  5088.7 2201.96  5108.1 2204.62
  5137.0 2205.25  5142.1 2203.56  5195.5 2207.60  5200.6 2206.24  5221.1 2208.47
#Mann=4,-1,0
  4432.8   0.035       0  4447.4    0.07       0  4943.5    0.07       0
  4947.5    0.07       0
Bank Sta=4943.5,4947.5
Exp/Cntr=0.3,0.1

Chan Stop Cuts=-1