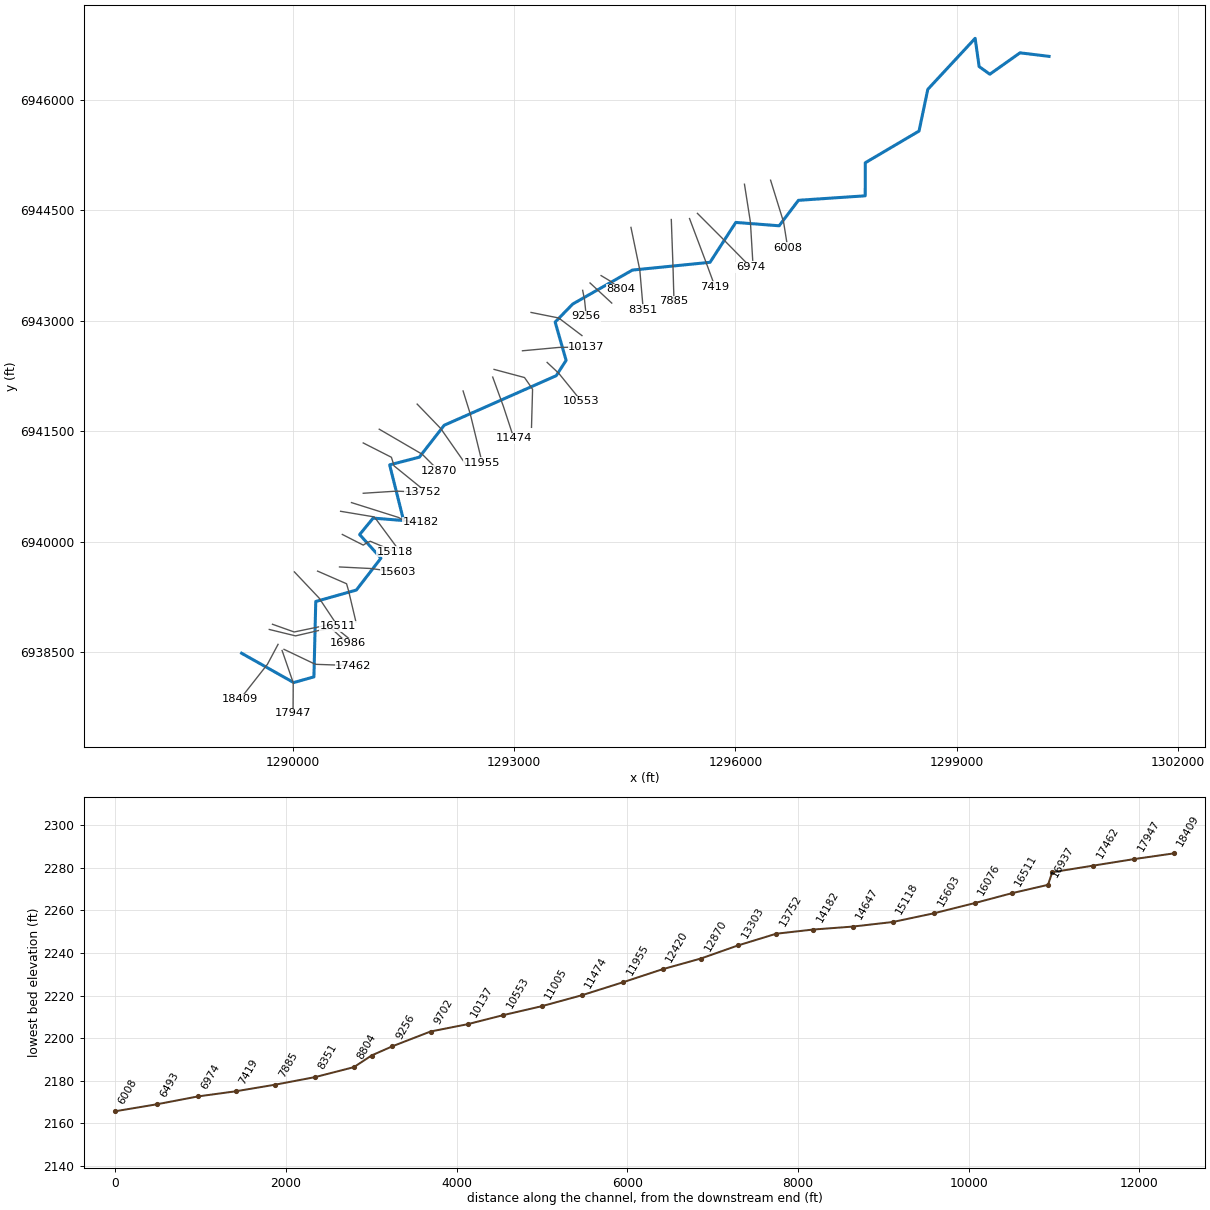
--- UCFB HW Trib 16.prj (project) ---

Proj Title=UCFB HW Trib 16 Base Level Engineering
Current Plan=p01
Default Exp/Contr=0.3,0.1
English Units
Geom File=g01
Flow File=f01
Plan File=p01
BEGIN DESCRIPTION:
UCFB HW Trib 16
END DESCRIPTION:

--- UCFB HW Trib 16.p01 (plan) ---

Plan Title=Multiple Run
Short Identifier=Multiple
Geom File=g01
Flow File=f01
Subcritical Flow
K Sum by GR= 0
Std Step Tol= 0.01
Critical Tol= 0.01
Num of Std Step Trials= 20
Max Error Tol= 0.3
Flow Tol Ratio= 0.001
Split Flow NTrial= 30
Split Flow Tol= 0.02
Split Flow Ratio= 0.02
Log Output Level= 0
Friction Slope Method= 1
Unsteady Friction Slope Method= 2
Unsteady Bridges Friction Slope Method= 1
Parabolic Critical Depth
Global Vel Dist=  1 , 1 , 1
Global Log Level= 0
CheckData=True
Encroach Param= -1, 0, 0, 0
BEGIN DESCRIPTION:
Multiple Run
END DESCRIPTION:

--- UCFB HW Trib 16.f01 (steady flow) ---

Flow Title=Multiple
Number of Profiles=7
Profile Names=10-year,25-year,50-year,1pct_min,100-year,1pct_plu,500-year
River Rch & RM= UCFB HW Trib 16,Reach-1,18409
     461     676     863     547    1092    2179    1775
River Rch & RM= UCFB HW Trib 16,Reach-1,12420
     511     754     966     615    1227    2448    2006
River Rch & RM= UCFB HW Trib 16,Reach-1,8351
     779    1171    1519     978    1952    3894    3266
River Rch & RM= UCFB HW Trib 16,Reach-1,3225
    1066    1623    2124    1378    2749    5485    4670
Boundary for River Rch & Prof#=UCFB HW Trib 16,Reach-1,1
Up Type=0
Dn Type=3
Dn Slope=0.005
Boundary for River Rch & Prof#=UCFB HW Trib 16,Reach-1,2
Up Type=0
Dn Type=3
Dn Slope=0.005
Boundary for River Rch & Prof#=UCFB HW Trib 16,Reach-1,3
Up Type=0
Dn Type=3
Dn Slope=0.005
Boundary for River Rch & Prof#=UCFB HW Trib 16,Reach-1,4
Up Type=0
Dn Type=3
Dn Slope=0.005
Boundary for River Rch & Prof#=UCFB HW Trib 16,Reach-1,5
Up Type=0
Dn Type=3
Dn Slope=0.005
Boundary for River Rch & Prof#=UCFB HW Trib 16,Reach-1,6
Up Type=0
Dn Type=3
Dn Slope=0.005
Boundary for River Rch & Prof#=UCFB HW Trib 16,Reach-1,7
Up Type=0
Dn Type=3
Dn Slope=0.005

--- UCFB HW Trib 16.g01 (geometry) ---

Geom Title=Existing Conditions

River Reach=UCFB HW Trib 16,Reach-1
Reach XY= 30
      1289305.00      6938488.00      1290010.93      6938090.23
      1290285.56      6938167.45      1290310.45      6939190.47
      1290861.21      6939345.80      1291194.05      6939778.00
      1290905.55      6940098.64      1291088.51      6940321.85
      1291501.57      6940289.22      1291312.67      6941044.52
      1291714.71      6941148.75      1292052.70      6941582.17
      1293571.71      6942254.63      1293705.42      6942463.00
      1293557.06      6942982.15      1293795.32      6943227.24
      1294605.00      6943688.00      1295657.71      6943793.40
      1296006.46      6944334.46      1296594.53      6944288.93
      1296856.25      6944634.55      1297761.84      6944695.80
      1297762.80      6945144.21      1298491.64      6945574.68
      1298610.45      6946140.47      1299252.39      6946832.73
      1299306.62      6946449.82      1299451.60      6946345.78
      1299860.89      6946636.04      1300255.00      6946588.00

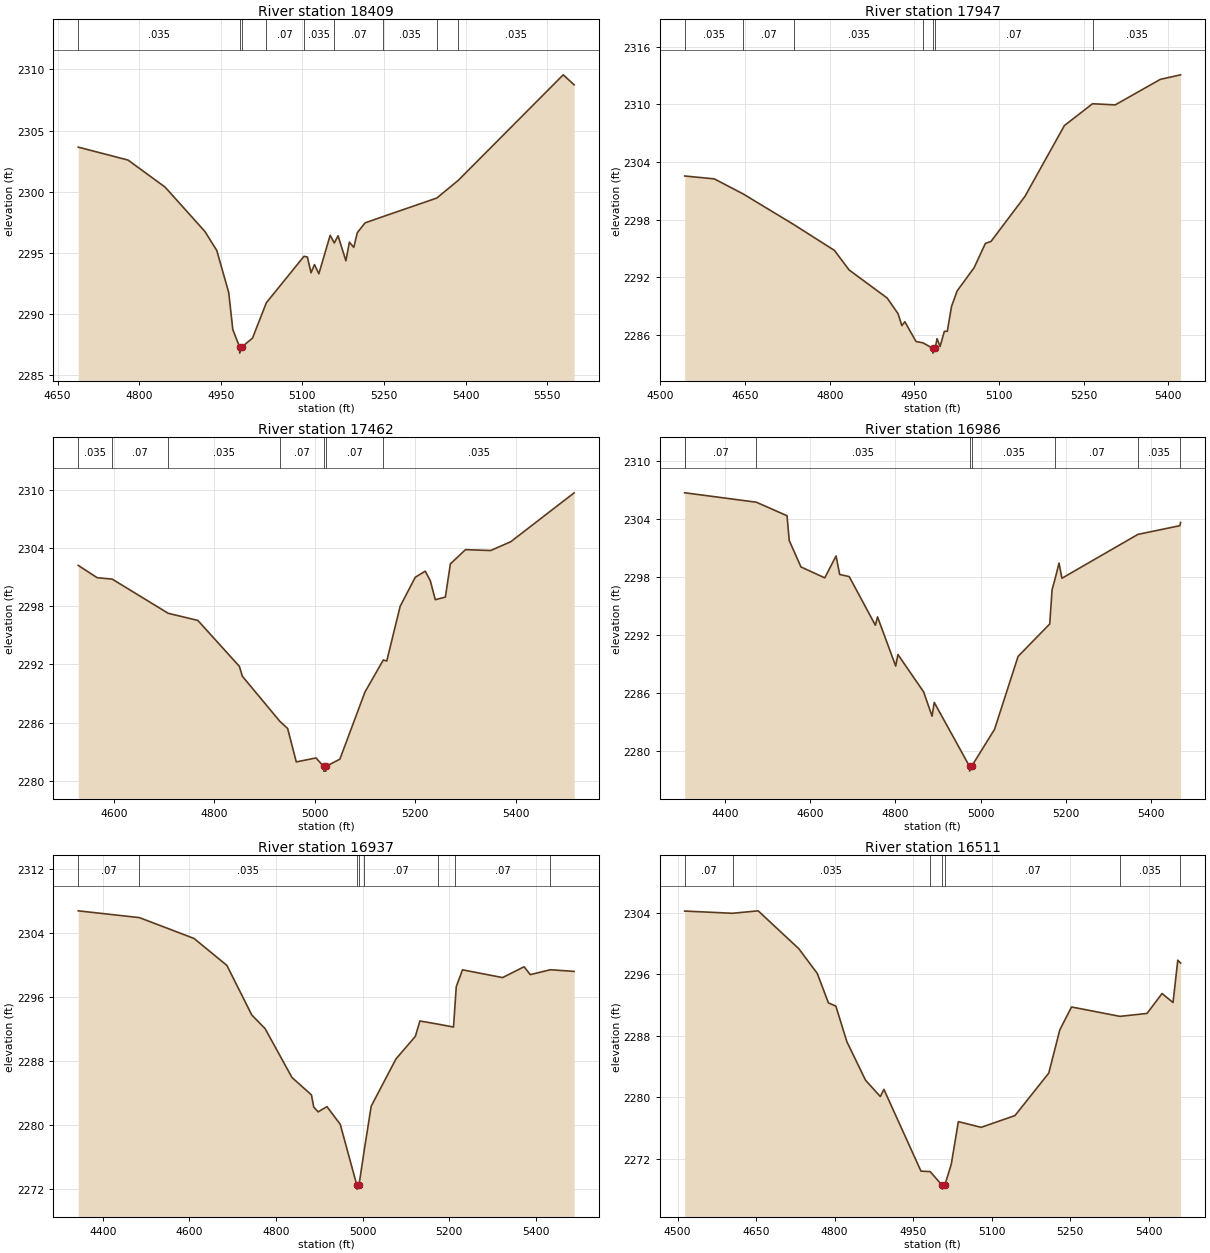
Type RM Length L Ch R = 1,18409,462,462,462
BEGIN DESCRIPTION:
UCFB HW Trib 16 39.0
END DESCRIPTION:
XS GIS Cut Line= 3
      1289799.24      6938608.83      1289655.00      6938338.00
      1289281.59      6937862.17
#Sta/Elev= 30
  4688.0 2303.64  4779.6 2302.58  4847.6 2300.37  4920.8 2296.74  4942.8 2295.17
  4964.7 2291.73  4972.2 2288.70  4984.7 2287.27  4984.9 2286.77  4988.7 2287.27
  5008.4 2288.00  5033.9 2290.90  5103.1 2294.70  5109.3 2294.64  5116.0 2293.35
  5122.3 2294.02  5130.4 2293.27  5151.2 2296.42  5158.8 2295.79  5165.7 2296.38
  5180.1 2294.33  5186.5 2295.86  5194.6 2295.43  5201.0 2296.63  5215.4 2297.44
  5248.2 2297.95  5347.2 2299.47  5386.7 2300.92  5579.6 2309.56  5599.7 2308.74
#Mann=9,-1,0
  4688.0   0.035       0  4984.7   0.035       0  4988.7   0.035       0
  5033.9    0.07       0  5103.1   0.035       0  5158.8    0.07       0
  5248.2   0.035       0  5347.2    0.07       0  5386.7   0.035       0
Bank Sta=4984.7,4988.7
Exp/Cntr=0.3,0.1

Type RM Length L Ch R = 1,17947,485,485,485
BEGIN DESCRIPTION:
UCFB HW Trib 16 38.0
END DESCRIPTION:
XS GIS Cut Line= 3
      1289853.92      6938525.43      1290005.00      6938088.00
      1290002.35      6937672.10
#Sta/Elev= 30
  4543.0 2302.55  4595.4 2302.25  4646.4 2300.69  4736.7 2297.48  4808.4 2294.80
  4834.3 2292.77  4901.9 2289.84  4921.2 2288.20  4927.8 2286.97  4933.1 2287.38
  4952.9 2285.32  4965.3 2285.18  4982.5 2284.61  4982.8 2284.11  4986.8 2284.61
  4990.2 2285.62  4995.5 2284.80  5003.1 2286.38  5008.3 2286.38  5015.8 2288.97
  5025.8 2290.59  5055.8 2293.00  5075.8 2295.53  5085.8 2295.74  5145.8 2300.42
  5215.8 2307.80  5265.6 2310.07  5305.8 2309.95  5385.8 2312.61  5421.7 2313.08
#Mann=7,-1,0
  4543.0   0.035       0  4646.4    0.07       0  4736.7   0.035       0
  4965.3    0.07       0  4982.5    0.07       0  4986.8    0.07       0
  5265.6   0.035       0
Bank Sta=4982.5,4986.8
Exp/Cntr=0.3,0.1

Type RM Length L Ch R = 1,17462,476,476,476
BEGIN DESCRIPTION:
UCFB HW Trib 16 37.0
END DESCRIPTION:
XS GIS Cut Line= 3
      1289879.95      6938541.09      1290305.00      6938338.00
      1290821.30      6938319.78
#Sta/Elev= 30
  4529.0 2302.22  4566.6 2300.95  4596.8 2300.80  4708.1 2297.28  4767.3 2296.54
  4849.9 2291.81  4856.0 2290.78  4930.7 2286.13  4946.1 2285.40  4963.3 2281.95
  5002.6 2282.36  5017.6 2281.50  5018.0 2281.00  5022.2 2281.00  5022.6 2281.50
  5050.1 2282.23  5100.1 2289.16  5136.6 2292.46  5143.5 2292.36  5170.2 2298.00
  5200.2 2300.99  5220.2 2301.62  5230.2 2300.64  5240.2 2298.68  5260.2 2298.95
  5270.2 2302.37  5300.3 2303.84  5350.3 2303.75  5390.3 2304.65  5516.7 2309.70
#Mann=7,-1,0
  4529.0   0.035       0  4596.8    0.07       0  4708.1   0.035       0
  4930.7    0.07       0  5017.6    0.07       0  5022.6    0.07       0
  5136.6   0.035       0
Bank Sta=5017.6,5022.6
Exp/Cntr=0.3,0.1

Type RM Length L Ch R = 1,16986,49,49,49
BEGIN DESCRIPTION:
UCFB HW Trib 16 36.0
END DESCRIPTION:
XS GIS Cut Line= 5
      1289680.01      6938810.83      1290036.39      6938723.71
      1290357.58      6938798.36      1290520.77      6938826.14
      1290742.54      6938622.41
#Sta/Elev= 30
  4305.9 2306.73  4307.2 2306.73  4474.0 2305.76  4546.0 2304.36  4551.2 2301.79
  4578.7 2299.06  4634.5 2297.93  4661.0 2300.20  4669.5 2298.28  4691.9 2298.06
  4753.2 2293.03  4758.3 2293.89  4800.9 2288.80  4806.1 2290.00  4866.4 2286.13
  4886.2 2283.62  4891.3 2285.04  4974.0 2278.43  4974.4 2277.93  4979.0 2278.43
  5032.8 2282.26  5087.9 2289.80  5162.2 2293.16  5167.7 2296.71  5175.5 2297.96
  5184.0 2299.46  5190.8 2297.89  5369.1 2302.43  5467.4 2303.33  5469.2 2303.67
#Mann=8,-1,0
  4305.9   0.035       0  4307.2    0.07       0  4474.0   0.035       0
  4974.0   0.035       0  4979.0   0.035       0  5175.5    0.07       0
  5369.1   0.035       0  5467.4    0.07       0
Bank Sta=4974,4979
Exp/Cntr=0.3,0.1

Type RM Length L Ch R = 1,16937,426,426,426
BEGIN DESCRIPTION:
UCFB HW Trib 16 35.5
END DESCRIPTION:
XS GIS Cut Line= 4
      1289723.75      6938881.34      1290017.12      6938776.77
      1290520.62      6938881.34      1290770.05      6938680.41
#Sta/Elev= 30
  4343.0 2306.78  4484.5 2305.93  4610.6 2303.33  4686.6 2299.96  4744.2 2293.76
  4774.9 2292.06  4836.9 2285.96  4882.0 2283.78  4887.2 2282.27  4897.4 2281.66
  4917.8 2282.32  4948.5 2280.11  4986.8 2272.51  4987.2 2272.01  4991.8 2272.51
  5004.5 2277.07  5020.0 2282.37  5077.3 2288.28  5122.1 2291.10  5132.6 2293.02
  5173.8 2292.63  5210.2 2292.26  5213.2 2294.63  5216.6 2297.31  5231.0 2299.41
  5323.7 2298.44  5373.3 2299.79  5387.7 2298.81  5434.3 2299.42  5489.0 2299.21
#Mann=8,-1,0
  4343.0    0.07       0  4484.5   0.035       0  4986.8   0.035       0
  4991.8   0.035       0  5004.5    0.07       0  5173.8   0.035       0
  5213.2    0.07       0  5434.3   0.035       0
Bank Sta=4986.8,4991.8
Exp/Cntr=0.3,0.1

Type RM Length L Ch R = 1,16511,435,435,435
BEGIN DESCRIPTION:
UCFB HW Trib 16 35.0
END DESCRIPTION:
XS GIS Cut Line= 3
      1290020.55      6939591.85      1290355.00      6939238.00
      1290610.44      6938854.59
#Sta/Elev= 30
  4513.6 2304.23  4605.0 2303.94  4654.0 2304.26  4731.7 2299.33  4766.9 2296.12
  4788.3 2292.28  4802.5 2291.86  4823.5 2287.24  4859.1 2282.23  4887.4 2280.10
  4894.3 2281.03  4965.1 2270.39  4982.7 2270.33  5005.5 2268.55  5005.9 2268.05
  5010.5 2268.55  5023.0 2271.29  5036.5 2276.83  5080.1 2276.09  5144.7 2277.62
  5209.3 2283.15  5230.4 2288.78  5252.8 2291.75  5345.3 2290.53  5397.0 2290.91
  5425.7 2293.50  5446.7 2292.33  5455.8 2297.84  5460.8 2297.50  5461.2 2297.47
#Mann=7,-1,0
  4513.6    0.07       0  4605.0   0.035       0  4982.7    0.07       0
  5005.5    0.07       0  5010.5    0.07       0  5345.3   0.035       0
  5460.8    0.07       0
Bank Sta=5005.5,5010.5
Exp/Cntr=0.3,0.1

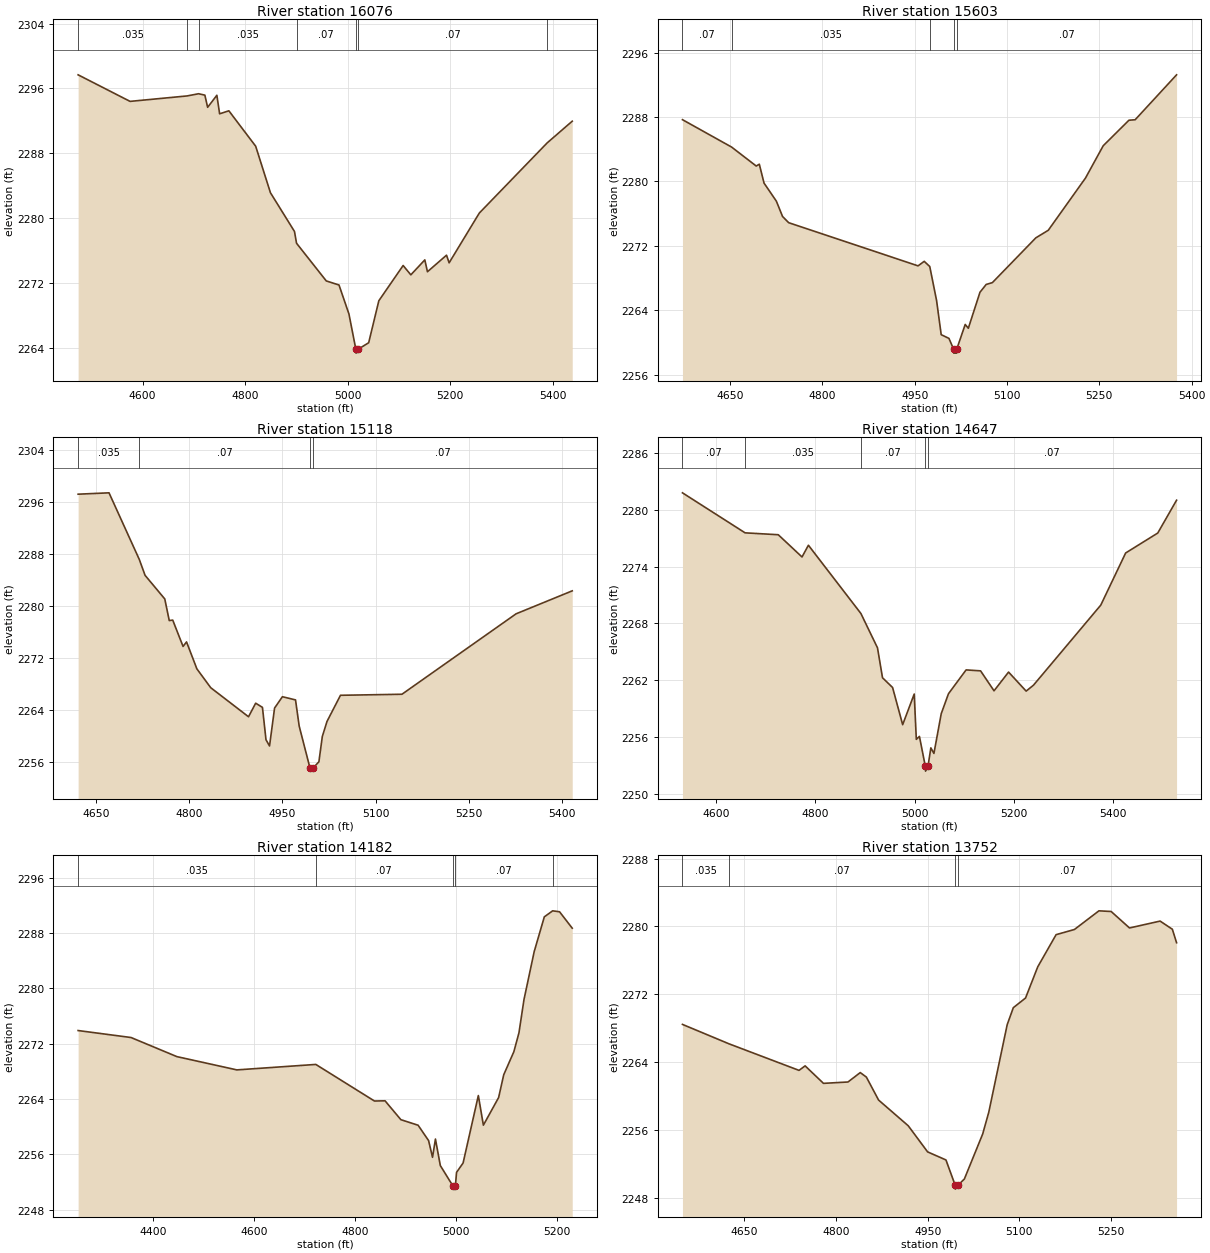
Type RM Length L Ch R = 1,16076,473,473,473
BEGIN DESCRIPTION:
UCFB HW Trib 16 34.0
END DESCRIPTION:
XS GIS Cut Line= 4
      1290335.27      6939602.66      1290728.04      6939431.23
      1290755.00      6939338.00      1290855.78      6938911.66
#Sta/Elev= 30
  4474.3 2297.68  4575.6 2294.41  4686.8 2295.08  4709.2 2295.35  4721.5 2295.18
  4726.9 2293.68  4744.9 2295.16  4750.3 2292.88  4768.3 2293.25  4820.6 2288.89
  4849.4 2283.16  4896.3 2278.39  4900.3 2276.94  4958.3 2272.30  4983.1 2271.80
  5002.5 2268.23  5015.9 2263.91  5016.3 2263.41  5021.0 2263.91  5041.0 2264.69
  5060.8 2269.86  5108.2 2274.20  5123.2 2273.05  5150.5 2274.89  5155.6 2273.43
  5192.8 2275.47  5197.9 2274.53  5256.8 2280.66  5389.0 2289.29  5438.0 2291.97
#Mann=7,-1,0
  4474.3   0.035       0  4686.8    0.07       0  4709.2   0.035       0
  4900.3    0.07       0  5015.9    0.07       0  5021.0    0.07       0
  5389.0   0.035       0
Bank Sta=5015.9,5021
Exp/Cntr=0.3,0.1

Type RM Length L Ch R = 1,15603,485,485,485
BEGIN DESCRIPTION:
UCFB HW Trib 16 33.0
END DESCRIPTION:
XS GIS Cut Line= 3
      1290632.54      6939659.10      1291055.00      6939638.00
      1291431.67      6939587.70
#Sta/Elev= 30
  4572.5 2287.66  4652.5 2284.25  4692.4 2281.90  4697.4 2282.13  4705.1 2279.78
  4725.1 2277.54  4735.2 2275.63  4745.2 2274.86  4955.4 2269.50  4965.4 2270.06
  4974.4 2269.42  4985.5 2265.19  4993.0 2260.95  5005.6 2260.49  5013.1 2259.16
  5013.5 2258.66  5017.9 2258.66  5018.3 2259.16  5032.0 2262.22  5037.1 2261.75
  5056.0 2266.22  5066.1 2267.19  5076.2 2267.42  5146.8 2272.98  5167.0 2273.92
  5227.5 2280.41  5256.3 2284.42  5298.1 2287.59  5308.2 2287.65  5375.5 2293.23
#Mann=5,-1,0
  4572.5    0.07       0  4652.5   0.035       0  4974.4    0.07       0
  5013.1    0.07       0  5018.3    0.07       0
Bank Sta=5013.1,5018.3
Exp/Cntr=0.3,0.1

Type RM Length L Ch R = 1,15118,471,471,471
BEGIN DESCRIPTION:
UCFB HW Trib 16 32.0
END DESCRIPTION:
XS GIS Cut Line= 5
      1290670.74      6940100.18      1290954.60      6939955.65
      1291005.00      6939988.00      1291049.65      6940007.73
      1291388.16      6939864.52
#Sta/Elev= 30
  4621.6 2297.23  4671.3 2297.44  4720.0 2287.17  4729.3 2284.72  4761.0 2281.08
  4768.2 2277.75  4773.8 2277.82  4790.4 2273.76  4796.0 2274.46  4812.6 2270.31
  4834.9 2267.40  4895.7 2262.92  4907.2 2265.01  4918.1 2264.37  4923.8 2259.38
  4929.5 2258.42  4937.6 2264.26  4950.2 2266.01  4971.3 2265.52  4977.2 2261.48
  4994.5 2255.04  4994.9 2254.54  4999.7 2255.04  5008.9 2255.98  5014.4 2259.88
  5021.9 2262.19  5043.6 2266.23  5142.5 2266.39  5326.1 2278.79  5416.4 2282.33
#Mann=4,-1,0
  4621.6   0.035       0  4720.0    0.07       0  4994.5    0.07       0
  4999.7    0.07       0
Bank Sta=4994.5,4999.7
Exp/Cntr=0.3,0.1

Type RM Length L Ch R = 1,14647,465,465,465
BEGIN DESCRIPTION:
UCFB HW Trib 16 31.0
END DESCRIPTION:
XS GIS Cut Line= 3
      1290647.41      6940414.42      1291105.00      6940338.00
      1291420.91      6939910.36
#Sta/Elev= 30
  4532.4 2281.80  4658.6 2277.57  4725.4 2277.37  4773.3 2275.02  4786.2 2276.26
  4892.0 2269.04  4925.4 2265.41  4935.5 2262.25  4955.8 2261.22  4976.1 2257.29
  4999.4 2260.53  5003.6 2255.74  5009.9 2256.05  5021.8 2252.88  5022.2 2252.38
  5027.1 2252.88  5032.9 2254.84  5039.1 2254.25  5053.8 2258.45  5068.4 2260.56
  5103.9 2263.08  5133.1 2262.98  5160.2 2260.87  5189.5 2262.85  5224.9 2260.84
  5239.6 2261.46  5375.3 2269.93  5425.4 2275.44  5490.1 2277.55  5528.0 2281.02
#Mann=5,-1,0
  4532.4    0.07       0  4658.6   0.035       0  4892.0    0.07       0
  5021.8    0.07       0  5027.1    0.07       0
Bank Sta=5021.8,5027.1
Exp/Cntr=0.3,0.1

Type RM Length L Ch R = 1,14182,430,430,430
BEGIN DESCRIPTION:
UCFB HW Trib 16 30.0
END DESCRIPTION:
XS GIS Cut Line= 4
      1290794.99      6940532.48      1291434.23      6940330.46
      1291505.00      6940288.00      1291729.98      6940263.00
#Sta/Elev= 30
  4250.8 2273.92  4355.7 2272.91  4446.5 2270.15  4565.4 2268.23  4721.9 2269.02
  4838.1 2263.73  4859.1 2263.76  4890.5 2261.03  4924.6 2260.23  4945.4 2258.01
  4953.2 2255.59  4959.0 2258.23  4968.7 2254.39  4993.3 2251.49  4993.7 2250.99
  4998.6 2251.49  5000.8 2253.41  5013.8 2254.77  5044.0 2264.52  5054.0 2260.24
  5084.2 2264.23  5094.3 2267.52  5114.4 2270.86  5124.5 2273.59  5134.5 2278.41
  5154.7 2285.33  5174.8 2290.36  5191.3 2291.23  5205.0 2291.09  5230.1 2288.72
#Mann=5,-1,0
  4250.8   0.035       0  4721.9    0.07       0  4993.3    0.07       0
  4998.6    0.07       0  5191.3   0.035       0
Bank Sta=4993.3,4998.6
Exp/Cntr=0.3,0.1

Type RM Length L Ch R = 1,13752,449,449,449
BEGIN DESCRIPTION:
UCFB HW Trib 16 29.0
END DESCRIPTION:
XS GIS Cut Line= 3
      1290954.74      6940659.21      1291405.00      6940688.00
      1291761.91      6940673.17
#Sta/Elev= 30
  4548.8 2268.45  4625.0 2266.16  4739.5 2263.03  4749.5 2263.56  4779.5 2261.50
  4819.6 2261.66  4839.7 2262.77  4849.7 2262.24  4869.7 2259.53  4918.2 2256.50
  4949.9 2253.42  4979.9 2252.47  4994.8 2249.53  4995.2 2249.03  5000.1 2249.53
  5010.0 2250.22  5040.0 2255.53  5050.0 2258.11  5080.1 2268.42  5090.1 2270.42
  5110.1 2271.56  5130.1 2275.24  5160.1 2279.03  5190.1 2279.64  5230.2 2281.84
  5250.2 2281.76  5280.2 2279.82  5330.3 2280.63  5350.3 2279.67  5357.2 2278.08
#Mann=4,-1,0
  4548.8   0.035       0  4625.0    0.07       0  4994.8    0.07       0
  5000.1    0.07       0
Bank Sta=4994.8,5000.1
Exp/Cntr=0.3,0.1

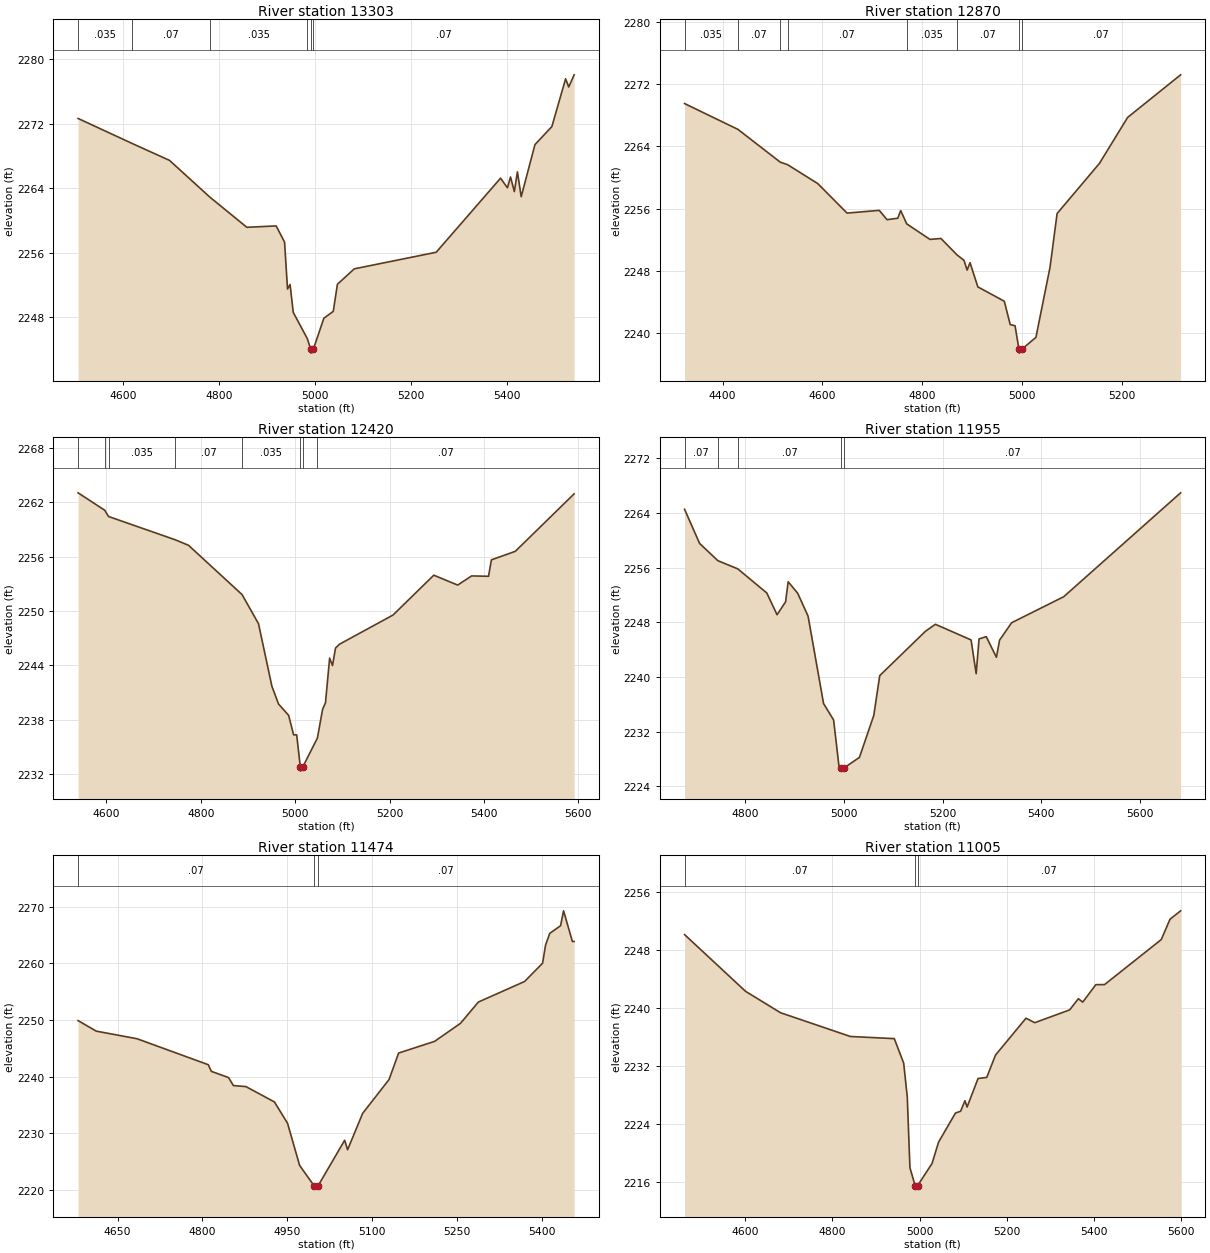
Type RM Length L Ch R = 1,13303,433,433,433
BEGIN DESCRIPTION:
UCFB HW Trib 16 28.0
END DESCRIPTION:
XS GIS Cut Line= 5
      1290954.34      6941341.92      1291336.26      6941147.49
      1291355.00      6941088.00      1291371.41      6941031.60
      1291748.55      6940725.64
#Sta/Elev= 30
  4505.4 2272.66  4618.3 2269.55  4696.3 2267.45  4780.2 2262.90  4857.6 2259.14
  4918.8 2259.31  4936.3 2257.31  4942.5 2251.47  4947.8 2252.04  4954.4 2248.58
  4983.8 2245.31  4990.9 2244.01  4991.4 2243.51  4996.5 2244.01  5018.3 2247.84
  5038.0 2248.70  5046.6 2252.06  5081.8 2253.98  5252.8 2256.04  5387.1 2265.24
  5401.5 2264.05  5407.9 2265.39  5415.9 2263.58  5422.3 2266.03  5430.2 2262.94
  5458.9 2269.41  5494.2 2271.65  5522.9 2277.59  5529.4 2276.57  5540.7 2278.08
#Mann=6,-1,0
  4505.4   0.035       0  4618.3    0.07       0  4780.2   0.035       0
  4983.8    0.07       0  4990.9    0.07       0  4996.5    0.07       0
Bank Sta=4990.9,4996.5
Exp/Cntr=0.3,0.1

Type RM Length L Ch R = 1,12870,450,450,450
BEGIN DESCRIPTION:
UCFB HW Trib 16 27.0
END DESCRIPTION:
XS GIS Cut Line= 3
      1291171.30      6941528.58      1291755.00      6941188.00
      1291980.00      6940963.00
#Sta/Elev= 30
  4323.7 2269.52  4430.6 2266.20  4515.4 2261.98  4530.2 2261.65  4590.6 2259.22
  4649.3 2255.42  4713.8 2255.77  4729.5 2254.57  4751.0 2254.76  4756.8 2255.74
  4768.9 2254.03  4815.5 2252.03  4837.4 2252.15  4869.8 2250.03  4883.7 2249.33
  4889.9 2248.08  4895.7 2249.04  4911.4 2245.92  4964.4 2244.07  4976.3 2241.06
  4985.9 2240.92  4993.8 2237.89  4994.3 2237.39  4999.5 2237.89  5027.8 2239.42
  5056.1 2248.47  5070.2 2255.36  5155.1 2261.82  5211.6 2267.74  5317.7 2273.22
#Mann=8,-1,0
  4323.7   0.035       0  4430.6    0.07       0  4515.4   0.035       0
  4530.2    0.07       0  4768.9   0.035       0  4869.8    0.07       0
  4993.8    0.07       0  4999.5    0.07       0
Bank Sta=4993.8,4999.5
Exp/Cntr=0.3,0.1

Type RM Length L Ch R = 1,12420,465,465,465
BEGIN DESCRIPTION:
UCFB HW Trib 16 26.0
END DESCRIPTION:
XS GIS Cut Line= 3
      1291685.66      6941869.26      1292005.00      6941538.00
      1292343.17      6941053.34
#Sta/Elev= 30
  4540.1 2263.03  4596.5 2261.11  4604.7 2260.42  4745.6 2257.86  4774.0 2257.25
  4887.6 2251.81  4922.4 2248.60  4950.7 2241.72  4964.8 2239.75  4986.2 2238.50
  4996.8 2236.35  5003.3 2236.35  5010.9 2232.85  5011.3 2232.35  5016.6 2232.85
  5047.2 2236.00  5058.2 2239.16  5064.3 2239.89  5073.1 2244.81  5079.2 2243.99
  5085.6 2245.92  5094.0 2246.34  5207.5 2249.56  5293.8 2253.95  5344.4 2252.86
  5374.0 2253.87  5409.8 2253.83  5415.9 2255.64  5466.5 2256.58  5591.2 2262.92
#Mann=8,-1,0
  4540.1   0.035       0  4596.5    0.07       0  4604.7   0.035       0
  4745.6    0.07       0  4887.6   0.035       0  5010.9   0.035       0
  5016.6   0.035       0  5047.2    0.07       0
Bank Sta=5010.9,5016.6
Exp/Cntr=0.3,0.1

Type RM Length L Ch R = 1,11955,481,481,481
BEGIN DESCRIPTION:
UCFB HW Trib 16 25.0
END DESCRIPTION:
XS GIS Cut Line= 3
      1292308.48      6942047.22      1292405.00      6941738.00
      1292566.73      6941074.97
#Sta/Elev= 30
  4676.4 2264.55  4707.0 2259.54  4744.1 2257.02  4784.3 2255.83  4843.2 2252.30
  4864.1 2249.11  4881.4 2251.00  4886.6 2253.94  4906.0 2252.25  4927.0 2248.90
  4958.4 2236.11  4978.8 2233.70  4989.9 2226.80  4994.8 2226.71  4995.3 2226.21
  5000.6 2226.71  5031.2 2228.22  5060.3 2234.37  5072.4 2240.20  5165.0 2246.68
  5185.3 2247.71  5257.7 2245.42  5268.0 2240.48  5273.9 2245.57  5288.5 2245.90
  5309.1 2242.88  5315.5 2245.39  5340.0 2247.94  5445.7 2251.75  5682.8 2266.96
#Mann=5,-1,0
  4676.4    0.07       0  4744.1   0.035       0  4784.3    0.07       0
  4994.8    0.07       0  5000.6    0.07       0
Bank Sta=4994.8,5000.6
Exp/Cntr=0.3,0.1

Type RM Length L Ch R = 1,11474,469,469,469
BEGIN DESCRIPTION:
UCFB HW Trib 16 24.0
END DESCRIPTION:
XS GIS Cut Line= 3
      1292709.96      6942236.02      1292855.00      6941838.00
      1292996.41      6941407.03
#Sta/Elev= 30
  4580.3 2249.88  4612.5 2248.02  4684.6 2246.68  4810.6 2242.09  4815.9 2240.92
  4846.4 2239.82  4854.9 2238.41  4877.0 2238.23  4927.5 2235.52  4950.7 2231.75
  4972.0 2224.32  4998.3 2220.62  4998.8 2220.12  5004.2 2220.62  5051.7 2228.75
  5056.9 2227.08  5083.5 2233.50  5130.2 2239.48  5147.1 2244.15  5210.8 2246.22
  5256.5 2249.40  5288.1 2253.16  5369.9 2256.79  5401.7 2260.02  5407.0 2263.24
  5414.4 2265.29  5433.5 2266.64  5438.8 2269.27  5454.4 2263.86  5457.5 2263.86
#Mann=3,-1,0
  4580.3    0.07       0  4998.3    0.07       0  5004.2    0.07       0
Bank Sta=4998.3,5004.2
Exp/Cntr=0.3,0.1

Type RM Length L Ch R = 1,11005,452,452,452
BEGIN DESCRIPTION:
UCFB HW Trib 16 23.0
END DESCRIPTION:
XS GIS Cut Line= 5
      1292728.36      6942340.11      1293141.38      6942229.52
      1293205.00      6942138.00      1293250.75      6942069.80
      1293236.17      6941553.66
#Sta/Elev= 30
  4461.0 2250.11  4600.9 2242.28  4680.9 2239.33  4841.1 2236.05  4942.0 2235.75
  4963.5 2232.36  4971.7 2227.71  4977.8 2217.94  4989.6 2215.48  4990.1 2214.98
  4995.6 2215.48  5028.5 2218.52  5043.5 2221.47  5082.2 2225.48  5094.0 2225.73
  5103.9 2227.18  5108.9 2226.31  5134.0 2230.25  5154.0 2230.40  5174.0 2233.48
  5244.0 2238.57  5264.0 2237.95  5344.1 2239.72  5364.1 2241.26  5374.1 2240.79
  5404.1 2243.20  5424.1 2243.21  5554.1 2249.42  5574.2 2252.23  5598.5 2253.39
#Mann=3,-1,0
  4461.0    0.07       0  4989.6    0.07       0  4995.6    0.07       0
Bank Sta=4989.6,4995.6
Exp/Cntr=0.3,0.1

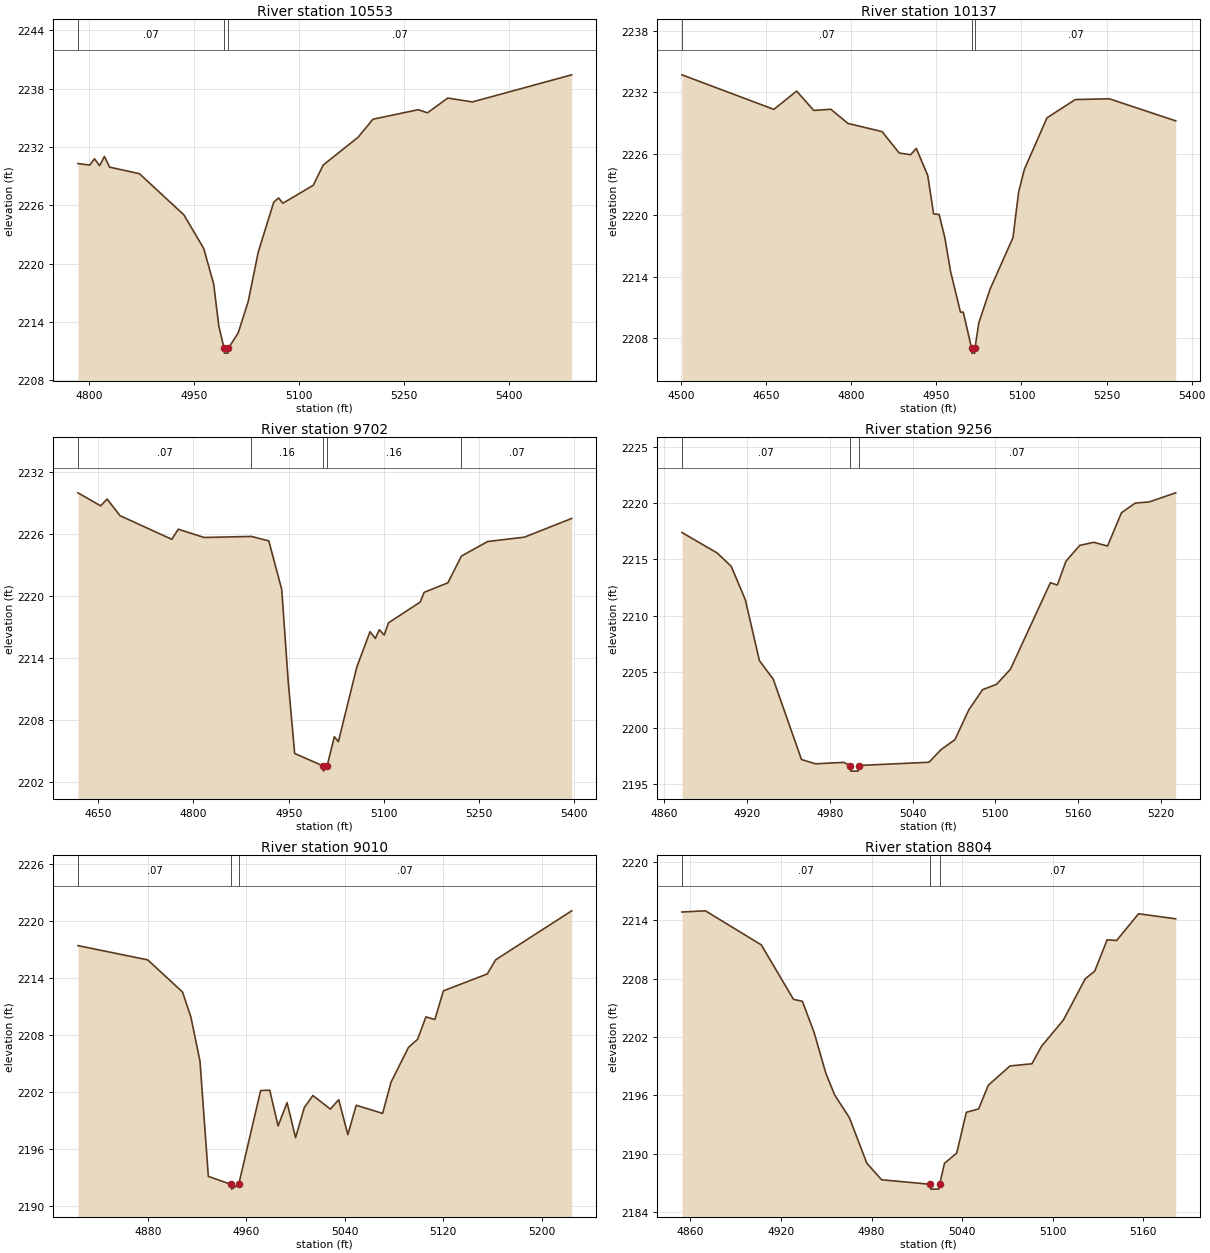
Type RM Length L Ch R = 1,10553,416,416,416
BEGIN DESCRIPTION:
UCFB HW Trib 16 22.0
END DESCRIPTION:
XS GIS Cut Line= 3
      1293448.05      6942434.74      1293605.00      6942288.00
      1293913.25      6941907.82
#Sta/Elev= 30
  4784.7 2230.29  4801.5 2230.13  4808.3 2230.78  4815.6 2230.07  4822.5 2231.02
  4829.8 2229.92  4872.3 2229.25  4935.8 2225.01  4964.1 2221.55  4978.3 2217.89
  4985.6 2213.57  4993.1 2211.28  4993.6 2210.78  4998.7 2210.78  4999.2 2211.28
  5013.2 2212.85  5027.6 2216.11  5041.9 2221.19  5063.9 2226.30  5070.7 2226.75
  5077.1 2226.21  5120.3 2228.05  5134.6 2230.14  5184.2 2232.99  5205.5 2234.85
  5269.9 2235.83  5283.3 2235.51  5312.1 2237.03  5347.3 2236.63  5489.0 2239.42
#Mann=3,-1,0
  4784.7    0.07       0  4993.1    0.07       0  4999.2    0.07       0
Bank Sta=4993.1,4999.2
Exp/Cntr=0.3,0.1

Type RM Length L Ch R = 1,10137,435,435,435
BEGIN DESCRIPTION:
UCFB HW Trib 16 21.0
END DESCRIPTION:
XS GIS Cut Line= 3
      1293113.74      6942592.71      1293605.00      6942638.00
      1293981.80      6942644.76
#Sta/Elev= 30
  4501.7 2233.68  4663.6 2230.31  4703.8 2232.09  4733.9 2230.21  4764.1 2230.32
  4794.2 2228.94  4854.4 2228.14  4884.6 2226.05  4904.7 2225.89  4914.7 2226.50
  4934.8 2223.87  4945.2 2220.11  4954.9 2220.06  4964.9 2217.81  4975.0 2214.52
  4992.5 2210.53  4997.5 2210.53  5012.0 2207.03  5012.5 2206.53  5017.6 2206.53
  5018.1 2207.03  5025.0 2209.51  5045.0 2212.81  5085.1 2217.80  5095.1 2222.26
  5105.1 2224.45  5145.1 2229.49  5195.1 2231.27  5255.1 2231.34  5371.9 2229.19
#Mann=3,-1,0
  4501.7    0.07       0  5012.0    0.07       0  5018.1    0.07       0
Bank Sta=5012,5018.1
Exp/Cntr=0.3,0.1

Type RM Length L Ch R = 1,9702,446,446,446
BEGIN DESCRIPTION:
UCFB HW Trib 16 20.0
END DESCRIPTION:
XS GIS Cut Line= 3
      1293230.01      6943113.00      1293605.00      6943038.00
      1293920.50      6942798.87
#Sta/Elev= 30
  4617.9 2230.02  4653.6 2228.76  4663.8 2229.42  4684.2 2227.81  4765.8 2225.52
  4776.0 2226.50  4816.7 2225.70  4891.3 2225.80  4918.7 2225.37  4939.1 2220.67
  4949.3 2211.78  4959.5 2204.80  5004.5 2203.59  5005.0 2203.09  5010.6 2203.59
  5022.1 2206.42  5028.4 2205.94  5057.5 2213.17  5078.3 2216.58  5086.6 2215.93
  5092.9 2216.77  5100.7 2216.26  5107.4 2217.44  5157.4 2219.45  5163.6 2220.39
  5201.0 2221.31  5222.4 2223.90  5263.8 2225.31  5321.7 2225.73  5396.2 2227.54
#Mann=5,-1,0
  4617.9    0.07       0  4891.3    0.16       0  5004.5    0.07       0
  5010.6    0.16       0  5222.4    0.07       0
Bank Sta=5004.5,5010.6
Exp/Cntr=0.3,0.1

Type RM Length L Ch R = 1,9256,246,246,246
BEGIN DESCRIPTION:
UCFB HW Trib 16 19.0
END DESCRIPTION:
XS GIS Cut Line= 3
      1293930.01      6943412.96      1293955.00      6943288.00
      1293979.09      6943058.90
#Sta/Elev= 30
  4872.9 2217.39  4898.4 2215.57  4908.6 2214.38  4918.8 2211.41  4929.0 2206.00
  4939.1 2204.33  4959.5 2197.20  4969.7 2196.82  4990.1 2196.95  4994.7 2196.67
  4995.2 2196.17  5000.4 2196.17  5000.9 2196.67  5051.9 2196.96  5060.7 2198.09
  5070.7 2198.97  5080.8 2201.63  5090.8 2203.42  5100.9 2203.89  5110.9 2205.23
  5139.9 2212.93  5144.9 2212.72  5151.2 2214.85  5161.2 2216.25  5171.3 2216.52
  5181.3 2216.19  5191.4 2219.15  5201.4 2220.01  5211.5 2220.11  5230.7 2220.92
#Mann=3,-1,0
  4872.9    0.07       0  4994.7    0.07       0  5000.9    0.07       0
Bank Sta=4994.7,5000.9
Exp/Cntr=0.3,0.1

Type RM Length L Ch R = 1,9010,206,206,206
BEGIN DESCRIPTION:
UCFB HW Trib 16 18.5
END DESCRIPTION:
XS GIS Cut Line= 2
      1294030.03      6943512.97      1294324.48      6943240.17
#Sta/Elev= 30
  4823.1 2217.43  4879.8 2215.93  4908.1 2212.55  4914.9 2209.92  4922.3 2205.27
  4929.1 2193.15  4947.5 2192.31  4948.0 2191.81  4953.8 2192.31  4971.6 2202.18
  4979.0 2202.22  4985.8 2198.46  4993.1 2200.91  5000.0 2197.23  5007.1 2200.39
  5014.1 2201.66  5028.3 2200.23  5035.1 2201.22  5042.5 2197.54  5049.3 2200.63
  5070.8 2199.78  5077.6 2203.05  5091.8 2206.72  5099.2 2207.57  5106.0 2209.93
  5113.3 2209.66  5120.2 2212.67  5155.9 2214.45  5162.7 2215.94  5224.5 2221.09
#Mann=3,-1,0
  4823.1    0.07       0  4947.5    0.07       0  4953.8    0.07       0
Bank Sta=4947.5,4953.8
Exp/Cntr=0.3,0.1

Type RM Length L Ch R = 1,8804,453,453,453
BEGIN DESCRIPTION:
UCFB HW Trib 16 18.0
END DESCRIPTION:
XS GIS Cut Line= 3
      1294180.01      6943612.99      1294305.00      6943538.00
      1294447.89      6943426.66
#Sta/Elev= 30
  4854.5 2214.85  4870.0 2214.97  4907.0 2211.47  4928.3 2205.87  4934.2 2205.67
  4941.9 2202.50  4949.7 2198.29  4955.6 2196.03  4965.3 2193.71  4976.9 2189.01
  4986.7 2187.31  5018.8 2186.85  5019.3 2186.35  5024.6 2186.35  5025.1 2186.85
  5028.3 2189.00  5036.4 2190.06  5042.8 2194.25  5050.9 2194.60  5057.3 2197.03
  5071.7 2199.02  5086.2 2199.24  5092.5 2201.03  5107.0 2203.73  5121.5 2207.98
  5127.8 2208.77  5136.0 2211.99  5142.3 2211.92  5156.8 2214.67  5181.4 2214.15
#Mann=3,-1,0
  4854.5    0.07       0  5018.8    0.07       0  5025.1    0.07       0
Bank Sta=5018.8,5025.1
Exp/Cntr=0.3,0.1

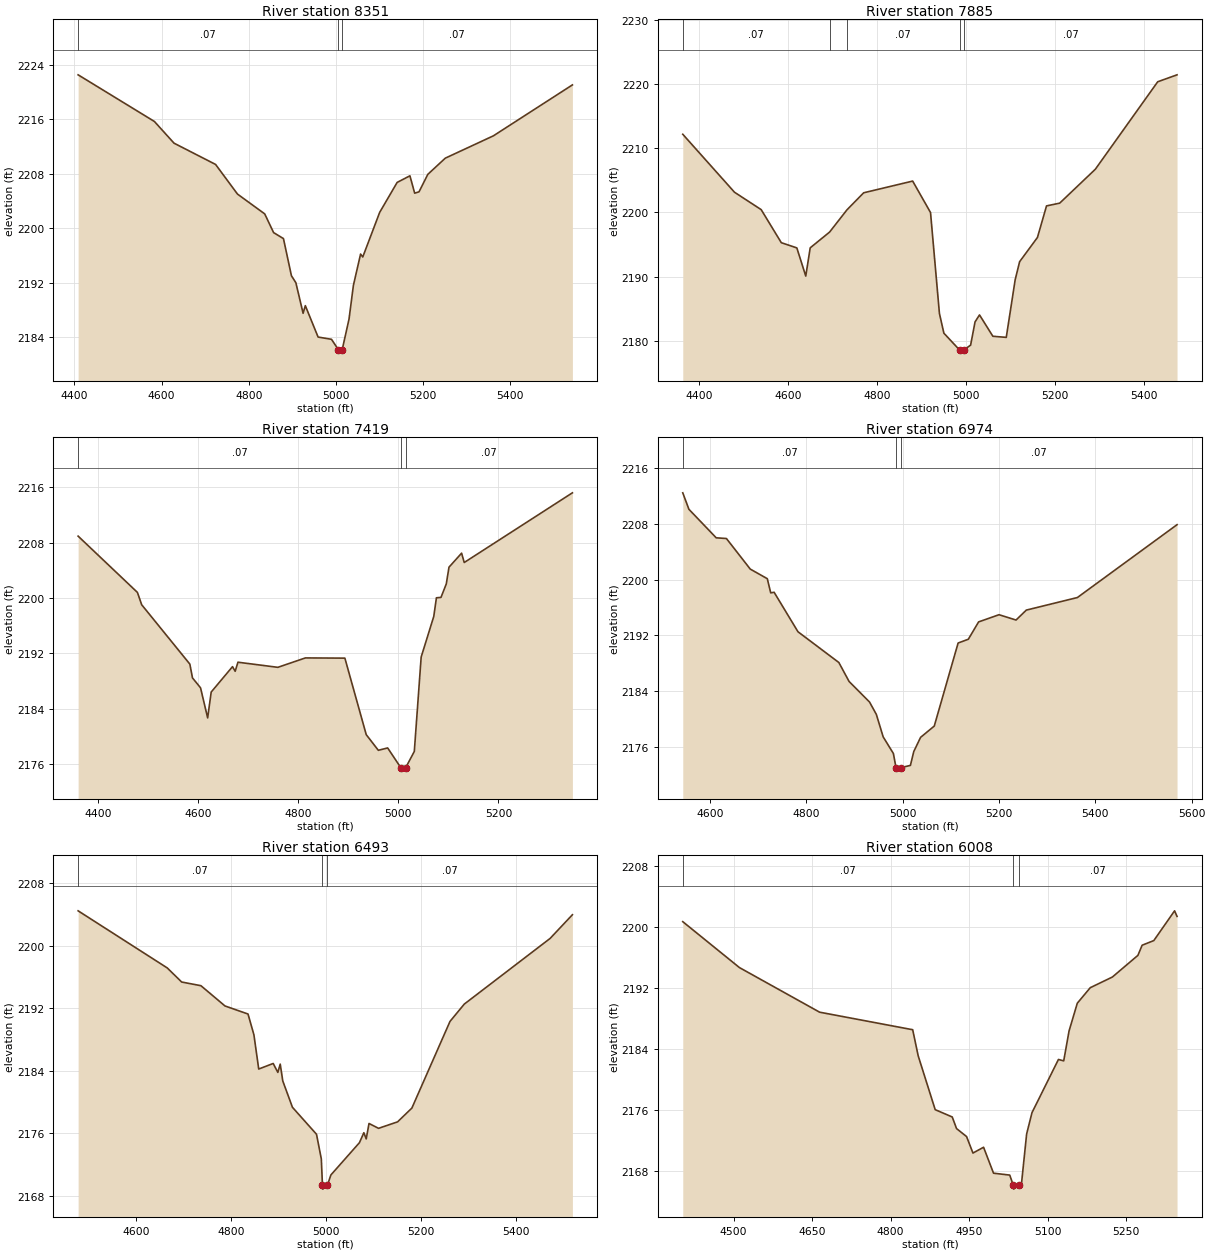
Type RM Length L Ch R = 1,8351,466,466,466
BEGIN DESCRIPTION:
UCFB HW Trib 16 17.0
END DESCRIPTION:
XS GIS Cut Line= 3
      1294585.12      6944267.20      1294705.00      6943688.00
      1294751.79      6943147.40
#Sta/Elev= 30
  4408.5 2222.55  4583.5 2215.70  4628.6 2212.51  4723.9 2209.39  4774.1 2205.04
  4836.6 2202.13  4857.0 2199.38  4879.6 2198.50  4897.9 2193.05  4908.1 2192.02
  4924.7 2187.53  4929.8 2188.65  4959.1 2184.04  4989.8 2183.71  5005.7 2182.18
  5006.2 2181.68  5014.4 2182.18  5030.1 2186.69  5040.1 2191.63  5056.6 2196.23
  5061.6 2195.80  5100.4 2202.35  5140.5 2206.75  5169.8 2207.72  5180.7 2205.17
  5190.7 2205.37  5210.8 2207.93  5250.9 2210.31  5361.3 2213.59  5542.6 2221.07
#Mann=3,-1,0
  4408.5    0.07       0  5005.7    0.07       0  5014.4    0.07       0
Bank Sta=5005.7,5014.4
Exp/Cntr=0.3,0.1

Type RM Length L Ch R = 1,7885,466,466,466
BEGIN DESCRIPTION:
UCFB HW Trib 16 16.0
END DESCRIPTION:
XS GIS Cut Line= 3
      1295132.00      6944374.01      1295155.00      6943738.00
      1295168.46      6943264.61
#Sta/Elev= 30
  4363.6 2212.16  4479.7 2203.15  4539.7 2200.44  4584.9 2195.30  4619.8 2194.49
  4639.8 2190.11  4649.8 2194.50  4693.3 2196.95  4732.5 2200.42  4769.9 2203.06
  4879.9 2204.88  4920.0 2199.99  4940.0 2184.29  4950.0 2181.23  4985.1 2178.63
  4985.6 2178.13  4994.9 2178.63  5010.0 2179.37  5020.0 2182.99  5030.0 2184.07
  5060.0 2180.75  5090.1 2180.58  5110.1 2189.54  5120.1 2192.35  5160.1 2196.11
  5180.5 2201.02  5210.1 2201.45  5290.1 2206.72  5430.2 2220.32  5473.6 2221.40
#Mann=5,-1,0
  4363.6    0.07       0  4693.3    0.16       0  4732.5    0.07       0
  4985.1    0.07       0  4994.9    0.07       0
Bank Sta=4985.1,4994.9
Exp/Cntr=0.3,0.1

Type RM Length L Ch R = 1,7419,445,445,445
BEGIN DESCRIPTION:
UCFB HW Trib 16 15.0
END DESCRIPTION:
XS GIS Cut Line= 3
      1295379.40      6944386.97      1295605.00      6943788.00
      1295725.18      6943461.46
#Sta/Elev= 30
  4359.9 2208.96  4478.4 2200.83  4487.0 2199.04  4583.2 2190.47  4588.5 2188.47
  4604.6 2187.04  4618.8 2182.69  4625.9 2186.43  4668.5 2190.10  4673.8 2189.43
  4679.4 2190.74  4759.1 2190.00  4814.2 2191.36  4893.1 2191.33  4935.8 2180.27
  4960.0 2178.01  4978.6 2178.35  5004.9 2175.50  5005.4 2175.00  5014.7 2175.50
  5031.9 2177.85  5045.6 2191.49  5070.8 2197.36  5076.1 2200.05  5085.2 2200.11
  5095.8 2202.05  5101.2 2204.47  5126.4 2206.50  5131.7 2205.15  5347.9 2215.22
#Mann=3,-1,0
  4359.9    0.07       0  5004.9    0.07       0  5014.7    0.07       0
Bank Sta=5004.9,5014.7
Exp/Cntr=0.3,0.1

Type RM Length L Ch R = 1,6974,481,481,481
BEGIN DESCRIPTION:
UCFB HW Trib 16 14.0
END DESCRIPTION:
XS GIS Cut Line= 3
      1295486.18      6944457.28      1295805.00      6944138.00
      1296207.54      6943728.11
#Sta/Elev= 30
  4544.0 2212.41  4556.8 2210.05  4613.4 2205.97  4634.6 2205.87  4684.1 2201.49
  4719.4 2200.12  4726.5 2198.09  4733.6 2198.17  4783.1 2192.52  4867.9 2188.12
  4889.1 2185.41  4931.6 2182.46  4945.7 2180.69  4959.9 2177.47  4981.1 2175.09
  4986.5 2173.07  4987.0 2172.57  4996.8 2173.07  5016.4 2173.39  5023.4 2175.38
  5037.6 2177.41  5065.9 2179.02  5115.4 2190.91  5136.6 2191.45  5157.9 2193.93
  5200.3 2194.96  5235.6 2194.20  5256.9 2195.62  5362.9 2197.42  5569.7 2207.85
#Mann=3,-1,0
  4544.0    0.07       0  4986.5    0.07       0  4996.8    0.07       0
Bank Sta=4986.5,4996.8
Exp/Cntr=0.3,0.1

Type RM Length L Ch R = 1,6493,485,485,485
BEGIN DESCRIPTION:
UCFB HW Trib 16 13.0
END DESCRIPTION:
XS GIS Cut Line= 3
      1296124.19      6944853.11      1296205.00      6944338.00
      1296236.06      6943821.14
#Sta/Elev= 30
  4478.6 2204.45  4666.0 2197.15  4696.3 2195.35  4736.8 2194.88  4787.4 2192.29
  4835.8 2191.26  4848.2 2188.60  4858.3 2184.23  4888.7 2184.94  4898.5 2183.80
  4903.5 2184.86  4908.9 2182.70  4929.2 2179.34  4979.8 2175.89  4989.9 2172.74
  4992.3 2169.38  4992.8 2168.88  5002.7 2169.38  5010.0 2170.69  5070.1 2174.82
  5079.3 2176.09  5084.3 2175.30  5090.2 2177.27  5110.2 2176.65  5150.3 2177.48
  5180.3 2179.24  5260.5 2190.32  5290.5 2192.53  5470.9 2200.92  5517.8 2203.95
#Mann=3,-1,0
  4478.6    0.07       0  4992.3    0.07       0  5002.7    0.07       0
Bank Sta=4992.3,5002.7
Exp/Cntr=0.3,0.1

Type RM Length L Ch R = 1,6008,472,472,472
BEGIN DESCRIPTION:
UCFB HW Trib 16 12.0
END DESCRIPTION:
XS GIS Cut Line= 3
      1296478.35      6944907.83      1296655.00      6944338.00
      1296710.06      6943994.16
#Sta/Elev= 30
  4402.8 2200.70  4511.1 2194.68  4664.4 2188.83  4842.3 2186.53  4852.8 2183.11
  4885.3 2176.05  4917.9 2175.09  4926.1 2173.57  4945.3 2172.52  4957.5 2170.36
  4977.8 2171.12  4996.8 2167.72  5027.8 2167.47  5034.7 2166.13  5035.2 2165.63
  5045.1 2166.13  5050.0 2166.17  5060.1 2172.86  5070.3 2175.65  5120.9 2182.63
  5131.0 2182.45  5141.2 2186.37  5156.9 2190.00  5181.7 2192.04  5224.0 2193.44
  5272.8 2196.28  5280.9 2197.61  5303.2 2198.22  5342.9 2202.12  5347.6 2201.39
#Mann=3,-1,0
  4402.8    0.07       0  5034.7    0.07       0  5045.1    0.07       0
Bank Sta=5034.7,5045.1
Exp/Cntr=0.3,0.1