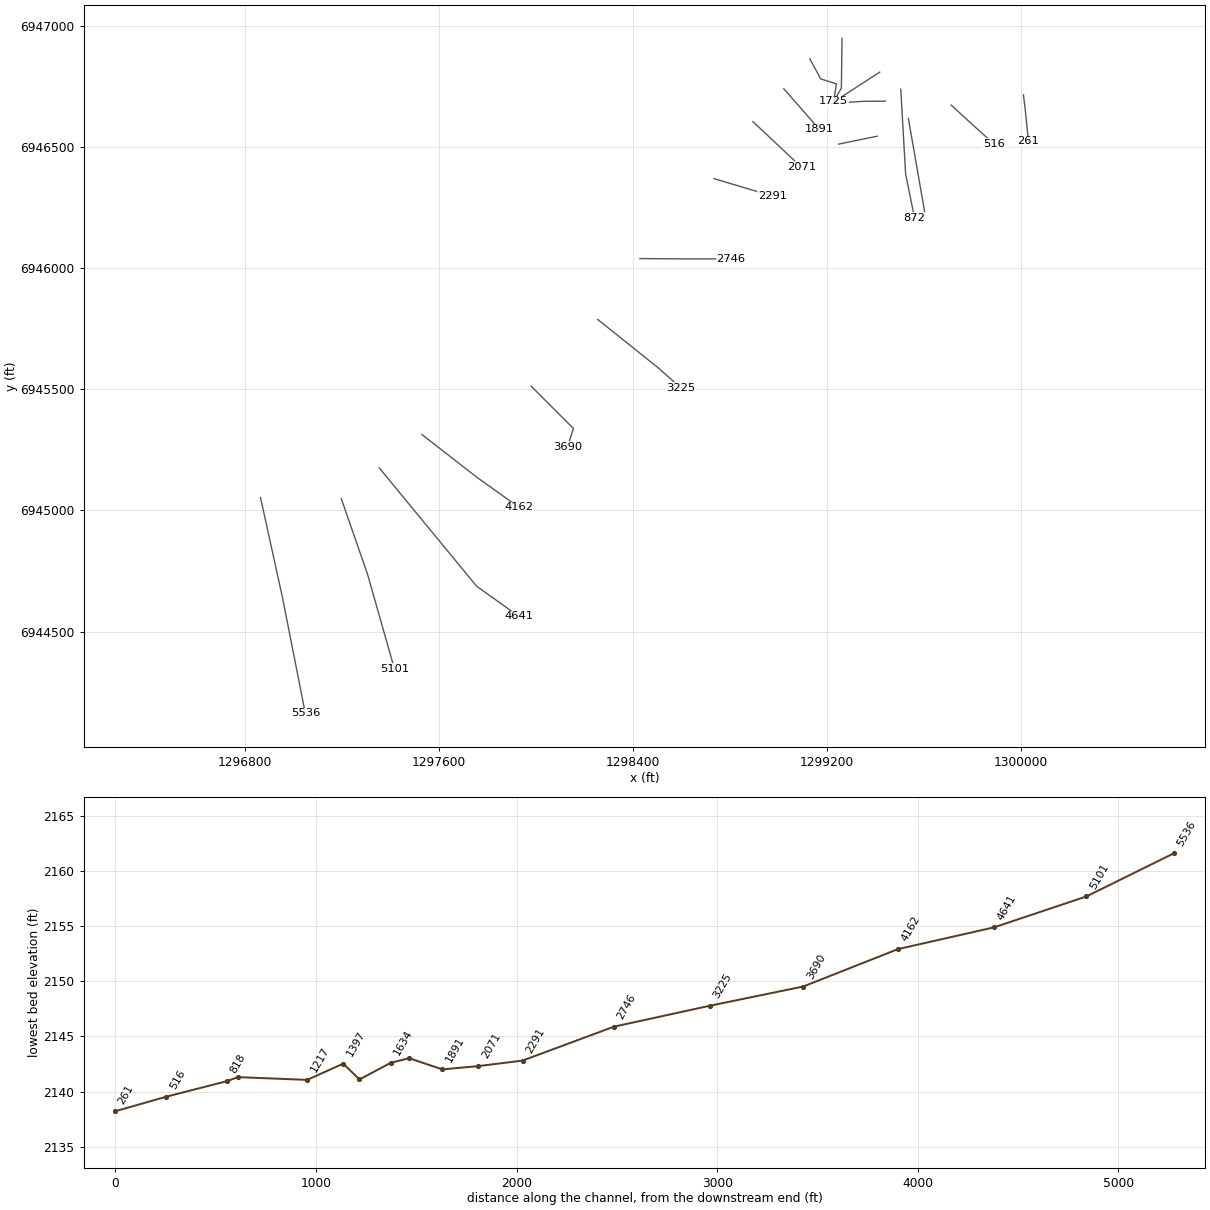
HEC-RAS study UCFB HW Trib 16.prj: UCFB HW Trib 16 Base Level Engineering

--- UCFB HW Trib 16.g01 (geometry) --- (continued)

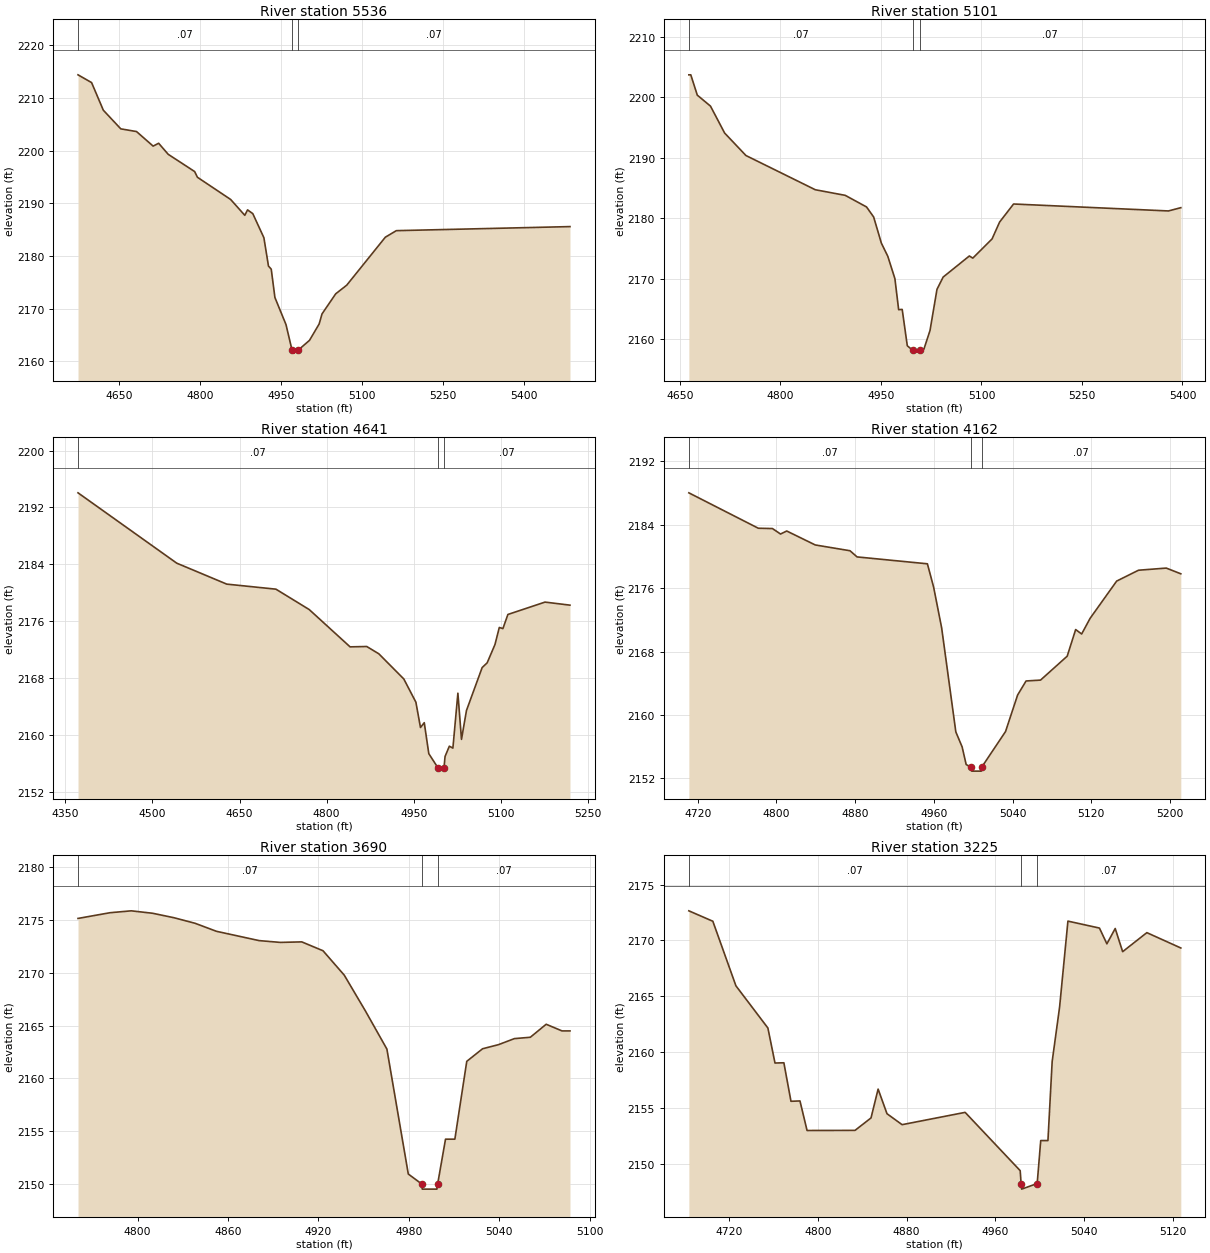
Type RM Length L Ch R = 1,5536,435,435,435
BEGIN DESCRIPTION:
UCFB HW Trib 16 11.0
END DESCRIPTION:
XS GIS Cut Line= 3
      1296863.77      6945053.67      1296955.00      6944638.00
      1297048.67      6944163.01
#Sta/Elev= 30
  4574.6 2214.37  4599.7 2212.90  4621.4 2207.66  4653.7 2204.12  4682.8 2203.61
  4713.5 2200.85  4723.7 2201.39  4741.3 2199.30  4790.3 2196.02  4795.4 2194.94
  4856.8 2190.73  4883.0 2187.72  4888.1 2188.75  4897.8 2188.04  4918.3 2183.48
  4926.8 2178.09  4931.9 2177.51  4938.7 2172.13  4959.2 2166.99  4970.5 2162.08
  4971.0 2161.58  4981.0 2162.08  5002.7 2164.01  5020.5 2167.11  5025.8 2169.02
  5051.1 2172.83  5071.5 2174.47  5142.9 2183.57  5163.2 2184.81  5484.3 2185.58
#Mann=3,-1,0
  4574.6    0.07       0  4970.5    0.07       0  4981.0    0.07       0
Bank Sta=4970.5,4981
Exp/Cntr=0.3,0.1

Type RM Length L Ch R = 1,5101,460,460,460
BEGIN DESCRIPTION:
UCFB HW Trib 16 10.0
END DESCRIPTION:
XS GIS Cut Line= 3
      1297197.10      6945048.47      1297305.00      6944738.00
      1297415.85      6944347.93
#Sta/Elev= 30
  4663.3 2203.72  4666.2 2203.72  4675.9 2200.36  4695.6 2198.54  4716.7 2194.09
  4748.5 2190.37  4852.0 2184.71  4896.7 2183.78  4928.5 2181.86  4939.1 2180.20
  4950.6 2175.88  4960.2 2173.70  4970.8 2170.01  4976.4 2164.87  4981.7 2164.91
  4989.3 2158.90  4997.1 2158.18  4997.6 2157.68  5007.7 2158.18  5014.1 2158.34
  5023.2 2161.42  5033.6 2168.23  5042.8 2170.26  5081.9 2173.75  5087.1 2173.40
  5115.8 2176.57  5127.1 2179.37  5147.9 2182.35  5379.0 2181.20  5397.5 2181.74
#Mann=3,-1,0
  4663.3    0.07       0  4997.1    0.07       0  5007.7    0.07       0
Bank Sta=4997.1,5007.7
Exp/Cntr=0.3,0.1

Type RM Length L Ch R = 1,4641,479,479,479
BEGIN DESCRIPTION:
UCFB HW Trib 16 9.0
END DESCRIPTION:
XS GIS Cut Line= 3
      1297353.38      6945176.02      1297755.00      6944688.00
      1297930.01      6944562.99
#Sta/Elev= 30
  4371.9 2194.05  4541.9 2184.15  4628.0 2181.20  4712.7 2180.49  4770.0 2177.62
  4840.4 2172.37  4869.1 2172.42  4889.9 2171.39  4932.9 2167.85  4953.7 2164.58
  4961.6 2161.02  4968.1 2161.70  4975.9 2157.34  4991.4 2155.38  4991.9 2154.88
  5002.1 2155.38  5003.9 2156.94  5011.3 2158.39  5017.4 2158.12  5026.0 2165.85
  5032.2 2159.35  5040.8 2163.42  5067.8 2169.46  5076.4 2170.12  5089.9 2172.71
  5097.3 2175.10  5103.5 2174.94  5112.1 2176.93  5176.0 2178.67  5219.0 2178.24
#Mann=3,-1,0
  4371.9    0.07       0  4991.4    0.07       0  5002.1    0.07       0
Bank Sta=4991.4,5002.1
Exp/Cntr=0.3,0.1

Type RM Length L Ch R = 1,4162,472,472,472
BEGIN DESCRIPTION:
UCFB HW Trib 16 8.0
END DESCRIPTION:
XS GIS Cut Line= 3
      1297530.02      6945312.98      1297755.00      6945138.00
      1297930.02      6945012.99
#Sta/Elev= 30
  4711.0 2188.04  4781.6 2183.57  4796.0 2183.53  4804.2 2182.84  4810.5 2183.22
  4839.5 2181.46  4874.8 2180.73  4882.0 2179.95  4953.5 2179.08  4959.8 2176.15
  4968.0 2170.98  4982.4 2157.86  4988.8 2155.97  4992.9 2153.74  4998.0 2153.41
  4998.5 2152.91  5008.2 2152.91  5008.7 2153.41  5032.9 2157.90  5045.2 2162.52
  5053.8 2164.29  5068.5 2164.40  5095.6 2167.42  5104.2 2170.78  5110.3 2170.22
  5118.9 2172.20  5145.9 2176.90  5168.1 2178.27  5196.3 2178.54  5211.1 2177.82
#Mann=3,-1,0
  4711.0    0.07       0  4998.0    0.07       0  5008.7    0.07       0
Bank Sta=4998,5008.7
Exp/Cntr=0.3,0.1

Type RM Length L Ch R = 1,3690,465,465,465
BEGIN DESCRIPTION:
UCFB HW Trib 16 7.0
END DESCRIPTION:
XS GIS Cut Line= 3
      1297980.03      6945512.97      1298155.00      6945338.00
      1298130.00      6945263.01
#Sta/Elev= 29
  4760.5 2175.15  4781.7 2175.69  4795.8 2175.87  4810.0 2175.64  4824.1 2175.22
  4838.2 2174.69  4852.4 2173.93  4880.7 2173.05  4894.8 2172.88  4909.0 2172.93
  4923.1 2172.09  4937.2 2169.78  4951.4 2166.35  4965.5 2162.78  4979.7 2150.95
  4988.5 2150.02  4989.0 2149.52  4998.7 2149.52  4999.2 2150.02  5004.4 2154.25
  5010.6 2154.25  5018.5 2161.62  5029.0 2162.81  5039.6 2163.20  5050.1 2163.77
  5060.7 2163.90  5071.2 2165.13  5081.7 2164.50  5087.0 2164.50
#Mann=3,-1,0
  4760.5    0.07       0  4988.5    0.07       0  4999.2    0.07       0
Bank Sta=4988.5,4999.2
Exp/Cntr=0.3,0.1

Type RM Length L Ch R = 1,3225,479,479,479
BEGIN DESCRIPTION:
UCFB HW Trib 16 6.0
END DESCRIPTION:
XS GIS Cut Line= 3
      1298255.00      6945788.00      1298505.00      6945588.00
      1298596.96      6945506.26
#Sta/Elev= 30
  4683.9 2172.65  4705.5 2171.72  4726.3 2165.95  4755.1 2162.18  4761.5 2159.05
  4769.5 2159.07  4775.9 2155.63  4784.0 2155.66  4790.4 2153.02  4833.6 2153.03
  4848.0 2154.14  4854.4 2156.72  4862.4 2154.52  4876.0 2153.54  4932.8 2154.64
  4982.4 2149.43  4983.2 2148.28  4983.7 2147.78  4997.7 2148.28  5000.9 2152.12
  5007.4 2152.12  5011.2 2159.18  5017.9 2164.05  5025.4 2171.73  5053.8 2171.11
  5060.5 2169.70  5068.0 2171.07  5074.7 2169.00  5096.5 2170.70  5127.1 2169.33
#Mann=3,-1,0
  4683.9    0.07       0  4983.2    0.07       0  4997.7    0.07       0
Bank Sta=4983.2,4997.7
Exp/Cntr=0.3,0.1

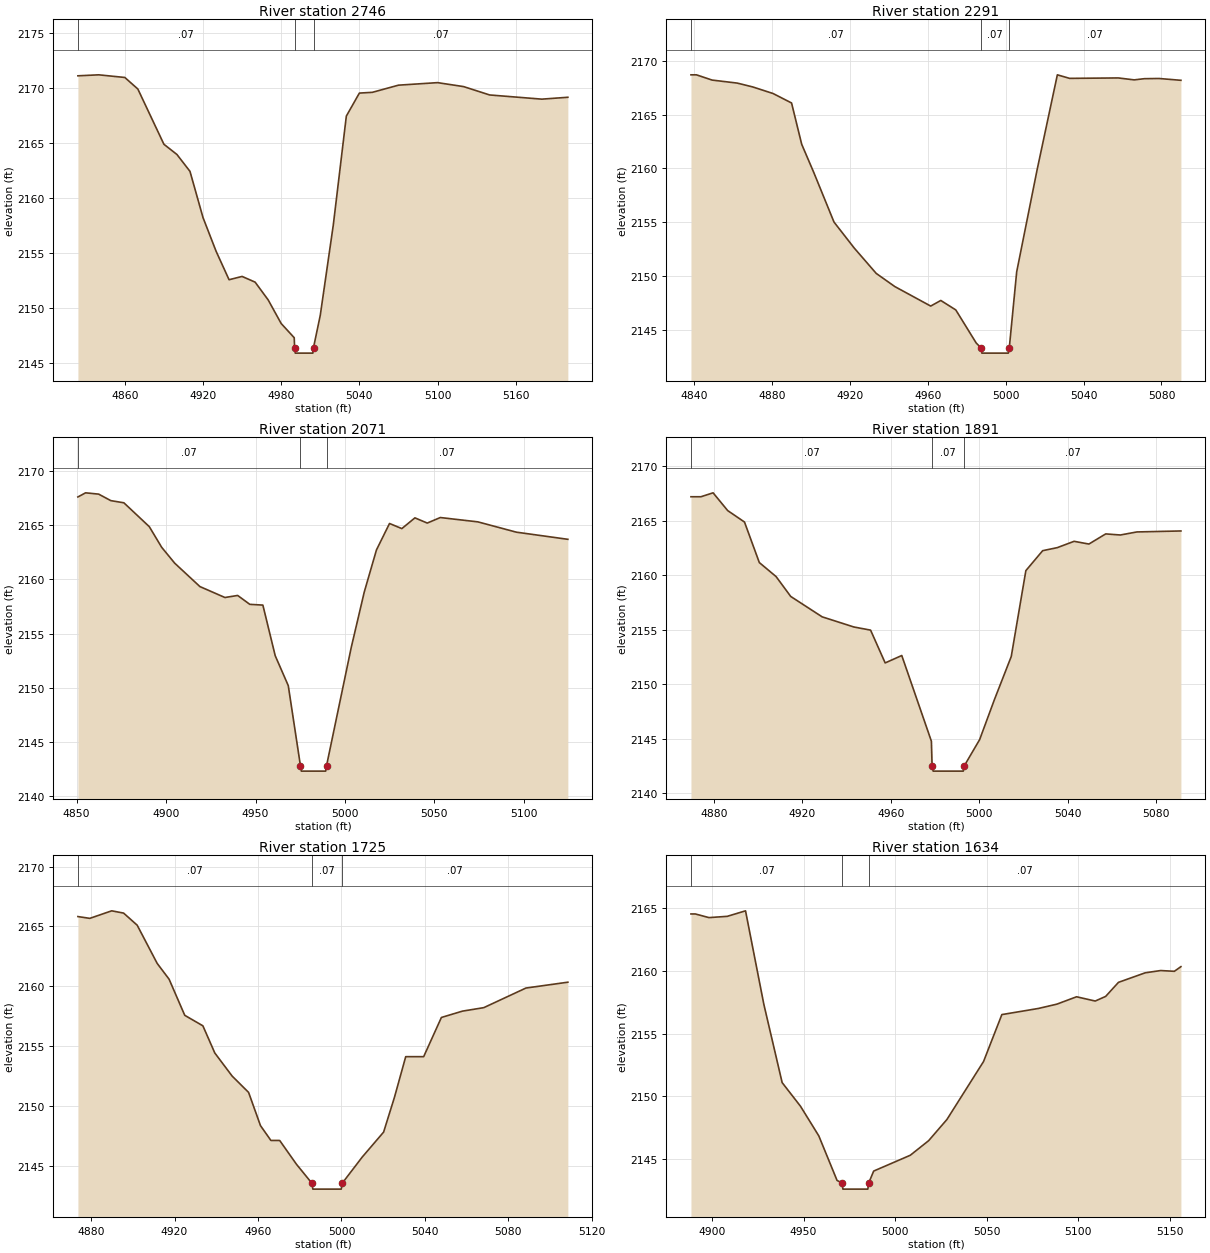
Type RM Length L Ch R = 1,2746,455,455,455
BEGIN DESCRIPTION:
UCFB HW Trib 16 5.0
END DESCRIPTION:
XS GIS Cut Line= 3
      1298428.99      6946039.15      1298605.00      6946038.00
      1298804.99      6946038.00
#Sta/Elev= 30
  4824.0 2171.08  4840.0 2171.17  4860.0 2170.93  4870.0 2169.88  4890.0 2164.86
  4900.0 2163.93  4910.0 2162.40  4920.0 2158.20  4930.0 2155.15  4940.0 2152.55
  4950.0 2152.85  4960.0 2152.33  4970.0 2150.72  4980.0 2148.57  4990.0 2147.28
  4990.3 2146.38  4990.8 2145.88  5004.3 2145.88  5004.8 2146.38  5010.0 2149.32
  5020.0 2157.53  5030.0 2167.42  5040.0 2169.51  5050.0 2169.58  5070.0 2170.23
  5100.0 2170.46  5120.0 2170.10  5140.0 2169.34  5180.0 2168.96  5200.0 2169.13
#Mann=3,-1,0
  4824.0    0.07       0  4990.3    0.07       0  5004.8    0.07       0
Bank Sta=4990.3,5004.8
Exp/Cntr=0.3,0.1

Type RM Length L Ch R = 1,2291,220,220,220
BEGIN DESCRIPTION:
UCFB HW Trib 16 4.0
END DESCRIPTION:
XS GIS Cut Line= 2
      1298734.56      6946369.00      1298975.84      6946296.96
#Sta/Elev= 30
  4838.2 2168.71  4841.0 2168.71  4849.1 2168.22  4862.0 2167.94  4870.0 2167.58
  4880.4 2166.97  4889.9 2166.09  4895.1 2162.25  4901.3 2159.63  4911.7 2155.01
  4922.1 2152.59  4933.4 2150.23  4943.0 2149.00  4961.4 2147.19  4966.6 2147.71
  4974.3 2146.83  4984.8 2143.75  4987.2 2143.31  4987.7 2142.81  5001.3 2142.81
  5001.8 2143.31  5005.6 2150.38  5016.1 2159.88  5026.5 2168.71  5032.8 2168.38
  5057.8 2168.42  5066.0 2168.24  5071.2 2168.35  5078.7 2168.37  5090.0 2168.20
#Mann=3,-1,0
  4838.2    0.07       0  4987.2    0.07       0  5001.8    0.07       0
Bank Sta=4987.2,5001.8
Exp/Cntr=0.3,0.1

Type RM Length L Ch R = 1,2071,180,180,180
BEGIN DESCRIPTION:
UCFB HW Trib 16 3.3
END DESCRIPTION:
XS GIS Cut Line= 2
      1298895.10      6946604.26      1299094.76      6946416.76
#Sta/Elev= 30
  4850.7 2167.61  4855.0 2167.99  4862.3 2167.87  4869.1 2167.27  4876.4 2167.07
  4890.6 2164.87  4897.5 2162.97  4904.8 2161.50  4918.9 2159.34  4932.9 2158.33
  4940.0 2158.52  4946.8 2157.70  4954.1 2157.63  4961.0 2152.96  4968.3 2150.20
  4975.1 2142.81  4975.6 2142.31  4989.2 2142.31  4989.7 2142.81  5003.5 2153.72
  5010.8 2158.85  5017.6 2162.72  5024.9 2165.16  5031.8 2164.69  5039.1 2165.68
  5046.0 2165.20  5053.3 2165.71  5074.3 2165.31  5095.8 2164.36  5124.6 2163.70
#Mann=3,-1,0
  4850.7    0.07       0  4975.1    0.07       0  4989.7    0.07       0
Bank Sta=4975.1,4989.7
Exp/Cntr=0.3,0.1

Type RM Length L Ch R = 1,1891,166,166,166
BEGIN DESCRIPTION:
UCFB HW Trib 16 3.15
END DESCRIPTION:
XS GIS Cut Line= 2
      1299022.70      6946739.69      1299168.56      6946572.99
#Sta/Elev= 30
  4869.6 2167.19  4874.1 2167.19  4879.6 2167.55  4886.2 2165.92  4893.8 2164.87
  4900.5 2161.15  4908.1 2159.86  4914.7 2158.04  4928.9 2156.17  4943.2 2155.24
  4950.8 2154.95  4957.4 2151.94  4964.9 2152.62  4978.3 2144.75  4978.6 2142.51
  4979.1 2142.01  4992.7 2142.01  4993.2 2142.51  5000.1 2144.90  5006.8 2148.58
  5014.4 2152.53  5021.0 2160.41  5028.6 2162.24  5035.2 2162.52  5042.8 2163.10
  5049.5 2162.85  5057.1 2163.78  5063.7 2163.68  5071.2 2163.96  5091.1 2164.05
#Mann=3,-1,0
  4869.6    0.07       0  4978.6    0.07       0  4993.2    0.07       0
Bank Sta=4978.6,4993.2
Exp/Cntr=0.3,0.1

Type RM Length L Ch R = 1,1725,91,91,91
BEGIN DESCRIPTION:
UCFB HW Trib 16 3.2
END DESCRIPTION:
XS GIS Cut Line= 4
      1299130.01      6946862.99      1299174.77      6946780.38
      1299239.87      6946759.77      1299227.95      6946688.20
#Sta/Elev= 30
  4873.7 2165.83  4879.4 2165.68  4889.9 2166.31  4895.6 2166.12  4902.1 2165.11
  4911.7 2161.91  4917.4 2160.59  4924.9 2157.57  4933.6 2156.69  4939.3 2154.42
  4947.6 2152.49  4955.5 2151.12  4961.2 2148.34  4966.2 2147.10  4970.4 2147.10
  4978.4 2145.12  4985.8 2143.53  4986.3 2143.03  4999.9 2143.03  5000.4 2143.53
  5009.9 2145.70  5020.2 2147.80  5025.4 2150.71  5030.8 2154.11  5039.4 2154.11
  5047.9 2157.39  5058.0 2157.92  5068.2 2158.21  5088.4 2159.85  5108.5 2160.34
#Mann=3,-1,0
  4873.7    0.07       0  4985.8    0.07       0  5000.4    0.07       0
Bank Sta=4985.8,5000.4
Exp/Cntr=0.3,0.1

Type RM Length L Ch R = 1,1634,156,156,156
BEGIN DESCRIPTION:
UCFB HW Trib 16 3.1
END DESCRIPTION:
XS GIS Cut Line= 3
      1299262.76      6946947.75      1299260.03      6946742.82
      1299229.14      6946688.31
#Sta/Elev= 30
  4888.5 2164.54  4890.9 2164.54  4898.3 2164.25  4908.3 2164.35  4918.3 2164.79
  4928.3 2157.34  4938.3 2151.10  4948.3 2149.22  4958.3 2146.86  4968.3 2143.30
  4971.0 2143.11  4971.5 2142.61  4985.1 2142.61  4985.6 2143.11  4988.3 2144.05
  5008.3 2145.31  5018.3 2146.47  5028.3 2148.16  5048.3 2152.78  5058.3 2156.52
  5078.3 2157.01  5088.3 2157.35  5099.1 2157.94  5109.3 2157.60  5115.0 2157.97
  5122.0 2159.09  5136.6 2159.85  5145.0 2160.03  5152.5 2159.97  5156.1 2160.34
#Mann=3,-1,0
  4888.5    0.07       0  4971.0    0.07       0  4985.6    0.07       0
Bank Sta=4971,4985.6
Exp/Cntr=0.3,0.1

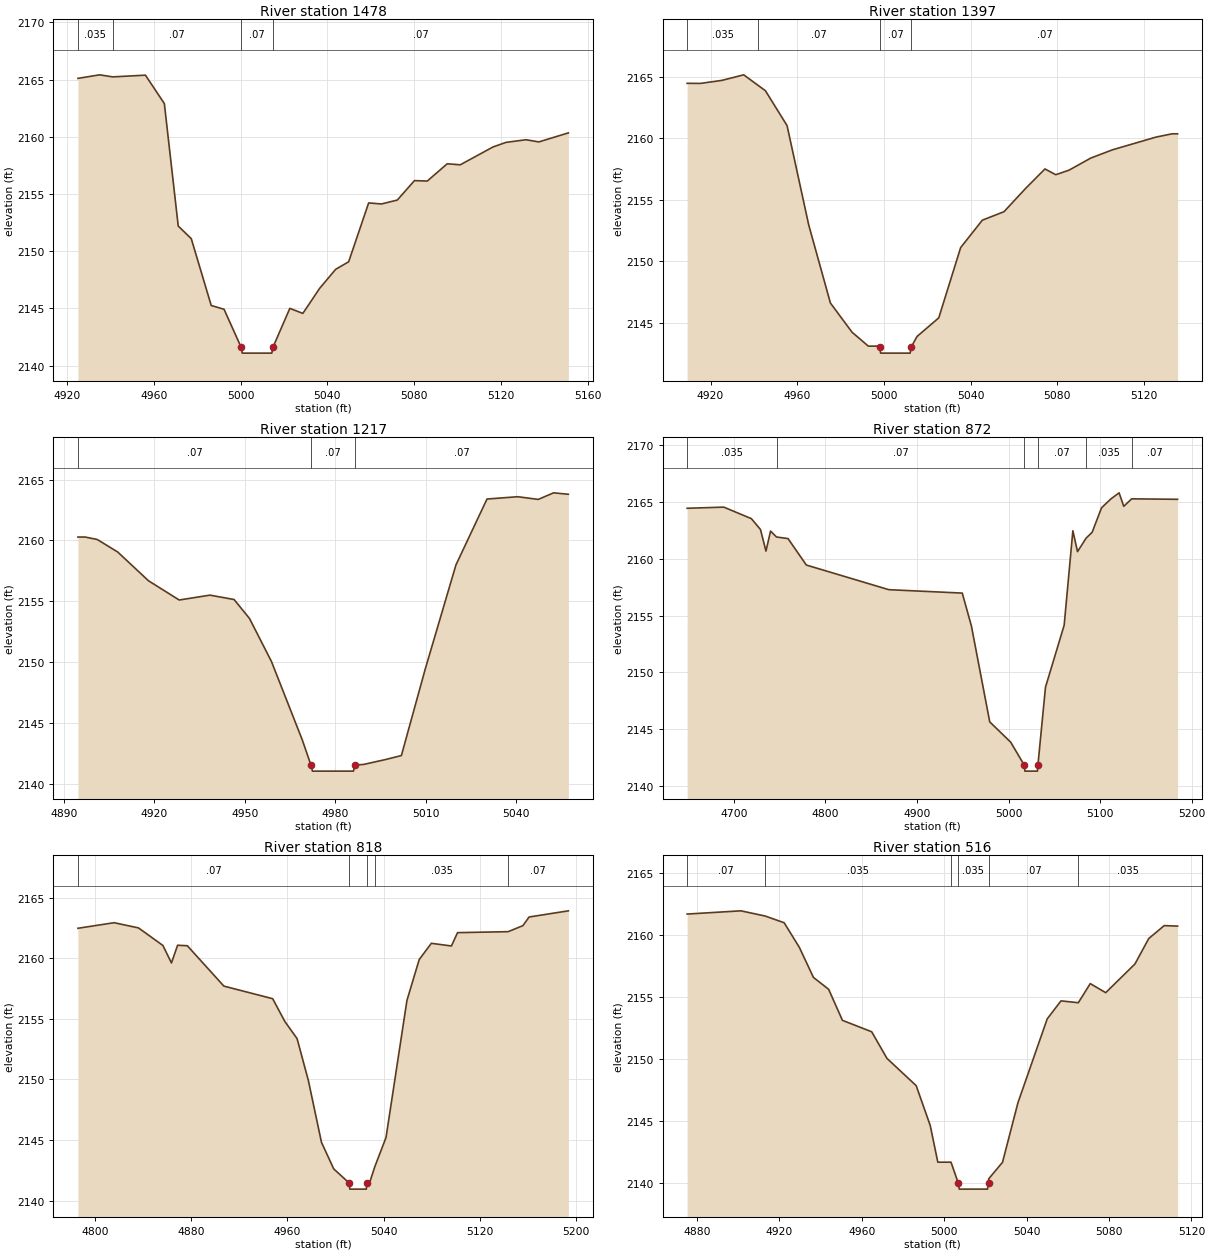
Type RM Length L Ch R = 1,1478,81,81,81
BEGIN DESCRIPTION:
UCFB HW Trib 16 3.05
END DESCRIPTION:
XS GIS Cut Line= 2
      1299418.36      6946808.44      1299228.88      6946685.45
#Sta/Elev= 30
  4925.1 2165.10  4935.1 2165.41  4941.1 2165.23  4956.2 2165.38  4964.9 2162.90
  4971.3 2152.20  4977.3 2151.10  4986.5 2145.26  4992.4 2144.93  5000.3 2141.60
  5000.8 2141.10  5014.4 2141.10  5014.9 2141.60  5022.7 2145.01  5028.7 2144.57
  5036.4 2146.75  5043.8 2148.42  5049.8 2149.08  5059.0 2154.22  5064.9 2154.13
  5072.2 2154.47  5080.1 2156.17  5086.0 2156.13  5095.2 2157.64  5101.2 2157.55
  5116.3 2159.11  5122.3 2159.51  5131.5 2159.74  5137.4 2159.55  5151.0 2160.34
#Mann=4,-1,0
  4925.1   0.035       0  4941.1    0.07       0  5000.3    0.07       0
  5014.9    0.07       0
Bank Sta=5000.3,5014.9
Exp/Cntr=0.3,0.1

Type RM Length L Ch R = 1,1397,180,180,180
BEGIN DESCRIPTION:
UCFB HW Trib 16 3.0
END DESCRIPTION:
XS GIS Cut Line= 3
      1299441.08      6946688.45      1299355.00      6946688.00
      1299215.04      6946679.55
#Sta/Elev= 30
  4909.2 2164.49  4915.3 2164.48  4925.3 2164.73  4935.3 2165.18  4942.1 2164.30
  4945.3 2163.89  4955.3 2161.05  4965.3 2152.96  4975.3 2146.61  4985.3 2144.23
  4992.8 2143.10  4997.8 2143.10  4998.0 2143.03  4998.5 2142.53  5012.1 2142.53
  5012.6 2143.03  5015.3 2143.89  5025.3 2145.40  5035.4 2151.12  5045.4 2153.35
  5055.4 2154.04  5065.4 2155.94  5074.3 2157.52  5079.3 2157.05  5085.4 2157.42
  5095.5 2158.41  5105.5 2159.08  5125.5 2160.11  5133.0 2160.38  5135.5 2160.38
#Mann=4,-1,0
  4909.2   0.035       0  4942.1    0.07       0  4998.0    0.07       0
  5012.6    0.07       0
Bank Sta=4998,5012.6
Exp/Cntr=0.3,0.1

Type RM Length L Ch R = 1,1217,345,345,345
BEGIN DESCRIPTION:
UCFB HW Trib 16 2.5
END DESCRIPTION:
XS GIS Cut Line= 2
      1299407.90      6946543.95      1299248.50      6946511.35
#Sta/Elev= 25
  4894.7 2160.28  4897.1 2160.28  4901.1 2160.08  4907.9 2159.05  4918.1 2156.69
  4928.3 2155.11  4938.5 2155.51  4946.5 2155.15  4951.6 2153.60  4958.9 2150.06
  4969.1 2143.64  4972.0 2141.56  4972.5 2141.06  4986.1 2141.06  4986.6 2141.56
  4989.5 2141.61  4996.9 2142.02  5002.0 2142.34  5009.9 2149.43  5020.1 2157.99
  5030.4 2163.40  5040.6 2163.59  5047.4 2163.37  5052.5 2163.91  5057.4 2163.79
#Mann=3,-1,0
  4894.7    0.07       0  4972.0    0.07       0  4986.6    0.07       0
Bank Sta=4972,4986.6
Exp/Cntr=0.3,0.1

Type RM Length L Ch R = 1,872,54,54,54
BEGIN DESCRIPTION:
UCFB HW Trib 16 2.0
END DESCRIPTION:
XS GIS Cut Line= 3
      1299505.00      6946737.97      1299525.13      6946387.45
      1299561.94      6946206.56
#Sta/Elev= 30
  4648.9 2164.46  4688.9 2164.56  4719.0 2163.55  4729.0 2162.59  4735.0 2160.69
  4740.0 2162.45  4746.5 2161.93  4759.1 2161.79  4779.1 2159.46  4869.2 2157.29
  4949.4 2156.99  4959.4 2154.09  4979.4 2145.65  5002.3 2143.86  5017.3 2141.81
  5017.8 2141.31  5031.5 2141.31  5032.0 2141.81  5040.3 2148.70  5060.7 2154.16
  5070.2 2162.48  5075.3 2160.64  5084.6 2161.82  5091.3 2162.35  5101.5 2164.50
  5111.7 2165.28  5120.7 2165.82  5125.8 2164.63  5134.4 2165.29  5184.6 2165.25
#Mann=6,-1,0
  4648.9   0.035       0  4746.5    0.07       0  5017.3    0.07       0
  5032.0    0.07       0  5084.6   0.035       0  5134.4    0.07       0
Bank Sta=5017.3,5032
Exp/Cntr=0.3,0.1

Type RM Length L Ch R = 1,818,302,302,302
BEGIN DESCRIPTION:
UCFB HW Trib 16 1.5
END DESCRIPTION:
XS GIS Cut Line= 2
      1299536.26      6946617.61      1299606.49      6946215.70
#Sta/Elev= 30
  4785.7 2162.47  4815.8 2162.93  4836.1 2162.50  4856.4 2161.05  4863.5 2159.61
  4868.6 2161.07  4876.7 2161.03  4907.1 2157.70  4947.7 2156.66  4957.9 2154.77
  4968.0 2153.37  4977.4 2149.91  4988.3 2144.81  4998.5 2142.62  5011.4 2141.45
  5011.9 2140.95  5025.6 2140.95  5026.1 2141.45  5028.9 2141.65  5032.7 2142.81
  5042.0 2145.21  5059.4 2156.52  5069.6 2159.89  5079.7 2161.23  5096.4 2161.01
  5101.5 2162.11  5143.6 2162.19  5155.9 2162.69  5161.0 2163.40  5193.7 2163.91
#Mann=5,-1,0
  4785.7    0.07       0  5011.4    0.07       0  5026.1    0.07       0
  5032.7   0.035       0  5143.6    0.07       0
Bank Sta=5011.4,5026.1
Exp/Cntr=0.3,0.1

Type RM Length L Ch R = 1,516,255,255,255
BEGIN DESCRIPTION:
UCFB HW Trib 16 1.0
END DESCRIPTION:
XS GIS Cut Line= 3
      1299712.81      6946672.54      1299805.00      6946588.00
      1299889.08      6946512.48
#Sta/Elev= 30
  4875.2 2161.69  4901.3 2161.95  4913.1 2161.53  4922.3 2160.99  4929.7 2159.00
  4936.5 2156.59  4943.9 2155.63  4950.6 2153.13  4964.8 2152.21  4972.2 2150.07
  4986.4 2147.87  4993.2 2144.67  4996.9 2141.71  5003.3 2141.71  5006.8 2140.04
  5007.3 2139.54  5021.0 2139.54  5021.5 2140.04  5021.6 2140.37  5028.3 2141.70
  5035.8 2146.50  5050.0 2153.25  5056.7 2154.70  5065.1 2154.55  5070.9 2156.09
  5078.4 2155.36  5092.6 2157.67  5099.3 2159.72  5106.8 2160.76  5113.3 2160.72
#Mann=6,-1,0
  4875.2    0.07       0  4913.1   0.035       0  5003.3    0.07       0
  5006.8   0.035       0  5021.5    0.07       0  5065.1   0.035       0
Bank Sta=5006.8,5021.5
Exp/Cntr=0.3,0.1

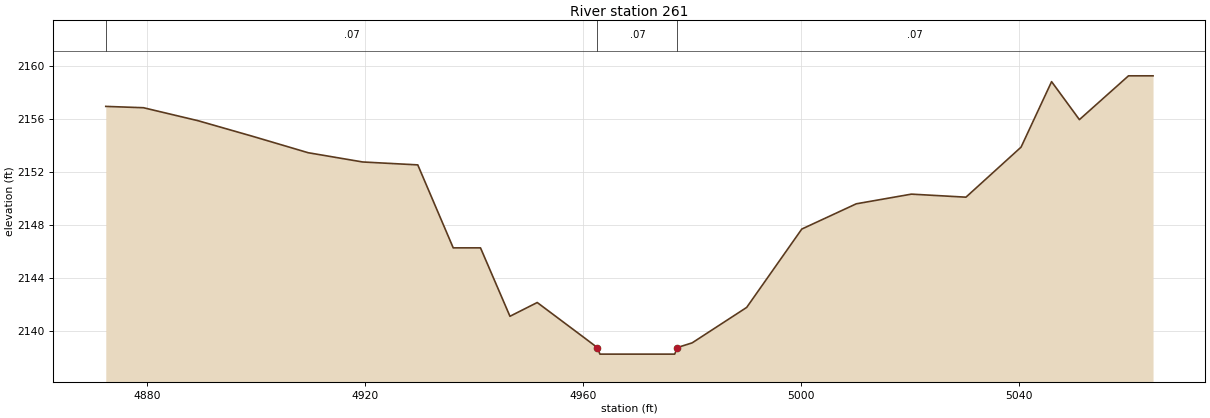
Type RM Length L Ch R = 1,261,0,0,0
BEGIN DESCRIPTION:
UCFB HW Trib 16 0.5
END DESCRIPTION:
XS GIS Cut Line= 3
      1300011.22      6946714.80      1300018.91      6946650.06
      1300031.83      6946523.92
#Sta/Elev= 27
  4872.5 2156.94  4879.4 2156.84  4889.4 2155.86  4899.5 2154.67  4909.6 2153.44
  4919.6 2152.74  4929.7 2152.52  4936.2 2146.25  4941.2 2146.25  4946.6 2141.08
  4951.6 2142.12  4959.9 2139.56  4962.6 2138.72  4963.1 2138.22  4976.8 2138.22
  4977.3 2138.72  4980.0 2139.07  4990.0 2141.75  5000.1 2147.67  5010.1 2149.58
  5020.2 2150.31  5030.2 2150.08  5040.3 2153.86  5045.9 2158.81  5051.0 2155.94
  5060.0 2159.25  5064.5 2159.25
#Mann=3,-1,0
  4872.5    0.07       0  4962.6    0.07       0  4977.3    0.07       0
Bank Sta=4962.6,4977.3
Exp/Cntr=0.3,0.1

Chan Stop Cuts=-1