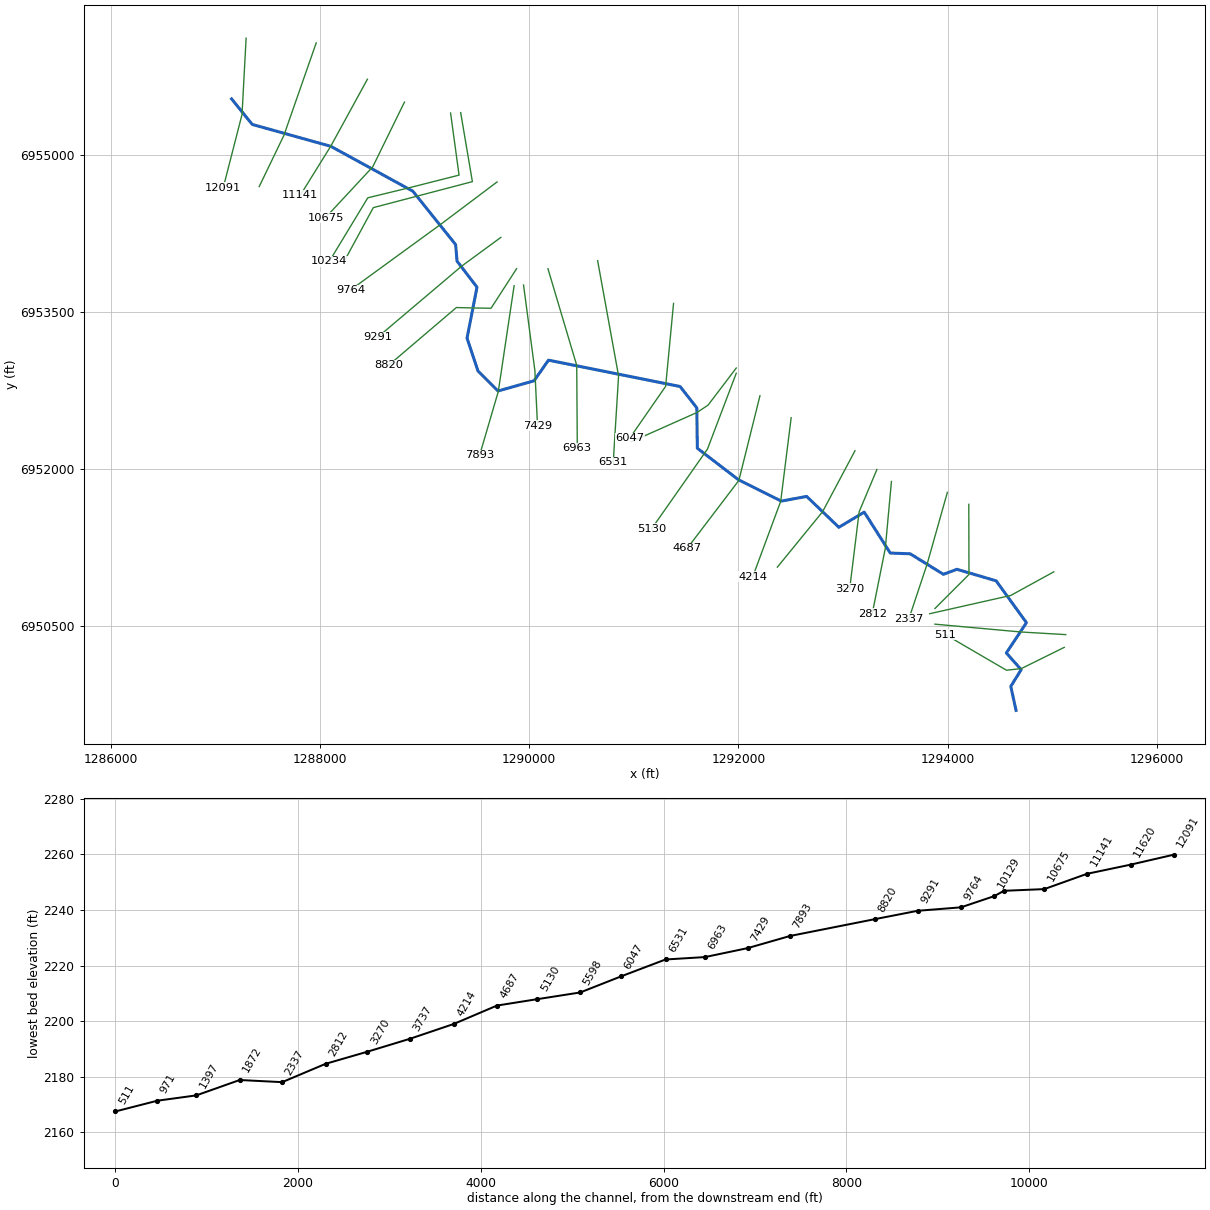
--- UCFB HW Trib 17.prj (project) ---

Proj Title=UCFB HW Trib 17 Base Level Engineering
Current Plan=p01
Default Exp/Contr=0.3,0.1
English Units
Geom File=g01
Flow File=f01
Plan File=p01
BEGIN DESCRIPTION:
UCFB HW Trib 17
END DESCRIPTION:

--- UCFB HW Trib 17.p01 (plan) ---

Plan Title=Multiple Run
Short Identifier=Multiple
Geom File=g01
Flow File=f01
Subcritical Flow
K Sum by GR= 0
Std Step Tol= 0.01
Critical Tol= 0.01
Num of Std Step Trials= 20
Max Error Tol= 0.3
Flow Tol Ratio= 0.001
Split Flow NTrial= 30
Split Flow Tol= 0.02
Split Flow Ratio= 0.02
Log Output Level= 0
Friction Slope Method= 1
Unsteady Friction Slope Method= 2
Unsteady Bridges Friction Slope Method= 1
Parabolic Critical Depth
Global Vel Dist=  1 , 1 , 1
Global Log Level= 0
CheckData=True
Encroach Param= -1, 0, 0, 0
BEGIN DESCRIPTION:
Multiple Run
END DESCRIPTION:

--- UCFB HW Trib 17.f01 (steady flow) ---

Flow Title=Multiple
Number of Profiles=7
Profile Names=10-year,25-year,50-year,1pct_min,100-year,1pct_plu,500-year
River Rch & RM= UCFB HW Trib 17,Reach-1,12091
     467     685     874     554    1106    2207    1795
River Rch & RM= UCFB HW Trib 17,Reach-1,6047
     575     852    1095     699    1394    2781    2290
River Rch & RM= UCFB HW Trib 17,Reach-1,2812
     707    1059    1370     879    1755    3501    2920
River Rch & RM= UCFB HW Trib 17,Reach-1,1397
     725    1085    1403     901    1797    3586    2989
Boundary for River Rch & Prof#=UCFB HW Trib 17,Reach-1,1
Up Type=0
Dn Type=3
Dn Slope=0.005
Boundary for River Rch & Prof#=UCFB HW Trib 17,Reach-1,2
Up Type=0
Dn Type=3
Dn Slope=0.005
Boundary for River Rch & Prof#=UCFB HW Trib 17,Reach-1,3
Up Type=0
Dn Type=3
Dn Slope=0.005
Boundary for River Rch & Prof#=UCFB HW Trib 17,Reach-1,4
Up Type=0
Dn Type=3
Dn Slope=0.005
Boundary for River Rch & Prof#=UCFB HW Trib 17,Reach-1,5
Up Type=0
Dn Type=3
Dn Slope=0.005
Boundary for River Rch & Prof#=UCFB HW Trib 17,Reach-1,6
Up Type=0
Dn Type=3
Dn Slope=0.005
Boundary for River Rch & Prof#=UCFB HW Trib 17,Reach-1,7
Up Type=0
Dn Type=3
Dn Slope=0.005

--- UCFB HW Trib 17.g01 (geometry) ---

Geom Title=Existing Conditions

River Reach=UCFB HW Trib 17,Reach-1
Reach XY= 30
      1287155.00      6955538.00      1287352.55      6955293.47
      1288103.44      6955084.24      1288888.35      6954654.67
      1289297.17      6954144.18      1289310.71      6953985.65
      1289501.47      6953736.53      1289406.22      6953248.50
      1289510.52      6952935.57      1289702.55      6952743.45
      1290046.99      6952841.03      1290184.82      6953038.43
      1291443.17      6952786.38      1291602.95      6952582.14
      1291607.95      6952195.98      1292002.57      6951893.52
      1292410.94      6951690.25      1292653.37      6951734.87
      1292961.05      6951439.58      1293203.36      6951584.91
      1293452.30      6951193.36      1293643.05      6951186.08
      1293961.11      6950989.80      1294089.60      6951037.90
      1294464.79      6950927.48      1294754.45      6950527.36
      1294562.08      6950238.00      1294704.07      6950077.51
      1294604.88      6949917.73      1294655.00      6949688.00

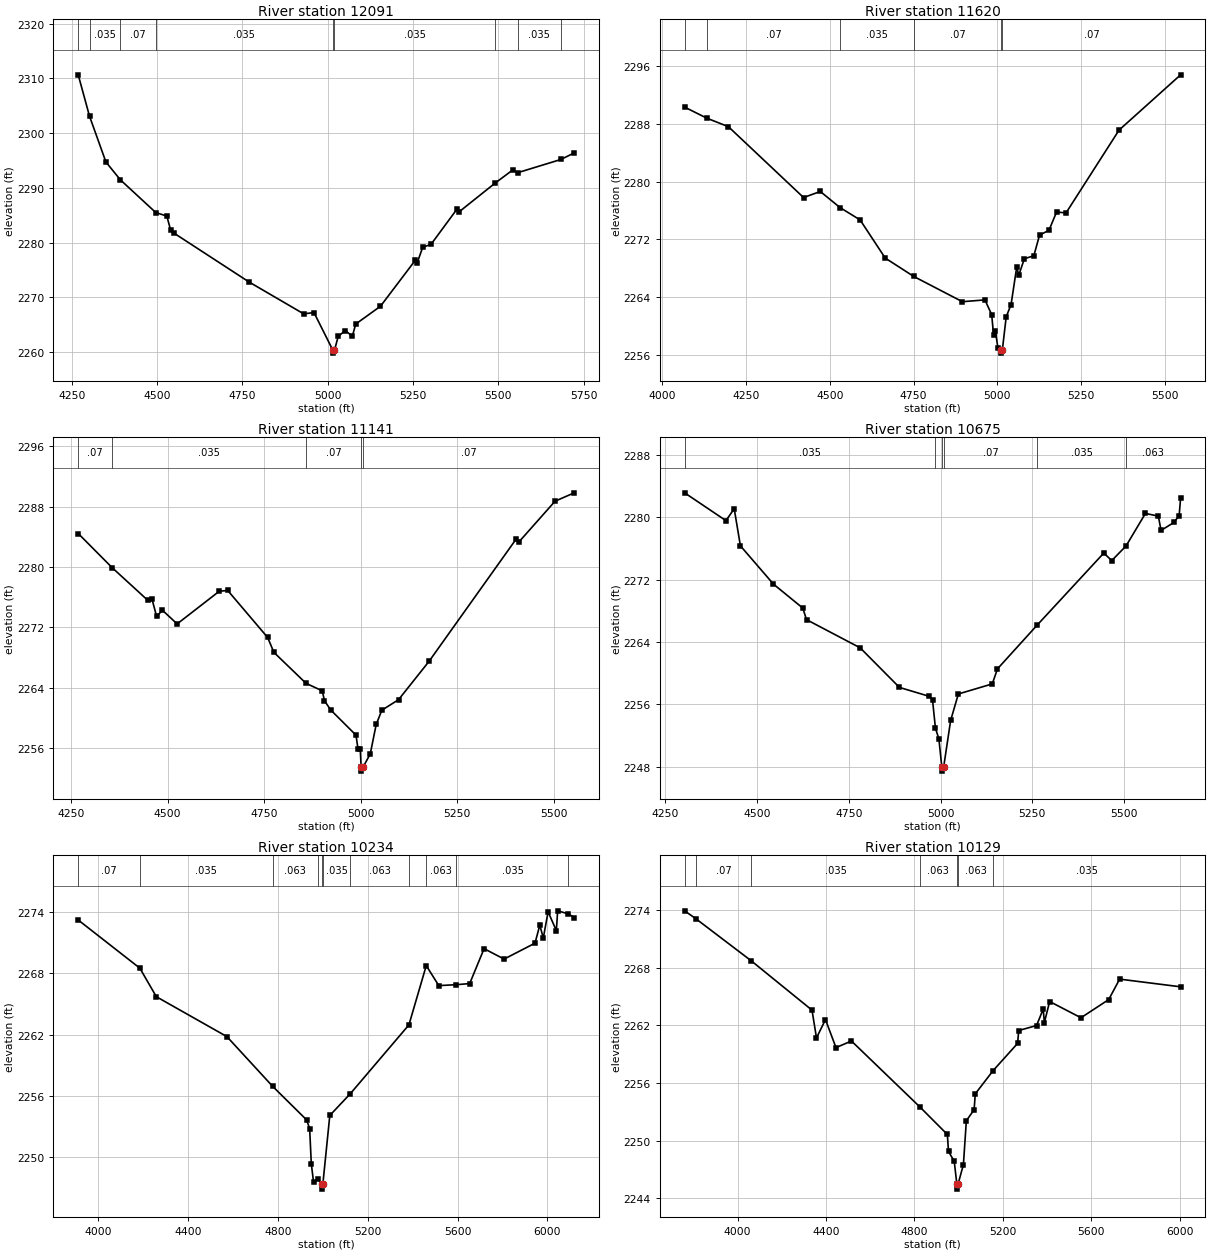
Type RM Length L Ch R = 1,12091,471,471,471
BEGIN DESCRIPTION:
UCFB HW Trib 17 25.0
END DESCRIPTION:
XS GIS Cut Line= 3
      1287294.11      6956118.30      1287255.00      6955388.00
      1287075.36      6954687.72
#Sta/Elev= 30
  4268.4 2310.65  4301.5 2303.10  4349.6 2294.73  4392.0 2291.47  4496.1 2285.48
  4528.2 2284.86  4539.1 2282.36  4549.1 2281.74  4769.4 2272.81  4929.6 2266.99
  4959.7 2267.23  5015.3 2260.32  5015.6 2259.82  5019.7 2260.32  5030.7 2262.87
  5051.4 2263.95  5072.0 2262.90  5082.3 2265.14  5154.6 2268.38  5257.0 2276.80
  5262.2 2276.30  5278.5 2279.15  5302.9 2279.69  5379.3 2286.15  5384.5 2285.59
  5490.7 2290.87  5542.4 2293.27  5556.7 2292.77  5683.6 2295.19  5722.7 2296.39
#Mann=9,-1,0
  4268.4    0.07       0  4301.5   0.035       0  4392.0    0.07       0
  4496.1   0.035       0  5015.3   0.035       0  5019.7   0.035       0
  5490.7    0.07       0  5556.7   0.035       0  5683.6    0.07       0
Bank Sta=5015.3,5019.7
Exp/Cntr=0.3,0.1

Type RM Length L Ch R = 1,11620,479,479,479
BEGIN DESCRIPTION:
UCFB HW Trib 17 24.0
END DESCRIPTION:
XS GIS Cut Line= 3
      1287964.26      6956073.15      1287655.00      6955188.00
      1287419.56      6954699.06
#Sta/Elev= 30
  4066.9 2290.31  4133.6 2288.77  4197.6 2287.60  4421.9 2277.79  4471.8 2278.63
  4530.5 2276.41  4590.7 2274.69  4665.6 2269.41  4751.0 2266.86  4895.9 2263.37
  4963.2 2263.62  4983.3 2261.58  4989.0 2258.78  4994.3 2259.35  5001.9 2256.97
  5010.8 2256.75  5011.1 2256.25  5015.3 2256.75  5026.7 2261.28  5041.2 2262.98
  5058.3 2268.24  5063.9 2267.01  5080.9 2269.32  5109.1 2269.73  5126.2 2272.59
  5154.4 2273.26  5177.0 2275.79  5205.2 2275.66  5363.5 2287.13  5547.2 2294.78
#Mann=6,-1,0
  4066.9   0.035       0  4133.6    0.07       0  4530.5   0.035       0
  4751.0    0.07       0  5010.8    0.07       0  5015.3    0.07       0
Bank Sta=5010.8,5015.3
Exp/Cntr=0.3,0.1

Type RM Length L Ch R = 1,11141,466,466,466
BEGIN DESCRIPTION:
UCFB HW Trib 17 23.0
END DESCRIPTION:
XS GIS Cut Line= 3
      1288453.83      6955725.89      1288105.00      6955088.00
      1287811.47      6954614.78
#Sta/Elev= 30
  4268.8 2284.43  4356.5 2279.91  4449.0 2275.57  4459.4 2275.81  4471.6 2273.46
  4486.9 2274.25  4524.9 2272.45  4634.0 2276.78  4655.8 2276.88  4759.2 2270.65
  4775.3 2268.68  4858.4 2264.58  4900.5 2263.58  4906.2 2262.28  4922.3 2261.05
  4987.8 2257.71  4993.0 2255.90  4998.8 2255.90  5001.2 2253.44  5001.5 2252.94
  5005.9 2253.44  5024.8 2255.23  5040.1 2259.12  5054.7 2261.01  5098.0 2262.41
  5177.1 2267.50  5402.8 2283.72  5408.7 2283.26  5503.1 2288.71  5552.7 2289.82
#Mann=5,-1,0
  4268.8    0.07       0  4356.5   0.035       0  4858.4    0.07       0
  5001.2    0.07       0  5005.9    0.07       0
Bank Sta=5001.2,5005.9
Exp/Cntr=0.3,0.1

Type RM Length L Ch R = 1,10675,441,441,441
BEGIN DESCRIPTION:
UCFB HW Trib 17 22.0
END DESCRIPTION:
XS GIS Cut Line= 3
      1288807.99      6955507.13      1288505.00      6954888.00
      1288054.55      6954403.01
#Sta/Elev= 30
  4302.7 2283.10  4415.2 2279.54  4437.8 2281.06  4454.7 2276.31  4544.7 2271.41
  4624.6 2268.34  4634.8 2266.86  4780.9 2263.25  4887.9 2258.18  4969.7 2257.03
  4978.0 2256.59  4986.0 2252.95  4995.4 2251.59  5003.4 2247.96  5003.8 2247.46
  5008.3 2247.96  5027.4 2253.95  5048.4 2257.34  5140.8 2258.63  5155.0 2260.56
  5262.9 2266.15  5444.7 2275.39  5466.2 2274.42  5505.3 2276.30  5558.0 2280.46
  5593.2 2280.12  5600.6 2278.28  5635.7 2279.31  5649.9 2280.19  5653.9 2282.45
#Mann=6,-1,0
  4302.7   0.035       0  4986.0    0.07       0  5003.4    0.07       0
  5008.3    0.07       0  5262.9   0.035       0  5505.3   0.063       0
Bank Sta=5003.4,5008.3
Exp/Cntr=0.3,0.1

Type RM Length L Ch R = 1,10234,105,105,105
BEGIN DESCRIPTION:
UCFB HW Trib 17 21.0
END DESCRIPTION:
XS GIS Cut Line= 5
      1289248.98      6955402.96      1289329.90      6954808.53
      1288855.00      6954688.00      1288457.50      6954591.51
      1288089.67      6953983.54
#Sta/Elev= 30
  3910.4 2273.23  4184.9 2268.51  4258.5 2265.71  4572.8 2261.80  4775.9 2256.94
  4928.1 2253.63  4941.4 2252.77  4948.7 2249.34  4959.0 2247.50  4978.8 2247.84
  4995.1 2247.35  4995.5 2246.85  5000.2 2247.35  5031.1 2254.07  5122.4 2256.20
  5383.6 2262.95  5460.8 2268.76  5516.6 2266.80  5595.5 2266.89  5654.3 2267.00
  5718.4 2270.42  5807.6 2269.40  5945.3 2270.96  5966.6 2272.73  5982.2 2271.46
  6003.5 2274.04  6040.3 2272.19  6046.2 2274.13  6094.3 2273.83  6119.9 2273.46
#Mann=11,-1,0
  3910.4    0.07       0  4184.9   0.035       0  4775.9   0.063       0
  4978.8   0.035       0  4995.1   0.035       0  5000.2   0.035       0
  5122.4   0.063       0  5383.6   0.035       0  5460.8   0.063       0
  5595.5   0.035       0  6094.3    0.07       0
Bank Sta=4995.1,5000.2
Exp/Cntr=0.3,0.1

Type RM Length L Ch R = 1,10129,365,365,365
BEGIN DESCRIPTION:
UCFB HW Trib 17 20.5
END DESCRIPTION:
XS GIS Cut Line= 4
      1289345.47      6955406.34      1289457.37      6954746.16
      1288510.01      6954497.37      1288226.57      6953974.08
#Sta/Elev= 30
  3760.5 2273.92  3810.1 2273.12  4061.2 2268.73  4336.9 2263.58  4357.2 2260.69
  4397.8 2262.60  4445.3 2259.68  4515.3 2260.37  4825.2 2253.50  4949.3 2250.64
  4954.5 2248.87  4980.5 2247.84  4992.3 2245.45  4992.7 2244.95  4997.4 2245.45
  5021.9 2247.50  5035.2 2252.07  5070.4 2253.22  5075.6 2254.87  5155.7 2257.27
  5267.1 2260.12  5272.2 2261.46  5353.0 2261.98  5383.0 2263.70  5388.2 2262.29
  5412.1 2264.48  5553.8 2262.79  5679.3 2264.68  5728.8 2266.81  6004.7 2266.01
#Mann=7,-1,0
  3760.5   0.035       0  3810.1    0.07       0  4061.2   0.035       0
  4825.2   0.063       0  4992.3   0.063       0  4997.4   0.063       0
  5155.7   0.035       0
Bank Sta=4992.3,4997.4
Exp/Cntr=0.3,0.1

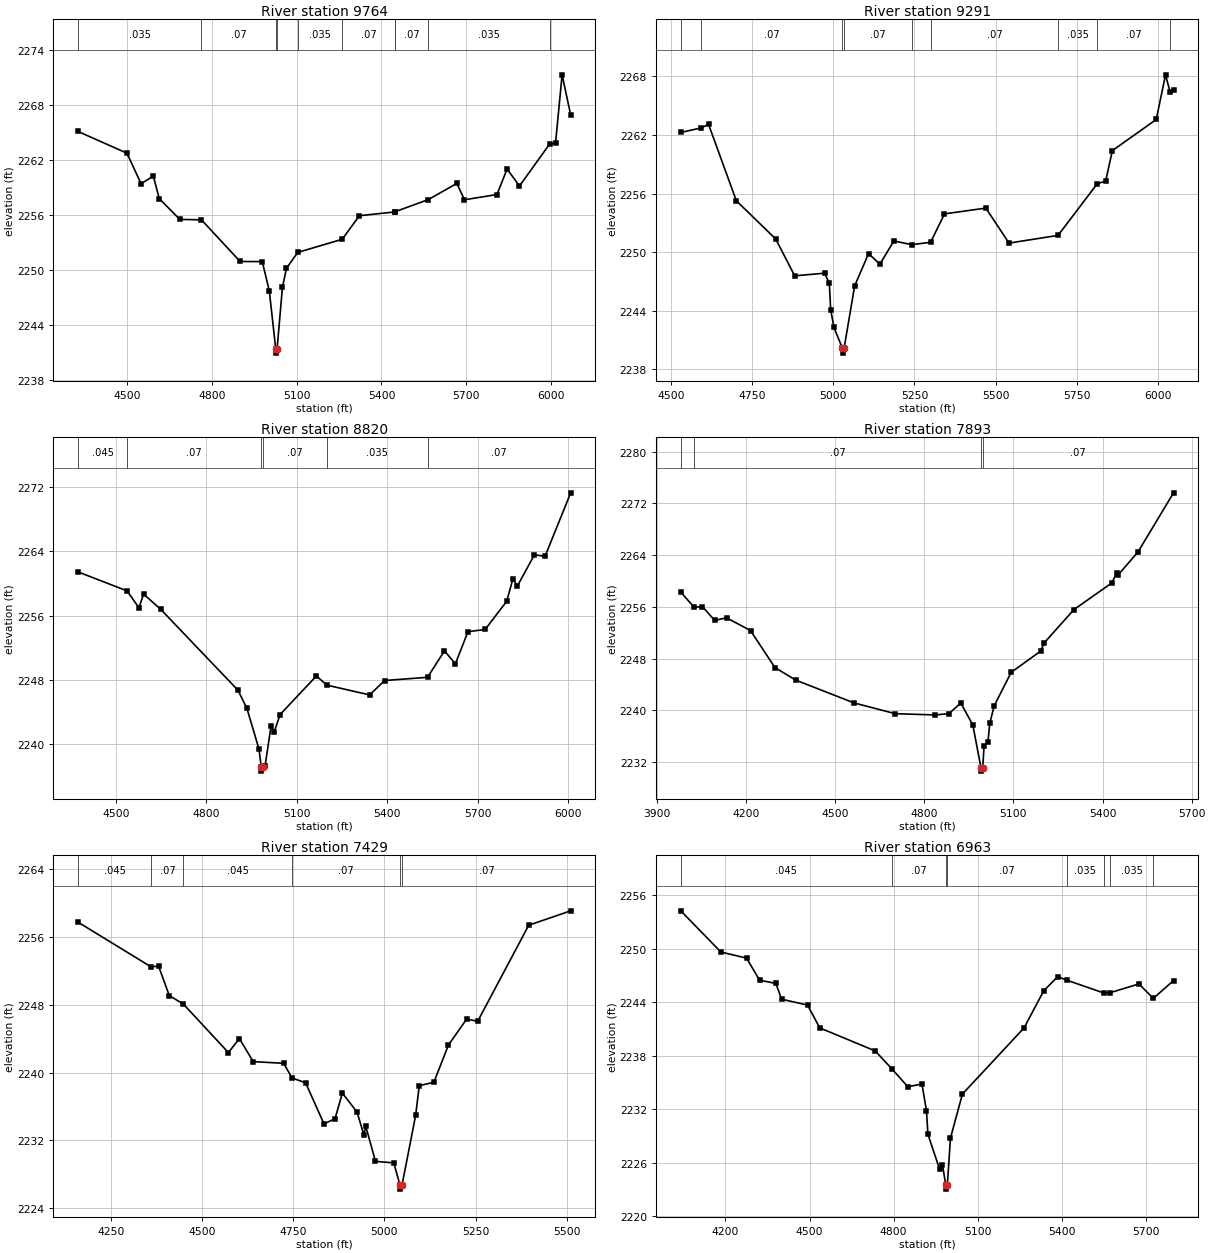
Type RM Length L Ch R = 1,9764,473,473,473
BEGIN DESCRIPTION:
UCFB HW Trib 17 20.0
END DESCRIPTION:
XS GIS Cut Line= 3
      1289693.46      6954743.29      1289155.00      6954338.00
      1288290.65      6953708.55
#Sta/Elev= 30
  4326.3 2265.08  4499.6 2262.71  4549.7 2259.38  4593.2 2260.20  4614.0 2257.75
  4686.8 2255.49  4763.4 2255.44  4900.1 2250.90  4978.4 2250.89  5003.3 2247.69
  5025.9 2241.41  5026.3 2240.91  5031.0 2241.41  5049.7 2248.07  5064.0 2250.16
  5103.8 2251.89  5261.2 2253.32  5321.9 2255.89  5446.8 2256.30  5449.6 2256.34
  5565.8 2257.65  5666.7 2259.41  5693.7 2257.63  5808.8 2258.20  5844.4 2260.98
  5888.4 2259.13  5994.7 2263.69  6015.9 2263.79  6039.1 2271.25  6069.5 2266.87
#Mann=10,-1,0
  4326.3   0.035       0  4763.4    0.07       0  5025.9    0.07       0
  5031.0    0.07       0  5103.8   0.035       0  5261.2    0.07       0
  5446.8   0.035       0  5449.6    0.07       0  5565.8   0.035       0
  5994.7    0.07       0
Bank Sta=5025.9,5031
Exp/Cntr=0.3,0.1

Type RM Length L Ch R = 1,9291,471,471,471
BEGIN DESCRIPTION:
UCFB HW Trib 17 19.0
END DESCRIPTION:
XS GIS Cut Line= 3
      1289729.98      6954212.98      1289355.00      6953938.00
      1288551.06      6953257.16
#Sta/Elev= 30
  4530.1 2262.25  4592.9 2262.72  4615.7 2263.08  4701.4 2255.26  4822.6 2251.35
  4881.2 2247.58  4973.1 2247.85  4987.8 2246.83  4992.0 2244.12  5002.2 2242.30
  5028.2 2240.17  5028.6 2239.67  5033.4 2240.17  5065.9 2246.55  5108.8 2249.85
  5143.9 2248.78  5186.8 2251.15  5241.5 2250.77  5299.9 2251.01  5342.8 2253.92
  5470.2 2254.51  5541.7 2250.93  5692.8 2251.72  5813.4 2257.00  5839.4 2257.28
  5860.2 2260.40  5995.4 2263.58  6023.9 2268.15  6037.7 2266.43  6048.6 2266.57
#Mann=9,-1,0
  4530.1   0.045       0  4592.9    0.07       0  5028.2    0.07       0
  5033.4    0.07       0  5241.5   0.035       0  5299.9    0.07       0
  5692.8   0.035       0  5813.4    0.07       0  6037.7   0.035       0
Bank Sta=5028.2,5033.4
Exp/Cntr=0.3,0.1

Type RM Length L Ch R = 1,8820,927,927,927
BEGIN DESCRIPTION:
UCFB HW Trib 17 18.0
END DESCRIPTION:
XS GIS Cut Line= 5
      1289880.01      6953913.01      1289635.78      6953534.93
      1289455.00      6953538.00      1289304.18      6953541.88
      1288655.02      6952988.02
#Sta/Elev= 30
  4374.1 2261.46  4537.2 2259.09  4576.7 2256.98  4591.8 2258.70  4649.2 2256.78
  4905.0 2246.73  4935.0 2244.45  4975.0 2239.37  4982.4 2237.15  4982.8 2236.65
  4987.6 2237.15  4995.0 2237.28  5015.0 2242.27  5025.0 2241.49  5045.0 2243.70
  5165.5 2248.50  5199.7 2247.36  5342.2 2246.14  5391.6 2247.93  5534.3 2248.33
  5590.3 2251.63  5626.6 2250.01  5668.3 2254.01  5725.4 2254.29  5796.8 2257.79
  5817.6 2260.61  5831.9 2259.67  5889.0 2263.59  5924.1 2263.39  6009.2 2271.30
#Mann=6,-1,0
  4374.1   0.045       0  4537.2    0.07       0  4982.4    0.07       0
  4987.6    0.07       0  5199.7   0.035       0  5534.3    0.07       0
Bank Sta=4982.4,4987.6
Exp/Cntr=0.3,0.1

Type RM Length L Ch R = 1,7893,464,464,464
BEGIN DESCRIPTION:
UCFB HW Trib 17 17.0
END DESCRIPTION:
XS GIS Cut Line= 3
      1289856.26      6953750.16      1289705.00      6952738.00
      1289526.39      6952128.64
#Sta/Elev= 30
  3980.6 2258.29  4025.2 2255.96  4053.6 2256.04  4094.8 2253.91  4134.5 2254.32
  4215.3 2252.35  4297.4 2246.63  4367.0 2244.69  4564.2 2241.15  4702.6 2239.49
  4836.0 2239.30  4882.7 2239.49  4923.1 2241.14  4963.6 2237.73  4991.0 2231.11
  4991.5 2230.61  4996.7 2231.11  5001.5 2234.49  5014.4 2235.15  5020.7 2238.01
  5035.3 2240.70  5092.7 2245.89  5191.6 2249.16  5203.4 2250.42  5303.6 2255.58
  5431.3 2259.71  5447.6 2261.24  5452.9 2260.96  5519.7 2264.52  5639.0 2273.64
#Mann=4,-1,0
  3980.6   0.045       0  4025.2    0.07       0  4991.0    0.07       0
  4996.7    0.07       0
Bank Sta=4991,4996.7
Exp/Cntr=0.3,0.1

Type RM Length L Ch R = 1,7429,466,466,466
BEGIN DESCRIPTION:
UCFB HW Trib 17 16.0
END DESCRIPTION:
XS GIS Cut Line= 3
      1289946.54      6953757.20      1290055.00      6952938.00
      1290080.00      6952413.05
#Sta/Elev= 30
  4159.1 2257.78  4360.2 2252.48  4380.2 2252.60  4409.7 2249.10  4448.5 2248.09
  4571.9 2242.37  4602.1 2244.02  4640.0 2241.30  4723.5 2241.10  4746.5 2239.37
  4783.7 2238.80  4834.1 2233.95  4864.4 2234.55  4884.6 2237.58  4924.9 2235.34
  4943.7 2232.63  4948.8 2233.67  4975.4 2229.52  5025.5 2229.34  5042.6 2226.74
  5043.1 2226.24  5048.4 2226.74  5085.6 2234.95  5095.6 2238.46  5135.6 2238.86
  5175.7 2243.27  5225.7 2246.33  5255.8 2246.06  5395.9 2257.41  5511.0 2259.11
#Mann=6,-1,0
  4159.1   0.045       0  4360.2    0.07       0  4448.5   0.045       0
  4746.5    0.07       0  5042.6    0.07       0  5048.4    0.07       0
Bank Sta=5042.6,5048.4
Exp/Cntr=0.3,0.1

Type RM Length L Ch R = 1,6963,432,432,432
BEGIN DESCRIPTION:
UCFB HW Trib 17 15.0
END DESCRIPTION:
XS GIS Cut Line= 3
      1290180.00      6953913.00      1290455.00      6952988.00
      1290460.43      6952194.63
#Sta/Elev= 30
  4040.6 2254.24  4183.8 2249.62  4275.3 2248.94  4321.8 2246.46  4379.7 2246.10
  4400.5 2244.33  4493.0 2243.67  4536.6 2241.11  4734.4 2238.53  4794.1 2236.51
  4851.0 2234.51  4901.3 2234.82  4917.4 2231.81  4922.6 2229.17  4963.9 2225.30
  4974.3 2225.79  4986.1 2223.53  4986.6 2223.03  4991.9 2223.53  5003.0 2228.75
  5045.6 2233.69  5265.6 2241.11  5335.6 2245.26  5385.6 2246.86  5419.5 2246.45
  5549.6 2245.03  5574.0 2245.07  5675.6 2246.04  5726.9 2244.42  5799.0 2246.42
#Mann=8,-1,0
  4040.6   0.045       0  4794.1    0.07       0  4986.1    0.07       0
  4991.9    0.07       0  5419.5   0.035       0  5549.6    0.07       0
  5574.0   0.035       0  5726.9    0.07       0
Bank Sta=4986.1,4991.9
Exp/Cntr=0.3,0.1

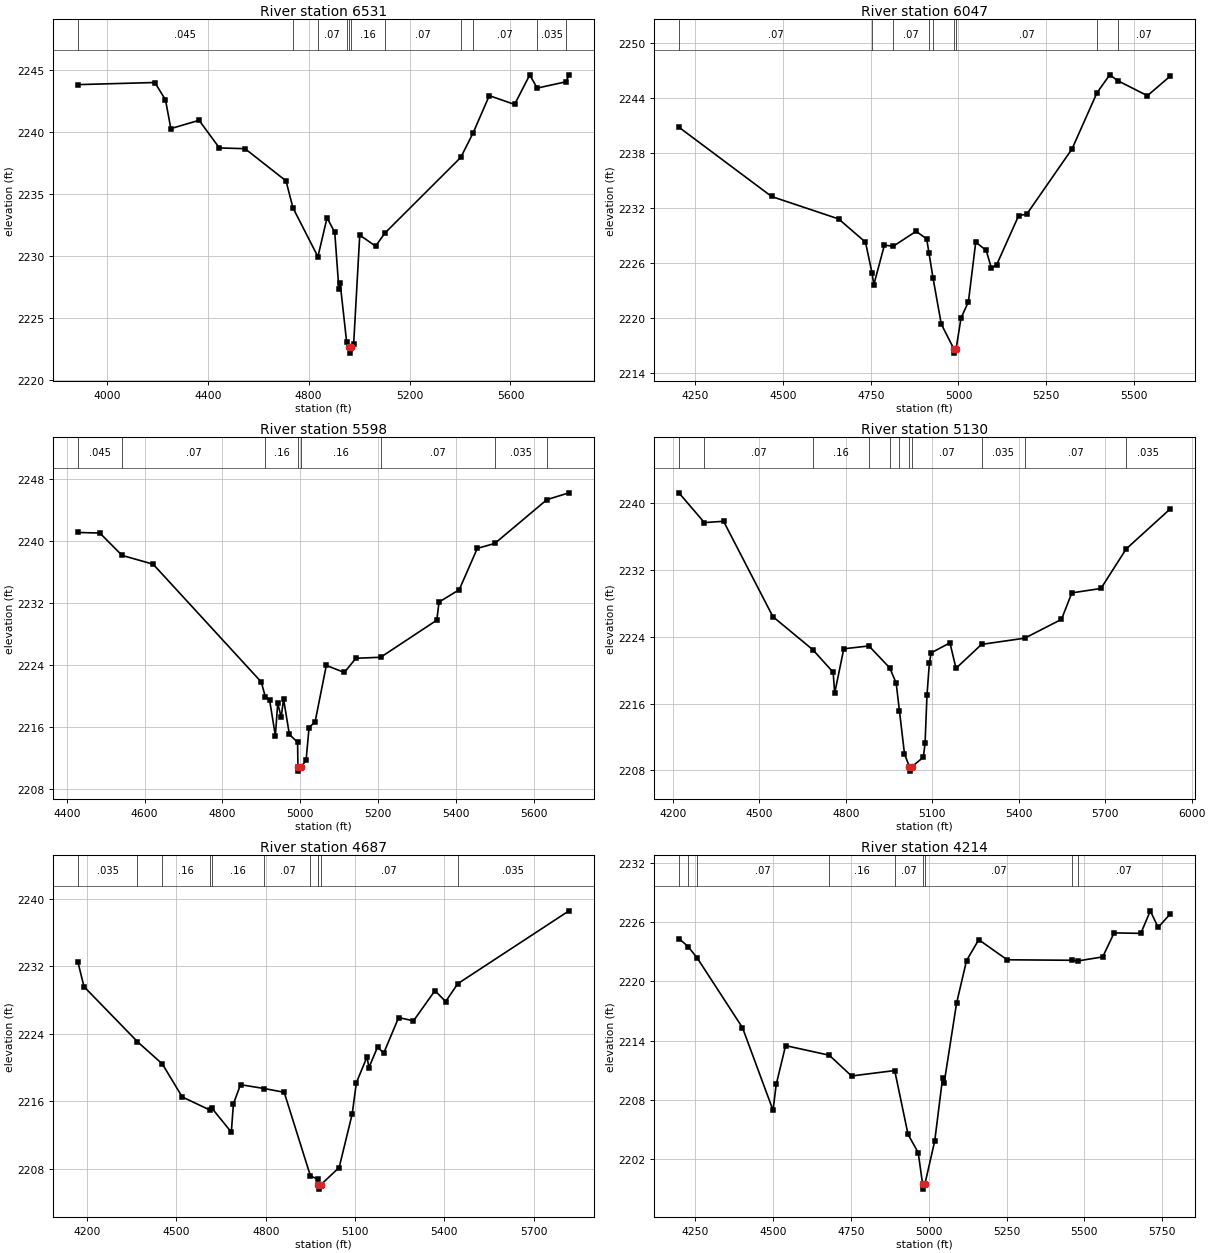
Type RM Length L Ch R = 1,6531,484,484,484
BEGIN DESCRIPTION:
UCFB HW Trib 17 14.0
END DESCRIPTION:
XS GIS Cut Line= 3
      1290654.87      6953989.83      1290855.00      6952888.00
      1290804.19      6952062.82
#Sta/Elev= 30
  3885.3 2243.83  4190.4 2244.00  4232.7 2242.60  4253.9 2240.28  4365.8 2240.95
  4446.2 2238.72  4547.8 2238.66  4710.4 2236.06  4737.8 2233.89  4836.8 2229.94
  4873.0 2233.08  4903.5 2231.91  4920.0 2227.32  4925.1 2227.78  4950.5 2223.09
  4961.6 2222.66  4962.1 2222.16  4967.4 2222.66  4978.5 2222.90  5002.6 2231.69
  5065.3 2230.79  5102.4 2231.85  5403.2 2237.96  5451.7 2239.92  5516.1 2242.94
  5616.3 2242.23  5676.4 2244.61  5706.0 2243.55  5820.4 2244.06  5831.9 2244.62
#Mann=11,-1,0
  3885.3   0.045       0  4737.8   0.035       0  4836.8    0.07       0
  4950.5    0.16       0  4961.6    0.07       0  4967.4    0.16       0
  5102.4    0.07       0  5403.2   0.035       0  5451.7    0.07       0
  5706.0   0.035       0  5820.4    0.07       0
Bank Sta=4961.6,4967.4
Exp/Cntr=0.3,0.1

Type RM Length L Ch R = 1,6047,449,449,449
BEGIN DESCRIPTION:
UCFB HW Trib 17 13.0
END DESCRIPTION:
XS GIS Cut Line= 3
      1291380.57      6953580.92      1291305.00      6952788.00
      1290961.68      6952292.42
#Sta/Elev= 30
  4203.4 2240.80  4467.5 2233.23  4658.4 2230.78  4735.1 2228.24  4753.7 2224.87
  4758.8 2223.59  4789.0 2227.92  4813.9 2227.79  4879.4 2229.43  4909.5 2228.59
  4916.0 2227.05  4927.6 2224.31  4951.0 2219.29  4986.4 2216.62  4986.9 2216.12
  4993.4 2216.62  5007.3 2219.96  5028.3 2221.72  5049.2 2228.24  5079.0 2227.34
  5093.8 2225.41  5108.7 2225.76  5171.5 2231.14  5194.6 2231.30  5323.5 2238.42
  5394.7 2244.56  5431.0 2246.52  5453.9 2245.88  5538.4 2244.24  5602.8 2246.36
#Mann=9,-1,0
  4203.4    0.07       0  4753.7    0.16       0  4813.9    0.07       0
  4916.0    0.16       0  4927.6    0.07       0  4986.4    0.07       0
  4993.4    0.07       0  5394.7   0.035       0  5453.9    0.07       0
Bank Sta=4986.4,4993.4
Exp/Cntr=0.3,0.1

Type RM Length L Ch R = 1,5598,468,468,468
BEGIN DESCRIPTION:
UCFB HW Trib 17 12.0
END DESCRIPTION:
XS GIS Cut Line= 4
      1291980.01      6952963.01      1291710.93      6952608.62
      1291605.00      6952538.00      1290974.73      6952257.14
#Sta/Elev= 30
  4428.3 2241.12  4484.8 2241.05  4542.0 2238.16  4621.7 2237.03  4899.9 2221.81
  4910.1 2219.90  4921.0 2219.52  4936.0 2214.89  4942.0 2219.07  4951.0 2217.26
  4957.0 2219.63  4972.0 2215.04  4993.1 2214.04  4994.0 2210.81  4994.5 2210.31
  5001.1 2210.81  5014.9 2211.69  5022.5 2215.91  5038.2 2216.70  5066.9 2223.95
  5113.3 2223.05  5142.9 2224.88  5206.6 2225.01  5350.9 2229.80  5356.6 2232.14
  5408.5 2233.73  5455.0 2239.07  5499.8 2239.70  5633.9 2245.36  5690.6 2246.24
#Mann=8,-1,0
  4428.3   0.045       0  4542.0    0.07       0  4910.1    0.16       0
  4994.0    0.07       0  5001.1    0.16       0  5206.6    0.07       0
  5499.8   0.035       0  5633.9    0.07       0
Bank Sta=4994,5001.1
Exp/Cntr=0.3,0.1

Type RM Length L Ch R = 1,5130,443,443,443
BEGIN DESCRIPTION:
UCFB HW Trib 17 11.0
END DESCRIPTION:
XS GIS Cut Line= 3
      1291980.01      6952913.01      1291705.00      6952188.00
      1291172.11      6951427.18
#Sta/Elev= 30
  4220.6 2241.26  4309.1 2237.69  4375.7 2237.85  4546.8 2226.42  4685.6 2222.45
  4755.9 2219.76  4761.2 2217.25  4792.8 2222.57  4880.1 2222.91  4952.3 2220.28
  4974.6 2218.46  4985.9 2215.14  5003.4 2209.99  5020.8 2208.41  5021.3 2207.91
  5028.0 2208.41  5068.8 2209.57  5074.9 2211.26  5081.5 2217.00  5089.7 2220.81
  5095.8 2222.08  5161.2 2223.28  5182.2 2220.23  5270.9 2223.10  5420.5 2223.84
  5548.3 2226.10  5584.1 2229.27  5685.2 2229.80  5772.9 2234.54  5924.9 2239.31
#Mann=11,-1,0
  4220.6   0.045       0  4309.1    0.07       0  4685.6    0.16       0
  4880.1    0.07       0  4952.3    0.16       0  4985.9    0.07       0
  5020.8    0.07       0  5028.0    0.07       0  5270.9   0.035       0
  5420.5    0.07       0  5772.9   0.035       0
Bank Sta=5020.8,5028
Exp/Cntr=0.3,0.1

Type RM Length L Ch R = 1,4687,473,473,473
BEGIN DESCRIPTION:
UCFB HW Trib 17 10.0
END DESCRIPTION:
XS GIS Cut Line= 3
      1292206.83      6952698.03      1292005.00      6951888.00
      1291512.35      6951239.62
#Sta/Elev= 30
  4169.2 2232.53  4189.8 2229.58  4369.4 2223.06  4453.0 2220.42  4519.6 2216.52
  4611.3 2214.99  4618.5 2215.22  4684.5 2212.35  4691.7 2215.72  4715.4 2217.97
  4795.7 2217.51  4862.0 2217.07  4950.0 2207.18  4974.8 2206.76  4977.1 2206.10
  4977.6 2205.60  4984.4 2206.10  5046.6 2208.16  5090.3 2214.48  5104.5 2218.21
  5140.2 2221.26  5146.5 2220.00  5175.5 2222.41  5196.4 2221.72  5246.3 2225.92
  5296.2 2225.53  5368.2 2229.10  5404.3 2227.82  5444.9 2229.93  5818.3 2238.56
#Mann=11,-1,0
  4169.2   0.035       0  4369.4    0.07       0  4453.0    0.16       0
  4611.3    0.07       0  4618.5    0.16       0  4795.7    0.07       0
  4950.0    0.16       0  4974.8    0.07       0  4977.1    0.07       0
  4984.4    0.07       0  5444.9   0.035       0
Bank Sta=4977.1,4984.4
Exp/Cntr=0.3,0.1

Type RM Length L Ch R = 1,4214,477,477,477
BEGIN DESCRIPTION:
UCFB HW Trib 17 9.0
END DESCRIPTION:
XS GIS Cut Line= 3
      1292505.00      6952488.00      1292405.00      6951688.00
      1292137.39      6950965.39
#Sta/Elev= 30
  4198.1 2224.32  4227.5 2223.51  4256.9 2222.35  4402.2 2215.31  4500.4 2206.95
  4510.5 2209.56  4540.7 2213.49  4680.9 2212.52  4752.4 2210.42  4891.0 2210.97
  4933.8 2204.51  4966.5 2202.67  4980.5 2199.48  4981.0 2198.98  4987.8 2199.48
  5019.5 2203.85  5044.6 2210.19  5049.9 2209.75  5089.6 2217.78  5121.6 2222.09
  5160.8 2224.20  5252.0 2222.17  5460.6 2222.12  5478.1 2222.05  5558.8 2222.46
  5595.4 2224.89  5681.2 2224.84  5711.6 2227.12  5736.7 2225.44  5774.9 2226.78
#Mann=9,-1,0
  4198.1    0.07       0  4227.5   0.035       0  4256.9    0.07       0
  4680.9    0.16       0  4891.0    0.07       0  4980.5    0.07       0
  4987.8    0.07       0  5460.6   0.035       0  5478.1    0.07       0
Bank Sta=4980.5,4987.8
Exp/Cntr=0.3,0.1

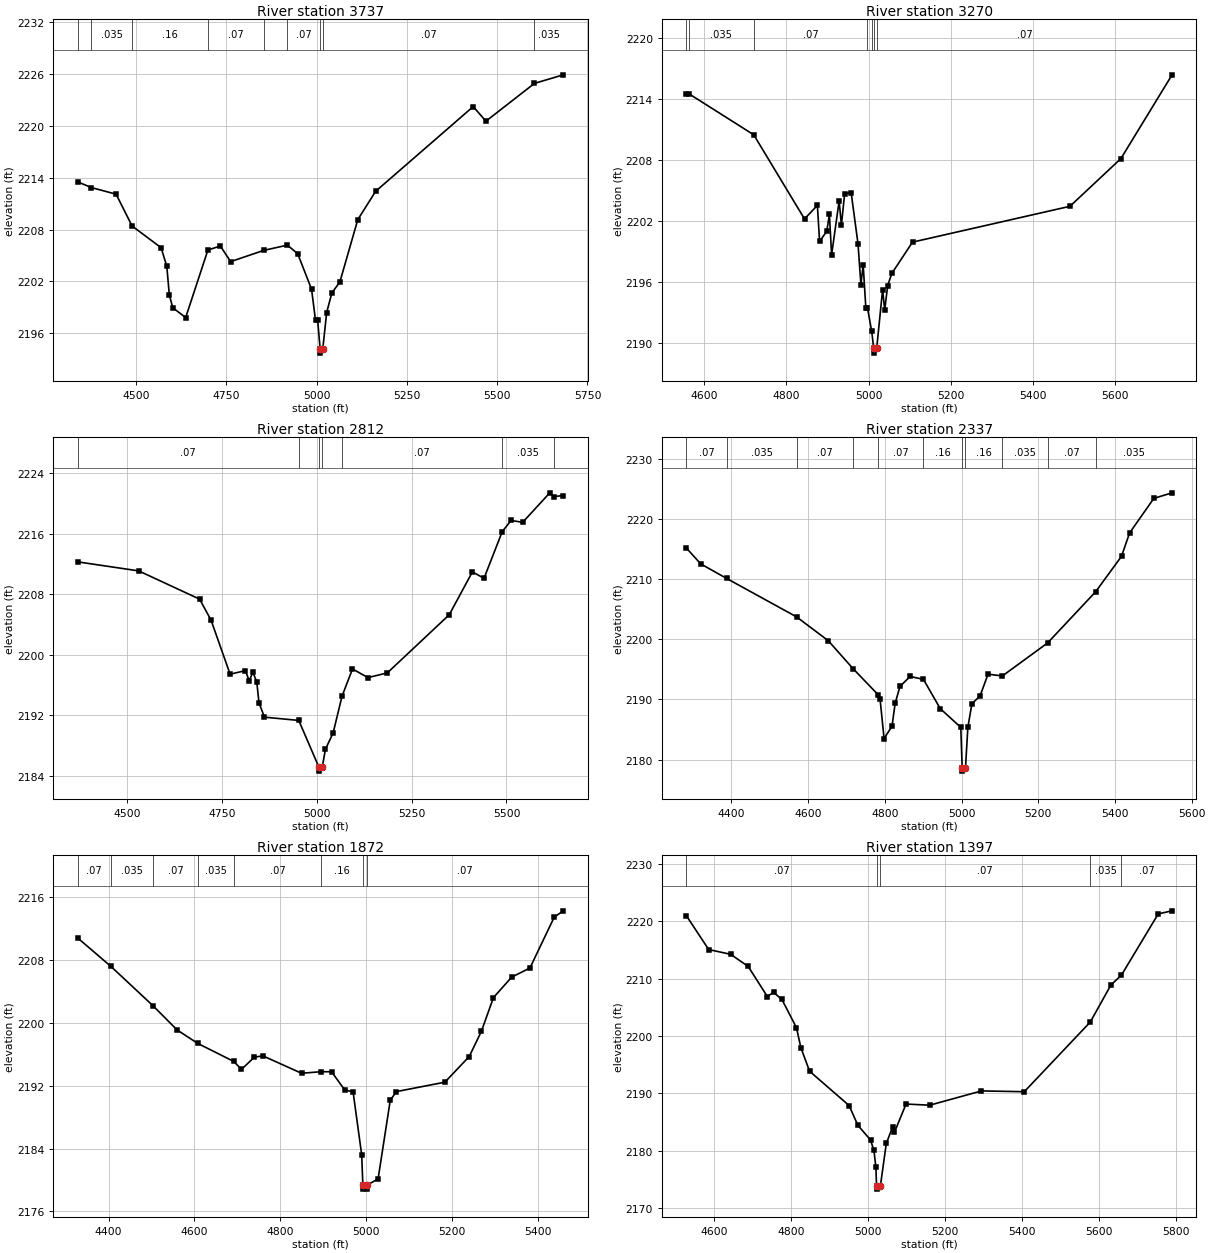
Type RM Length L Ch R = 1,3737,467,467,467
BEGIN DESCRIPTION:
UCFB HW Trib 17 8.0
END DESCRIPTION:
XS GIS Cut Line= 3
      1293115.23      6952171.92      1292805.00      6951588.00
      1292373.07      6951058.68
#Sta/Elev= 30
  4338.8 2213.52  4376.8 2212.86  4445.2 2212.09  4489.3 2208.41  4569.7 2205.89
  4585.5 2203.73  4592.4 2200.44  4601.9 2198.94  4637.7 2197.80  4699.2 2205.62
  4733.7 2206.09  4762.2 2204.28  4854.4 2205.59  4919.3 2206.19  4947.9 2205.19
  4986.2 2201.08  4997.2 2197.46  5003.2 2197.46  5009.9 2194.18  5010.4 2193.68
  5017.3 2194.18  5028.0 2198.37  5042.4 2200.66  5064.5 2201.91  5114.2 2209.15
  5163.7 2212.43  5433.7 2222.24  5468.9 2220.55  5603.3 2224.93  5683.2 2225.92
#Mann=9,-1,0
  4338.8    0.07       0  4376.8   0.035       0  4489.3    0.16       0
  4699.2    0.07       0  4854.4    0.16       0  4919.3    0.07       0
  5009.9    0.07       0  5017.3    0.07       0  5603.3   0.035       0
Bank Sta=5009.9,5017.3
Exp/Cntr=0.3,0.1

Type RM Length L Ch R = 1,3270,458,458,458
BEGIN DESCRIPTION:
UCFB HW Trib 17 7.0
END DESCRIPTION:
XS GIS Cut Line= 3
      1293324.87      6951992.69      1293155.00      6951588.00
      1293064.61      6950851.62
#Sta/Elev= 30
  4556.9 2214.51  4562.6 2214.50  4720.6 2210.46  4844.0 2202.20  4875.3 2203.53
  4880.7 2199.99  4898.2 2200.99  4904.5 2202.65  4909.9 2198.67  4928.2 2203.97
  4933.7 2201.60  4941.6 2204.68  4957.4 2204.79  4974.1 2199.75  4981.2 2195.73
  4986.6 2197.72  4993.1 2193.49  4997.0 2193.49  5007.4 2191.15  5012.2 2189.52
  5012.7 2189.02  5019.6 2189.52  5033.9 2195.25  5039.0 2193.27  5046.2 2195.64
  5056.2 2196.84  5106.6 2199.92  5489.5 2203.44  5613.4 2208.13  5737.7 2216.35
#Mann=7,-1,0
  4556.9    0.07       0  4562.6   0.035       0  4720.6    0.07       0
  4997.0    0.16       0  5007.4    0.07       0  5012.2    0.07       0
  5019.6    0.07       0
Bank Sta=5012.2,5019.6
Exp/Cntr=0.3,0.1

Type RM Length L Ch R = 1,2812,475,475,475
BEGIN DESCRIPTION:
UCFB HW Trib 17 6.0
END DESCRIPTION:
XS GIS Cut Line= 3
      1293463.76      6951878.13      1293405.00      6951238.00
      1293280.00      6950613.00
#Sta/Elev= 30
  4369.7 2212.27  4530.5 2211.08  4691.2 2207.35  4721.3 2204.57  4771.5 2197.45
  4811.7 2197.92  4821.7 2196.60  4831.8 2197.71  4841.8 2196.39  4847.6 2193.69
  4861.9 2191.78  4952.5 2191.35  5005.7 2185.16  5006.2 2184.66  5014.3 2185.16
  5022.7 2187.54  5043.1 2189.71  5066.4 2194.53  5094.1 2198.14  5134.9 2197.00
  5185.9 2197.62  5349.1 2205.29  5410.2 2210.95  5440.8 2210.10  5488.9 2216.27
  5512.2 2217.73  5542.8 2217.49  5614.2 2221.38  5624.9 2220.89  5649.9 2221.02
#Mann=7,-1,0
  4369.7    0.07       0  4952.5    0.16       0  5005.7    0.07       0
  5014.3    0.16       0  5066.4    0.07       0  5488.9   0.035       0
  5624.9    0.07       0
Bank Sta=5005.7,5014.3
Exp/Cntr=0.3,0.1

Type RM Length L Ch R = 1,2337,465,465,465
BEGIN DESCRIPTION:
UCFB HW Trib 17 5.0
END DESCRIPTION:
XS GIS Cut Line= 3
      1293998.47      6951773.90      1293805.00      6951088.00
      1293629.99      6950562.96
#Sta/Elev= 30
  4282.8 2215.17  4320.1 2212.54  4387.3 2210.13  4569.9 2203.73  4652.6 2199.76
  4717.0 2195.13  4783.0 2190.75  4787.7 2190.02  4798.1 2183.49  4818.8 2185.55
  4826.9 2189.33  4839.6 2192.18  4866.1 2193.81  4900.6 2193.34  4944.5 2188.47
  4998.1 2185.35  5001.7 2178.57  5002.2 2178.07  5010.3 2178.57  5016.5 2185.34
  5027.1 2189.29  5048.2 2190.56  5069.2 2194.20  5106.5 2193.90  5224.4 2199.39
  5349.6 2207.90  5417.1 2213.80  5438.2 2217.69  5501.4 2223.44  5548.9 2224.36
#Mann=11,-1,0
  4282.8    0.07       0  4387.3   0.035       0  4569.9    0.07       0
  4717.0    0.16       0  4783.0    0.07       0  4900.6    0.16       0
  5001.7    0.07       0  5010.3    0.16       0  5106.5   0.035       0
  5224.4    0.07       0  5349.6   0.035       0
Bank Sta=5001.7,5010.3
Exp/Cntr=0.3,0.1

Type RM Length L Ch R = 1,1872,475,475,475
BEGIN DESCRIPTION:
UCFB HW Trib 17 4.0
END DESCRIPTION:
XS GIS Cut Line= 3
      1294203.34      6951659.36      1294205.00      6950988.00
      1293879.98      6950662.98
#Sta/Elev= 30
  4328.2 2210.75  4405.5 2207.14  4503.4 2202.15  4559.6 2199.07  4607.9 2197.35
  4691.7 2195.06  4709.6 2194.05  4739.6 2195.61  4759.6 2195.77  4849.6 2193.56
  4894.9 2193.76  4919.6 2193.75  4949.6 2191.47  4969.6 2191.17  4989.6 2183.19
  4992.3 2179.34  4992.8 2178.84  5001.3 2178.84  5001.8 2179.34  5027.8 2180.14
  5056.1 2190.12  5070.3 2191.23  5183.4 2192.43  5240.0 2195.69  5268.3 2198.88
  5296.5 2203.18  5339.0 2205.78  5381.4 2206.93  5438.0 2213.40  5459.2 2214.20
#Mann=8,-1,0
  4328.2    0.07       0  4405.5   0.035       0  4503.4    0.07       0
  4607.9   0.035       0  4691.7    0.07       0  4894.9    0.16       0
  4992.3    0.07       0  5001.8    0.07       0
Bank Sta=4992.3,5001.8
Exp/Cntr=0.3,0.1

Type RM Length L Ch R = 1,1397,426,426,426
BEGIN DESCRIPTION:
UCFB HW Trib 17 3.0
END DESCRIPTION:
XS GIS Cut Line= 3
      1295015.86      6951013.53      1294605.00      6950788.00
      1293830.00      6950613.00
#Sta/Elev= 30
  4527.3 2220.96  4585.2 2215.07  4642.4 2214.24  4688.0 2212.12  4737.8 2206.88
  4753.9 2207.62  4775.7 2206.37  4813.5 2201.45  4825.0 2197.96  4847.7 2193.86
  4950.4 2187.88  4973.2 2184.44  5006.2 2181.87  5015.0 2180.05  5020.2 2177.09
  5021.8 2173.81  5022.3 2173.31  5031.7 2173.81  5047.2 2181.27  5063.4 2184.11
  5068.5 2183.23  5098.5 2188.14  5160.0 2187.94  5294.8 2190.43  5406.1 2190.29
  5577.7 2202.43  5631.6 2208.91  5658.9 2210.62  5754.6 2221.29  5790.5 2221.82
#Mann=5,-1,0
  4527.3    0.07       0  5021.8    0.07       0  5031.7    0.07       0
  5577.7   0.035       0  5658.9    0.07       0
Bank Sta=5021.8,5031.7
Exp/Cntr=0.3,0.1

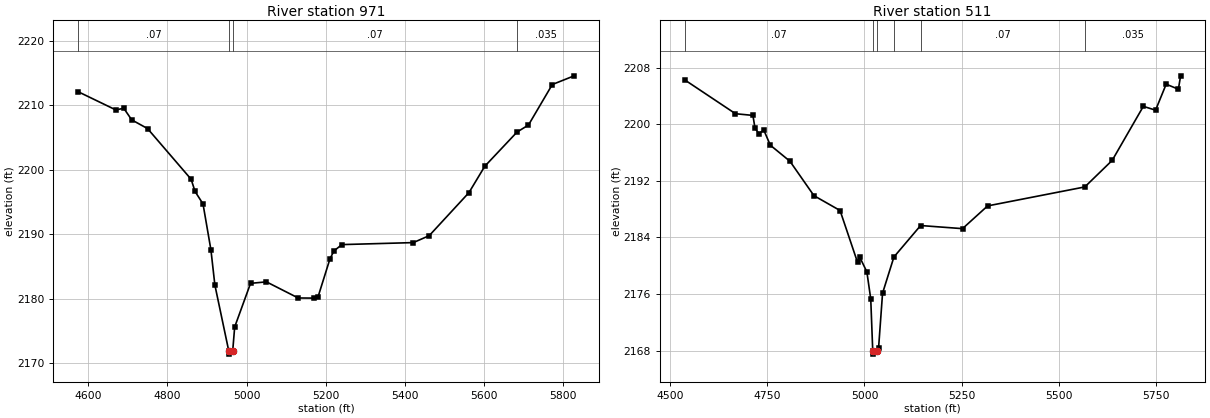
Type RM Length L Ch R = 1,971,460,460,460
BEGIN DESCRIPTION:
UCFB HW Trib 17 2.0
END DESCRIPTION:
XS GIS Cut Line= 3
      1295130.02      6950413.00      1294705.00      6950438.00
      1293879.96      6950513.00
#Sta/Elev= 30
  4574.3 2212.10  4669.5 2209.28  4689.5 2209.54  4709.6 2207.74  4749.6 2206.39
  4859.8 2198.53  4869.8 2196.63  4889.9 2194.70  4909.9 2187.58  4919.9 2182.12
  4955.0 2171.90  4955.5 2171.40  4965.0 2171.90  4970.0 2175.61  5010.1 2182.38
  5050.3 2182.61  5130.6 2180.11  5170.8 2180.09  5180.8 2180.28  5210.9 2186.17
  5221.0 2187.40  5241.0 2188.39  5421.8 2188.70  5462.0 2189.78  5562.4 2196.45
  5602.5 2200.54  5684.1 2205.85  5713.0 2206.94  5773.2 2213.22  5828.5 2214.57
#Mann=4,-1,0
  4574.3    0.07       0  4955.0    0.07       0  4965.0    0.07       0
  5684.1   0.035       0
Bank Sta=4955,4965
Exp/Cntr=0.3,0.1

Type RM Length L Ch R = 1,511,0,0,0
BEGIN DESCRIPTION:
UCFB HW Trib 17 1.0
END DESCRIPTION:
XS GIS Cut Line= 4
      1295116.52      6950291.29      1294705.00      6950088.00
      1294563.61      6950072.42      1293979.96      6950413.02
#Sta/Elev= 30
  4537.0 2206.26  4667.8 2201.48  4712.7 2201.24  4718.2 2199.40  4728.3 2198.67
  4740.7 2199.17  4757.6 2197.03  4808.0 2194.77  4869.8 2189.91  4937.1 2187.81
  4982.0 2180.51  4987.6 2181.24  5006.1 2179.15  5016.1 2175.33  5021.2 2168.03
  5021.7 2167.53  5031.2 2168.03  5036.2 2168.35  5046.5 2176.13  5075.8 2181.25
  5144.5 2185.69  5252.4 2185.25  5317.0 2188.46  5567.3 2191.14  5637.8 2194.89
  5718.0 2202.52  5749.5 2201.98  5776.8 2205.65  5808.2 2204.94  5814.0 2206.83
#Mann=6,-1,0
  4537.0    0.07       0  5021.2    0.07       0  5031.2    0.07       0
  5075.8    0.16       0  5144.5    0.07       0  5567.3   0.035       0
Bank Sta=5021.2,5031.2
Exp/Cntr=0.3,0.1

Chan Stop Cuts=-1