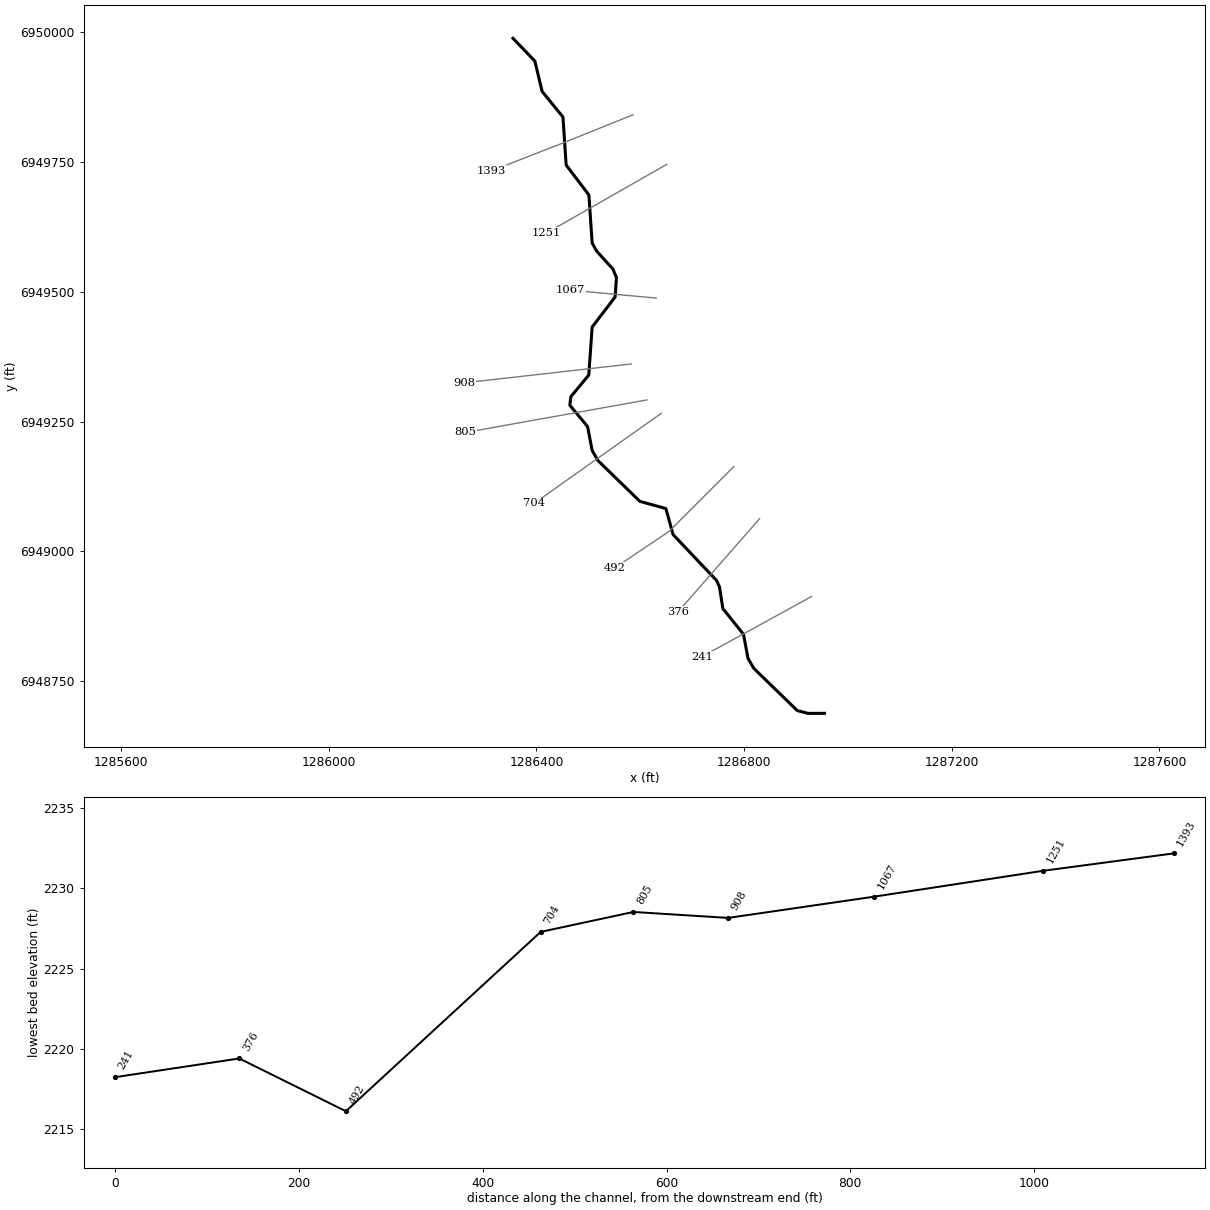
--- UCFB HW Trib 18.prj (project) ---

Proj Title=UCFB HW Trib 18 Base Level Engineering
Current Plan=p01
Default Exp/Contr=0.3,0.1
English Units
Geom File=g01
Flow File=f01
Plan File=p01
BEGIN DESCRIPTION:
UCFB HW Trib 18
END DESCRIPTION:

--- UCFB HW Trib 18.p01 (plan) ---

Plan Title=Multiple Run
Short Identifier=Multiple
Geom File=g01
Flow File=f01
Subcritical Flow
K Sum by GR= 0
Std Step Tol= 0.01
Critical Tol= 0.01
Num of Std Step Trials= 20
Max Error Tol= 0.3
Flow Tol Ratio= 0.001
Split Flow NTrial= 30
Split Flow Tol= 0.02
Split Flow Ratio= 0.02
Log Output Level= 0
Friction Slope Method= 1
Unsteady Friction Slope Method= 2
Unsteady Bridges Friction Slope Method= 1
Parabolic Critical Depth
Global Vel Dist=  1 , 1 , 1
Global Log Level= 0
CheckData=True
Encroach Param= -1, 0, 0, 0
BEGIN DESCRIPTION:
Multiple Run
END DESCRIPTION:

--- UCFB HW Trib 18.f01 (steady flow) ---

Flow Title=Multiple
Number of Profiles=7
Profile Names=10-year,25-year,50-year,1pct_min,100-year,1pct_plu,500-year
River Rch & RM= UCFB HW Trib 18,Reach-1,1393
     303     435     548     343     685    1367    1085
Boundary for River Rch & Prof#=UCFB HW Trib 18,Reach-1,1
Up Type=0
Dn Type=3
Dn Slope=0.005
Boundary for River Rch & Prof#=UCFB HW Trib 18,Reach-1,2
Up Type=0
Dn Type=3
Dn Slope=0.005
Boundary for River Rch & Prof#=UCFB HW Trib 18,Reach-1,3
Up Type=0
Dn Type=3
Dn Slope=0.005
Boundary for River Rch & Prof#=UCFB HW Trib 18,Reach-1,4
Up Type=0
Dn Type=3
Dn Slope=0.005
Boundary for River Rch & Prof#=UCFB HW Trib 18,Reach-1,5
Up Type=0
Dn Type=3
Dn Slope=0.005
Boundary for River Rch & Prof#=UCFB HW Trib 18,Reach-1,6
Up Type=0
Dn Type=3
Dn Slope=0.005
Boundary for River Rch & Prof#=UCFB HW Trib 18,Reach-1,7
Up Type=0
Dn Type=3
Dn Slope=0.005

--- UCFB HW Trib 18.g01 (geometry) ---

Geom Title=Existing Conditions

River Reach=UCFB HW Trib 18,Reach-1
Reach XY= 30
      1286355.00      6949988.00      1286397.09      6949944.15
      1286411.03      6949885.78      1286451.18      6949836.42
      1286457.35      6949743.97      1286501.15      6949686.40
      1286507.38      6949593.97      1286515.95      6949578.35
      1286547.19      6949543.92      1286554.23      6949527.31
      1286551.63      6949489.73      1286507.38      6949432.03
      1286500.91      6949339.50      1286466.45      6949297.90
      1286464.41      6949281.38      1286498.59      6949240.28
      1286507.45      6949194.04      1286518.60      6949174.76
      1286599.23      6949096.28      1286649.38      6949082.38
      1286663.30      6949032.26      1286746.84      6948944.05
      1286752.49      6948931.96      1286759.19      6948889.73
      1286798.90      6948840.19      1286807.49      6948794.03
      1286818.60      6948774.76      1286902.46      6948693.30
      1286923.11      6948687.92      1286955.00      6948688.00

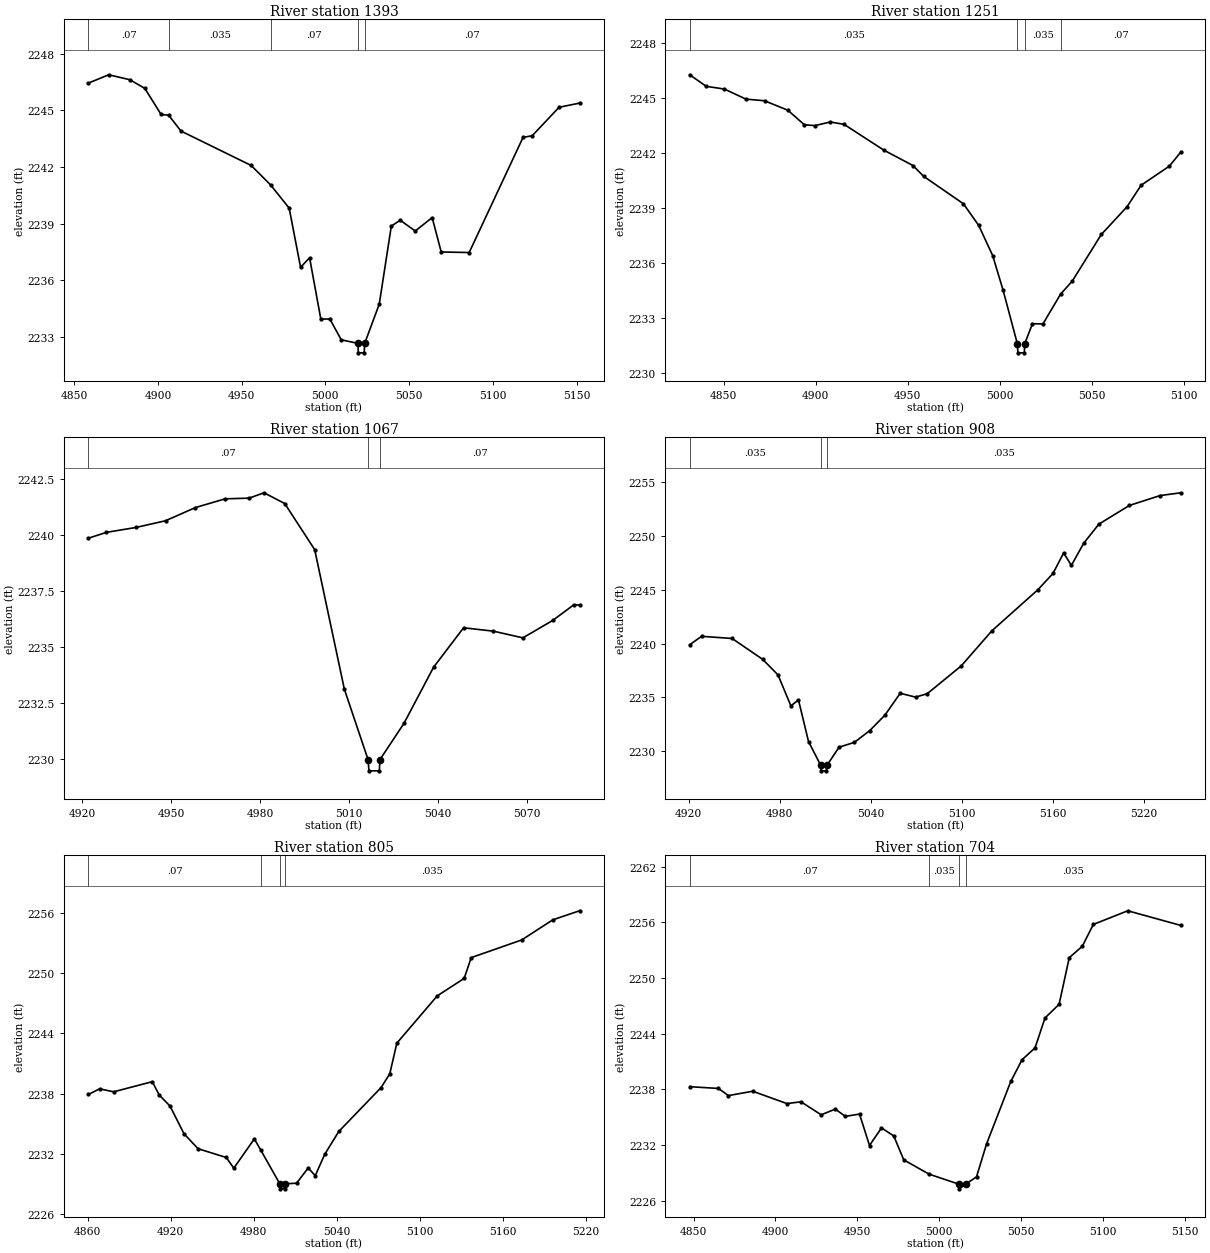
Type RM Length L Ch R = 1,1393,142,142,142
BEGIN DESCRIPTION:
UCFB HW Trib 18 3.0
END DESCRIPTION:
XS GIS Cut Line= 3
      1286586.26      6949840.85      1286455.00      6949788.00
      1286313.65      6949732.66
#Sta/Elev= 30
  4858.5 2246.44  4870.6 2246.88  4883.2 2246.62  4892.2 2246.16  4901.9 2244.78
  4906.4 2244.74  4913.8 2243.90  4955.7 2242.08  4967.3 2241.05  4978.4 2239.82
  4985.2 2236.69  4990.6 2237.19  4997.3 2233.95  5002.7 2233.95  5009.5 2232.85
  5019.5 2232.66  5019.7 2232.16  5023.2 2232.16  5023.5 2232.66  5032.2 2234.74
  5039.4 2238.87  5044.7 2239.18  5053.7 2238.61  5063.8 2239.32  5069.2 2237.50
  5085.9 2237.47  5118.1 2243.57  5123.5 2243.65  5139.6 2245.16  5151.8 2245.38
#Mann=5,-1,0
  4858.5    0.07       0  4906.4   0.035       0  4967.3    0.07       0
  5019.5    0.07       0  5023.5    0.07       0
Bank Sta=5019.5,5023.5
Exp/Cntr=0.3,0.1

Type RM Length L Ch R = 1,1251,184,184,184
BEGIN DESCRIPTION:
UCFB HW Trib 18 2.5
END DESCRIPTION:
XS GIS Cut Line= 2
      1286651.31      6949745.34      1286419.62      6949613.25
#Sta/Elev= 30
  4831.6 2246.28  4840.5 2245.65  4850.4 2245.50  4862.1 2244.95  4872.2 2244.86
  4884.9 2244.34  4893.8 2243.55  4899.5 2243.50  4907.9 2243.70  4915.4 2243.57
  4937.0 2242.16  4952.8 2241.32  4958.6 2240.73  4980.2 2239.23  4988.5 2238.05
  4996.1 2236.40  5001.8 2234.49  5009.5 2231.58  5009.8 2231.08  5013.3 2231.08
  5013.5 2231.58  5017.7 2232.67  5023.4 2232.66  5033.0 2234.29  5039.3 2235.00
  5055.1 2237.55  5069.1 2239.07  5076.7 2240.24  5092.1 2241.29  5098.3 2242.06
#Mann=4,-1,0
  4831.6   0.035       0  5009.5   0.035       0  5013.5   0.035       0
  5033.0    0.07       0
Bank Sta=5009.5,5013.5
Exp/Cntr=0.3,0.1

Type RM Length L Ch R = 1,1067,159,159,159
BEGIN DESCRIPTION:
UCFB HW Trib 18 2.0
END DESCRIPTION:
XS GIS Cut Line= 2
      1286630.93      6949487.75      1286466.03      6949502.94
#Sta/Elev= 23
  4922.1 2239.86  4928.1 2240.12  4938.1 2240.34  4948.1 2240.64  4958.2 2241.23
  4968.2 2241.62  4976.3 2241.65  4981.3 2241.89  4988.3 2241.41  4998.4 2239.35
  5008.4 2233.12  5016.4 2229.97  5016.7 2229.47  5020.2 2229.47  5020.4 2229.97
  5028.5 2231.59  5038.5 2234.10  5048.6 2235.86  5058.6 2235.71  5068.6 2235.41
  5078.7 2236.19  5085.7 2236.88  5087.7 2236.88
#Mann=3,-1,0
  4922.1    0.07       0  5016.4    0.07       0  5020.4    0.07       0
Bank Sta=5016.4,5020.4
Exp/Cntr=0.3,0.1

Type RM Length L Ch R = 1,908,103,103,103
BEGIN DESCRIPTION:
UCFB HW Trib 18 1.8
END DESCRIPTION:
XS GIS Cut Line= 2
      1286582.72      6949360.87      1286261.36      6949324.55
#Sta/Elev= 30
  4920.8 2239.89  4928.6 2240.67  4948.7 2240.47  4968.8 2238.53  4978.9 2237.08
  4987.4 2234.20  4992.4 2234.75  4999.0 2230.88  5007.1 2228.65  5007.3 2228.15
  5010.8 2228.15  5011.1 2228.65  5019.1 2230.35  5029.2 2230.80  5039.3 2231.89
  5049.3 2233.33  5059.4 2235.37  5069.5 2235.01  5077.2 2235.33  5099.6 2237.92
  5119.8 2241.19  5150.0 2245.00  5160.0 2246.52  5167.0 2248.43  5172.1 2247.27
  5180.2 2249.33  5190.2 2251.11  5210.3 2252.85  5230.5 2253.77  5244.2 2254.03
#Mann=3,-1,0
  4920.8   0.035       0  5007.1   0.035       0  5011.1   0.035       0
Bank Sta=5007.1,5011.1
Exp/Cntr=0.3,0.1

Type RM Length L Ch R = 1,805,101,101,101
BEGIN DESCRIPTION:
UCFB HW Trib 18 1.7
END DESCRIPTION:
XS GIS Cut Line= 2
      1286612.96      6949291.58      1286263.91      6949229.06
#Sta/Elev= 30
  4860.6 2237.91  4868.7 2238.47  4878.8 2238.17  4906.7 2239.18  4911.8 2237.84
  4919.5 2236.76  4929.6 2234.00  4939.8 2232.51  4960.1 2231.64  4965.6 2230.58
  4980.4 2233.49  4984.9 2232.41  4998.8 2229.02  4999.0 2228.52  5002.5 2228.52
  5002.8 2229.02  5010.9 2229.08  5019.3 2230.60  5024.4 2229.83  5031.2 2231.95
  5041.4 2234.23  5071.9 2238.59  5078.2 2239.96  5083.3 2243.01  5112.5 2247.72
  5131.9 2249.45  5137.0 2251.52  5173.5 2253.28  5195.9 2255.28  5215.2 2256.18
#Mann=4,-1,0
  4860.6    0.07       0  4984.9   0.035       0  4998.8   0.035       0
  5002.8   0.035       0
Bank Sta=4998.8,5002.8
Exp/Cntr=0.3,0.1

Type RM Length L Ch R = 1,704,212,212,212
BEGIN DESCRIPTION:
UCFB HW Trib 18 1.5
END DESCRIPTION:
XS GIS Cut Line= 2
      1286640.49      6949265.75      1286395.88      6949092.58
#Sta/Elev= 30
  4847.7 2238.29  4865.2 2238.10  4871.3 2237.33  4886.1 2237.80  4907.0 2236.47
  4915.6 2236.66  4927.9 2235.26  4936.5 2235.87  4942.7 2235.09  4951.3 2235.34
  4957.4 2231.95  4964.7 2233.85  4972.2 2232.98  4978.3 2230.40  4993.8 2228.86
  5012.0 2227.78  5012.3 2227.28  5016.0 2227.78  5022.7 2228.57  5028.8 2232.11
  5043.6 2238.85  5050.5 2241.20  5058.4 2242.47  5064.5 2245.70  5073.1 2247.17
  5079.3 2252.20  5087.2 2253.41  5094.0 2255.78  5115.0 2257.25  5147.4 2255.67
#Mann=4,-1,0
  4847.7    0.07       0  4993.8   0.035       0  5012.0   0.035       0
  5016.0   0.035       0
Bank Sta=5012,5016
Exp/Cntr=0.3,0.1

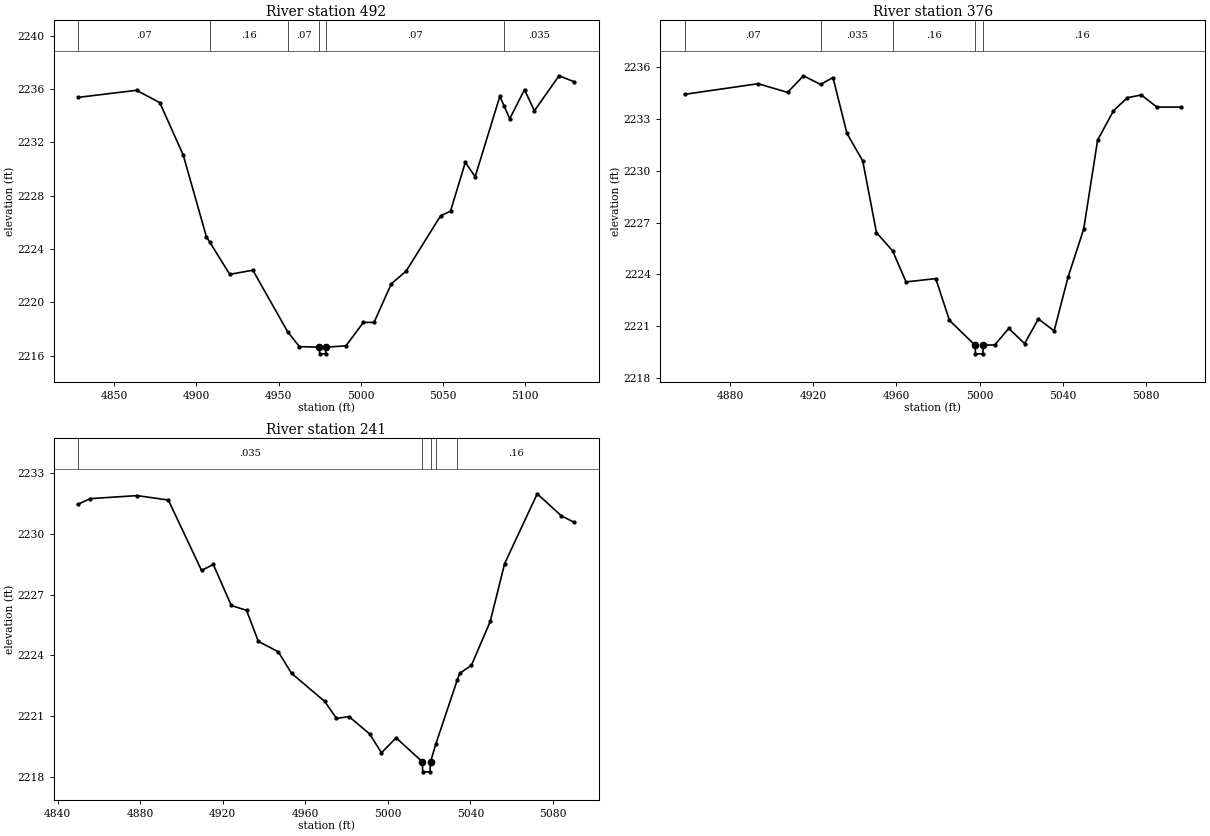
Type RM Length L Ch R = 1,492,116,116,116
BEGIN DESCRIPTION:
UCFB HW Trib 18 1.0
END DESCRIPTION:
XS GIS Cut Line= 3
      1286780.03      6949163.03      1286655.00      6949038.00
      1286551.52      6948968.45
#Sta/Elev= 30
  4828.3 2235.39  4863.7 2235.92  4877.8 2234.99  4892.0 2231.08  4906.1 2224.94
  4908.3 2224.50  4920.3 2222.10  4934.4 2222.41  4955.6 2217.78  4962.7 2216.67
  4974.8 2216.63  4975.1 2216.13  4978.6 2216.13  4978.8 2216.63  4991.0 2216.73
  5001.6 2218.49  5008.1 2218.49  5018.6 2221.39  5027.6 2222.34  5048.6 2226.50
  5054.6 2226.84  5063.6 2230.51  5069.6 2229.43  5084.6 2235.47  5087.1 2234.77
  5090.6 2233.78  5099.6 2235.97  5105.6 2234.38  5120.6 2237.01  5129.8 2236.56
#Mann=6,-1,0
  4828.3    0.07       0  4908.3    0.16       0  4955.6    0.07       0
  4974.8    0.07       0  4978.8    0.07       0  5087.1   0.035       0
Bank Sta=4974.8,4978.8
Exp/Cntr=0.3,0.1

Type RM Length L Ch R = 1,376,135,135,135
BEGIN DESCRIPTION:
UCFB HW Trib 18 0.7
END DESCRIPTION:
XS GIS Cut Line= 2
      1286830.03      6949063.03      1286673.01      6948883.78
#Sta/Elev= 30
  4858.3 2234.42  4893.5 2235.03  4907.7 2234.53  4915.3 2235.49  4923.5 2234.99
  4929.5 2235.39  4936.2 2232.16  4943.8 2230.57  4950.4 2226.42  4958.2 2225.36
  4964.6 2223.57  4978.9 2223.76  4985.5 2221.34  4997.8 2219.91  4998.0 2219.41
  5001.5 2219.41  5001.8 2219.91  5007.3 2219.93  5014.0 2220.88  5021.6 2220.00
  5028.2 2221.43  5035.8 2220.74  5042.5 2223.85  5050.0 2226.62  5056.7 2231.77
  5064.3 2233.46  5070.9 2234.22  5077.7 2234.38  5085.2 2233.68  5096.6 2233.68
#Mann=5,-1,0
  4858.3    0.07       0  4923.5   0.035       0  4958.2    0.16       0
  4997.8    0.07       0  5001.8    0.16       0
Bank Sta=4997.8,5001.8
Exp/Cntr=0.3,0.1

Type RM Length L Ch R = 1,241,0,0,0
BEGIN DESCRIPTION:
UCFB HW Trib 18 0.5
END DESCRIPTION:
XS GIS Cut Line= 2
      1286929.99      6948913.00      1286719.33      6948797.39
#Sta/Elev= 30
  4850.0 2231.48  4855.7 2231.75  4878.5 2231.90  4893.6 2231.68  4909.7 2228.20
  4915.4 2228.50  4924.1 2226.47  4931.5 2226.23  4937.2 2224.70  4946.9 2224.18
  4953.3 2223.12  4969.4 2221.73  4975.1 2220.89  4981.2 2220.98  4991.2 2220.12
  4996.9 2219.19  5004.0 2219.93  5016.7 2218.75  5016.9 2218.25  5020.4 2218.25
  5020.7 2218.75  5023.3 2219.64  5033.7 2222.81  5034.8 2223.12  5040.5 2223.51
  5049.6 2225.68  5056.6 2228.54  5072.4 2231.99  5084.1 2230.90  5090.3 2230.58
#Mann=5,-1,0
  4850.0   0.035       0  5016.7   0.035       0  5020.7   0.035       0
  5023.3    0.07       0  5033.7    0.16       0
Bank Sta=5016.7,5020.7
Exp/Cntr=0.3,0.1

Chan Stop Cuts=-1