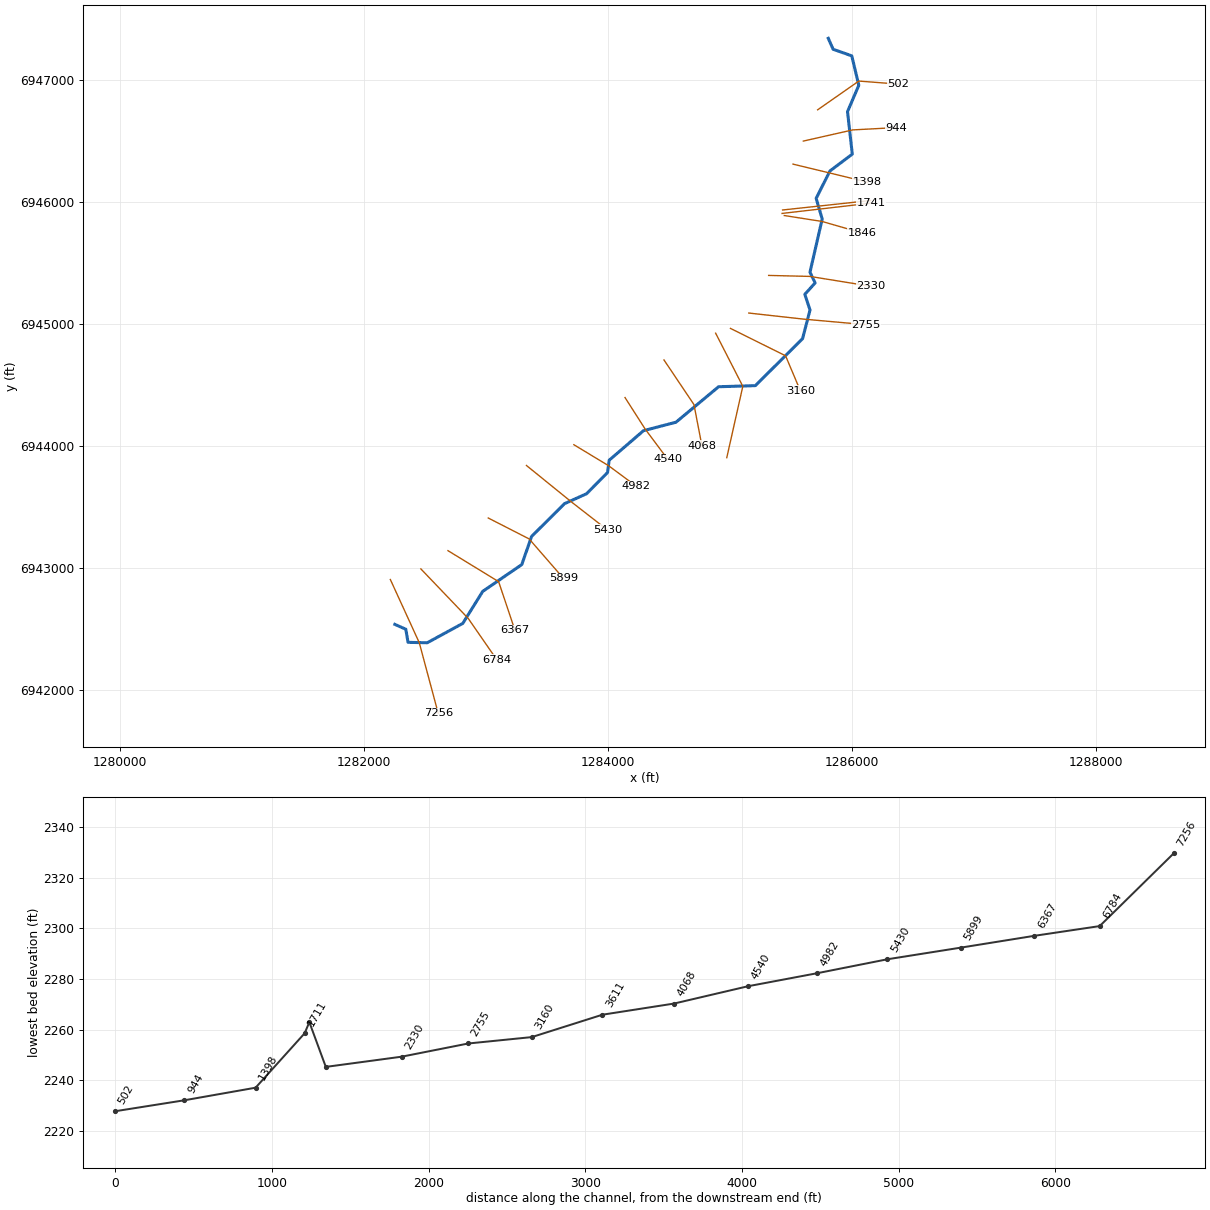
--- UCFB HW Trib 19.prj (project) ---

Proj Title=UCFB HW Trib 19 Base Level Engineering
Current Plan=p01
Default Exp/Contr=0.3,0.1
English Units
Geom File=g01
Flow File=f01
Plan File=p01
BEGIN DESCRIPTION:
UCFB HW Trib 19
END DESCRIPTION:

--- UCFB HW Trib 19.p01 (plan) ---

Plan Title=Multiple Run
Short Identifier=Multiple
Geom File=g01
Flow File=f01
Subcritical Flow
K Sum by GR= 0
Std Step Tol= 0.01
Critical Tol= 0.01
Num of Std Step Trials= 20
Max Error Tol= 0.3
Flow Tol Ratio= 0.001
Split Flow NTrial= 30
Split Flow Tol= 0.02
Split Flow Ratio= 0.02
Log Output Level= 0
Friction Slope Method= 1
Unsteady Friction Slope Method= 2
Unsteady Bridges Friction Slope Method= 1
Parabolic Critical Depth
Global Vel Dist=  1 , 1 , 1
Global Log Level= 0
CheckData=True
Encroach Param= -1, 0, 0, 0
BEGIN DESCRIPTION:
Multiple Run
END DESCRIPTION:

--- UCFB HW Trib 19.f01 (steady flow) ---

Flow Title=Multiple
Number of Profiles=7
Profile Names=10-year,25-year,50-year,1pct_min,100-year,1pct_plu,500-year
River Rch & RM= UCFB HW Trib 19,Reach-1,7256
     289     414     519     325     648    1293    1021
Boundary for River Rch & Prof#=UCFB HW Trib 19,Reach-1,1
Up Type=0
Dn Type=3
Dn Slope=0.005
Boundary for River Rch & Prof#=UCFB HW Trib 19,Reach-1,2
Up Type=0
Dn Type=3
Dn Slope=0.005
Boundary for River Rch & Prof#=UCFB HW Trib 19,Reach-1,3
Up Type=0
Dn Type=3
Dn Slope=0.005
Boundary for River Rch & Prof#=UCFB HW Trib 19,Reach-1,4
Up Type=0
Dn Type=3
Dn Slope=0.005
Boundary for River Rch & Prof#=UCFB HW Trib 19,Reach-1,5
Up Type=0
Dn Type=3
Dn Slope=0.005
Boundary for River Rch & Prof#=UCFB HW Trib 19,Reach-1,6
Up Type=0
Dn Type=3
Dn Slope=0.005
Boundary for River Rch & Prof#=UCFB HW Trib 19,Reach-1,7
Up Type=0
Dn Type=3
Dn Slope=0.005

--- UCFB HW Trib 19.g01 (geometry) ---

Geom Title=Existing Conditions

River Reach=UCFB HW Trib 19,Reach-1
Reach XY= 30
      1282255.00      6942538.00      1282344.72      6942498.05
      1282362.97      6942390.93      1282520.18      6942387.56
      1282811.33      6942546.04      1282974.77      6942808.42
      1283294.61      6943027.90      1283374.78      6943258.09
      1283645.32      6943527.24      1283825.09      6943607.78
      1283997.12      6943781.88      1284010.26      6943882.53
      1284291.68      6944124.63      1284557.30      6944193.83
      1284906.46      6944484.46      1285207.45      6944493.46
      1285594.38      6944878.01      1285655.31      6945112.96
      1285612.83      6945241.42      1285697.15      6945334.59
      1285655.15      6945422.58      1285755.09      6945858.10
      1285705.75      6946027.32      1285818.47      6946251.57
      1286001.47      6946389.45      1285962.56      6946738.00
      1286054.91      6946953.39      1285997.32      6947194.52
      1285844.91      6947248.27      1285805.00      6947338.00

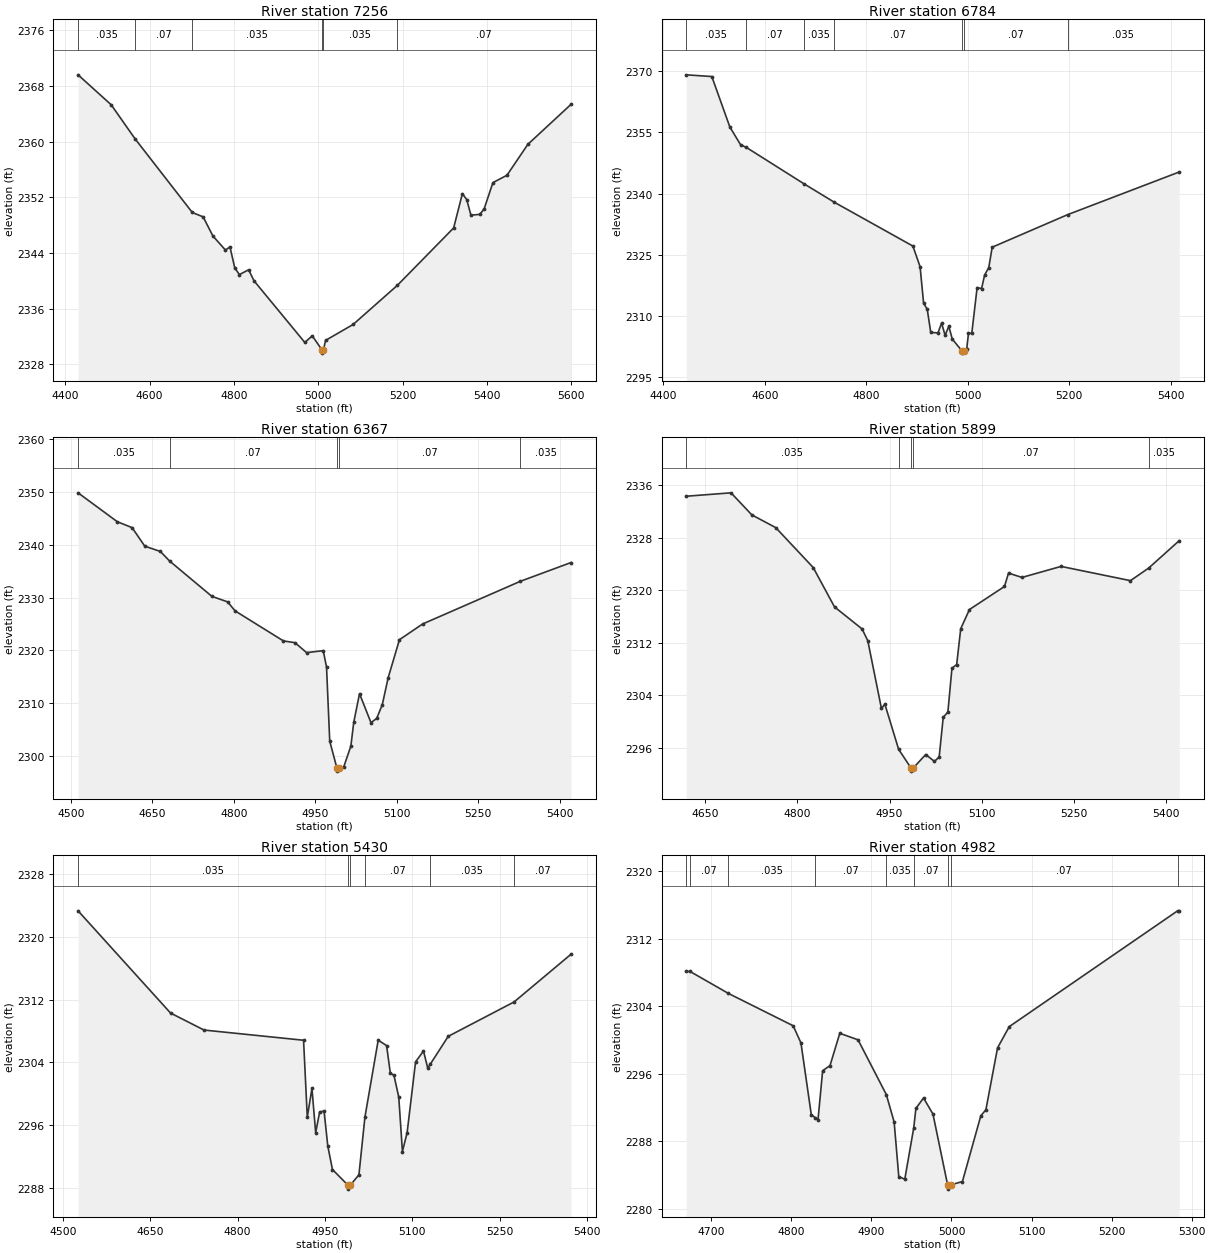
Type RM Length L Ch R = 1,7256,472,472,472
BEGIN DESCRIPTION:
UCFB HW Trib 19 16.0
END DESCRIPTION:
XS GIS Cut Line= 3
      1282217.97      6942905.73      1282455.00      6942388.00
      1282610.17      6941809.14
#Sta/Elev= 30
  4430.4 2369.60  4508.9 2365.30  4565.5 2360.41  4701.2 2349.83  4726.9 2349.20
  4750.0 2346.46  4779.8 2344.43  4790.5 2344.89  4801.8 2341.89  4812.8 2340.91
  4834.8 2341.60  4847.5 2340.02  4968.0 2331.16  4985.6 2332.12  5008.2 2330.13
  5008.4 2329.63  5012.2 2330.13  5017.2 2331.46  5082.6 2333.75  5187.3 2339.36
  5320.8 2347.61  5341.5 2352.53  5351.8 2351.69  5361.8 2349.44  5382.9 2349.56
  5393.2 2350.36  5413.9 2354.12  5447.1 2355.17  5496.8 2359.62  5599.1 2365.36
#Mann=6,-1,0
  4430.4   0.035       0  4565.5    0.07       0  4701.2   0.035       0
  5008.2   0.035       0  5012.2   0.035       0  5187.3    0.07       0
Bank Sta=5008.2,5012.2
Exp/Cntr=0.3,0.1

Type RM Length L Ch R = 1,6784,417,417,417
BEGIN DESCRIPTION:
UCFB HW Trib 19 15.0
END DESCRIPTION:
XS GIS Cut Line= 3
      1282468.02      6942992.46      1282855.00      6942588.00
      1283089.51      6942249.46
#Sta/Elev= 30
  4444.9 2369.04  4495.3 2368.62  4530.9 2356.26  4551.9 2351.95  4563.6 2351.26
  4676.8 2342.39  4736.5 2337.88  4891.6 2327.14  4905.8 2322.08  4912.7 2313.18
  4919.9 2311.67  4926.8 2306.01  4941.0 2305.89  4948.2 2308.29  4955.1 2305.29
  4962.4 2307.51  4969.3 2304.36  4988.7 2301.44  4988.9 2300.94  4992.7 2301.44
  4997.6 2301.89  5001.2 2305.80  5007.7 2305.80  5018.2 2316.98  5027.0 2316.74
  5033.0 2320.05  5041.2 2321.89  5047.9 2326.86  5196.5 2334.82  5416.5 2345.26
#Mann=7,-1,0
  4444.9   0.035       0  4563.6    0.07       0  4676.8   0.035       0
  4736.5    0.07       0  4988.7    0.07       0  4992.7    0.07       0
  5196.5   0.035       0
Bank Sta=4988.7,4992.7
Exp/Cntr=0.3,0.1

Type RM Length L Ch R = 1,6367,468,468,468
BEGIN DESCRIPTION:
UCFB HW Trib 19 14.0
END DESCRIPTION:
XS GIS Cut Line= 3
      1282690.24      6943141.78      1283105.00      6942888.00
      1283238.84      6942488.99
#Sta/Elev= 30
  4513.5 2349.88  4585.7 2344.40  4612.9 2343.28  4636.3 2339.76  4665.0 2338.76
  4681.8 2336.96  4759.8 2330.24  4788.7 2329.20  4802.4 2327.49  4891.4 2321.79
  4912.7 2321.46  4934.0 2319.57  4964.6 2319.95  4970.7 2316.83  4976.6 2302.78
  4990.0 2297.60  4990.3 2297.10  4994.0 2297.60  5002.4 2297.91  5015.5 2301.86
  5020.8 2306.37  5031.4 2311.79  5052.5 2306.29  5063.0 2307.10  5073.3 2309.70
  5084.1 2314.81  5104.9 2322.03  5147.4 2325.00  5327.1 2333.09  5420.6 2336.66
#Mann=5,-1,0
  4513.5   0.035       0  4681.8    0.07       0  4990.0    0.07       0
  4994.0    0.07       0  5327.1   0.035       0
Bank Sta=4990,4994
Exp/Cntr=0.3,0.1

Type RM Length L Ch R = 1,5899,469,469,469
BEGIN DESCRIPTION:
UCFB HW Trib 19 13.0
END DESCRIPTION:
XS GIS Cut Line= 3
      1283020.06      6943409.17      1283355.00      6943238.00
      1283634.69      6942916.07
#Sta/Elev= 30
  4618.9 2334.33  4691.8 2334.85  4725.7 2331.49  4764.6 2329.55  4825.6 2323.47
  4860.3 2317.47  4905.2 2314.11  4914.5 2312.31  4936.7 2302.00  4942.3 2302.65
  4964.7 2295.77  4984.7 2292.95  4985.0 2292.45  4988.7 2292.95  5008.8 2294.98
  5023.0 2293.93  5030.7 2294.61  5037.3 2300.64  5044.9 2301.46  5051.5 2308.12
  5059.2 2308.69  5065.8 2314.15  5080.0 2317.07  5137.0 2320.58  5143.6 2322.62
  5165.5 2321.96  5229.1 2323.64  5342.1 2321.47  5371.7 2323.38  5421.5 2327.56
#Mann=5,-1,0
  4618.9   0.035       0  4964.7    0.07       0  4984.7    0.07       0
  4988.7    0.07       0  5371.7   0.035       0
Bank Sta=4984.7,4988.7
Exp/Cntr=0.3,0.1

Type RM Length L Ch R = 1,5430,448,448,448
BEGIN DESCRIPTION:
UCFB HW Trib 19 12.0
END DESCRIPTION:
XS GIS Cut Line= 3
      1283332.61      6943839.69      1283705.00      6943538.00
      1283995.08      6943312.47
#Sta/Elev= 30
  4526.1 2323.31  4684.9 2310.29  4742.4 2308.12  4913.4 2306.82  4919.8 2297.01
  4927.8 2300.68  4934.2 2295.04  4941.0 2297.67  4948.6 2297.80  4955.0 2293.36
  4963.0 2290.35  4989.7 2288.35  4990.0 2287.85  4993.7 2288.35  5008.5 2289.68
  5018.8 2297.02  5041.6 2306.83  5056.0 2306.14  5062.4 2302.65  5068.7 2302.33
  5076.9 2299.58  5083.2 2292.64  5091.3 2295.06  5105.8 2304.07  5119.4 2305.45
  5126.6 2303.29  5130.9 2303.75  5161.9 2307.32  5275.0 2311.70  5372.8 2317.78
#Mann=6,-1,0
  4526.1   0.035       0  4989.7   0.035       0  4993.7   0.035       0
  5018.8    0.07       0  5130.9   0.035       0  5275.0    0.07       0
Bank Sta=4989.7,4993.7
Exp/Cntr=0.3,0.1

Type RM Length L Ch R = 1,4982,442,442,442
BEGIN DESCRIPTION:
UCFB HW Trib 19 11.0
END DESCRIPTION:
XS GIS Cut Line= 3
      1283721.34      6944009.49      1284005.00      6943838.00
      1284233.49      6943668.78
#Sta/Elev= 30
  4668.7 2308.12  4673.5 2308.12  4721.4 2305.52  4802.3 2301.69  4812.0 2299.66
  4824.9 2291.17  4829.7 2290.82  4833.3 2290.55  4839.1 2296.37  4848.3 2296.98
  4860.5 2300.80  4883.3 2300.03  4918.6 2293.55  4928.4 2290.30  4934.2 2283.84
  4941.7 2283.52  4952.9 2289.61  4955.6 2291.91  4965.1 2293.14  4976.9 2291.24
  4995.2 2282.85  4995.5 2282.35  4999.2 2282.85  5013.7 2283.25  5036.7 2291.04
  5043.0 2291.74  5057.6 2299.08  5072.2 2301.59  5282.5 2315.30  5284.5 2315.30
#Mann=9,-1,0
  4668.7   0.035       0  4673.5    0.07       0  4721.4   0.035       0
  4829.7    0.07       0  4918.6   0.035       0  4952.9    0.07       0
  4995.2    0.07       0  4999.2    0.07       0  5282.5   0.035       0
Bank Sta=4995.2,4999.2
Exp/Cntr=0.3,0.1

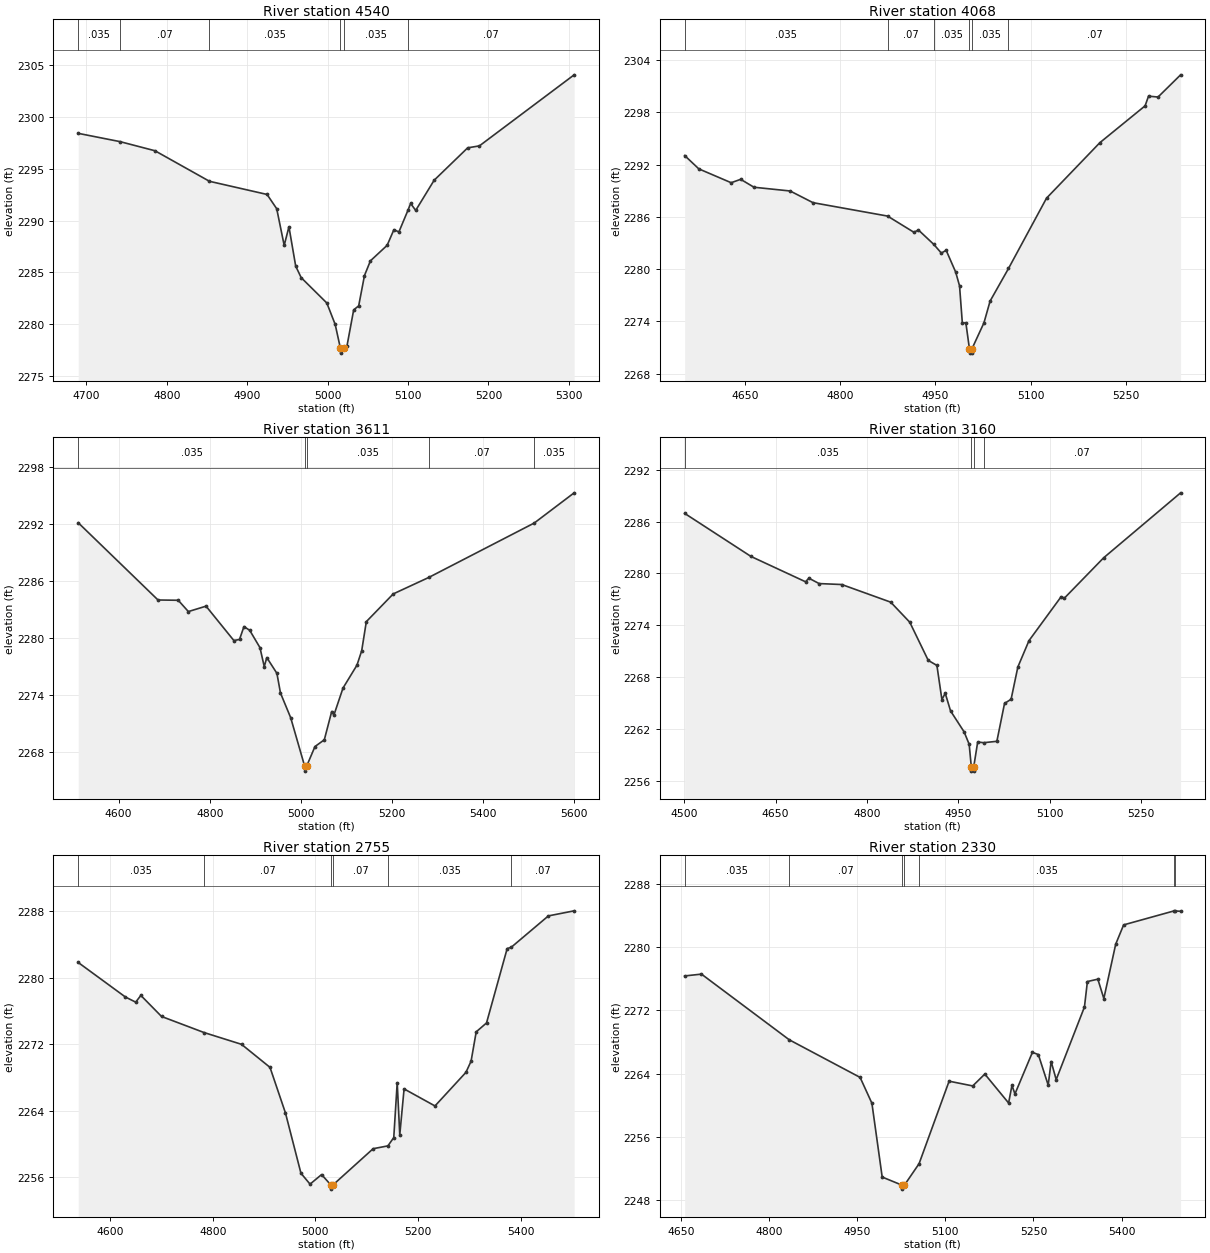
Type RM Length L Ch R = 1,4540,472,472,472
BEGIN DESCRIPTION:
UCFB HW Trib 19 10.0
END DESCRIPTION:
XS GIS Cut Line= 3
      1284140.18      6944395.79      1284305.00      6944138.00
      1284490.88      6943889.13
#Sta/Elev= 30
  4690.0 2298.42  4742.0 2297.62  4785.4 2296.74  4853.2 2293.79  4924.8 2292.52
  4936.8 2291.14  4946.1 2287.60  4952.0 2289.40  4960.4 2285.60  4967.2 2284.49
  4999.1 2282.04  5009.5 2279.97  5015.9 2277.70  5016.1 2277.20  5019.9 2277.70
  5024.1 2277.87  5032.5 2281.38  5038.7 2281.76  5045.9 2284.69  5053.3 2286.11
  5074.1 2287.61  5082.5 2289.12  5088.7 2288.90  5099.9 2290.98  5103.3 2291.65
  5109.6 2290.98  5132.5 2293.89  5174.2 2297.02  5188.8 2297.21  5306.6 2304.07
#Mann=6,-1,0
  4690.0   0.035       0  4742.0    0.07       0  4853.2   0.035       0
  5015.9   0.035       0  5019.9   0.035       0  5099.9    0.07       0
Bank Sta=5015.9,5019.9
Exp/Cntr=0.3,0.1

Type RM Length L Ch R = 1,4068,457,457,457
BEGIN DESCRIPTION:
UCFB HW Trib 19 9.0
END DESCRIPTION:
XS GIS Cut Line= 3
      1284459.18      6944703.96      1284705.00      6944338.00
      1284769.53      6944003.02
#Sta/Elev= 30
  4554.7 2293.05  4577.0 2291.52  4628.0 2289.93  4643.0 2290.32  4664.0 2289.41
  4721.0 2288.98  4757.0 2287.64  4874.6 2286.10  4916.1 2284.24  4923.3 2284.50
  4947.6 2282.84  4959.4 2281.85  4967.0 2282.17  4982.0 2279.67  4988.1 2278.09
  4992.5 2273.83  4998.1 2273.83  5003.7 2270.86  5004.0 2270.36  5007.5 2270.36
  5007.7 2270.86  5026.6 2273.84  5036.3 2276.34  5065.3 2280.08  5125.3 2288.16
  5209.4 2294.53  5280.7 2298.76  5286.1 2299.87  5301.1 2299.77  5336.7 2302.32
#Mann=6,-1,0
  4554.7   0.035       0  4874.6    0.07       0  4947.6   0.035       0
  5003.7   0.035       0  5007.7   0.035       0  5065.3    0.07       0
Bank Sta=5003.7,5007.7
Exp/Cntr=0.3,0.1

Type RM Length L Ch R = 1,3611,451,451,451
BEGIN DESCRIPTION:
UCFB HW Trib 19 8.0
END DESCRIPTION:
XS GIS Cut Line= 3
      1284882.40      6944923.07      1285105.00      6944488.00
      1284973.52      6943903.11
#Sta/Elev= 30
  4511.2 2292.13  4686.3 2283.99  4730.7 2283.96  4752.9 2282.77  4791.7 2283.34
  4852.7 2279.72  4865.1 2279.83  4874.9 2281.19  4887.6 2280.79  4910.0 2278.97
  4919.4 2276.97  4925.0 2277.92  4947.2 2276.26  4955.0 2274.19  4977.4 2271.59
  5008.2 2266.46  5008.4 2265.96  5012.2 2266.46  5030.7 2268.55  5051.2 2269.26
  5067.4 2272.24  5072.5 2271.90  5092.2 2274.71  5122.9 2277.13  5133.2 2278.64
  5143.4 2281.71  5202.4 2284.63  5280.2 2286.36  5511.9 2292.10  5599.4 2295.28
#Mann=5,-1,0
  4511.2   0.035       0  5008.2   0.035       0  5012.2   0.035       0
  5280.2    0.07       0  5511.9   0.035       0
Bank Sta=5008.2,5012.2
Exp/Cntr=0.3,0.1

Type RM Length L Ch R = 1,3160,405,405,405
BEGIN DESCRIPTION:
UCFB HW Trib 19 7.0
END DESCRIPTION:
XS GIS Cut Line= 3
      1285003.88      6944962.19      1285455.00      6944738.00
      1285576.19      6944451.54
#Sta/Elev= 30
  4500.6 2286.94  4609.5 2281.96  4699.1 2279.03  4704.7 2279.44  4721.5 2278.82
  4758.7 2278.71  4839.1 2276.67  4870.4 2274.35  4900.8 2269.93  4915.0 2269.35
  4923.2 2265.40  4928.7 2266.13  4937.4 2264.09  4959.7 2261.66  4968.0 2260.23
  4971.5 2257.62  4971.8 2257.12  4975.3 2257.12  4975.5 2257.62  4982.0 2260.49
  4991.8 2260.41  5013.5 2260.57  5026.1 2264.95  5036.9 2265.44  5048.0 2269.17
  5066.3 2272.22  5119.1 2277.30  5124.5 2277.14  5188.9 2281.80  5315.4 2289.32
#Mann=4,-1,0
  4500.6   0.035       0  4971.5    0.07       0  4975.5   0.035       0
  4991.8    0.07       0
Bank Sta=4971.5,4975.5
Exp/Cntr=0.3,0.1

Type RM Length L Ch R = 1,2755,425,425,425
BEGIN DESCRIPTION:
UCFB HW Trib 19 6.0
END DESCRIPTION:
XS GIS Cut Line= 3
      1285153.70      6945088.04      1285605.00      6945038.00
      1286115.01      6944992.56
#Sta/Elev= 30
  4538.0 2281.85  4629.9 2277.70  4650.0 2277.08  4660.0 2277.89  4700.3 2275.36
  4783.4 2273.42  4856.1 2272.01  4911.6 2269.24  4941.7 2263.76  4971.9 2256.51
  4989.6 2255.20  5012.1 2256.35  5030.2 2255.10  5030.5 2254.60  5034.2 2255.10
  5112.5 2259.46  5141.3 2259.80  5152.7 2260.80  5159.4 2267.40  5164.4 2261.13
  5172.8 2266.65  5233.0 2264.60  5293.3 2268.64  5303.3 2269.98  5313.3 2273.51
  5333.4 2274.58  5373.6 2283.52  5381.6 2283.68  5453.9 2287.45  5504.1 2288.06
#Mann=6,-1,0
  4538.0   0.035       0  4783.4    0.07       0  5030.2    0.07       0
  5034.2    0.07       0  5141.3   0.035       0  5381.6    0.07       0
Bank Sta=5030.2,5034.2
Exp/Cntr=0.3,0.1

Type RM Length L Ch R = 1,2330,484,484,484
BEGIN DESCRIPTION:
UCFB HW Trib 19 5.0
END DESCRIPTION:
XS GIS Cut Line= 3
      1285316.44      6945396.20      1285655.00      6945388.00
      1286154.05      6945307.23
#Sta/Elev= 30
  4656.4 2276.37  4685.0 2276.60  4834.4 2268.29  4955.0 2263.53  4975.1 2260.26
  4992.6 2250.92  5026.4 2249.89  5026.7 2249.39  5030.4 2249.89  5055.4 2252.61
  5106.5 2263.05  5146.7 2262.45  5167.3 2263.95  5207.8 2260.29  5213.5 2262.52
  5218.6 2261.44  5248.3 2266.70  5258.4 2266.42  5275.2 2262.55  5280.2 2265.54
  5288.8 2263.25  5336.9 2272.44  5341.9 2275.66  5359.7 2275.96  5369.9 2273.51
  5390.1 2280.39  5403.6 2282.83  5489.9 2284.61  5490.9 2284.60  5500.6 2284.55
#Mann=7,-1,0
  4656.4   0.035       0  4834.4    0.07       0  5026.4    0.07       0
  5030.4    0.07       0  5055.4   0.035       0  5489.9    0.07       0
  5490.9   0.035       0
Bank Sta=5026.4,5030.4
Exp/Cntr=0.3,0.1

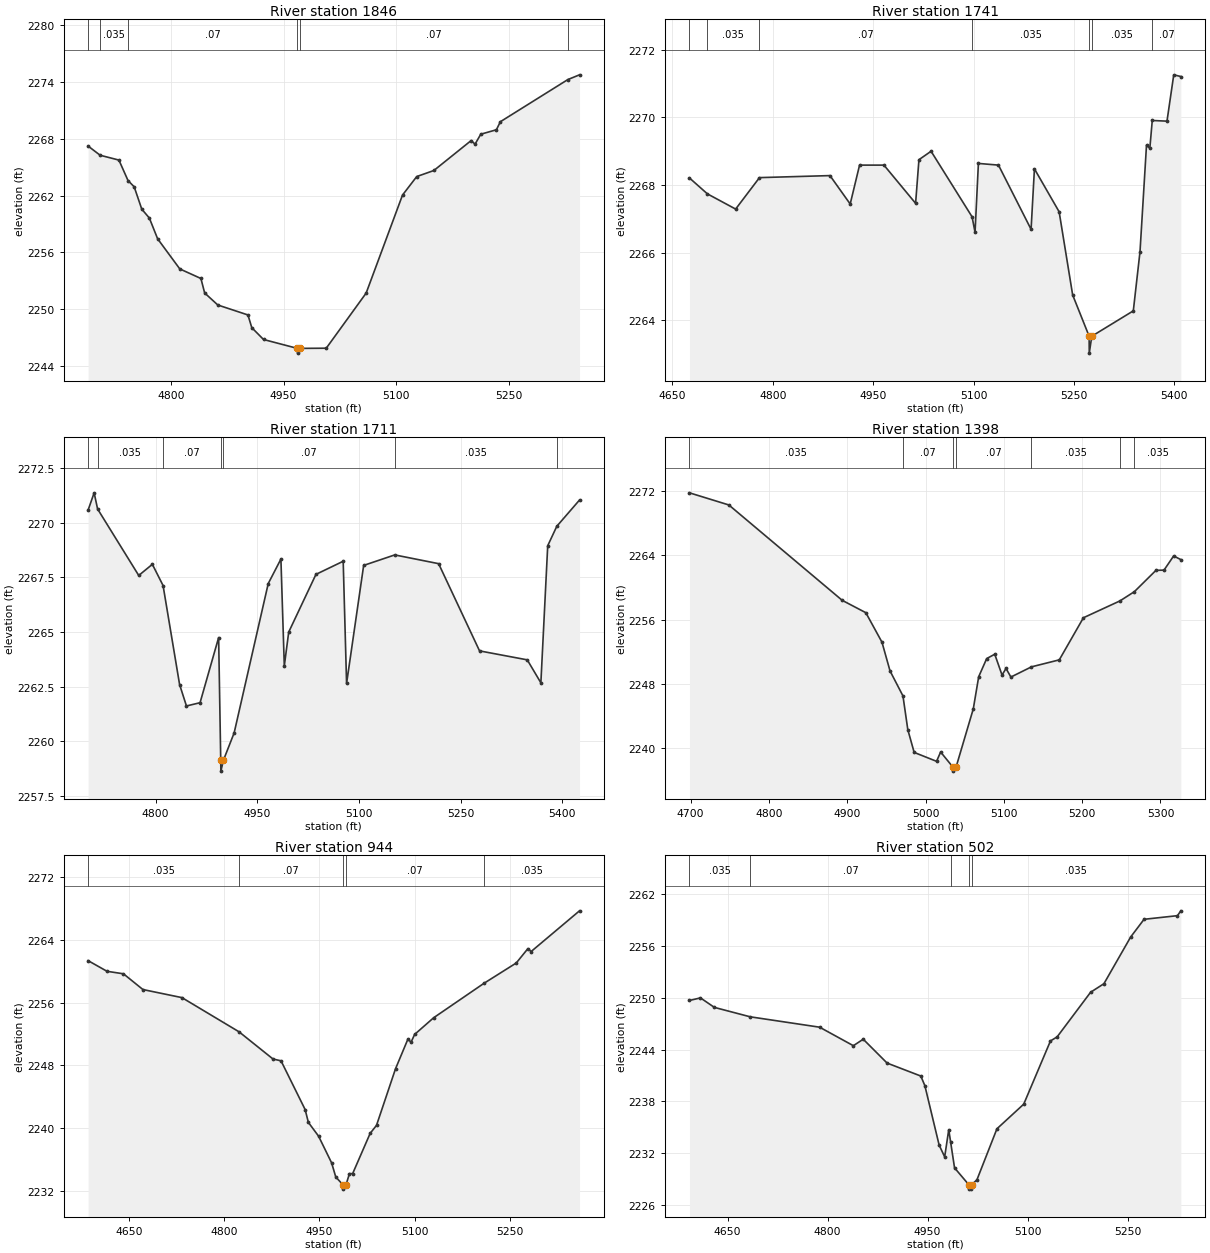
Type RM Length L Ch R = 1,1846,105,105,105
BEGIN DESCRIPTION:
UCFB HW Trib 19 4.0
END DESCRIPTION:
XS GIS Cut Line= 3
      1285444.45      6945886.65      1285755.00      6945838.00
      1286081.23      6945743.78
#Sta/Elev= 30
  4689.9 2267.22  4705.9 2266.25  4730.9 2265.74  4743.0 2263.58  4751.2 2262.92
  4761.3 2260.56  4771.4 2259.62  4782.4 2257.43  4811.9 2254.25  4840.0 2253.24
  4845.0 2251.71  4862.5 2250.44  4902.6 2249.39  4907.7 2248.05  4923.3 2246.80
  4968.4 2245.86  4968.6 2245.36  4972.4 2245.86  5006.8 2245.88  5059.9 2251.70
  5108.3 2262.05  5127.2 2264.00  5150.0 2264.64  5199.6 2267.80  5204.8 2267.42
  5212.4 2268.47  5233.2 2268.94  5238.5 2269.79  5328.3 2274.24  5343.8 2274.74
#Mann=6,-1,0
  4689.9    0.07       0  4705.9   0.035       0  4743.0    0.07       0
  4968.4    0.07       0  4972.4    0.07       0  5328.3   0.035       0
Bank Sta=4968.4,4972.4
Exp/Cntr=0.3,0.1

Type RM Length L Ch R = 1,1741,30,30,30
BEGIN DESCRIPTION:
UCFB HW Trib 19 3.8
END DESCRIPTION:
XS GIS Cut Line= 2
      1285426.45      6945903.88      1286155.57      6945988.37
#Sta/Elev= 30
  4675.6 2268.21  4702.4 2267.74  4744.6 2267.29  4780.2 2268.22  4885.5 2268.28
  4915.7 2267.44  4929.7 2268.59  4966.1 2268.59  5013.4 2267.46  5018.4 2268.75
  5036.5 2269.00  5097.8 2267.06  5102.2 2266.60  5107.2 2268.64  5137.2 2268.59
  5185.9 2266.69  5190.9 2268.48  5227.8 2267.21  5248.0 2264.75  5272.6 2263.53
  5272.8 2263.03  5276.6 2263.53  5338.6 2264.28  5348.6 2266.03  5358.3 2269.18
  5363.3 2269.09  5366.9 2269.91  5388.9 2269.89  5399.0 2271.26  5409.6 2271.21
#Mann=7,-1,0
  4675.6    0.07       0  4702.4   0.035       0  4780.2    0.07       0
  5097.8   0.035       0  5272.6    0.07       0  5276.6   0.035       0
  5366.9    0.07       0
Bank Sta=5272.6,5276.6
Exp/Cntr=0.3,0.1

Type RM Length L Ch R = 1,1711,313,313,313
BEGIN DESCRIPTION:
UCFB HW Trib 19 3.5
END DESCRIPTION:
XS GIS Cut Line= 2
      1285430.74      6945932.09      1286151.66      6946009.88
#Sta/Elev= 30
  4700.3 2270.57  4709.2 2271.36  4714.3 2270.62  4775.0 2267.58  4795.1 2268.09
  4810.9 2267.12  4835.3 2262.59  4845.4 2261.61  4865.5 2261.76  4892.9 2264.74
  4896.0 2259.13  4896.2 2258.63  4900.0 2259.13  4915.8 2260.38  4966.1 2267.21
  4984.8 2268.33  4989.8 2263.44  4996.3 2264.99  5036.5 2267.63  5076.7 2268.23
  5081.7 2262.64  5106.9 2268.04  5152.8 2268.52  5217.5 2268.12  5277.9 2264.13
  5348.3 2263.72  5368.4 2262.67  5378.5 2268.94  5391.9 2269.83  5425.4 2271.03
#Mann=7,-1,0
  4700.3    0.07       0  4714.3   0.035       0  4810.9    0.07       0
  4896.0    0.07       0  4900.0    0.07       0  5152.8   0.035       0
  5391.9    0.07       0
Bank Sta=4896,4900
Exp/Cntr=0.3,0.1

Type RM Length L Ch R = 1,1398,454,454,454
BEGIN DESCRIPTION:
UCFB HW Trib 19 3.0
END DESCRIPTION:
XS GIS Cut Line= 3
      1285516.06      6946307.66      1285805.00      6946238.00
      1286125.86      6946160.09
#Sta/Elev= 30
  4698.6 2271.79  4748.9 2270.28  4893.6 2258.41  4923.8 2256.87  4944.4 2253.20
  4954.7 2249.62  4971.2 2246.51  4977.4 2242.31  4985.5 2239.48  5014.1 2238.37
  5019.3 2239.53  5035.0 2237.65  5035.2 2237.15  5039.0 2237.65  5061.0 2244.90
  5067.9 2248.90  5078.1 2251.16  5088.4 2251.70  5097.7 2249.11  5102.8 2249.93
  5109.0 2248.86  5135.3 2250.13  5170.8 2251.00  5201.6 2256.24  5248.3 2258.34
  5266.7 2259.49  5294.2 2262.14  5304.5 2262.17  5316.8 2263.93  5326.0 2263.48
#Mann=7,-1,0
  4698.6   0.035       0  4971.2    0.07       0  5035.0    0.07       0
  5039.0    0.07       0  5135.3   0.035       0  5248.3    0.07       0
  5266.7   0.035       0
Bank Sta=5035,5039
Exp/Cntr=0.3,0.1

Type RM Length L Ch R = 1,944,442,442,442
BEGIN DESCRIPTION:
UCFB HW Trib 19 2.0
END DESCRIPTION:
XS GIS Cut Line= 3
      1285600.71      6946496.46      1286005.00      6946588.00
      1286364.56      6946607.14
#Sta/Elev= 30
  4585.4 2261.36  4615.2 2260.00  4641.1 2259.68  4671.8 2257.67  4733.3 2256.64
  4823.4 2252.27  4876.9 2248.80  4889.5 2248.57  4927.5 2242.35  4932.6 2240.71
  4948.7 2238.95  4969.2 2235.55  4975.8 2233.74  4987.7 2232.69  4987.9 2232.19
  4991.7 2232.69  4997.4 2234.17  5002.4 2234.17  5030.0 2239.31  5040.0 2240.33
  5070.0 2247.56  5089.5 2251.34  5094.5 2250.95  5100.1 2251.94  5130.1 2254.07
  5209.3 2258.46  5260.3 2261.06  5278.7 2262.90  5283.7 2262.52  5360.0 2267.72
#Mann=5,-1,0
  4585.4   0.035       0  4823.4    0.07       0  4987.7    0.07       0
  4991.7    0.07       0  5209.3   0.035       0
Bank Sta=4987.7,4991.7
Exp/Cntr=0.3,0.1

Type RM Length L Ch R = 1,502,0,0,0
BEGIN DESCRIPTION:
UCFB HW Trib 19 1.0
END DESCRIPTION:
XS GIS Cut Line= 3
      1285717.89      6946752.54      1286055.00      6946988.00
      1286380.04      6946963.00
#Sta/Elev= 30
  4592.7 2249.68  4609.2 2249.98  4630.1 2248.88  4683.9 2247.79  4788.0 2246.59
  4838.6 2244.45  4853.4 2245.20  4889.2 2242.44  4939.8 2240.94  4945.9 2239.82
  4967.3 2232.95  4975.6 2231.59  4981.7 2234.74  4984.5 2233.32  4990.4 2230.32
  5011.9 2228.36  5012.2 2227.86  5015.7 2227.86  5015.9 2228.36  5024.0 2228.94
  5054.0 2234.84  5094.2 2237.69  5134.3 2245.00  5144.3 2245.47  5194.5 2250.63
  5214.5 2251.62  5254.6 2257.02  5274.7 2259.07  5324.8 2259.49  5329.9 2260.05
#Mann=5,-1,0
  4592.7   0.035       0  4683.9    0.07       0  4984.5   0.035       0
  5011.9   0.035       0  5015.9   0.035       0
Bank Sta=5011.9,5015.9
Exp/Cntr=0.3,0.1

Chan Stop Cuts=-1