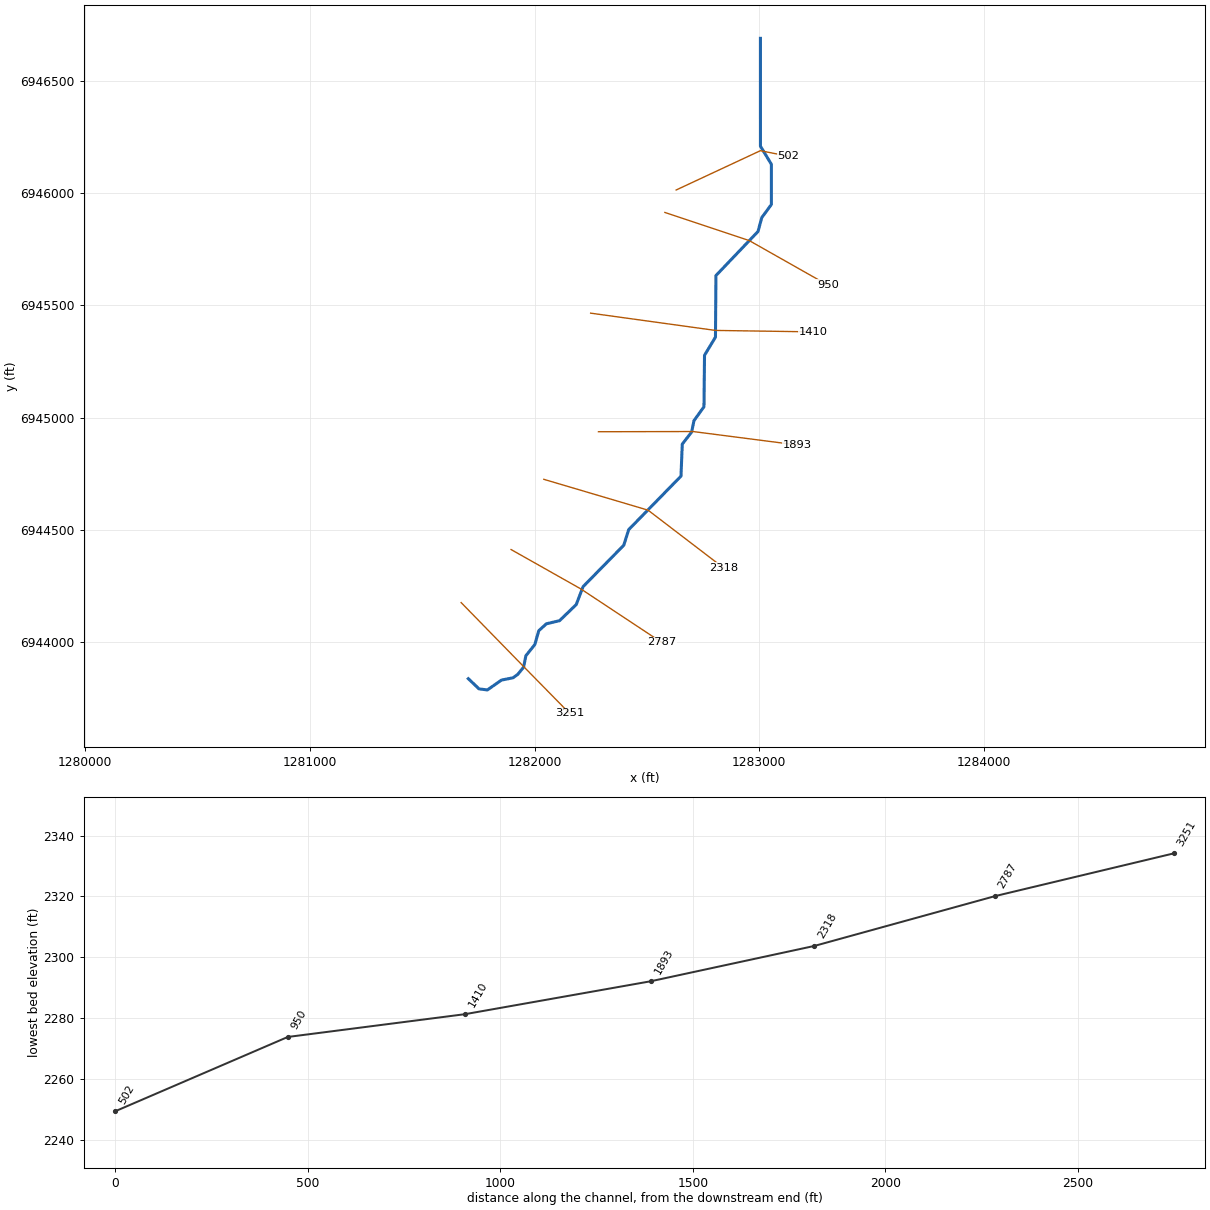
--- UCFB HW Trib 20.prj (project) ---

Proj Title=UCFB HW Trib 20 Base Level Engineering
Current Plan=p01
Default Exp/Contr=0.3,0.1
English Units
Geom File=g01
Flow File=f01
Plan File=p01
BEGIN DESCRIPTION:
UCFB HW Trib 20
END DESCRIPTION:

--- UCFB HW Trib 20.p01 (plan) ---

Plan Title=Multiple Run
Short Identifier=Multiple
Geom File=g01
Flow File=f01
Subcritical Flow
K Sum by GR= 0
Std Step Tol= 0.01
Critical Tol= 0.01
Num of Std Step Trials= 20
Max Error Tol= 0.3
Flow Tol Ratio= 0.001
Split Flow NTrial= 30
Split Flow Tol= 0.02
Split Flow Ratio= 0.02
Log Output Level= 0
Friction Slope Method= 1
Unsteady Friction Slope Method= 2
Unsteady Bridges Friction Slope Method= 1
Parabolic Critical Depth
Global Vel Dist=  1 , 1 , 1
Global Log Level= 0
CheckData=True
Encroach Param= -1, 0, 0, 0
BEGIN DESCRIPTION:
Multiple Run
END DESCRIPTION:

--- UCFB HW Trib 20.f01 (steady flow) ---

Flow Title=Multiple
Number of Profiles=7
Profile Names=10-year,25-year,50-year,1pct_min,100-year,1pct_plu,500-year
River Rch & RM= UCFB HW Trib 20,Reach-1,3251
     100     134     161      97     194     386     283
Boundary for River Rch & Prof#=UCFB HW Trib 20,Reach-1,1
Up Type=0
Dn Type=3
Dn Slope=0.005
Boundary for River Rch & Prof#=UCFB HW Trib 20,Reach-1,2
Up Type=0
Dn Type=3
Dn Slope=0.005
Boundary for River Rch & Prof#=UCFB HW Trib 20,Reach-1,3
Up Type=0
Dn Type=3
Dn Slope=0.005
Boundary for River Rch & Prof#=UCFB HW Trib 20,Reach-1,4
Up Type=0
Dn Type=3
Dn Slope=0.005
Boundary for River Rch & Prof#=UCFB HW Trib 20,Reach-1,5
Up Type=0
Dn Type=3
Dn Slope=0.005
Boundary for River Rch & Prof#=UCFB HW Trib 20,Reach-1,6
Up Type=0
Dn Type=3
Dn Slope=0.005
Boundary for River Rch & Prof#=UCFB HW Trib 20,Reach-1,7
Up Type=0
Dn Type=3
Dn Slope=0.005

--- UCFB HW Trib 20.g01 (geometry) ---

Geom Title=Existing Conditions

River Reach=UCFB HW Trib 20,Reach-1
Reach XY= 30
      1281705.00      6943838.00      1281752.64      6943792.60
      1281789.68      6943787.95      1281852.83      6943831.83
      1281903.58      6943841.85      1281925.48      6943857.62
      1281951.14      6943889.42      1281961.11      6943940.16
      1282000.80      6943989.76      1282018.47      6944051.57
      1282052.46      6944082.25      1282111.05      6944096.16
      1282185.23      6944167.87      1282215.78      6944247.68
      1282396.84      6944431.95      1282418.63      6944501.21
      1282651.46      6944739.47      1282657.25      6944882.07
      1282698.88      6944935.82      1282709.19      6944986.26
      1282753.80      6945048.50      1282756.22      6945277.50
      1282804.93      6945358.03      1282807.06      6945632.15
      1282994.24      6945828.32      1283011.14      6945890.17
      1283053.80      6945948.50      1283053.78      6946127.49
      1283005.07      6946208.03      1283005.00      6946688.00

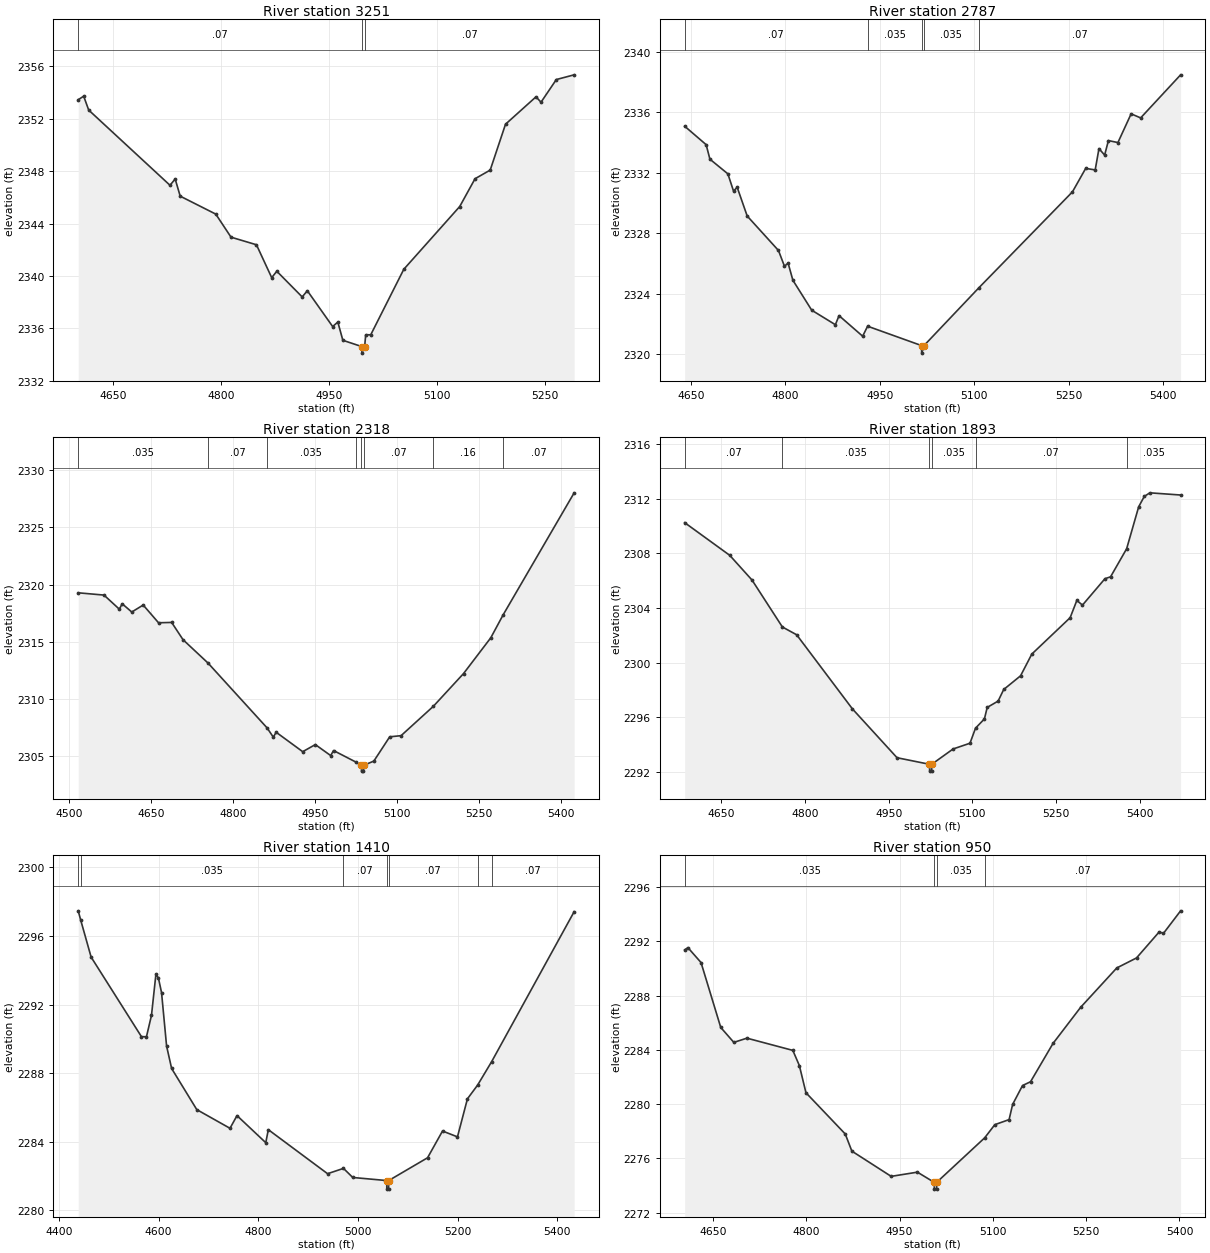
Type RM Length L Ch R = 1,3251,464,464,464
BEGIN DESCRIPTION:
UCFB HW Trib 20 7.0
END DESCRIPTION:
XS GIS Cut Line= 3
      1281673.03      6944176.69      1281955.00      6943888.00
      1282155.70      6943683.60
#Sta/Elev= 30
  4601.1 2353.46  4608.7 2353.73  4615.7 2352.67  4728.8 2346.93  4736.0 2347.41
  4743.0 2346.10  4792.5 2344.73  4813.7 2342.97  4849.1 2342.39  4870.3 2339.88
  4877.4 2340.37  4912.7 2338.41  4919.9 2338.88  4955.1 2336.15  4962.3 2336.49
  4969.3 2335.10  4995.6 2334.62  4995.8 2334.12  4999.6 2334.62  5001.1 2335.52
  5008.1 2335.52  5054.1 2340.52  5131.9 2345.31  5153.2 2347.43  5174.3 2348.09
  5195.6 2351.59  5238.0 2353.68  5245.0 2353.27  5266.3 2355.00  5291.1 2355.36
#Mann=3,-1,0
  4601.1    0.07       0  4995.6    0.07       0  4999.6    0.07       0
Bank Sta=4995.6,4999.6
Exp/Cntr=0.3,0.1

Type RM Length L Ch R = 1,2787,469,469,469
BEGIN DESCRIPTION:
UCFB HW Trib 20 6.0
END DESCRIPTION:
XS GIS Cut Line= 3
      1281895.27      6944412.79      1282205.00      6944238.00
      1282565.43      6943999.58
#Sta/Elev= 30
  4639.9 2335.08  4674.0 2333.86  4680.0 2332.90  4708.5 2331.93  4717.5 2330.79
  4723.3 2331.04  4739.2 2329.14  4788.9 2326.86  4798.4 2325.82  4804.2 2326.02
  4811.8 2324.89  4841.7 2322.91  4879.3 2321.95  4885.1 2322.55  4922.6 2321.19
  4930.5 2321.85  5016.1 2320.57  5016.4 2320.07  5020.1 2320.57  5106.7 2324.37
  5255.9 2330.74  5276.9 2332.29  5292.0 2332.19  5298.0 2333.60  5307.0 2333.17
  5313.0 2334.13  5328.1 2334.00  5349.1 2335.90  5364.2 2335.63  5427.7 2338.48
#Mann=5,-1,0
  4639.9    0.07       0  4930.5   0.035       0  5016.1   0.035       0
  5020.1   0.035       0  5106.7    0.07       0
Bank Sta=5016.1,5020.1
Exp/Cntr=0.3,0.1

Type RM Length L Ch R = 1,2318,425,425,425
BEGIN DESCRIPTION:
UCFB HW Trib 20 5.0
END DESCRIPTION:
XS GIS Cut Line= 3
      1282041.07      6944725.31      1282505.00      6944588.00
      1282841.58      6944330.68
#Sta/Elev= 30
  4516.2 2319.28  4563.4 2319.08  4591.4 2317.85  4596.7 2318.32  4614.2 2317.60
  4635.1 2318.21  4663.2 2316.66  4687.2 2316.69  4708.0 2315.18  4753.7 2313.14
  4861.8 2307.47  4873.2 2306.66  4878.4 2307.09  4927.0 2305.39  4950.1 2306.01
  4978.2 2305.05  4983.4 2305.49  5023.6 2304.50  5034.3 2304.19  5034.6 2303.69
  5038.1 2303.69  5038.3 2304.19  5057.2 2304.57  5086.2 2306.69  5107.0 2306.79
  5166.1 2309.36  5221.3 2312.22  5271.2 2315.35  5293.6 2317.34  5423.7 2328.02
#Mann=8,-1,0
  4516.2   0.035       0  4753.7    0.07       0  4861.8   0.035       0
  5023.6    0.07       0  5034.3   0.035       0  5038.3    0.07       0
  5166.1    0.16       0  5293.6    0.07       0
Bank Sta=5034.3,5038.3
Exp/Cntr=0.3,0.1

Type RM Length L Ch R = 1,1893,483,483,483
BEGIN DESCRIPTION:
UCFB HW Trib 20 4.0
END DESCRIPTION:
XS GIS Cut Line= 3
      1282284.15      6944937.11      1282705.00      6944938.00
      1283169.60      6944878.07
#Sta/Elev= 30
  4584.2 2310.24  4665.0 2307.85  4705.0 2306.04  4759.4 2302.61  4785.0 2302.04
  4885.0 2296.62  4965.0 2293.05  5023.2 2292.57  5023.5 2292.07  5027.0 2292.07
  5027.2 2292.57  5065.5 2293.69  5095.8 2294.11  5105.7 2295.21  5121.7 2295.89
  5126.7 2296.73  5146.2 2297.19  5156.3 2298.04  5186.5 2299.04  5206.7 2300.63
  5275.4 2303.29  5287.4 2304.55  5297.5 2304.21  5337.8 2306.14  5347.9 2306.28
  5376.7 2308.33  5398.3 2311.40  5408.4 2312.16  5418.4 2312.42  5473.5 2312.26
#Mann=6,-1,0
  4584.2    0.07       0  4759.4   0.035       0  5023.2   0.035       0
  5027.2   0.035       0  5105.7    0.07       0  5376.7   0.035       0
Bank Sta=5023.2,5027.2
Exp/Cntr=0.3,0.1

Type RM Length L Ch R = 1,1410,460,460,460
BEGIN DESCRIPTION:
UCFB HW Trib 20 3.0
END DESCRIPTION:
XS GIS Cut Line= 3
      1282249.38      6945464.89      1282805.00      6945388.00
      1283239.04      6945381.55
#Sta/Elev= 30
  4438.7 2297.47  4443.8 2296.92  4464.6 2294.77  4565.5 2290.13  4575.6 2290.12
  4585.7 2291.37  4594.6 2293.77  4599.6 2293.55  4605.9 2292.70  4616.0 2289.58
  4626.1 2288.27  4676.6 2285.87  4743.2 2284.78  4757.3 2285.52  4815.0 2283.94
  4820.1 2284.70  4939.0 2282.13  4970.9 2282.44  4989.5 2281.91  5057.6 2281.73
  5057.9 2281.23  5061.4 2281.23  5061.6 2281.73  5139.6 2283.06  5169.6 2284.62
  5199.6 2284.28  5219.6 2286.50  5240.0 2287.30  5268.2 2288.67  5433.7 2297.42
#Mann=7,-1,0
  4438.7    0.07       0  4443.8   0.035       0  4970.9    0.07       0
  5057.6    0.07       0  5061.6    0.07       0  5240.0   0.035       0
  5268.2    0.07       0
Bank Sta=5057.6,5061.6
Exp/Cntr=0.3,0.1

Type RM Length L Ch R = 1,950,448,448,448
BEGIN DESCRIPTION:
UCFB HW Trib 20 2.0
END DESCRIPTION:
XS GIS Cut Line= 3
      1282580.02      6945912.99      1282955.00      6945788.00
      1283304.96      6945589.89
#Sta/Elev= 30
  4604.5 2291.36  4609.7 2291.53  4630.8 2290.43  4662.5 2285.65  4683.5 2284.55
  4704.6 2284.86  4778.4 2283.96  4788.9 2282.84  4799.5 2280.84  4862.7 2277.80
  4873.3 2276.54  4936.5 2274.68  4978.7 2274.99  5005.7 2274.24  5006.0 2273.74
  5009.5 2273.74  5009.7 2274.24  5086.9 2277.52  5103.2 2278.49  5126.1 2278.86
  5131.8 2279.98  5147.7 2281.37  5160.6 2281.65  5196.7 2284.47  5241.1 2287.13
  5299.2 2290.03  5331.0 2290.77  5367.5 2292.69  5374.3 2292.58  5401.9 2294.24
#Mann=4,-1,0
  4604.5   0.035       0  5005.7   0.035       0  5009.7   0.035       0
  5086.9    0.07       0
Bank Sta=5005.7,5009.7
Exp/Cntr=0.3,0.1

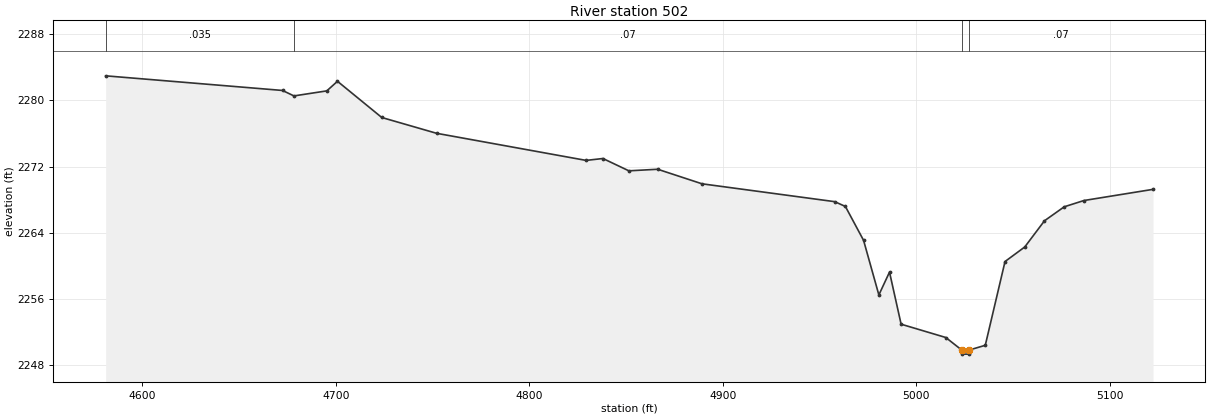
Type RM Length L Ch R = 1,502,0,0,0
BEGIN DESCRIPTION:
UCFB HW Trib 20 1.0
END DESCRIPTION:
XS GIS Cut Line= 3
      1282630.01      6946013.00      1283005.00      6946188.00
      1283130.01      6946163.00
#Sta/Elev= 30
  4581.0 2282.97  4672.4 2281.20  4678.3 2280.54  4695.3 2281.15  4700.8 2282.31
  4723.7 2277.93  4752.0 2276.02  4829.3 2272.74  4838.0 2272.97  4851.4 2271.48
  4866.3 2271.67  4889.2 2269.91  4957.8 2267.75  4963.3 2267.17  4972.7 2263.07
  4980.6 2256.47  4986.1 2259.23  4992.1 2252.93  5015.2 2251.32  5023.4 2249.81
  5023.7 2249.31  5027.2 2249.31  5027.4 2249.81  5035.6 2250.38  5045.8 2260.51
  5056.0 2262.27  5066.2 2265.44  5076.4 2267.13  5086.6 2267.89  5122.3 2269.24
#Mann=4,-1,0
  4581.0   0.035       0  4678.3    0.07       0  5023.4    0.07       0
  5027.4    0.07       0
Bank Sta=5023.4,5027.4
Exp/Cntr=0.3,0.1

Chan Stop Cuts=-1