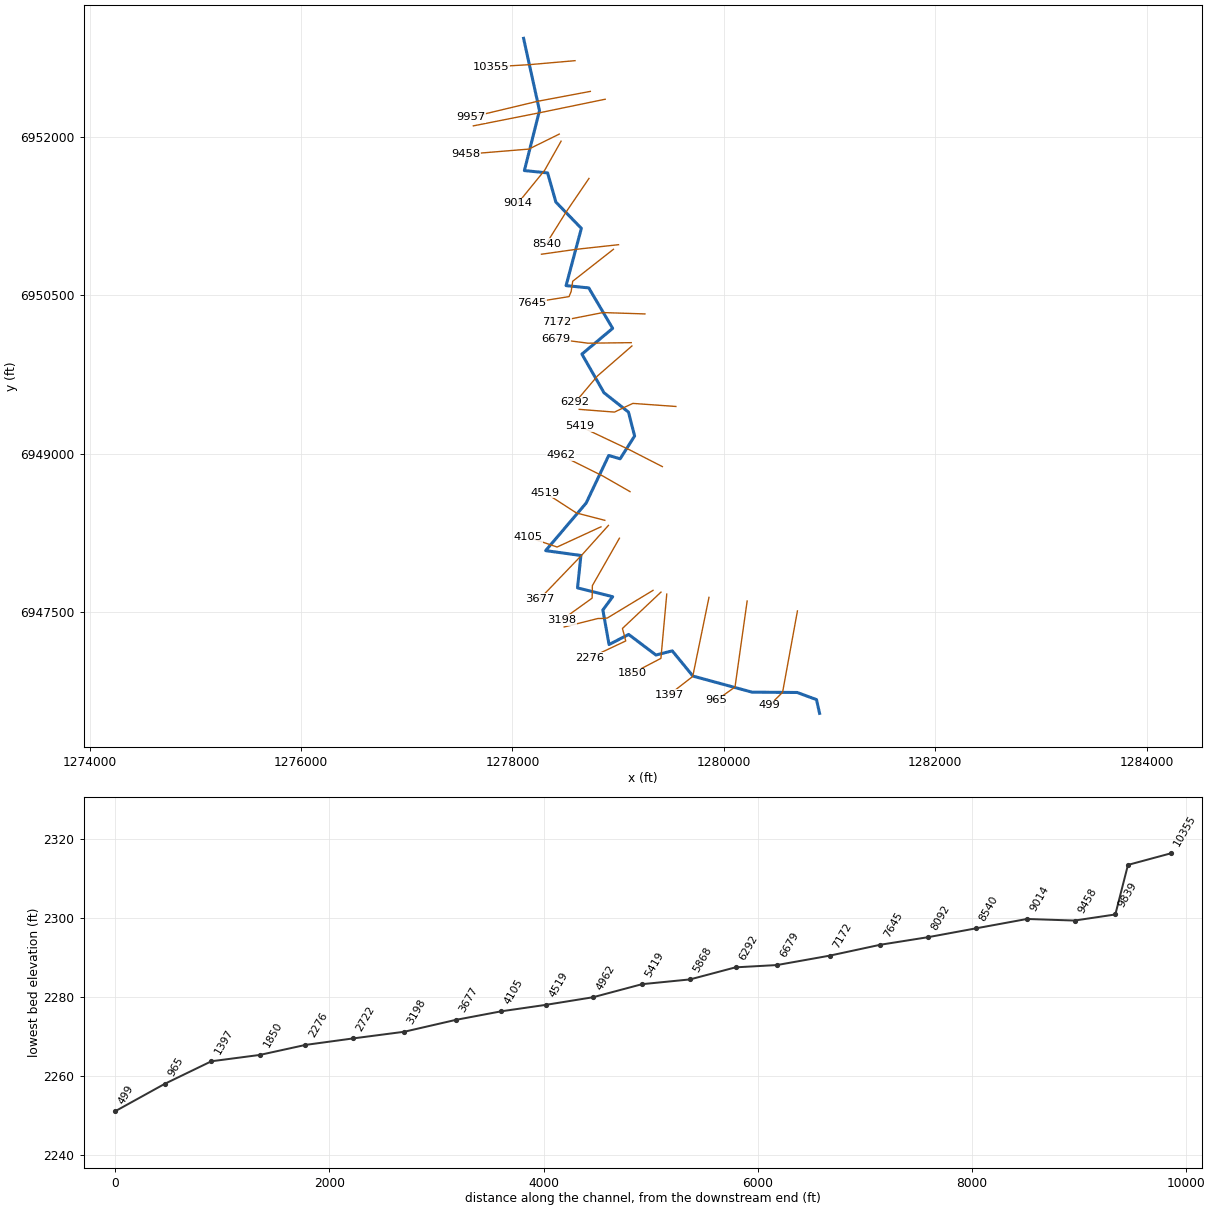
--- UCFB HW Trib 21.prj (project) ---

Proj Title=UCFB HW Trib 21 Base Level Engineering
Current Plan=p01
Default Exp/Contr=0.3,0.1
English Units
Geom File=g01
Flow File=f01
Plan File=p01
BEGIN DESCRIPTION:
UCFB HW Trib 21
END DESCRIPTION:

--- UCFB HW Trib 21.p01 (plan) ---

Plan Title=Multiple Run
Short Identifier=Multiple
Geom File=g01
Flow File=f01
Subcritical Flow
K Sum by GR= 0
Std Step Tol= 0.01
Critical Tol= 0.01
Num of Std Step Trials= 20
Max Error Tol= 0.3
Flow Tol Ratio= 0.001
Split Flow NTrial= 30
Split Flow Tol= 0.02
Split Flow Ratio= 0.02
Log Output Level= 0
Friction Slope Method= 1
Unsteady Friction Slope Method= 2
Unsteady Bridges Friction Slope Method= 1
Parabolic Critical Depth
Global Vel Dist=  1 , 1 , 1
Global Log Level= 0
CheckData=True
Encroach Param= -1, 0, 0, 0
BEGIN DESCRIPTION:
Multiple Run
END DESCRIPTION:

--- UCFB HW Trib 21.f01 (steady flow) ---

Flow Title=Multiple
Number of Profiles=7
Profile Names=10-year,25-year,50-year,1pct_min,100-year,1pct_plu,500-year
River Rch & RM= UCFB HW Trib 21,Reach-1,10355
     320     460     578     362     722    1440    1139
River Rch & RM= UCFB HW Trib 21,Reach-1,9014
     472     690     879     556    1110    2215    1794
River Rch & RM= UCFB HW Trib 21,Reach-1,7172
     543     796    1015     642    1282    2557    2073
Boundary for River Rch & Prof#=UCFB HW Trib 21,Reach-1,1
Up Type=0
Dn Type=3
Dn Slope=0.005
Boundary for River Rch & Prof#=UCFB HW Trib 21,Reach-1,2
Up Type=0
Dn Type=3
Dn Slope=0.005
Boundary for River Rch & Prof#=UCFB HW Trib 21,Reach-1,3
Up Type=0
Dn Type=3
Dn Slope=0.005
Boundary for River Rch & Prof#=UCFB HW Trib 21,Reach-1,4
Up Type=0
Dn Type=3
Dn Slope=0.005
Boundary for River Rch & Prof#=UCFB HW Trib 21,Reach-1,5
Up Type=0
Dn Type=3
Dn Slope=0.005
Boundary for River Rch & Prof#=UCFB HW Trib 21,Reach-1,6
Up Type=0
Dn Type=3
Dn Slope=0.005
Boundary for River Rch & Prof#=UCFB HW Trib 21,Reach-1,7
Up Type=0
Dn Type=3
Dn Slope=0.005

--- UCFB HW Trib 21.g01 (geometry) ---

Geom Title=Existing Conditions

River Reach=UCFB HW Trib 21,Reach-1
Reach XY= 30
      1278105.00      6952938.00      1278255.48      6952253.16
      1278112.69      6951684.26      1278332.28      6951662.15
      1278410.52      6951385.56      1278651.66      6951136.28
      1278506.98      6950593.62      1278721.71      6950571.80
      1278947.52      6950187.97      1278656.76      6949944.13
      1278865.51      6949578.19      1279097.19      6949394.21
      1279155.29      6949167.82      1279018.39      6948951.54
      1278910.59      6948983.21      1278696.86      6948531.94
      1278313.82      6948081.00      1278647.15      6948035.07
      1278615.32      6947727.82      1278947.80      6947644.08
      1278854.93      6947518.12      1278913.47      6947190.58
      1279098.95      6947286.42      1279356.72      6947091.34
      1279511.34      6947130.63      1279706.52      6946891.74
      1280265.50      6946739.22      1280693.03      6946736.03
      1280875.65      6946668.63      1280905.00      6946538.00

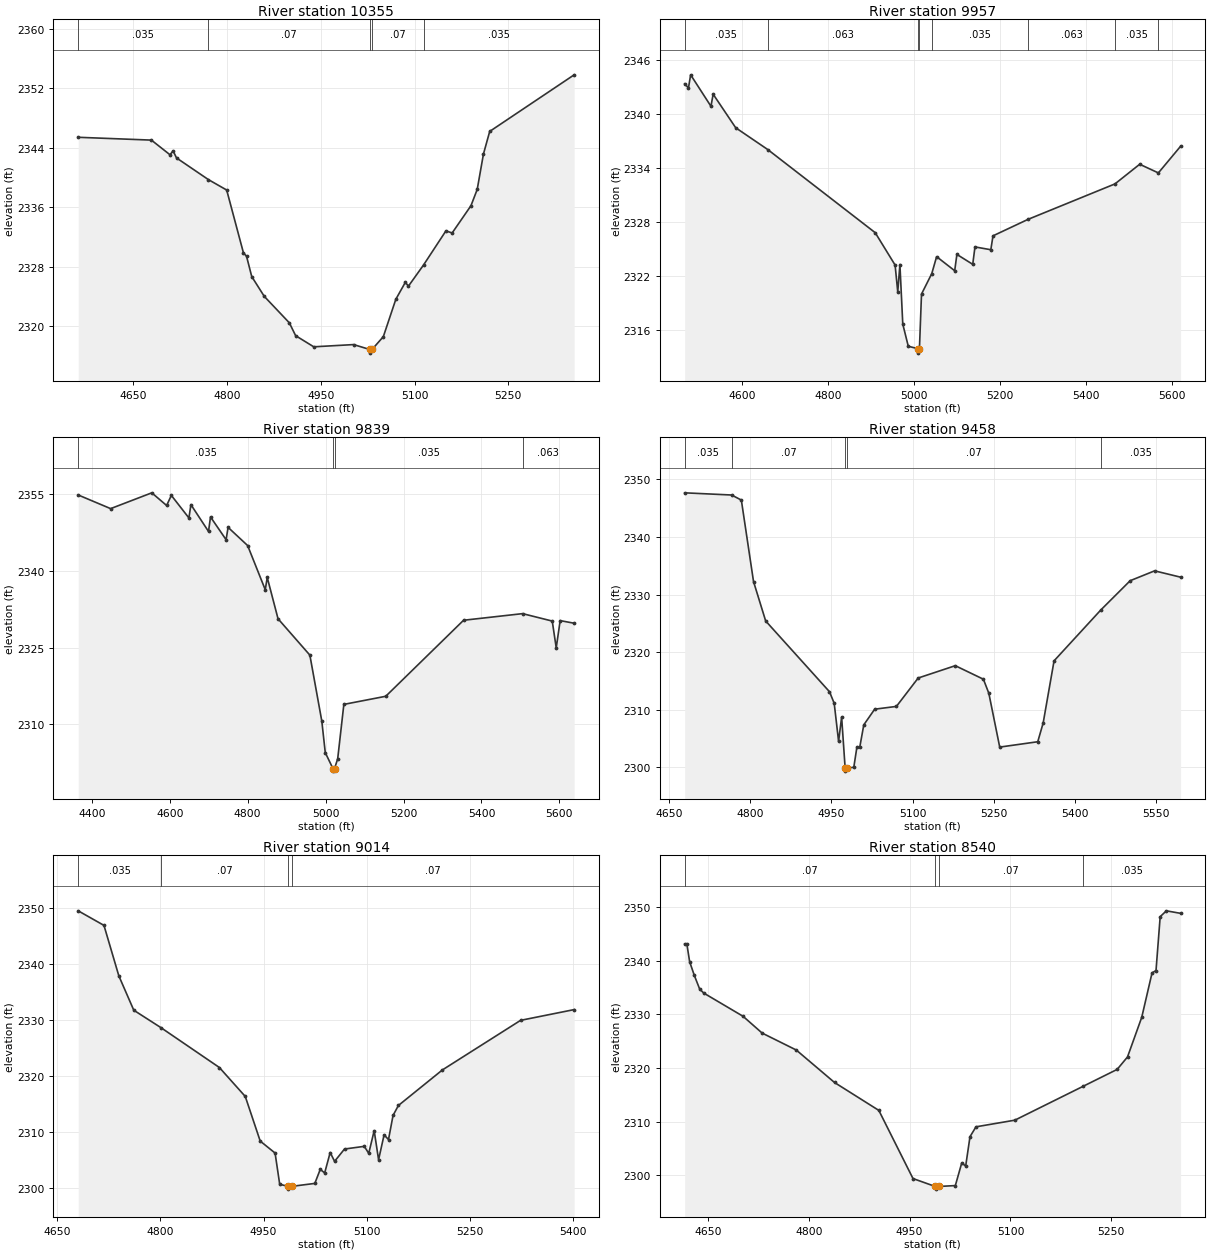
Type RM Length L Ch R = 1,10355,398,398,398
BEGIN DESCRIPTION:
UCFB HW Trib 21 23.0
END DESCRIPTION:
XS GIS Cut Line= 3
      1278591.76      6952726.19      1278155.00      6952688.00
      1277800.04      6952667.16
#Sta/Elev= 30
  4561.5 2345.42  4678.7 2345.04  4708.4 2343.07  4713.4 2343.59  4718.9 2342.64
  4770.0 2339.72  4799.2 2338.32  4826.0 2329.87  4831.0 2329.40  4839.3 2326.67
  4859.4 2324.00  4899.5 2320.44  4909.6 2318.71  4938.6 2317.21  5002.4 2317.51
  5027.9 2316.86  5028.2 2316.36  5032.0 2316.86  5050.0 2318.58  5070.0 2323.61
  5085.2 2325.89  5090.2 2325.38  5114.4 2328.23  5150.2 2332.82  5160.2 2332.54
  5190.3 2336.21  5200.3 2338.40  5210.3 2343.17  5220.3 2346.21  5355.5 2353.83
#Mann=5,-1,0
  4561.5   0.035       0  4770.0    0.07       0  5027.9    0.07       0
  5032.0    0.07       0  5114.4   0.035       0
Bank Sta=5027.9,5032
Exp/Cntr=0.3,0.1

Type RM Length L Ch R = 1,9957,118,118,118
BEGIN DESCRIPTION:
UCFB HW Trib 21 22.5
END DESCRIPTION:
XS GIS Cut Line= 3
      1278736.56      6952435.01      1278234.94      6952340.55
      1277608.15      6952190.65
#Sta/Elev= 30
  4465.6 2343.32  4474.4 2342.87  4479.5 2344.32  4526.8 2340.83  4531.9 2342.17
  4584.4 2338.45  4659.1 2336.03  4909.3 2326.81  4955.6 2323.22  4961.8 2320.24
  4966.8 2323.28  4973.5 2316.67  4986.3 2314.21  5008.2 2313.95  5008.4 2313.45
  5012.3 2313.95  5017.1 2320.00  5041.0 2322.27  5052.3 2324.15  5094.4 2322.59
  5099.5 2324.40  5136.4 2323.30  5141.6 2325.23  5178.5 2324.92  5183.6 2326.46
  5265.3 2328.29  5467.6 2332.22  5525.2 2334.40  5568.7 2333.44  5620.5 2336.40
#Mann=8,-1,0
  4465.6   0.035       0  4659.1   0.063       0  5008.2   0.063       0
  5012.3   0.063       0  5041.0   0.035       0  5265.3   0.063       0
  5467.6   0.035       0  5568.7   0.063       0
Bank Sta=5008.2,5012.3
Exp/Cntr=0.3,0.1

Type RM Length L Ch R = 1,9839,381,381,381
BEGIN DESCRIPTION:
UCFB HW Trib 21 22.0
END DESCRIPTION:
XS GIS Cut Line= 3
      1278877.20      6952360.73      1278253.46      6952231.81
      1277629.83      6952108.13
#Sta/Elev= 30
  4365.1 2354.74  4448.3 2352.08  4553.9 2355.16  4592.0 2352.69  4604.1 2354.66
  4649.2 2350.26  4654.3 2352.86  4699.5 2347.63  4704.6 2350.46  4744.6 2346.02
  4749.7 2348.43  4799.9 2344.88  4845.1 2336.27  4850.2 2338.66  4877.9 2330.61
  4959.6 2323.52  4990.2 2310.67  4999.1 2304.52  5018.8 2301.41  5019.0 2300.91
  5022.9 2301.41  5031.0 2303.32  5046.8 2313.92  5154.3 2315.50  5354.0 2330.32
  5505.5 2331.61  5581.6 2330.16  5591.8 2324.94  5601.9 2330.25  5637.8 2329.74
#Mann=4,-1,0
  4365.1   0.035       0  5018.8   0.035       0  5022.9   0.035       0
  5505.5   0.063       0
Bank Sta=5018.8,5022.9
Exp/Cntr=0.3,0.1

Type RM Length L Ch R = 1,9458,444,444,444
BEGIN DESCRIPTION:
UCFB HW Trib 21 21.0
END DESCRIPTION:
XS GIS Cut Line= 3
      1278442.42      6952030.01      1278155.00      6951888.00
      1277562.21      6951839.04
#Sta/Elev= 30
  4679.4 2347.67  4766.1 2347.29  4784.0 2346.41  4806.5 2332.26  4828.9 2325.43
  4946.7 2313.15  4955.4 2311.14  4963.5 2304.53  4969.1 2308.75  4975.6 2299.87
  4975.9 2299.37  4979.7 2299.87  4991.6 2300.05  4997.2 2303.49  5002.5 2303.49
  5010.0 2307.40  5030.1 2310.12  5070.2 2310.60  5110.4 2315.53  5178.9 2317.67
  5230.8 2315.32  5240.8 2312.88  5260.9 2303.54  5331.1 2304.47  5341.1 2307.73
  5361.2 2318.51  5447.4 2327.33  5501.7 2332.42  5546.8 2334.13  5594.8 2333.03
#Mann=5,-1,0
  4679.4   0.035       0  4766.1    0.07       0  4975.6    0.07       0
  4979.7    0.07       0  5447.4   0.035       0
Bank Sta=4975.6,4979.7
Exp/Cntr=0.3,0.1

Type RM Length L Ch R = 1,9014,474,474,474
BEGIN DESCRIPTION:
UCFB HW Trib 21 20.0
END DESCRIPTION:
XS GIS Cut Line= 3
      1278459.78      6951962.99      1278305.00      6951688.00
      1278050.07      6951373.77
#Sta/Elev= 30
  4680.9 2349.47  4718.3 2346.87  4739.9 2337.85  4761.6 2331.72  4801.4 2328.58
  4885.9 2321.49  4923.5 2316.32  4945.2 2308.35  4966.8 2306.21  4973.5 2300.64
  4985.5 2300.27  4986.0 2299.77  4991.4 2300.27  5024.5 2300.79  5032.4 2303.30
  5038.8 2302.66  5046.8 2306.31  5053.2 2304.73  5067.6 2306.93  5096.3 2307.41
  5102.8 2306.16  5110.7 2310.21  5117.1 2305.02  5125.1 2309.47  5131.5 2308.62
  5138.1 2312.93  5145.9 2314.71  5209.8 2321.06  5323.3 2329.91  5401.1 2331.83
#Mann=4,-1,0
  4680.9   0.035       0  4801.4    0.07       0  4985.5    0.07       0
  4991.4    0.07       0
Bank Sta=4985.5,4991.4
Exp/Cntr=0.3,0.1

Type RM Length L Ch R = 1,8540,448,448,448
BEGIN DESCRIPTION:
UCFB HW Trib 21 19.0
END DESCRIPTION:
XS GIS Cut Line= 3
      1278723.65      6951609.83      1278505.00      6951288.00
      1278320.49      6950992.21
#Sta/Elev= 30
  4615.4 2343.12  4618.6 2343.12  4622.8 2339.78  4629.7 2337.25  4637.7 2334.69
  4643.8 2333.94  4702.2 2329.62  4730.6 2326.49  4781.4 2323.33  4838.3 2317.28
  4904.2 2312.08  4955.0 2299.38  4988.0 2297.91  4988.5 2297.41  4993.9 2297.91
  5018.0 2298.07  5027.5 2302.28  5033.4 2301.72  5039.8 2307.18  5048.7 2309.02
  5106.5 2310.26  5208.4 2316.59  5258.7 2319.72  5274.1 2322.04  5295.3 2329.44
  5310.6 2337.71  5316.5 2338.14  5322.7 2348.18  5331.9 2349.27  5353.1 2348.80
#Mann=4,-1,0
  4615.4    0.07       0  4988.0    0.07       0  4993.9    0.07       0
  5208.4   0.035       0
Bank Sta=4988,4993.9
Exp/Cntr=0.3,0.1

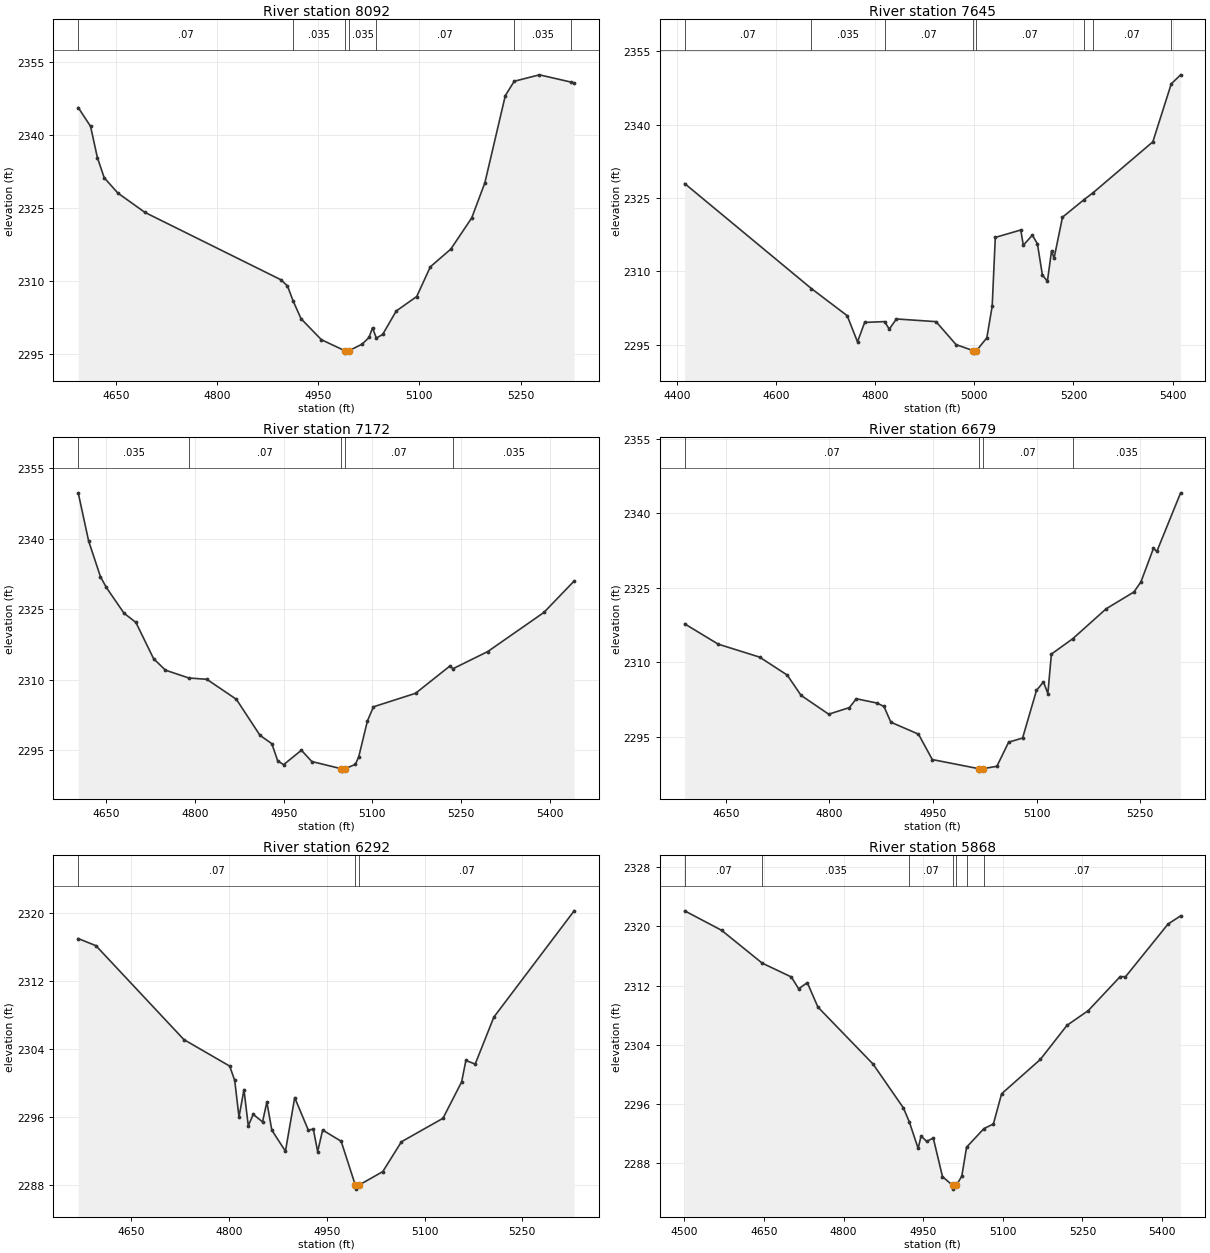
Type RM Length L Ch R = 1,8092,447,447,447
BEGIN DESCRIPTION:
UCFB HW Trib 21 18.0
END DESCRIPTION:
XS GIS Cut Line= 3
      1279003.23      6950981.40      1278605.00      6950938.00
      1278273.99      6950891.12
#Sta/Elev= 30
  4594.4 2345.56  4612.7 2341.70  4622.8 2335.29  4632.9 2331.16  4653.0 2328.03
  4693.2 2324.05  4894.4 2310.25  4904.5 2308.96  4912.7 2305.93  4924.6 2302.23
  4954.7 2297.93  4989.4 2295.67  4989.9 2295.17  4995.6 2295.67  5015.2 2297.02
  5025.3 2298.39  5030.5 2300.37  5036.2 2298.25  5045.5 2299.00  5065.7 2303.82
  5096.0 2306.78  5116.2 2312.88  5146.5 2316.51  5177.5 2322.91  5197.0 2330.12
  5227.3 2348.01  5240.5 2350.95  5277.8 2352.27  5324.4 2350.79  5329.3 2350.62
#Mann=7,-1,0
  4594.4    0.07       0  4912.7   0.035       0  4989.4   0.035       0
  4995.6   0.035       0  5036.2    0.07       0  5240.5   0.035       0
  5324.4    0.07       0
Bank Sta=4989.4,4995.6
Exp/Cntr=0.3,0.1

Type RM Length L Ch R = 1,7645,473,473,473
BEGIN DESCRIPTION:
UCFB HW Trib 21 17.0
END DESCRIPTION:
XS GIS Cut Line= 5
      1278954.98      6950937.98      1278569.81      6950635.05
      1278555.00      6950538.00      1278535.09      6950489.21
      1278179.58      6950432.42
#Sta/Elev= 30
  4415.3 2327.94  4670.9 2306.47  4743.3 2300.91  4764.1 2295.55  4778.5 2299.53
  4818.7 2299.70  4828.2 2298.17  4842.7 2300.24  4922.6 2299.69  4963.0 2294.99
  4997.9 2293.75  4998.4 2293.25  5004.1 2293.75  5025.1 2296.38  5035.9 2302.84
  5042.2 2316.92  5093.6 2318.44  5098.7 2315.32  5117.0 2317.38  5127.2 2315.61
  5137.3 2309.19  5147.4 2307.97  5155.7 2314.19  5160.8 2312.66  5177.8 2321.06
  5221.2 2324.64  5240.0 2326.10  5360.1 2336.47  5397.3 2348.33  5416.2 2350.18
#Mann=8,-1,0
  4415.3    0.07       0  4670.9   0.035       0  4818.7    0.07       0
  4997.9    0.07       0  5004.1    0.07       0  5221.2   0.035       0
  5240.0    0.07       0  5397.3   0.035       0
Bank Sta=4997.9,5004.1
Exp/Cntr=0.3,0.1

Type RM Length L Ch R = 1,7172,493,493,493
BEGIN DESCRIPTION:
UCFB HW Trib 21 16.0
END DESCRIPTION:
XS GIS Cut Line= 3
      1279252.57      6950325.15      1278855.00      6950338.00
      1278421.68      6950252.73
#Sta/Elev= 30
  4602.2 2349.77  4619.8 2339.52  4639.8 2331.92  4649.8 2329.61  4679.8 2324.12
  4699.8 2322.17  4729.8 2314.44  4749.8 2312.00  4789.4 2310.33  4819.9 2310.05
  4869.9 2305.79  4909.9 2298.11  4929.9 2296.34  4939.9 2292.66  4949.9 2291.87
  4980.0 2294.94  4997.5 2292.54  5047.8 2290.99  5048.3 2290.49  5054.0 2290.99
  5071.3 2291.94  5077.0 2293.54  5091.7 2301.18  5101.9 2304.19  5173.2 2307.07
  5231.2 2312.87  5236.6 2312.31  5295.5 2315.97  5390.4 2324.29  5441.6 2330.99
#Mann=5,-1,0
  4602.2   0.035       0  4789.4    0.07       0  5047.8    0.07       0
  5054.0    0.07       0  5236.6   0.035       0
Bank Sta=5047.8,5054
Exp/Cntr=0.3,0.1

Type RM Length L Ch R = 1,6679,387,387,387
BEGIN DESCRIPTION:
UCFB HW Trib 21 15.0
END DESCRIPTION:
XS GIS Cut Line= 3
      1279123.45      6950052.80      1278713.98      6950047.73
      1278408.09      6950087.74
#Sta/Elev= 30
  4590.5 2317.76  4639.0 2313.67  4699.0 2311.06  4739.0 2307.44  4759.0 2303.36
  4799.0 2299.57  4829.0 2300.90  4839.0 2302.68  4869.0 2301.81  4879.0 2301.13
  4889.0 2297.96  4929.0 2295.55  4949.0 2290.44  5016.0 2288.61  5016.5 2288.11
  5022.3 2288.61  5042.5 2289.08  5059.5 2293.94  5079.7 2294.77  5099.8 2304.34
  5109.9 2306.07  5116.3 2303.73  5121.4 2311.67  5152.4 2314.77  5200.7 2320.79
  5241.0 2324.18  5251.1 2326.22  5269.1 2332.93  5274.1 2332.34  5308.5 2344.13
#Mann=4,-1,0
  4590.5    0.07       0  5016.0    0.07       0  5022.3    0.07       0
  5152.4   0.035       0
Bank Sta=5016,5022.3
Exp/Cntr=0.3,0.1

Type RM Length L Ch R = 1,6292,424,424,424
BEGIN DESCRIPTION:
UCFB HW Trib 21 14.0
END DESCRIPTION:
XS GIS Cut Line= 3
      1279129.95      6950021.36      1278805.00      6949738.00
      1278592.80      6949486.38
#Sta/Elev= 30
  4569.1 2317.00  4596.3 2316.16  4731.1 2305.12  4801.3 2302.00  4809.0 2300.32
  4815.6 2296.01  4823.2 2299.24  4829.8 2294.98  4837.4 2296.32  4851.7 2295.44
  4858.3 2297.77  4865.9 2294.47  4886.8 2291.99  4901.0 2298.29  4921.9 2294.46
  4929.5 2294.60  4936.2 2291.94  4943.8 2294.48  4972.2 2293.16  4993.8 2288.03
  4994.3 2287.53  5000.1 2288.03  5036.0 2289.59  5064.6 2293.10  5128.3 2295.86
  5156.9 2300.14  5163.4 2302.66  5177.7 2302.24  5206.3 2307.76  5329.4 2320.26
#Mann=3,-1,0
  4569.1    0.07       0  4993.8    0.07       0  5000.1    0.07       0
Bank Sta=4993.8,5000.1
Exp/Cntr=0.3,0.1

Type RM Length L Ch R = 1,5868,449,449,449
BEGIN DESCRIPTION:
UCFB HW Trib 21 13.0
END DESCRIPTION:
XS GIS Cut Line= 5
      1279545.49      6949447.76      1279138.82      6949476.84
      1279055.00      6949438.00      1278965.21      6949394.38
      1278631.44      6949420.42
#Sta/Elev= 30
  4500.4 2322.10  4569.9 2319.47  4646.5 2315.03  4701.4 2313.16  4715.2 2311.56
  4731.5 2312.39  4751.5 2309.09  4855.5 2301.38  4912.7 2295.45  4923.7 2293.58
  4940.4 2289.99  4946.0 2291.67  4956.4 2290.93  4968.9 2291.39  4986.3 2286.17
  5005.6 2284.98  5006.1 2284.48  5012.4 2284.98  5022.7 2286.24  5031.7 2290.15
  5064.5 2292.67  5082.2 2293.28  5097.7 2297.37  5170.7 2302.01  5220.9 2306.62
  5261.0 2308.61  5321.2 2313.21  5331.2 2313.19  5411.5 2320.32  5435.1 2321.42
#Mann=7,-1,0
  4500.4    0.07       0  4646.5   0.035       0  4923.7    0.07       0
  5005.6    0.07       0  5012.4    0.07       0  5031.7    0.16       0
  5064.5    0.07       0
Bank Sta=5005.6,5012.4
Exp/Cntr=0.3,0.1

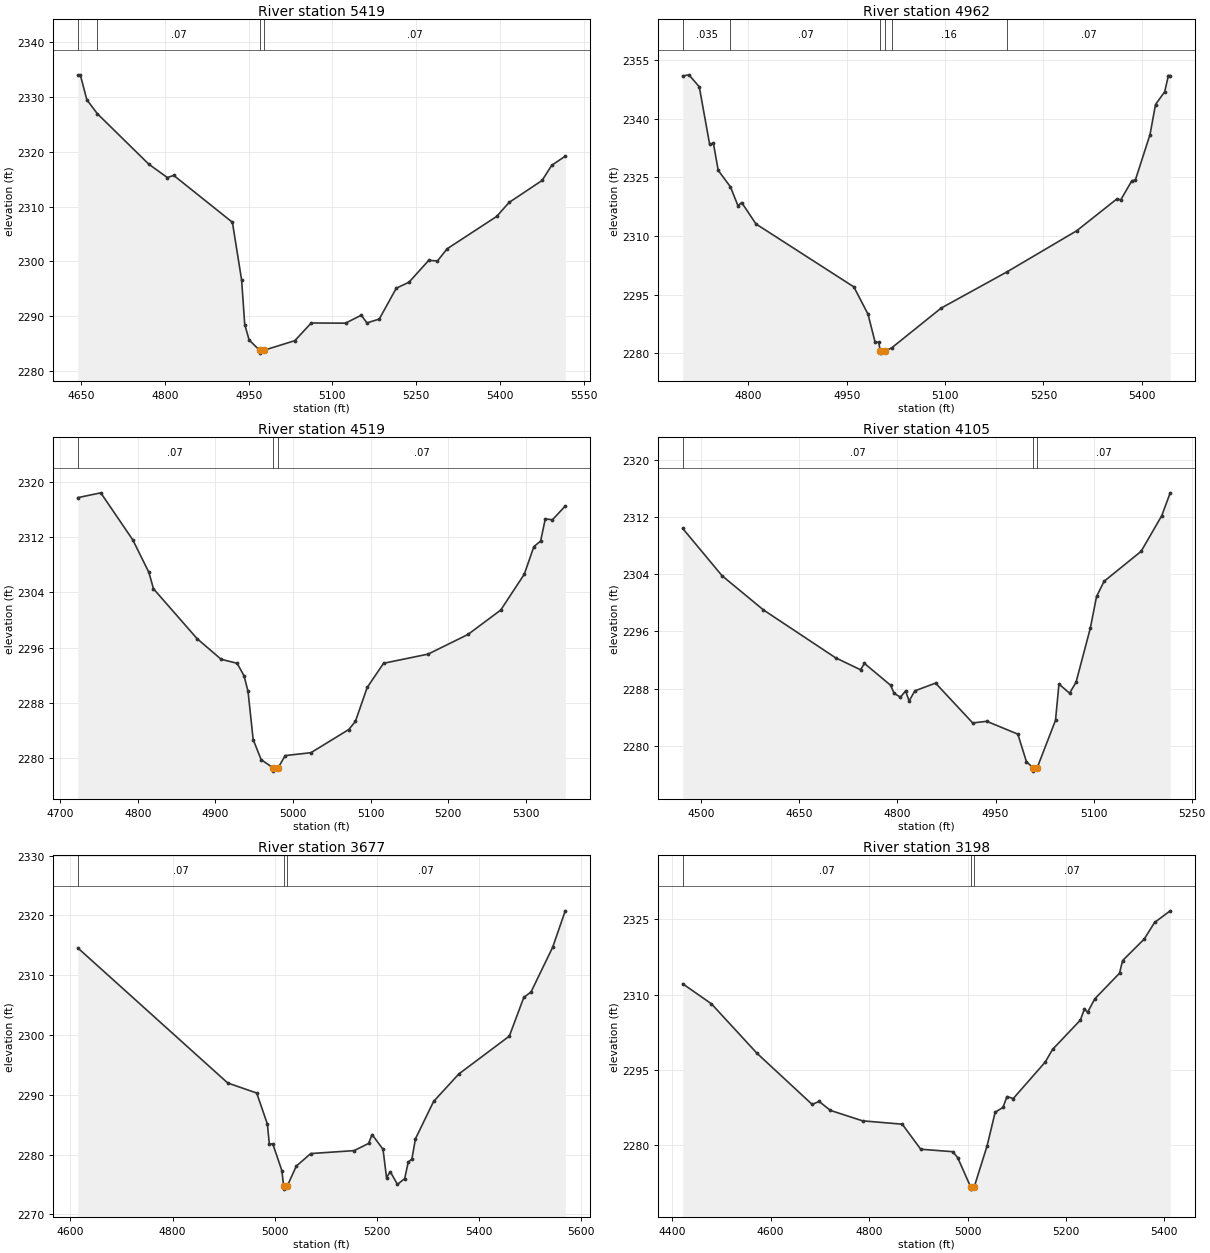
Type RM Length L Ch R = 1,5419,457,457,457
BEGIN DESCRIPTION:
UCFB HW Trib 21 12.0
END DESCRIPTION:
XS GIS Cut Line= 3
      1279417.93      6948877.44      1279105.00      6949038.00
      1278634.09      6949261.55
#Sta/Elev= 30
  4644.0 2334.06  4648.5 2334.06  4660.2 2329.52  4678.9 2326.98  4771.1 2317.76
  4804.3 2315.32  4815.9 2315.70  4920.9 2307.15  4937.4 2296.62  4943.0 2288.49
  4950.8 2285.68  4969.8 2283.77  4970.3 2283.27  4976.6 2283.77  5032.6 2285.54
  5062.1 2288.77  5123.5 2288.74  5151.8 2290.20  5161.8 2288.78  5183.9 2289.49
  5214.4 2295.12  5237.1 2296.21  5272.5 2300.20  5288.1 2300.09  5305.3 2302.30
  5394.2 2308.22  5416.4 2310.77  5475.5 2314.78  5492.7 2317.54  5517.0 2319.22
#Mann=4,-1,0
  4644.0   0.035       0  4678.9    0.07       0  4969.8    0.07       0
  4976.6    0.07       0
Bank Sta=4969.8,4976.6
Exp/Cntr=0.3,0.1

Type RM Length L Ch R = 1,4962,443,443,443
BEGIN DESCRIPTION:
UCFB HW Trib 21 11.0
END DESCRIPTION:
XS GIS Cut Line= 3
      1279111.90      6948640.48      1278855.00      6948788.00
      1278454.97      6948988.02
#Sta/Elev= 30
  4699.8 2351.04  4709.2 2351.32  4725.0 2348.26  4740.8 2333.52  4746.6 2333.75
  4753.9 2326.83  4772.6 2322.59  4784.0 2317.77  4789.7 2318.57  4811.5 2313.09
  4960.8 2296.95  4982.4 2289.95  4993.2 2282.77  4998.8 2282.77  5001.0 2280.47
  5001.5 2279.97  5007.9 2280.47  5018.5 2281.32  5093.9 2291.51  5193.8 2300.75
  5300.7 2311.34  5362.2 2319.54  5367.8 2319.24  5384.6 2324.12  5390.2 2324.37
  5412.5 2336.00  5420.9 2343.71  5434.9 2346.98  5440.5 2351.14  5443.3 2351.14
#Mann=6,-1,0
  4699.8   0.035       0  4772.6    0.07       0  5001.0    0.07       0
  5007.9    0.07       0  5018.5    0.16       0  5193.8    0.07       0
Bank Sta=5001,5007.9
Exp/Cntr=0.3,0.1

Type RM Length L Ch R = 1,4519,414,414,414
BEGIN DESCRIPTION:
UCFB HW Trib 21 10.0
END DESCRIPTION:
XS GIS Cut Line= 3
      1278873.66      6948368.33      1278605.00      6948438.00
      1278311.13      6948628.76
#Sta/Elev= 30
  4722.7 2317.79  4752.3 2318.49  4793.6 2311.64  4814.3 2306.92  4820.2 2304.54
  4876.3 2297.30  4907.3 2294.29  4927.9 2293.71  4936.8 2291.91  4942.0 2289.62
  4948.6 2282.62  4958.9 2279.70  4973.9 2278.53  4974.4 2278.03  4980.8 2278.53
  4989.9 2280.29  5023.0 2280.71  5071.8 2284.08  5080.3 2285.26  5095.5 2290.20
  5116.6 2293.71  5173.9 2295.04  5225.3 2297.90  5267.5 2301.45  5297.8 2306.65
  5310.2 2310.67  5318.9 2311.49  5324.9 2314.71  5334.1 2314.57  5350.6 2316.57
#Mann=3,-1,0
  4722.7    0.07       0  4973.9    0.07       0  4980.8    0.07       0
Bank Sta=4973.9,4980.8
Exp/Cntr=0.3,0.1

Type RM Length L Ch R = 1,4105,428,428,428
BEGIN DESCRIPTION:
UCFB HW Trib 21 9.0
END DESCRIPTION:
XS GIS Cut Line= 4
      1278837.14      6948306.95      1278422.24      6948115.12
      1278355.00      6948138.00      1278149.22      6948207.72
#Sta/Elev= 30
  4471.7 2310.45  4531.7 2303.83  4595.0 2299.03  4705.4 2292.31  4743.6 2290.63
  4749.5 2291.52  4789.5 2288.46  4795.0 2287.31  4804.6 2286.79  4812.4 2287.65
  4817.9 2286.26  4826.6 2287.67  4858.3 2288.76  4915.1 2283.17  4936.5 2283.40
  4984.1 2281.60  4997.2 2277.75  5006.8 2276.91  5007.3 2276.41  5013.8 2276.91
  5041.7 2283.54  5047.0 2288.63  5063.2 2287.34  5073.1 2288.88  5094.9 2296.45
  5104.5 2300.91  5116.0 2303.04  5172.6 2307.24  5204.1 2312.23  5217.1 2315.45
#Mann=3,-1,0
  4471.7    0.07       0  5006.8    0.07       0  5013.8    0.07       0
Bank Sta=5006.8,5013.8
Exp/Cntr=0.3,0.1

Type RM Length L Ch R = 1,3677,479,479,479
BEGIN DESCRIPTION:
UCFB HW Trib 21 8.0
END DESCRIPTION:
XS GIS Cut Line= 3
      1278907.51      6948320.02      1278655.00      6948038.00
      1278256.21      6947621.88
#Sta/Elev= 30
  4614.4 2314.56  4908.1 2291.97  4964.9 2290.29  4985.8 2285.10  4989.6 2281.78
  4996.4 2281.78  5014.2 2277.31  5017.6 2274.72  5018.1 2274.22  5024.6 2274.72
  5042.5 2278.08  5070.8 2280.17  5155.7 2280.66  5184.0 2281.86  5190.9 2283.35
  5212.3 2280.89  5219.2 2276.14  5226.5 2277.14  5240.6 2275.01  5254.8 2275.99
  5261.7 2278.74  5268.9 2279.25  5275.8 2282.63  5311.4 2288.88  5360.7 2293.47
  5459.8 2299.81  5488.1 2306.28  5502.3 2307.20  5544.7 2314.68  5569.3 2320.76
#Mann=3,-1,0
  4614.4    0.07       0  5017.6    0.07       0  5024.6    0.07       0
Bank Sta=5017.6,5024.6
Exp/Cntr=0.3,0.1

Type RM Length L Ch R = 1,3198,476,476,476
BEGIN DESCRIPTION:
UCFB HW Trib 21 7.0
END DESCRIPTION:
XS GIS Cut Line= 5
      1279011.64      6948198.87      1278755.58      6947748.81
      1278755.00      6947688.00      1278753.41      6947630.53
      1278465.83      6947423.26
#Sta/Elev= 30
  4421.3 2312.15  4479.7 2308.15  4571.9 2298.33  4684.3 2288.11  4698.4 2288.70
  4721.4 2286.92  4786.7 2284.84  4867.4 2284.17  4904.9 2279.18  4969.9 2278.69
  4979.9 2277.53  5006.1 2271.73  5006.6 2271.23  5013.8 2271.73  5039.9 2279.89
  5056.2 2286.56  5072.1 2287.51  5080.1 2289.68  5093.0 2289.29  5158.0 2296.56
  5172.7 2299.06  5229.2 2304.90  5237.7 2307.15  5243.9 2306.44  5258.6 2309.15
  5308.9 2314.26  5315.1 2316.77  5359.2 2321.08  5380.1 2324.37  5411.9 2326.69
#Mann=3,-1,0
  4421.3    0.07       0  5006.1    0.07       0  5013.8    0.07       0
Bank Sta=5006.1,5013.8
Exp/Cntr=0.3,0.1

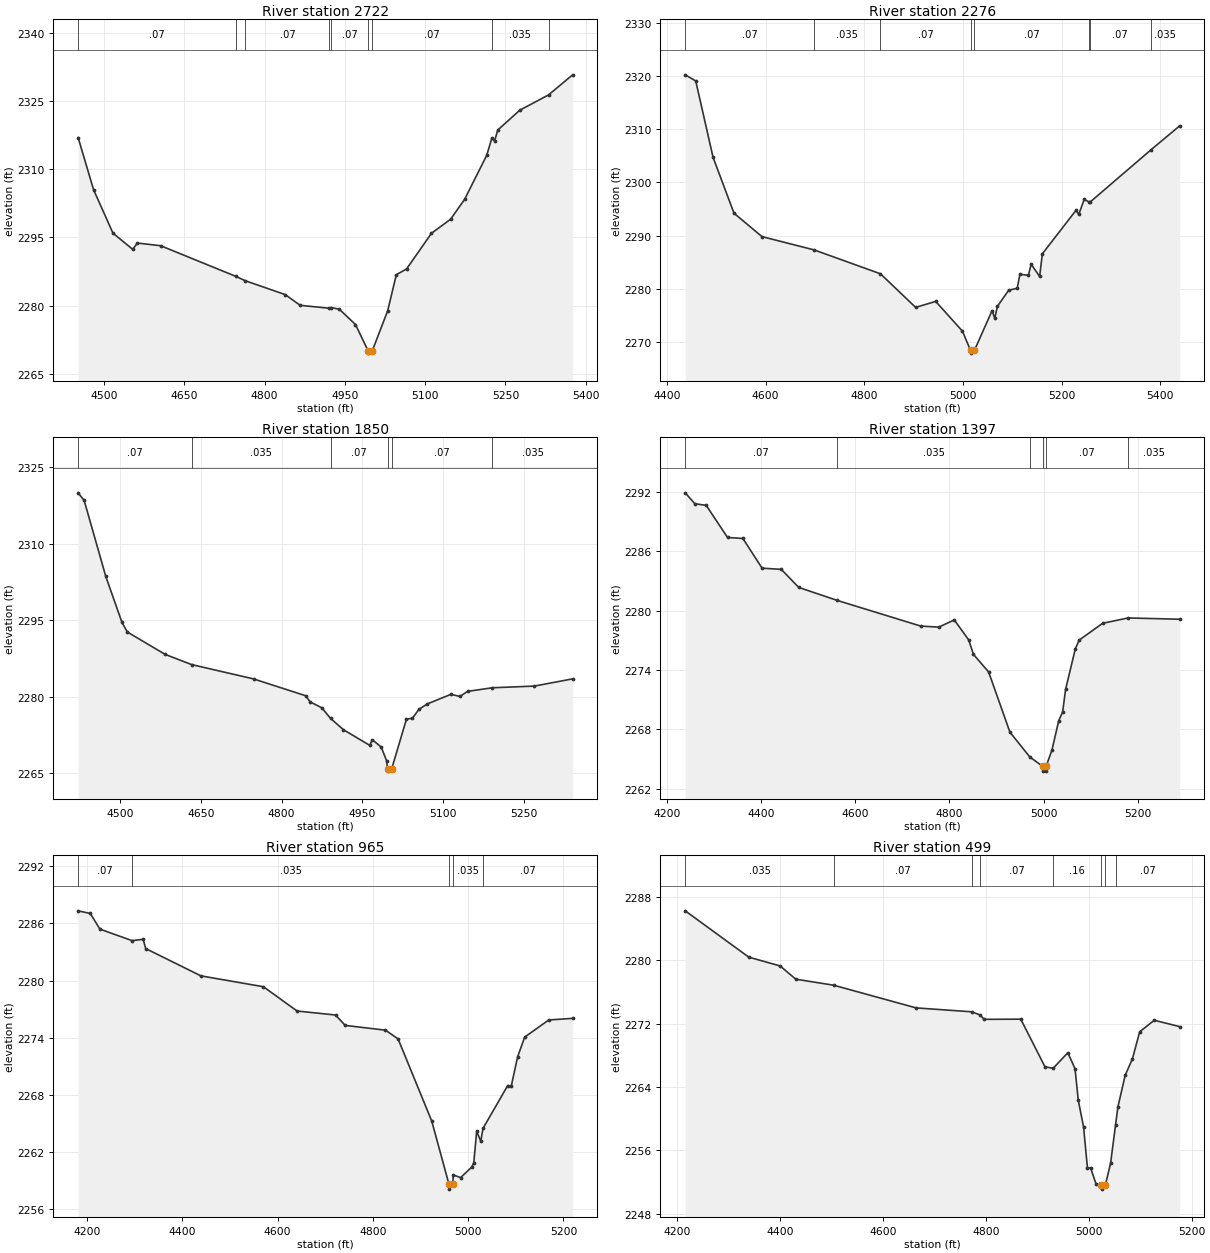
Type RM Length L Ch R = 1,2722,446,446,446
BEGIN DESCRIPTION:
UCFB HW Trib 21 6.0
END DESCRIPTION:
XS GIS Cut Line= 5
      1279329.61      6947704.34      1278896.64      6947441.73
      1278855.00      6947438.00      1278807.66      6947437.39
      1278489.32      6947357.26
#Sta/Elev= 30
  4451.7 2316.91  4480.5 2305.47  4516.8 2295.91  4553.6 2292.36  4562.4 2293.74
  4605.9 2293.15  4746.5 2286.41  4763.9 2285.46  4838.6 2282.41  4866.4 2280.06
  4921.1 2279.41  4924.5 2279.55  4939.4 2279.22  4969.8 2275.84  4993.5 2270.05
  4994.0 2269.55  5001.2 2270.05  5029.9 2278.84  5046.1 2286.77  5065.3 2288.06
  5111.8 2295.89  5147.5 2298.98  5173.7 2303.35  5215.0 2313.02  5224.4 2316.73
  5229.8 2316.21  5235.6 2318.58  5276.8 2322.94  5330.4 2326.29  5375.5 2330.71
#Mann=9,-1,0
  4451.7    0.07       0  4746.5   0.035       0  4763.9    0.07       0
  4921.1   0.035       0  4924.5    0.07       0  4993.5    0.07       0
  5001.2    0.07       0  5224.4   0.035       0  5330.4    0.07       0
Bank Sta=4993.5,5001.2
Exp/Cntr=0.3,0.1

Type RM Length L Ch R = 1,2276,426,426,426
BEGIN DESCRIPTION:
UCFB HW Trib 21 5.0
END DESCRIPTION:
XS GIS Cut Line= 5
      1279405.01      6947688.01      1279039.86      6947342.99
      1279055.00      6947288.00      1279071.33      6947224.72
      1278729.96      6947062.98
#Sta/Elev= 30
  4437.0 2320.21  4458.3 2319.06  4493.5 2304.68  4535.9 2294.20  4592.6 2289.80
  4698.4 2287.30  4832.8 2282.81  4904.1 2276.50  4944.8 2277.62  4999.0 2272.03
  5015.5 2268.40  5016.0 2267.90  5023.2 2268.40  5059.1 2275.89  5064.5 2274.45
  5070.0 2276.71  5092.8 2279.73  5110.0 2280.09  5115.5 2282.71  5132.7 2282.53
  5138.3 2284.61  5155.5 2282.31  5161.0 2286.57  5229.2 2294.74  5234.8 2293.97
  5245.8 2296.78  5256.4 2296.29  5257.5 2296.27  5380.5 2306.06  5439.5 2310.63
#Mann=8,-1,0
  4437.0    0.07       0  4698.4   0.035       0  4832.8    0.07       0
  5015.5    0.07       0  5023.2    0.07       0  5256.4   0.035       0
  5257.5    0.07       0  5380.5   0.035       0
Bank Sta=5015.5,5023.2
Exp/Cntr=0.3,0.1

Type RM Length L Ch R = 1,1850,453,453,453
BEGIN DESCRIPTION:
UCFB HW Trib 21 4.0
END DESCRIPTION:
XS GIS Cut Line= 4
      1279459.37      6947669.17      1279406.92      6947091.79
      1279404.02      6947059.54      1279131.93      6946916.80
#Sta/Elev= 30
  4421.8 2319.99  4433.0 2318.49  4473.2 2303.58  4503.3 2294.55  4513.3 2292.67
  4583.6 2288.28  4632.8 2286.28  4747.9 2283.47  4844.7 2280.17  4853.3 2278.95
  4874.8 2277.80  4891.1 2275.72  4915.0 2273.50  4963.8 2270.44  4968.9 2271.52
  4985.3 2270.09  4995.3 2267.41  4997.1 2265.87  4997.6 2265.37  5004.9 2265.87
  5032.2 2275.57  5043.3 2275.76  5055.4 2277.49  5071.0 2278.56  5115.1 2280.45
  5131.5 2280.02  5145.8 2281.02  5191.7 2281.73  5270.0 2282.06  5341.2 2283.48
#Mann=6,-1,0
  4421.8    0.07       0  4632.8   0.035       0  4891.1    0.07       0
  4997.1    0.07       0  5004.9    0.07       0  5191.7   0.035       0
Bank Sta=4997.1,5004.9
Exp/Cntr=0.3,0.1

Type RM Length L Ch R = 1,1397,432,432,432
BEGIN DESCRIPTION:
UCFB HW Trib 21 3.0
END DESCRIPTION:
XS GIS Cut Line= 3
      1279858.69      6947637.98      1279705.00      6946888.00
      1279480.01      6946713.01
#Sta/Elev= 30
  4238.6 2291.94  4259.0 2290.84  4283.2 2290.67  4328.5 2287.42  4361.1 2287.32
  4401.9 2284.31  4442.7 2284.19  4479.8 2282.36  4561.2 2281.05  4738.8 2278.45
  4777.2 2278.34  4810.2 2279.07  4840.8 2277.05  4851.0 2275.58  4883.2 2273.80
  4928.5 2267.70  4971.0 2265.18  4997.7 2264.26  4998.2 2263.76  5005.0 2263.76
  5005.5 2264.26  5017.7 2265.89  5032.2 2268.88  5040.4 2269.74  5046.7 2272.04
  5067.5 2276.16  5075.7 2277.03  5125.4 2278.73  5179.6 2279.27  5289.2 2279.14
#Mann=6,-1,0
  4238.6    0.07       0  4561.2   0.035       0  4971.0    0.07       0
  4997.7    0.07       0  5005.5    0.07       0  5179.6   0.035       0
Bank Sta=4997.7,5005.5
Exp/Cntr=0.3,0.1

Type RM Length L Ch R = 1,965,466,466,466
BEGIN DESCRIPTION:
UCFB HW Trib 21 2.0
END DESCRIPTION:
XS GIS Cut Line= 3
      1280219.79      6947603.25      1280105.00      6946788.00
      1279930.04      6946663.03
#Sta/Elev= 30
  4181.1 2287.32  4206.6 2287.04  4226.8 2285.40  4294.3 2284.19  4317.7 2284.33
  4322.9 2283.36  4438.9 2280.49  4570.1 2279.35  4640.8 2276.80  4721.6 2276.38
  4741.8 2275.29  4826.4 2274.79  4852.9 2273.87  4923.6 2265.24  4959.8 2258.60
  4960.3 2258.10  4967.6 2258.60  4968.8 2259.59  4984.2 2259.31  5007.5 2260.41
  5011.8 2260.87  5017.9 2264.17  5026.5 2263.13  5031.1 2264.47  5083.0 2268.97
  5090.4 2268.89  5103.9 2272.00  5118.7 2274.06  5169.1 2275.86  5219.4 2276.03
#Mann=5,-1,0
  4181.1    0.07       0  4294.3   0.035       0  4959.8   0.035       0
  4967.6   0.035       0  5031.1    0.07       0
Bank Sta=4959.8,4967.6
Exp/Cntr=0.3,0.1

Type RM Length L Ch R = 1,499,0,0,0
BEGIN DESCRIPTION:
UCFB HW Trib 21 1.0
END DESCRIPTION:
XS GIS Cut Line= 3
      1280695.48      6947509.46      1280555.00      6946738.00
      1280430.02      6946613.02
#Sta/Elev= 30
  4215.9 2286.21  4339.4 2280.37  4400.3 2279.26  4430.8 2277.59  4504.4 2276.83
  4664.6 2273.97  4772.3 2273.48  4788.9 2273.08  4796.8 2272.53  4867.9 2272.55
  4915.0 2266.54  4930.9 2266.36  4959.4 2268.32  4973.4 2266.29  4979.7 2262.31
  4989.9 2258.98  4997.5 2253.80  5003.6 2253.80  5014.2 2251.78  5024.3 2251.62
  5024.8 2251.12  5032.3 2251.62  5042.5 2254.41  5052.1 2259.21  5056.6 2261.46
  5070.8 2265.47  5084.9 2267.55  5099.0 2270.96  5127.3 2272.41  5176.8 2271.61
#Mann=8,-1,0
  4215.9   0.035       0  4504.4    0.07       0  4772.3   0.035       0
  4788.9    0.07       0  4930.9    0.16       0  5024.3    0.07       0
  5032.3    0.16       0  5052.1    0.07       0
Bank Sta=5024.3,5032.3
Exp/Cntr=0.3,0.1

Chan Stop Cuts=-1