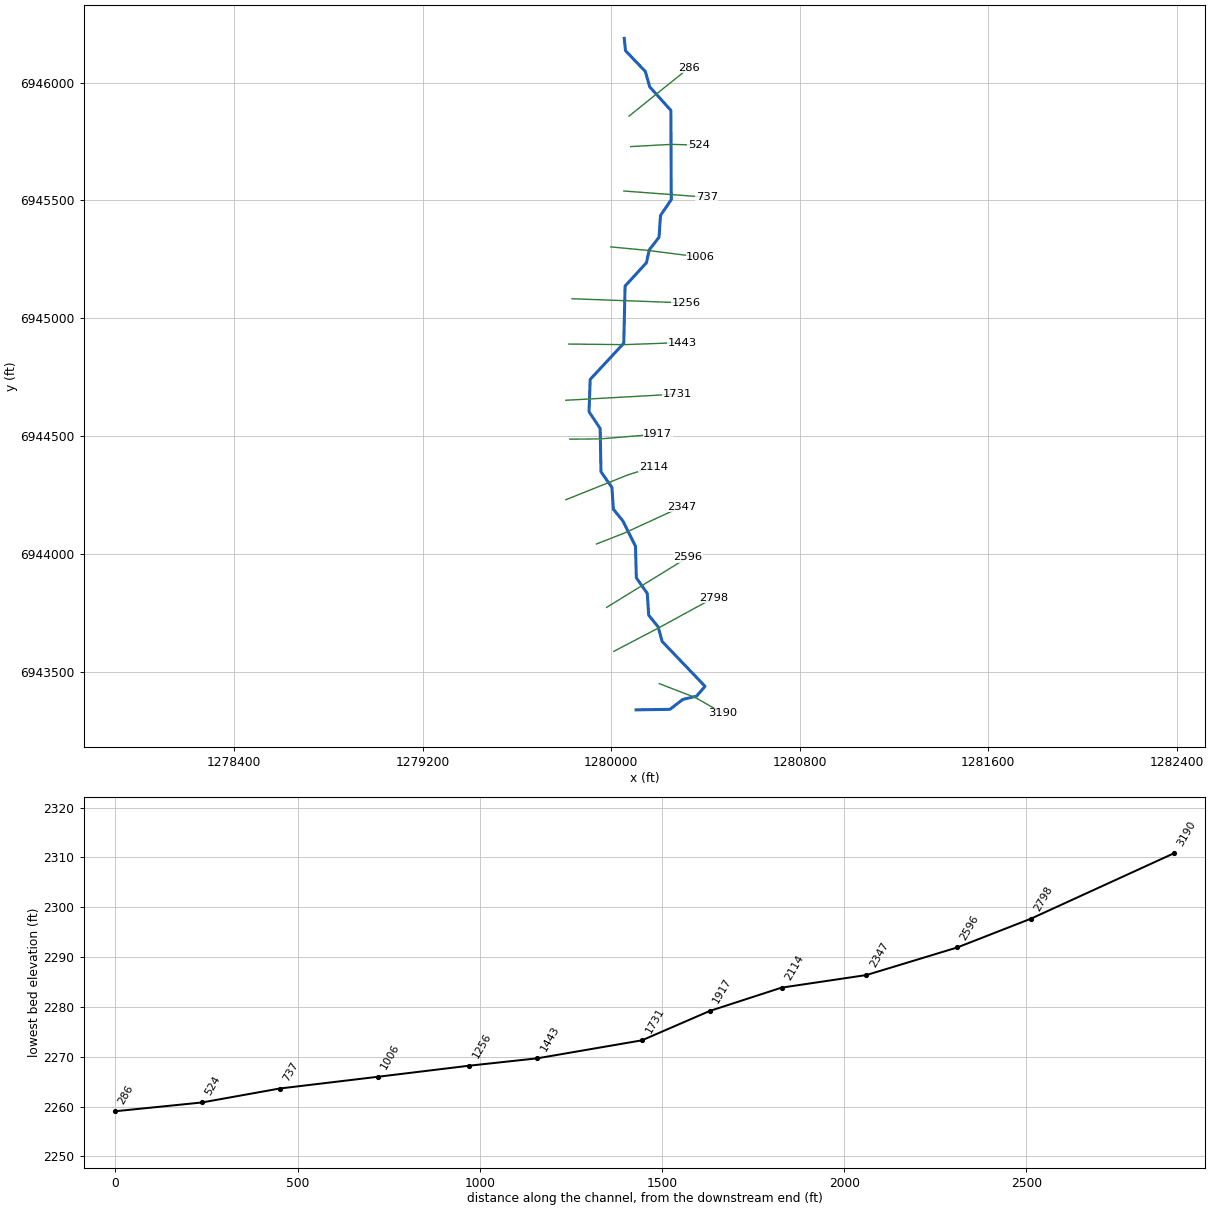
--- UCFB HW Trib 22.prj (project) ---

Proj Title=UCFB HW Trib 22 Base Level Engineering
Current Plan=p01
Default Exp/Contr=0.3,0.1
English Units
Geom File=g01
Flow File=f01
Plan File=p01
BEGIN DESCRIPTION:
UCFB HW Trib 22
END DESCRIPTION:

--- UCFB HW Trib 22.p01 (plan) ---

Plan Title=Multiple Run
Short Identifier=Multiple
Geom File=g01
Flow File=f01
Subcritical Flow
K Sum by GR= 0
Std Step Tol= 0.01
Critical Tol= 0.01
Num of Std Step Trials= 20
Max Error Tol= 0.3
Flow Tol Ratio= 0.001
Split Flow NTrial= 30
Split Flow Tol= 0.02
Split Flow Ratio= 0.02
Log Output Level= 0
Friction Slope Method= 1
Unsteady Friction Slope Method= 2
Unsteady Bridges Friction Slope Method= 1
Parabolic Critical Depth
Global Vel Dist=  1 , 1 , 1
Global Log Level= 0
CheckData=True
Encroach Param= -1, 0, 0, 0
BEGIN DESCRIPTION:
Multiple Run
END DESCRIPTION:

--- UCFB HW Trib 22.f01 (steady flow) ---

Flow Title=Multiple
Number of Profiles=7
Profile Names=10-year,25-year,50-year,1pct_min,100-year,1pct_plu,500-year
River Rch & RM= UCFB HW Trib 22,Reach-1,3190
      81     108     128      77     153     305     219
Boundary for River Rch & Prof#=UCFB HW Trib 22,Reach-1,1
Up Type=0
Dn Type=3
Dn Slope=0.005
Boundary for River Rch & Prof#=UCFB HW Trib 22,Reach-1,2
Up Type=0
Dn Type=3
Dn Slope=0.005
Boundary for River Rch & Prof#=UCFB HW Trib 22,Reach-1,3
Up Type=0
Dn Type=3
Dn Slope=0.005
Boundary for River Rch & Prof#=UCFB HW Trib 22,Reach-1,4
Up Type=0
Dn Type=3
Dn Slope=0.005
Boundary for River Rch & Prof#=UCFB HW Trib 22,Reach-1,5
Up Type=0
Dn Type=3
Dn Slope=0.005
Boundary for River Rch & Prof#=UCFB HW Trib 22,Reach-1,6
Up Type=0
Dn Type=3
Dn Slope=0.005
Boundary for River Rch & Prof#=UCFB HW Trib 22,Reach-1,7
Up Type=0
Dn Type=3
Dn Slope=0.005

--- UCFB HW Trib 22.g01 (geometry) ---

Geom Title=Existing Conditions

River Reach=UCFB HW Trib 22,Reach-1
Reach XY= 30
      1280105.00      6943338.00      1280249.09      6943340.19
      1280302.88      6943381.86      1280361.72      6943396.14
      1280398.02      6943437.79      1280215.76      6943628.32
      1280198.86      6943690.17      1280158.82      6943739.58
      1280152.64      6943832.02      1280106.23      6943898.51
      1280102.75      6944032.07      1280048.89      6944140.18
      1280008.83      6944189.58      1280002.64      6944282.02
      1279956.22      6944348.50      1279952.74      6944532.06
      1279905.51      6944603.22      1279910.45      6944740.45
      1280052.94      6944893.85      1280058.55      6945136.53
      1280149.15      6945235.71      1280161.14      6945290.17
      1280202.67      6945343.97      1280208.86      6945436.40
      1280254.48      6945503.22      1280252.94      6945882.14
      1280163.18      6945981.96      1280144.22      6946047.68
      1280060.33      6946135.49      1280055.00      6946188.00

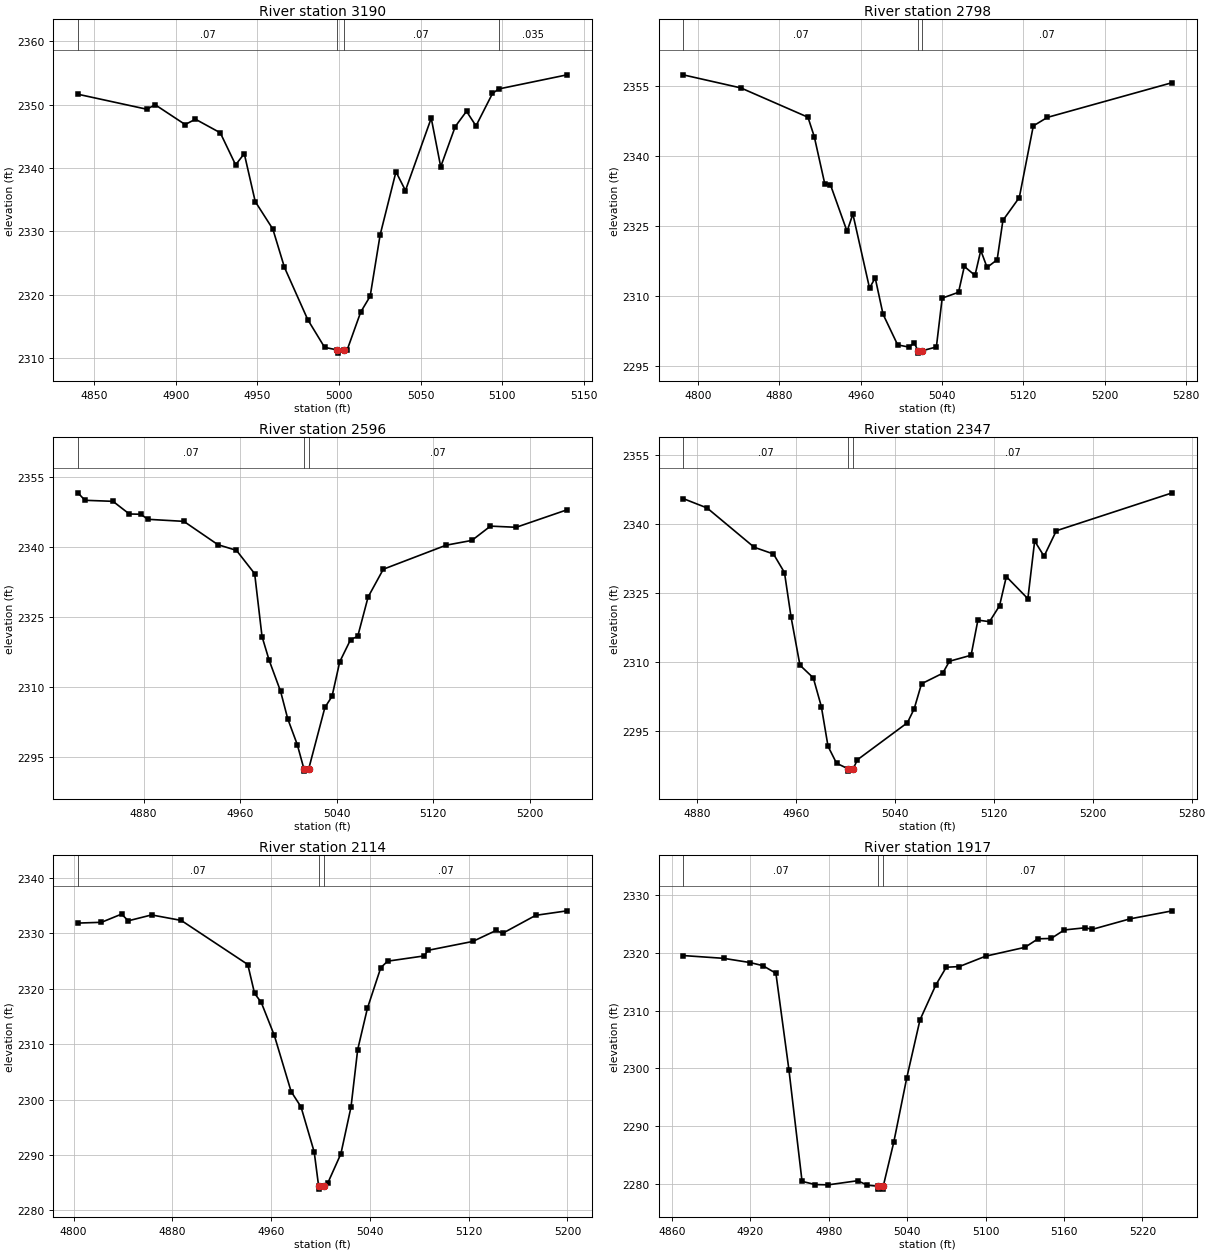
Type RM Length L Ch R = 1,3190,392,392,392
BEGIN DESCRIPTION:
UCFB HW Trib 22 7.0
END DESCRIPTION:
XS GIS Cut Line= 3
      1280203.70      6943449.32      1280357.52      6943389.79
      1280474.47      6943323.04
#Sta/Elev= 30
  4840.1 2351.62  4882.2 2349.26  4887.5 2349.95  4905.8 2346.84  4912.1 2347.68
  4927.3 2345.54  4936.7 2340.48  4942.0 2342.25  4948.7 2334.70  4959.5 2330.35
  4966.6 2324.32  4980.9 2316.06  4991.2 2311.70  4999.0 2311.29  4999.3 2310.79
  5003.0 2311.29  5005.0 2311.29  5013.3 2317.26  5019.1 2319.77  5025.2 2329.43
  5034.9 2339.39  5040.7 2336.43  5056.5 2347.85  5062.3 2340.18  5071.2 2346.52
  5078.1 2348.93  5083.9 2346.62  5094.0 2351.74  5097.8 2352.45  5139.7 2354.68
#Mann=4,-1,0
  4840.1    0.07       0  4999.0    0.07       0  5003.0    0.07       0
  5097.8   0.035       0
Bank Sta=4999,5003
Exp/Cntr=0.3,0.1

Type RM Length L Ch R = 1,2798,202,202,202
BEGIN DESCRIPTION:
UCFB HW Trib 22 6.0
END DESCRIPTION:
XS GIS Cut Line= 3
      1280010.64      6943586.18      1280205.00      6943688.00
      1280435.07      6943813.54
#Sta/Elev= 30
  4785.2 2357.29  4842.0 2354.49  4908.1 2348.21  4914.3 2344.07  4924.6 2334.00
  4930.2 2333.77  4946.6 2323.76  4952.3 2327.48  4968.7 2311.62  4974.3 2313.78
  4982.0 2306.02  4996.4 2299.44  5007.5 2298.98  5012.7 2299.89  5016.4 2298.18
  5016.6 2297.68  5020.4 2298.18  5034.5 2299.00  5040.2 2309.46  5056.3 2310.71
  5062.0 2316.25  5072.5 2314.33  5078.2 2319.68  5084.4 2316.04  5094.3 2317.68
  5100.0 2326.12  5116.1 2331.00  5129.9 2346.35  5143.7 2348.17  5266.7 2355.62
#Mann=3,-1,0
  4785.2    0.07       0  5016.4    0.07       0  5020.4    0.07       0
Bank Sta=5016.4,5020.4
Exp/Cntr=0.3,0.1

Type RM Length L Ch R = 1,2596,249,249,249
BEGIN DESCRIPTION:
UCFB HW Trib 22 5.5
END DESCRIPTION:
XS GIS Cut Line= 2
      1279980.25      6943772.80      1280325.36      6943985.51
#Sta/Elev= 30
  4825.6 2351.51  4831.5 2349.91  4854.7 2349.69  4868.2 2346.98  4877.7 2346.92
  4883.6 2345.84  4913.4 2345.40  4941.6 2340.41  4957.0 2339.19  4972.1 2334.19
  4978.2 2320.73  4984.1 2315.65  4993.6 2308.98  4999.5 2303.12  5007.4 2297.60
  5012.9 2292.41  5013.2 2291.91  5016.9 2292.41  5030.3 2305.55  5036.2 2307.92
  5042.6 2315.33  5051.6 2320.08  5057.5 2320.77  5066.1 2329.20  5078.7 2335.15
  5130.8 2340.30  5152.1 2341.32  5167.5 2344.38  5188.8 2344.13  5231.0 2347.88
#Mann=3,-1,0
  4825.6    0.07       0  5012.9    0.07       0  5016.9    0.07       0
Bank Sta=5012.9,5016.9
Exp/Cntr=0.3,0.1

Type RM Length L Ch R = 1,2347,233,233,233
BEGIN DESCRIPTION:
UCFB HW Trib 22 5.0
END DESCRIPTION:
XS GIS Cut Line= 3
      1279936.92      6944041.93      1280055.00      6944088.00
      1280299.26      6944200.32
#Sta/Elev= 30
  4868.7 2345.52  4888.1 2343.48  4926.2 2334.95  4941.8 2333.49  4950.7 2329.45
  4956.0 2319.84  4963.2 2309.37  4974.0 2306.61  4980.5 2300.39  4985.9 2291.78
  4992.8 2288.09  5002.2 2286.88  5002.4 2286.38  5006.2 2286.88  5009.7 2288.85
  5050.1 2296.88  5055.6 2299.92  5061.5 2305.33  5078.6 2307.61  5084.1 2310.22
  5101.6 2311.52  5107.1 2319.14  5116.5 2318.81  5124.6 2322.26  5130.1 2328.58
  5147.5 2323.79  5153.0 2336.31  5160.6 2333.00  5170.5 2338.53  5264.3 2346.76
#Mann=3,-1,0
  4868.7    0.07       0  5002.2    0.07       0  5006.2    0.07       0
Bank Sta=5002.2,5006.2
Exp/Cntr=0.3,0.1

Type RM Length L Ch R = 1,2114,197,197,197
BEGIN DESCRIPTION:
UCFB HW Trib 22 3.5
END DESCRIPTION:
XS GIS Cut Line= 3
      1279807.25      6944229.79      1280071.06      6944335.32
      1280177.75      6944369.60
#Sta/Elev= 30
  4803.5 2331.82  4822.6 2331.96  4838.9 2333.44  4844.3 2332.23  4863.2 2333.29
  4887.2 2332.30  4941.1 2324.35  4946.6 2319.14  4952.0 2317.52  4962.6 2311.56
  4976.2 2301.45  4984.2 2298.68  4994.9 2290.54  4998.5 2284.35  4998.7 2283.85
  5002.5 2284.35  5005.9 2284.95  5016.5 2290.22  5024.7 2298.66  5030.1 2309.00
  5038.0 2316.47  5048.8 2323.77  5054.3 2324.95  5083.9 2325.90  5087.1 2326.91
  5123.3 2328.51  5142.2 2330.49  5147.5 2329.98  5174.3 2333.22  5199.7 2334.03
#Mann=3,-1,0
  4803.5    0.07       0  4998.5    0.07       0  5002.5    0.07       0
Bank Sta=4998.5,5002.5
Exp/Cntr=0.3,0.1

Type RM Length L Ch R = 1,1917,186,186,186
BEGIN DESCRIPTION:
UCFB HW Trib 22 4.0
END DESCRIPTION:
XS GIS Cut Line= 3
      1279824.00      6944486.79      1279955.00      6944488.00
      1280197.33      6944508.50
#Sta/Elev= 30
  4868.6 2319.49  4899.6 2319.01  4919.6 2318.29  4929.6 2317.75  4939.6 2316.43
  4949.6 2299.70  4959.6 2280.51  4969.6 2279.96  4979.6 2279.91  5002.1 2280.62
  5009.6 2279.85  5017.7 2279.67  5017.9 2279.17  5021.4 2279.17  5021.7 2279.67
  5029.7 2287.22  5039.7 2298.39  5049.8 2308.38  5061.9 2314.40  5069.9 2317.47
  5079.9 2317.59  5100.0 2319.38  5130.1 2320.91  5140.1 2322.38  5150.1 2322.44
  5160.2 2323.91  5176.4 2324.29  5181.4 2324.00  5210.4 2325.82  5242.8 2327.21
#Mann=3,-1,0
  4868.6    0.07       0  5017.7    0.07       0  5021.7    0.07       0
Bank Sta=5017.7,5021.7
Exp/Cntr=0.3,0.1

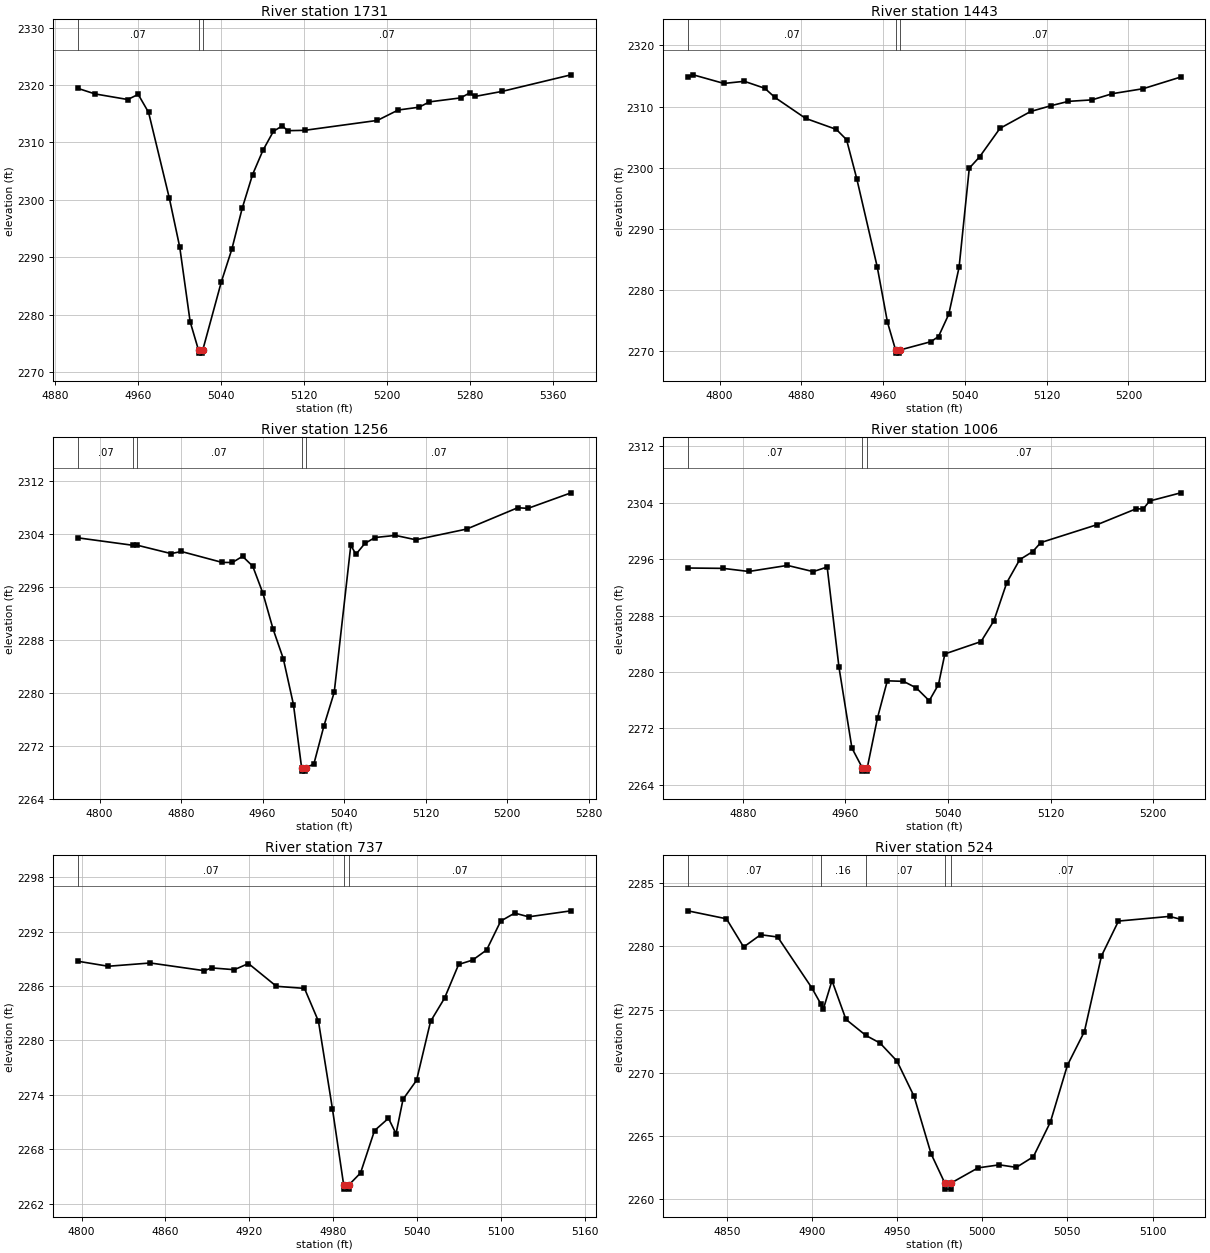
Type RM Length L Ch R = 1,1731,288,288,288
BEGIN DESCRIPTION:
UCFB HW Trib 22 3.4
END DESCRIPTION:
XS GIS Cut Line= 2
      1279807.23      6944651.88      1280281.10      6944678.21
#Sta/Elev= 30
  4902.5 2319.39  4918.9 2318.43  4950.3 2317.46  4960.4 2318.35  4970.4 2315.21
  4990.4 2300.25  5000.4 2291.74  5010.4 2278.76  5018.5 2273.78  5018.7 2273.28
  5022.2 2273.28  5022.5 2273.78  5040.5 2285.74  5050.5 2291.35  5060.5 2298.50
  5070.5 2304.38  5080.5 2308.61  5090.6 2311.93  5099.2 2312.87  5104.2 2312.03
  5120.6 2312.09  5190.7 2313.82  5210.7 2315.63  5230.8 2316.12  5240.8 2317.05
  5270.8 2317.74  5279.5 2318.60  5284.5 2317.99  5310.9 2318.88  5377.1 2321.76
#Mann=3,-1,0
  4902.5    0.07       0  5018.5    0.07       0  5022.5    0.07       0
Bank Sta=5018.5,5022.5
Exp/Cntr=0.3,0.1

Type RM Length L Ch R = 1,1443,187,187,187
BEGIN DESCRIPTION:
UCFB HW Trib 22 3.0
END DESCRIPTION:
XS GIS Cut Line= 3
      1279819.68      6944890.44      1280055.00      6944888.00
      1280301.81      6944896.88
#Sta/Elev= 30
  4768.9 2314.86  4774.2 2315.20  4804.2 2313.79  4824.2 2314.14  4844.2 2313.00
  4854.2 2311.49  4884.2 2308.07  4914.2 2306.27  4924.2 2304.59  4934.2 2298.20
  4954.2 2283.79  4964.2 2274.75  4972.2 2270.16  4972.5 2269.66  4976.0 2269.66
  4976.2 2270.16  5006.7 2271.53  5014.2 2272.38  5024.2 2276.02  5034.3 2283.70
  5044.3 2299.93  5054.3 2301.76  5074.3 2306.44  5104.3 2309.20  5124.3 2310.15
  5141.3 2310.86  5164.3 2311.10  5184.4 2312.12  5214.4 2312.93  5251.2 2314.84
#Mann=3,-1,0
  4768.9    0.07       0  4972.2    0.07       0  4976.2    0.07       0
Bank Sta=4972.2,4976.2
Exp/Cntr=0.3,0.1

Type RM Length L Ch R = 1,1256,250,250,250
BEGIN DESCRIPTION:
UCFB HW Trib 22 2.5
END DESCRIPTION:
XS GIS Cut Line= 2
      1279833.62      6945082.77      1280317.30      6945065.19
#Sta/Elev= 30
  4778.8 2303.41  4832.5 2302.29  4836.6 2302.31  4870.2 2301.03  4880.2 2301.35
  4920.3 2299.70  4930.3 2299.69  4940.3 2300.62  4950.3 2299.13  4960.3 2295.04
  4970.3 2289.62  4980.3 2285.17  4990.3 2278.22  4998.3 2268.68  4998.6 2268.18
  5002.1 2268.18  5002.3 2268.68  5010.3 2269.25  5020.3 2275.07  5030.3 2280.08
  5046.6 2302.31  5051.6 2300.92  5060.4 2302.57  5070.4 2303.46  5090.4 2303.78
  5110.4 2303.12  5160.4 2304.74  5210.5 2307.96  5220.5 2307.86  5262.8 2310.21
#Mann=5,-1,0
  4778.8    0.07       0  4832.5    0.16       0  4836.6    0.07       0
  4998.3    0.07       0  5002.3    0.07       0
Bank Sta=4998.3,5002.3
Exp/Cntr=0.3,0.1

Type RM Length L Ch R = 1,1006,269,269,269
BEGIN DESCRIPTION:
UCFB HW Trib 22 2.0
END DESCRIPTION:
XS GIS Cut Line= 3
      1279997.60      6945302.77      1280155.00      6945288.00
      1280379.59      6945259.36
#Sta/Elev= 30
  4837.1 2294.73  4864.6 2294.68  4884.7 2294.24  4914.8 2295.10  4934.9 2294.22
  4945.8 2294.87  4955.0 2280.68  4965.1 2269.23  4973.1 2266.46  4973.3 2265.96
  4976.8 2265.96  4977.1 2266.46  4985.1 2273.54  4992.7 2278.75  5005.3 2278.68
  5015.3 2277.75  5025.4 2275.93  5032.6 2278.22  5037.6 2282.56  5065.8 2284.31
  5075.8 2287.24  5085.9 2292.66  5096.0 2295.92  5106.1 2297.05  5112.4 2298.33
  5156.5 2300.88  5186.7 2303.11  5192.3 2303.10  5197.3 2304.22  5221.6 2305.38
#Mann=3,-1,0
  4837.1    0.07       0  4973.1    0.07       0  4977.1    0.07       0
Bank Sta=4973.1,4977.1
Exp/Cntr=0.3,0.1

Type RM Length L Ch R = 1,737,213,213,213
BEGIN DESCRIPTION:
UCFB HW Trib 22 1.5
END DESCRIPTION:
XS GIS Cut Line= 2
      1280053.49      6945540.04      1280405.20      6945513.66
#Sta/Elev= 30
  4797.5 2288.73  4819.1 2288.18  4849.2 2288.54  4887.9 2287.69  4893.0 2288.00
  4909.3 2287.80  4919.4 2288.48  4939.4 2285.97  4959.5 2285.74  4969.5 2282.11
  4979.5 2272.46  4987.5 2264.11  4987.8 2263.61  4991.3 2263.61  4991.5 2264.11
  4999.6 2265.39  5009.6 2270.06  5019.6 2271.42  5025.0 2269.71  5030.0 2273.51
  5039.7 2275.61  5049.7 2282.10  5059.7 2284.66  5069.8 2288.38  5079.8 2288.86
  5089.8 2289.97  5099.9 2293.16  5109.9 2294.04  5119.9 2293.63  5150.2 2294.29
#Mann=3,-1,0
  4797.5    0.07       0  4987.5    0.07       0  4991.5    0.07       0
Bank Sta=4987.5,4991.5
Exp/Cntr=0.3,0.1

Type RM Length L Ch R = 1,524,238,238,238
BEGIN DESCRIPTION:
UCFB HW Trib 22 1.0
END DESCRIPTION:
XS GIS Cut Line= 3
      1280082.29      6945728.55      1280255.00      6945738.00
      1280371.58      6945734.66
#Sta/Elev= 30
  4827.0 2282.81  4849.7 2282.18  4859.8 2279.95  4869.8 2280.92  4879.8 2280.74
  4899.8 2276.73  4905.1 2275.46  4906.7 2275.08  4911.7 2277.29  4919.9 2274.23
  4931.6 2272.96  4939.9 2272.36  4949.9 2270.93  4959.9 2268.15  4969.9 2263.61
  4977.9 2261.31  4978.2 2260.81  4981.7 2260.81  4981.9 2261.31  4997.5 2262.49
  5010.0 2262.73  5020.0 2262.53  5030.0 2263.37  5040.0 2266.11  5050.0 2270.60
  5060.0 2273.27  5070.0 2279.24  5080.0 2282.00  5110.0 2282.37  5116.6 2282.14
#Mann=5,-1,0
  4827.0    0.07       0  4905.1    0.16       0  4931.6    0.07       0
  4977.9    0.07       0  4981.9    0.07       0
Bank Sta=4977.9,4981.9
Exp/Cntr=0.3,0.1

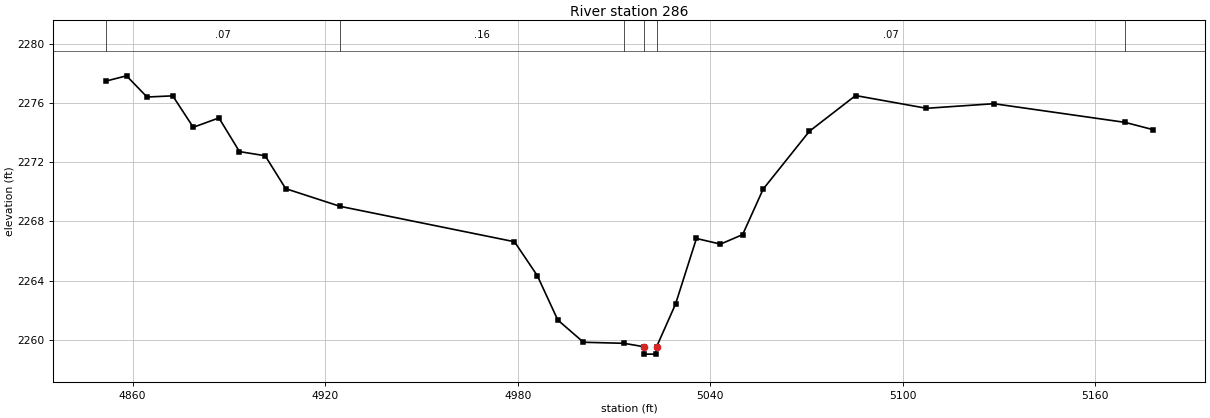
Type RM Length L Ch R = 1,286,0,0,0
BEGIN DESCRIPTION:
UCFB HW Trib 22 0.5
END DESCRIPTION:
XS GIS Cut Line= 2
      1280075.73      6945858.29      1280329.97      6946062.98
#Sta/Elev= 30
  4851.6 2277.46  4858.1 2277.82  4864.5 2276.39  4872.5 2276.47  4878.9 2274.35
  4886.9 2274.98  4893.3 2272.71  4901.3 2272.43  4907.7 2270.21  4924.6 2269.02
  4979.0 2266.63  4986.1 2264.35  4992.5 2261.35  5000.5 2259.85  5013.1 2259.78
  5019.3 2259.55  5019.5 2259.05  5023.0 2259.05  5023.3 2259.55  5029.2 2262.43
  5035.7 2266.85  5043.2 2266.47  5050.1 2267.11  5056.5 2270.18  5070.9 2274.08
  5085.3 2276.49  5107.4 2275.63  5128.4 2275.94  5169.3 2274.68  5178.0 2274.19
#Mann=6,-1,0
  4851.6    0.07       0  4924.6    0.16       0  5013.1    0.07       0
  5019.3    0.07       0  5023.3    0.07       0  5169.3   0.035       0
Bank Sta=5019.3,5023.3
Exp/Cntr=0.3,0.1

Chan Stop Cuts=-1