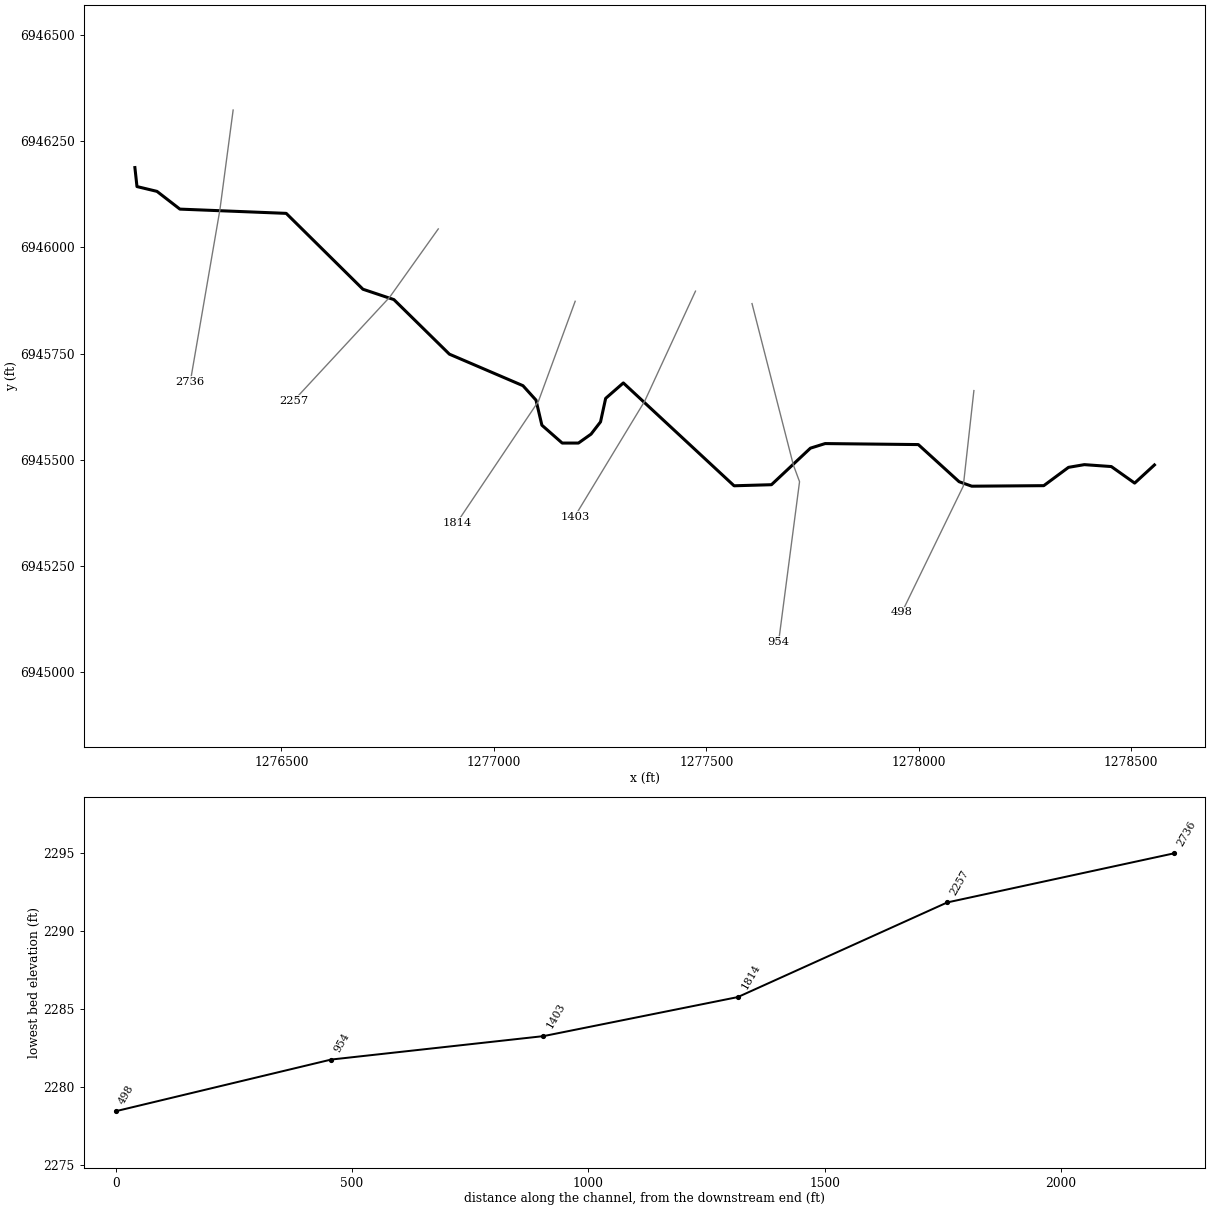
--- UCFB HW Trib 23.prj (project) ---

Proj Title=UCFB HW Trib 23 Base Level Engineering
Current Plan=p01
Default Exp/Contr=0.3,0.1
English Units
Geom File=g01
Flow File=f01
Plan File=p01
BEGIN DESCRIPTION:
UCFB HW Trib 23
END DESCRIPTION:

--- UCFB HW Trib 23.p01 (plan) ---

Plan Title=Multiple Run
Short Identifier=Multiple
Geom File=g01
Flow File=f01
Subcritical Flow
K Sum by GR= 0
Std Step Tol= 0.01
Critical Tol= 0.01
Num of Std Step Trials= 20
Max Error Tol= 0.3
Flow Tol Ratio= 0.001
Split Flow NTrial= 30
Split Flow Tol= 0.02
Split Flow Ratio= 0.02
Log Output Level= 0
Friction Slope Method= 1
Unsteady Friction Slope Method= 2
Unsteady Bridges Friction Slope Method= 1
Parabolic Critical Depth
Global Vel Dist=  1 , 1 , 1
Global Log Level= 0
CheckData=True
Encroach Param= -1, 0, 0, 0
BEGIN DESCRIPTION:
Multiple Run
END DESCRIPTION:

--- UCFB HW Trib 23.f01 (steady flow) ---

Flow Title=Multiple
Number of Profiles=7
Profile Names=10-year,25-year,50-year,1pct_min,100-year,1pct_plu,500-year
River Rch & RM= UCFB HW Trib 23,Reach-1,2736
     203     284     351     217     433     863     664
Boundary for River Rch & Prof#=UCFB HW Trib 23,Reach-1,1
Up Type=0
Dn Type=3
Dn Slope=0.005
Boundary for River Rch & Prof#=UCFB HW Trib 23,Reach-1,2
Up Type=0
Dn Type=3
Dn Slope=0.005
Boundary for River Rch & Prof#=UCFB HW Trib 23,Reach-1,3
Up Type=0
Dn Type=3
Dn Slope=0.005
Boundary for River Rch & Prof#=UCFB HW Trib 23,Reach-1,4
Up Type=0
Dn Type=3
Dn Slope=0.005
Boundary for River Rch & Prof#=UCFB HW Trib 23,Reach-1,5
Up Type=0
Dn Type=3
Dn Slope=0.005
Boundary for River Rch & Prof#=UCFB HW Trib 23,Reach-1,6
Up Type=0
Dn Type=3
Dn Slope=0.005
Boundary for River Rch & Prof#=UCFB HW Trib 23,Reach-1,7
Up Type=0
Dn Type=3
Dn Slope=0.005

--- UCFB HW Trib 23.g01 (geometry) ---

Geom Title=Existing Conditions

River Reach=UCFB HW Trib 23,Reach-1
Reach XY= 30
      1276155.00      6946188.00      1276159.90      6946143.28
      1276207.00      6946131.96      1276260.90      6946090.21
      1276511.19      6946080.19      1276691.79      6945901.63
      1276764.68      6945877.22      1276895.32      6945748.77
      1277068.56      6945674.52      1277099.24      6945640.51
      1277113.05      6945581.59      1277160.91      6945539.49
      1277199.09      6945539.49      1277228.83      6945560.56
      1277251.11      6945589.43      1277263.17      6945644.69
      1277304.79      6945681.02      1277565.48      6945438.93
      1277653.50      6945441.47      1277745.21      6945527.50
      1277779.88      6945538.29      1277999.14      6945535.93
      1278095.21      6945448.50      1278124.99      6945437.96
      1278294.50      6945439.22      1278352.69      6945482.31
      1278389.94      6945488.70      1278453.52      6945484.18
      1278508.45      6945445.24      1278555.00      6945488.00

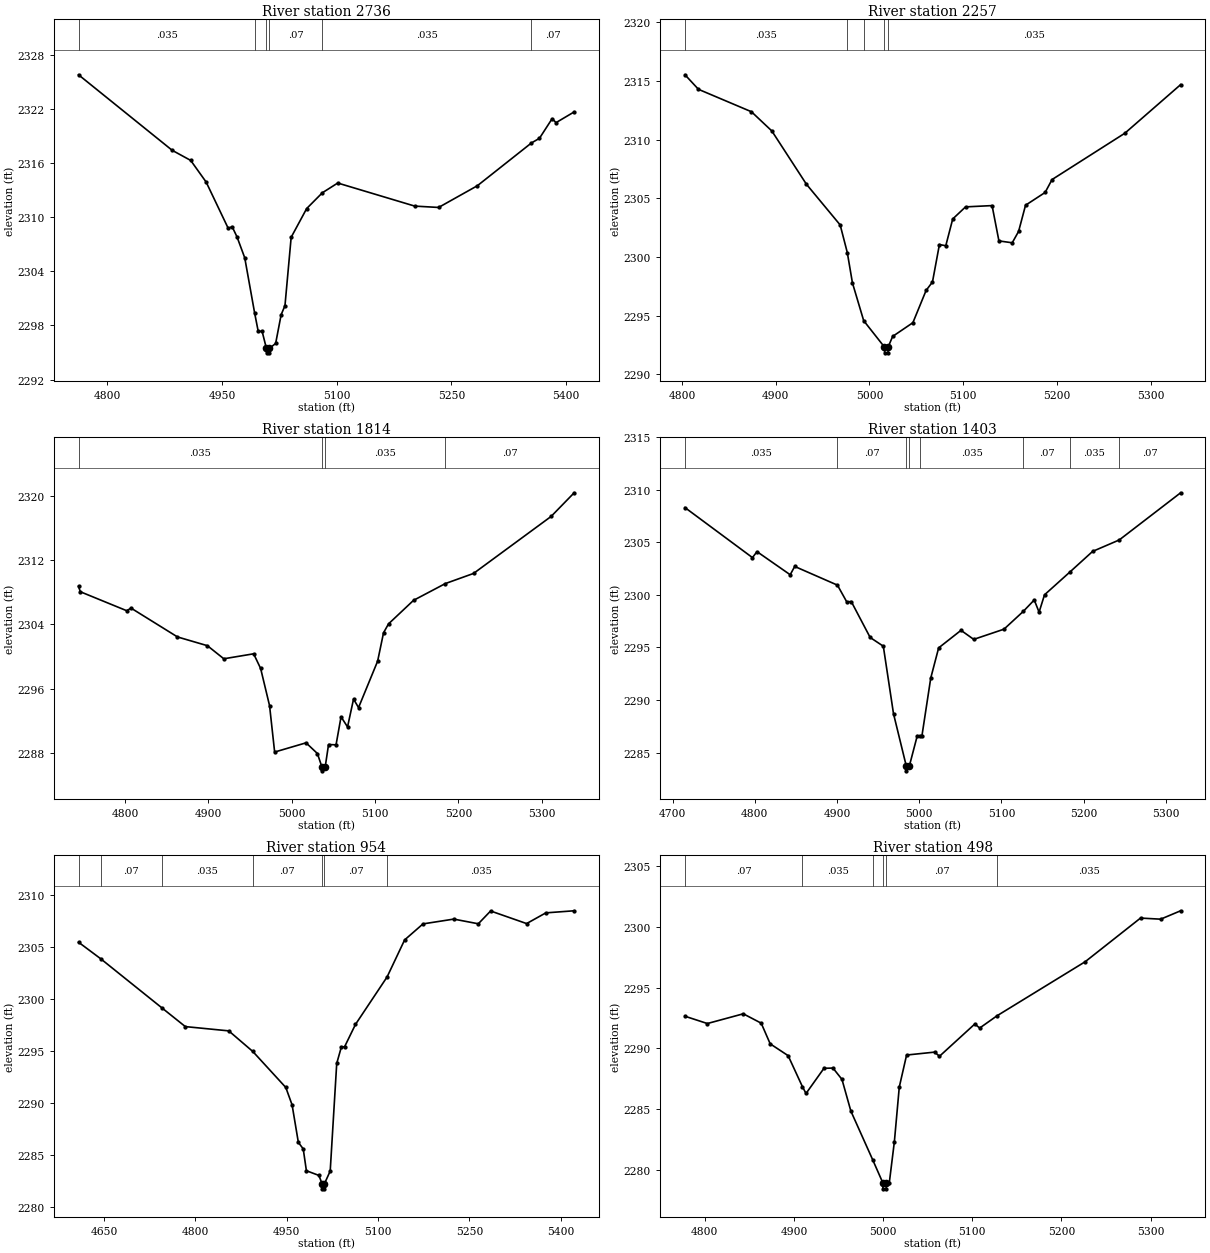
Type RM Length L Ch R = 1,2736,479,479,479
BEGIN DESCRIPTION:
UCFB HW Trib 23 6.0
END DESCRIPTION:
XS GIS Cut Line= 3
      1276386.27      6946323.46      1276355.00      6946088.00
      1276285.36      6945683.28
#Sta/Elev= 30
  4762.4 2325.81  4884.9 2317.43  4909.1 2316.31  4929.3 2313.91  4958.2 2308.77
  4963.3 2308.96  4969.7 2307.82  4979.8 2305.50  4992.7 2299.39  4997.4 2297.35
  5002.5 2297.35  5008.1 2295.46  5008.3 2294.96  5011.8 2294.96  5012.1 2295.46
  5020.2 2296.00  5027.4 2299.19  5032.4 2300.20  5040.5 2307.78  5060.8 2310.97
  5081.3 2312.72  5101.4 2313.80  5202.1 2311.24  5233.3 2311.09  5284.0 2313.50
  5354.8 2318.25  5365.2 2318.76  5381.8 2320.94  5386.9 2320.50  5410.6 2321.69
#Mann=6,-1,0
  4762.4   0.035       0  4992.7    0.07       0  5008.1    0.07       0
  5012.1    0.07       0  5081.3   0.035       0  5354.8    0.07       0
Bank Sta=5008.1,5012.1
Exp/Cntr=0.3,0.1

Type RM Length L Ch R = 1,2257,443,443,443
BEGIN DESCRIPTION:
UCFB HW Trib 23 5.0
END DESCRIPTION:
XS GIS Cut Line= 3
      1276869.14      6946043.56      1276755.00      6945883.24
      1276529.23      6945639.68
#Sta/Elev= 30
  4803.2 2315.52  4817.6 2314.28  4874.1 2312.37  4895.9 2310.73  4932.8 2306.19
  4968.8 2302.72  4976.4 2300.37  4981.9 2297.78  4993.9 2294.56  5016.0 2292.32
  5016.3 2291.82  5019.8 2291.82  5020.0 2292.32  5024.8 2293.22  5046.4 2294.39
  5060.5 2297.14  5067.3 2297.86  5074.7 2301.05  5081.5 2300.95  5088.9 2303.23
  5102.6 2304.26  5130.9 2304.37  5138.2 2301.36  5152.4 2301.20  5159.2 2302.17
  5166.6 2304.40  5187.5 2305.49  5194.9 2306.59  5272.6 2310.54  5332.1 2314.68
#Mann=5,-1,0
  4803.2   0.035       0  4976.4    0.07       0  4993.9   0.035       0
  5016.0   0.035       0  5020.0   0.035       0
Bank Sta=5016,5020
Exp/Cntr=0.3,0.1

Type RM Length L Ch R = 1,1814,411,411,411
BEGIN DESCRIPTION:
UCFB HW Trib 23 4.0
END DESCRIPTION:
XS GIS Cut Line= 3
      1277191.41      6945873.23      1277105.00      6945638.00
      1276913.11      6945352.13
#Sta/Elev= 30
  4744.1 2308.74  4746.3 2308.07  4801.9 2305.71  4807.2 2306.03  4862.9 2302.44
  4898.8 2301.35  4918.5 2299.72  4954.3 2300.34  4962.7 2298.51  4973.4 2293.88
  4979.5 2288.10  5017.2 2289.25  5030.8 2287.92  5036.2 2286.26  5036.4 2285.76
  5040.2 2286.26  5044.2 2289.04  5053.2 2289.00  5059.2 2292.49  5067.0 2291.23
  5074.2 2294.70  5080.2 2293.64  5103.1 2299.42  5110.2 2302.96  5116.2 2304.07
  5146.2 2307.00  5184.4 2309.09  5218.2 2310.35  5311.3 2317.45  5339.0 2320.40
#Mann=4,-1,0
  4744.1   0.035       0  5036.2   0.035       0  5040.2   0.035       0
  5184.4    0.07       0
Bank Sta=5036.2,5040.2
Exp/Cntr=0.3,0.1

Type RM Length L Ch R = 1,1403,449,449,449
BEGIN DESCRIPTION:
UCFB HW Trib 23 3.0
END DESCRIPTION:
XS GIS Cut Line= 3
      1277474.61      6945897.10      1277355.00      6945638.00
      1277190.29      6945366.42
#Sta/Elev= 30
  4715.0 2308.31  4797.1 2303.55  4802.6 2304.12  4843.0 2301.92  4848.5 2302.71
  4900.5 2300.93  4911.8 2299.34  4917.3 2299.37  4940.3 2295.95  4956.3 2295.12
  4968.7 2288.69  4984.1 2283.76  4984.4 2283.26  4988.1 2283.76  4997.6 2286.60
  5000.8 2286.60  5003.3 2286.60  5014.0 2292.09  5023.6 2294.96  5050.8 2296.63
  5066.3 2295.77  5103.1 2296.74  5126.8 2298.45  5139.9 2299.52  5145.8 2298.36
  5152.4 2300.01  5183.0 2302.16  5210.9 2304.14  5243.3 2305.23  5318.0 2309.72
#Mann=8,-1,0
  4715.0   0.035       0  4900.5    0.07       0  4984.1    0.07       0
  4988.1    0.07       0  5000.8   0.035       0  5126.8    0.07       0
  5183.0   0.035       0  5243.3    0.07       0
Bank Sta=4984.1,4988.1
Exp/Cntr=0.3,0.1

Type RM Length L Ch R = 1,954,456,456,456
BEGIN DESCRIPTION:
UCFB HW Trib 23 2.0
END DESCRIPTION:
XS GIS Cut Line= 4
      1277607.70      6945867.75      1277705.00      6945488.00
      1277719.58      6945448.59      1277670.35      6945071.93
#Sta/Elev= 30
  4608.0 2305.46  4644.2 2303.88  4744.5 2299.17  4783.4 2297.35  4854.7 2296.94
  4894.2 2294.96  4948.4 2291.50  4958.7 2289.83  4969.0 2286.22  4977.0 2285.60
  4982.2 2283.50  5002.7 2283.05  5007.9 2282.26  5008.1 2281.76  5011.6 2281.76
  5011.9 2282.26  5021.3 2283.47  5032.0 2293.81  5039.7 2295.41  5044.9 2295.41
  5062.8 2297.56  5114.7 2302.12  5143.5 2305.68  5173.7 2307.22  5224.2 2307.68
  5264.5 2307.23  5284.7 2308.46  5343.8 2307.25  5375.4 2308.28  5421.9 2308.48
#Mann=7,-1,0
  4608.0   0.035       0  4644.2    0.07       0  4744.5   0.035       0
  4894.2    0.07       0  5007.9    0.07       0  5011.9    0.07       0
  5114.7   0.035       0
Bank Sta=5007.9,5011.9
Exp/Cntr=0.3,0.1

Type RM Length L Ch R = 1,498,0,0,0
BEGIN DESCRIPTION:
UCFB HW Trib 23 1.0
END DESCRIPTION:
XS GIS Cut Line= 3
      1278130.00      6945662.99      1278105.00      6945438.00
      1277960.78      6945141.60
#Sta/Elev= 30
  4777.7 2292.64  4802.8 2292.04  4843.1 2292.84  4863.2 2292.07  4873.3 2290.37
  4893.4 2289.40  4909.5 2286.84  4913.5 2286.29  4933.6 2288.36  4943.7 2288.38
  4953.8 2287.45  4963.8 2284.84  4988.2 2280.85  4999.6 2278.95  4999.8 2278.45
  5003.3 2278.45  5003.6 2278.95  5006.9 2278.95  5012.6 2282.33  5018.1 2286.82
  5026.3 2289.45  5057.7 2289.69  5063.2 2289.35  5102.8 2292.00  5108.3 2291.67
  5127.8 2292.68  5226.6 2297.12  5288.7 2300.71  5311.3 2300.62  5333.7 2301.31
#Mann=6,-1,0
  4777.7    0.07       0  4909.5   0.035       0  4988.2    0.07       0
  4999.6    0.07       0  5003.6    0.07       0  5127.8   0.035       0
Bank Sta=4999.6,5003.6
Exp/Cntr=0.3,0.1

Chan Stop Cuts=-1