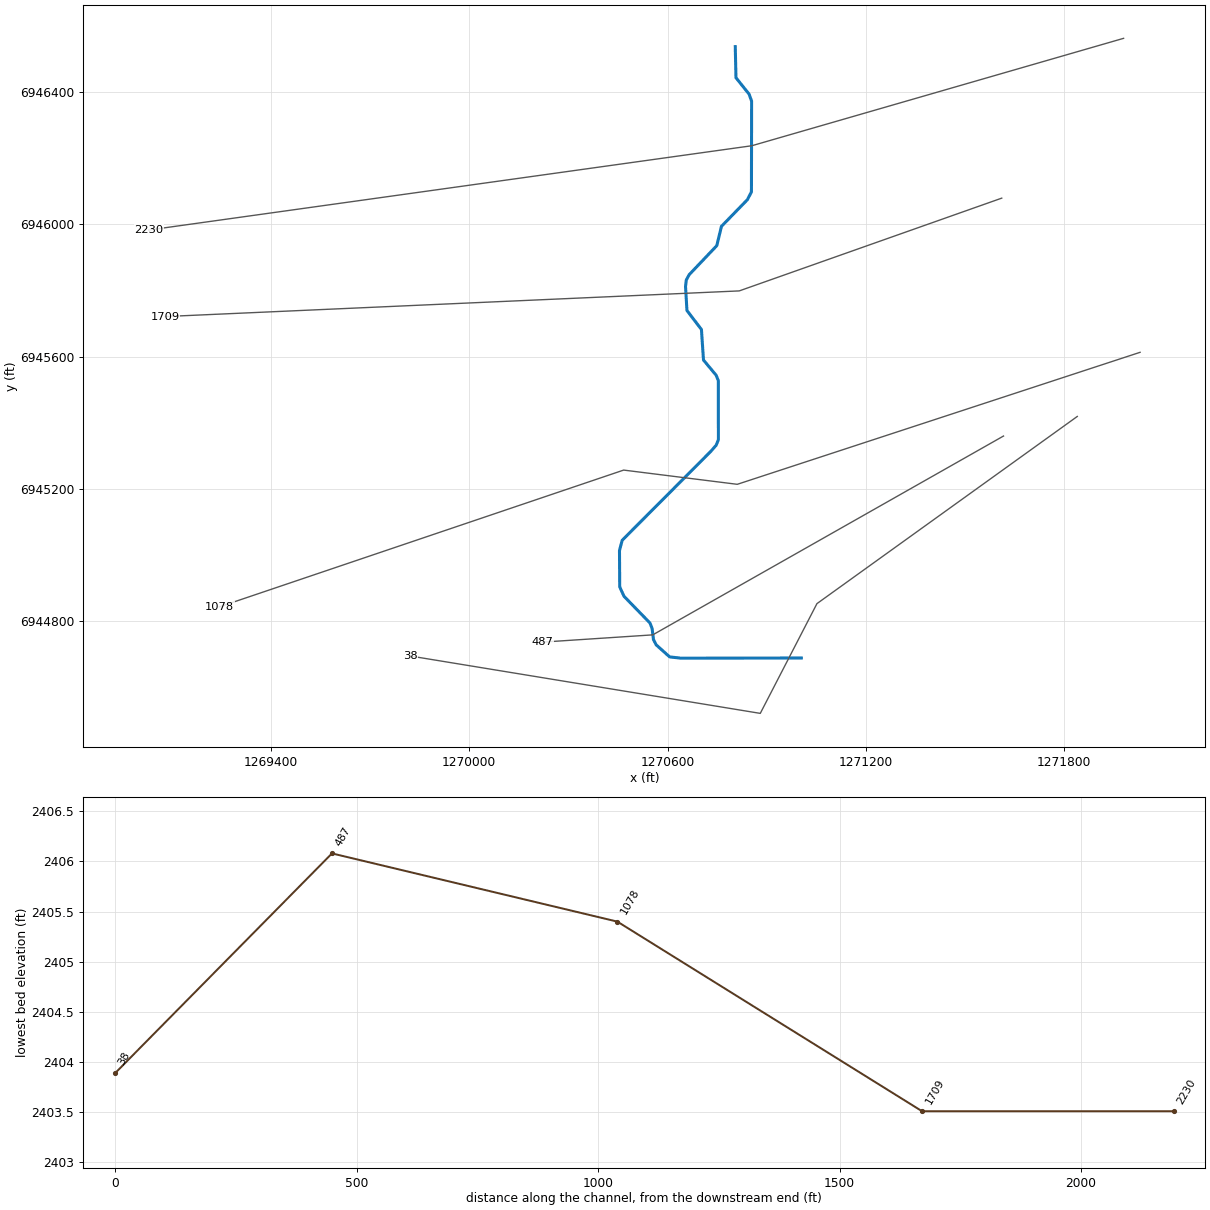
--- UCFB HW Trib 24-01.prj (project) ---

Proj Title=UCFB HW Trib 24-01 Base Level Engineering
Current Plan=p01
Default Exp/Contr=0.3,0.1
English Units
Geom File=g01
Flow File=f01
Plan File=p01
BEGIN DESCRIPTION:
UCFB HW Trib 24-01
END DESCRIPTION:

--- UCFB HW Trib 24-01.p01 (plan) ---

Plan Title=Multiple Run
Short Identifier=Multiple
Geom File=g01
Flow File=f01
Subcritical Flow
K Sum by GR= 0
Std Step Tol= 0.01
Critical Tol= 0.01
Num of Std Step Trials= 20
Max Error Tol= 0.3
Flow Tol Ratio= 0.001
Split Flow NTrial= 30
Split Flow Tol= 0.02
Split Flow Ratio= 0.02
Log Output Level= 0
Friction Slope Method= 1
Unsteady Friction Slope Method= 2
Unsteady Bridges Friction Slope Method= 1
Parabolic Critical Depth
Global Vel Dist=  1 , 1 , 1
Global Log Level= 0
CheckData=True
Encroach Param= -1, 0, 0, 0
BEGIN DESCRIPTION:
Multiple Run
END DESCRIPTION:

--- UCFB HW Trib 24-01.f01 (steady flow) ---

Flow Title=Multiple
Number of Profiles=7
Profile Names=10-year,25-year,50-year,1pct_min,100-year,1pct_plu,500-year
River Rch & RM= UCFB HW Trib 24-,Reach-1,2230
     230     318     388     236     471     940     702
River Rch & RM= UCFB HW Trib 24-,Reach-1,38
     694    1022    1308     829    1654    3301    2685
Boundary for River Rch & Prof#=UCFB HW Trib 24-,Reach-1,1
Up Type=0
Dn Type=3
Dn Slope=0.005
Boundary for River Rch & Prof#=UCFB HW Trib 24-,Reach-1,2
Up Type=0
Dn Type=3
Dn Slope=0.005
Boundary for River Rch & Prof#=UCFB HW Trib 24-,Reach-1,3
Up Type=0
Dn Type=3
Dn Slope=0.005
Boundary for River Rch & Prof#=UCFB HW Trib 24-,Reach-1,4
Up Type=0
Dn Type=3
Dn Slope=0.005
Boundary for River Rch & Prof#=UCFB HW Trib 24-,Reach-1,5
Up Type=0
Dn Type=3
Dn Slope=0.005
Boundary for River Rch & Prof#=UCFB HW Trib 24-,Reach-1,6
Up Type=0
Dn Type=3
Dn Slope=0.005
Boundary for River Rch & Prof#=UCFB HW Trib 24-,Reach-1,7
Up Type=0
Dn Type=3
Dn Slope=0.005

--- UCFB HW Trib 24-01.g01 (geometry) ---

Geom Title=Existing Conditions

River Reach=UCFB HW Trib 24-,Reach-1
Reach XY= 30
      1270805.00      6946538.00      1270807.10      6946443.87
      1270846.90      6946394.07      1270854.49      6946372.79
      1270853.95      6946098.44      1270841.60      6946074.69
      1270763.18      6945994.04      1270749.13      6945935.72
      1270665.46      6945847.78      1270656.97      6945832.11
      1270654.51      6945813.04      1270658.70      6945739.60
      1270702.64      6945682.03      1270708.86      6945589.60
      1270746.86      6945544.06      1270753.78      6945527.50
      1270753.95      6945348.43      1270747.19      6945331.81
      1270732.14      6945314.47      1270462.81      6945044.19
      1270454.68      6945013.11      1270455.37      6944903.17
      1270468.39      6944874.69      1270546.81      6944794.02
      1270553.42      6944777.31      1270557.45      6944743.84
      1270565.62      6944727.94      1270606.25      6944691.45
      1270639.74      6944687.49      1271005.00      6944688.00

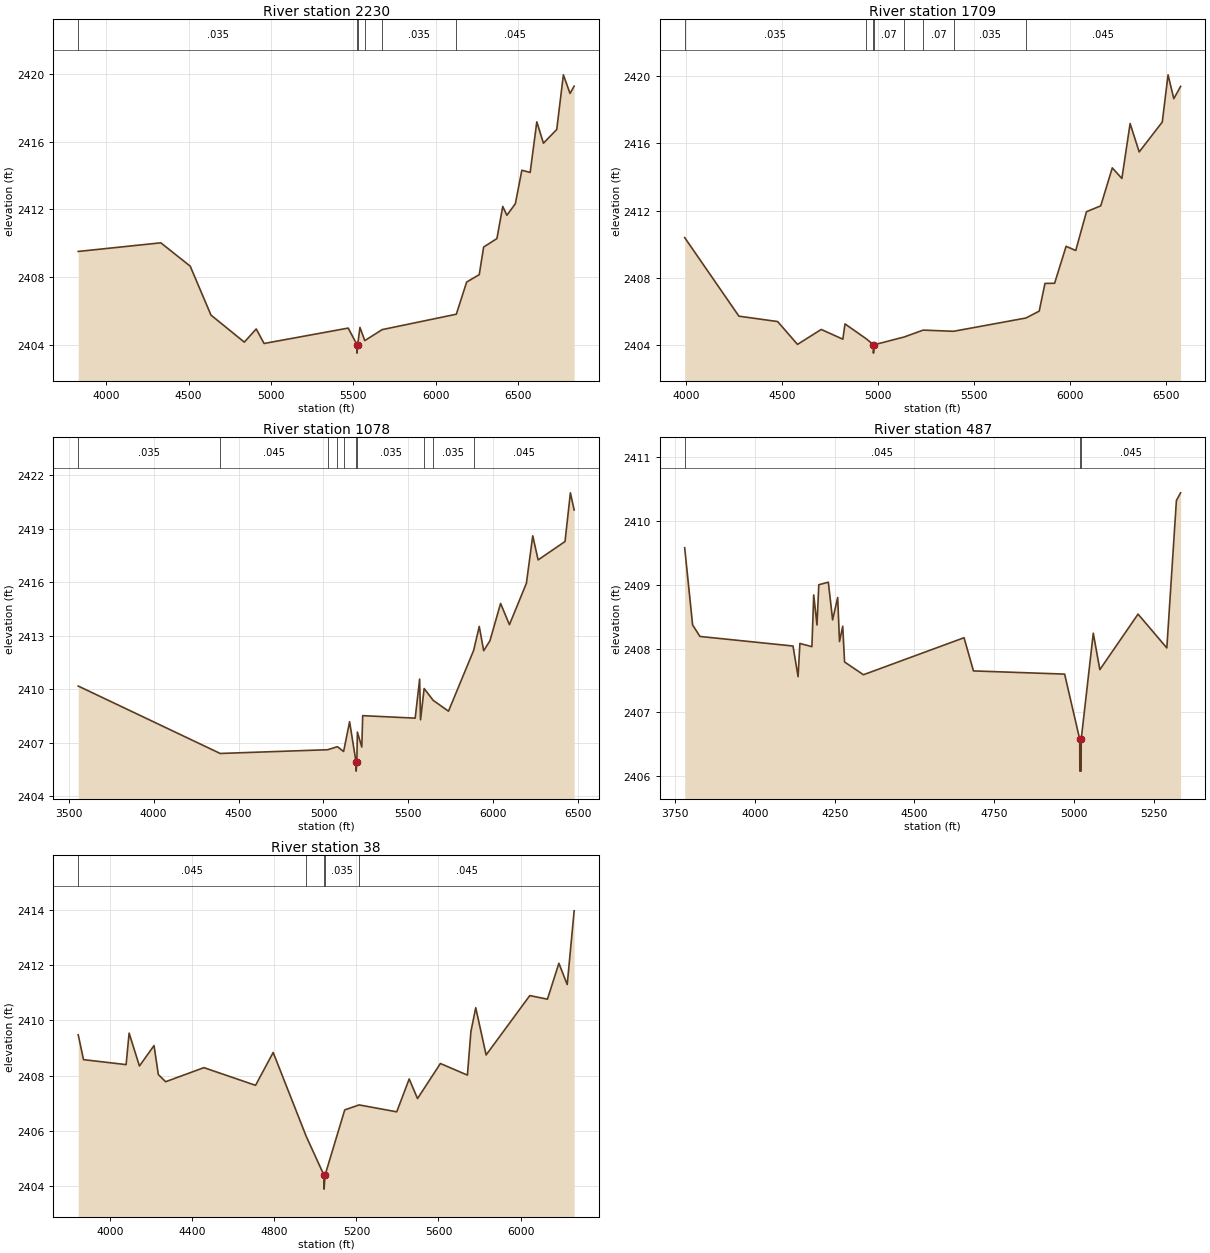
Type RM Length L Ch R = 1,2230,521,521,521
BEGIN DESCRIPTION:
UCFB HW Trib 24-01 7.0
END DESCRIPTION:
XS GIS Cut Line= 3
      1271980.02      6946563.01      1270855.00      6946238.00
      1269030.26      6945982.97
#Sta/Elev= 30
  3829.0 2409.52  4331.1 2410.03  4509.6 2408.65  4635.7 2405.76  4838.3 2404.16
  4910.7 2404.94  4958.4 2404.08  5469.6 2404.99  5522.9 2404.01  5523.2 2403.51
  5527.2 2404.01  5541.0 2405.03  5570.4 2404.25  5676.0 2404.90  6126.5 2405.81
  6189.3 2407.71  6265.8 2408.15  6292.5 2409.78  6373.2 2410.28  6408.7 2412.18
  6433.8 2411.66  6485.2 2412.34  6524.7 2414.32  6575.2 2414.19  6615.6 2417.18
  6656.0 2415.92  6736.7 2416.73  6777.1 2419.96  6817.5 2418.86  6842.5 2419.29
#Mann=6,-1,0
  3829.0   0.035       0  5522.9   0.035       0  5527.2   0.035       0
  5570.4    0.07       0  5676.0   0.035       0  6126.5   0.045       0
Bank Sta=5522.9,5527.2
Exp/Cntr=0.3,0.1

Type RM Length L Ch R = 1,1709,631,631,631
BEGIN DESCRIPTION:
UCFB HW Trib 24-01 6.4
END DESCRIPTION:
XS GIS Cut Line= 3
      1271611.27      6946079.46      1270817.03      6945798.78
      1269079.64      6945721.17
#Sta/Elev= 30
  3994.6 2410.39  4277.0 2405.71  4478.5 2405.39  4581.8 2404.03  4705.4 2404.92
  4817.9 2404.34  4829.1 2405.25  4939.0 2404.37  4977.0 2404.01  4977.2 2403.51
  4981.3 2404.01  5137.0 2404.47  5236.0 2404.88  5394.3 2404.81  5770.7 2405.60
  5840.0 2406.01  5870.0 2407.66  5920.1 2407.67  5980.1 2409.87  6030.2 2409.62
  6086.1 2411.93  6160.3 2412.28  6220.4 2414.54  6270.4 2413.91  6313.2 2417.18
  6360.5 2415.49  6480.6 2417.27  6510.7 2420.08  6540.7 2418.66  6576.1 2419.39
#Mann=8,-1,0
  3994.6   0.035       0  4939.0    0.07       0  4977.0    0.07       0
  4981.3    0.07       0  5137.0   0.035       0  5236.0    0.07       0
  5394.3   0.035       0  5770.7   0.045       0
Bank Sta=4977,4981.3
Exp/Cntr=0.3,0.1

Type RM Length L Ch R = 1,1078,591,591,591
BEGIN DESCRIPTION:
UCFB HW Trib 24-01 6.2
END DESCRIPTION:
XS GIS Cut Line= 4
      1272029.96      6945612.99      1270811.05      6945213.57
      1270467.29      6945256.61      1269244.02      6944842.78
#Sta/Elev= 30
  3555.7 2410.17  4391.8 2406.39  5025.3 2406.60  5082.1 2406.77  5118.6 2406.50
  5153.8 2408.17  5192.0 2405.90  5192.4 2405.40  5196.6 2405.90  5199.6 2407.59
  5225.7 2406.75  5231.0 2408.51  5540.1 2408.37  5566.3 2410.56  5571.6 2408.28
  5592.8 2410.03  5645.8 2409.37  5736.2 2408.76  5884.4 2412.17  5917.4 2413.51
  5943.5 2412.15  5980.3 2412.71  6043.1 2414.80  6095.1 2413.61  6195.0 2415.93
  6232.4 2418.59  6264.0 2417.24  6422.4 2418.27  6454.1 2421.00  6476.2 2420.04
#Mann=10,-1,0
  3555.7   0.035       0  4391.8   0.045       0  5025.3   0.035       0
  5082.1    0.07       0  5118.6   0.035       0  5192.0   0.045       0
  5196.6   0.035       0  5592.8   0.045       0  5645.8   0.035       0
  5884.4   0.045       0
Bank Sta=5192,5196.6
Exp/Cntr=0.3,0.1

Type RM Length L Ch R = 1,487,449,449,449
BEGIN DESCRIPTION:
UCFB HW Trib 24-01 6.0
END DESCRIPTION:
XS GIS Cut Line= 3
      1271616.67      6945359.69      1270555.34      6944758.04
      1270221.86      6944736.08
#Sta/Elev= 30
  3780.0 2409.58  3804.9 2408.37  3827.9 2408.19  4119.5 2408.04  4135.4 2407.56
  4141.1 2408.08  4178.7 2408.03  4184.4 2408.84  4194.6 2408.37  4200.3 2409.00
  4230.2 2409.04  4243.6 2408.45  4259.5 2408.80  4265.2 2408.11  4275.3 2408.35
  4281.1 2407.79  4340.2 2407.59  4655.5 2408.17  4685.0 2407.65  4970.7 2407.60
  5018.0 2406.58  5018.4 2406.08  5022.4 2406.08  5022.7 2406.58  5060.5 2408.24
  5081.1 2407.67  5200.8 2408.54  5291.0 2408.01  5321.0 2410.32  5334.2 2410.44
#Mann=3,-1,0
  3780.0   0.045       0  5018.0   0.045       0  5022.7   0.045       0
Bank Sta=5018,5022.7
Exp/Cntr=0.3,0.1

Type RM Length L Ch R = 1,38,0,0,0
BEGIN DESCRIPTION:
UCFB HW Trib 24-01 5.0
END DESCRIPTION:
XS GIS Cut Line= 4
      1271839.90      6945418.92      1271052.12      6944852.50
      1270880.68      6944520.47      1269821.66      6944694.08
#Sta/Elev= 30
  3844.1 2409.48  3870.0 2408.58  4077.5 2408.40  4092.2 2409.54  4142.5 2408.35
  4213.7 2409.09  4234.6 2408.04  4270.2 2407.78  4456.8 2408.29  4708.4 2407.65
  4794.4 2408.84  4955.5 2405.80  5042.2 2404.39  5042.5 2403.89  5046.9 2404.39
  5143.1 2406.76  5213.4 2406.94  5396.5 2406.69  5457.3 2407.88  5497.8 2407.17
  5609.3 2408.44  5741.0 2408.02  5758.1 2409.60  5781.5 2410.46  5832.2 2408.75
  6045.0 2410.90  6131.0 2410.77  6186.9 2412.07  6227.4 2411.30  6261.2 2413.97
#Mann=5,-1,0
  3844.1   0.045       0  4955.5   0.035       0  5042.2   0.035       0
  5046.9   0.035       0  5213.4   0.045       0
Bank Sta=5042.2,5046.9
Exp/Cntr=0.3,0.1

Chan Stop Cuts=-1