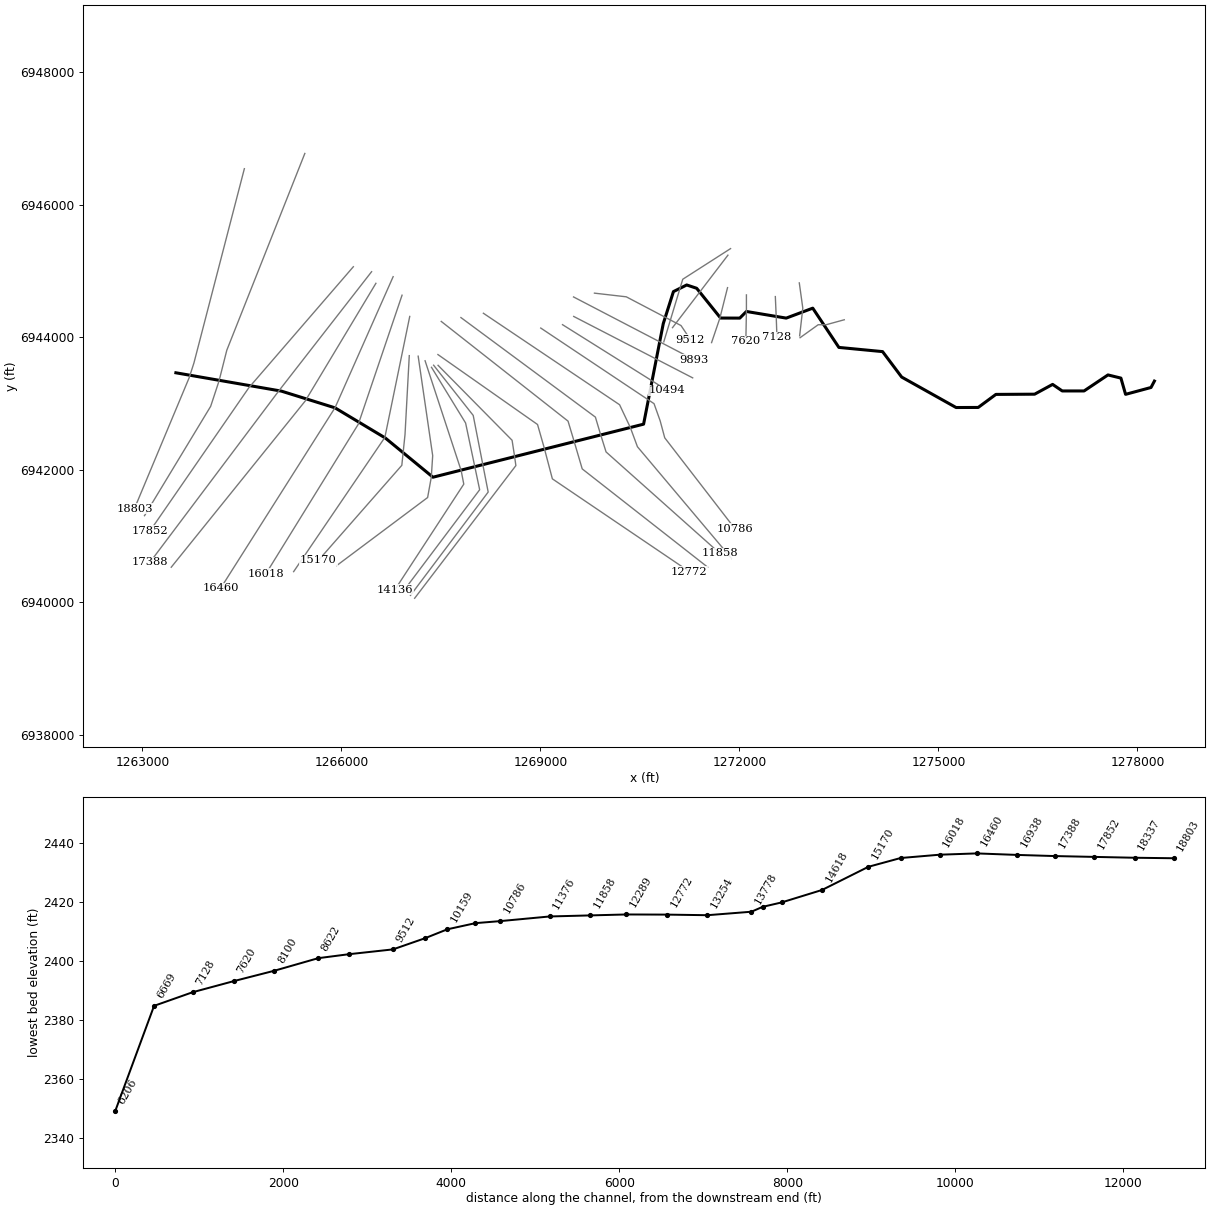
--- UCFB HW Trib 24.prj (project) ---

Proj Title=UCFB HW Trib 24 Base Level Engineering
Current Plan=p01
Default Exp/Contr=0.3,0.1
English Units
Geom File=g01
Flow File=f01
Plan File=p01
BEGIN DESCRIPTION:
UCFB HW Trib 24
END DESCRIPTION:

--- UCFB HW Trib 24.p01 (plan) ---

Plan Title=Multiple Run
Short Identifier=Multiple
Geom File=g01
Flow File=f01
Subcritical Flow
K Sum by GR= 0
Std Step Tol= 0.01
Critical Tol= 0.01
Num of Std Step Trials= 20
Max Error Tol= 0.3
Flow Tol Ratio= 0.001
Split Flow NTrial= 30
Split Flow Tol= 0.02
Split Flow Ratio= 0.02
Log Output Level= 0
Friction Slope Method= 1
Unsteady Friction Slope Method= 2
Unsteady Bridges Friction Slope Method= 1
Parabolic Critical Depth
Global Vel Dist=  1 , 1 , 1
Global Log Level= 0
CheckData=True
Encroach Param= -1, 0, 0, 0
BEGIN DESCRIPTION:
Multiple Run
END DESCRIPTION:

--- UCFB HW Trib 24.f01 (steady flow) ---

Flow Title=Multiple
Number of Profiles=7
Profile Names=10-year,25-year,50-year,1pct_min,100-year,1pct_plu,500-year
River Rch & RM= UCFB HW Trib 24,Reach-1,18803
     248     341     416     252     503    1003     744
River Rch & RM= UCFB HW Trib 24,Reach-1,11858
     338     472     582     356     710    1416    1071
River Rch & RM= UCFB HW Trib 24,Reach-1,8986
     694    1022    1308     829    1654    3301    2685
Boundary for River Rch & Prof#=UCFB HW Trib 24,Reach-1,1
Up Type=0
Dn Type=3
Dn Slope=0.005
Boundary for River Rch & Prof#=UCFB HW Trib 24,Reach-1,2
Up Type=0
Dn Type=3
Dn Slope=0.005
Boundary for River Rch & Prof#=UCFB HW Trib 24,Reach-1,3
Up Type=0
Dn Type=3
Dn Slope=0.005
Boundary for River Rch & Prof#=UCFB HW Trib 24,Reach-1,4
Up Type=0
Dn Type=3
Dn Slope=0.005
Boundary for River Rch & Prof#=UCFB HW Trib 24,Reach-1,5
Up Type=0
Dn Type=3
Dn Slope=0.005
Boundary for River Rch & Prof#=UCFB HW Trib 24,Reach-1,6
Up Type=0
Dn Type=3
Dn Slope=0.005
Boundary for River Rch & Prof#=UCFB HW Trib 24,Reach-1,7
Up Type=0
Dn Type=3
Dn Slope=0.005

--- UCFB HW Trib 24.g01 (geometry) ---

Geom Title=Existing Conditions

River Reach=UCFB HW Trib 24,Reach-1
Reach XY= 30
      1263505.00      6943463.07      1265094.50      6943186.78
      1265903.50      6942934.39      1266661.05      6942479.84
      1267380.00      6941887.59      1270555.00      6942688.00
      1270851.56      6944204.37      1271005.00      6944688.00
      1271205.00      6944788.00      1271355.00      6944738.00
      1271715.48      6944288.93      1272005.00      6944288.00
      1272105.00      6944388.00      1272705.00      6944288.00
      1273105.00      6944438.00      1273498.79      6943845.76
      1274157.43      6943782.48      1274445.21      6943398.52
      1275265.44      6942939.05      1275599.07      6942940.24
      1275865.43      6943136.95      1276449.07      6943140.24
      1276720.41      6943287.98      1276865.44      6943189.06
      1277194.57      6943189.05      1277554.90      6943430.67
      1277750.00      6943382.99      1277820.22      6943137.83
      1278203.74      6943241.37      1278255.00      6943338.00

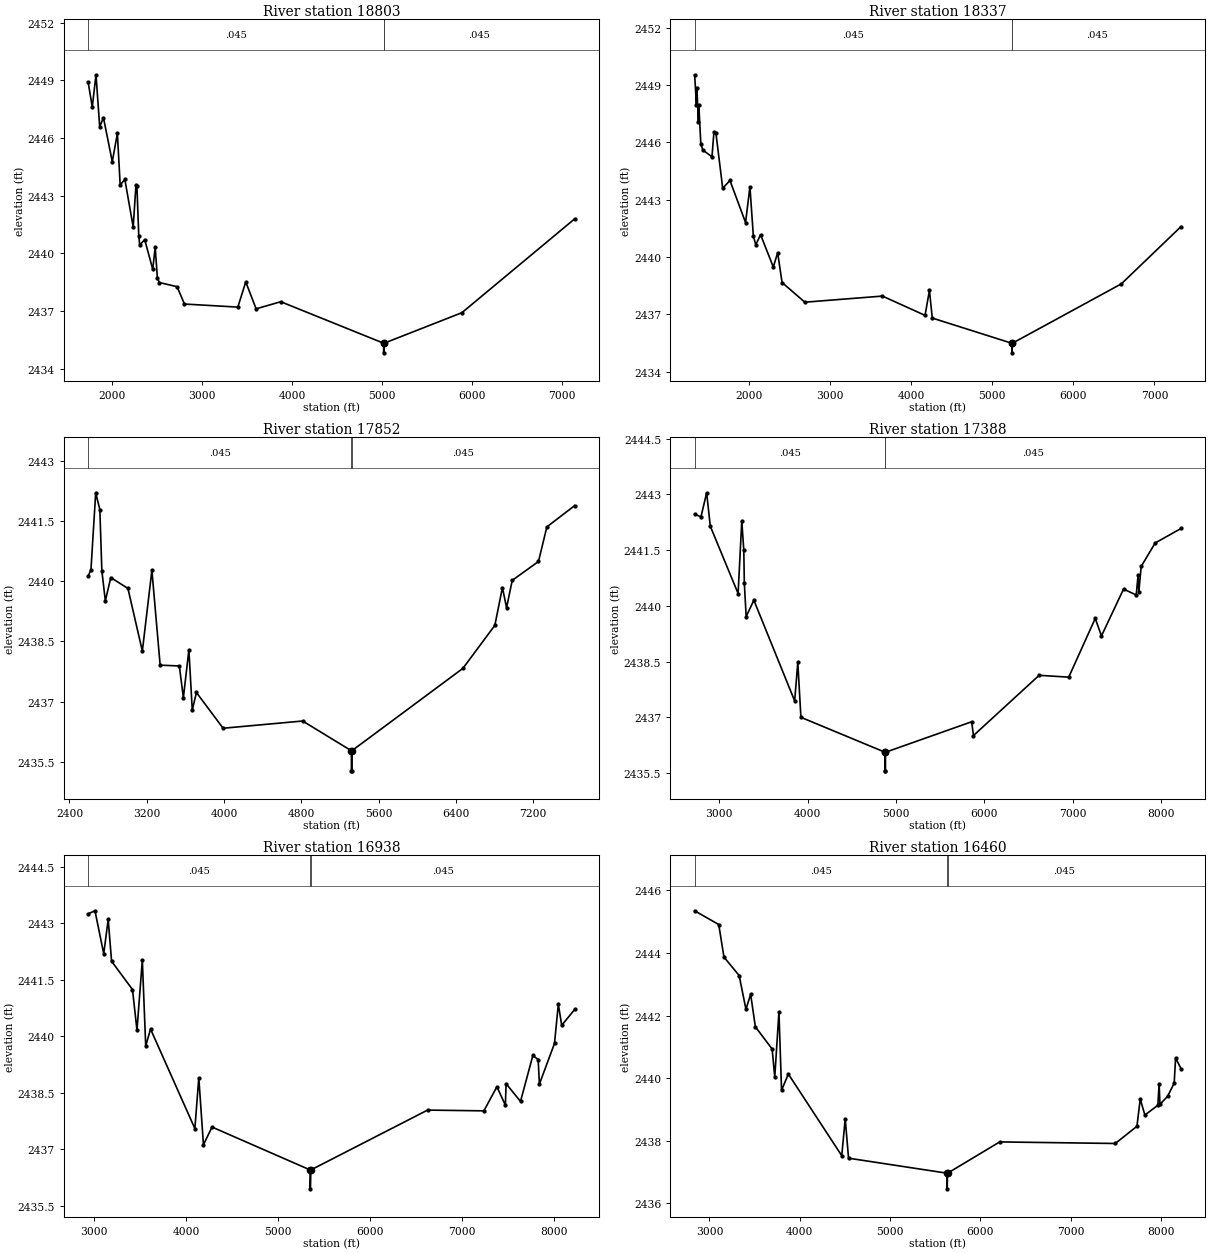
Type RM Length L Ch R = 1,18803,466,466,466
BEGIN DESCRIPTION:
UCFB HW Trib 24 32.0
END DESCRIPTION:
XS GIS Cut Line= 5
      1264537.26      6946542.03      1263777.28      6943611.76
      1263705.00      6943388.00      1263621.52      6943188.14
      1262880.02      6941413.04
#Sta/Elev= 30
  1737.6 2448.90  1783.1 2447.61  1824.4 2449.29  1865.7 2446.58  1907.1 2447.06
  2005.4 2444.77  2062.0 2446.24  2093.0 2443.55  2144.7 2443.85  2237.6 2441.37
  2268.6 2443.57  2279.0 2443.48  2299.6 2440.90  2310.0 2440.43  2365.4 2440.71
  2454.6 2439.17  2482.0 2440.31  2506.2 2438.72  2527.7 2438.48  2725.4 2438.26
  2806.6 2437.36  3399.8 2437.20  3487.7 2438.51  3602.7 2437.11  3876.4 2437.48
  5019.3 2435.32  5019.6 2434.82  5023.9 2435.32  5888.6 2436.91  7140.3 2441.79
#Mann=3,-1,0
  1737.6   0.045       0  5019.3   0.045       0  5023.9   0.045       0
Bank Sta=5019.3,5023.9
Exp/Cntr=0.3,0.1

Type RM Length L Ch R = 1,18337,485,485,485
BEGIN DESCRIPTION:
UCFB HW Trib 24 31.0
END DESCRIPTION:
XS GIS Cut Line= 5
      1265448.72      6946772.06      1264272.51      6943803.34
      1264155.00      6943338.00      1264029.46      6942956.98
      1263032.22      6941307.33
#Sta/Elev= 30
  1326.9 2449.54  1349.0 2447.97  1354.4 2448.87  1373.3 2447.06  1378.7 2447.94
  1403.0 2445.94  1427.4 2445.60  1540.8 2445.25  1565.1 2446.56  1589.4 2446.49
  1673.2 2443.60  1762.3 2444.01  1955.1 2441.81  2008.9 2443.68  2051.5 2441.09
  2081.2 2440.65  2140.6 2441.17  2297.4 2439.48  2351.4 2440.23  2405.4 2438.67
  2686.6 2437.64  3643.9 2437.96  4169.8 2436.95  4223.8 2438.26  4258.9 2436.81
  5241.3 2435.49  5241.6 2434.99  5246.0 2435.49  6592.0 2438.60  7328.9 2441.60
#Mann=3,-1,0
  1326.9   0.045       0  5241.3   0.045       0  5246.0   0.045       0
Bank Sta=5241.3,5246
Exp/Cntr=0.3,0.1

Type RM Length L Ch R = 1,17852,464,464,464
BEGIN DESCRIPTION:
UCFB HW Trib 24 30.0
END DESCRIPTION:
XS GIS Cut Line= 3
      1266180.03      6945063.03      1264605.00      6943238.00
      1263115.56      6941078.17
#Sta/Elev= 30
  2593.7 2440.13  2622.3 2440.28  2671.6 2442.20  2714.4 2441.78  2735.3 2440.26
  2771.4 2439.51  2827.4 2440.09  3005.1 2439.82  3154.3 2438.26  3253.0 2440.27
  3338.6 2437.91  3537.1 2437.89  3578.9 2437.10  3635.9 2438.29  3671.0 2436.79
  3713.8 2437.23  3990.2 2436.34  4813.0 2436.52  5317.9 2435.78  5318.2 2435.28
  5322.2 2435.28  5322.6 2435.78  6471.7 2437.83  6802.2 2438.90  6880.8 2439.84
  6923.7 2439.34  6982.2 2440.02  7254.0 2440.49  7340.5 2441.35  7628.0 2441.88
#Mann=3,-1,0
  2593.7   0.045       0  5317.9   0.045       0  5322.6   0.045       0
Bank Sta=5317.9,5322.6
Exp/Cntr=0.3,0.1

Type RM Length L Ch R = 1,17388,450,450,450
BEGIN DESCRIPTION:
UCFB HW Trib 24 29.0
END DESCRIPTION:
XS GIS Cut Line= 3
      1266455.02      6944988.03      1265055.00      6943188.00
      1263115.55      6940605.94
#Sta/Elev= 30
  2720.1 2442.47  2791.6 2442.39  2855.9 2443.04  2897.5 2442.14  3212.4 2440.33
  3254.0 2442.28  3276.6 2441.50  3283.0 2440.60  3303.8 2439.71  3390.7 2440.15
  3853.1 2437.44  3888.4 2438.48  3923.7 2437.00  4876.9 2436.06  4877.2 2435.56
  4881.2 2435.56  4881.6 2436.06  5857.6 2436.88  5878.4 2436.51  6622.0 2438.13
  6957.4 2438.08  7257.3 2439.66  7328.1 2439.19  7578.1 2440.45  7721.8 2440.29
  7742.6 2440.83  7750.9 2440.37  7778.0 2441.06  7936.3 2441.69  8229.8 2442.08
#Mann=3,-1,0
  2720.1   0.045       0  4876.9   0.045       0  4881.6   0.045       0
Bank Sta=4876.9,4881.6
Exp/Cntr=0.3,0.1

Type RM Length L Ch R = 1,16938,478,478,478
BEGIN DESCRIPTION:
UCFB HW Trib 24 28.0
END DESCRIPTION:
XS GIS Cut Line= 3
      1266520.00      6944812.99      1265455.00      6943038.00
      1263435.03      6940529.59
#Sta/Elev= 30
  2934.2 2443.25  3008.1 2443.33  3103.3 2442.19  3151.9 2443.10  3188.8 2441.99
  3416.2 2441.24  3464.8 2440.16  3523.1 2442.02  3560.0 2439.74  3612.5 2440.19
  4094.6 2437.55  4137.3 2438.90  4187.8 2437.12  4281.1 2437.59  5349.6 2436.45
  5350.0 2435.95  5354.7 2436.45  6625.4 2438.04  7238.0 2438.02  7379.5 2438.66
  7471.6 2438.17  7479.6 2438.74  7636.2 2438.27  7770.7 2439.49  7828.3 2439.38
  7841.7 2438.73  8005.9 2439.81  8047.5 2440.85  8084.3 2440.29  8224.8 2440.71
#Mann=3,-1,0
  2934.2   0.045       0  5349.6   0.045       0  5354.7   0.045       0
Bank Sta=5349.6,5354.7
Exp/Cntr=0.3,0.1

Type RM Length L Ch R = 1,16460,442,442,442
BEGIN DESCRIPTION:
UCFB HW Trib 24 27.0
END DESCRIPTION:
XS GIS Cut Line= 3
      1266780.01      6944913.03      1265905.00      6942938.00
      1264178.09      6940210.16
#Sta/Elev= 30
  2835.8 2445.35  3102.9 2444.91  3160.4 2443.87  3328.8 2443.28  3404.1 2442.20
  3456.1 2442.68  3508.5 2441.64  3694.4 2440.93  3723.2 2440.03  3769.7 2442.12
  3798.5 2439.61  3873.8 2440.13  4465.4 2437.52  4503.8 2438.70  4540.7 2437.44
  5632.5 2436.96  5632.9 2436.46  5637.6 2436.96  6214.8 2437.96  7495.5 2437.91
  7735.4 2438.46  7771.8 2439.33  7823.5 2438.82  7966.7 2439.13  7981.2 2439.82
  7990.4 2439.16  8075.2 2439.42  8148.1 2439.84  8163.4 2440.64  8224.5 2440.30
#Mann=3,-1,0
  2835.8   0.045       0  5632.5   0.045       0  5637.6   0.045       0
Bank Sta=5632.5,5637.6
Exp/Cntr=0.3,0.1

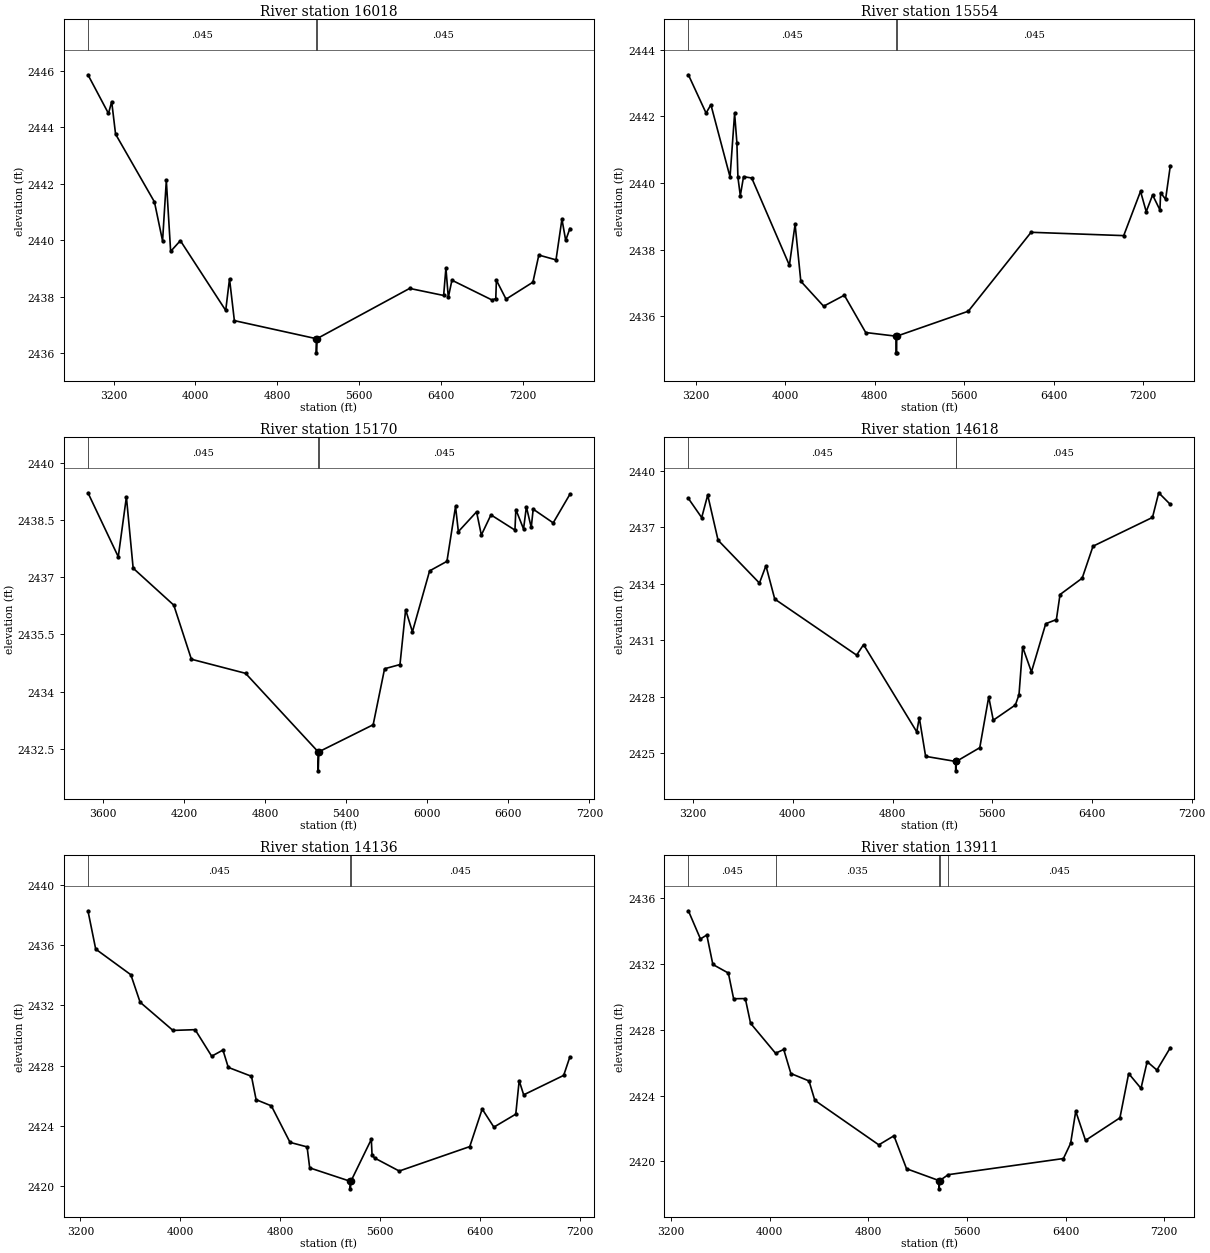
Type RM Length L Ch R = 1,16018,464,464,464
BEGIN DESCRIPTION:
UCFB HW Trib 24 26.0
END DESCRIPTION:
XS GIS Cut Line= 3
      1266914.17      6944633.71      1266255.00      6942688.00
      1264859.32      6940426.54
#Sta/Elev= 30
  2950.2 2445.86  3150.9 2444.49  3182.3 2444.91  3220.2 2443.76  3600.3 2441.36
  3679.7 2439.98  3716.4 2442.12  3758.7 2439.61  3853.7 2439.99  4297.1 2437.52
  4334.3 2438.64  4381.6 2437.16  5183.4 2436.52  5183.8 2436.02  5188.6 2436.52
  6095.4 2438.30  6427.7 2438.05  6449.9 2439.02  6473.4 2437.98  6508.7 2438.59
  6900.7 2437.89  6937.4 2437.94  6943.5 2438.59  7037.9 2437.92  7300.4 2438.52
  7358.3 2439.48  7526.3 2439.31  7584.2 2440.75  7620.9 2440.00  7662.0 2440.42
#Mann=3,-1,0
  2950.2   0.045       0  5183.4   0.045       0  5188.6   0.045       0
Bank Sta=5183.4,5188.6
Exp/Cntr=0.3,0.1

Type RM Length L Ch R = 1,15554,384,384,384
BEGIN DESCRIPTION:
UCFB HW Trib 24 25.0
END DESCRIPTION:
XS GIS Cut Line= 3
      1267030.00      6944313.01      1266655.00      6942488.00
      1265280.02      6940463.03
#Sta/Elev= 30
  3132.4 2443.25  3290.6 2442.10  3333.9 2442.35  3505.0 2440.18  3545.9 2442.09
  3566.3 2441.21  3575.5 2440.17  3596.9 2439.62  3625.8 2440.19  3699.0 2440.15
  4035.9 2437.53  4086.9 2438.76  4138.0 2437.05  4342.2 2436.30  4527.3 2436.63
  4718.5 2435.51  4990.4 2435.40  4990.8 2434.90  4995.2 2434.90  4995.6 2435.40
  5636.2 2436.15  6197.7 2438.52  7026.2 2438.42  7176.8 2439.75  7227.6 2439.14
  7284.6 2439.64  7350.4 2439.19  7356.4 2439.71  7400.9 2439.51  7443.2 2440.52
#Mann=3,-1,0
  3132.4   0.045       0  4990.4   0.045       0  4995.6   0.045       0
Bank Sta=4990.4,4995.6
Exp/Cntr=0.3,0.1

Type RM Length L Ch R = 1,15170,552,552,552
BEGIN DESCRIPTION:
UCFB HW Trib 24 25.5
END DESCRIPTION:
XS GIS Cut Line= 4
      1267023.22      6943721.85      1266958.96      6942533.00
      1266910.77      6942067.10      1265654.79      6940634.48
#Sta/Elev= 30
  3491.0 2439.22  3715.2 2437.54  3775.3 2439.11  3825.3 2437.24  4125.8 2436.27
  4256.0 2434.85  4656.6 2434.48  5193.4 2432.42  5193.8 2431.92  5198.6 2432.42
  5600.3 2433.13  5684.7 2434.60  5798.6 2434.71  5840.4 2436.15  5890.6 2435.57
  6017.8 2437.17  6145.9 2437.42  6209.5 2438.86  6230.4 2438.20  6365.1 2438.72
  6400.3 2438.11  6471.4 2438.64  6648.9 2438.24  6655.5 2438.78  6712.5 2438.27
  6733.4 2438.85  6769.4 2438.31  6783.7 2438.79  6931.7 2438.43  7055.2 2439.18
#Mann=3,-1,0
  3491.0   0.045       0  5193.4   0.045       0  5198.6   0.045       0
Bank Sta=5193.4,5198.6
Exp/Cntr=0.3,0.1

Type RM Length L Ch R = 1,14618,482,482,482
BEGIN DESCRIPTION:
UCFB HW Trib 24 24.0
END DESCRIPTION:
XS GIS Cut Line= 5
      1267157.23      6943713.65      1267375.99      6942213.15
      1267355.00      6941888.00      1267299.60      6941581.21
      1265929.00      6940554.59
#Sta/Elev= 30
  3161.9 2438.54  3268.7 2437.52  3316.9 2438.72  3400.0 2436.32  3732.0 2434.04
  3784.1 2434.96  3854.8 2433.19  4511.7 2430.21  4567.3 2430.77  4994.1 2426.13
  5014.3 2426.89  5065.1 2424.83  5306.1 2424.56  5306.5 2424.06  5311.3 2424.56
  5499.6 2425.29  5571.5 2427.99  5607.9 2426.75  5785.0 2427.56  5814.2 2428.10
  5843.4 2430.64  5914.2 2429.32  6028.8 2431.88  6114.2 2432.10  6143.4 2433.43
  6321.1 2434.30  6408.1 2436.00  6885.2 2437.53  6935.2 2438.84  7028.3 2438.22
#Mann=3,-1,0
  3161.9   0.045       0  5306.1   0.045       0  5311.3   0.045       0
Bank Sta=5306.1,5311.3
Exp/Cntr=0.3,0.1

Type RM Length L Ch R = 1,14136,225,225,225
BEGIN DESCRIPTION:
UCFB HW Trib 24 23.0
END DESCRIPTION:
XS GIS Cut Line= 4
      1267261.40      6943644.20      1267805.00      6941988.00
      1267844.74      6941783.06      1266805.01      6940188.01
#Sta/Elev= 30
  3261.0 2438.26  3323.0 2435.72  3604.2 2434.02  3678.3 2432.20  3941.1 2430.33
  4118.5 2430.38  4251.1 2428.62  4341.1 2429.03  4383.6 2427.88  4569.3 2427.29
  4606.4 2425.74  4728.4 2425.33  4877.8 2422.91  5014.3 2422.61  5035.1 2421.22
  5359.5 2420.33  5359.9 2419.83  5364.7 2420.33  5528.1 2423.11  5534.1 2422.07
  5555.2 2421.87  5751.4 2421.01  6315.7 2422.63  6415.2 2425.12  6508.8 2423.92
  6683.9 2424.78  6711.1 2427.00  6747.2 2426.06  7067.2 2427.35  7116.9 2428.58
#Mann=3,-1,0
  3261.0   0.045       0  5359.5   0.045       0  5364.7   0.045       0
Bank Sta=5359.5,5364.7
Exp/Cntr=0.3,0.1

Type RM Length L Ch R = 1,13911,133,133,133
BEGIN DESCRIPTION:
UCFB HW Trib 24 24.6
END DESCRIPTION:
XS GIS Cut Line= 4
      1267358.29      6943545.48      1267872.21      6942705.49
      1268084.01      6941698.55      1266946.07      6940184.27
#Sta/Elev= 30
  3341.4 2435.22  3439.3 2433.51  3490.8 2433.75  3539.9 2431.96  3665.6 2431.44
  3708.2 2429.88  3803.0 2429.89  3845.6 2428.39  4048.3 2426.57  4114.6 2426.80
  4172.6 2425.34  4319.6 2424.89  4366.8 2423.71  4885.6 2421.01  5008.2 2421.56
  5110.4 2419.56  5373.9 2418.84  5374.3 2418.34  5379.1 2418.84  5448.6 2419.20
  6382.5 2420.18  6440.8 2421.10  6482.4 2423.05  6561.6 2421.28  6840.7 2422.65
  6911.5 2425.34  7011.5 2424.44  7061.5 2426.06  7140.6 2425.55  7249.3 2426.91
#Mann=5,-1,0
  3341.4   0.045       0  4048.3   0.035       0  5373.9   0.035       0
  5379.1   0.035       0  5448.6   0.045       0
Bank Sta=5373.9,5379.1
Exp/Cntr=0.3,0.1

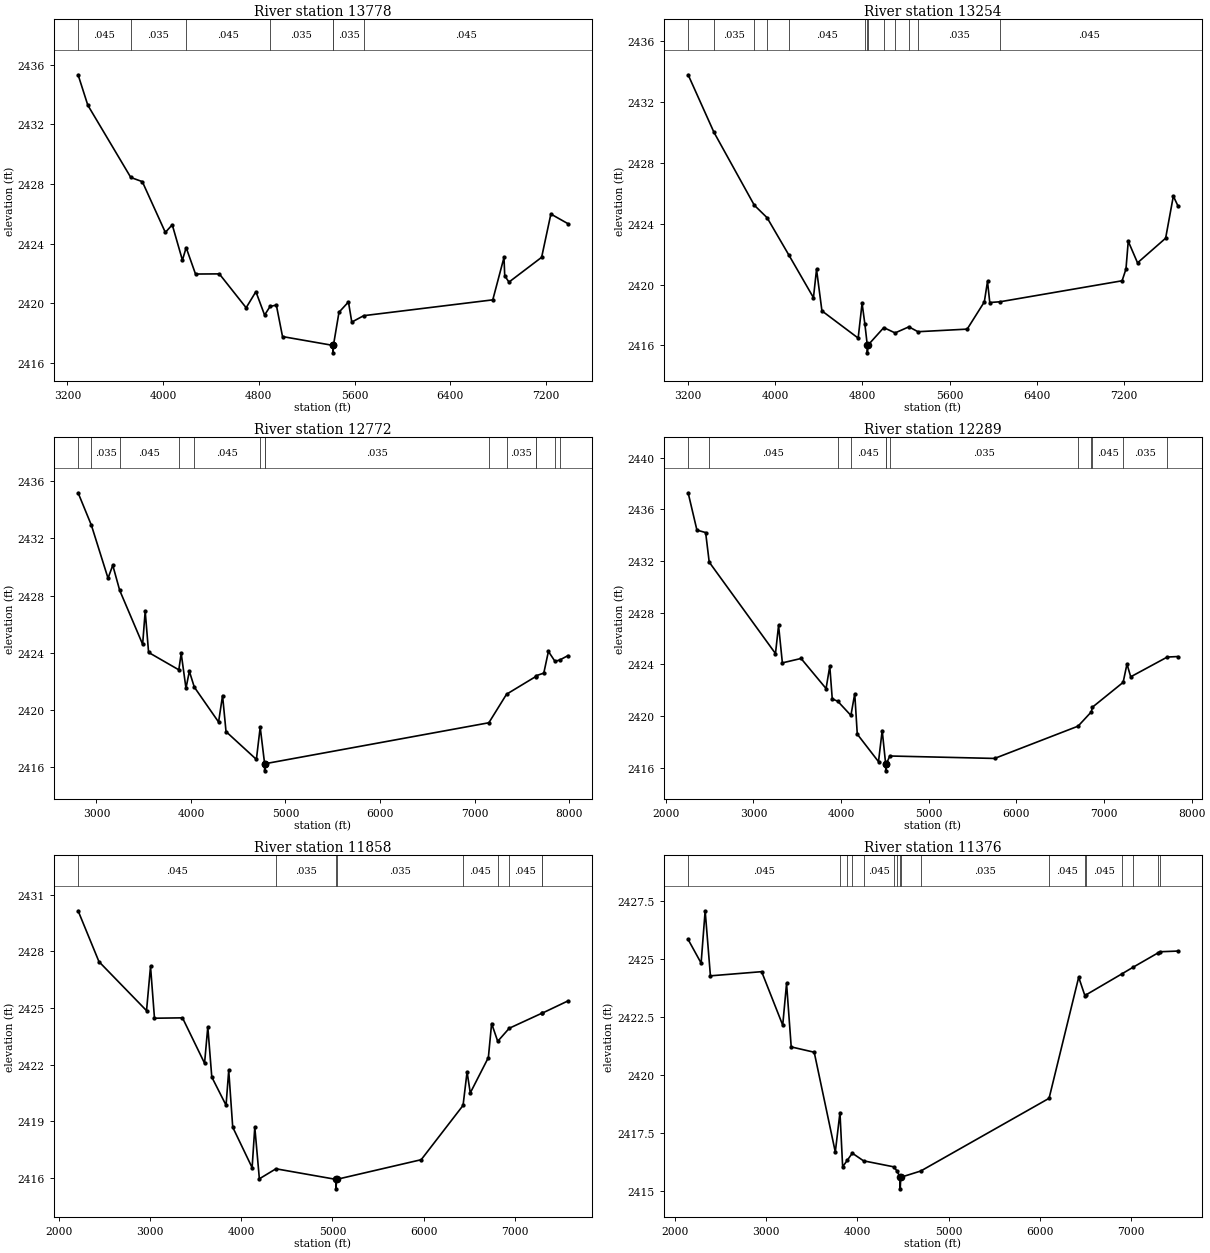
Type RM Length L Ch R = 1,13778,524,524,524
BEGIN DESCRIPTION:
UCFB HW Trib 24 24.3
END DESCRIPTION:
XS GIS Cut Line= 4
      1267389.97      6943577.24      1267986.79      6942820.08
      1268212.49      6941663.83      1267041.14      6940104.93
#Sta/Elev= 30
  3290.0 2435.32  3371.3 2433.28  3730.5 2428.44  3826.7 2428.16  4019.1 2424.76
  4076.9 2425.27  4161.8 2422.90  4193.1 2423.74  4271.2 2421.97  4470.2 2421.98
  4694.3 2419.71  4775.8 2420.79  4848.6 2419.22  4894.4 2419.80  4946.7 2419.89
  4998.3 2417.78  5418.4 2417.19  5418.8 2416.69  5423.7 2417.19  5470.2 2419.41
  5549.3 2420.10  5577.1 2418.75  5676.8 2419.18  6755.3 2420.24  6849.0 2423.08
  6855.2 2421.85  6890.6 2421.43  7163.5 2423.09  7240.7 2425.99  7382.1 2425.35
#Mann=7,-1,0
  3290.0   0.045       0  3730.5   0.035       0  4193.1   0.045       0
  4894.4   0.035       0  5418.4   0.035       0  5423.7   0.035       0
  5676.8   0.045       0
Bank Sta=5418.4,5423.7
Exp/Cntr=0.3,0.1

Type RM Length L Ch R = 1,13254,482,482,482
BEGIN DESCRIPTION:
UCFB HW Trib 24 22.0
END DESCRIPTION:
XS GIS Cut Line= 5
      1267457.14      6943575.64      1268572.75      6942445.09
      1268605.00      6942238.00      1268630.00      6942063.00
      1267104.08      6940061.50
#Sta/Elev= 30
  3202.5 2433.80  3439.1 2430.02  3809.4 2425.22  3926.6 2424.40  4125.8 2421.95
  4351.9 2419.14  4380.2 2421.00  4429.7 2418.27  4762.0 2416.48  4798.0 2418.77
  4824.0 2417.38  4845.8 2416.01  4846.3 2415.51  4851.3 2416.01  4997.1 2417.17
  5100.6 2416.82  5227.1 2417.22  5310.5 2416.90  5761.9 2417.07  5919.2 2418.86
  5948.3 2420.21  5969.1 2418.82  6064.0 2418.87  7182.8 2420.25  7218.3 2421.02
  7239.2 2422.85  7324.4 2421.43  7582.1 2423.05  7652.8 2425.82  7694.0 2425.19
#Mann=13,-1,0
  3202.5   0.045       0  3439.1   0.035       0  3809.4   0.045       0
  3926.6   0.035       0  4125.8   0.045       0  4824.0   0.035       0
  4845.8   0.045       0  4851.3   0.035       0  4997.1   0.045       0
  5100.6   0.035       0  5227.1   0.045       0  5310.5   0.035       0
  6064.0   0.045       0
Bank Sta=4845.8,4851.3
Exp/Cntr=0.3,0.1

Type RM Length L Ch R = 1,12772,483,483,483
BEGIN DESCRIPTION:
UCFB HW Trib 24 21.0
END DESCRIPTION:
XS GIS Cut Line= 5
      1267454.97      6943738.02      1268956.55      6942682.71
      1269055.00      6942338.00      1269180.00      6941863.00
      1271244.62      6940463.73
#Sta/Elev= 30
  2806.6 2435.20  2947.6 2432.92  3123.3 2429.21  3173.3 2430.12  3246.7 2428.36
  3489.3 2424.58  3516.3 2426.90  3552.2 2424.01  3871.9 2422.79  3897.1 2423.94
  3947.6 2421.50  3983.3 2422.69  4035.6 2421.58  4292.6 2419.13  4334.5 2420.99
  4371.1 2418.46  4692.3 2416.51  4732.6 2418.77  4779.3 2416.21  4779.7 2415.71
  4784.8 2416.21  7150.8 2419.08  7338.0 2421.08  7644.4 2422.31  7647.1 2422.37
  7731.9 2422.56  7780.8 2424.08  7850.8 2423.38  7903.5 2423.49  7985.7 2423.78
#Mann=14,-1,0
  2806.6   0.045       0  2947.6   0.035       0  3246.7   0.045       0
  3871.9   0.035       0  4035.6   0.045       0  4732.6   0.035       0
  4779.3   0.035       0  4784.8   0.035       0  7150.8   0.045       0
  7338.0   0.035       0  7644.4   0.045       0  7647.1   0.035       0
  7850.8   0.045       0  7903.5   0.035       0
Bank Sta=4779.3,4784.8
Exp/Cntr=0.3,0.1

Type RM Length L Ch R = 1,12289,431,431,431
BEGIN DESCRIPTION:
UCFB HW Trib 24 20.0
END DESCRIPTION:
XS GIS Cut Line= 5
      1267505.01      6944237.99      1269416.33      6942733.64
      1269505.00      6942438.00      1269630.00      6942013.00
      1271521.57      6940529.97
#Sta/Elev= 30
  2254.8 2437.29  2355.1 2434.40  2454.5 2434.21  2495.4 2431.92  3251.5 2424.84
  3286.7 2427.02  3330.1 2424.12  3543.3 2424.46  3828.8 2422.13  3871.0 2423.86
  3899.3 2421.33  3961.7 2421.15  4112.1 2420.05  4155.9 2421.73  4184.8 2418.60
  4427.0 2416.47  4469.1 2418.88  4509.2 2416.26  4509.7 2415.76  4514.7 2416.26
  4555.4 2416.91  5751.6 2416.72  6704.2 2419.22  6857.3 2420.34  6864.6 2420.67
  7218.2 2422.61  7262.2 2424.03  7304.7 2423.04  7721.5 2424.57  7842.4 2424.61
#Mann=12,-1,0
  2254.8   0.035       0  2495.4   0.045       0  3961.7   0.035       0
  4112.1   0.045       0  4509.2   0.035       0  4514.7   0.045       0
  4555.4   0.035       0  6704.2   0.045       0  6857.3   0.035       0
  6864.6   0.045       0  7218.2   0.035       0  7721.5   0.045       0
Bank Sta=4509.2,4514.7
Exp/Cntr=0.3,0.1

Type RM Length L Ch R = 1,11858,482,482,482
BEGIN DESCRIPTION:
UCFB HW Trib 24 19.0
END DESCRIPTION:
XS GIS Cut Line= 5
      1267801.77      6944296.12      1269828.65      6942794.40
      1269905.00      6942538.00      1269989.24      6942269.23
      1271704.97      6940738.03
#Sta/Elev= 30
  2210.3 2430.14  2439.2 2427.45  2961.1 2424.86  3004.8 2427.20  3048.2 2424.46
  3355.5 2424.48  3597.5 2422.08  3633.1 2424.00  3676.8 2421.35  3833.3 2419.86
  3862.6 2421.70  3906.4 2418.70  4119.2 2416.56  4148.5 2418.70  4198.6 2415.97
  4380.5 2416.50  5038.8 2415.94  5039.3 2415.44  5045.8 2415.94  5973.7 2416.98
  6432.9 2419.85  6476.9 2421.62  6512.1 2420.51  6710.5 2422.38  6746.1 2424.18
  6813.2 2423.24  6939.7 2423.93  7295.3 2424.72  7298.2 2424.72  7581.7 2425.37
#Mann=9,-1,0
  2210.3   0.045       0  4380.5   0.035       0  5038.8   0.035       0
  5045.8   0.035       0  6432.9   0.045       0  6813.2   0.035       0
  6939.7   0.045       0  7295.3   0.035       0  7298.2   0.045       0
Bank Sta=5038.8,5045.8
Exp/Cntr=0.3,0.1

Type RM Length L Ch R = 1,11376,590,590,590
BEGIN DESCRIPTION:
UCFB HW Trib 24 18.0
END DESCRIPTION:
XS GIS Cut Line= 5
      1268140.26      6944361.26      1270193.24      6942981.03
      1270355.00      6942638.00      1270462.33      6942347.35
      1271880.03      6940662.96
#Sta/Elev= 30
  2147.3 2425.85  2289.6 2424.83  2333.8 2427.09  2391.5 2424.28  2952.5 2424.46
  3183.5 2422.15  3225.5 2423.95  3276.5 2421.21  3528.5 2420.98  3759.5 2416.67
  3810.5 2418.37  3840.0 2416.03  3891.9 2416.32  3945.7 2416.62  4068.8 2416.29
  4400.1 2416.03  4433.8 2415.86  4469.8 2415.58  4470.3 2415.08  4477.0 2415.58
  4695.6 2415.85  6101.3 2418.99  6425.8 2424.22  6493.1 2423.43  6506.8 2423.46
  6896.8 2424.36  7021.0 2424.65  7294.3 2425.27  7317.8 2425.32  7511.8 2425.35
#Mann=17,-1,0
  2147.3   0.045       0  3810.5   0.035       0  3891.9   0.045       0
  3945.7   0.035       0  4068.8   0.045       0  4400.1   0.035       0
  4433.8   0.045       0  4469.8   0.035       0  4477.0   0.045       0
  4695.6   0.035       0  6101.3   0.045       0  6493.1   0.035       0
  6506.8   0.045       0  6896.8   0.035       0  7021.0   0.045       0
  7294.3   0.035       0  7317.8   0.045       0
Bank Sta=4469.8,4477
Exp/Cntr=0.3,0.1

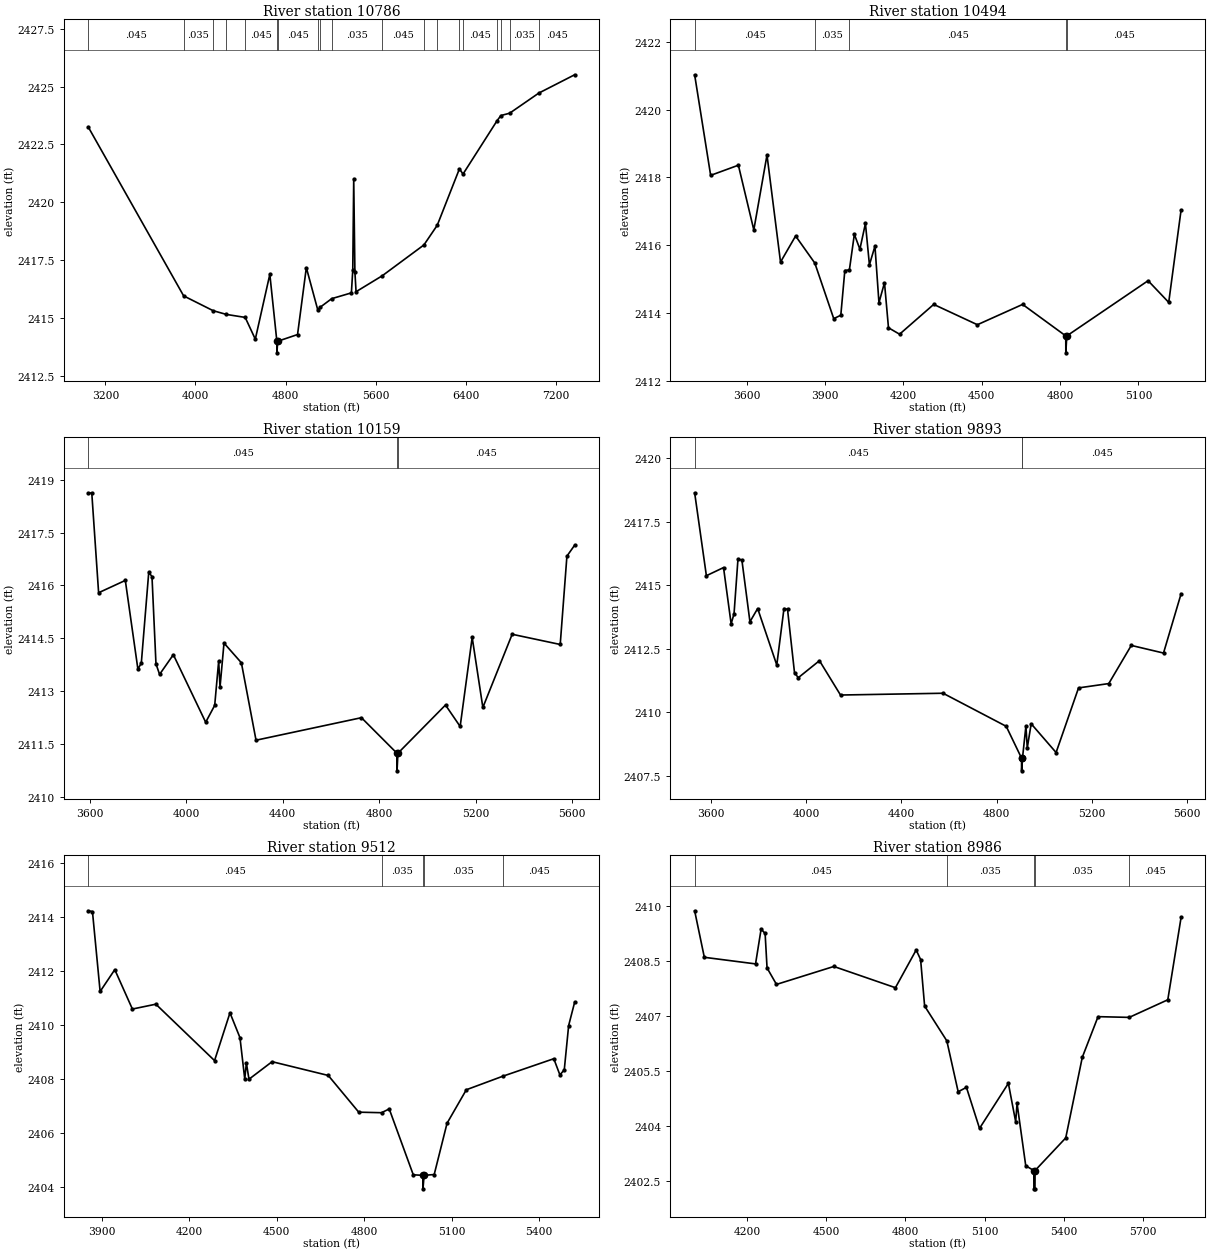
Type RM Length L Ch R = 1,10786,292,292,292
BEGIN DESCRIPTION:
UCFB HW Trib 24 17.0
END DESCRIPTION:
XS GIS Cut Line= 5
      1269005.03      6944137.98      1270712.33      6942997.52
      1270805.00      6942738.00      1270873.79      6942481.90
      1271929.98      6941113.03
#Sta/Elev= 30
  3046.3 2423.26  3894.7 2415.96  4157.1 2415.32  4273.8 2415.16  4441.7 2415.03
  4531.5 2414.09  4660.6 2416.89  4723.1 2414.00  4723.6 2413.50  4730.4 2414.00
  4906.9 2414.29  4985.0 2417.18  5086.8 2415.35  5105.3 2415.46  5210.4 2415.84
  5385.4 2416.09  5397.6 2417.07  5406.1 2421.02  5416.5 2417.01  5426.8 2416.14
  5660.0 2416.83  6029.9 2418.16  6148.4 2419.01  6345.7 2421.45  6377.2 2421.22
  6680.5 2423.53  6714.1 2423.75  6791.8 2423.85  7051.1 2424.72  7369.2 2425.51
#Mann=19,-1,0
  3046.3   0.045       0  3894.7   0.035       0  4157.1   0.045       0
  4273.8   0.035       0  4441.7   0.045       0  4723.1   0.045       0
  4730.4   0.045       0  5086.8   0.035       0  5105.3   0.045       0
  5210.4   0.035       0  5660.0   0.045       0  6029.9   0.035       0
  6148.4   0.045       0  6345.7   0.035       0  6377.2   0.045       0
  6680.5   0.035       0  6714.1   0.045       0  6791.8   0.035       0
  7051.1   0.045       0
Bank Sta=4723.1,4730.4
Exp/Cntr=0.3,0.1

Type RM Length L Ch R = 1,10494,335,335,335
BEGIN DESCRIPTION:
UCFB HW Trib 24 16.0
END DESCRIPTION:
XS GIS Cut Line= 2
      1269333.11      6944188.96      1270911.02      6943198.33
#Sta/Elev= 30
  3400.2 2421.03  3461.5 2418.06  3567.7 2418.36  3626.8 2416.45  3677.3 2418.66
  3729.1 2415.50  3786.9 2416.27  3860.5 2415.47  3932.9 2413.83  3960.0 2413.93
  3975.4 2415.25  3992.9 2415.27  4011.9 2416.32  4033.1 2415.88  4054.3 2416.64
  4069.6 2415.42  4090.8 2415.97  4106.1 2414.30  4127.3 2414.89  4142.6 2413.56
  4185.1 2413.37  4315.8 2414.25  4483.1 2413.65  4656.3 2414.25  4821.6 2413.32
  4821.8 2412.82  4825.6 2413.32  5136.9 2414.95  5215.9 2414.31  5263.3 2417.04
#Mann=5,-1,0
  3400.2   0.045       0  3860.5   0.035       0  3992.9   0.045       0
  4821.6   0.045       0  4825.6   0.045       0
Bank Sta=4821.6,4825.6
Exp/Cntr=0.3,0.1

Type RM Length L Ch R = 1,10159,266,266,266
BEGIN DESCRIPTION:
UCFB HW Trib 24 15.0
END DESCRIPTION:
XS GIS Cut Line= 2
      1269501.76      6944313.01      1271295.07      6943386.54
#Sta/Elev= 30
  3592.7 2418.61  3607.6 2418.63  3636.0 2415.79  3746.8 2416.14  3799.0 2413.62
  3813.2 2413.79  3844.0 2416.37  3857.5 2416.25  3874.0 2413.77  3889.0 2413.47
  3946.1 2414.03  4080.3 2412.11  4117.7 2412.59  4134.2 2413.85  4139.8 2413.11
  4156.3 2414.36  4228.4 2413.80  4289.2 2411.60  4726.6 2412.24  4874.0 2411.23
  4874.3 2410.73  4878.0 2411.23  5075.4 2412.60  5136.2 2411.99  5186.1 2414.52
  5230.4 2412.53  5352.0 2414.61  5551.4 2414.32  5579.2 2416.83  5611.2 2417.14
#Mann=3,-1,0
  3592.7   0.045       0  4874.0   0.045       0  4878.0   0.045       0
Bank Sta=4874,4878
Exp/Cntr=0.3,0.1

Type RM Length L Ch R = 1,9893,381,381,381
BEGIN DESCRIPTION:
UCFB HW Trib 24 14.1
END DESCRIPTION:
XS GIS Cut Line= 2
      1269499.12      6944607.30      1271310.46      6943663.23
#Sta/Elev= 30
  3532.4 2418.63  3581.7 2415.37  3653.7 2415.69  3685.6 2413.48  3697.8 2413.87
  3714.3 2416.02  3730.7 2415.99  3764.6 2413.56  3797.0 2414.08  3877.3 2411.86
  3907.5 2414.08  3922.4 2414.05  3951.7 2411.56  3967.5 2411.36  4056.5 2412.03
  4144.9 2410.68  4575.5 2410.75  4840.7 2409.45  4905.0 2408.20  4905.2 2407.70
  4909.0 2408.20  4923.4 2409.46  4929.1 2408.60  4945.5 2409.55  5050.1 2408.42
  5144.4 2410.96  5271.3 2411.13  5365.9 2412.63  5501.2 2412.33  5575.0 2414.66
#Mann=3,-1,0
  3532.4   0.045       0  4905.0   0.045       0  4909.0   0.045       0
Bank Sta=4905,4909
Exp/Cntr=0.3,0.1

Type RM Length L Ch R = 1,9512,526,526,526
BEGIN DESCRIPTION:
UCFB HW Trib 24 14.2
END DESCRIPTION:
XS GIS Cut Line= 4
      1269814.31      6944664.56      1270294.43      6944609.16
      1271119.29      6944175.62      1271260.51      6943964.70
#Sta/Elev= 30
  3852.9 2414.22  3867.6 2414.19  3893.9 2411.23  3944.2 2412.04  4004.6 2410.58
  4085.1 2410.76  4286.5 2408.67  4339.4 2410.44  4373.7 2409.52  4390.1 2407.99
  4395.7 2408.58  4404.6 2407.98  4483.9 2408.63  4676.6 2408.12  4781.2 2406.76
  4859.4 2406.74  4885.8 2406.88  4968.3 2404.44  5001.4 2404.42  5001.6 2403.92
  5005.4 2404.42  5040.1 2404.45  5084.2 2406.35  5150.3 2407.59  5275.1 2408.09
  5450.4 2408.74  5471.4 2408.14  5486.4 2408.33  5501.4 2409.97  5521.9 2410.83
#Mann=5,-1,0
  3852.9   0.045       0  4859.4   0.035       0  5001.4   0.035       0
  5005.4   0.035       0  5275.1   0.045       0
Bank Sta=5001.4,5005.4
Exp/Cntr=0.3,0.1

Type RM Length L Ch R = 1,8986,364,364,364
BEGIN DESCRIPTION:
UCFB HW Trib 24 12.7
END DESCRIPTION:
XS GIS Cut Line= 3
      1271865.90      6945336.43      1271145.43      6944874.20
      1270859.49      6943929.73
#Sta/Elev= 30
  4001.7 2409.87  4038.4 2408.60  4232.4 2408.42  4253.5 2409.37  4268.7 2409.25
  4276.0 2408.31  4311.7 2407.86  4529.0 2408.35  4762.3 2407.77  4840.9 2408.80
  4857.7 2408.54  4872.9 2407.27  4957.0 2406.32  5000.0 2404.93  5031.3 2405.05
  5080.9 2403.93  5190.2 2405.16  5217.9 2404.11  5223.1 2404.61  5256.0 2402.91
  5286.6 2402.78  5286.9 2402.28  5290.9 2402.28  5291.3 2402.78  5407.5 2403.67
  5470.2 2405.87  5529.9 2406.98  5648.0 2406.96  5794.1 2407.44  5844.5 2409.69
#Mann=5,-1,0
  4001.7   0.045       0  4957.0   0.035       0  5286.6   0.035       0
  5291.3   0.035       0  5648.0   0.045       0
Bank Sta=5286.6,5291.3
Exp/Cntr=0.3,0.1

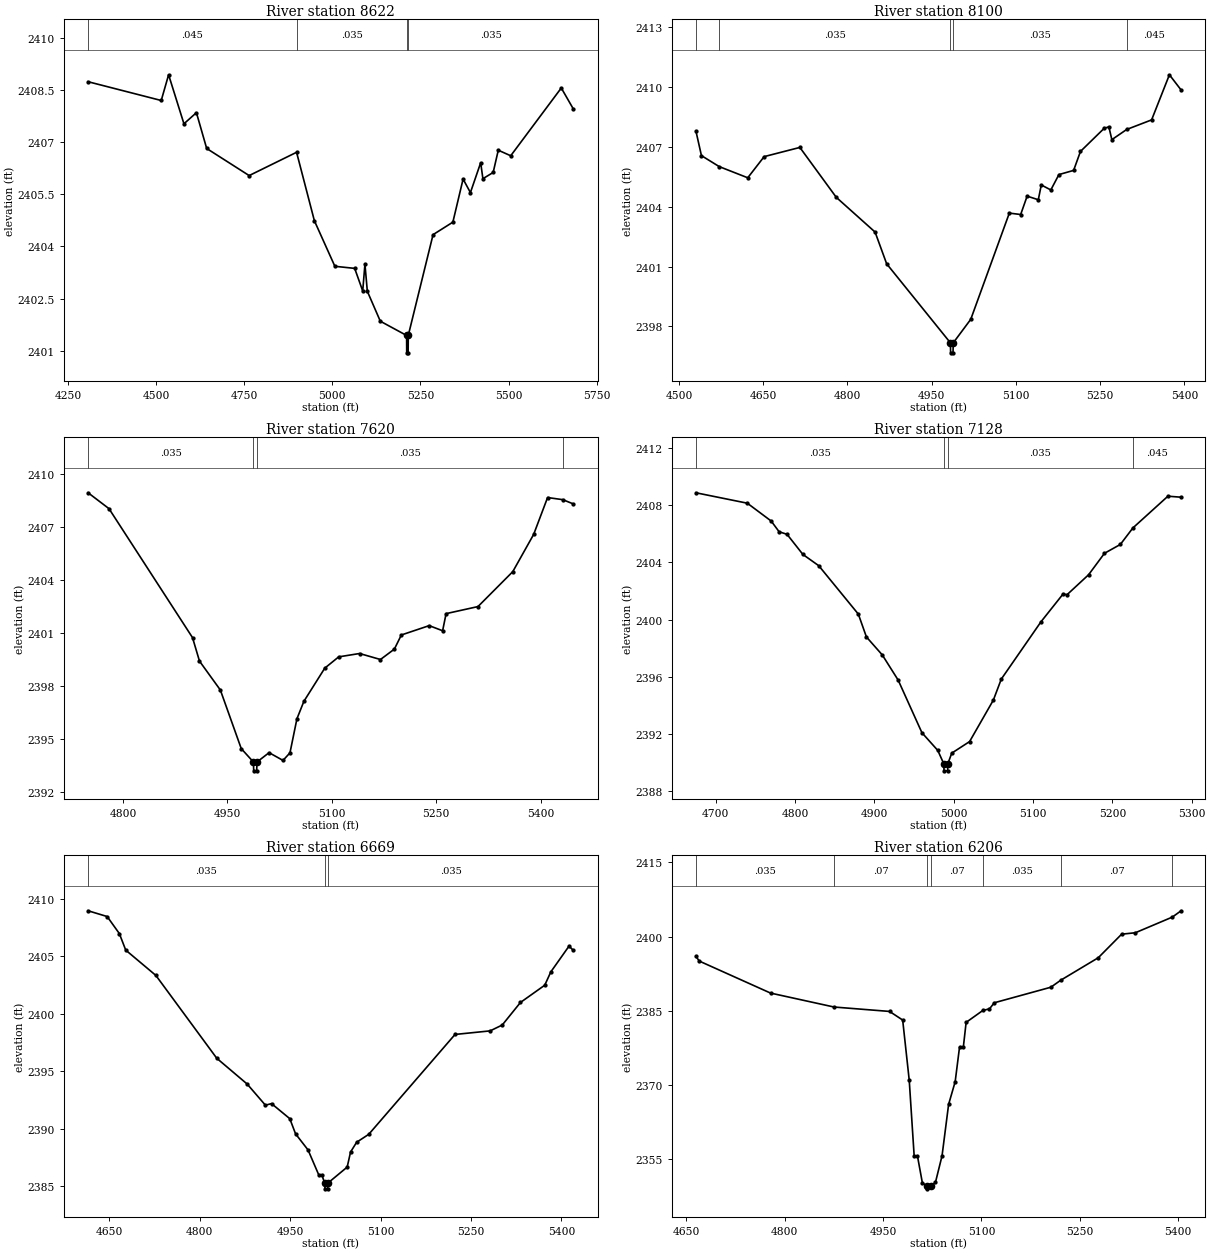
Type RM Length L Ch R = 1,8622,522,522,522
BEGIN DESCRIPTION:
UCFB HW Trib 24 12.6
END DESCRIPTION:
XS GIS Cut Line= 3
      1271826.22      6945237.45      1271267.57      6944505.96
      1270991.00      6944143.81
#Sta/Elev= 30
  4307.5 2408.74  4514.9 2408.20  4535.8 2408.94  4579.3 2407.53  4614.7 2407.85
  4643.8 2406.82  4764.3 2406.04  4898.8 2406.71  4949.3 2404.74  5007.4 2403.43
  5063.6 2403.37  5086.4 2402.72  5092.7 2403.49  5099.5 2402.71  5136.3 2401.85
  5210.9 2401.44  5211.2 2400.94  5215.2 2400.94  5215.6 2401.44  5285.9 2404.34
  5342.1 2404.70  5371.1 2405.94  5391.9 2405.55  5421.0 2406.41  5427.3 2405.95
  5456.4 2406.13  5470.9 2406.77  5506.2 2406.61  5649.6 2408.56  5683.6 2407.96
#Mann=4,-1,0
  4307.5   0.045       0  4898.8   0.035       0  5210.9   0.035       0
  5215.6   0.035       0
Bank Sta=5210.9,5215.6
Exp/Cntr=0.3,0.1

Type RM Length L Ch R = 1,8100,480,480,480
BEGIN DESCRIPTION:
UCFB HW Trib 24 12.1
END DESCRIPTION:
XS GIS Cut Line= 3
      1271820.43      6944747.47      1271705.00      6944288.00
      1271579.72      6943918.30
#Sta/Elev= 30
  4530.1 2407.79  4539.9 2406.56  4571.6 2406.01  4622.4 2405.45  4651.6 2406.51
  4715.2 2406.97  4780.1 2404.47  4849.2 2402.73  4869.8 2401.14  4983.4 2397.18
  4983.7 2396.68  4988.0 2396.68  4988.4 2397.18  5019.6 2398.36  5088.3 2403.68
  5108.5 2403.61  5120.0 2404.53  5139.9 2404.35  5145.2 2405.09  5162.2 2404.84
  5176.6 2405.61  5202.8 2405.82  5215.0 2406.77  5257.3 2407.93  5265.6 2408.00
  5270.9 2407.36  5297.3 2407.87  5341.7 2408.35  5373.4 2410.61  5394.2 2409.85
#Mann=5,-1,0
  4530.1   0.045       0  4571.6   0.035       0  4983.4   0.035       0
  4988.4   0.035       0  5297.3   0.045       0
Bank Sta=4983.4,4988.4
Exp/Cntr=0.3,0.1

Type RM Length L Ch R = 1,7620,492,492,492
BEGIN DESCRIPTION:
UCFB HW Trib 24 12.2
END DESCRIPTION:
XS GIS Cut Line= 3
      1272105.00      6944638.00      1272105.00      6944388.00
      1272096.52      6943941.08
#Sta/Elev= 30
  4750.0 2408.94  4780.0 2408.04  4900.0 2400.73  4910.0 2399.40  4940.0 2397.76
  4970.0 2394.44  4987.5 2393.68  4987.9 2393.18  4992.2 2393.18  4992.6 2393.68
  5010.0 2394.21  5030.0 2393.77  5040.0 2394.20  5050.0 2396.13  5060.0 2397.12
  5090.0 2399.00  5110.0 2399.64  5140.0 2399.83  5170.0 2399.49  5190.0 2400.08
  5200.0 2400.88  5240.0 2401.41  5259.3 2401.12  5264.3 2402.09  5310.1 2402.49
  5360.1 2404.47  5390.1 2406.58  5410.1 2408.67  5431.9 2408.55  5447.0 2408.31
#Mann=4,-1,0
  4750.0   0.035       0  4987.5   0.035       0  4992.6   0.035       0
  5431.9   0.045       0
Bank Sta=4987.5,4992.6
Exp/Cntr=0.3,0.1

Type RM Length L Ch R = 1,7128,459,459,459
BEGIN DESCRIPTION:
UCFB HW Trib 24 12.3
END DESCRIPTION:
XS GIS Cut Line= 3
      1272540.93      6944612.76      1272555.00      6944288.00
      1272565.18      6944001.45
#Sta/Elev= 30
  4674.9 2408.88  4739.7 2408.15  4769.8 2406.90  4779.8 2406.15  4789.8 2405.97
  4809.8 2404.56  4829.8 2403.77  4879.7 2400.38  4889.9 2398.78  4909.9 2397.52
  4929.9 2395.76  4959.9 2392.07  4979.9 2390.83  4987.4 2389.90  4987.8 2389.40
  4992.2 2389.40  4992.6 2389.90  4997.5 2390.64  5020.0 2391.45  5050.0 2394.36
  5060.0 2395.83  5110.0 2399.84  5137.9 2401.79  5142.9 2401.74  5170.1 2403.14
  5190.1 2404.64  5210.1 2405.26  5226.0 2406.42  5270.1 2408.64  5286.7 2408.57
#Mann=4,-1,0
  4674.9   0.035       0  4987.4   0.035       0  4992.6   0.035       0
  5226.0   0.045       0
Bank Sta=4987.4,4992.6
Exp/Cntr=0.3,0.1

Type RM Length L Ch R = 1,6669,463,463,463
BEGIN DESCRIPTION:
UCFB HW Trib 24 12.4
END DESCRIPTION:
XS GIS Cut Line= 3
      1272902.05      6944819.34      1272955.00      6944438.00
      1272907.47      6944021.00
#Sta/Elev= 30
  4615.0 2408.95  4646.6 2408.45  4666.8 2406.97  4677.4 2405.53  4727.4 2403.33
  4828.4 2396.13  4878.8 2393.89  4909.1 2392.05  4919.2 2392.19  4949.5 2390.88
  4959.1 2389.56  4979.8 2388.16  4997.5 2386.00  5002.5 2386.00  5007.5 2385.28
  5007.9 2384.78  5012.3 2384.78  5012.7 2385.28  5044.7 2386.67  5050.3 2387.98
  5060.4 2388.83  5080.5 2389.52  5223.6 2398.20  5281.8 2398.51  5301.9 2399.02
  5332.1 2400.98  5372.4 2402.48  5382.5 2403.64  5412.7 2405.88  5419.7 2405.51
#Mann=3,-1,0
  4615.0   0.035       0  5007.5   0.035       0  5012.7   0.035       0
Bank Sta=5007.5,5012.7
Exp/Cntr=0.3,0.1

Type RM Length L Ch R = 1,6206,649,649,649
BEGIN DESCRIPTION:
UCFB HW Trib 24 12.5
END DESCRIPTION:
XS GIS Cut Line= 5
      1273580.00      6944263.00      1273306.55      6944188.00
      1273255.00      6944188.00      1273186.76      6944188.00
      1272913.68      6943992.14
#Sta/Elev= 30
  4664.9 2396.02  4670.1 2395.07  4778.6 2388.61  4875.4 2385.79  4960.0 2384.90
  4980.0 2383.16  4990.0 2370.98  4997.5 2355.70  5002.5 2355.70  5010.0 2350.26
  5017.4 2349.55  5017.8 2349.05  5022.6 2349.55  5030.0 2350.38  5040.0 2355.73
  5050.0 2366.12  5060.0 2370.70  5066.6 2377.64  5072.4 2377.64  5076.7 2382.69
  5102.2 2385.10  5112.3 2385.42  5119.6 2386.65  5205.8 2389.79  5220.8 2391.20
  5278.1 2395.75  5313.7 2400.51  5334.6 2400.80  5390.9 2403.96  5404.3 2405.24
#Mann=7,-1,0
  4664.9   0.035       0  4875.4    0.07       0  5017.4    0.07       0
  5022.6    0.07       0  5102.2   0.035       0  5220.8    0.07       0
  5390.9   0.035       0
Bank Sta=5017.4,5022.6
Exp/Cntr=0.3,0.1