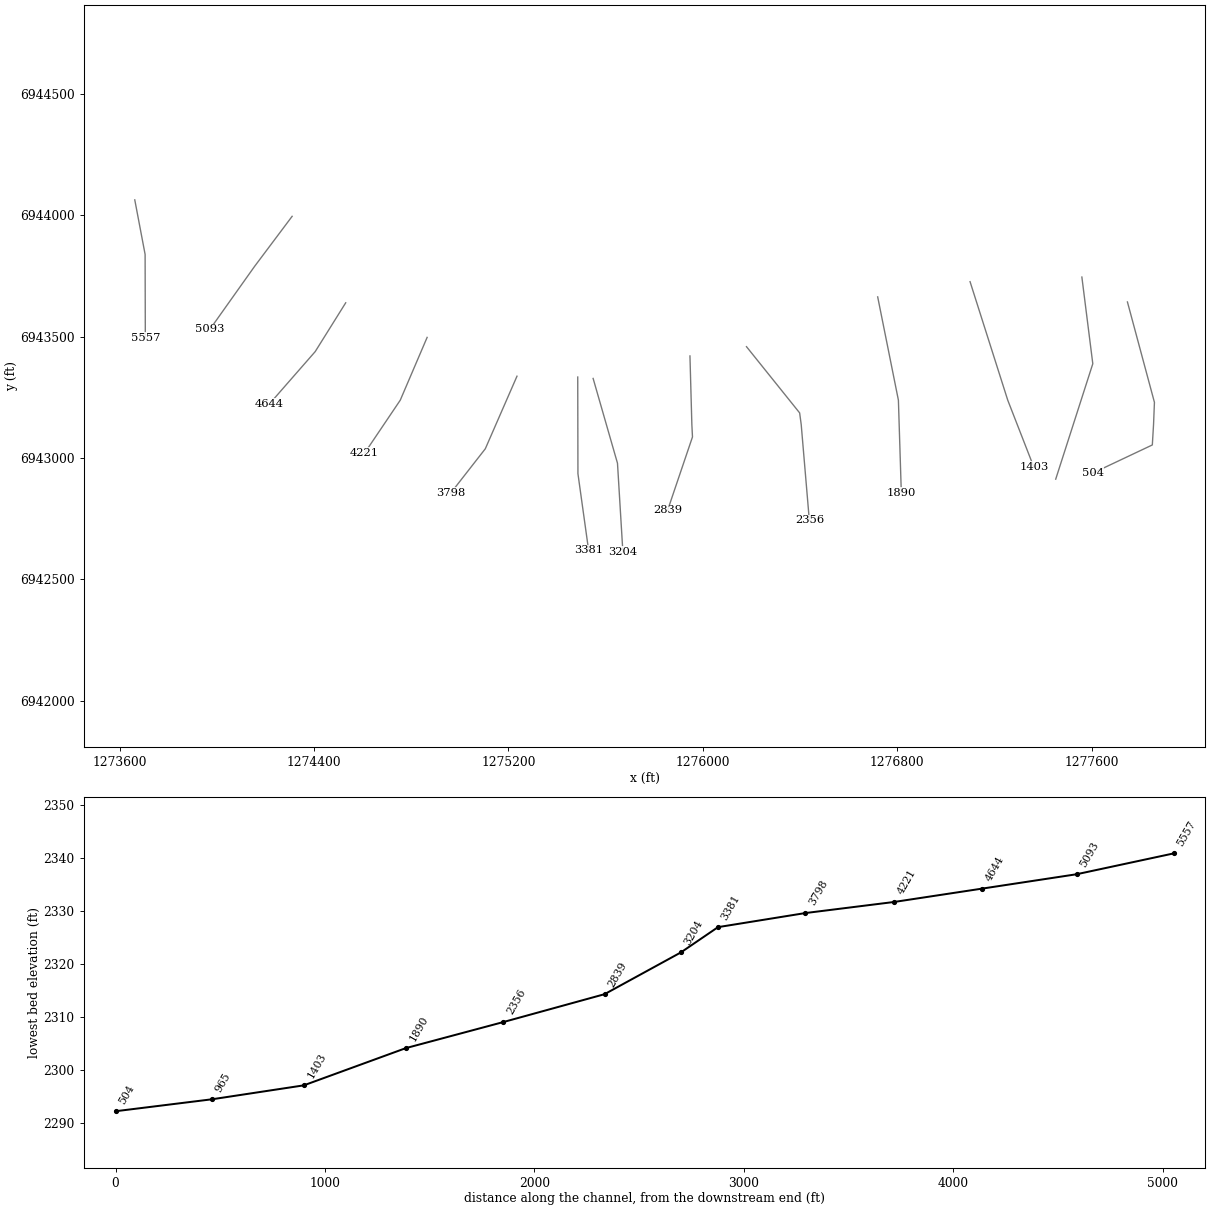
HEC-RAS study UCFB HW Trib 24.prj: UCFB HW Trib 24 Base Level Engineering

--- UCFB HW Trib 24.g01 (geometry) --- (continued)

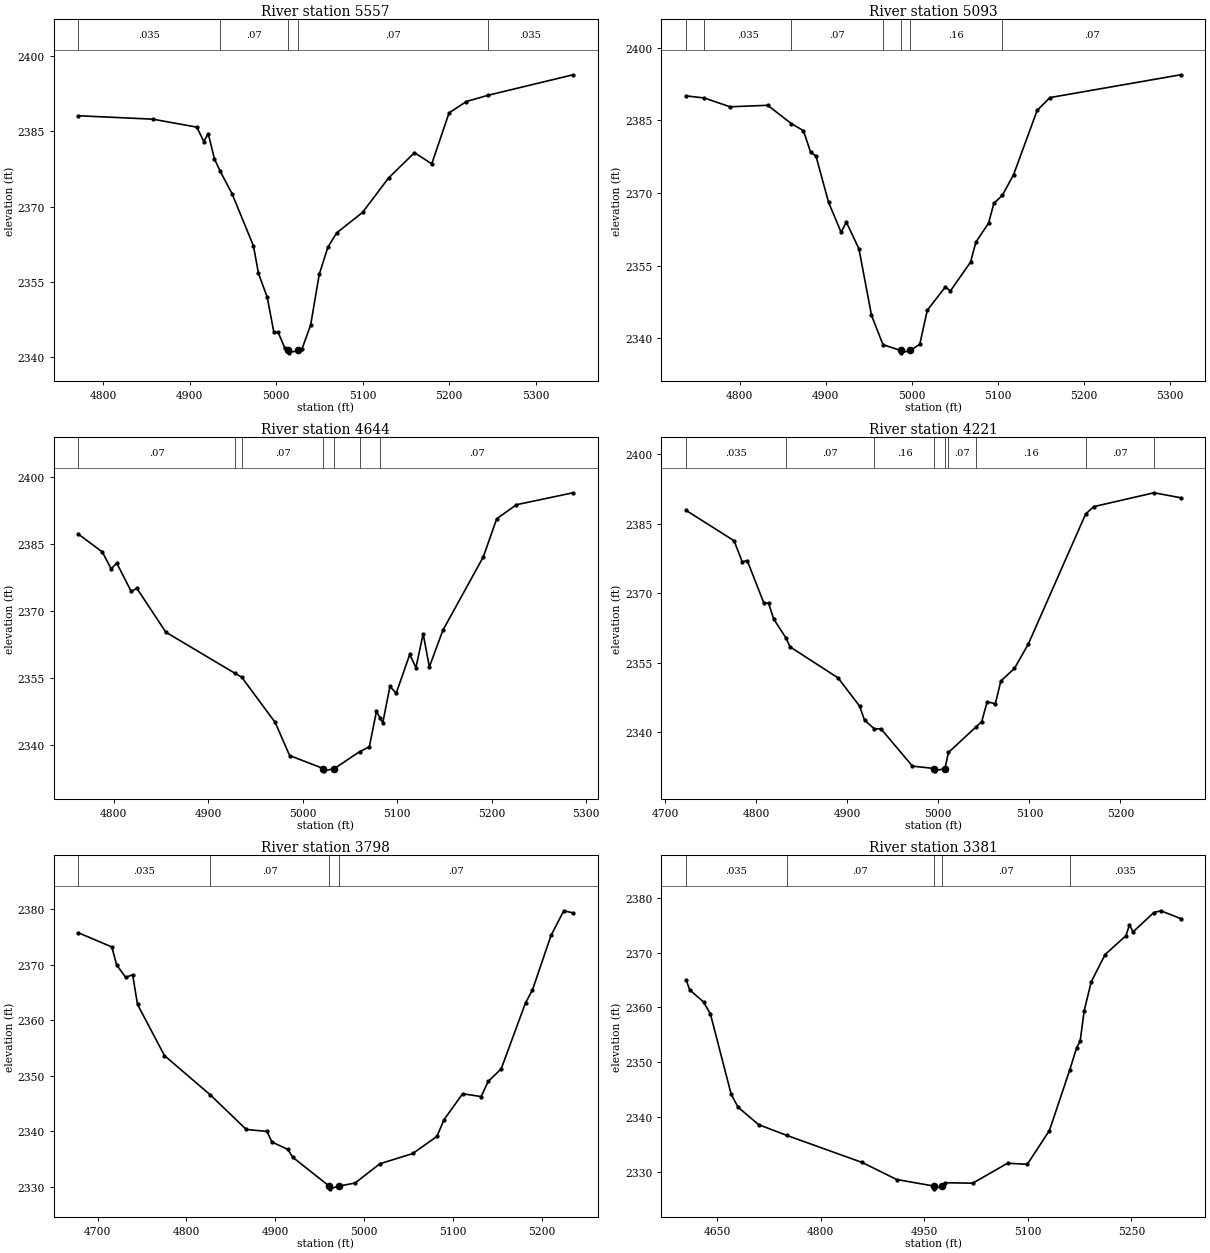
Type RM Length L Ch R = 1,5557,464,464,464
BEGIN DESCRIPTION:
UCFB HW Trib 24 12.0
END DESCRIPTION:
XS GIS Cut Line= 3
      1273662.46      6944062.42      1273705.00      6943838.00
      1273705.86      6943494.71
#Sta/Elev= 30
  4771.6 2388.13  4857.5 2387.45  4908.4 2385.86  4916.5 2383.00  4921.6 2384.57
  4928.8 2379.53  4935.5 2377.06  4949.1 2372.61  4973.9 2362.21  4979.7 2356.72
  4989.8 2351.99  4997.5 2344.97  5002.5 2344.97  5010.0 2341.90  5014.3 2341.41
  5014.8 2340.91  5025.8 2341.41  5030.0 2341.68  5040.0 2346.45  5050.0 2356.58
  5060.0 2361.98  5070.0 2364.79  5100.0 2368.88  5130.0 2375.72  5160.0 2380.78
  5180.0 2378.55  5200.0 2388.71  5220.0 2390.96  5244.7 2392.19  5343.3 2396.29
#Mann=5,-1,0
  4771.6   0.035       0  4935.5    0.07       0  5014.3    0.07       0
  5025.8    0.07       0  5244.7   0.035       0
Bank Sta=5014.3,5025.8
Exp/Cntr=0.3,0.1

Type RM Length L Ch R = 1,5093,449,449,449
BEGIN DESCRIPTION:
UCFB HW Trib 24 11.0
END DESCRIPTION:
XS GIS Cut Line= 3
      1274310.04      6943994.75      1274155.00      6943788.00
      1273971.47      6943529.44
#Sta/Elev= 30
  4737.5 2390.03  4758.6 2389.60  4788.6 2387.78  4832.4 2388.09  4860.0 2384.30
  4874.0 2382.85  4882.4 2378.38  4888.6 2377.61  4903.2 2368.10  4917.8 2361.88
  4924.0 2363.95  4938.6 2358.46  4953.2 2344.73  4966.6 2338.65  4987.0 2337.47
  4987.5 2336.97  4998.5 2337.47  5009.4 2338.74  5018.1 2345.75  5039.0 2350.55
  5045.1 2349.77  5068.5 2355.71  5074.7 2359.85  5089.4 2363.74  5095.6 2367.84
  5105.5 2369.50  5118.6 2373.79  5146.0 2387.04  5160.8 2389.68  5313.0 2394.39
#Mann=7,-1,0
  4737.5    0.07       0  4758.6   0.035       0  4860.0    0.07       0
  4966.6    0.16       0  4987.0    0.07       0  4998.5    0.16       0
  5105.5    0.07       0
Bank Sta=4987,4998.5
Exp/Cntr=0.3,0.1

Type RM Length L Ch R = 1,4644,423,423,423
BEGIN DESCRIPTION:
UCFB HW Trib 24 10.0
END DESCRIPTION:
XS GIS Cut Line= 3
      1274530.52      6943638.84      1274405.00      6943438.00
      1274216.64      6943222.58
#Sta/Elev= 30
  4762.9 2387.27  4788.1 2383.28  4797.5 2379.49  4803.4 2380.79  4818.7 2374.43
  4824.6 2375.15  4855.3 2365.32  4928.0 2356.16  4935.5 2355.25  4970.9 2345.11
  4986.2 2337.70  5022.0 2334.77  5022.5 2334.27  5033.5 2334.77  5060.2 2338.56
  5070.5 2339.65  5078.0 2347.59  5082.1 2346.02  5084.7 2345.02  5092.3 2353.18
  5098.9 2351.63  5113.2 2360.33  5119.8 2357.39  5127.4 2364.96  5134.0 2357.54
  5148.3 2365.76  5191.0 2382.17  5205.2 2390.71  5226.1 2393.86  5285.9 2396.53
#Mann=7,-1,0
  4762.9    0.07       0  4928.0    0.16       0  4935.5    0.07       0
  5022.0    0.07       0  5033.5    0.07       0  5060.2    0.16       0
  5082.1    0.07       0
Bank Sta=5022,5033.5
Exp/Cntr=0.3,0.1

Type RM Length L Ch R = 1,4221,423,423,423
BEGIN DESCRIPTION:
UCFB HW Trib 24 9.0
END DESCRIPTION:
XS GIS Cut Line= 3
      1274865.59      6943496.48      1274755.00      6943238.00
      1274608.63      6943020.76
#Sta/Elev= 30
  4723.0 2387.84  4775.7 2381.30  4784.6 2376.76  4790.1 2377.04  4808.2 2367.98
  4813.6 2367.83  4819.2 2364.44  4832.5 2360.40  4837.2 2358.44  4889.8 2351.76
  4913.4 2345.71  4918.9 2342.67  4929.8 2340.76  4937.0 2340.78  4971.5 2332.75
  4995.7 2332.23  4996.2 2331.73  5007.2 2332.23  5011.1 2335.69  5041.4 2341.21
  5047.6 2342.33  5053.6 2346.61  5062.6 2346.19  5068.6 2351.08  5083.6 2353.81
  5098.6 2358.98  5161.7 2387.04  5170.5 2388.65  5236.8 2391.64  5266.1 2390.57
#Mann=9,-1,0
  4723.0   0.035       0  4832.5    0.07       0  4929.8    0.16       0
  4995.7    0.07       0  5007.2    0.16       0  5011.1    0.07       0
  5041.4    0.16       0  5161.7    0.07       0  5236.8   0.035       0
Bank Sta=4995.7,5007.2
Exp/Cntr=0.3,0.1

Type RM Length L Ch R = 1,3798,417,417,417
BEGIN DESCRIPTION:
UCFB HW Trib 24 8.0
END DESCRIPTION:
XS GIS Cut Line= 3
      1275235.36      6943336.72      1275105.00      6943038.00
      1274962.81      6942855.85
#Sta/Elev= 30
  4678.4 2375.79  4716.0 2373.24  4721.4 2370.00  4731.6 2367.74  4739.4 2368.24
  4744.9 2362.89  4775.2 2353.67  4827.0 2346.56  4867.4 2340.34  4890.8 2339.99
  4896.2 2338.09  4914.2 2336.74  4919.7 2335.34  4960.7 2330.14  4961.2 2329.64
  4972.3 2330.14  4989.9 2330.69  5017.9 2334.16  5055.0 2336.01  5082.1 2339.09
  5090.2 2342.13  5111.1 2346.78  5131.9 2346.27  5140.0 2349.03  5154.5 2351.26
  5181.9 2363.17  5189.7 2365.49  5210.6 2375.31  5225.0 2379.76  5235.4 2379.38
#Mann=4,-1,0
  4678.4   0.035       0  4827.0    0.07       0  4960.7    0.07       0
  4972.3    0.07       0
Bank Sta=4960.7,4972.3
Exp/Cntr=0.3,0.1

Type RM Length L Ch R = 1,3381,177,177,177
BEGIN DESCRIPTION:
UCFB HW Trib 24 7.0
END DESCRIPTION:
XS GIS Cut Line= 3
      1275485.37      6943333.25      1275486.20      6942935.49
      1275530.23      6942619.50
#Sta/Elev= 30
  4604.7 2365.02  4609.9 2363.21  4629.9 2361.01  4639.9 2358.82  4669.9 2344.25
  4679.9 2341.85  4709.9 2338.66  4750.4 2336.72  4859.9 2331.78  4909.9 2328.68
  4964.0 2327.48  4964.5 2326.98  4975.8 2327.48  4979.9 2328.09  5020.1 2328.01
  5070.6 2331.64  5099.2 2331.45  5131.2 2337.58  5160.7 2348.62  5170.7 2352.67
  5175.8 2353.88  5181.7 2359.44  5191.8 2364.66  5212.0 2369.64  5242.2 2373.07
  5247.3 2375.06  5252.4 2373.75  5282.6 2377.28  5292.7 2377.60  5321.5 2376.18
#Mann=5,-1,0
  4604.7   0.035       0  4750.4    0.07       0  4964.0    0.07       0
  4975.8    0.07       0  5160.7   0.035       0
Bank Sta=4964,4975.8
Exp/Cntr=0.3,0.1

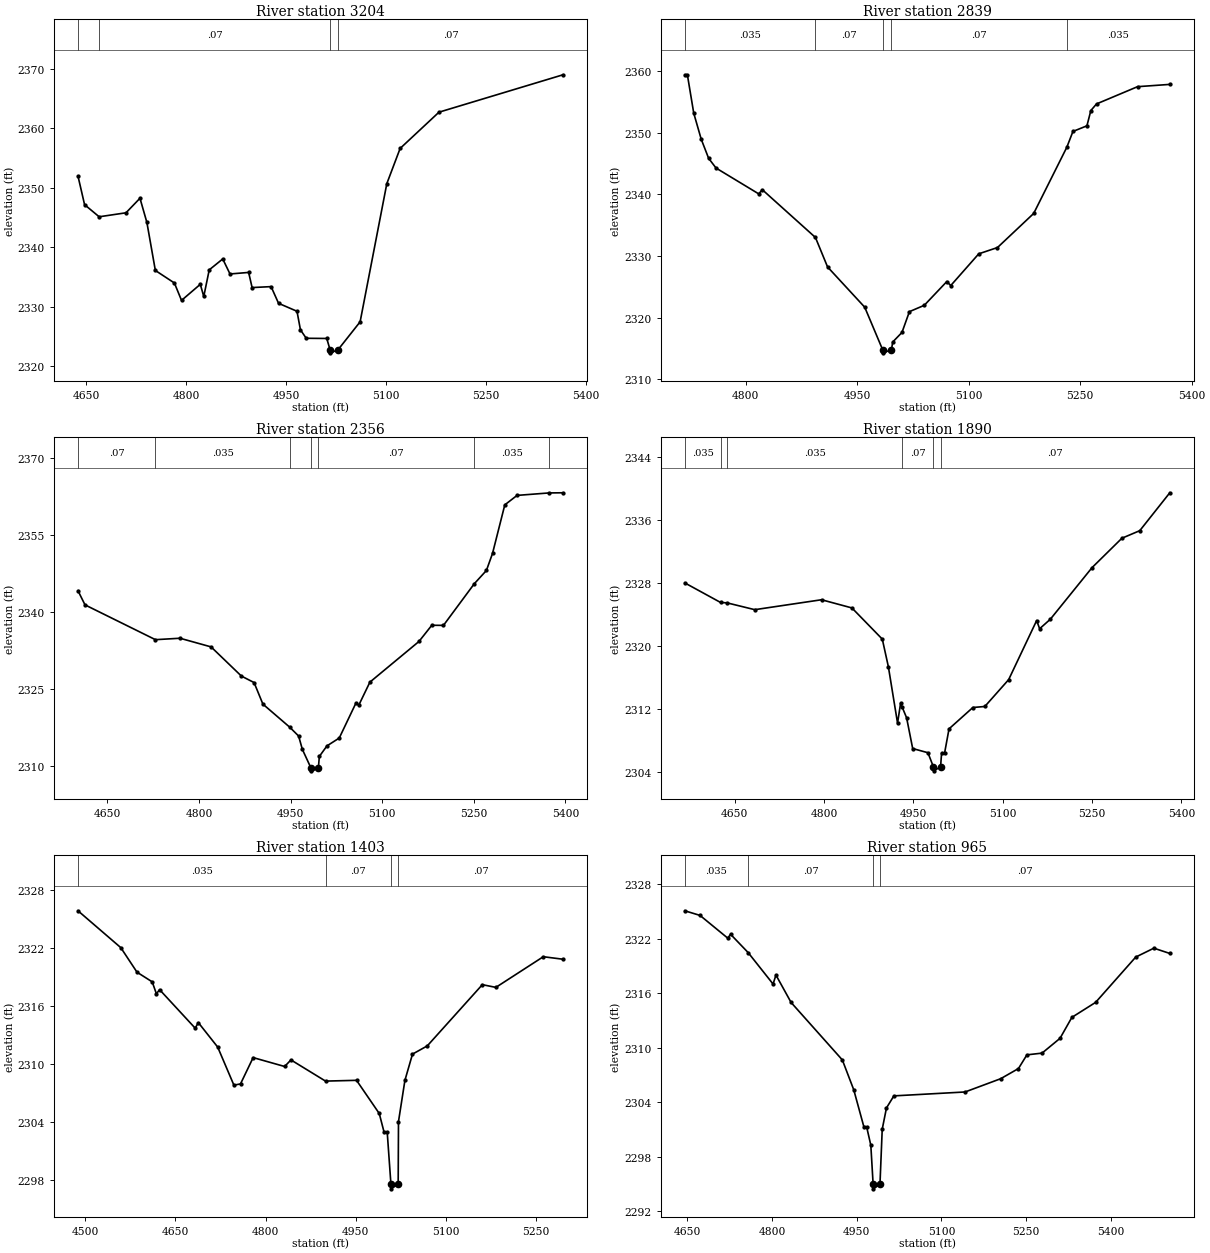
Type RM Length L Ch R = 1,3204,365,365,365
BEGIN DESCRIPTION:
UCFB HW Trib 24 6.5
END DESCRIPTION:
XS GIS Cut Line= 3
      1275548.69      6943327.46      1275648.96      6942978.46
      1275671.10      6942613.85
#Sta/Elev= 30
  4637.7 2351.98  4647.6 2347.16  4669.5 2345.12  4709.8 2345.79  4730.8 2348.24
  4741.2 2344.16  4753.9 2336.08  4782.5 2333.97  4793.2 2331.04  4821.4 2333.75
  4826.6 2331.70  4834.8 2336.18  4855.1 2338.02  4866.0 2335.49  4894.0 2335.75
  4899.2 2333.20  4927.7 2333.36  4938.9 2330.55  4966.6 2329.21  4971.8 2326.08
  4980.5 2324.66  5011.3 2324.63  5016.3 2322.71  5016.8 2322.21  5028.1 2322.71
  5061.4 2327.43  5101.5 2350.70  5121.5 2356.63  5179.8 2362.73  5366.1 2369.03
#Mann=4,-1,0
  4637.7   0.035       0  4669.5    0.07       0  5016.3    0.07       0
  5028.1    0.07       0
Bank Sta=5016.3,5028.1
Exp/Cntr=0.3,0.1

Type RM Length L Ch R = 1,2839,483,483,483
BEGIN DESCRIPTION:
UCFB HW Trib 24 6.0
END DESCRIPTION:
XS GIS Cut Line= 4
      1275947.18      6943420.05      1275955.00      6943138.00
      1275957.59      6943086.75      1275855.15      6942784.62
#Sta/Elev= 30
  4718.0 2359.41  4721.5 2359.41  4730.1 2353.17  4740.1 2348.97  4750.1 2345.86
  4760.1 2344.28  4817.4 2340.10  4822.4 2340.76  4893.8 2333.02  4910.1 2328.24
  4960.1 2321.71  4984.2 2314.81  4984.7 2314.31  4996.1 2314.81  4997.7 2316.06
  5010.2 2317.62  5020.2 2320.99  5040.2 2322.02  5070.6 2325.88  5075.8 2325.22
  5113.5 2330.37  5138.7 2331.39  5187.4 2336.92  5232.0 2347.66  5240.2 2350.22
  5259.0 2351.13  5264.3 2353.61  5271.9 2354.68  5327.1 2357.48  5370.5 2357.85
#Mann=5,-1,0
  4718.0   0.035       0  4893.8    0.07       0  4984.2    0.07       0
  4996.1    0.07       0  5232.0   0.035       0
Bank Sta=4984.2,4996.1
Exp/Cntr=0.3,0.1

Type RM Length L Ch R = 1,2356,466,466,466
BEGIN DESCRIPTION:
UCFB HW Trib 24 5.0
END DESCRIPTION:
XS GIS Cut Line= 4
      1276179.83      6943458.25      1276398.57      6943185.70
      1276405.00      6943138.00      1276438.50      6942743.02
#Sta/Elev= 30
  4602.0 2344.19  4613.5 2341.43  4728.8 2334.64  4769.0 2334.92  4819.9 2333.23
  4869.5 2327.54  4890.3 2326.27  4904.7 2322.07  4948.5 2317.58  4963.2 2315.84
  4969.3 2313.24  4983.6 2309.55  4984.1 2309.05  4995.5 2309.55  4997.1 2311.86
  5009.6 2313.92  5029.7 2315.45  5056.8 2322.22  5061.8 2321.89  5079.9 2326.36
  5160.2 2334.29  5181.2 2337.45  5200.3 2337.43  5250.8 2345.56  5270.6 2348.14
  5280.6 2351.46  5300.7 2360.94  5320.8 2362.79  5373.1 2363.27  5396.0 2363.30
#Mann=7,-1,0
  4602.0    0.07       0  4728.8   0.035       0  4948.5    0.07       0
  4983.6    0.07       0  4995.5    0.07       0  5250.8   0.035       0
  5373.1    0.07       0
Bank Sta=4983.6,4995.5
Exp/Cntr=0.3,0.1

Type RM Length L Ch R = 1,1890,487,487,487
BEGIN DESCRIPTION:
UCFB HW Trib 24 4.0
END DESCRIPTION:
XS GIS Cut Line= 3
      1276719.74      6943663.16      1276805.00      6943238.00
      1276816.97      6942857.61
#Sta/Elev= 30
  4566.4 2327.98  4626.4 2325.50  4637.6 2325.44  4683.9 2324.58  4796.0 2325.84
  4847.0 2324.80  4898.0 2320.84  4908.2 2317.33  4923.6 2310.17  4928.7 2312.70
  4931.3 2312.22  4938.8 2310.85  4949.0 2306.95  4974.6 2306.42  4983.8 2304.62
  4984.3 2304.12  4995.8 2304.62  4997.5 2306.36  5002.5 2306.36  5010.0 2309.45
  5050.0 2312.16  5070.1 2312.29  5110.1 2315.70  5157.1 2323.20  5162.1 2322.16
  5180.1 2323.37  5250.1 2329.92  5300.2 2333.65  5330.2 2334.61  5380.6 2339.42
#Mann=6,-1,0
  4566.4   0.035       0  4626.4    0.07       0  4637.6   0.035       0
  4931.3    0.07       0  4983.8    0.07       0  4995.8    0.07       0
Bank Sta=4983.8,4995.8
Exp/Cntr=0.3,0.1

Type RM Length L Ch R = 1,1403,438,438,438
BEGIN DESCRIPTION:
UCFB HW Trib 24 3.0
END DESCRIPTION:
XS GIS Cut Line= 3
      1277099.94      6943725.68      1277255.00      6943238.00
      1277362.12      6942962.96
#Sta/Elev= 30
  4488.0 2325.84  4559.2 2322.03  4586.2 2319.49  4611.5 2318.49  4618.5 2317.25
  4623.7 2317.69  4683.0 2313.70  4688.2 2314.28  4720.4 2311.75  4747.4 2307.81
  4758.4 2307.94  4779.4 2310.66  4831.8 2309.74  4842.3 2310.42  4899.8 2308.23
  4951.4 2308.31  4989.2 2304.88  4997.1 2302.98  5002.4 2302.98  5008.6 2297.59
  5009.1 2297.09  5020.7 2297.59  5021.2 2304.04  5031.9 2308.31  5044.5 2311.02
  5069.1 2311.87  5160.7 2318.20  5183.2 2317.92  5262.1 2321.09  5294.9 2320.83
#Mann=4,-1,0
  4488.0   0.035       0  4899.8    0.07       0  5008.6    0.07       0
  5020.7    0.07       0
Bank Sta=5008.6,5020.7
Exp/Cntr=0.3,0.1

Type RM Length L Ch R = 1,965,461,461,461
BEGIN DESCRIPTION:
UCFB HW Trib 24 2.0
END DESCRIPTION:
XS GIS Cut Line= 3
      1277560.02      6943744.74      1277605.00      6943388.00
      1277452.38      6942912.98
#Sta/Elev= 30
  4645.6 2325.09  4672.6 2324.58  4721.6 2322.08  4726.7 2322.50  4757.7 2320.49
  4801.9 2317.02  4807.0 2318.01  4833.8 2314.99  4924.5 2308.66  4944.7 2305.37
  4962.5 2301.32  4967.5 2301.29  4974.9 2299.27  4979.0 2294.96  4979.5 2294.46
  4991.1 2294.96  4995.1 2301.03  5002.6 2303.37  5015.7 2304.70  5141.7 2305.13
  5204.7 2306.59  5236.2 2307.71  5251.2 2309.22  5278.0 2309.41  5309.8 2311.04
  5330.8 2313.35  5372.8 2315.00  5443.8 2319.99  5475.9 2320.97  5504.1 2320.39
#Mann=4,-1,0
  4645.6   0.035       0  4757.7    0.07       0  4979.0    0.07       0
  4991.1    0.07       0
Bank Sta=4979,4991.1
Exp/Cntr=0.3,0.1

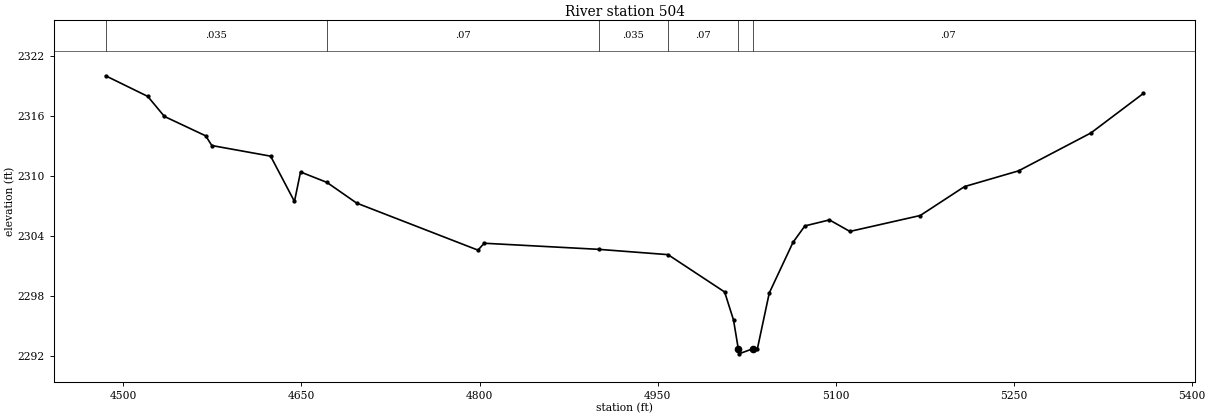
Type RM Length L Ch R = 1,504,0,0,0
BEGIN DESCRIPTION:
UCFB HW Trib 24 1.0
END DESCRIPTION:
XS GIS Cut Line= 5
      1277747.53      6943642.27      1277858.64      6943229.11
      1277855.00      6943138.00      1277849.96      6943053.76
      1277605.04      6942938.02
#Sta/Elev= 30
  4485.0 2319.98  4520.5 2317.92  4534.5 2315.92  4569.3 2313.98  4574.5 2313.01
  4624.0 2311.95  4644.1 2307.42  4649.2 2310.37  4671.4 2309.33  4696.5 2307.26
  4798.7 2302.56  4803.9 2303.25  4900.4 2302.64  4958.8 2302.11  5006.5 2298.38
  5014.0 2295.57  5018.0 2292.70  5018.5 2292.20  5030.1 2292.70  5034.1 2292.71
  5044.1 2298.28  5064.1 2303.34  5074.1 2304.98  5094.8 2305.58  5112.0 2304.43
  5171.3 2306.02  5208.6 2308.91  5254.1 2310.48  5315.1 2314.27  5359.3 2318.22
#Mann=6,-1,0
  4485.0   0.035       0  4671.4    0.07       0  4900.4   0.035       0
  4958.8    0.07       0  5018.0    0.07       0  5030.1    0.07       0
Bank Sta=5018,5030.1
Exp/Cntr=0.3,0.1

Chan Stop Cuts=-1