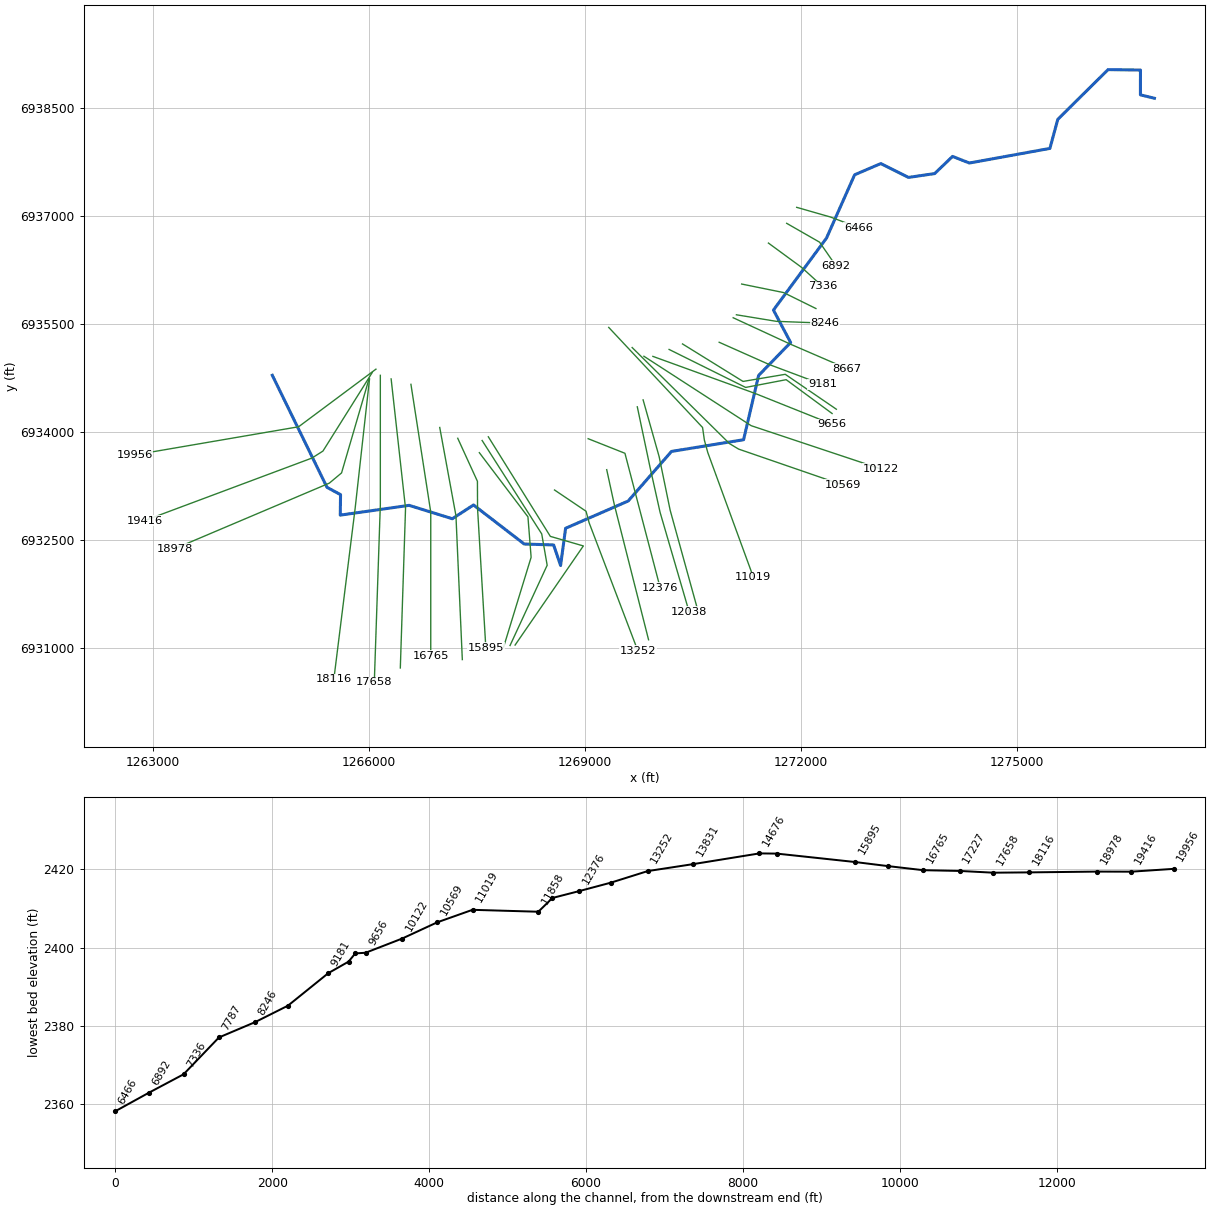
--- UCFB HW Trib 25.prj (project) ---

Proj Title=UCFB HW Trib 25 Base Level Engineering
Current Plan=p01
Default Exp/Contr=0.3,0.1
English Units
Geom File=g01
Flow File=f01
Plan File=p01
BEGIN DESCRIPTION:
UCFB HW Trib 25
END DESCRIPTION:

--- UCFB HW Trib 25.p01 (plan) ---

Plan Title=Multiple Run
Short Identifier=Multiple
Geom File=g01
Flow File=f01
Subcritical Flow
K Sum by GR= 0
Std Step Tol= 0.01
Critical Tol= 0.01
Num of Std Step Trials= 20
Max Error Tol= 0.3
Flow Tol Ratio= 0.001
Split Flow NTrial= 30
Split Flow Tol= 0.02
Split Flow Ratio= 0.02
Log Output Level= 0
Friction Slope Method= 1
Unsteady Friction Slope Method= 2
Unsteady Bridges Friction Slope Method= 1
Parabolic Critical Depth
Global Vel Dist=  1 , 1 , 1
Global Log Level= 0
CheckData=True
Encroach Param= -1, 0, 0, 0
BEGIN DESCRIPTION:
Multiple Run
END DESCRIPTION:

--- UCFB HW Trib 25.f01 (steady flow) ---

Flow Title=Multiple
Number of Profiles=7
Profile Names=10-year,25-year,50-year,1pct_min,100-year,1pct_plu,500-year
River Rch & RM= UCFB HW Trib 25,Reach-1,19956
     207     279     336     201     401     799     577
River Rch & RM= UCFB HW Trib 25,Reach-1,17658
     274     375     456     275     548    1094     803
River Rch & RM= UCFB HW Trib 25,Reach-1,10122
     406     573     712     438     874    1744    1336
River Rch & RM= UCFB HW Trib 25,Reach-1,7336
     535     770     969     604    1206    2406    1892
River Rch & RM= UCFB HW Trib 25,Reach-1,2811
     573     829    1047     655    1307    2609    2067
Boundary for River Rch & Prof#=UCFB HW Trib 25,Reach-1,1
Up Type=0
Dn Type=3
Dn Slope=0.005
Boundary for River Rch & Prof#=UCFB HW Trib 25,Reach-1,2
Up Type=0
Dn Type=3
Dn Slope=0.005
Boundary for River Rch & Prof#=UCFB HW Trib 25,Reach-1,3
Up Type=0
Dn Type=3
Dn Slope=0.005
Boundary for River Rch & Prof#=UCFB HW Trib 25,Reach-1,4
Up Type=0
Dn Type=3
Dn Slope=0.005
Boundary for River Rch & Prof#=UCFB HW Trib 25,Reach-1,5
Up Type=0
Dn Type=3
Dn Slope=0.005
Boundary for River Rch & Prof#=UCFB HW Trib 25,Reach-1,6
Up Type=0
Dn Type=3
Dn Slope=0.005
Boundary for River Rch & Prof#=UCFB HW Trib 25,Reach-1,7
Up Type=0
Dn Type=3
Dn Slope=0.005

--- UCFB HW Trib 25.g01 (geometry) ---

Geom Title=Existing Conditions

River Reach=UCFB HW Trib 25,Reach-1
Reach XY= 30
      1264655.00      6934788.00      1265414.29      6933231.31
      1265602.50      6933129.85      1265598.62      6932845.32
      1266555.00      6932980.88      1267155.21      6932794.99
      1267448.96      6932986.42      1268152.71      6932443.81
      1268561.39      6932430.66      1268658.41      6932145.38
      1268727.86      6932662.42      1269596.68      6933041.15
      1270198.50      6933730.27      1271199.56      6933893.19
      1271408.54      6934786.53      1271853.12      6935243.67
      1271614.41      6935694.62      1272351.84      6936696.34
      1272741.60      6937574.47      1273105.00      6937730.50
      1273489.64      6937537.90      1273853.54      6937591.52
      1274101.71      6937829.99      1274334.95      6937738.03
      1275453.38      6937941.12      1275562.81      6938344.19
      1276260.86      6939035.93      1276711.39      6939030.00
      1276710.28      6938685.29      1276905.00      6938638.00

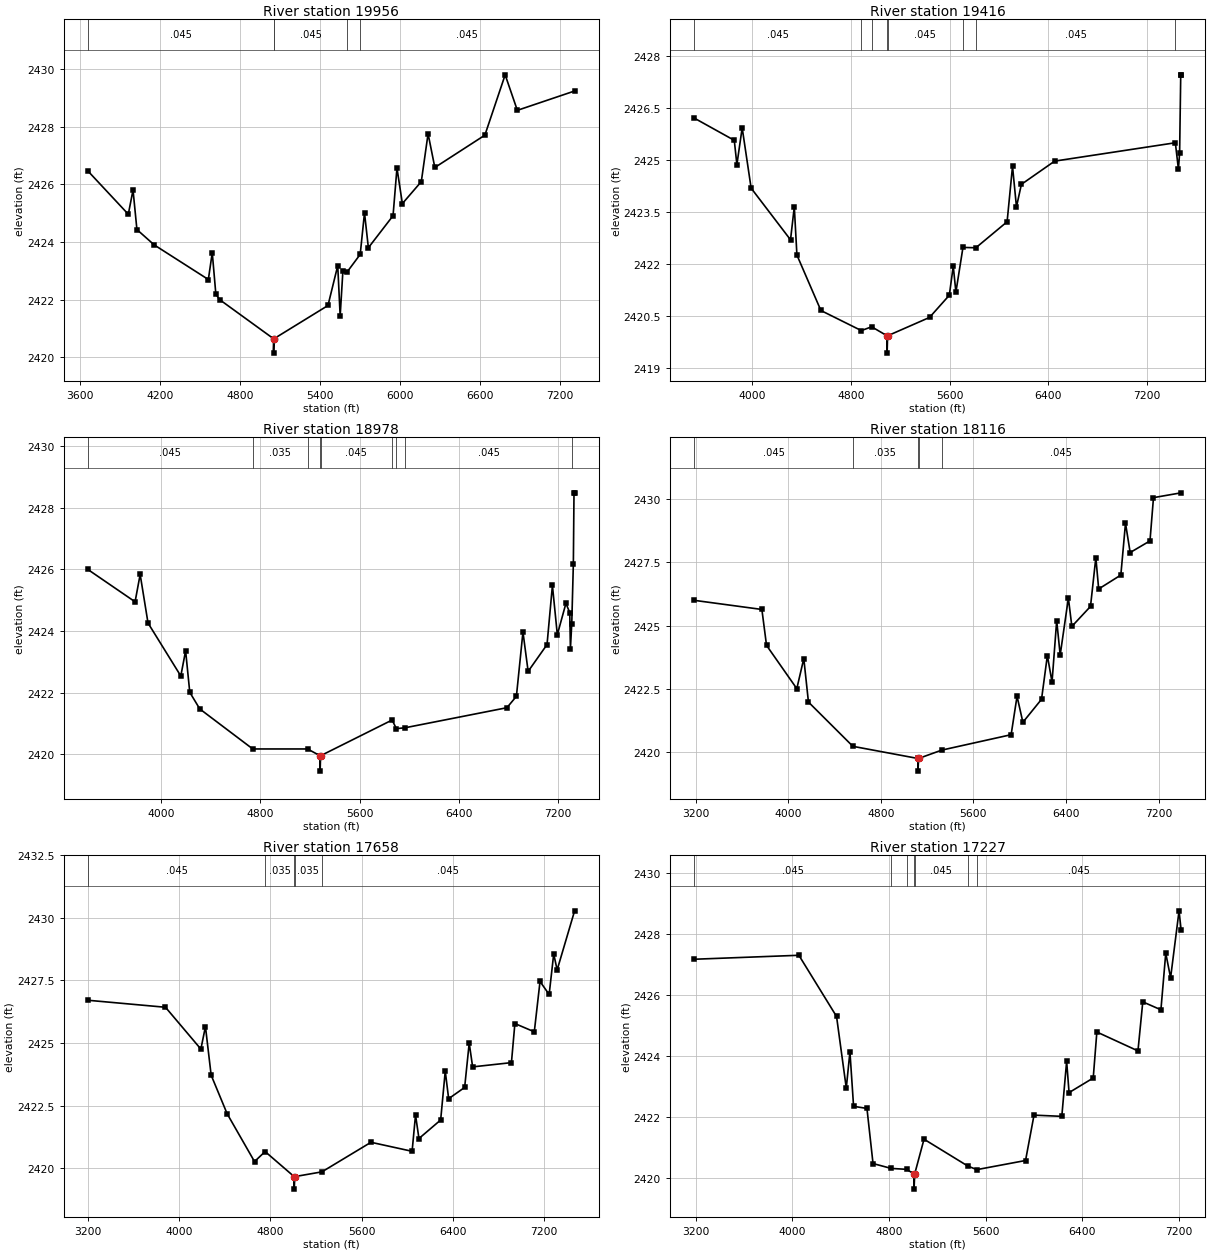
Type RM Length L Ch R = 1,19956,540,540,540
BEGIN DESCRIPTION:
UCFB HW Trib 25 35.0
END DESCRIPTION:
XS GIS Cut Line= 3
      1266094.02      6934873.62      1265019.99      6934073.00
      1262741.53      6933681.82
#Sta/Elev= 30
  3660.4 2426.46  3963.7 2424.96  3999.1 2425.80  4028.3 2424.43  4157.6 2423.90
  4564.2 2422.70  4593.4 2423.63  4620.5 2422.19  4649.7 2422.00  5052.9 2420.65
  5053.2 2420.15  5056.9 2420.65  5461.6 2421.80  5534.8 2423.18  5553.0 2421.44
  5573.3 2422.98  5603.4 2422.95  5703.3 2423.57  5735.6 2425.01  5764.6 2423.80
  5949.7 2424.91  5979.1 2426.56  6019.7 2425.33  6161.7 2426.09  6212.5 2427.75
  6263.2 2426.58  6638.6 2427.70  6790.8 2429.79  6882.1 2428.56  7311.8 2429.23
#Mann=5,-1,0
  3660.4   0.045       0  5052.9   0.045       0  5056.9   0.045       0
  5603.4   0.035       0  5703.3   0.045       0
Bank Sta=5052.9,5056.9
Exp/Cntr=0.3,0.1

Type RM Length L Ch R = 1,19416,438,438,438
BEGIN DESCRIPTION:
UCFB HW Trib 25 34.0
END DESCRIPTION:
XS GIS Cut Line= 4
      1266042.42      6934826.64      1265358.11      6933735.33
      1265205.00      6933638.00      1262884.76      6932770.37
#Sta/Elev= 30
  3530.2 2426.21  3854.0 2425.57  3875.2 2424.87  3918.1 2425.93  3990.7 2424.19
  4310.0 2422.70  4340.7 2423.65  4361.9 2422.26  4556.3 2420.66  4884.4 2420.08
  4967.8 2420.19  5093.1 2419.93  5093.3 2419.43  5097.1 2419.93  5437.2 2420.46
  5597.6 2421.10  5629.6 2421.94  5651.0 2421.19  5708.3 2422.48  5812.9 2422.47
  6066.2 2423.22  6110.1 2424.82  6142.1 2423.65  6182.0 2424.30  6451.7 2424.97
  7430.4 2425.50  7455.3 2424.74  7465.0 2425.20  7474.1 2427.46  7476.9 2427.46
#Mann=8,-1,0
  3530.2   0.045       0  4884.4   0.035       0  4967.8   0.045       0
  5093.1   0.045       0  5097.1   0.045       0  5708.3   0.035       0
  5812.9   0.045       0  7430.4   0.063       0
Bank Sta=5093.1,5097.1
Exp/Cntr=0.3,0.1

Type RM Length L Ch R = 1,18978,862,862,862
BEGIN DESCRIPTION:
UCFB HW Trib 25 33.0
END DESCRIPTION:
XS GIS Cut Line= 4
      1265999.19      6934742.80      1265616.36      6933431.51
      1265446.96      6933289.79      1263300.54      6932379.16
#Sta/Elev= 30
  3413.1 2426.00  3793.1 2424.95  3834.0 2425.84  3897.3 2424.26  4161.2 2422.54
  4199.9 2423.36  4233.4 2422.01  4314.0 2421.47  4740.6 2420.17  5181.4 2420.17
  5282.5 2419.95  5282.8 2419.45  5286.6 2419.95  5862.4 2421.11  5896.7 2420.83
  5968.6 2420.86  6786.6 2421.51  6863.0 2421.88  6915.7 2423.97  6957.4 2422.69
  7109.5 2423.56  7152.9 2425.48  7192.4 2423.88  7261.6 2424.90  7292.4 2424.60
  7297.9 2423.43  7308.6 2424.24  7321.5 2426.19  7326.7 2428.49  7331.6 2428.49
#Mann=9,-1,0
  3413.1   0.045       0  4740.6   0.035       0  5181.4   0.045       0
  5282.5   0.035       0  5286.6   0.045       0  5862.4   0.035       0
  5896.7   0.063       0  5968.6   0.045       0  7308.6   0.063       0
Bank Sta=5282.5,5286.6
Exp/Cntr=0.3,0.1

Type RM Length L Ch R = 1,18116,458,458,458
BEGIN DESCRIPTION:
UCFB HW Trib 25 32.0
END DESCRIPTION:
XS GIS Cut Line= 3
      1266005.00      6934738.01      1265805.00      6932938.00
      1265509.08      6930561.34
#Sta/Elev= 30
  3189.0 2426.00  3772.6 2425.64  3812.8 2424.22  4074.4 2422.51  4134.8 2423.70
  4175.0 2421.98  4559.0 2420.23  5121.0 2419.75  5121.5 2419.25  5126.5 2419.75
  5326.4 2420.08  5926.5 2420.69  5977.6 2422.21  6028.0 2421.18  6189.2 2422.09
  6239.6 2423.82  6279.9 2422.77  6320.2 2425.20  6350.4 2423.84  6421.2 2426.09
  6451.2 2424.97  6612.4 2425.76  6658.5 2427.69  6683.0 2426.45  6874.5 2427.00
  6914.8 2429.05  6955.1 2427.89  7126.4 2428.35  7156.6 2430.06  7395.1 2430.25
#Mann=5,-1,0
  3189.0   0.045       0  4559.0   0.035       0  5121.0   0.035       0
  5126.5   0.035       0  5326.4   0.045       0
Bank Sta=5121,5126.5
Exp/Cntr=0.3,0.1

Type RM Length L Ch R = 1,17658,431,431,431
BEGIN DESCRIPTION:
UCFB HW Trib 25 31.0
END DESCRIPTION:
XS GIS Cut Line= 3
      1266155.00      6934788.01      1266155.00      6932988.00
      1266071.38      6930525.03
#Sta/Elev= 30
  3200.8 2426.71  3880.8 2426.43  4190.8 2424.76  4230.8 2425.66  4280.8 2423.72
  4420.8 2422.18  4660.8 2420.27  4753.6 2420.67  5007.9 2419.67  5008.4 2419.17
  5013.8 2419.67  5251.6 2419.86  5681.2 2421.04  6041.4 2420.68  6071.4 2422.13
  6101.4 2421.19  6291.6 2421.93  6331.8 2423.88  6361.6 2422.78  6501.7 2423.23
  6541.7 2425.00  6571.7 2424.05  6911.7 2424.22  6941.9 2425.78  7112.0 2425.45
  7162.1 2427.46  7242.1 2426.94  7282.1 2428.56  7312.1 2427.92  7465.2 2430.28
#Mann=5,-1,0
  3200.8   0.045       0  4753.6   0.035       0  5007.9   0.035       0
  5013.8   0.035       0  5251.6   0.045       0
Bank Sta=5007.9,5013.8
Exp/Cntr=0.3,0.1

Type RM Length L Ch R = 1,17227,462,462,462
BEGIN DESCRIPTION:
UCFB HW Trib 25 30.0
END DESCRIPTION:
XS GIS Cut Line= 3
      1266305.00      6934738.04      1266505.00      6932938.00
      1266432.55      6930721.21
#Sta/Elev= 30
  3188.9 2427.17  4054.2 2427.30  4366.1 2425.29  4446.6 2422.94  4476.8 2424.13
  4507.0 2422.34  4617.7 2422.27  4668.0 2420.46  4818.6 2420.30  4945.5 2420.27
  5007.0 2420.12  5007.5 2419.62  5013.0 2420.12  5090.1 2421.26  5451.8 2420.38
  5526.8 2420.26  5930.5 2420.56  6000.6 2422.05  6230.7 2422.01  6270.7 2423.82
  6290.7 2422.79  6490.8 2423.27  6520.8 2424.78  6861.0 2424.16  6901.0 2425.77
  7051.1 2425.51  7091.1 2427.37  7131.2 2426.56  7201.2 2428.76  7218.0 2428.14
#Mann=7,-1,0
  3188.9   0.045       0  4818.6   0.035       0  4945.5   0.045       0
  5007.0   0.045       0  5013.0   0.045       0  5451.8   0.035       0
  5526.8   0.045       0
Bank Sta=5007,5013
Exp/Cntr=0.3,0.1

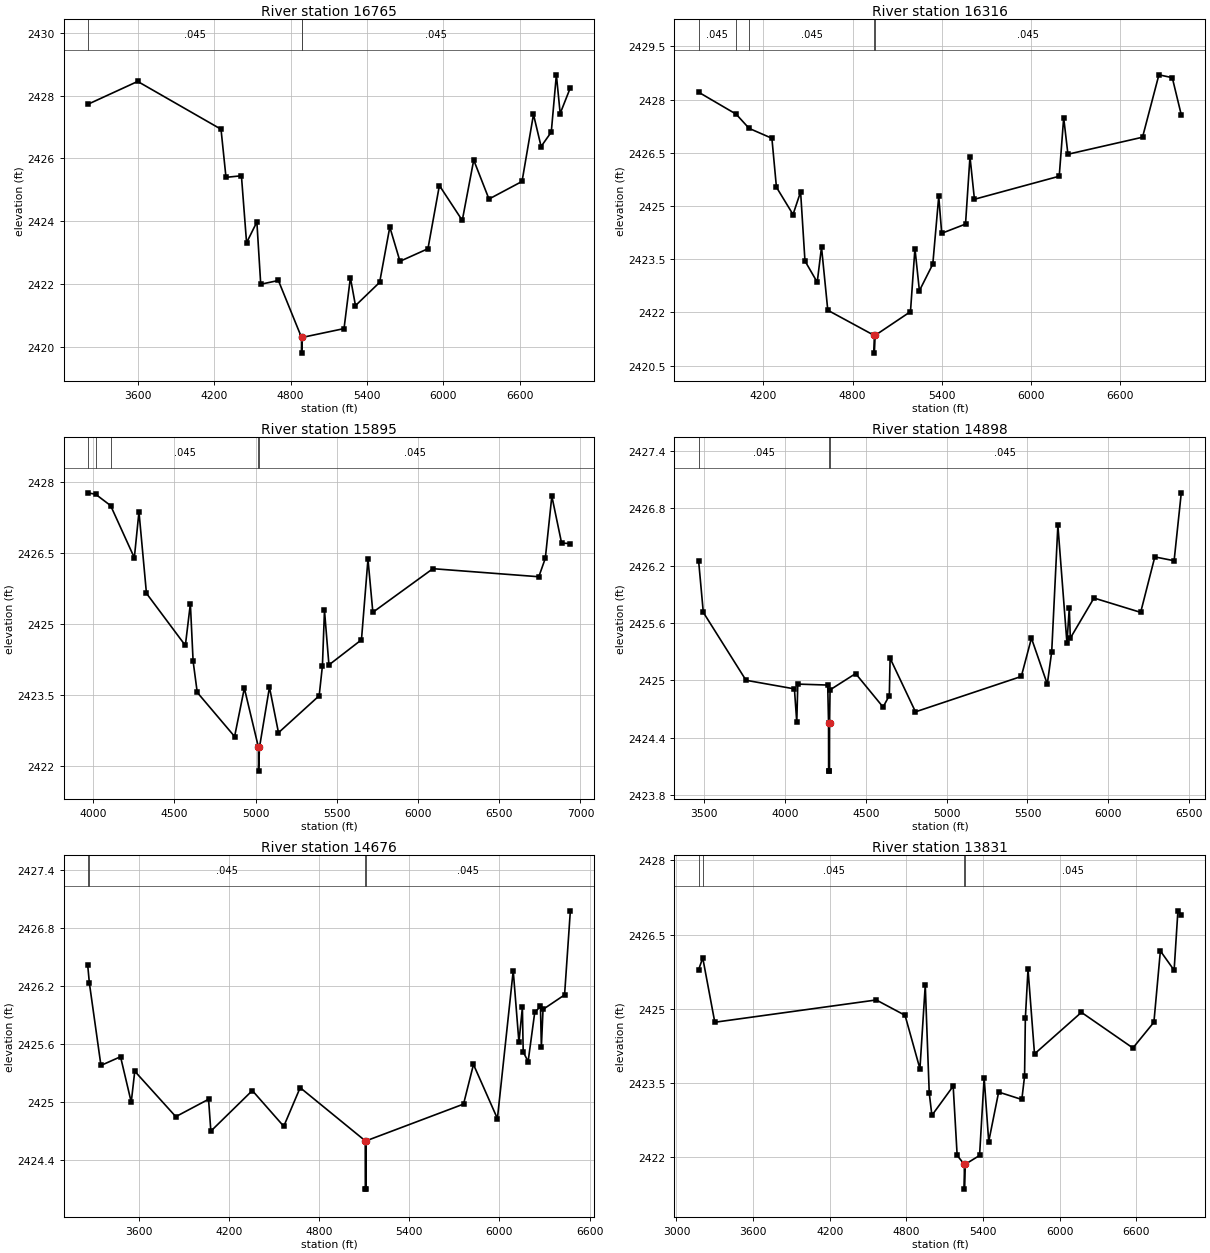
Type RM Length L Ch R = 1,16765,449,449,449
BEGIN DESCRIPTION:
UCFB HW Trib 25 29.0
END DESCRIPTION:
XS GIS Cut Line= 3
      1266580.00      6934662.99      1266855.00      6932888.00
      1266855.00      6930887.96
#Sta/Elev= 30
  3203.7 2427.72  3597.0 2428.45  4252.4 2426.93  4291.5 2425.40  4412.9 2425.45
  4453.4 2423.32  4534.4 2423.98  4564.7 2422.00  4703.6 2422.12  4885.5 2420.31
  4886.0 2419.81  4891.5 2420.31  5219.9 2420.59  5269.9 2422.21  5309.9 2421.32
  5499.9 2422.06  5579.9 2423.82  5659.9 2422.73  5879.9 2423.13  5969.9 2425.14
  6149.9 2424.03  6239.9 2425.95  6359.9 2424.71  6619.9 2425.27  6709.9 2427.40
  6769.9 2426.38  6849.9 2426.84  6889.9 2428.66  6919.9 2427.43  6999.9 2428.25
#Mann=3,-1,0
  3203.7   0.045       0  4885.5   0.045       0  4891.5   0.045       0
Bank Sta=4885.5,4891.5
Exp/Cntr=0.3,0.1

Type RM Length L Ch R = 1,16316,421,421,421
BEGIN DESCRIPTION:
UCFB HW Trib 25 28.0
END DESCRIPTION:
XS GIS Cut Line= 3
      1266979.99      6934063.05      1267205.00      6932838.00
      1267293.60      6930837.50
#Sta/Elev= 30
  3764.1 2428.21  4016.9 2427.59  4103.8 2427.19  4257.3 2426.91  4287.8 2425.53
  4399.6 2424.76  4450.4 2425.40  4479.8 2423.45  4562.3 2422.85  4591.1 2423.84
  4633.4 2422.06  4945.6 2421.35  4946.1 2420.85  4951.7 2421.35  5189.8 2422.02
  5219.8 2423.80  5249.9 2422.61  5340.0 2423.36  5380.0 2425.27  5400.0 2424.23
  5560.2 2424.49  5590.2 2426.39  5620.2 2425.19  6190.8 2425.84  6220.8 2427.49
  6249.3 2426.46  6751.3 2426.94  6861.5 2428.70  6951.5 2428.62  7012.1 2427.57
#Mann=5,-1,0
  3764.1   0.045       0  4016.9   0.035       0  4103.8   0.045       0
  4945.6   0.045       0  4951.7   0.045       0
Bank Sta=4945.6,4951.7
Exp/Cntr=0.3,0.1

Type RM Length L Ch R = 1,15895,997,997,997
BEGIN DESCRIPTION:
UCFB HW Trib 25 27.0
END DESCRIPTION:
XS GIS Cut Line= 4
      1267229.98      6933913.04      1267503.38      6933314.98
      1267505.00      6932938.00      1267619.99      6931004.19
#Sta/Elev= 30
  3966.1 2427.77  4015.0 2427.74  4107.5 2427.50  4253.4 2426.40  4281.9 2427.37
  4328.0 2425.65  4567.5 2424.55  4598.4 2425.43  4615.2 2424.22  4640.7 2423.56
  4870.7 2422.63  4930.7 2423.65  5017.7 2422.40  5018.2 2421.90  5023.8 2422.40
  5085.4 2423.67  5140.9 2422.71  5391.4 2423.49  5411.4 2424.12  5424.1 2425.29
  5451.5 2424.14  5651.8 2424.67  5691.9 2426.37  5721.9 2425.25  6091.7 2426.17
  6743.7 2426.00  6783.8 2426.39  6823.9 2427.70  6884.0 2426.71  6937.9 2426.70
#Mann=5,-1,0
  3966.1   0.045       0  4015.0   0.035       0  4107.5   0.045       0
  5017.7   0.045       0  5023.8   0.045       0
Bank Sta=5017.7,5023.8
Exp/Cntr=0.3,0.1

Type RM Length L Ch R = 1,14898,222,222,222
BEGIN DESCRIPTION:
UCFB HW Trib 25 26.1
END DESCRIPTION:
XS GIS Cut Line= 4
      1267530.02      6933712.97      1268204.89      6932821.05
      1268249.06      6932259.46      1267866.76      6931011.38
#Sta/Elev= 30
  3464.8 2426.25  3493.9 2425.71  3758.1 2425.00  4057.8 2424.91  4072.3 2424.56
  4078.6 2424.96  4263.8 2424.95  4269.0 2424.55  4269.5 2424.05  4274.7 2424.05
  4275.2 2424.55  4278.4 2424.90  4436.5 2425.07  4606.4 2424.72  4645.0 2424.84
  4650.0 2425.23  4807.0 2424.67  5461.9 2425.04  5524.6 2425.44  5622.7 2424.96
  5650.1 2425.30  5688.2 2426.62  5744.3 2425.39  5758.9 2425.76  5765.2 2425.44
  5911.6 2425.86  6200.5 2425.71  6288.1 2426.29  6407.5 2426.25  6451.9 2426.96
#Mann=3,-1,0
  3464.8   0.045       0  4269.0   0.045       0  4275.2   0.045       0
Bank Sta=4269,4275.2
Exp/Cntr=0.3,0.1

Type RM Length L Ch R = 1,14676,845,845,845
BEGIN DESCRIPTION:
UCFB HW Trib 25 26.15
END DESCRIPTION:
XS GIS Cut Line= 4
      1267568.63      6933882.35      1268396.22      6932584.05
      1268471.92      6932148.75      1267956.26      6931033.03
#Sta/Elev= 30
  3261.0 2426.42  3272.5 2426.23  3349.2 2425.38  3479.6 2425.47  3550.8 2425.00
  3574.2 2425.32  3847.2 2424.85  4065.1 2425.03  4080.3 2424.70  4356.2 2425.12
  4565.3 2424.75  4674.4 2425.15  5107.3 2424.60  5107.8 2424.10  5113.0 2424.10
  5113.5 2424.60  5761.1 2424.98  5827.2 2425.39  5986.4 2424.83  6091.6 2426.36
  6129.6 2425.62  6152.5 2425.98  6158.0 2425.52  6190.7 2425.42  6234.8 2425.93
  6272.7 2425.99  6278.8 2425.57  6289.9 2425.96  6433.1 2426.11  6471.6 2426.98
#Mann=4,-1,0
  3261.0   0.035       0  3272.5   0.045       0  5107.3   0.045       0
  5113.5   0.045       0
Bank Sta=5107.3,5113.5
Exp/Cntr=0.3,0.1

Type RM Length L Ch R = 1,13831,579,579,579
BEGIN DESCRIPTION:
UCFB HW Trib 25 26.2
END DESCRIPTION:
XS GIS Cut Line= 4
      1267654.80      6933933.56      1268515.92      6932549.85
      1268974.26      6932417.04      1268026.34      6931039.43
#Sta/Elev= 30
  3173.4 2425.79  3205.8 2426.03  3300.2 2424.73  4564.4 2425.18  4789.8 2424.87
  4906.3 2423.79  4948.0 2425.48  4979.2 2423.30  5000.0 2422.85  5166.6 2423.44
  5197.8 2422.04  5253.9 2421.86  5254.4 2421.36  5260.1 2421.86  5373.2 2422.04
  5409.0 2423.61  5444.9 2422.32  5522.6 2423.32  5704.1 2423.17  5725.6 2423.64
  5731.7 2424.81  5752.6 2425.80  5803.4 2424.09  6170.7 2424.93  6573.8 2424.21
  6738.2 2424.73  6788.9 2426.17  6896.5 2425.78  6926.2 2426.98  6952.6 2426.89
#Mann=4,-1,0
  3173.4   0.035       0  3205.8   0.045       0  5253.9   0.045       0
  5260.1   0.045       0
Bank Sta=5253.9,5260.1
Exp/Cntr=0.3,0.1

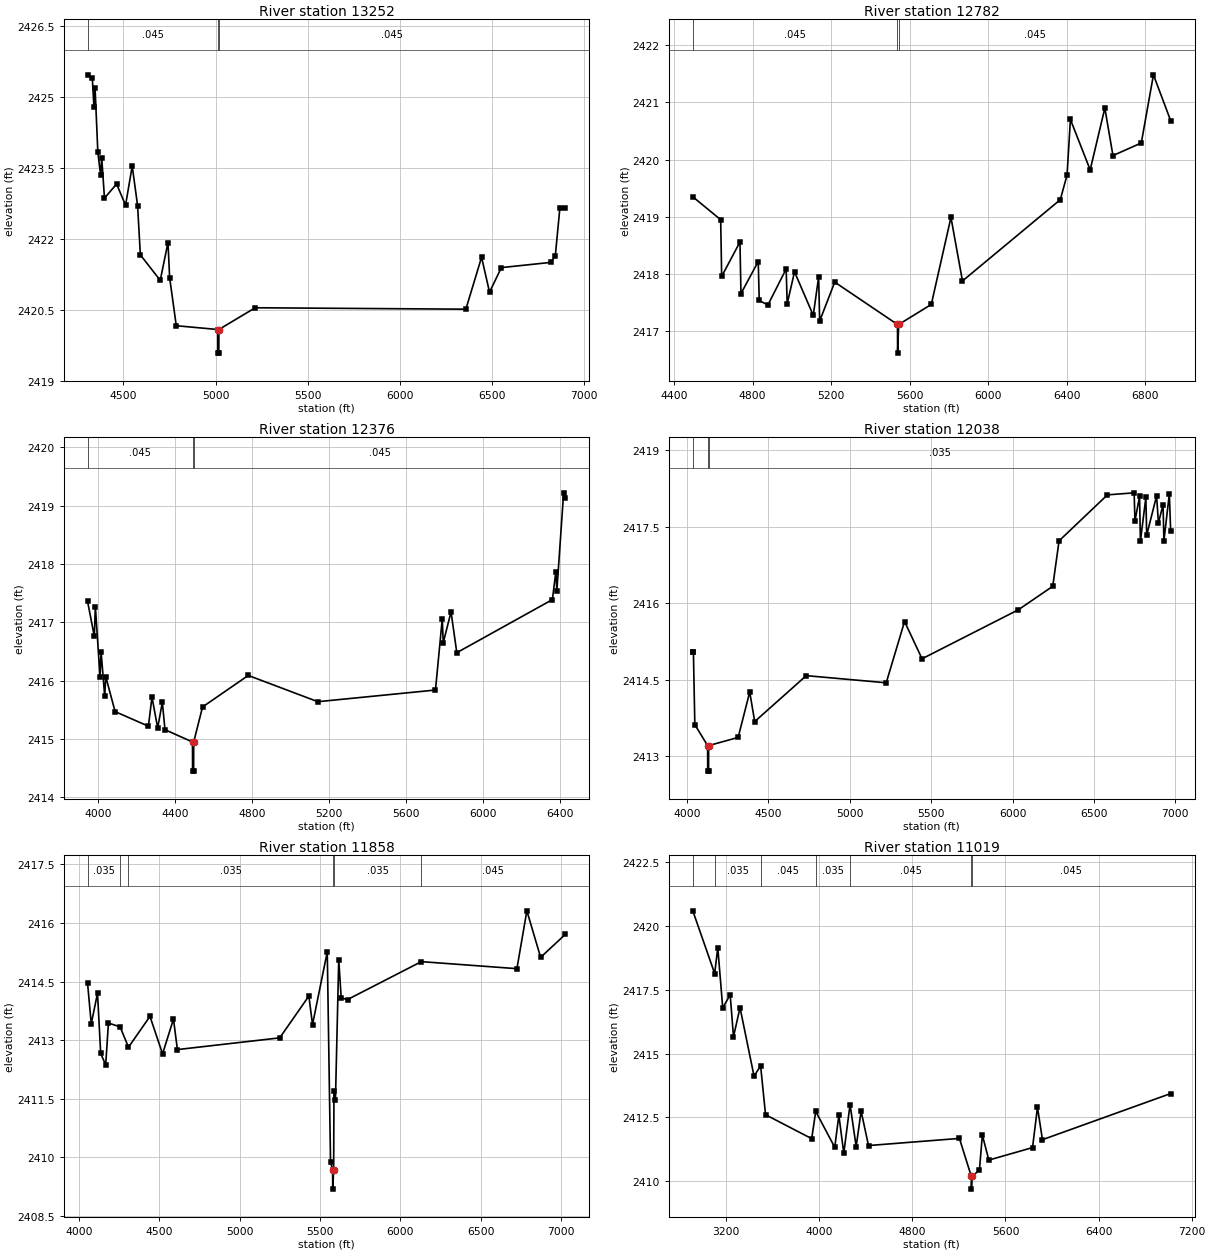
Type RM Length L Ch R = 1,13252,470,470,470
BEGIN DESCRIPTION:
UCFB HW Trib 25 26.0
END DESCRIPTION:
XS GIS Cut Line= 4
      1268574.07      6933194.41      1269011.60      6932899.25
      1269055.00      6932738.00      1269730.00      6930962.99
#Sta/Elev= 30
  4305.5 2425.47  4331.3 2425.40  4340.3 2424.78  4346.3 2425.19  4361.3 2423.83
  4376.3 2423.35  4382.3 2423.72  4397.3 2422.86  4463.2 2423.16  4511.7 2422.71
  4547.9 2423.54  4577.1 2422.70  4592.1 2421.66  4700.0 2421.12  4742.0 2421.92
  4751.0 2421.18  4787.0 2420.16  5012.2 2420.08  5012.7 2419.58  5017.9 2419.58
  5018.4 2420.08  5215.4 2420.54  6359.0 2420.51  6444.2 2421.61  6487.4 2420.87
  6551.6 2421.39  6819.6 2421.50  6844.4 2421.64  6869.2 2422.65  6899.3 2422.65
#Mann=3,-1,0
  4305.5   0.045       0  5012.2   0.045       0  5018.4   0.045       0
Bank Sta=5012.2,5018.4
Exp/Cntr=0.3,0.1

Type RM Length L Ch R = 1,12782,406,406,406
BEGIN DESCRIPTION:
UCFB HW Trib 25 25.0
END DESCRIPTION:
XS GIS Cut Line= 3
      1269298.78      6933476.83      1269405.00      6932988.00
      1269880.01      6931112.97
#Sta/Elev= 30
  4495.4 2419.35  4637.4 2418.95  4642.5 2417.96  4735.6 2418.56  4740.8 2417.66
  4828.8 2418.22  4833.9 2417.54  4877.9 2417.46  4971.1 2418.09  4976.2 2417.48
  5013.6 2418.04  5109.1 2417.28  5136.5 2417.95  5141.7 2417.18  5218.5 2417.86
  5538.2 2417.12  5538.7 2416.62  5544.4 2417.12  5710.4 2417.47  5810.6 2418.99
  5869.2 2417.88  6367.7 2419.30  6402.1 2419.73  6419.2 2420.70  6519.9 2419.82
  6594.6 2420.90  6635.9 2420.07  6780.3 2420.29  6842.2 2421.48  6929.9 2420.68
#Mann=3,-1,0
  4495.4   0.045       0  5538.2   0.045       0  5544.4   0.045       0
Bank Sta=5538.2,5544.4
Exp/Cntr=0.3,0.1

Type RM Length L Ch R = 1,12376,338,338,338
BEGIN DESCRIPTION:
UCFB HW Trib 25 24.5
END DESCRIPTION:
XS GIS Cut Line= 3
      1269040.79      6933907.37      1269551.87      6933704.52
      1270041.98      6931832.58
#Sta/Elev= 30
  3943.3 2417.36  3978.5 2416.76  3983.9 2417.27  4008.2 2416.06  4013.6 2416.50
  4032.5 2415.73  4037.9 2416.07  4086.5 2415.47  4259.8 2415.22  4278.2 2415.72
  4307.9 2415.19  4332.2 2415.63  4345.9 2415.16  4489.0 2414.95  4489.5 2414.45
  4494.8 2414.45  4495.3 2414.95  4541.3 2415.55  4779.0 2416.09  5140.8 2415.64
  5752.5 2415.84  5787.8 2417.06  5792.9 2416.65  5833.4 2417.18  5863.4 2416.48
  6360.6 2417.39  6378.5 2417.87  6383.7 2417.54  6418.9 2419.22  6428.2 2419.13
#Mann=3,-1,0
  3943.3   0.045       0  4489.0   0.045       0  4495.3   0.045       0
Bank Sta=4489,4495.3
Exp/Cntr=0.3,0.1

Type RM Length L Ch R = 1,12038,180,180,180
BEGIN DESCRIPTION:
UCFB HW Trib 25 24.2
END DESCRIPTION:
XS GIS Cut Line= 5
      1269723.56      6934350.26      1269798.41      6933994.73
      1269901.54      6933504.80      1270039.95      6932883.78
      1270442.17      6931504.99
#Sta/Elev= 30
  4035.4 2415.05  4039.1 2415.05  4047.9 2413.62  4126.5 2413.21  4127.0 2412.71
  4132.3 2412.71  4132.8 2413.21  4314.1 2413.37  4385.2 2414.26  4415.8 2413.68
  4732.6 2414.58  5224.0 2414.44  5336.7 2415.64  5444.1 2414.91  6036.1 2415.87
  6247.4 2416.33  6286.1 2417.22  6583.3 2418.12  6747.4 2418.16  6752.6 2417.61
  6780.8 2418.09  6786.0 2417.21  6819.5 2418.07  6824.7 2417.33  6885.4 2418.10
  6896.9 2417.57  6925.2 2417.93  6930.4 2417.22  6963.9 2418.14  6971.9 2417.41
#Mann=3,-1,0
  4035.4   0.035       0  4126.5   0.035       0  4132.8   0.035       0
Bank Sta=4126.5,4132.8
Exp/Cntr=0.3,0.1

Type RM Length L Ch R = 1,11858,839,839,839
BEGIN DESCRIPTION:
UCFB HW Trib 25 24.1
END DESCRIPTION:
XS GIS Cut Line= 6
      1269804.27      6934446.69      1270026.94      6933657.58
      1270141.53      6933100.12      1270160.28      6933008.05
      1270180.00      6932913.00      1270551.77      6931566.56
#Sta/Elev= 30
  4052.0 2414.46  4074.9 2413.42  4114.0 2414.20  4133.8 2412.66  4164.9 2412.37
  4182.0 2413.44  4254.9 2413.34  4306.9 2412.82  4440.8 2413.61  4519.2 2412.65
  4587.2 2413.54  4611.7 2412.76  5249.2 2413.06  5430.7 2414.13  5453.4 2413.40
  5545.3 2415.26  5565.7 2409.88  5578.8 2409.69  5579.3 2409.19  5585.1 2409.69
  5587.0 2411.69  5596.3 2411.47  5616.8 2415.06  5632.1 2414.08  5671.6 2414.04
  6131.3 2415.01  6726.7 2414.83  6788.8 2416.31  6874.5 2415.12  7028.9 2415.71
#Mann=6,-1,0
  4052.0   0.035       0  4254.9   0.045       0  4306.9   0.035       0
  5578.8   0.035       0  5585.1   0.035       0  6131.3   0.045       0
Bank Sta=5578.8,5585.1
Exp/Cntr=0.3,0.1

Type RM Length L Ch R = 1,11019,450,450,450
BEGIN DESCRIPTION:
UCFB HW Trib 25 24.0
END DESCRIPTION:
XS GIS Cut Line= 5
      1269326.94      6935453.66      1270630.00      6934063.00
      1270655.00      6933888.00      1270702.34      6933715.21
      1271335.27      6931983.32
#Sta/Elev= 30
  2913.4 2420.60  3101.3 2418.14  3128.1 2419.15  3170.6 2416.79  3234.6 2417.31
  3262.9 2415.66  3319.1 2416.80  3439.7 2414.11  3496.0 2414.52  3538.4 2412.60
  3935.0 2411.66  3969.5 2412.73  4132.9 2411.32  4168.2 2412.58  4210.5 2411.09
  4264.5 2413.00  4317.0 2411.35  4359.5 2412.74  4423.0 2411.39  5204.1 2411.67
  5306.4 2410.18  5306.9 2409.68  5312.7 2410.18  5376.0 2410.43  5401.2 2411.80
  5456.9 2410.82  5832.2 2411.31  5874.8 2412.89  5917.4 2411.62  7019.0 2413.43
#Mann=7,-1,0
  2913.4   0.045       0  3101.3   0.035       0  3496.0   0.045       0
  3969.5   0.035       0  4264.5   0.045       0  5306.4   0.045       0
  5312.7   0.045       0
Bank Sta=5306.4,5312.7
Exp/Cntr=0.3,0.1

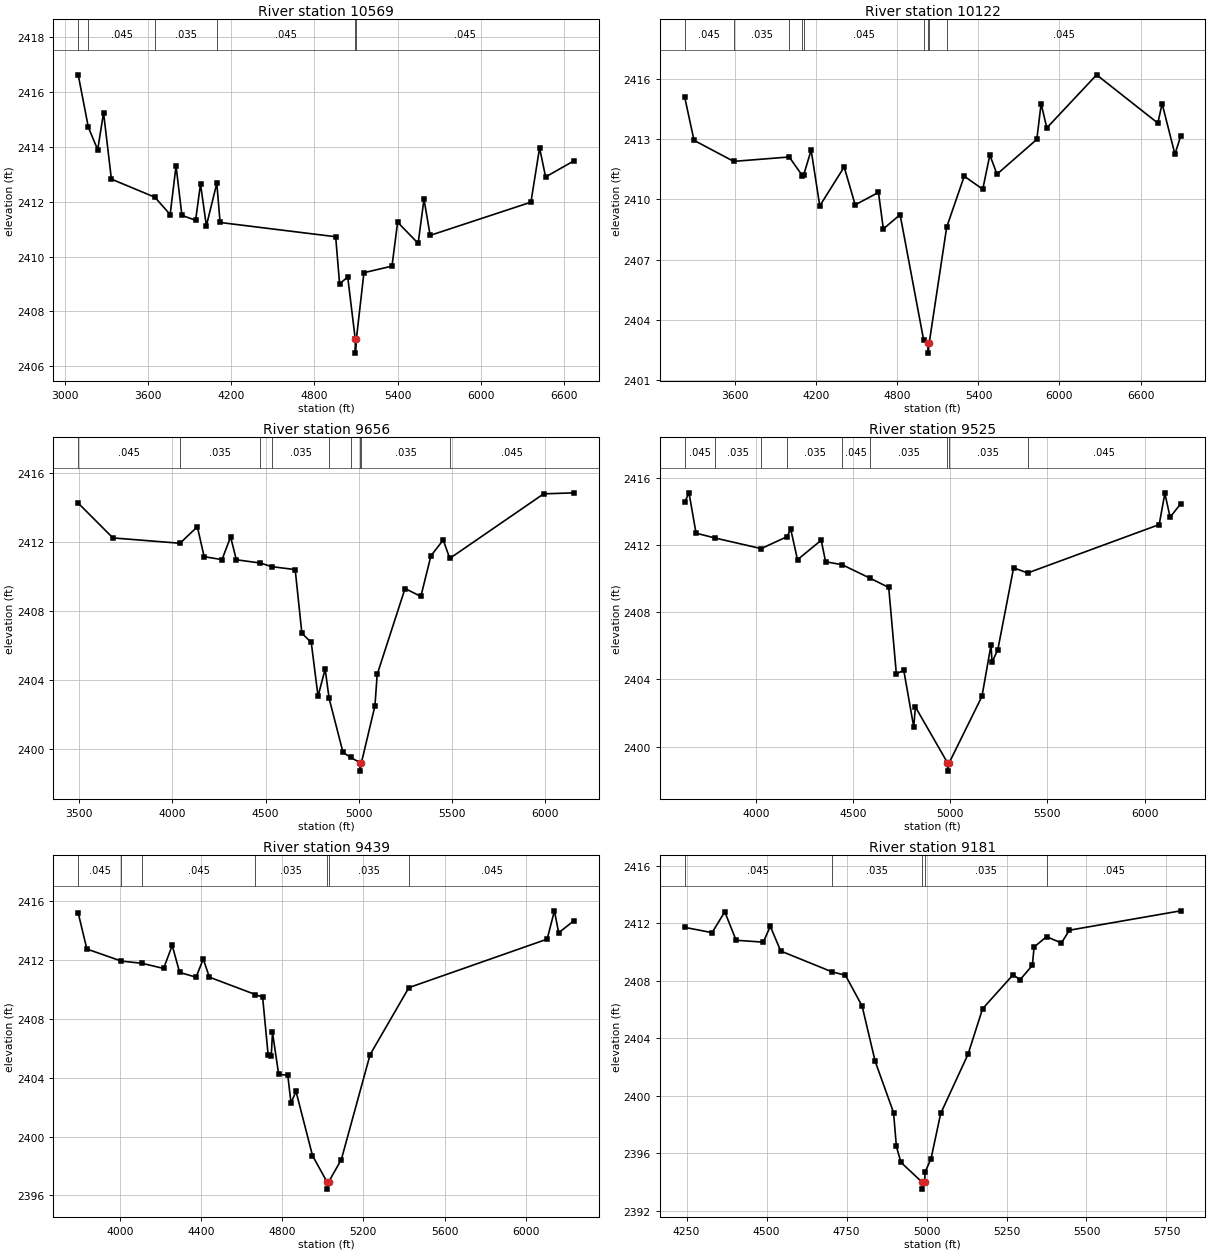
Type RM Length L Ch R = 1,10569,447,447,447
BEGIN DESCRIPTION:
UCFB HW Trib 25 23.0
END DESCRIPTION:
XS GIS Cut Line= 4
      1269652.22      6935173.95      1271005.00      6933838.00
      1271130.00      6933763.00      1272579.98      6933263.01
#Sta/Elev= 30
  3094.2 2416.62  3167.3 2414.71  3234.8 2413.89  3277.2 2415.24  3333.8 2412.82
  3647.8 2412.16  3758.0 2411.53  3800.5 2413.30  3842.9 2411.50  3941.8 2411.32
  3977.2 2412.64  4019.6 2411.12  4094.8 2412.67  4118.6 2411.24  4953.1 2410.72
  4981.4 2409.01  5040.2 2409.25  5094.7 2406.98  5095.2 2406.48  5102.3 2406.98
  5157.1 2409.41  5359.7 2409.65  5400.4 2411.25  5548.5 2410.48  5590.8 2412.09
  5635.2 2410.77  6363.0 2411.98  6425.4 2413.96  6468.8 2412.90  6675.0 2413.49
#Mann=6,-1,0
  3094.2   0.035       0  3167.3   0.045       0  3647.8   0.035       0
  4094.8   0.045       0  5094.7   0.045       0  5102.3   0.045       0
Bank Sta=5094.7,5102.3
Exp/Cntr=0.3,0.1

Type RM Length L Ch R = 1,10122,466,466,466
BEGIN DESCRIPTION:
UCFB HW Trib 25 22.0
END DESCRIPTION:
XS GIS Cut Line= 3
      1269815.38      6935052.82      1271305.00      6934088.00
      1273104.96      6933488.01
#Sta/Elev= 30
  3224.8 2415.11  3294.0 2412.95  3587.6 2411.90  3998.9 2412.12  4096.8 2411.18
  4105.4 2411.21  4161.1 2412.46  4225.1 2409.68  4405.8 2411.62  4487.3 2409.73
  4659.6 2410.35  4695.9 2408.53  4819.9 2409.24  4993.7 2403.00  5027.2 2402.83
  5027.7 2402.33  5035.2 2402.83  5164.9 2408.62  5294.7 2411.16  5431.8 2410.51
  5484.5 2412.22  5537.2 2411.26  5832.3 2413.00  5863.9 2414.78  5906.1 2413.57
  6275.0 2416.22  6728.3 2413.81  6759.9 2414.78  6854.8 2412.26  6896.9 2413.15
#Mann=9,-1,0
  3224.8   0.045       0  3587.6   0.035       0  3998.9   0.045       0
  4096.8   0.035       0  4105.4   0.045       0  4993.7   0.035       0
  5027.2   0.035       0  5035.2   0.035       0  5164.9   0.045       0
Bank Sta=5027.2,5035.2
Exp/Cntr=0.3,0.1

Type RM Length L Ch R = 1,9656,131,131,131
BEGIN DESCRIPTION:
UCFB HW Trib 25 21.0
END DESCRIPTION:
XS GIS Cut Line= 3
      1269940.02      6935051.00      1271355.00      6934538.00
      1272427.01      6934109.16
#Sta/Elev= 30
  3494.9 2414.27  3681.0 2412.25  4040.8 2411.94  4133.8 2412.90  4170.3 2411.16
  4266.1 2410.99  4312.2 2412.31  4342.9 2410.98  4472.4 2410.79  4533.1 2410.58
  4658.5 2410.41  4694.4 2406.71  4744.7 2406.18  4781.0 2403.05  4819.2 2404.63
  4840.6 2402.92  4914.9 2399.79  4955.3 2399.50  5004.9 2399.20  5005.4 2398.70
  5013.9 2399.20  5086.2 2402.49  5098.3 2404.32  5247.7 2409.31  5332.5 2408.85
  5386.4 2411.21  5452.4 2412.13  5487.5 2411.06  5990.9 2414.81  6154.6 2414.87
#Mann=9,-1,0
  3494.9   0.045       0  4040.8   0.035       0  4472.4   0.045       0
  4533.1   0.035       0  4840.6   0.045       0  4955.3   0.035       0
  5004.9   0.035       0  5013.9   0.035       0  5487.5   0.045       0
Bank Sta=5004.9,5013.9
Exp/Cntr=0.3,0.1

Type RM Length L Ch R = 1,9525,86,86,86
BEGIN DESCRIPTION:
UCFB HW Trib 25 20.7
END DESCRIPTION:
XS GIS Cut Line= 4
      1270165.00      6935147.60      1271228.43      6934619.69
      1271790.93      6934727.32      1272428.73      6934257.37
#Sta/Elev= 30
  3633.5 2414.54  3655.8 2415.10  3691.9 2412.70  3790.5 2412.41  4027.3 2411.78
  4159.9 2412.49  4179.3 2412.93  4214.1 2411.12  4336.2 2412.28  4358.6 2411.00
  4444.4 2410.82  4585.6 2410.03  4683.5 2409.47  4722.7 2404.34  4761.1 2404.53
  4812.3 2401.17  4820.8 2402.36  4985.9 2399.04  4986.4 2398.54  4994.9 2399.04
  5163.4 2402.99  5210.0 2406.05  5215.1 2405.03  5244.9 2405.76  5326.3 2410.64
  5398.3 2410.33  6075.3 2413.21  6104.6 2415.07  6131.6 2413.65  6185.7 2414.44
#Mann=9,-1,0
  3633.5   0.045       0  3790.5   0.035       0  4027.3   0.045       0
  4159.9   0.035       0  4444.4   0.045       0  4585.6   0.035       0
  4985.9   0.035       0  4994.9   0.035       0  5398.3   0.045       0
Bank Sta=4985.9,4994.9
Exp/Cntr=0.3,0.1

Type RM Length L Ch R = 1,9439,258,258,258
BEGIN DESCRIPTION:
UCFB HW Trib 25 20.4
END DESCRIPTION:
XS GIS Cut Line= 4
      1270351.51      6935223.91      1271191.97      6934703.02
      1271778.25      6934801.96      1272488.08      6934316.72
#Sta/Elev= 30
  3795.5 2415.16  3838.0 2412.72  4007.8 2411.90  4110.1 2411.75  4216.1 2411.40
  4258.6 2412.96  4295.2 2411.13  4376.1 2410.81  4411.4 2412.04  4441.7 2410.81
  4668.4 2409.63  4704.0 2409.45  4731.1 2405.54  4746.5 2405.45  4752.6 2407.06
  4783.1 2404.21  4827.9 2404.16  4843.7 2402.28  4868.5 2403.06  4949.6 2398.71
  5020.6 2396.93  5021.1 2396.43  5029.7 2396.93  5091.6 2398.43  5233.6 2405.56
  5424.5 2410.10  6105.7 2413.39  6141.5 2415.31  6162.5 2413.82  6238.7 2414.65
#Mann=7,-1,0
  3795.5   0.045       0  4007.8   0.035       0  4110.1   0.045       0
  4668.4   0.035       0  5020.6   0.035       0  5029.7   0.035       0
  5424.5   0.045       0
Bank Sta=5020.6,5029.7
Exp/Cntr=0.3,0.1

Type RM Length L Ch R = 1,9181,514,514,514
BEGIN DESCRIPTION:
UCFB HW Trib 25 20.0
END DESCRIPTION:
XS GIS Cut Line= 3
      1270860.56      6935247.24      1271555.00      6934938.00
      1272294.55      6934660.45
#Sta/Elev= 30
  4244.1 2411.72  4329.7 2411.35  4369.4 2412.80  4404.9 2410.82  4489.8 2410.69
  4511.7 2411.79  4544.3 2410.07  4703.6 2408.63  4746.6 2408.38  4798.5 2406.25
  4839.6 2402.38  4897.0 2398.82  4905.8 2396.46  4920.2 2395.35  4985.4 2393.99
  4985.9 2393.49  4994.5 2393.99  4995.4 2394.67  5014.1 2395.61  5044.3 2398.76
  5129.7 2402.88  5175.2 2406.05  5270.3 2408.41  5292.7 2408.08  5330.8 2409.07
  5336.2 2410.35  5375.3 2411.07  5421.6 2410.63  5446.5 2411.52  5794.2 2412.87
#Mann=5,-1,0
  4244.1   0.045       0  4703.6   0.035       0  4985.4   0.035       0
  4994.5   0.035       0  5375.3   0.045       0
Bank Sta=4985.4,4994.5
Exp/Cntr=0.3,0.1

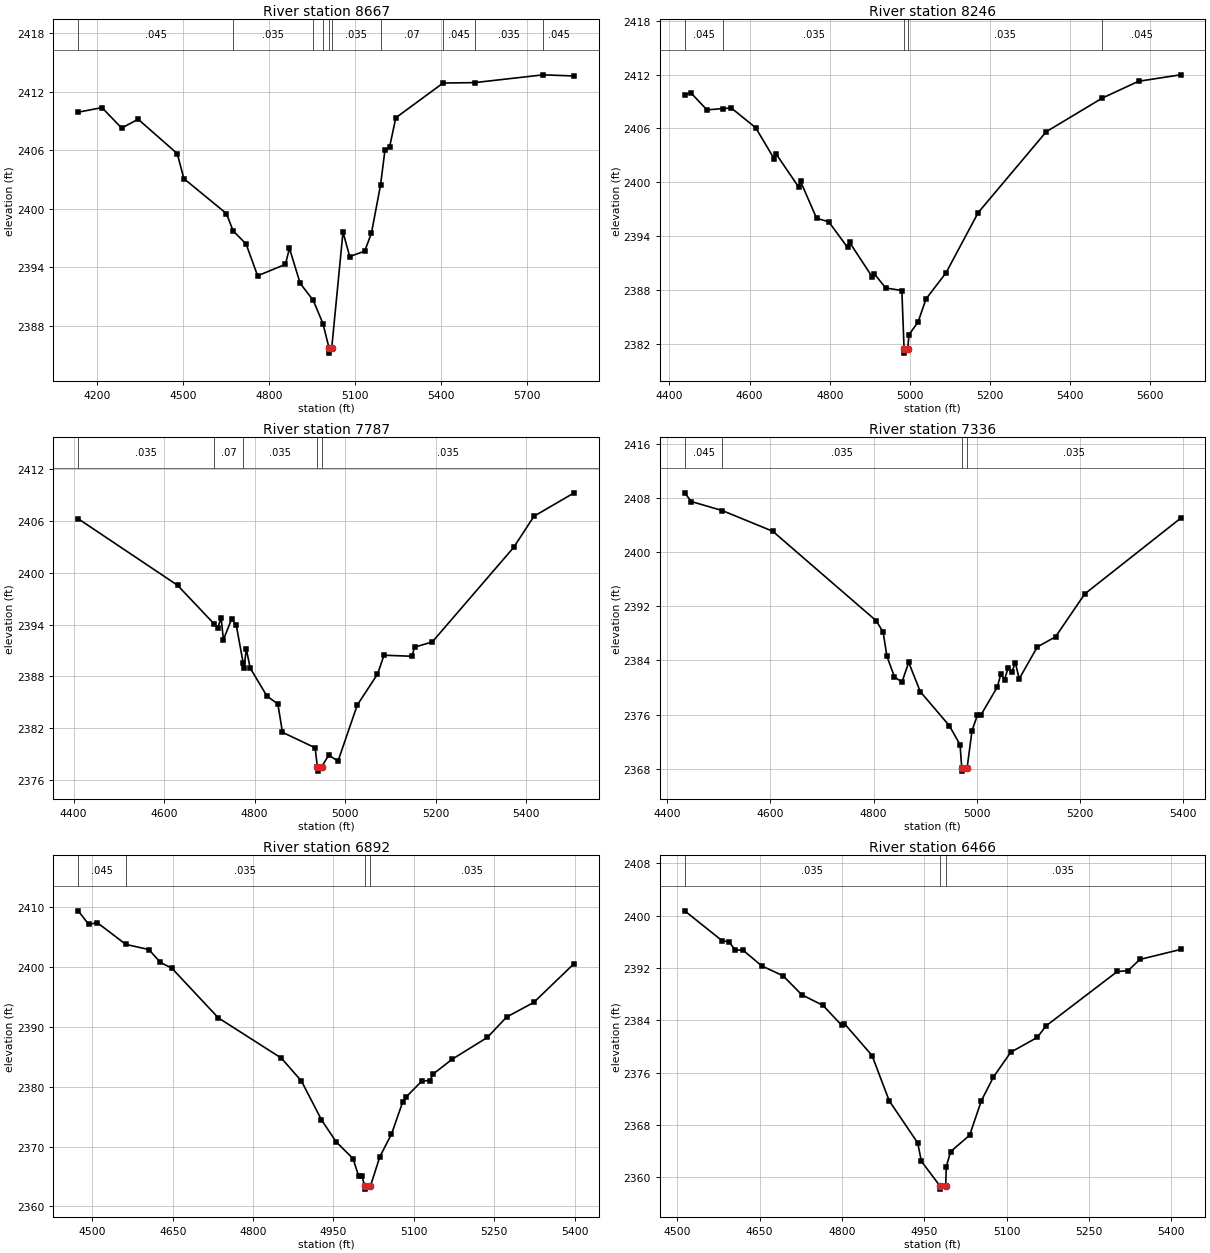
Type RM Length L Ch R = 1,8667,421,421,421
BEGIN DESCRIPTION:
UCFB HW Trib 25 19.0
END DESCRIPTION:
XS GIS Cut Line= 3
      1271055.04      6935587.98      1271841.81      6935224.21
      1272636.97      6934880.66
#Sta/Elev= 30
  4133.2 2409.88  4216.2 2410.35  4285.0 2408.25  4342.5 2409.16  4479.4 2405.63
  4502.4 2403.07  4651.0 2399.49  4674.5 2397.71  4719.8 2396.37  4760.1 2393.11
  4857.3 2394.28  4871.3 2395.93  4908.7 2392.34  4954.5 2390.59  4988.8 2388.18
  5009.8 2385.68  5010.3 2385.18  5019.0 2385.68  5058.4 2397.59  5081.9 2395.08
  5134.4 2395.64  5157.9 2397.49  5189.8 2402.44  5204.9 2405.96  5221.3 2406.32
  5243.1 2409.31  5408.3 2412.87  5518.0 2412.91  5758.6 2413.71  5866.2 2413.59
#Mann=10,-1,0
  4133.2   0.045       0  4674.5   0.035       0  4954.5    0.07       0
  4988.8   0.035       0  5009.8   0.035       0  5019.0   0.035       0
  5189.8    0.07       0  5408.3   0.045       0  5518.0   0.035       0
  5758.6   0.045       0
Bank Sta=5009.8,5019
Exp/Cntr=0.3,0.1

Type RM Length L Ch R = 1,8246,459,459,459
BEGIN DESCRIPTION:
UCFB HW Trib 25 18.0
END DESCRIPTION:
XS GIS Cut Line= 3
      1271100.19      6935629.18      1271655.00      6935538.00
      1272329.98      6935513.00
#Sta/Elev= 30
  4438.1 2409.71  4453.1 2410.00  4493.6 2408.07  4533.9 2408.22  4554.5 2408.28
  4615.3 2406.08  4661.0 2402.65  4666.1 2403.17  4722.3 2399.48  4727.3 2400.10
  4767.3 2395.99  4797.7 2395.59  4844.7 2392.73  4849.8 2393.29  4906.0 2389.46
  4911.0 2389.82  4939.6 2388.22  4980.1 2387.93  4985.6 2381.45  4986.1 2380.95
  4994.8 2381.45  4997.8 2383.01  5020.4 2384.40  5040.4 2386.99  5090.4 2389.91
  5170.5 2396.61  5340.6 2405.64  5480.4 2409.39  5570.7 2411.26  5675.8 2411.98
#Mann=5,-1,0
  4438.1   0.045       0  4533.9   0.035       0  4985.6   0.035       0
  4994.8   0.035       0  5480.4   0.045       0
Bank Sta=4985.6,4994.8
Exp/Cntr=0.3,0.1

Type RM Length L Ch R = 1,7787,451,451,451
BEGIN DESCRIPTION:
UCFB HW Trib 25 17.0
END DESCRIPTION:
XS GIS Cut Line= 3
      1271173.02      6936056.28      1271755.00      6935938.00
      1272204.27      6935716.01
#Sta/Elev= 30
  4410.4 2406.25  4629.8 2398.55  4709.8 2394.12  4718.6 2393.65  4725.9 2394.77
  4731.0 2392.26  4749.2 2394.66  4759.4 2393.93  4774.8 2389.52  4776.5 2389.02
  4781.6 2391.17  4790.0 2388.99  4827.1 2385.73  4851.2 2384.82  4861.4 2381.54
  4933.5 2379.75  4938.4 2377.55  4938.9 2377.05  4947.8 2377.55  4963.5 2378.89
  4984.1 2378.22  5026.6 2384.70  5071.2 2388.27  5085.6 2390.46  5147.4 2390.34
  5152.9 2391.39  5192.2 2392.00  5371.8 2402.93  5416.7 2406.54  5505.4 2409.25
#Mann=5,-1,0
  4410.4   0.035       0  4709.8    0.07       0  4774.8   0.035       0
  4938.4   0.035       0  4947.8   0.035       0
Bank Sta=4938.4,4947.8
Exp/Cntr=0.3,0.1

Type RM Length L Ch R = 1,7336,444,444,444
BEGIN DESCRIPTION:
UCFB HW Trib 25 16.0
END DESCRIPTION:
XS GIS Cut Line= 3
      1271544.60      6936625.71      1272005.00      6936288.00
      1272294.62      6936024.99
#Sta/Elev= 30
  4433.5 2408.79  4446.4 2407.50  4506.3 2406.17  4604.3 2403.11  4804.9 2389.88
  4818.5 2388.20  4825.8 2384.65  4840.5 2381.56  4855.1 2380.80  4868.1 2383.72
  4890.6 2379.38  4947.0 2374.35  4967.8 2371.53  4971.0 2368.13  4971.5 2367.63
  4981.5 2368.13  4991.0 2373.63  5001.4 2375.89  5007.9 2375.89  5040.0 2380.06
  5046.7 2381.93  5054.2 2381.18  5060.9 2382.87  5068.3 2382.32  5075.1 2383.66
  5082.5 2381.28  5117.7 2386.00  5153.1 2387.50  5209.6 2393.83  5395.7 2405.03
#Mann=4,-1,0
  4433.5   0.045       0  4506.3   0.035       0  4971.0   0.035       0
  4981.5   0.035       0
Bank Sta=4971,4981.5
Exp/Cntr=0.3,0.1

Type RM Length L Ch R = 1,6892,426,426,426
BEGIN DESCRIPTION:
UCFB HW Trib 25 15.0
END DESCRIPTION:
XS GIS Cut Line= 3
      1271798.09      6936900.00      1272255.00      6936638.00
      1272482.06      6936309.78
#Sta/Elev= 30
  4473.5 2409.41  4493.2 2407.13  4509.0 2407.44  4562.4 2403.80  4605.3 2402.94
  4626.9 2400.80  4648.5 2399.80  4735.1 2391.52  4852.8 2384.79  4890.2 2380.96
  4927.6 2374.49  4954.9 2370.81  4986.5 2368.00  4997.3 2365.02  5003.2 2365.02
  5008.4 2363.40  5008.9 2362.90  5019.0 2363.40  5036.7 2368.35  5058.3 2372.09
  5079.3 2377.48  5085.3 2378.27  5115.1 2380.97  5130.0 2381.05  5136.0 2382.13
  5171.8 2384.62  5237.4 2388.26  5273.2 2391.66  5323.9 2394.10  5399.3 2400.60
#Mann=4,-1,0
  4473.5   0.045       0  4562.4   0.035       0  5008.4   0.035       0
  5019.0   0.035       0
Bank Sta=5008.4,5019
Exp/Cntr=0.3,0.1

Type RM Length L Ch R = 1,6466,471,471,471
BEGIN DESCRIPTION:
UCFB HW Trib 25 14.0
END DESCRIPTION:
XS GIS Cut Line= 3
      1271936.93      6937122.25      1272405.00      6936988.00
      1272794.54      6936841.01
#Sta/Elev= 30
  4513.5 2400.76  4581.2 2396.22  4594.7 2395.98  4605.1 2394.80  4620.2 2394.71
  4653.9 2392.33  4692.8 2390.82  4726.6 2387.93  4765.5 2386.29  4799.3 2383.27
  4804.5 2383.50  4854.8 2378.62  4886.0 2371.71  4938.0 2365.25  4944.6 2362.46
  4978.3 2358.69  4978.8 2358.19  4988.9 2358.69  4990.0 2361.62  4997.8 2363.93
  5032.5 2366.43  5053.9 2371.72  5075.9 2375.34  5107.3 2379.12  5155.8 2381.40
  5171.5 2383.15  5301.5 2391.48  5321.0 2391.60  5342.5 2393.32  5416.8 2394.85
#Mann=3,-1,0
  4513.5   0.035       0  4978.3   0.035       0  4988.9   0.035       0
Bank Sta=4978.3,4988.9
Exp/Cntr=0.3,0.1