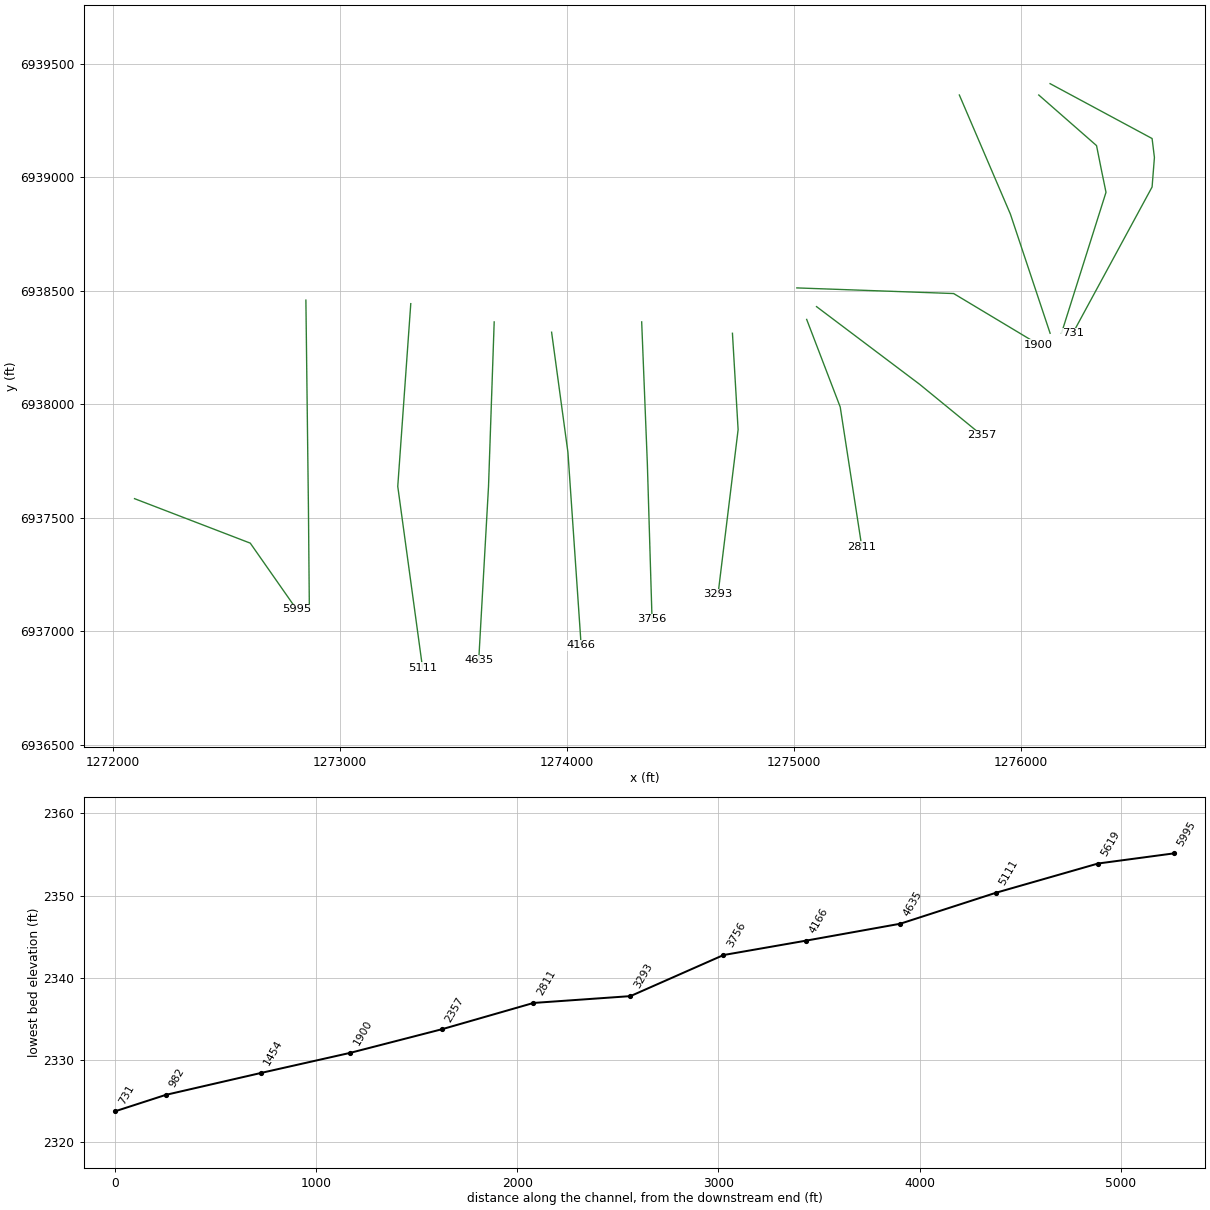
HEC-RAS study UCFB HW Trib 25.prj: UCFB HW Trib 25 Base Level Engineering

--- UCFB HW Trib 25.g01 (geometry) --- (continued)

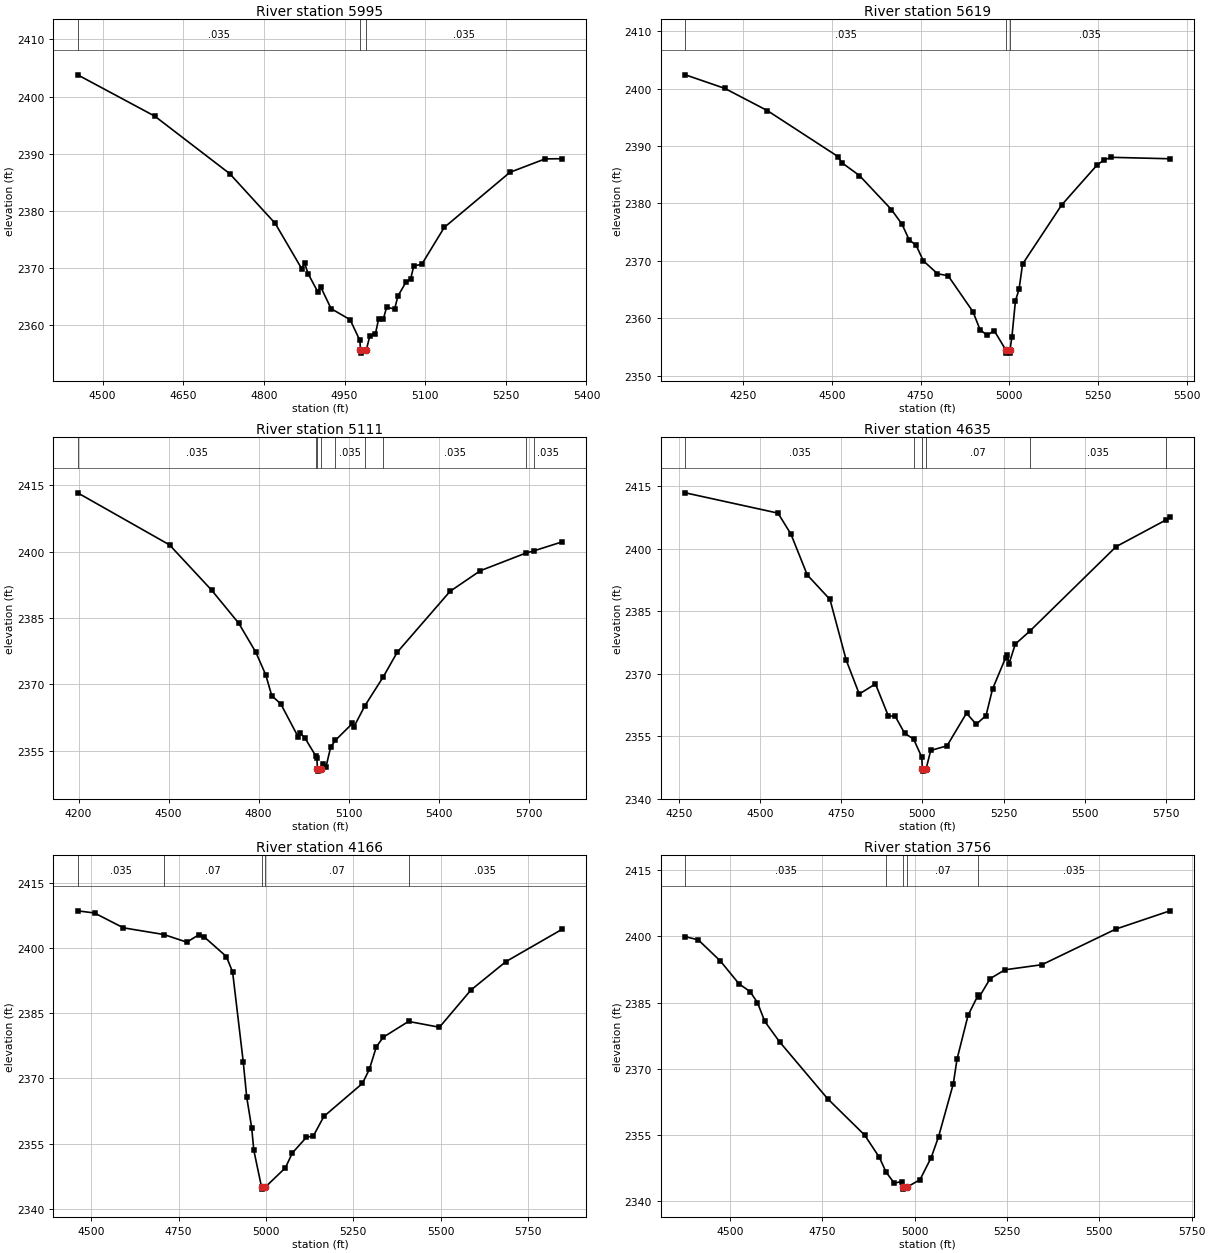
Type RM Length L Ch R = 1,5995,376,376,376
BEGIN DESCRIPTION:
UCFB HW Trib 25 13.0
END DESCRIPTION:
XS GIS Cut Line= 3
      1272094.95      6937584.04      1272605.00      6937388.00
      1272808.44      6937097.11
#Sta/Elev= 30
  4453.6 2403.81  4597.1 2396.58  4736.4 2386.53  4821.1 2377.82  4870.4 2369.90
  4875.7 2370.90  4882.2 2369.04  4900.4 2365.84  4905.7 2366.72  4925.0 2362.92
  4960.4 2360.99  4978.6 2357.35  4979.7 2355.64  4980.2 2355.14  4990.4 2355.64
  4997.3 2358.22  5007.4 2358.49  5013.5 2361.13  5022.3 2361.15  5028.4 2363.18
  5043.2 2362.85  5049.3 2365.11  5064.1 2367.52  5072.8 2368.08  5078.9 2370.38
  5093.8 2370.69  5135.6 2377.13  5257.7 2386.76  5323.1 2389.11  5355.0 2389.14
#Mann=3,-1,0
  4453.6   0.035       0  4979.7   0.035       0  4990.4   0.035       0
Bank Sta=4979.7,4990.4
Exp/Cntr=0.3,0.1

Type RM Length L Ch R = 1,5619,508,508,508
BEGIN DESCRIPTION:
UCFB HW Trib 25 12.0
END DESCRIPTION:
XS GIS Cut Line= 3
      1272850.14      6938459.06      1272861.31      6937545.43
      1272865.45      6937092.35
#Sta/Elev= 30
  4086.3 2402.42  4197.4 2400.06  4317.4 2396.19  4517.4 2388.15  4527.4 2387.11
  4577.4 2384.86  4667.4 2378.94  4697.4 2376.38  4717.4 2373.68  4737.4 2372.68
  4757.4 2370.01  4797.4 2367.75  4827.4 2367.40  4897.5 2361.13  4917.4 2358.01
  4937.4 2357.01  4957.4 2357.83  4990.7 2354.41  4991.2 2353.91  5001.3 2353.91
  5001.8 2354.41  5007.4 2356.77  5017.4 2363.06  5027.4 2365.01  5037.4 2369.43
  5147.4 2379.71  5247.4 2386.69  5267.4 2387.59  5287.4 2388.04  5453.1 2387.79
#Mann=3,-1,0
  4086.3   0.035       0  4990.7   0.035       0  5001.8   0.035       0
Bank Sta=4990.7,5001.8
Exp/Cntr=0.3,0.1

Type RM Length L Ch R = 1,5111,476,476,476
BEGIN DESCRIPTION:
UCFB HW Trib 25 11.0
END DESCRIPTION:
XS GIS Cut Line= 3
      1273312.38      6938443.43      1273255.00      6937638.00
      1273364.46      6936837.52
#Sta/Elev= 30
  4197.0 2413.34  4503.2 2401.56  4643.6 2391.31  4733.8 2383.84  4791.2 2377.23
  4824.0 2372.14  4844.1 2367.42  4874.1 2365.57  4931.7 2358.15  4936.7 2359.07
  4954.3 2357.88  4991.5 2353.71  4994.4 2353.35  4996.3 2350.85  4996.8 2350.35
  5007.6 2350.85  5014.6 2351.99  5024.7 2351.28  5040.6 2355.82  5056.5 2357.35
  5112.8 2361.13  5117.9 2360.37  5154.9 2365.19  5215.4 2371.64  5262.3 2377.26
  5438.5 2391.05  5539.4 2395.71  5691.7 2399.72  5718.1 2400.21  5812.4 2402.25
#Mann=9,-1,0
  4197.0   0.035       0  4991.5    0.07       0  4996.3    0.07       0
  5007.6    0.07       0  5056.5   0.035       0  5154.9    0.07       0
  5215.4   0.035       0  5691.7   0.045       0  5718.1   0.035       0
Bank Sta=4996.3,5007.6
Exp/Cntr=0.3,0.1

Type RM Length L Ch R = 1,4635,469,469,469
BEGIN DESCRIPTION:
UCFB HW Trib 25 10.0
END DESCRIPTION:
XS GIS Cut Line= 3
      1273680.00      6938363.04      1273655.00      6937638.00
      1273611.88      6936872.59
#Sta/Elev= 30
  4270.4 2413.36  4555.6 2408.49  4595.6 2403.44  4645.7 2393.66  4715.7 2387.78
  4765.7 2373.21  4805.8 2365.08  4855.8 2367.51  4895.8 2359.74  4915.8 2359.85
  4945.8 2355.63  4973.1 2354.29  4998.4 2349.92  5000.2 2347.08  5000.7 2346.58
  5011.5 2347.08  5025.9 2351.55  5076.0 2352.64  5136.1 2360.49  5166.1 2357.82
  5196.2 2359.92  5216.2 2366.26  5256.3 2373.75  5261.9 2374.46  5266.9 2372.32
  5286.3 2377.06  5331.9 2380.24  5596.8 2400.45  5750.2 2406.85  5762.5 2407.58
#Mann=6,-1,0
  4270.4   0.035       0  4973.1    0.07       0  5000.2    0.07       0
  5011.5    0.07       0  5331.9   0.035       0  5750.2   0.045       0
Bank Sta=5000.2,5011.5
Exp/Cntr=0.3,0.1

Type RM Length L Ch R = 1,4166,410,410,410
BEGIN DESCRIPTION:
UCFB HW Trib 25 9.0
END DESCRIPTION:
XS GIS Cut Line= 3
      1273933.04      6938317.56      1274005.00      6937788.00
      1274063.25      6936937.32
#Sta/Elev= 30
  4461.2 2408.56  4509.5 2408.06  4592.1 2404.65  4707.8 2403.11  4773.6 2401.35
  4809.4 2403.11  4824.1 2402.51  4886.9 2398.04  4904.8 2394.47  4935.1 2373.87
  4945.2 2365.65  4959.4 2358.62  4965.4 2353.48  4987.5 2345.02  4988.0 2344.52
  4998.8 2345.02  5055.8 2349.42  5075.8 2352.85  5115.9 2356.44  5136.0 2356.77
  5166.0 2361.25  5276.3 2368.84  5296.3 2372.12  5316.4 2377.32  5336.4 2379.50
  5408.3 2383.11  5496.8 2381.77  5587.0 2390.34  5687.2 2396.88  5848.3 2404.33
#Mann=5,-1,0
  4461.2   0.035       0  4707.8    0.07       0  4987.5    0.07       0
  4998.8    0.07       0  5408.3   0.035       0
Bank Sta=4987.5,4998.8
Exp/Cntr=0.3,0.1

Type RM Length L Ch R = 1,3756,463,463,463
BEGIN DESCRIPTION:
UCFB HW Trib 25 8.0
END DESCRIPTION:
XS GIS Cut Line= 3
      1274330.00      6938363.04      1274355.00      6937738.00
      1274375.71      6937051.55
#Sta/Elev= 30
  4378.9 2399.94  4414.0 2399.21  4474.0 2394.40  4524.1 2389.27  4554.1 2387.50
  4574.1 2385.03  4594.1 2380.73  4634.1 2376.12  4764.2 2363.24  4864.3 2355.02
  4904.4 2349.95  4922.3 2346.64  4944.4 2344.15  4964.4 2344.46  4968.7 2343.27
  4969.2 2342.77  4980.1 2343.27  5014.4 2344.92  5044.5 2349.89  5064.5 2354.61
  5104.5 2366.62  5114.5 2372.16  5144.5 2382.13  5171.7 2386.70  5174.9 2386.32
  5204.5 2390.45  5244.5 2392.44  5344.6 2393.59  5544.7 2401.66  5691.2 2405.79
#Mann=5,-1,0
  4378.9   0.035       0  4922.3    0.07       0  4968.7    0.07       0
  4980.1    0.07       0  5171.7   0.035       0
Bank Sta=4968.7,4980.1
Exp/Cntr=0.3,0.1

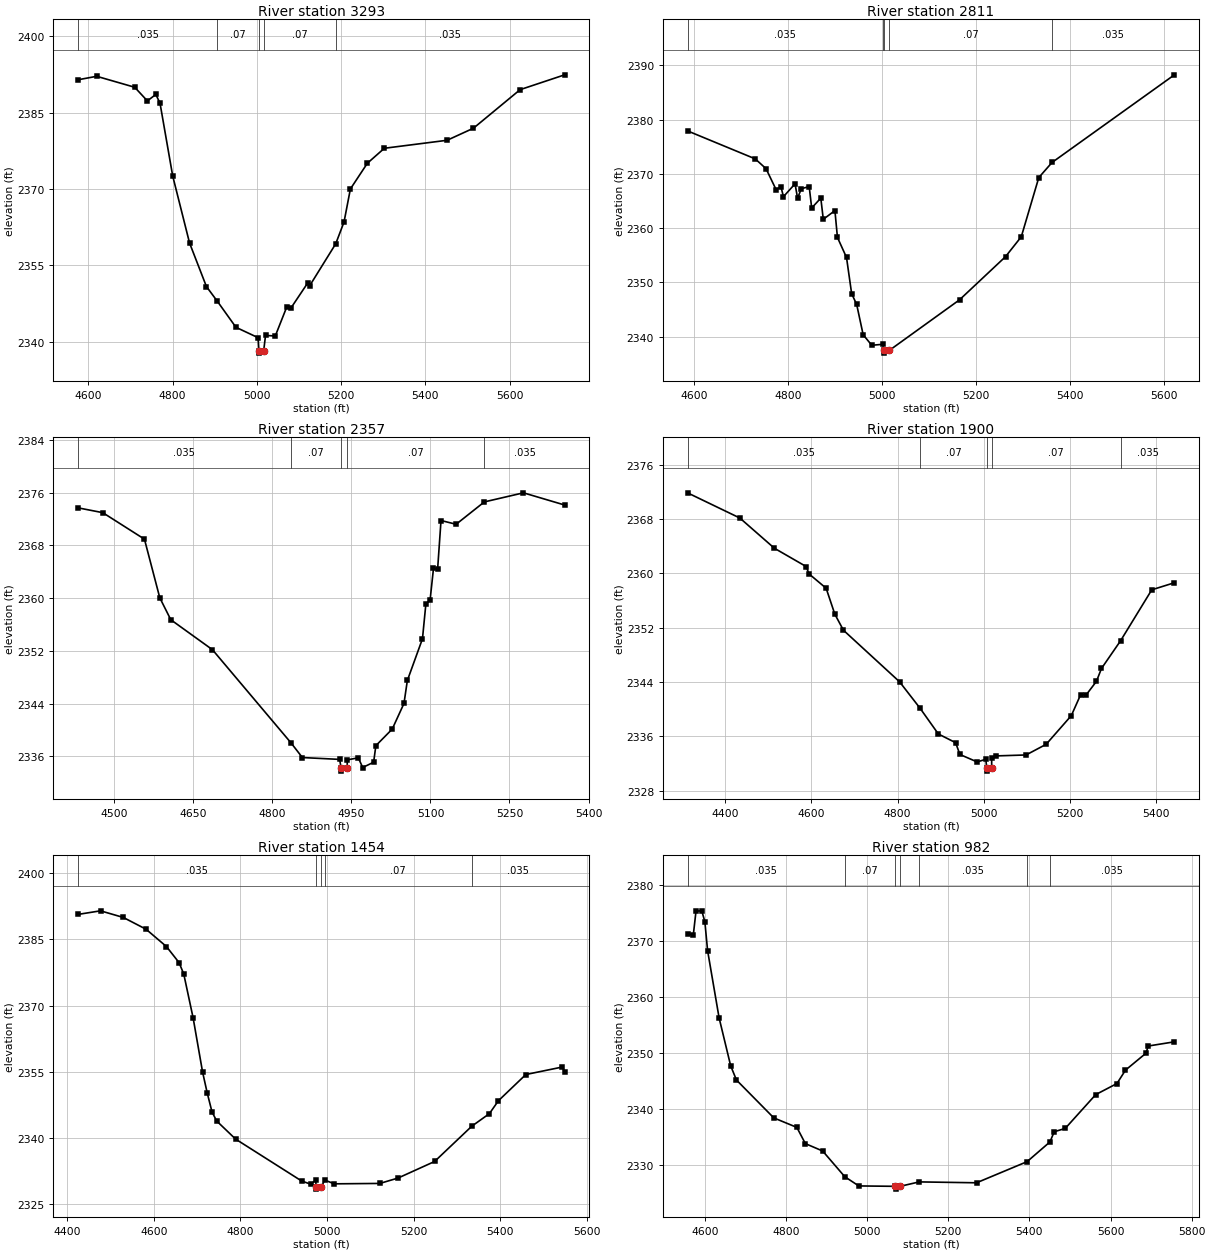
Type RM Length L Ch R = 1,3293,482,482,482
BEGIN DESCRIPTION:
UCFB HW Trib 25 7.0
END DESCRIPTION:
XS GIS Cut Line= 3
      1274730.00      6938312.96      1274755.00      6937888.00
      1274666.55      6937163.08
#Sta/Elev= 30
  4574.8 2391.43  4619.8 2392.12  4710.0 2389.97  4740.1 2387.29  4760.1 2388.56
  4770.1 2386.84  4800.2 2372.56  4840.2 2359.40  4880.3 2350.84  4906.5 2347.92
  4950.4 2342.84  5003.0 2340.80  5004.9 2338.27  5005.4 2337.77  5016.3 2338.27
  5020.6 2341.24  5043.8 2341.14  5071.0 2346.83  5081.1 2346.64  5120.4 2351.50
  5125.4 2350.99  5187.3 2359.24  5207.0 2363.52  5222.1 2370.00  5262.4 2375.05
  5302.7 2377.99  5451.7 2379.56  5514.3 2381.93  5625.1 2389.50  5730.8 2392.41
#Mann=5,-1,0
  4574.8   0.035       0  4906.5    0.07       0  5004.9    0.07       0
  5016.3    0.07       0  5187.3   0.035       0
Bank Sta=5004.9,5016.3
Exp/Cntr=0.3,0.1

Type RM Length L Ch R = 1,2811,454,454,454
BEGIN DESCRIPTION:
UCFB HW Trib 25 6.0
END DESCRIPTION:
XS GIS Cut Line= 3
      1275057.18      6938373.97      1275205.00      6937988.00
      1275299.99      6937372.90
#Sta/Elev= 30
  4586.8 2377.93  4730.8 2372.77  4753.8 2370.96  4775.2 2367.09  4785.5 2367.60
  4790.9 2365.80  4815.5 2368.17  4820.9 2365.51  4828.8 2367.26  4845.6 2367.66
  4850.9 2363.71  4870.3 2365.53  4875.6 2361.62  4900.3 2363.23  4905.7 2358.28
  4925.0 2354.58  4935.9 2347.91  4946.6 2345.92  4960.4 2340.33  4978.7 2338.39
  5002.7 2338.57  5004.5 2337.44  5005.0 2336.94  5016.0 2337.44  5165.5 2346.78
  5263.2 2354.73  5296.8 2358.41  5334.0 2369.32  5362.1 2372.10  5622.5 2388.27
#Mann=5,-1,0
  4586.8   0.035       0  5002.7    0.07       0  5004.5   0.035       0
  5016.0    0.07       0  5362.1   0.035       0
Bank Sta=5004.5,5016
Exp/Cntr=0.3,0.1

Type RM Length L Ch R = 1,2357,457,457,457
BEGIN DESCRIPTION:
UCFB HW Trib 25 5.0
END DESCRIPTION:
XS GIS Cut Line= 3
      1275100.54      6938430.43      1275555.00      6938088.00
      1275829.97      6937863.03
#Sta/Elev= 30
  4430.4 2373.70  4477.9 2372.96  4557.0 2368.94  4586.1 2360.05  4607.0 2356.72
  4686.1 2352.17  4835.3 2338.03  4856.8 2335.81  4927.6 2335.53  4930.2 2334.25
  4930.7 2333.75  4941.7 2334.25  4942.2 2335.46  4963.0 2335.77  4971.3 2334.30
  4992.1 2335.10  4996.3 2337.61  5027.4 2340.13  5049.7 2344.02  5056.1 2347.50
  5084.8 2353.83  5091.3 2359.15  5099.2 2359.65  5105.7 2364.49  5113.6 2364.44
  5120.0 2371.77  5148.7 2371.20  5202.2 2374.59  5276.5 2375.97  5354.7 2374.12
#Mann=5,-1,0
  4430.4   0.035       0  4835.3    0.07       0  4930.2    0.07       0
  4941.7    0.07       0  5202.2   0.035       0
Bank Sta=4930.2,4941.7
Exp/Cntr=0.3,0.1

Type RM Length L Ch R = 1,1900,446,446,446
BEGIN DESCRIPTION:
UCFB HW Trib 25 4.0
END DESCRIPTION:
XS GIS Cut Line= 3
      1275013.76      6938512.87      1275705.00      6938488.00
      1276079.99      6938263.00
#Sta/Elev= 30
  4313.0 2371.85  4434.3 2368.14  4514.4 2363.69  4588.5 2360.98  4594.4 2359.93
  4634.4 2357.80  4654.5 2353.99  4674.5 2351.62  4804.6 2344.03  4852.1 2340.14
  4894.6 2336.34  4934.6 2335.06  4944.6 2333.32  4984.7 2332.22  5004.7 2332.62
  5006.7 2331.37  5007.2 2330.87  5018.2 2331.37  5018.3 2332.81  5028.0 2333.11
  5098.0 2333.25  5144.6 2334.82  5202.9 2339.04  5224.3 2342.09  5237.9 2342.14
  5261.2 2344.09  5272.9 2345.99  5317.1 2350.06  5389.5 2357.57  5442.0 2358.61
#Mann=5,-1,0
  4313.0   0.035       0  4852.1    0.07       0  5006.7    0.07       0
  5018.2    0.07       0  5317.1   0.035       0
Bank Sta=5006.7,5018.2
Exp/Cntr=0.3,0.1

Type RM Length L Ch R = 1,1454,472,472,472
BEGIN DESCRIPTION:
UCFB HW Trib 25 3.0
END DESCRIPTION:
XS GIS Cut Line= 3
      1275730.00      6939363.00      1275955.00      6938838.00
      1276130.01      6938312.98
#Sta/Elev= 30
  4424.5 2390.63  4477.1 2391.45  4529.7 2389.95  4582.3 2387.28  4629.4 2383.35
  4658.4 2379.73  4669.3 2377.15  4691.0 2367.18  4712.8 2354.93  4723.7 2350.12
  4734.6 2345.90  4745.4 2343.84  4789.0 2339.75  4941.3 2330.27  4963.0 2329.51
  4973.9 2330.46  4975.3 2328.91  4975.8 2328.41  4987.0 2328.91  4995.0 2330.47
  5016.8 2329.61  5122.2 2329.70  5164.3 2330.92  5248.7 2334.67  5334.7 2342.67
  5375.2 2345.50  5396.2 2348.44  5459.5 2354.37  5543.8 2356.07  5549.1 2355.01
#Mann=5,-1,0
  4424.5   0.035       0  4975.3    0.07       0  4987.0   0.035       0
  4995.0    0.07       0  5334.7   0.035       0
Bank Sta=4975.3,4987
Exp/Cntr=0.3,0.1

Type RM Length L Ch R = 1,982,251,251,251
BEGIN DESCRIPTION:
UCFB HW Trib 25 2.0
END DESCRIPTION:
XS GIS Cut Line= 5
      1276079.99      6939363.00      1276334.67      6939139.98
      1276355.00      6939038.00      1276376.34      6938934.26
      1276179.99      6938312.98
#Sta/Elev= 30
  4557.5 2371.35  4571.7 2371.08  4578.4 2375.35  4592.6 2375.40  4600.2 2373.47
  4606.9 2368.32  4635.3 2356.31  4663.8 2347.76  4678.0 2345.22  4770.1 2338.46
  4827.0 2336.76  4847.9 2333.87  4890.6 2332.55  4945.0 2327.97  4979.6 2326.32
  5069.7 2326.25  5070.2 2325.75  5081.4 2326.25  5128.6 2327.04  5269.8 2326.88
  5394.4 2330.65  5450.7 2334.17  5461.3 2335.99  5488.4 2336.58  5563.5 2342.61
  5615.9 2344.59  5636.9 2346.98  5687.6 2350.01  5692.8 2351.28  5757.5 2352.03
#Mann=7,-1,0
  4557.5   0.035       0  4945.0    0.07       0  5069.7    0.07       0
  5081.4    0.07       0  5128.6   0.035       0  5394.4    0.07       0
  5450.7   0.035       0
Bank Sta=5069.7,5081.4
Exp/Cntr=0.3,0.1

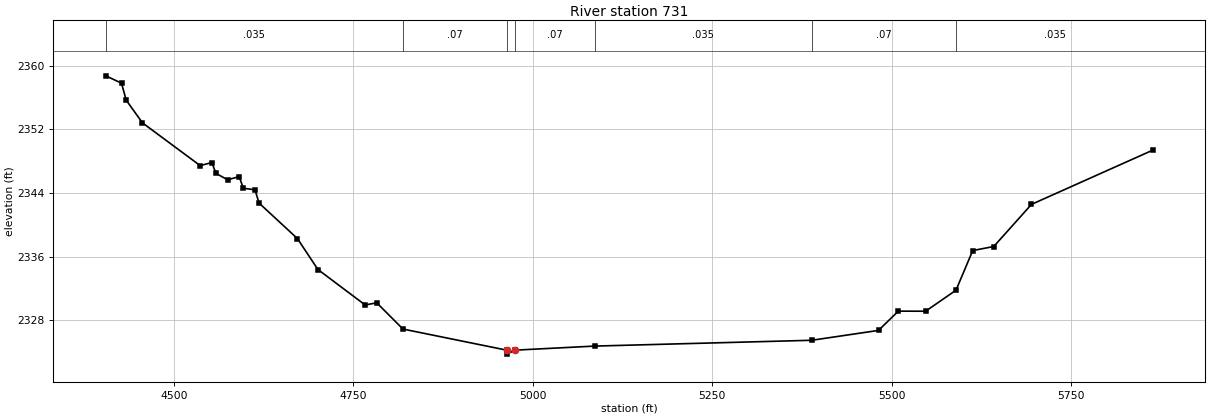
Type RM Length L Ch R = 1,731,0,0,0
BEGIN DESCRIPTION:
UCFB HW Trib 25 1.0
END DESCRIPTION:
XS GIS Cut Line= 5
      1276129.99      6939413.00      1276579.46      6939171.23
      1276589.73      6939087.63      1276579.46      6938957.69
      1276229.98      6938312.97
#Sta/Elev= 30
  4405.4 2358.72  4427.3 2357.80  4433.8 2355.67  4456.5 2352.81  4536.9 2347.44
  4553.1 2347.83  4558.8 2346.47  4575.0 2345.66  4591.2 2346.06  4596.9 2344.60
  4613.2 2344.40  4618.8 2342.74  4672.2 2338.28  4700.8 2334.39  4766.5 2329.94
  4782.8 2330.20  4819.2 2326.91  4963.6 2324.26  4964.1 2323.76  4975.3 2324.26
  5086.2 2324.77  5388.4 2325.50  5481.4 2326.74  5509.0 2329.16  5547.0 2329.15
  5589.3 2331.79  5612.6 2336.77  5641.9 2337.28  5694.4 2342.57  5863.7 2349.40
#Mann=7,-1,0
  4405.4   0.035       0  4819.2    0.07       0  4963.6    0.07       0
  4975.3    0.07       0  5086.2   0.035       0  5388.4    0.07       0
  5589.3   0.035       0
Bank Sta=4963.6,4975.3
Exp/Cntr=0.3,0.1

Chan Stop Cuts=-1