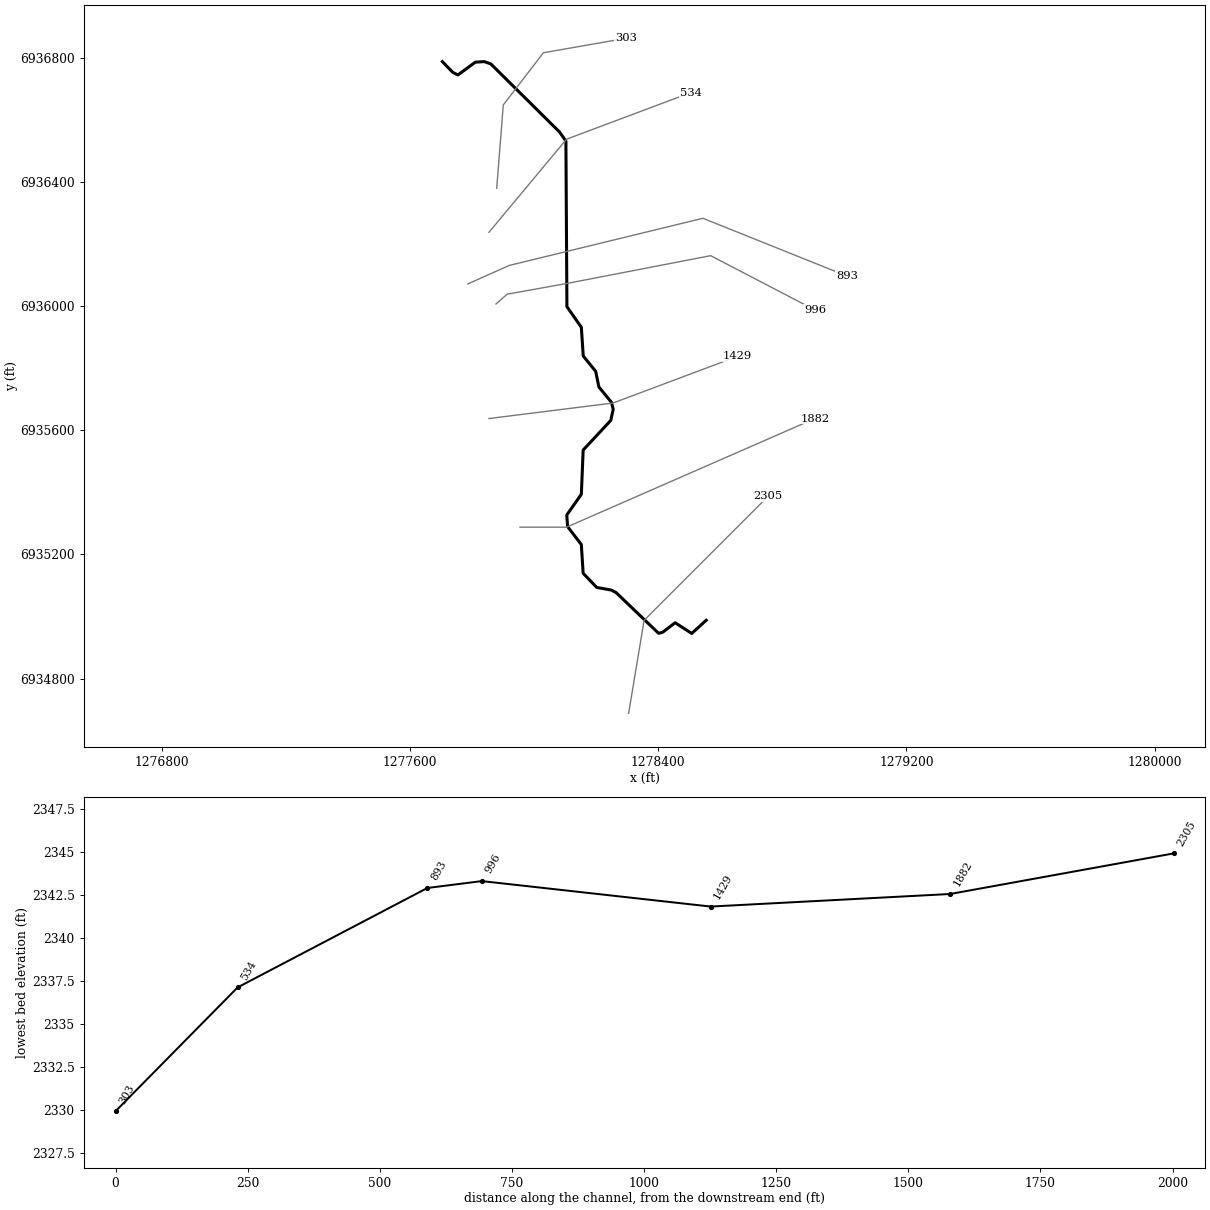
--- UCFB HW Trib 26.prj (project) ---

Proj Title=UCFB HW Trib 26 Base Level Engineering
Current Plan=p01
Default Exp/Contr=0.3,0.1
English Units
Geom File=g01
Flow File=f01
Plan File=p01
BEGIN DESCRIPTION:
UCFB HW Trib 26
END DESCRIPTION:

--- UCFB HW Trib 26.p01 (plan) ---

Plan Title=Multiple Run
Short Identifier=Multiple
Geom File=g01
Flow File=f01
Subcritical Flow
K Sum by GR= 0
Std Step Tol= 0.01
Critical Tol= 0.01
Num of Std Step Trials= 20
Max Error Tol= 0.3
Flow Tol Ratio= 0.001
Split Flow NTrial= 30
Split Flow Tol= 0.02
Split Flow Ratio= 0.02
Log Output Level= 0
Friction Slope Method= 1
Unsteady Friction Slope Method= 2
Unsteady Bridges Friction Slope Method= 1
Parabolic Critical Depth
Global Vel Dist=  1 , 1 , 1
Global Log Level= 0
CheckData=True
Encroach Param= -1, 0, 0, 0
BEGIN DESCRIPTION:
Multiple Run
END DESCRIPTION:

--- UCFB HW Trib 26.f01 (steady flow) ---

Flow Title=Multiple
Number of Profiles=7
Profile Names=10-year,25-year,50-year,1pct_min,100-year,1pct_plu,500-year
River Rch & RM= UCFB HW Trib 26,Reach-1,2305
     259     363     449     276     552    1101     842
Boundary for River Rch & Prof#=UCFB HW Trib 26,Reach-1,1
Up Type=0
Dn Type=3
Dn Slope=0.005
Boundary for River Rch & Prof#=UCFB HW Trib 26,Reach-1,2
Up Type=0
Dn Type=3
Dn Slope=0.005
Boundary for River Rch & Prof#=UCFB HW Trib 26,Reach-1,3
Up Type=0
Dn Type=3
Dn Slope=0.005
Boundary for River Rch & Prof#=UCFB HW Trib 26,Reach-1,4
Up Type=0
Dn Type=3
Dn Slope=0.005
Boundary for River Rch & Prof#=UCFB HW Trib 26,Reach-1,5
Up Type=0
Dn Type=3
Dn Slope=0.005
Boundary for River Rch & Prof#=UCFB HW Trib 26,Reach-1,6
Up Type=0
Dn Type=3
Dn Slope=0.005
Boundary for River Rch & Prof#=UCFB HW Trib 26,Reach-1,7
Up Type=0
Dn Type=3
Dn Slope=0.005

--- UCFB HW Trib 26.g01 (geometry) ---

Geom Title=Existing Conditions

River Reach=UCFB HW Trib 26,Reach-1
Reach XY= 30
      1278555.00      6934988.00      1278508.33      6934945.50
      1278455.00      6934980.11      1278415.00      6934949.65
      1278401.67      6934945.98      1278264.66      6935077.21
      1278248.91      6935085.45      1278202.43      6935093.74
      1278158.52      6935139.28      1278152.62      6935232.03
      1278108.37      6935289.73      1278105.77      6935327.31
      1278152.70      6935393.93      1278158.56      6935536.53
      1278247.50      6935631.95      1278255.37      6935667.80
      1278249.69      6935690.19      1278209.22      6935739.72
      1278198.89      6935790.18      1278158.83      6935839.58
      1278152.64      6935932.02      1278106.22      6935998.50
      1278102.94      6936532.15      1278082.14      6936561.53
      1277861.05      6936780.51      1277839.65      6936788.02
      1277811.04      6936786.14      1277754.88      6936744.95
      1277738.17      6936753.56      1277705.00      6936788.00

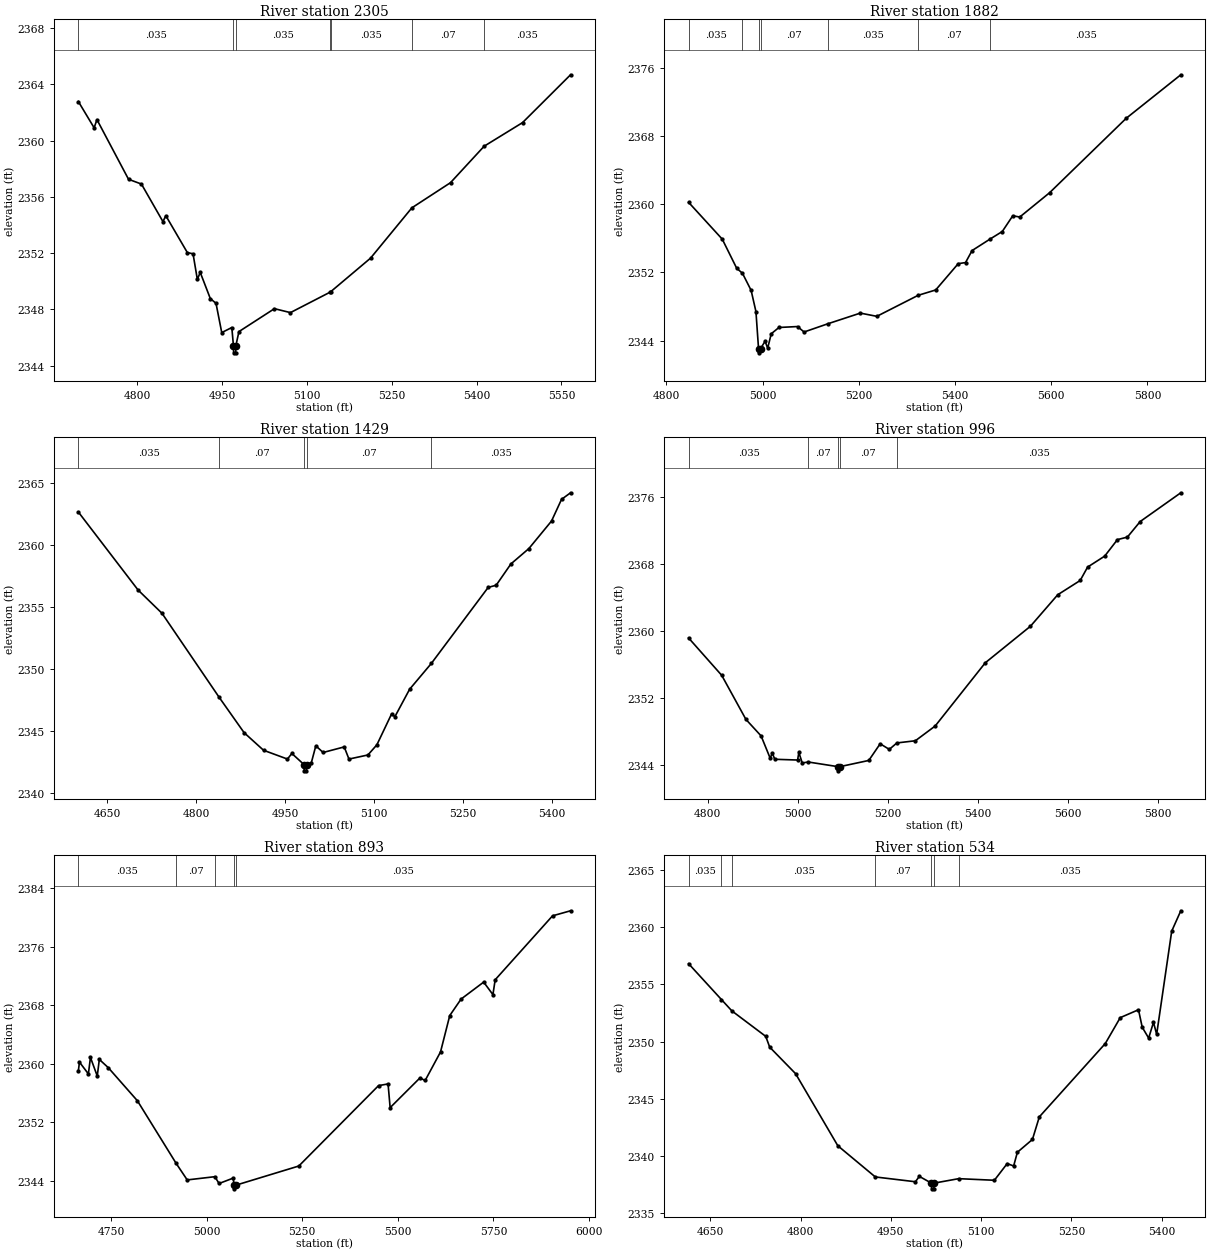
Type RM Length L Ch R = 1,2305,423,423,423
BEGIN DESCRIPTION:
UCFB HW Trib 26 5.0
END DESCRIPTION:
XS GIS Cut Line= 3
      1278305.00      6934688.02      1278355.00      6934988.00
      1278754.99      6935387.99
#Sta/Elev= 30
  4696.3 2362.78  4724.2 2360.91  4729.2 2361.49  4785.0 2357.25  4807.8 2356.91
  4845.8 2354.24  4850.9 2354.66  4888.9 2352.04  4899.0 2351.95  4906.6 2350.13
  4911.7 2350.63  4929.5 2348.77  4939.6 2348.43  4949.7 2346.35  4967.5 2346.71
  4970.4 2345.41  4970.7 2344.91  4974.4 2344.91  4974.6 2345.41  4980.1 2346.42
  5042.8 2348.05  5071.1 2347.77  5141.5 2349.23  5142.7 2349.27  5212.6 2351.64
  5285.7 2355.22  5354.0 2357.01  5413.4 2359.60  5481.3 2361.28  5566.1 2364.68
#Mann=7,-1,0
  4696.3   0.035       0  4970.4   0.035       0  4974.6   0.035       0
  5141.5    0.07       0  5142.7   0.035       0  5285.7    0.07       0
  5413.4   0.035       0
Bank Sta=4970.4,4974.6
Exp/Cntr=0.3,0.1

Type RM Length L Ch R = 1,1882,453,453,453
BEGIN DESCRIPTION:
UCFB HW Trib 26 4.0
END DESCRIPTION:
XS GIS Cut Line= 3
      1277955.00      6935288.00      1278105.00      6935288.00
      1278904.99      6935637.99
#Sta/Elev= 30
  4846.2 2360.24  4916.2 2355.91  4946.2 2352.49  4958.2 2351.90  4976.2 2349.89
  4986.2 2347.40  4991.6 2343.05  4991.9 2342.55  4995.8 2343.05  5005.2 2343.91
  5010.6 2343.10  5018.0 2344.79  5034.0 2345.53  5072.6 2345.64  5086.3 2345.00
  5135.9 2345.97  5203.2 2347.22  5237.5 2346.84  5323.4 2349.31  5359.9 2349.94
  5406.7 2353.03  5421.9 2353.16  5435.5 2354.57  5473.4 2355.94  5498.3 2356.81
  5520.1 2358.66  5534.6 2358.51  5596.5 2361.36  5756.0 2370.12  5869.4 2375.23
#Mann=7,-1,0
  4846.2   0.035       0  4958.2    0.07       0  4991.6    0.07       0
  4995.8    0.07       0  5135.9   0.035       0  5323.4    0.07       0
  5473.4   0.035       0
Bank Sta=4991.6,4995.8
Exp/Cntr=0.3,0.1

Type RM Length L Ch R = 1,1429,433,433,433
BEGIN DESCRIPTION:
UCFB HW Trib 26 3.0
END DESCRIPTION:
XS GIS Cut Line= 3
      1277855.04      6935638.00      1278255.00      6935688.00
      1278655.02      6935838.01
#Sta/Elev= 30
  4600.9 2362.70  4701.6 2356.41  4742.0 2354.53  4838.6 2347.74  4880.5 2344.90
  4913.3 2343.48  4953.6 2342.77  4961.1 2343.22  4981.7 2342.32  4982.0 2341.82
  4985.7 2341.82  4986.0 2342.32  4993.9 2342.47  5001.5 2343.84  5013.8 2343.30
  5049.4 2343.75  5057.4 2342.77  5089.4 2343.10  5104.5 2343.92  5129.5 2346.43
  5134.8 2346.18  5159.7 2348.40  5196.3 2350.48  5292.3 2356.62  5305.7 2356.79
  5330.6 2358.51  5360.9 2359.75  5399.1 2361.97  5416.0 2363.72  5431.2 2364.25
#Mann=5,-1,0
  4600.9   0.035       0  4838.6    0.07       0  4981.7    0.07       0
  4986.0    0.07       0  5196.3   0.035       0
Bank Sta=4981.7,4986
Exp/Cntr=0.3,0.1

Type RM Length L Ch R = 1,996,103,103,103
BEGIN DESCRIPTION:
UCFB HW Trib 26 2.0
END DESCRIPTION:
XS GIS Cut Line= 5
      1277877.55      6936007.08      1277913.77      6936038.68
      1278104.86      6936072.94      1278569.34      6936162.78
      1278904.98      6935988.01
#Sta/Elev= 30
  4757.8 2359.16  4831.4 2354.70  4885.2 2349.44  4918.9 2347.47  4938.9 2344.83
  4944.0 2345.40  4949.3 2344.68  5000.0 2344.59  5002.8 2345.49  5010.3 2344.25
  5024.2 2344.35  5089.7 2343.80  5090.0 2343.30  5094.0 2343.80  5158.2 2344.54
  5183.5 2346.53  5203.8 2345.86  5220.6 2346.63  5261.7 2346.89  5305.7 2348.65
  5417.1 2356.20  5517.4 2360.56  5578.1 2364.32  5627.9 2366.02  5644.4 2367.62
  5682.4 2368.93  5710.7 2370.90  5732.8 2371.20  5761.3 2373.06  5851.5 2376.49
#Mann=5,-1,0
  4757.8   0.035       0  5024.2    0.07       0  5089.7   0.035       0
  5094.0    0.07       0  5220.6   0.035       0
Bank Sta=5089.7,5094
Exp/Cntr=0.3,0.1

Type RM Length L Ch R = 1,893,359,359,359
BEGIN DESCRIPTION:
UCFB HW Trib 26 1.5
END DESCRIPTION:
XS GIS Cut Line= 4
      1277787.17      6936071.78      1277920.47      6936131.31
      1278544.39      6936283.22      1279008.04      6936097.24
#Sta/Elev= 30
  4664.1 2359.03  4667.1 2360.22  4690.4 2358.61  4695.8 2360.86  4713.6 2358.32
  4719.0 2360.59  4742.3 2359.47  4818.6 2354.94  4920.0 2346.38  4948.9 2344.12
  5021.2 2344.56  5032.3 2343.63  5068.9 2344.36  5071.9 2343.40  5072.2 2342.90
  5076.2 2343.40  5240.9 2346.02  5449.5 2357.01  5474.4 2357.24  5479.8 2354.00
  5557.8 2358.06  5571.4 2357.71  5611.6 2361.61  5635.8 2366.59  5665.4 2368.84
  5724.5 2371.16  5748.7 2369.45  5754.6 2371.48  5904.7 2380.22  5951.8 2380.91
#Mann=5,-1,0
  4664.1   0.035       0  4920.0    0.07       0  5021.2   0.035       0
  5071.9    0.07       0  5076.2   0.035       0
Bank Sta=5071.9,5076.2
Exp/Cntr=0.3,0.1

Type RM Length L Ch R = 1,534,231,231,231
BEGIN DESCRIPTION:
UCFB HW Trib 26 1.0
END DESCRIPTION:
XS GIS Cut Line= 3
      1277855.02      6936238.02      1278105.00      6936538.00
      1278505.02      6936688.01
#Sta/Elev= 30
  4614.0 2356.82  4668.6 2353.68  4685.9 2352.69  4742.2 2350.46  4748.7 2349.52
  4791.7 2347.20  4861.9 2340.89  4924.2 2338.16  4990.8 2337.74  4997.3 2338.21
  5017.4 2337.62  5017.7 2337.12  5021.5 2337.12  5021.8 2337.62  5062.7 2338.01
  5122.0 2337.87  5143.3 2339.33  5154.0 2339.12  5160.2 2340.32  5185.2 2341.44
  5196.7 2343.42  5306.2 2349.83  5331.1 2352.10  5361.4 2352.79  5367.6 2351.26
  5378.3 2350.31  5386.3 2351.69  5391.6 2350.64  5416.6 2359.67  5431.7 2361.45
#Mann=7,-1,0
  4614.0   0.035       0  4668.6    0.07       0  4685.9   0.035       0
  4924.2    0.07       0  5017.4    0.07       0  5021.8    0.07       0
  5062.7   0.035       0
Bank Sta=5017.4,5021.8
Exp/Cntr=0.3,0.1

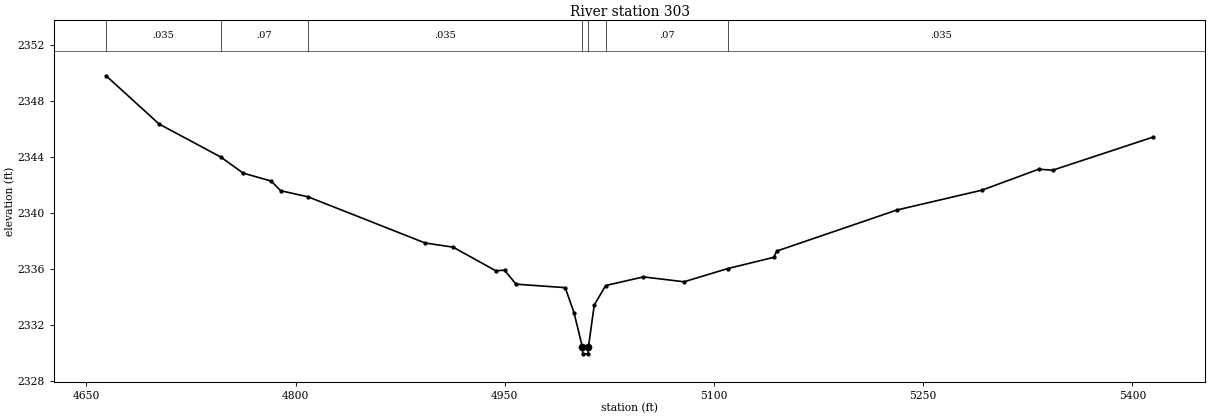
Type RM Length L Ch R = 1,303,0,0,0
BEGIN DESCRIPTION:
UCFB HW Trib 26 0.5
END DESCRIPTION:
XS GIS Cut Line= 4
      1277880.00      6936380.01      1277901.19      6936648.43
      1278030.53      6936816.57      1278295.82      6936863.00
#Sta/Elev= 30
  4664.1 2349.83  4702.2 2346.37  4746.2 2344.02  4762.4 2342.86  4782.5 2342.29
  4789.3 2341.60  4809.0 2341.16  4892.8 2337.86  4912.9 2337.56  4943.5 2335.87
  4949.8 2335.91  4958.0 2334.91  4993.3 2334.66  4999.6 2332.87  5005.6 2330.42
  5005.9 2329.92  5009.7 2329.92  5010.0 2330.42  5014.1 2333.41  5022.3 2334.81
  5049.4 2335.43  5078.5 2335.08  5110.0 2336.03  5142.8 2336.83  5145.0 2337.28
  5231.2 2340.22  5292.1 2341.64  5332.8 2343.14  5342.9 2343.07  5414.8 2345.44
#Mann=7,-1,0
  4664.1   0.035       0  4746.2    0.07       0  4809.0   0.035       0
  5005.6   0.035       0  5010.0   0.035       0  5022.3    0.07       0
  5110.0   0.035       0
Bank Sta=5005.6,5010
Exp/Cntr=0.3,0.1

Chan Stop Cuts=-1