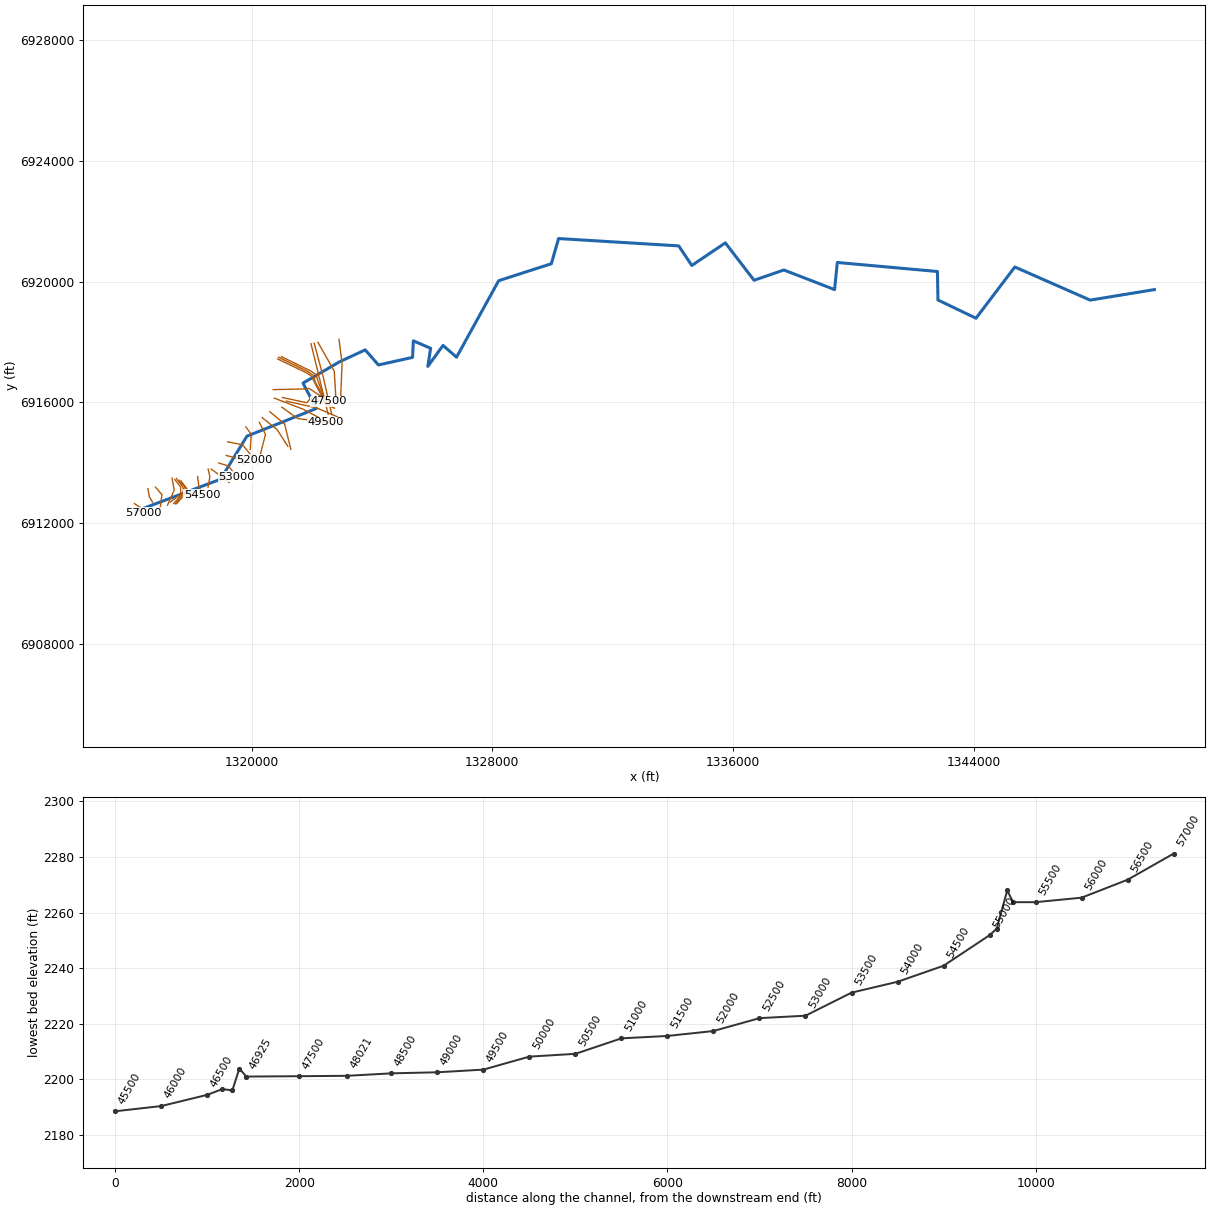
--- Bull Creek.prj (project) ---

Proj Title=Bull Creek Base Level Engineering
Current Plan=p01
Default Exp/Contr=0.3,0.1
English Units
Geom File=g01
Flow File=f01
Plan File=p01
BEGIN DESCRIPTION:
Bull Creek
END DESCRIPTION:

--- Bull Creek.p01 (plan) ---

Plan Title=Multiple Run
Short Identifier=Multiple
Geom File=g01
Flow File=f01
Subcritical Flow
K Sum by GR= 0
Std Step Tol= 0.01
Critical Tol= 0.01
Num of Std Step Trials= 20
Max Error Tol= 0.3
Flow Tol Ratio= 0.001
Split Flow NTrial= 30
Split Flow Tol= 0.02
Split Flow Ratio= 0.02
Log Output Level= 0
Friction Slope Method= 1
Unsteady Friction Slope Method= 2
Unsteady Bridges Friction Slope Method= 1
Parabolic Critical Depth
Global Vel Dist=  1 , 1 , 1
Global Log Level= 0
CheckData=True
Encroach Param= -1, 0, 0, 0
BEGIN DESCRIPTION:
Multiple Run
END DESCRIPTION:

--- Bull Creek.f01 (steady flow) ---

Flow Title=Multiple
Number of Profiles=7
Profile Names=10-year,25-year,50-year,1pct_min,100-year,1pct_plu,500-year
River Rch & RM= Bull Creek,Reach-1,57000
     360     526     671     425     849    1694    1378
River Rch & RM= Bull Creek,Reach-1,54500
     439     644     823     523    1043    2081    1698
River Rch & RM= Bull Creek,Reach-1,48500
     607     906    1170     750    1497    2986    2484
River Rch & RM= Bull Creek,Reach-1,46925
     629     934    1203     768    1533    3059    2526
River Rch & RM= Bull Creek,Reach-1,39500
     722    1077    1390     890    1775    3542    2936
River Rch & RM= Bull Creek,Reach-1,35000
     762    1137    1468     939    1874    3738    3096
River Rch & RM= Bull Creek,Reach-1,29393
     975    1469    1908    1228    2449    4887    4095
River Rch & RM= Bull Creek,Reach-1,25000
    1172    1779    2323    1502    2997    5980    5059
River Rch & RM= Bull Creek,Reach-1,23620
    1476    2255    2957    1919    3828    7638    6507
River Rch & RM= Bull Creek,Reach-1,17000
    1457    2221    2909    1884    3760    7502    6372
River Rch & RM= Bull Creek,Reach-1,14000
    1520    2319    3039    1970    3931    7842    6668
River Rch & RM= Bull Creek,Reach-1,11500
    1534    2342    3069    1989    3969    7918    6732
River Rch & RM= Bull Creek,Reach-1,10000
    1627    2482    3251    2105    4200    8380    7112
Boundary for River Rch & Prof#=Bull Creek,Reach-1,1
Up Type=0
Dn Type=3
Dn Slope=0.005
Boundary for River Rch & Prof#=Bull Creek,Reach-1,2
Up Type=0
Dn Type=3
Dn Slope=0.005
Boundary for River Rch & Prof#=Bull Creek,Reach-1,3
Up Type=0
Dn Type=3
Dn Slope=0.005
Boundary for River Rch & Prof#=Bull Creek,Reach-1,4
Up Type=0
Dn Type=3
Dn Slope=0.005
Boundary for River Rch & Prof#=Bull Creek,Reach-1,5
Up Type=0
Dn Type=3
Dn Slope=0.005
Boundary for River Rch & Prof#=Bull Creek,Reach-1,6
Up Type=0
Dn Type=3
Dn Slope=0.005
Boundary for River Rch & Prof#=Bull Creek,Reach-1,7
Up Type=0
Dn Type=3
Dn Slope=0.005

--- Bull Creek.g01 (geometry) ---

Geom Title=Existing Conditions

River Reach=Bull Creek,Reach-1
Reach XY= 30
      1316155.00      6912388.00      1318965.13      6913448.27
      1319845.29      6914877.25      1322149.42      6915793.58
      1321708.46      6916636.50      1322906.70      6917334.70
      1323774.94      6917738.26      1324215.47      6917238.57
      1325349.12      6917489.48      1325375.01      6918038.45
      1325949.92      6917790.86      1325856.40      6917191.00
      1326360.71      6917886.12      1326811.20      6917495.80
      1328210.61      6920032.41      1329961.48      6920595.69
      1330201.43      6921430.47      1334194.72      6921187.03
      1334629.69      6920537.73      1335744.73      6921287.02
      1336698.25      6920047.10      1337689.78      6920387.51
      1339374.99      6919737.94      1339465.33      6920637.13
      1342794.32      6920337.25      1342810.47      6919393.42
      1344075.10      6918787.90      1345365.48      6920486.81
      1347870.88      6919388.51      1350005.00      6919738.00

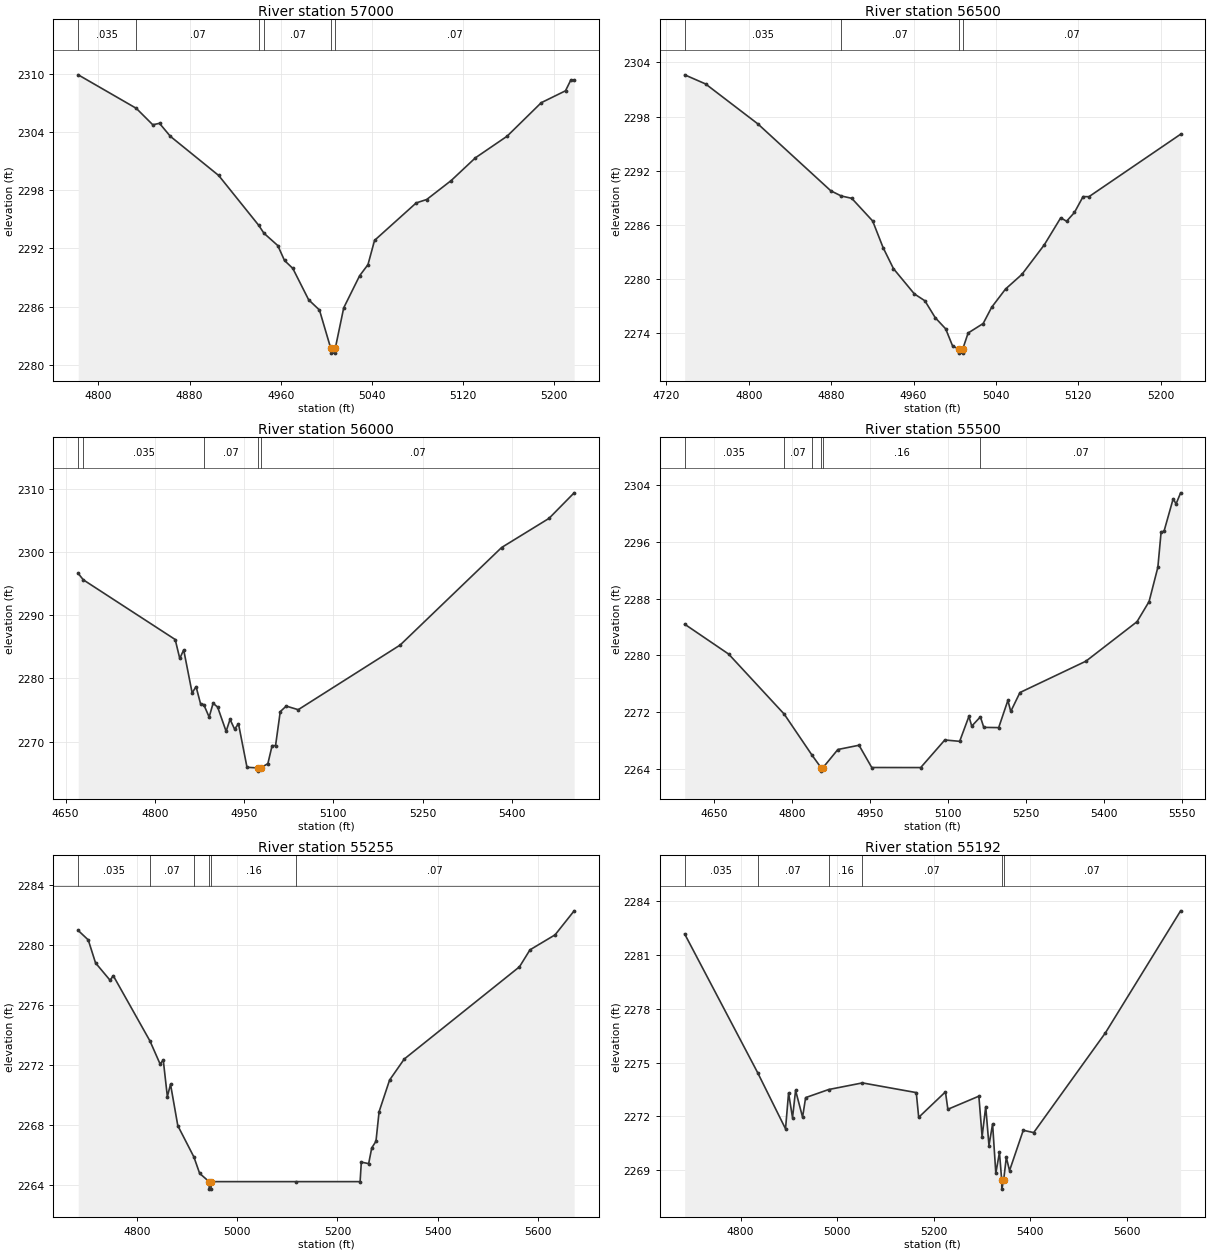
Type RM Length L Ch R = 1,57000,500,500,500
BEGIN DESCRIPTION:
Bull Creek 114.0
END DESCRIPTION:
XS GIS Cut Line= 3
      1316104.98      6912638.01      1316289.89      6912522.93
      1316404.99      6912338.02
#Sta/Elev= 30
  4782.2 2309.94  4833.2 2306.48  4847.7 2304.78  4853.6 2304.93  4863.1 2303.59
  4905.6 2299.54  4940.7 2294.40  4945.3 2293.58  4957.5 2292.30  4963.4 2290.76
  4970.7 2289.94  4984.6 2286.70  4994.1 2285.64  5004.0 2281.69  5004.2 2281.19
  5007.7 2281.19  5008.0 2281.69  5015.4 2285.87  5029.4 2289.19  5036.7 2290.33
  5042.5 2292.84  5079.1 2296.71  5088.3 2297.06  5109.8 2299.02  5131.1 2301.37
  5158.9 2303.60  5188.9 2307.06  5210.2 2308.29  5214.9 2309.41  5217.8 2309.41
#Mann=6,-1,0
  4782.2   0.035       0  4833.2    0.07       0  4940.7   0.035       0
  4945.3    0.07       0  5004.0    0.07       0  5008.0    0.07       0
Bank Sta=5004,5008
Exp/Cntr=0.3,0.1

Type RM Length L Ch R = 1,56500,500,500,500
BEGIN DESCRIPTION:
Bull Creek 113.0
END DESCRIPTION:
XS GIS Cut Line= 3
      1316555.00      6913138.03      1316597.81      6912879.34
      1316704.99      6912688.02
#Sta/Elev= 30
  4737.8 2302.63  4758.1 2301.62  4808.8 2297.20  4879.7 2289.78  4889.8 2289.21
  4900.0 2288.95  4920.3 2286.44  4930.4 2283.50  4940.5 2281.16  4960.8 2278.36
  4971.0 2277.60  4981.1 2275.72  4991.2 2274.49  4998.1 2272.54  5003.9 2272.30
  5004.1 2271.80  5007.6 2271.80  5007.9 2272.30  5013.0 2274.03  5027.6 2275.08
  5035.9 2276.89  5049.3 2278.90  5065.2 2280.52  5086.9 2283.79  5102.9 2286.79
  5108.6 2286.41  5116.2 2287.38  5124.6 2289.14  5130.3 2289.13  5219.3 2296.05
#Mann=4,-1,0
  4737.8   0.035       0  4889.8    0.07       0  5003.9    0.07       0
  5007.9    0.07       0
Bank Sta=5003.9,5007.9
Exp/Cntr=0.3,0.1

Type RM Length L Ch R = 1,56000,500,500,500
BEGIN DESCRIPTION:
Bull Creek 112.0
END DESCRIPTION:
XS GIS Cut Line= 3
      1316804.97      6913188.03      1317019.29      6912938.68
      1316955.00      6912437.99
#Sta/Elev= 30
  4671.2 2296.59  4679.8 2295.58  4834.2 2286.15  4841.9 2283.15  4848.5 2284.51
  4862.7 2277.71  4869.3 2278.70  4877.0 2275.93  4882.2 2275.87  4891.3 2273.89
  4897.9 2276.07  4905.5 2275.48  4919.8 2271.64  4926.4 2273.53  4934.0 2271.99
  4940.6 2272.82  4954.9 2265.96  4973.8 2265.85  4974.0 2265.35  4977.8 2265.85
  4990.0 2266.54  4997.1 2269.38  5002.9 2269.38  5010.8 2274.75  5020.8 2275.63
  5041.0 2275.06  5212.4 2285.28  5382.9 2300.69  5462.5 2305.29  5504.8 2309.33
#Mann=5,-1,0
  4671.2    0.07       0  4679.8   0.035       0  4882.2    0.07       0
  4973.8    0.07       0  4977.8    0.07       0
Bank Sta=4973.8,4977.8
Exp/Cntr=0.3,0.1

Type RM Length L Ch R = 1,55500,245,245,245
BEGIN DESCRIPTION:
Bull Creek 111.0
END DESCRIPTION:
XS GIS Cut Line= 3
      1317355.01      6913487.95      1317428.64      6913087.97
      1317205.00      6912588.01
#Sta/Elev= 30
  4593.3 2284.39  4677.9 2280.19  4784.8 2271.75  4838.4 2265.97  4855.6 2264.23
  4855.9 2263.73  4859.6 2264.23  4888.1 2266.77  4928.8 2267.37  4953.3 2264.24
  5047.5 2264.23  5093.9 2268.11  5122.5 2267.92  5140.3 2271.43  5145.7 2270.06
  5162.4 2271.36  5168.9 2269.88  5197.6 2269.85  5215.3 2273.68  5220.8 2272.12
  5238.5 2274.78  5365.5 2279.19  5463.8 2284.74  5487.0 2287.57  5503.9 2292.39
  5510.2 2297.38  5515.7 2297.44  5533.4 2302.03  5538.9 2301.30  5547.7 2302.86
#Mann=6,-1,0
  4593.3   0.035       0  4784.8    0.07       0  4838.4    0.16       0
  4855.6    0.07       0  4859.6    0.16       0  5162.4    0.07       0
Bank Sta=4855.6,4859.6
Exp/Cntr=0.3,0.1

Type RM Length L Ch R = 1,55255,63,63,63
BEGIN DESCRIPTION:
Bull Creek 110.7
END DESCRIPTION:
XS GIS Cut Line= 4
      1317448.81      6913440.12      1317642.06      6913189.55
      1317641.95      6912944.34      1317299.39      6912690.49
#Sta/Elev= 30
  4683.5 2280.97  4703.5 2280.34  4718.0 2278.81  4747.0 2277.65  4753.3 2277.96
  4826.5 2273.60  4846.6 2272.07  4852.9 2272.34  4861.1 2269.90  4867.4 2270.72
  4881.9 2267.96  4914.0 2265.87  4925.4 2264.78  4944.2 2264.23  4944.5 2263.73
  4948.0 2263.73  4948.2 2264.23  5116.9 2264.23  5245.1 2264.23  5247.5 2265.53
  5262.1 2265.43  5268.3 2266.48  5276.7 2266.92  5282.9 2268.89  5303.8 2271.00
  5333.0 2272.40  5562.6 2278.55  5583.5 2279.68  5633.5 2280.68  5671.5 2282.28
#Mann=6,-1,0
  4683.5   0.035       0  4826.5    0.07       0  4914.0    0.16       0
  4944.2    0.07       0  4948.2    0.16       0  5116.9    0.07       0
Bank Sta=4944.2,4948.2
Exp/Cntr=0.3,0.1

Type RM Length L Ch R = 1,55192,115,115,115
BEGIN DESCRIPTION:
Bull Creek 110.6
END DESCRIPTION:
XS GIS Cut Line= 5
      1317499.82      6913474.83      1317693.05      6913224.27
      1317738.52      6913120.12      1317714.65      6912979.06
      1317410.50      6912642.44
#Sta/Elev= 30
  4684.3 2282.17  4835.4 2274.44  4893.1 2271.31  4899.4 2273.31  4907.6 2271.93
  4913.9 2273.45  4928.4 2271.96  4934.7 2273.05  4982.3 2273.50  5052.3 2273.87
  5163.8 2273.33  5168.8 2271.95  5224.2 2273.37  5229.2 2272.40  5293.4 2273.13
  5300.1 2270.88  5307.6 2272.55  5314.3 2270.38  5321.8 2271.58  5328.5 2268.83
  5336.0 2270.00  5340.7 2268.45  5340.9 2267.95  5344.7 2268.45  5350.2 2269.72
  5356.9 2268.98  5385.3 2271.23  5406.9 2271.10  5555.4 2276.66  5711.1 2283.46
#Mann=6,-1,0
  4684.3   0.035       0  4835.4    0.07       0  4982.3    0.16       0
  5052.3    0.07       0  5340.7    0.07       0  5344.7    0.07       0
Bank Sta=5340.7,5344.7
Exp/Cntr=0.3,0.1

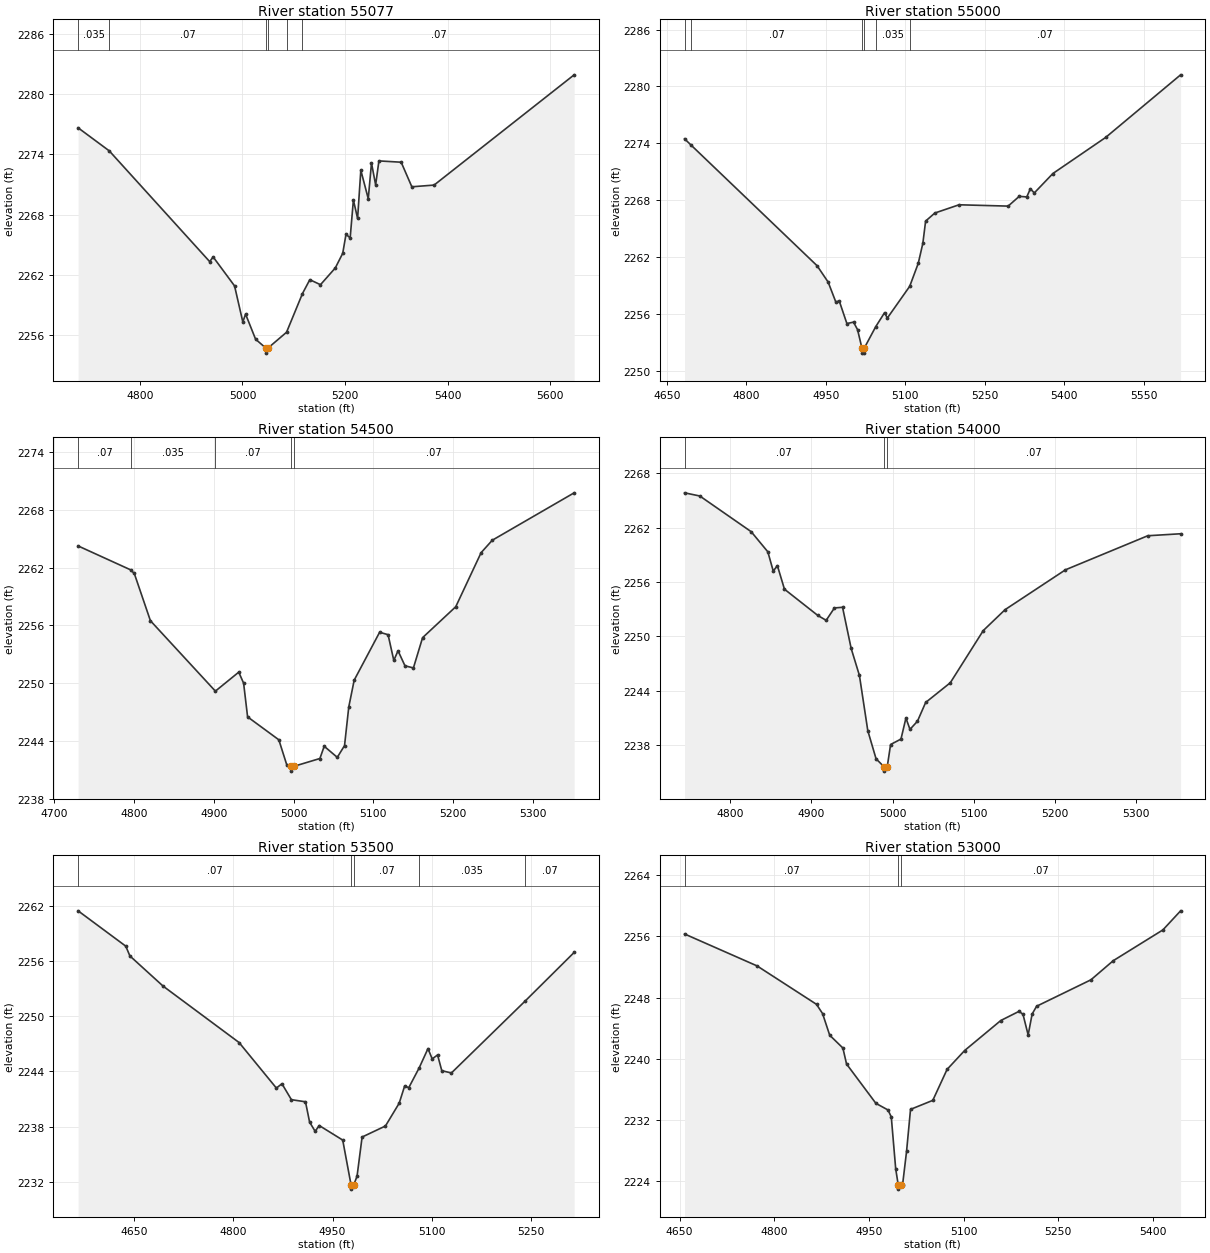
Type RM Length L Ch R = 1,55077,77,77,77
BEGIN DESCRIPTION:
Bull Creek 110.5
END DESCRIPTION:
XS GIS Cut Line= 5
      1317586.64      6913411.87      1317772.15      6913204.75
      1317779.86      6913161.33      1317802.54      6913069.12
      1317463.97      6912635.06
#Sta/Elev= 30
  4679.4 2276.66  4740.2 2274.36  4936.1 2263.32  4942.8 2263.79  4984.6 2260.90
  5000.7 2257.31  5006.1 2258.09  5025.6 2255.59  5045.7 2254.70  5045.9 2254.20
  5049.7 2254.70  5086.0 2256.28  5117.1 2260.14  5131.4 2261.52  5152.2 2261.02
  5181.1 2262.69  5195.6 2264.15  5202.0 2266.05  5210.1 2265.68  5216.4 2269.47
  5224.6 2267.62  5230.9 2272.43  5245.4 2269.59  5251.7 2273.15  5259.8 2270.97
  5266.2 2273.36  5309.6 2273.23  5330.4 2270.78  5373.8 2270.95  5647.0 2281.94
#Mann=6,-1,0
  4679.4   0.035       0  4740.2    0.07       0  5045.7    0.07       0
  5049.7    0.07       0  5086.0   0.035       0  5117.1    0.07       0
Bank Sta=5045.7,5049.7
Exp/Cntr=0.3,0.1

Type RM Length L Ch R = 1,55000,500,500,500
BEGIN DESCRIPTION:
Bull Creek 110.0
END DESCRIPTION:
XS GIS Cut Line= 4
      1317654.99      6913388.01      1317848.22      6913137.46
      1317796.03      6912958.44      1317505.03      6912638.04
#Sta/Elev= 30
  4683.6 2274.47  4696.0 2273.80  4933.6 2261.08  4954.5 2259.35  4969.0 2257.24
  4975.3 2257.38  4989.8 2254.98  5002.3 2255.13  5009.9 2254.34  5018.3 2252.36
  5018.5 2251.86  5022.0 2251.86  5022.3 2252.36  5044.1 2254.64  5060.9 2256.13
  5066.1 2255.56  5108.3 2258.91  5124.4 2261.33  5133.1 2263.45  5138.3 2265.79
  5155.7 2266.64  5201.4 2267.51  5294.0 2267.37  5314.9 2268.40  5329.1 2268.34
  5335.9 2269.20  5343.3 2268.76  5378.4 2270.81  5477.8 2274.61  5619.3 2281.22
#Mann=6,-1,0
  4683.6   0.035       0  4696.0    0.07       0  5018.3    0.07       0
  5022.3    0.07       0  5044.1   0.035       0  5108.3    0.07       0
Bank Sta=5018.3,5022.3
Exp/Cntr=0.3,0.1

Type RM Length L Ch R = 1,54500,500,500,500
BEGIN DESCRIPTION:
Bull Creek 109.0
END DESCRIPTION:
XS GIS Cut Line= 3
      1318205.00      6913538.01      1318237.39      6913269.56
      1318355.00      6912938.00
#Sta/Elev= 30
  4729.6 2264.25  4795.4 2261.77  4800.1 2261.39  4820.3 2256.49  4901.8 2249.18
  4931.1 2251.15  4937.2 2250.01  4942.2 2246.51  4981.4 2244.13  4991.5 2241.49
  4996.2 2241.38  4996.5 2240.88  5000.4 2241.38  5032.9 2242.19  5038.3 2243.46
  5054.7 2242.31  5063.8 2243.53  5069.1 2247.53  5075.9 2250.32  5107.8 2255.29
  5118.4 2255.04  5125.6 2252.37  5130.9 2253.37  5139.6 2251.81  5150.2 2251.59
  5161.7 2254.73  5203.3 2257.94  5235.1 2263.55  5249.1 2264.84  5351.8 2269.76
#Mann=5,-1,0
  4729.6    0.07       0  4795.4   0.035       0  4901.8    0.07       0
  4996.2    0.07       0  5000.4    0.07       0
Bank Sta=4996.2,5000.4
Exp/Cntr=0.3,0.1

Type RM Length L Ch R = 1,54000,500,500,500
BEGIN DESCRIPTION:
Bull Creek 108.0
END DESCRIPTION:
XS GIS Cut Line= 3
      1318555.01      6913787.97      1318612.83      6913538.17
      1318555.00      6913188.02
#Sta/Elev= 30
  4743.6 2265.85  4762.4 2265.50  4825.7 2261.56  4846.2 2259.34  4852.9 2257.21
  4858.0 2257.81  4866.7 2255.21  4907.8 2252.31  4918.1 2251.77  4928.3 2253.14
  4938.3 2253.21  4948.9 2248.67  4959.1 2245.68  4969.4 2239.59  4979.6 2236.48
  4989.2 2235.62  4989.4 2235.12  4993.4 2235.62  4997.5 2238.06  5010.3 2238.66
  5016.4 2240.98  5021.4 2239.73  5030.6 2240.63  5040.7 2242.70  5071.1 2244.88
  5111.7 2250.64  5138.6 2252.95  5213.0 2257.35  5314.4 2261.11  5354.9 2261.33
#Mann=3,-1,0
  4743.6    0.07       0  4989.2    0.07       0  4993.4    0.07       0
Bank Sta=4989.2,4993.4
Exp/Cntr=0.3,0.1

Type RM Length L Ch R = 1,53500,500,500,500
BEGIN DESCRIPTION:
Bull Creek 107.0
END DESCRIPTION:
XS GIS Cut Line= 3
      1318655.02      6913787.99      1319005.42      6913530.73
      1319254.97      6913338.02
#Sta/Elev= 30
  4565.3 2261.45  4637.4 2257.61  4643.6 2256.55  4693.8 2253.27  4808.7 2247.14
  4865.1 2242.19  4873.5 2242.66  4887.8 2240.93  4909.1 2240.70  4915.3 2238.50
  4923.7 2237.49  4929.9 2238.12  4965.4 2236.54  4977.9 2231.71  4978.2 2231.21
  4982.3 2231.71  4987.1 2232.63  4994.7 2236.87  5030.0 2238.07  5050.8 2240.55
  5059.0 2242.41  5065.3 2242.24  5081.1 2244.40  5094.3 2246.48  5100.7 2245.36
  5108.8 2245.79  5115.2 2244.08  5129.7 2243.83  5241.4 2251.66  5315.3 2256.93
#Mann=5,-1,0
  4565.3    0.07       0  4977.9    0.07       0  4982.3    0.07       0
  5081.1   0.035       0  5241.4    0.07       0
Bank Sta=4977.9,4982.3
Exp/Cntr=0.3,0.1

Type RM Length L Ch R = 1,53000,500,500,500
BEGIN DESCRIPTION:
Bull Creek 106.0
END DESCRIPTION:
XS GIS Cut Line= 3
      1318904.98      6913988.01      1319232.22      6913888.27
      1319505.03      6913537.97
#Sta/Elev= 30
  4657.9 2256.33  4772.8 2252.15  4867.0 2247.12  4876.6 2245.91  4887.9 2243.08
  4908.8 2241.40  4914.6 2239.31  4961.1 2234.16  4980.3 2233.29  4985.5 2232.38
  4992.5 2225.58  4996.6 2223.43  4996.9 2222.93  5001.0 2223.43  5003.3 2223.43
  5009.7 2227.87  5016.0 2233.37  5051.3 2234.55  5073.9 2238.60  5101.7 2241.07
  5159.0 2245.00  5187.9 2246.20  5194.2 2245.82  5202.4 2243.11  5208.7 2245.85
  5215.8 2246.87  5301.9 2250.33  5337.2 2252.83  5415.9 2256.86  5444.0 2259.36
#Mann=3,-1,0
  4657.9    0.07       0  4996.6    0.07       0  5001.0    0.07       0
Bank Sta=4996.6,5001
Exp/Cntr=0.3,0.1

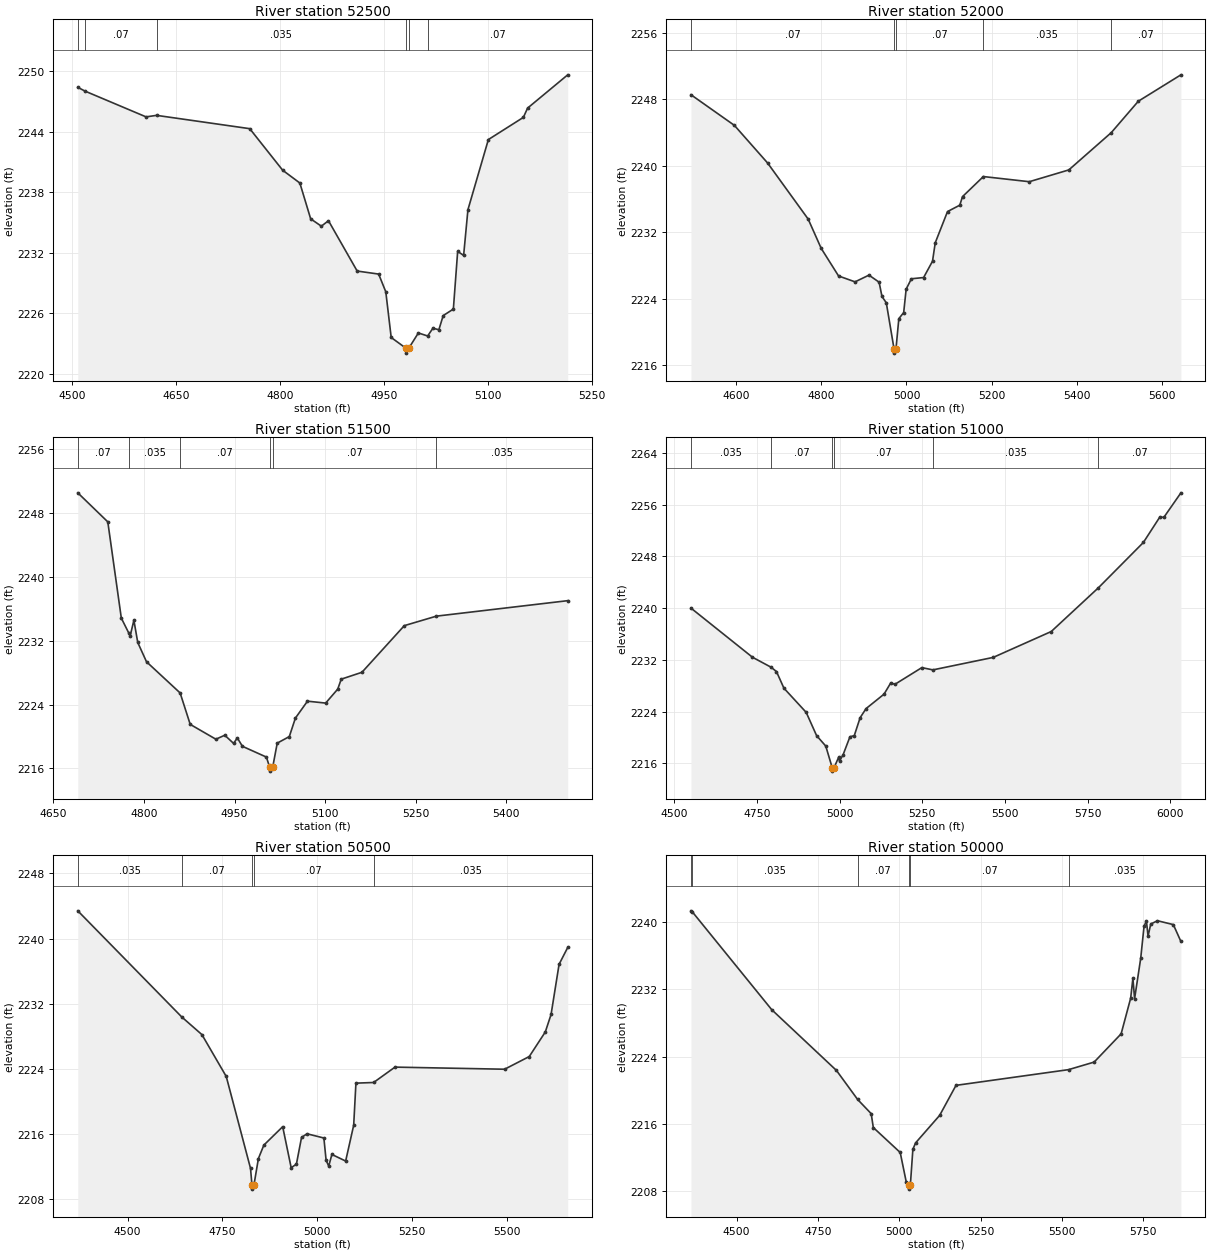
Type RM Length L Ch R = 1,52500,500,500,500
BEGIN DESCRIPTION:
Bull Creek 105.0
END DESCRIPTION:
XS GIS Cut Line= 3
      1319155.01      6914238.00      1319630.92      6914113.60
      1319754.99      6913938.01
#Sta/Elev= 30
  4508.1 2248.41  4518.7 2248.03  4606.6 2245.48  4621.8 2245.63  4756.2 2244.31
  4803.7 2240.19  4828.5 2238.92  4844.1 2235.37  4859.5 2234.64  4869.8 2235.18
  4911.2 2230.19  4942.2 2229.89  4952.5 2228.13  4960.3 2223.60  4981.3 2222.55
  4981.6 2222.05  4985.8 2222.55  4999.5 2224.05  5012.9 2223.75  5020.5 2224.52
  5029.1 2224.37  5035.3 2225.77  5050.0 2226.42  5056.2 2232.14  5064.8 2231.74
  5071.0 2236.27  5100.5 2243.23  5151.0 2245.43  5157.1 2246.35  5215.0 2249.65
#Mann=6,-1,0
  4508.1   0.035       0  4518.7    0.07       0  4621.8   0.035       0
  4981.3   0.035       0  4985.8   0.035       0  5012.9    0.07       0
Bank Sta=4981.3,4985.8
Exp/Cntr=0.3,0.1

Type RM Length L Ch R = 1,52000,500,500,500
BEGIN DESCRIPTION:
Bull Creek 104.0
END DESCRIPTION:
XS GIS Cut Line= 3
      1319205.00      6914688.00      1319701.38      6914590.28
      1320105.03      6914087.97
#Sta/Elev= 30
  4494.1 2248.56  4596.0 2244.87  4673.9 2240.34  4769.3 2233.57  4799.9 2230.04
  4840.6 2226.72  4879.3 2226.01  4912.0 2226.82  4935.8 2225.97  4942.5 2224.25
  4952.7 2223.48  4970.9 2217.92  4971.2 2217.42  4975.4 2217.92  4982.1 2221.57
  4993.5 2222.31  4999.3 2225.13  5011.6 2226.38  5040.3 2226.53  5061.2 2228.50
  5067.6 2230.72  5096.4 2234.48  5125.2 2235.25  5131.6 2236.28  5180.6 2238.70
  5288.4 2238.08  5381.2 2239.50  5481.0 2244.00  5544.4 2247.78  5644.4 2250.96
#Mann=5,-1,0
  4494.1    0.07       0  4970.9    0.07       0  4975.4    0.07       0
  5180.6   0.035       0  5481.0    0.07       0
Bank Sta=4970.9,4975.4
Exp/Cntr=0.3,0.1

Type RM Length L Ch R = 1,51500,500,500,500
BEGIN DESCRIPTION:
Bull Creek 103.0
END DESCRIPTION:
XS GIS Cut Line= 3
      1319805.00      6915188.00      1319988.52      6914938.65
      1319955.00      6914437.97
#Sta/Elev= 30
  4690.4 2250.54  4740.1 2246.90  4762.5 2234.83  4774.8 2232.97  4777.1 2232.59
  4783.3 2234.56  4789.7 2231.78  4804.2 2229.36  4859.9 2225.45  4876.6 2221.51
  4919.1 2219.65  4933.8 2220.15  4948.4 2219.13  4954.6 2219.81  4963.1 2218.76
  5002.8 2217.41  5008.1 2216.15  5008.5 2215.65  5013.2 2216.15  5020.7 2219.16
  5040.7 2219.98  5050.8 2222.30  5070.8 2224.42  5100.9 2224.18  5120.9 2225.93
  5126.7 2227.18  5161.0 2228.04  5231.2 2233.89  5284.3 2235.08  5501.8 2237.02
#Mann=6,-1,0
  4690.4    0.07       0  4774.8   0.035       0  4859.9    0.07       0
  5008.1    0.07       0  5013.2    0.07       0  5284.3   0.035       0
Bank Sta=5008.1,5013.2
Exp/Cntr=0.3,0.1

Type RM Length L Ch R = 1,51000,500,500,500
BEGIN DESCRIPTION:
Bull Creek 102.0
END DESCRIPTION:
XS GIS Cut Line= 3
      1320254.98      6915338.03      1320460.40      6914937.99
      1320205.00      6913937.99
#Sta/Elev= 30
  4550.3 2239.99  4736.1 2232.40  4792.6 2230.85  4808.9 2230.18  4831.4 2227.61
  4898.8 2223.87  4930.2 2220.28  4958.0 2218.66  4977.6 2215.29  4978.0 2214.79
  4982.7 2215.29  4996.7 2216.90  4999.6 2216.35  5010.3 2217.31  5031.0 2220.09
  5044.2 2220.28  5061.9 2223.05  5079.9 2224.46  5134.2 2226.69  5154.8 2228.45
  5166.8 2228.20  5248.5 2230.79  5282.0 2230.44  5464.4 2232.37  5639.9 2236.37
  5782.5 2243.13  5918.6 2250.14  5968.2 2254.06  5980.5 2254.02  6032.1 2257.81
#Mann=6,-1,0
  4550.3   0.035       0  4792.6    0.07       0  4977.6    0.07       0
  4982.7    0.07       0  5282.0   0.035       0  5782.5    0.07       0
Bank Sta=4977.6,4982.7
Exp/Cntr=0.3,0.1

Type RM Length L Ch R = 1,50500,500,500,500
BEGIN DESCRIPTION:
Bull Creek 101.0
END DESCRIPTION:
XS GIS Cut Line= 3
      1320355.00      6915488.00      1320847.80      6915093.58
      1321205.00      6914538.00
#Sta/Elev= 30
  4368.8 2243.41  4642.9 2230.37  4696.1 2228.20  4760.2 2223.06  4824.2 2211.77
  4828.0 2209.72  4828.4 2209.22  4833.2 2209.72  4845.0 2212.98  4859.4 2214.63
  4909.0 2216.89  4931.4 2211.85  4945.2 2212.29  4958.7 2215.57  4973.1 2216.02
  5017.6 2215.50  5023.5 2212.76  5030.4 2212.05  5038.7 2213.48  5075.0 2212.67
  5096.2 2217.07  5102.1 2222.24  5148.7 2222.32  5205.1 2224.21  5494.1 2223.95
  5559.1 2225.51  5601.4 2228.53  5616.6 2230.68  5637.7 2236.84  5660.5 2238.91
#Mann=5,-1,0
  4368.8   0.035       0  4642.9    0.07       0  4828.0    0.07       0
  4833.2    0.07       0  5148.7   0.035       0
Bank Sta=4828,4833.2
Exp/Cntr=0.3,0.1

Type RM Length L Ch R = 1,50000,500,500,500
BEGIN DESCRIPTION:
Bull Creek 100.0
END DESCRIPTION:
XS GIS Cut Line= 3
      1320604.96      6915688.03      1321097.20      6915278.54
      1321304.99      6914438.04
#Sta/Elev= 30
  4359.7 2241.34  4363.6 2241.23  4607.8 2229.58  4807.0 2222.34  4872.0 2218.89
  4913.7 2217.20  4920.2 2215.55  5002.9 2212.58  5021.2 2209.12  5028.8 2208.72
  5029.3 2208.22  5034.1 2208.72  5041.8 2212.95  5050.1 2213.72  5124.2 2217.00
  5174.4 2220.57  5520.4 2222.44  5599.1 2223.34  5682.0 2226.70  5711.3 2230.94
  5718.2 2233.32  5723.4 2230.88  5742.2 2235.69  5752.5 2239.52  5759.7 2240.13
  5764.8 2238.33  5773.1 2239.77  5793.7 2240.16  5842.5 2239.70  5865.8 2237.69
#Mann=6,-1,0
  4359.7    0.07       0  4363.6   0.035       0  4872.0    0.07       0
  5028.8    0.07       0  5034.1    0.07       0  5520.4   0.035       0
Bank Sta=5028.8,5034.1
Exp/Cntr=0.3,0.1

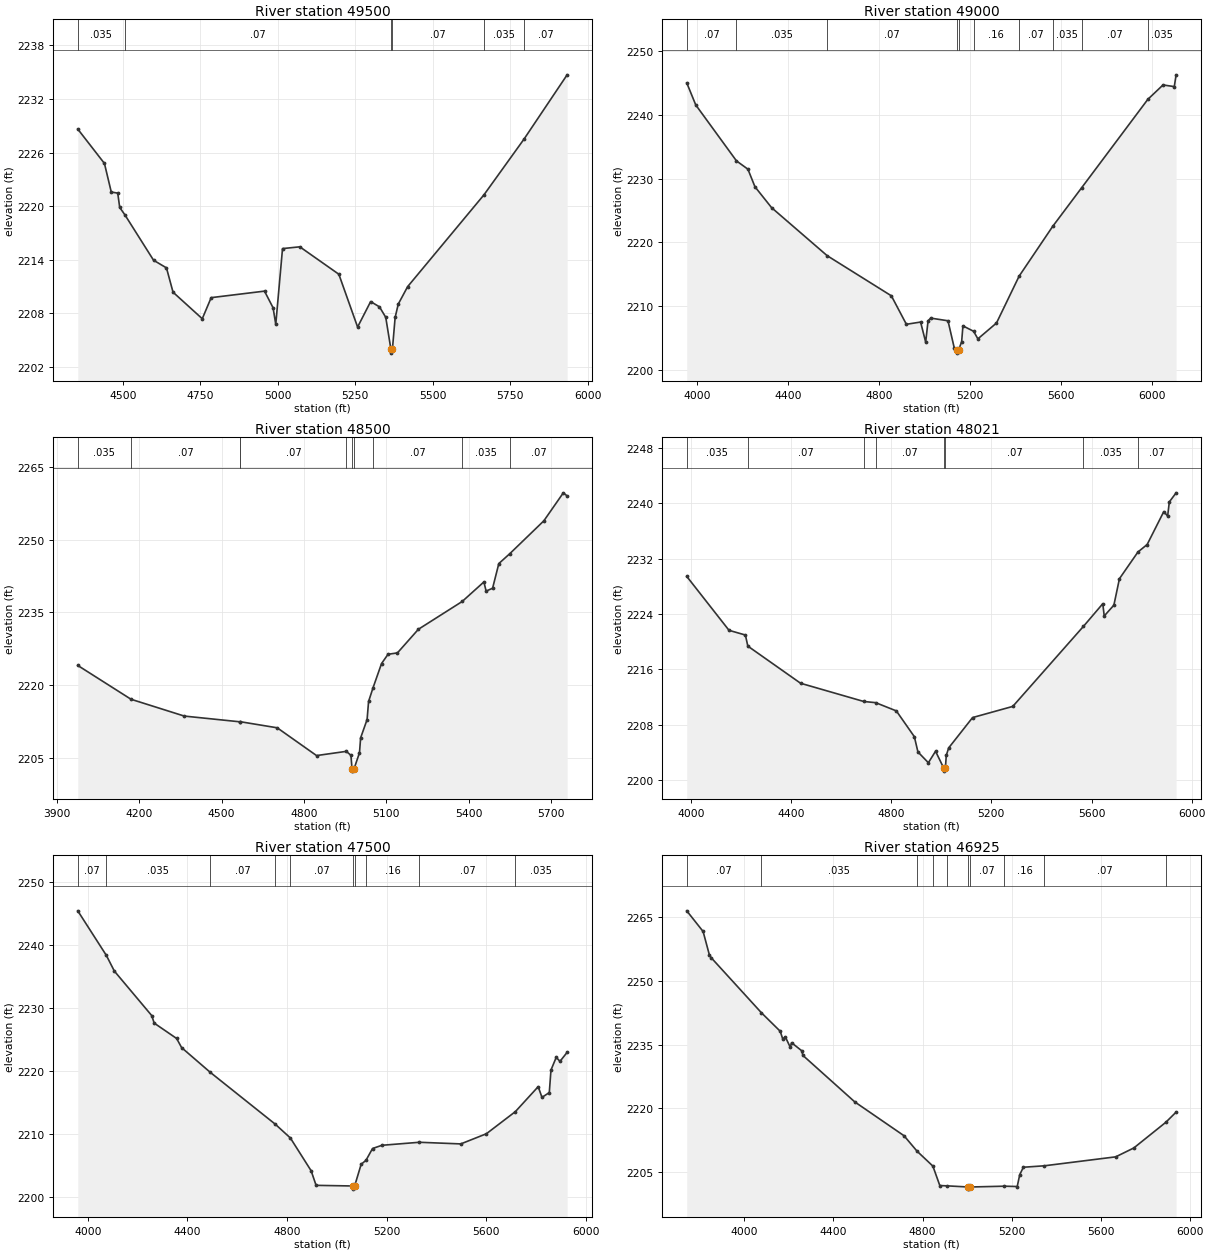
Type RM Length L Ch R = 1,49500,500,500,500
BEGIN DESCRIPTION:
Bull Creek 99.0
END DESCRIPTION:
XS GIS Cut Line= 3
      1321005.00      6915838.00      1321529.70      6915462.52
      1322454.95      6915338.01
#Sta/Elev= 30
  4354.8 2228.63  4440.9 2224.78  4462.9 2221.58  4483.8 2221.46  4490.1 2219.86
  4507.2 2219.01  4599.3 2213.95  4641.0 2213.09  4662.2 2210.37  4756.5 2207.40
  4785.2 2209.76  4957.3 2210.49  4985.0 2208.62  4993.6 2206.77  5015.4 2215.25
  5071.2 2215.45  5197.1 2212.38  5257.6 2206.47  5299.7 2209.32  5328.2 2208.73
  5348.4 2207.56  5364.8 2204.05  5365.2 2203.55  5370.1 2204.05  5378.7 2207.54
  5388.8 2209.04  5419.0 2210.99  5665.3 2221.27  5794.6 2227.51  5933.6 2234.70
#Mann=6,-1,0
  4354.8   0.035       0  4507.2    0.07       0  5364.8    0.07       0
  5370.1    0.07       0  5665.3   0.035       0  5794.6    0.07       0
Bank Sta=5364.8,5370.1
Exp/Cntr=0.3,0.1

Type RM Length L Ch R = 1,49000,500,500,500
BEGIN DESCRIPTION:
Bull Creek 98.0
END DESCRIPTION:
XS GIS Cut Line= 3
      1320755.04      6916137.99      1321730.29      6915763.44
      1322704.98      6915238.01
#Sta/Elev= 30
  3955.3 2245.04  3994.9 2241.57  4174.0 2232.78  4224.3 2231.48  4255.2 2228.72
  4328.3 2225.44  4572.6 2217.90  4855.1 2211.59  4921.1 2207.12  4983.6 2207.47
  5006.0 2204.32  5016.5 2207.67  5028.1 2208.09  5104.1 2207.67  5131.7 2203.40
  5145.2 2203.09  5145.7 2202.59  5150.6 2203.09  5164.1 2204.36  5169.8 2206.87
  5216.8 2206.02  5235.5 2204.83  5317.4 2207.32  5416.9 2214.68  5564.4 2222.49
  5692.0 2228.57  5982.9 2242.45  6049.7 2244.71  6099.2 2244.45  6107.3 2246.30
#Mann=10,-1,0
  3955.3    0.07       0  4174.0   0.035       0  4572.6    0.07       0
  5145.2    0.07       0  5150.6    0.07       0  5216.8    0.16       0
  5416.9    0.07       0  5564.4   0.035       0  5692.0    0.07       0
  5982.9   0.035       0
Bank Sta=5145.2,5150.6
Exp/Cntr=0.3,0.1

Type RM Length L Ch R = 1,48500,479,479,479
BEGIN DESCRIPTION:
Bull Creek 97.0
END DESCRIPTION:
XS GIS Cut Line= 3
      1321154.97      6916038.01      1322155.49      6915816.25
      1322854.13      6915518.08
#Sta/Elev= 30
  3975.2 2224.02  4169.4 2217.04  4363.7 2213.57  4567.7 2212.38  4568.5 2212.40
  4702.5 2211.15  4845.9 2205.42  4954.4 2206.29  4971.3 2205.47  4975.2 2202.71
  4975.7 2202.21  4982.8 2202.71  5002.5 2206.01  5006.6 2209.07  5030.2 2212.85
  5035.6 2216.58  5051.5 2219.35  5082.9 2224.41  5106.5 2226.32  5140.9 2226.61
  5217.2 2231.48  5377.0 2237.22  5456.1 2241.25  5464.2 2239.36  5487.8 2239.95
  5510.5 2245.04  5550.7 2247.09  5674.8 2253.87  5745.7 2259.64  5759.6 2259.00
#Mann=10,-1,0
  3975.2   0.035       0  4169.4    0.07       0  4567.7    0.16       0
  4568.5    0.07       0  4954.4    0.16       0  4975.2    0.07       0
  4982.8    0.16       0  5051.5    0.07       0  5377.0   0.035       0
  5550.7    0.07       0
Bank Sta=4975.2,4982.8
Exp/Cntr=0.3,0.1

Type RM Length L Ch R = 1,48021,521,521,521
BEGIN DESCRIPTION:
Bull Creek 96.0
END DESCRIPTION:
XS GIS Cut Line= 5
      1321026.00      6916158.71      1321836.15      6915984.45
      1321955.12      6916130.51      1321988.75      6916197.37
      1322755.15      6915801.08
#Sta/Elev= 30
  3983.3 2229.43  4152.1 2221.65  4217.5 2220.97  4227.3 2219.37  4438.0 2214.01
  4690.4 2211.38  4737.9 2211.21  4820.5 2210.02  4892.4 2206.30  4906.7 2204.10
  4948.4 2202.54  4977.1 2204.20  5008.9 2201.83  5009.4 2201.33  5016.6 2201.83
  5019.9 2203.59  5029.5 2204.68  5125.0 2209.06  5285.6 2210.67  5567.6 2222.21
  5645.1 2225.49  5650.8 2223.72  5689.4 2225.28  5711.6 2229.10  5785.5 2232.95
  5822.3 2234.03  5888.7 2238.78  5904.1 2238.14  5910.9 2240.18  5938.0 2241.49
#Mann=8,-1,0
  3983.3   0.035       0  4227.3    0.07       0  4690.4    0.16       0
  4737.9    0.07       0  5008.9    0.07       0  5016.6    0.07       0
  5567.6   0.035       0  5785.5    0.07       0
Bank Sta=5008.9,5016.6
Exp/Cntr=0.3,0.1

Type RM Length L Ch R = 1,47500,575,575,575
BEGIN DESCRIPTION:
Bull Creek 95.0
END DESCRIPTION:
XS GIS Cut Line= 4
      1320718.05      6916420.27      1321757.78      6916443.96
      1321900.37      6916464.54      1322555.00      6916038.00
#Sta/Elev= 30
  3960.0 2245.37  4074.9 2238.29  4107.0 2235.80  4257.0 2228.74  4267.0 2227.54
  4357.1 2225.10  4377.1 2223.65  4492.3 2219.72  4753.3 2211.49  4813.9 2209.30
  4897.2 2204.10  4917.2 2201.78  5064.3 2201.68  5064.8 2201.18  5072.0 2201.68
  5098.2 2205.13  5117.3 2205.74  5143.9 2207.63  5181.5 2208.14  5331.8 2208.62
  5498.3 2208.36  5601.0 2209.97  5717.6 2213.49  5809.2 2217.45  5824.3 2215.75
  5853.8 2216.51  5860.5 2220.09  5881.6 2222.10  5896.7 2221.47  5925.4 2222.90
#Mann=10,-1,0
  3960.0    0.07       0  4074.9   0.035       0  4492.3    0.07       0
  4753.3    0.16       0  4813.9    0.07       0  5064.3    0.07       0
  5072.0    0.07       0  5117.3    0.16       0  5331.8    0.07       0
  5717.6   0.035       0
Bank Sta=5064.3,5072
Exp/Cntr=0.3,0.1

Type RM Length L Ch R = 1,46925,76,76,76
BEGIN DESCRIPTION:
Bull Creek 94.7
END DESCRIPTION:
XS GIS Cut Line= 4
      1320866.52      6917435.89      1321824.85      6916977.56
      1321975.89      6916878.60      1322420.59      6916038.62
#Sta/Elev= 30
  3742.8 2266.41  3816.1 2261.56  3844.3 2256.04  3852.0 2255.42  4077.3 2242.48
  4161.7 2238.13  4173.4 2236.25  4184.4 2236.83  4206.7 2234.37  4212.6 2235.44
  4258.0 2233.55  4263.5 2232.45  4495.8 2221.54  4716.6 2213.59  4775.2 2209.95
  4845.9 2206.46  4877.0 2201.89  4908.8 2201.82  5005.0 2201.55  5005.5 2201.05
  5013.0 2201.55  5166.7 2201.74  5223.9 2201.66  5235.3 2204.46  5251.6 2206.19
  5345.6 2206.53  5665.2 2208.63  5746.3 2210.71  5889.8 2216.74  5936.1 2219.14
#Mann=10,-1,0
  3742.8    0.07       0  4077.3   0.035       0  4775.2    0.07       0
  4845.9    0.16       0  4908.8    0.07       0  5005.0    0.07       0
  5013.0    0.07       0  5166.7    0.16       0  5345.6    0.07       0
  5889.8   0.035       0
Bank Sta=5005,5013
Exp/Cntr=0.3,0.1

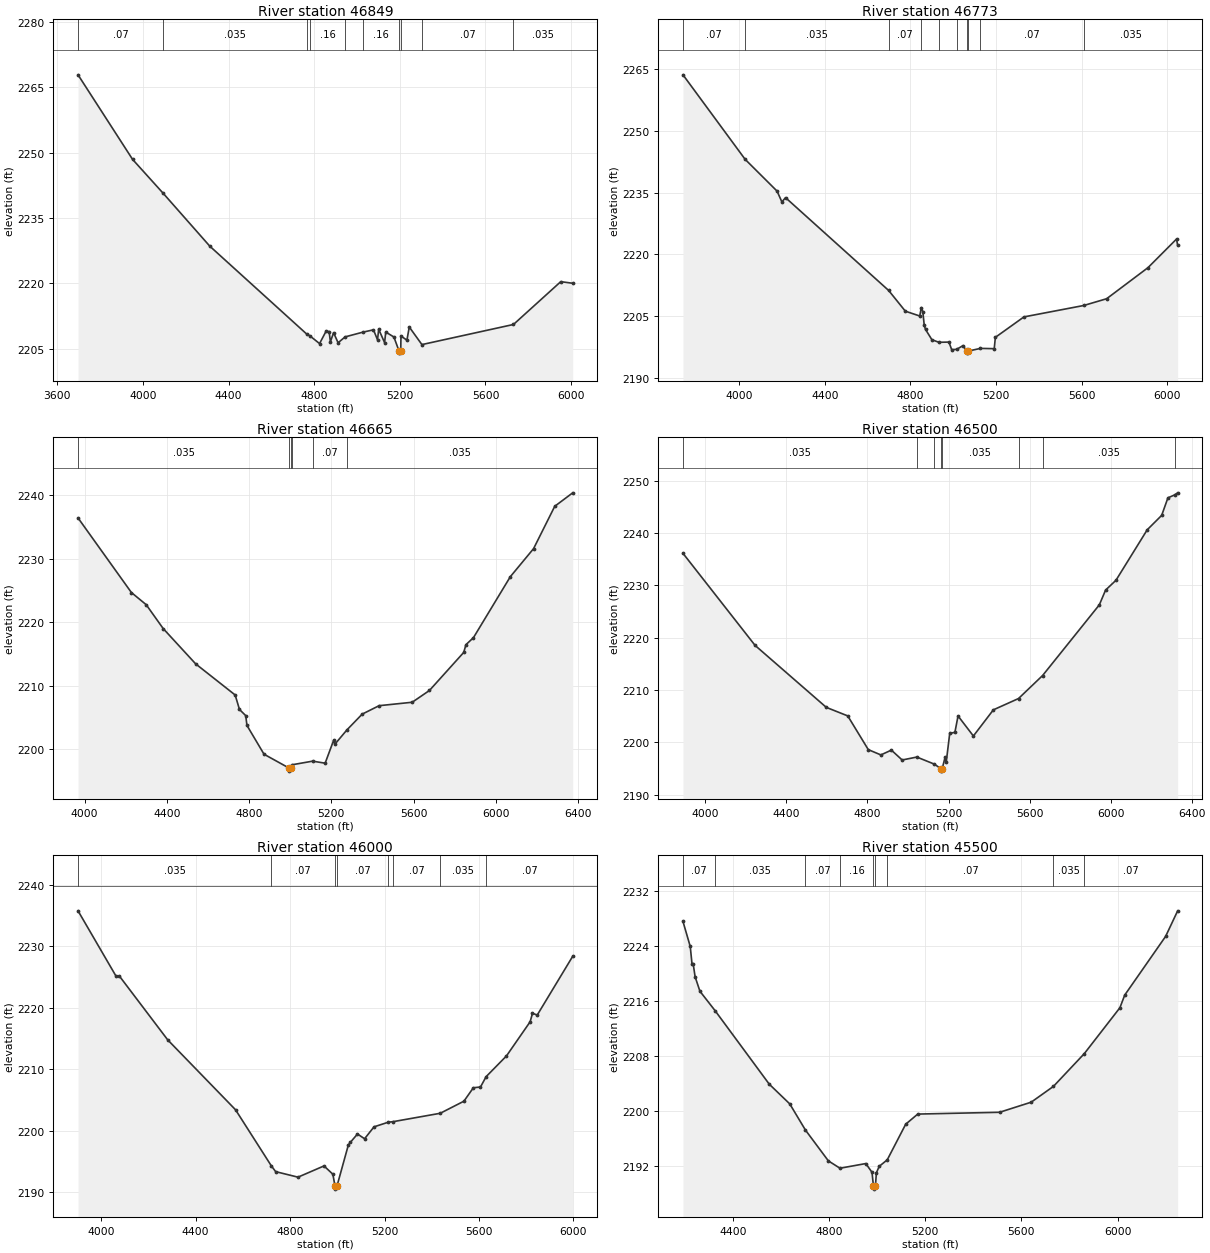
Type RM Length L Ch R = 1,46849,76,76,76
BEGIN DESCRIPTION:
Bull Creek 94.6
END DESCRIPTION:
XS GIS Cut Line= 5
      1320897.76      6917493.19      1321863.92      6917021.83
      1322051.42      6916891.62      1322124.33      6916649.44
      1322496.75      6915993.14
#Sta/Elev= 30
  3696.7 2267.84  3951.6 2248.42  4093.4 2240.70  4312.0 2228.51  4764.0 2208.36
  4779.4 2207.92  4825.0 2206.13  4854.7 2208.91  4869.6 2208.90  4875.7 2206.55
  4890.5 2208.64  4911.5 2206.32  4944.4 2207.67  5028.6 2208.77  5076.9 2209.29
  5095.8 2206.99  5101.1 2209.43  5128.8 2206.35  5134.1 2208.78  5172.3 2207.64
  5196.1 2204.44  5196.6 2203.94  5204.1 2204.44  5205.3 2207.87  5233.1 2206.91
  5244.0 2209.94  5303.1 2205.90  5730.8 2210.52  5951.7 2220.35  6007.5 2219.98
#Mann=10,-1,0
  3696.7    0.07       0  4093.4   0.035       0  4764.0    0.07       0
  4779.4    0.16       0  4944.4    0.07       0  5028.6    0.16       0
  5196.1    0.07       0  5204.1    0.16       0  5303.1    0.07       0
  5730.8   0.035       0
Bank Sta=5196.1,5204.1
Exp/Cntr=0.3,0.1

Type RM Length L Ch R = 1,46773,108,108,108
BEGIN DESCRIPTION:
Bull Creek 94.5
END DESCRIPTION:
XS GIS Cut Line= 5
      1320991.53      6917514.02      1321957.67      6917042.66
      1322145.17      6916912.46      1322218.08      6916670.27
      1322491.52      6915967.16
#Sta/Elev= 30
  3737.8 2263.59  4028.0 2243.09  4177.3 2235.37  4199.8 2232.74  4216.8 2233.79
  4698.6 2211.26  4776.4 2206.24  4843.6 2205.07  4851.2 2207.12  4858.2 2206.07
  4864.6 2202.85  4870.6 2201.81  4900.4 2199.32  4933.1 2198.69  4980.0 2198.74
  4992.9 2196.90  5016.2 2196.98  5046.0 2197.89  5062.6 2196.56  5063.1 2196.06
  5070.7 2196.56  5127.2 2197.21  5191.6 2197.14  5196.9 2199.89  5330.4 2204.85
  5609.8 2207.62  5716.7 2209.26  5909.8 2216.80  6043.2 2223.75  6048.4 2222.18
#Mann=10,-1,0
  3737.8    0.07       0  4028.0   0.035       0  4698.6    0.07       0
  4851.2    0.16       0  4933.1    0.07       0  5016.2    0.16       0
  5062.6    0.07       0  5070.7    0.16       0  5127.2    0.07       0
  5609.8   0.035       0
Bank Sta=5062.6,5070.7
Exp/Cntr=0.3,0.1

Type RM Length L Ch R = 1,46665,165,165,165
BEGIN DESCRIPTION:
Bull Creek 94.0
END DESCRIPTION:
XS GIS Cut Line= 3
      1321973.89      6917940.00      1322220.43      6916936.49
      1322543.34      6915603.18
#Sta/Elev= 30
  3968.4 2236.42  4227.9 2224.68  4300.0 2222.76  4382.4 2219.01  4540.4 2213.45
  4732.5 2208.55  4753.3 2206.28  4783.9 2205.30  4789.7 2203.76  4872.8 2199.23
  4993.5 2197.07  4994.0 2196.57  5001.6 2197.07  5009.1 2197.57  5109.1 2198.14
  5169.9 2197.82  5211.7 2201.46  5216.9 2200.79  5275.6 2203.05  5350.0 2205.54
  5432.3 2206.87  5593.3 2207.41  5676.9 2209.26  5843.9 2215.26  5854.5 2216.47
  5891.1 2217.58  6070.3 2227.17  6183.4 2231.59  6286.3 2238.25  6373.6 2240.37
#Mann=6,-1,0
  3968.4   0.035       0  4993.5   0.035       0  5001.6   0.035       0
  5009.1    0.16       0  5109.1    0.07       0  5275.6   0.035       0
Bank Sta=4993.5,5001.6
Exp/Cntr=0.3,0.1

Type RM Length L Ch R = 1,46500,500,500,500
BEGIN DESCRIPTION:
Bull Creek 93.0
END DESCRIPTION:
XS GIS Cut Line= 3
      1322078.06      6917960.83      1322368.53      6916888.79
      1322664.45      6915591.10
#Sta/Elev= 30
  3889.3 2236.13  4245.3 2218.52  4596.8 2206.67  4702.6 2205.04  4804.0 2198.59
  4866.1 2197.58  4917.9 2198.50  4971.1 2196.61  5043.7 2197.17  5130.5 2195.81
  5160.8 2194.98  5161.3 2194.48  5169.0 2194.98  5183.4 2197.19  5188.5 2196.15
  5205.9 2201.69  5231.5 2201.91  5247.0 2205.03  5322.7 2201.20  5421.3 2206.20
  5545.4 2208.36  5664.3 2212.76  5944.4 2226.28  5975.2 2229.10  6026.5 2230.98
  6180.7 2240.63  6252.1 2243.39  6282.9 2246.74  6315.8 2247.30  6331.0 2247.70
#Mann=8,-1,0
  3889.3   0.035       0  5043.7    0.07       0  5130.5   0.035       0
  5160.8   0.035       0  5169.0   0.035       0  5545.4    0.07       0
  5664.3   0.035       0  6315.8    0.07       0
Bank Sta=5160.8,5169
Exp/Cntr=0.3,0.1

Type RM Length L Ch R = 1,46000,500,500,500
BEGIN DESCRIPTION:
Bull Creek 92.0
END DESCRIPTION:
XS GIS Cut Line= 3
      1322204.99      6917988.01      1322747.53      6917033.07
      1322805.00      6916038.03
#Sta/Elev= 30
  3901.7 2235.80  4062.7 2225.15  4076.9 2225.17  4281.6 2214.77  4568.8 2203.38
  4719.9 2194.27  4738.7 2193.30  4833.3 2192.40  4943.4 2194.23  4980.9 2192.88
  4990.1 2190.95  4990.6 2190.45  4998.4 2190.95  5046.5 2197.64  5055.2 2198.08
  5085.2 2199.43  5115.3 2198.66  5155.3 2200.60  5216.1 2201.36  5235.6 2201.44
  5435.7 2202.81  5536.0 2204.78  5576.0 2206.97  5606.1 2207.09  5630.1 2208.78
  5716.3 2212.16  5816.4 2217.72  5826.4 2219.10  5846.5 2218.82  5996.7 2228.39
#Mann=8,-1,0
  3901.7   0.035       0  4719.9    0.07       0  4990.1    0.07       0
  4998.4    0.07       0  5216.1   0.035       0  5235.6    0.07       0
  5435.7   0.035       0  5630.1    0.07       0
Bank Sta=4990.1,4998.4
Exp/Cntr=0.3,0.1

Type RM Length L Ch R = 1,45500,500,500,500
BEGIN DESCRIPTION:
Bull Creek 91.0
END DESCRIPTION:
XS GIS Cut Line= 3
      1322905.00      6918087.99      1323005.99      6917286.83
      1322955.00      6916037.98
#Sta/Elev= 30
  4192.5 2227.52  4222.7 2223.88  4230.1 2221.33  4235.2 2221.30  4242.9 2219.48
  4263.0 2217.37  4325.7 2214.56  4551.3 2203.85  4636.6 2200.98  4701.7 2197.18
  4797.2 2192.69  4845.5 2191.62  4952.8 2192.30  4978.7 2191.03  4984.5 2189.08
  4985.0 2188.58  4993.0 2189.08  4996.9 2190.96  5008.8 2191.90  5042.0 2192.84
  5118.9 2198.03  5169.0 2199.50  5509.3 2199.76  5640.8 2201.23  5733.3 2203.53
  5861.5 2208.29  6009.7 2214.97  6029.7 2216.81  6199.8 2225.35  6249.9 2229.07
#Mann=9,-1,0
  4192.5    0.07       0  4325.7   0.035       0  4701.7    0.07       0
  4845.5    0.16       0  4984.5    0.07       0  4993.0    0.16       0
  5042.0    0.07       0  5733.3   0.035       0  5861.5    0.07       0
Bank Sta=4984.5,4993
Exp/Cntr=0.3,0.1