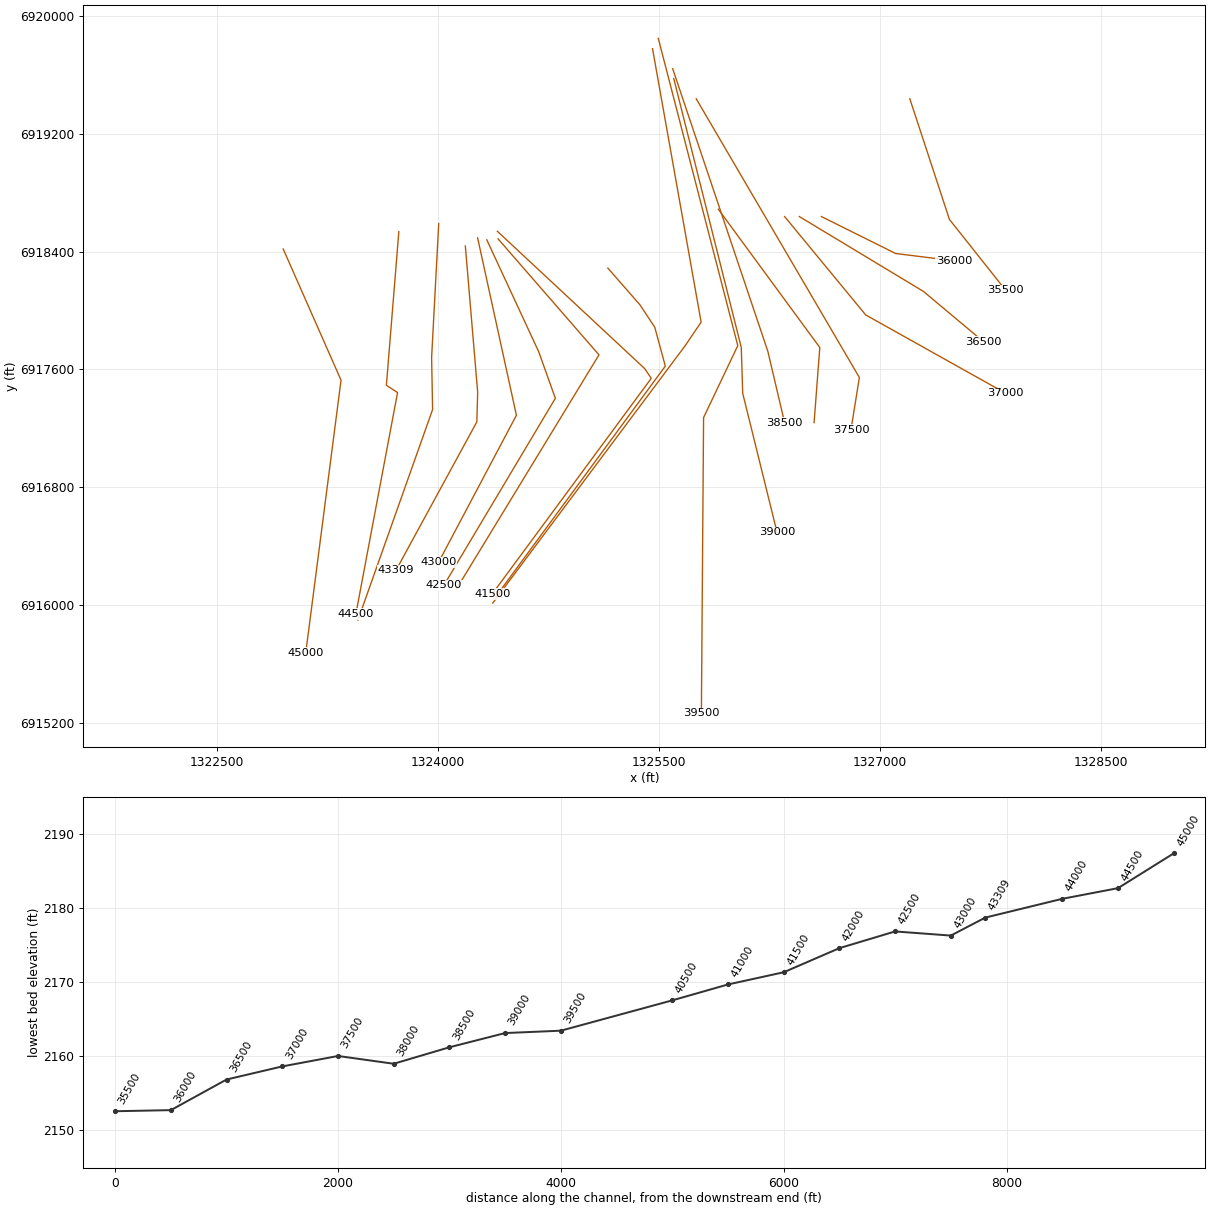
HEC-RAS study Bull Creek.prj: Bull Creek Base Level Engineering

--- Bull Creek.g01 (geometry) --- (continued)

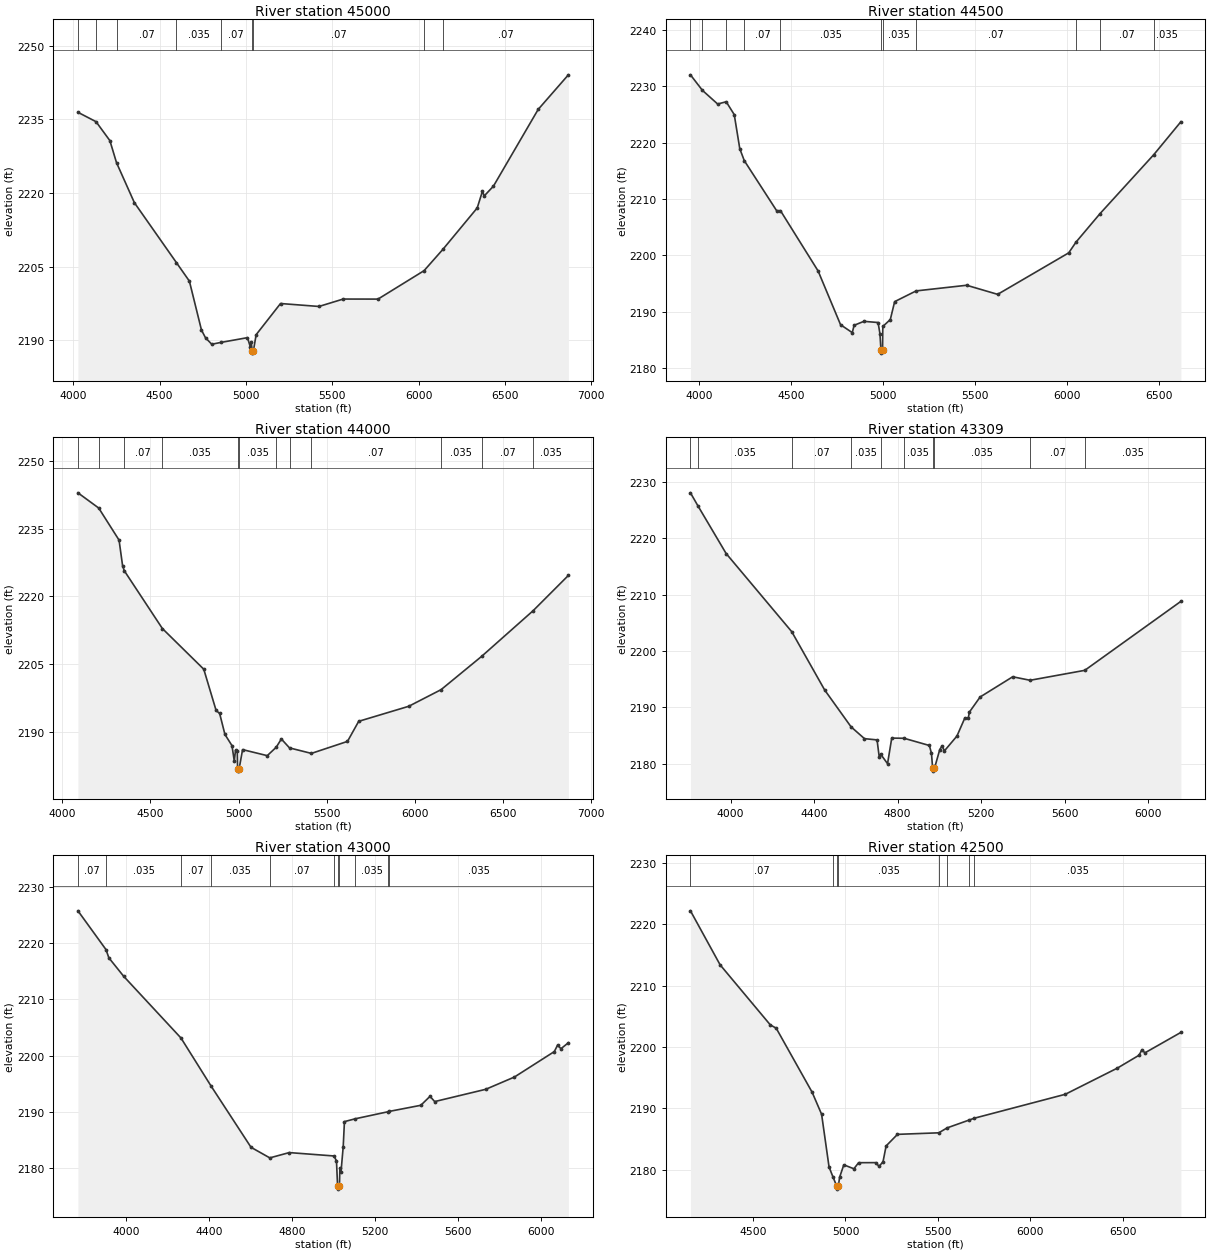
Type RM Length L Ch R = 1,45000,500,500,500
BEGIN DESCRIPTION:
Bull Creek 90.0
END DESCRIPTION:
XS GIS Cut Line= 3
      1322951.34      6918417.36      1323343.67      6917526.42
      1323104.11      6915674.35
#Sta/Elev= 30
  4026.5 2236.43  4131.4 2234.52  4211.6 2230.66  4249.9 2226.18  4353.6 2218.02
  4597.1 2205.82  4672.1 2202.06  4742.1 2192.10  4765.5 2190.52  4801.6 2189.21
  4853.3 2189.57  5008.5 2190.55  5026.1 2188.56  5031.2 2189.62  5034.5 2187.90
  5035.0 2187.40  5043.0 2187.90  5058.9 2191.16  5200.1 2197.50  5422.7 2196.90
  5563.1 2198.41  5764.7 2198.40  6031.6 2204.19  6140.2 2208.51  6339.5 2216.96
  6369.7 2220.35  6379.8 2219.39  6433.5 2221.40  6692.4 2237.01  6867.5 2244.06
#Mann=9,-1,0
  4026.5    0.07       0  4131.4   0.035       0  4249.9    0.07       0
  4597.1   0.035       0  4853.3    0.07       0  5034.5    0.07       0
  5043.0    0.07       0  6031.6   0.035       0  6140.2    0.07       0
Bank Sta=5034.5,5043
Exp/Cntr=0.3,0.1

Type RM Length L Ch R = 1,44500,500,500,500
BEGIN DESCRIPTION:
Bull Creek 89.0
END DESCRIPTION:
XS GIS Cut Line= 4
      1323736.05      6918535.48      1323651.51      6917491.70
      1323727.38      6917442.50      1323444.38      6915938.21
#Sta/Elev= 30
  3952.8 2231.99  4017.9 2229.24  4100.8 2226.82  4147.3 2227.22  4191.1 2224.94
  4221.2 2218.90  4245.7 2216.79  4421.8 2207.92  4442.6 2207.93  4647.3 2197.25
  4769.5 2187.73  4833.2 2186.33  4843.2 2187.63  4896.6 2188.33  4973.6 2188.12
  4983.6 2186.17  4989.4 2183.20  4989.9 2182.70  4997.9 2183.20  4999.3 2187.42
  5040.1 2188.65  5063.8 2191.82  5180.6 2193.72  5455.5 2194.72  5624.1 2193.11
  6010.8 2200.46  6050.9 2202.38  6181.5 2207.42  6473.6 2217.85  6621.1 2223.68
#Mann=11,-1,0
  3952.8   0.035       0  4017.9    0.07       0  4147.3   0.035       0
  4245.7    0.07       0  4442.6   0.035       0  4989.4   0.035       0
  4997.9   0.035       0  5180.6    0.07       0  6050.9   0.035       0
  6181.5    0.07       0  6473.6   0.035       0
Bank Sta=4989.4,4997.9
Exp/Cntr=0.3,0.1

Type RM Length L Ch R = 1,44000,691,691,691
BEGIN DESCRIPTION:
Bull Creek 88.0
END DESCRIPTION:
XS GIS Cut Line= 4
      1324006.88      6918590.96      1323958.60      6917681.04
      1323965.22      6917327.12      1323458.28      6915896.57
#Sta/Elev= 30
  4088.8 2242.95  4206.6 2239.58  4322.1 2232.47  4342.1 2226.82  4351.6 2225.69
  4567.9 2212.87  4802.8 2203.85  4872.9 2194.70  4892.9 2194.04  4922.9 2189.39
  4963.0 2186.91  4975.8 2183.51  4983.0 2185.90  4993.0 2185.72  4994.7 2181.76
  4995.2 2181.26  5003.4 2181.76  5023.0 2186.03  5163.1 2184.69  5213.8 2186.55
  5243.1 2188.38  5289.3 2186.41  5413.5 2185.19  5618.3 2187.85  5681.9 2192.30
  5965.7 2195.63  6149.4 2199.32  6379.2 2206.69  6672.2 2216.84  6871.7 2224.64
#Mann=12,-1,0
  4088.8    0.07       0  4206.6   0.035       0  4351.6    0.07       0
  4567.9   0.035       0  4994.7   0.035       0  5003.4   0.035       0
  5213.8    0.07       0  5289.3   0.035       0  5413.5    0.07       0
  6149.4   0.035       0  6379.2    0.07       0  6672.2   0.035       0
Bank Sta=4994.7,5003.4
Exp/Cntr=0.3,0.1

Type RM Length L Ch R = 1,43309,309,309,309
BEGIN DESCRIPTION:
Bull Creek 87.0
END DESCRIPTION:
XS GIS Cut Line= 4
      1324187.44      6918438.18      1324271.25      6917444.60
      1324265.63      6917243.40      1323716.12      6916233.85
#Sta/Elev= 30
  3808.1 2228.01  3843.9 2225.70  3978.9 2217.26  4292.9 2203.42  4450.6 2193.09
  4577.0 2186.56  4641.2 2184.47  4701.4 2184.25  4711.5 2181.31  4718.8 2181.71
  4751.6 2180.04  4771.7 2184.57  4830.5 2184.54  4951.9 2183.26  4961.9 2181.86
  4967.5 2179.22  4968.0 2178.72  4976.3 2179.22  5001.7 2182.55  5012.6 2183.18
  5024.0 2182.31  5083.8 2184.93  5121.8 2188.15  5137.9 2188.12  5143.7 2189.19
  5194.8 2191.85  5350.7 2195.43  5434.1 2194.81  5695.7 2196.57  6155.9 2208.79
#Mann=10,-1,0
  3808.1    0.07       0  3843.9   0.035       0  4292.9    0.07       0
  4577.0   0.035       0  4718.8    0.07       0  4830.5   0.035       0
  4967.5   0.035       0  4976.3   0.035       0  5434.1    0.07       0
  5695.7   0.035       0
Bank Sta=4967.5,4976.3
Exp/Cntr=0.3,0.1

Type RM Length L Ch R = 1,43000,500,500,500
BEGIN DESCRIPTION:
Bull Creek 86.0
END DESCRIPTION:
XS GIS Cut Line= 3
      1324270.78      6918493.76      1324534.14      6917288.19
      1324005.02      6916288.03
#Sta/Elev= 30
  3766.0 2225.72  3901.2 2218.84  3915.2 2217.37  3986.9 2214.08  4263.0 2203.13
  4406.9 2194.67  4600.8 2183.72  4691.4 2181.84  4785.2 2182.78  5000.8 2182.18
  5013.0 2181.31  5018.4 2176.79  5018.9 2176.29  5027.3 2176.79  5029.4 2180.09
  5035.0 2179.42  5045.5 2183.84  5051.4 2188.28  5103.0 2188.78  5263.5 2190.05
  5265.4 2190.08  5419.8 2191.18  5464.1 2192.77  5486.7 2191.84  5732.9 2194.02
  5871.3 2196.20  6063.7 2200.72  6079.4 2201.87  6095.7 2201.23  6131.5 2202.29
#Mann=11,-1,0
  3766.0    0.07       0  3901.2   0.035       0  4263.0    0.07       0
  4406.9   0.035       0  4691.4    0.07       0  5000.8   0.035       0
  5018.4    0.07       0  5027.3   0.035       0  5103.0   0.035       0
  5263.5    0.07       0  5265.4   0.035       0
Bank Sta=5018.4,5027.3
Exp/Cntr=0.3,0.1

Type RM Length L Ch R = 1,42500,500,500,500
BEGIN DESCRIPTION:
Bull Creek 85.0
END DESCRIPTION:
XS GIS Cut Line= 4
      1324333.27      6918479.90      1324685.80      6917719.33
      1324798.55      6917403.51      1324041.72      6916132.87
#Sta/Elev= 30
  4161.7 2222.22  4322.0 2213.42  4593.7 2203.62  4625.4 2203.09  4819.7 2192.65
  4871.0 2189.06  4911.3 2180.46  4931.7 2178.90  4952.7 2177.35  4953.2 2176.85
  4961.6 2177.35  4968.4 2178.78  4991.1 2180.81  5045.7 2180.17  5071.2 2181.16
  5163.6 2181.17  5181.9 2180.56  5203.2 2181.31  5219.9 2183.89  5281.5 2185.78
  5504.7 2186.03  5550.3 2186.84  5670.7 2188.13  5695.7 2188.40  6189.0 2192.31
  6471.3 2196.59  6588.1 2198.68  6603.7 2199.59  6619.3 2199.06  6814.3 2202.40
#Mann=8,-1,0
  4161.7    0.07       0  4931.7   0.035       0  4952.7   0.035       0
  4961.6   0.035       0  5504.7    0.07       0  5550.3   0.035       0
  5670.7    0.07       0  5695.7   0.035       0
Bank Sta=4952.7,4961.6
Exp/Cntr=0.3,0.1

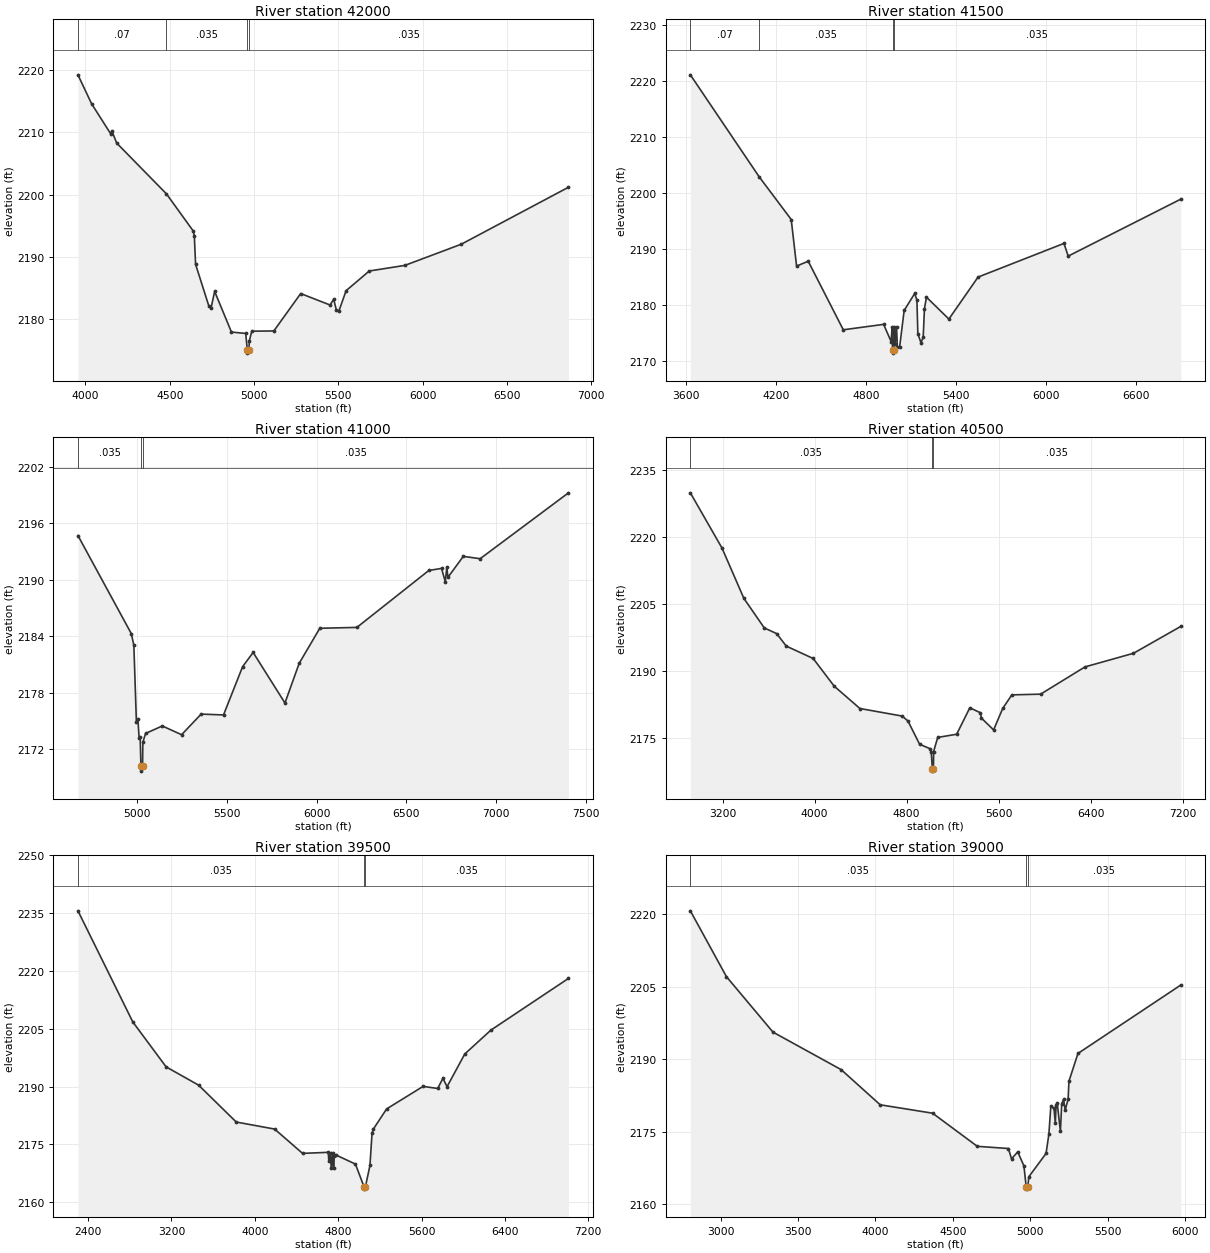
Type RM Length L Ch R = 1,42000,500,500,500
BEGIN DESCRIPTION:
Bull Creek 84.0
END DESCRIPTION:
XS GIS Cut Line= 3
      1324409.66      6918486.85      1325094.70      6917698.64
      1324124.94      6916104.89
#Sta/Elev= 30
  3955.7 2219.25  4036.4 2214.62  4150.3 2209.77  4157.0 2210.24  4185.5 2208.30
  4480.7 2200.15  4639.4 2194.20  4646.0 2193.44  4653.6 2188.84  4731.5 2182.21
  4745.7 2181.87  4766.6 2184.49  4866.3 2177.97  4950.8 2177.75  4960.6 2175.09
  4961.1 2174.59  4969.5 2175.09  4972.7 2176.59  4986.9 2178.11  5117.8 2178.15
  5277.1 2184.15  5451.5 2182.31  5472.8 2183.24  5488.3 2181.54  5503.7 2181.35
  5546.4 2184.61  5684.0 2187.77  5895.1 2188.67  6229.9 2192.07  6865.6 2201.21
#Mann=4,-1,0
  3955.7    0.07       0  4480.7   0.035       0  4960.6   0.035       0
  4969.5   0.035       0
Bank Sta=4960.6,4969.5
Exp/Cntr=0.3,0.1

Type RM Length L Ch R = 1,41500,500,500,500
BEGIN DESCRIPTION:
Bull Creek 83.0
END DESCRIPTION:
XS GIS Cut Line= 4
      1324405.00      6918538.00      1325405.44      6917604.82
      1325449.59      6917539.07      1324369.54      6916073.69
#Sta/Elev= 30
  3631.9 2221.07  4089.4 2202.88  4303.9 2195.21  4339.5 2186.89  4417.2 2187.75
  4650.7 2175.50  4919.4 2176.47  4969.3 2173.40  4976.1 2175.98  4979.0 2171.83
  4979.5 2171.33  4987.9 2171.83  4990.3 2176.03  4996.3 2172.96  5005.2 2176.06
  5011.2 2172.40  5026.2 2172.47  5056.2 2178.96  5126.5 2181.99  5141.2 2180.80
  5147.4 2174.78  5168.2 2173.20  5182.9 2174.17  5191.3 2179.25  5204.8 2181.33
  5354.1 2177.42  5548.4 2184.92  6120.7 2190.94  6148.9 2188.67  6899.6 2198.86
#Mann=4,-1,0
  3631.9    0.07       0  4089.4   0.035       0  4979.0   0.035       0
  4987.9   0.035       0
Bank Sta=4979,4987.9
Exp/Cntr=0.3,0.1

Type RM Length L Ch R = 1,41000,500,500,500
BEGIN DESCRIPTION:
Bull Creek 82.0
END DESCRIPTION:
XS GIS Cut Line= 5
      1325155.03      6918287.97      1325372.96      6918038.30
      1325473.27      6917886.86      1325545.08      6917622.26
      1324391.26      6916052.02
#Sta/Elev= 30
  4668.6 2194.71  4966.2 2184.29  4980.4 2183.06  4994.6 2174.92  5003.2 2175.18
  5009.6 2173.22  5015.6 2173.30  5019.9 2170.18  5020.4 2169.68  5028.9 2170.18
  5030.6 2172.75  5045.7 2173.68  5138.9 2174.48  5246.7 2173.55  5355.8 2175.74
  5480.5 2175.65  5587.0 2180.78  5645.6 2182.29  5823.1 2176.92  5902.6 2181.14
  6017.5 2184.86  6224.3 2184.95  6625.5 2191.00  6696.5 2191.22  6717.4 2189.80
  6725.8 2191.39  6732.0 2190.27  6817.7 2192.50  6911.8 2192.25  7404.4 2199.25
#Mann=3,-1,0
  4668.6   0.035       0  5019.9   0.035       0  5028.9   0.035       0
Bank Sta=5019.9,5028.9
Exp/Cntr=0.3,0.1

Type RM Length L Ch R = 1,40500,1000,1000,1000
BEGIN DESCRIPTION:
Bull Creek 81.0
END DESCRIPTION:
XS GIS Cut Line= 4
      1325458.27      6919778.66      1325788.14      6917921.01
      1325680.19      6917761.39      1324373.56      6916012.49
#Sta/Elev= 30
  2920.6 2229.79  3195.5 2217.44  3385.7 2206.18  3562.9 2199.57  3670.9 2198.29
  3754.1 2195.50  3987.7 2192.73  4170.5 2186.54  4394.0 2181.54  4762.7 2179.84
  4812.1 2178.71  4912.3 2173.56  5005.4 2172.52  5013.8 2171.79  5023.8 2168.03
  5024.3 2167.53  5032.9 2168.03  5034.6 2171.92  5070.0 2175.07  5234.7 2175.78
  5349.3 2181.71  5441.1 2180.58  5449.4 2179.41  5555.7 2176.75  5634.9 2181.56
  5714.1 2184.59  5964.3 2184.75  6349.9 2190.85  6770.9 2193.89  7183.1 2199.92
#Mann=3,-1,0
  2920.6   0.035       0  5023.8   0.035       0  5032.9   0.035       0
Bank Sta=5023.8,5032.9
Exp/Cntr=0.3,0.1

Type RM Length L Ch R = 1,39500,500,500,500
BEGIN DESCRIPTION:
Bull Creek 79.0
END DESCRIPTION:
XS GIS Cut Line= 4
      1325497.33      6919848.97      1326037.02      6917761.29
      1325804.81      6917272.57      1325789.87      6915263.02
#Sta/Elev= 30
  2302.6 2235.58  2828.9 2206.78  3148.8 2195.12  3460.4 2190.39  3821.9 2180.82
  4189.9 2179.00  4458.0 2172.70  4704.4 2172.97  4710.0 2170.79  4727.2 2172.86
  4732.7 2168.78  4749.9 2172.82  4755.4 2168.89  4761.5 2172.05  4778.1 2172.28
  4965.5 2169.92  5049.2 2163.93  5049.7 2163.43  5060.0 2163.93  5104.6 2169.56
  5124.6 2177.87  5134.6 2178.89  5264.6 2184.22  5614.6 2190.07  5754.6 2189.52
  5804.6 2192.15  5844.6 2190.00  6014.6 2198.47  6264.6 2204.64  7009.6 2218.06
#Mann=3,-1,0
  2302.6   0.035       0  5049.2   0.035       0  5060.0   0.035       0
Bank Sta=5049.2,5060
Exp/Cntr=0.3,0.1

Type RM Length L Ch R = 1,39000,500,500,500
BEGIN DESCRIPTION:
Bull Creek 78.0
END DESCRIPTION:
XS GIS Cut Line= 4
      1325602.37      6919575.52      1326060.70      6917749.14
      1326070.39      6917437.51      1326303.67      6916492.58
#Sta/Elev= 30
  2805.2 2220.73  3038.3 2207.10  3338.8 2195.62  3779.2 2187.85  4031.3 2180.57
  4369.8 2178.83  4658.5 2171.97  4859.4 2171.52  4879.4 2169.38  4919.5 2170.82
  4959.5 2167.93  4974.1 2163.61  4974.6 2163.11  4984.9 2163.61  4991.0 2165.66
  5102.5 2170.50  5120.7 2174.47  5133.4 2180.32  5154.0 2179.81  5162.2 2176.75
  5167.4 2180.55  5174.6 2180.93  5195.2 2175.08  5203.7 2180.82  5215.8 2181.69
  5226.1 2179.45  5245.1 2181.77  5250.3 2185.45  5308.5 2191.20  5973.3 2205.38
#Mann=3,-1,0
  2805.2   0.035       0  4974.1   0.035       0  4984.9   0.035       0
Bank Sta=4974.1,4984.9
Exp/Cntr=0.3,0.1

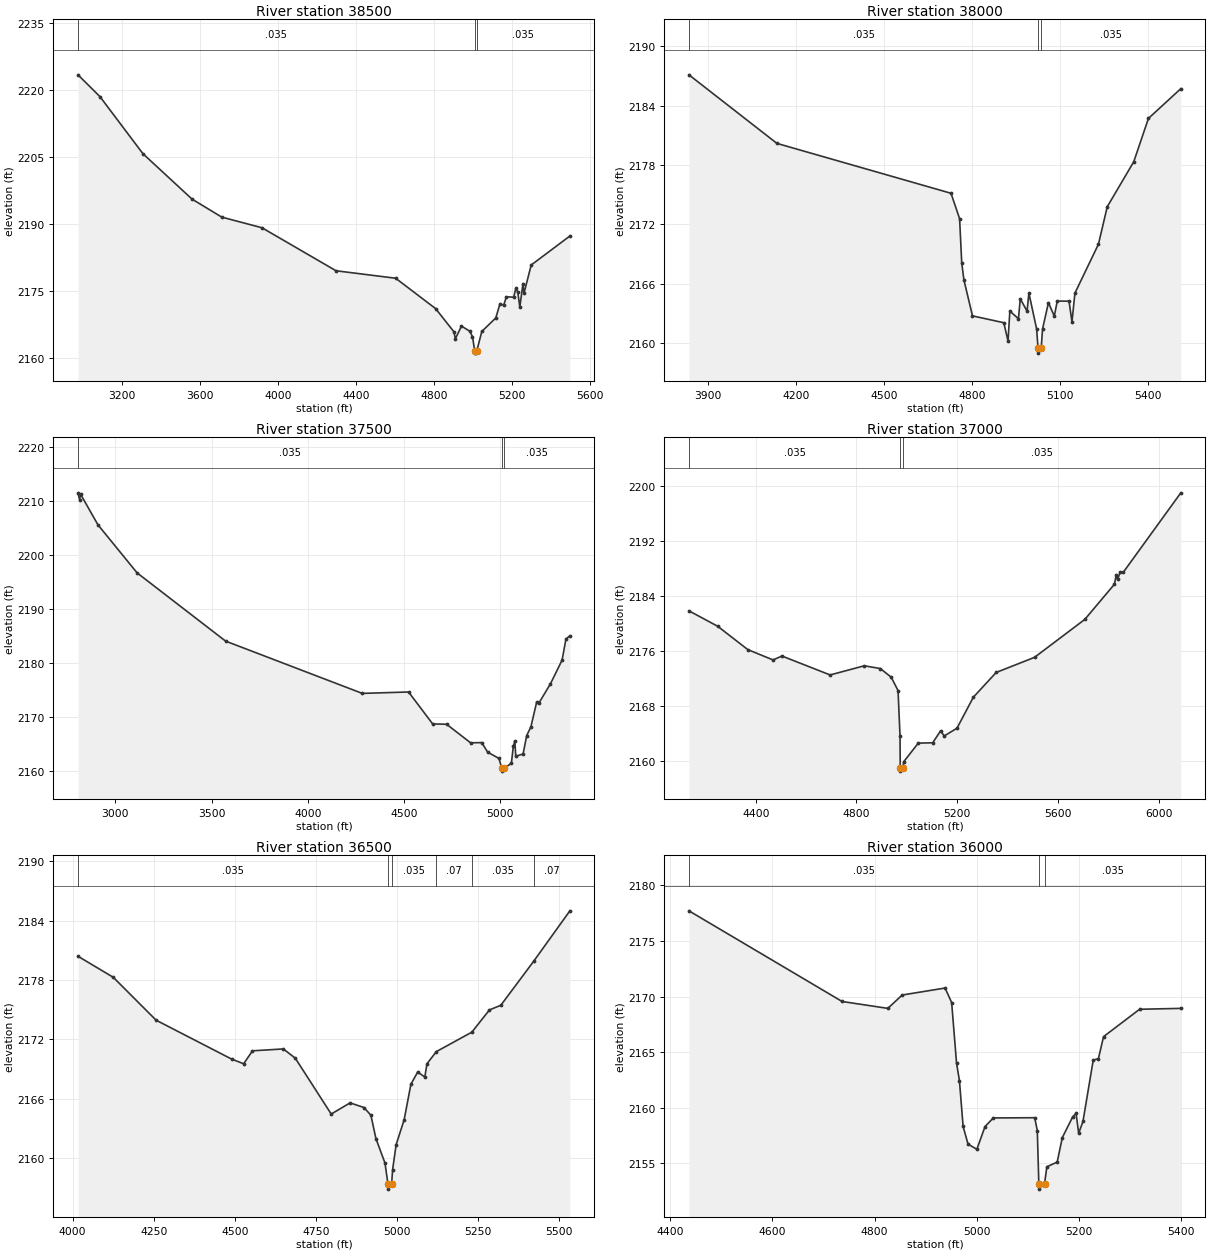
Type RM Length L Ch R = 1,38500,500,500,500
BEGIN DESCRIPTION:
Bull Creek 77.0
END DESCRIPTION:
XS GIS Cut Line= 3
      1325595.00      6919642.79      1326240.84      6917723.23
      1326355.01      6917237.98
#Sta/Elev= 30
  2974.7 2223.33  3087.5 2218.45  3308.0 2205.71  3560.1 2195.57  3712.3 2191.56
  3918.8 2189.18  4298.6 2179.58  4604.6 2177.91  4809.8 2171.12  4904.3 2165.91
  4910.6 2164.37  4942.2 2167.22  4984.4 2166.10  4998.7 2164.89  5010.2 2161.69
  5010.7 2161.19  5021.0 2161.69  5046.5 2166.03  5118.4 2169.05  5138.9 2172.08
  5159.5 2171.98  5172.9 2173.77  5210.2 2173.68  5221.1 2175.65  5231.4 2174.78
  5241.6 2171.46  5257.7 2176.71  5262.8 2174.53  5300.1 2180.87  5498.5 2187.34
#Mann=3,-1,0
  2974.7   0.035       0  5010.2   0.035       0  5021.0   0.035       0
Bank Sta=5010.2,5021
Exp/Cntr=0.3,0.1

Type RM Length L Ch R = 1,38000,500,500,500
BEGIN DESCRIPTION:
Bull Creek 76.0
END DESCRIPTION:
XS GIS Cut Line= 3
      1325904.98      6918688.03      1326593.74      6917748.69
      1326555.00      6917237.95
#Sta/Elev= 30
  3835.2 2187.13  4135.1 2180.19  4728.7 2175.14  4758.0 2172.56  4765.2 2168.10
  4772.6 2166.38  4801.9 2162.73  4908.5 2162.04  4923.1 2160.19  4929.3 2163.22
  4958.6 2162.44  4964.8 2164.46  4988.0 2163.21  4994.2 2165.04  5020.7 2161.39
  5025.3 2159.46  5025.8 2158.96  5036.2 2159.46  5040.8 2161.41  5060.9 2164.07
  5080.9 2162.70  5090.9 2164.23  5131.1 2164.22  5141.1 2162.12  5151.1 2165.03
  5231.3 2169.98  5261.4 2173.78  5351.7 2178.33  5401.8 2182.72  5512.2 2185.73
#Mann=3,-1,0
  3835.2   0.035       0  5025.3   0.035       0  5036.2   0.035       0
Bank Sta=5025.3,5036.2
Exp/Cntr=0.3,0.1

Type RM Length L Ch R = 1,37500,500,500,500
BEGIN DESCRIPTION:
Bull Creek 75.0
END DESCRIPTION:
XS GIS Cut Line= 3
      1325754.98      6919438.04      1326862.36      6917544.71
      1326805.00      6917187.99
#Sta/Elev= 30
  2806.6 2211.53  2814.5 2210.28  2820.3 2211.25  2910.3 2205.60  3113.6 2196.71
  3573.1 2184.08  4283.0 2174.40  4523.5 2174.66  4648.6 2168.75  4721.0 2168.69
  4845.6 2165.25  4903.5 2165.29  4934.2 2163.53  4992.9 2162.36  5007.9 2160.51
  5008.4 2160.01  5018.8 2160.51  5057.4 2161.46  5067.6 2164.59  5075.2 2165.58
  5080.3 2162.77  5118.2 2163.18  5137.1 2166.60  5158.7 2168.19  5189.1 2172.84
  5199.0 2172.53  5260.0 2176.15  5320.8 2180.56  5341.0 2184.49  5361.3 2185.05
#Mann=3,-1,0
  2806.6   0.035       0  5007.9   0.035       0  5018.8   0.035       0
Bank Sta=5007.9,5018.8
Exp/Cntr=0.3,0.1

Type RM Length L Ch R = 1,37000,500,500,500
BEGIN DESCRIPTION:
Bull Creek 74.0
END DESCRIPTION:
XS GIS Cut Line= 3
      1326355.01      6918637.99      1326905.40      6917969.91
      1327854.98      6917438.01
#Sta/Elev= 30
  4134.4 2181.90  4248.4 2179.66  4368.3 2176.26  4468.6 2174.76  4503.8 2175.33
  4695.3 2172.58  4830.9 2173.91  4894.7 2173.51  4937.7 2172.26  4965.1 2170.31
  4972.9 2163.71  4973.8 2159.10  4974.3 2158.60  4985.0 2159.10  4987.3 2159.95
  5045.4 2162.67  5102.7 2162.72  5134.1 2164.45  5148.5 2163.71  5199.2 2164.84
  5264.3 2169.35  5354.9 2172.94  5507.4 2175.14  5707.2 2180.66  5824.8 2185.77
  5831.6 2187.09  5837.3 2186.47  5847.5 2187.55  5859.2 2187.47  6088.4 2199.05
#Mann=3,-1,0
  4134.4   0.035       0  4973.8   0.035       0  4985.0   0.035       0
Bank Sta=4973.8,4985
Exp/Cntr=0.3,0.1

Type RM Length L Ch R = 1,36500,500,500,500
BEGIN DESCRIPTION:
Bull Creek 73.0
END DESCRIPTION:
XS GIS Cut Line= 3
      1326454.97      6918638.02      1327296.93      6918129.91
      1327705.02      6917787.98
#Sta/Elev= 30
  4016.6 2180.40  4125.3 2178.27  4257.3 2173.93  4490.2 2169.99  4527.1 2169.52
  4554.3 2170.83  4649.4 2171.02  4686.3 2170.08  4796.9 2164.43  4855.1 2165.56
  4897.9 2165.09  4919.2 2164.31  4934.7 2161.95  4962.7 2159.46  4971.8 2157.33
  4972.3 2156.83  4983.0 2157.33  4986.1 2158.81  4997.0 2161.33  5021.7 2163.86
  5042.5 2167.45  5063.4 2168.68  5085.4 2168.18  5092.0 2169.52  5120.9 2170.75
  5230.3 2172.72  5284.5 2174.97  5319.6 2175.44  5420.7 2179.89  5532.4 2185.00
#Mann=6,-1,0
  4016.6   0.035       0  4971.8   0.035       0  4983.0   0.035       0
  5120.9    0.07       0  5230.3   0.035       0  5420.7    0.07       0
Bank Sta=4971.8,4983
Exp/Cntr=0.3,0.1

Type RM Length L Ch R = 1,36000,500,500,500
BEGIN DESCRIPTION:
Bull Creek 72.0
END DESCRIPTION:
XS GIS Cut Line= 3
      1326605.01      6918637.99      1327109.13      6918387.09
      1327504.99      6918338.00
#Sta/Elev= 30
  4436.9 2177.71  4736.4 2169.56  4825.9 2168.94  4853.9 2170.14  4937.9 2170.77
  4950.7 2169.46  4960.3 2164.00  4965.9 2162.45  4973.1 2158.33  4982.7 2156.74
  5000.0 2156.27  5016.0 2158.32  5032.2 2159.09  5113.1 2159.11  5118.2 2157.96
  5121.2 2153.19  5121.7 2152.69  5132.4 2153.19  5136.9 2154.70  5157.1 2155.12
  5167.1 2157.32  5187.3 2159.18  5194.1 2159.50  5199.1 2157.71  5207.5 2158.77
  5227.6 2164.29  5237.7 2164.42  5247.8 2166.40  5318.3 2168.86  5398.9 2168.94
#Mann=3,-1,0
  4436.9   0.035       0  5121.2   0.035       0  5132.4   0.035       0
Bank Sta=5121.2,5132.4
Exp/Cntr=0.3,0.1

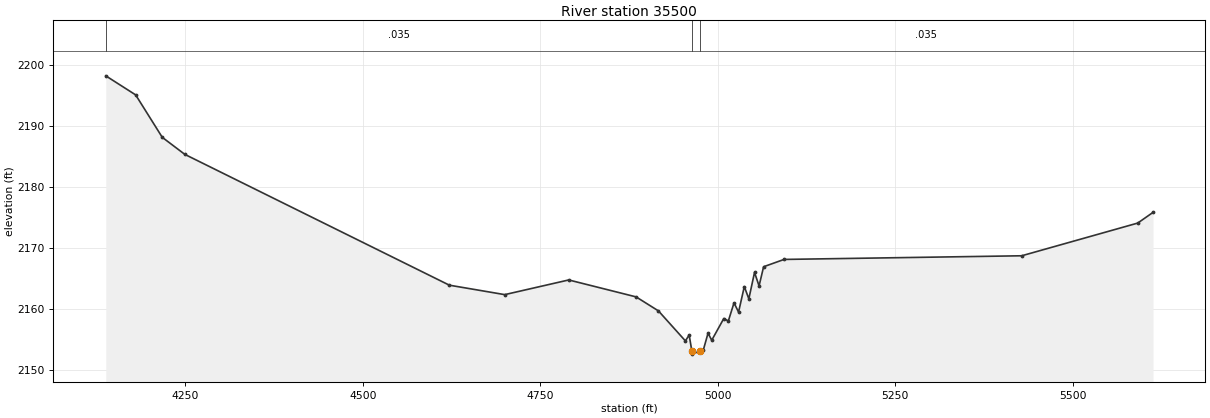
Type RM Length L Ch R = 1,35500,500,500,500
BEGIN DESCRIPTION:
Bull Creek 71.0
END DESCRIPTION:
XS GIS Cut Line= 3
      1327204.99      6919438.03      1327473.81      6918618.70
      1327855.00      6918138.00
#Sta/Elev= 30
  4137.7 2198.24  4179.8 2195.11  4217.3 2188.14  4249.1 2185.34  4621.9 2163.86
  4699.9 2162.31  4790.1 2164.72  4885.0 2161.94  4916.5 2159.64  4954.5 2154.71
  4959.8 2155.68  4963.6 2153.04  4964.1 2152.54  4974.8 2153.04  4979.7 2153.20
  4986.4 2155.98  4991.6 2154.82  5008.6 2158.39  5015.0 2157.98  5023.0 2160.96
  5029.4 2159.44  5037.5 2163.63  5043.9 2161.62  5051.9 2165.96  5058.3 2163.74
  5064.7 2166.89  5093.5 2168.09  5428.4 2168.69  5591.9 2174.06  5613.5 2175.82
#Mann=3,-1,0
  4137.7   0.035       0  4963.6   0.035       0  4974.8   0.035       0
Bank Sta=4963.6,4974.8
Exp/Cntr=0.3,0.1