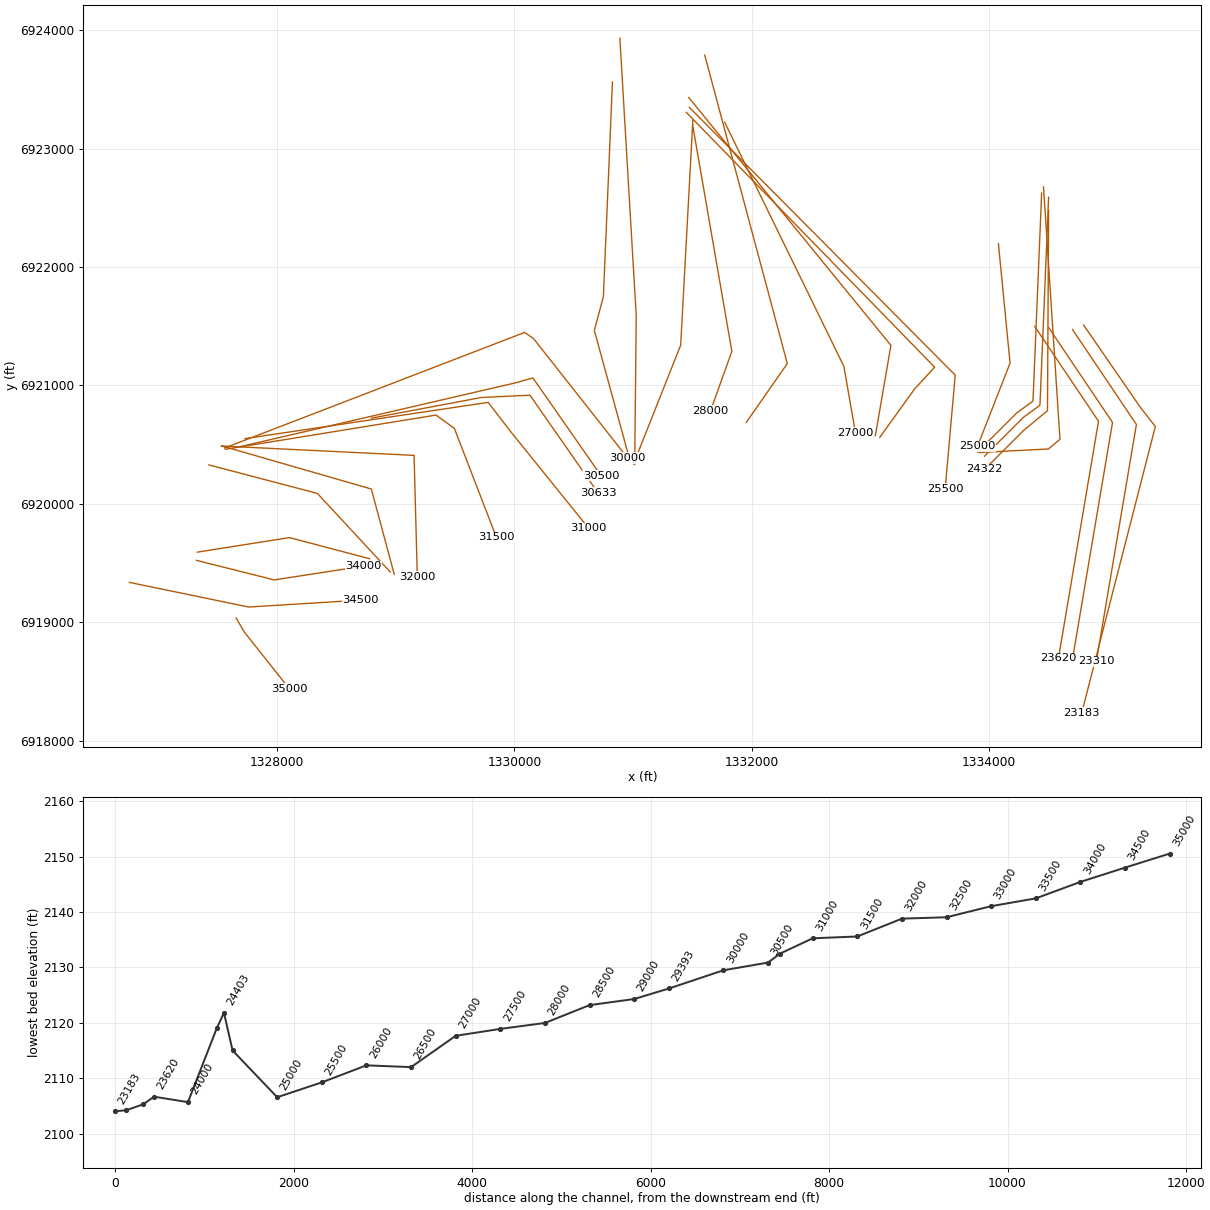
HEC-RAS study Bull Creek.prj: Bull Creek Base Level Engineering

--- Bull Creek.g01 (geometry) --- (continued)

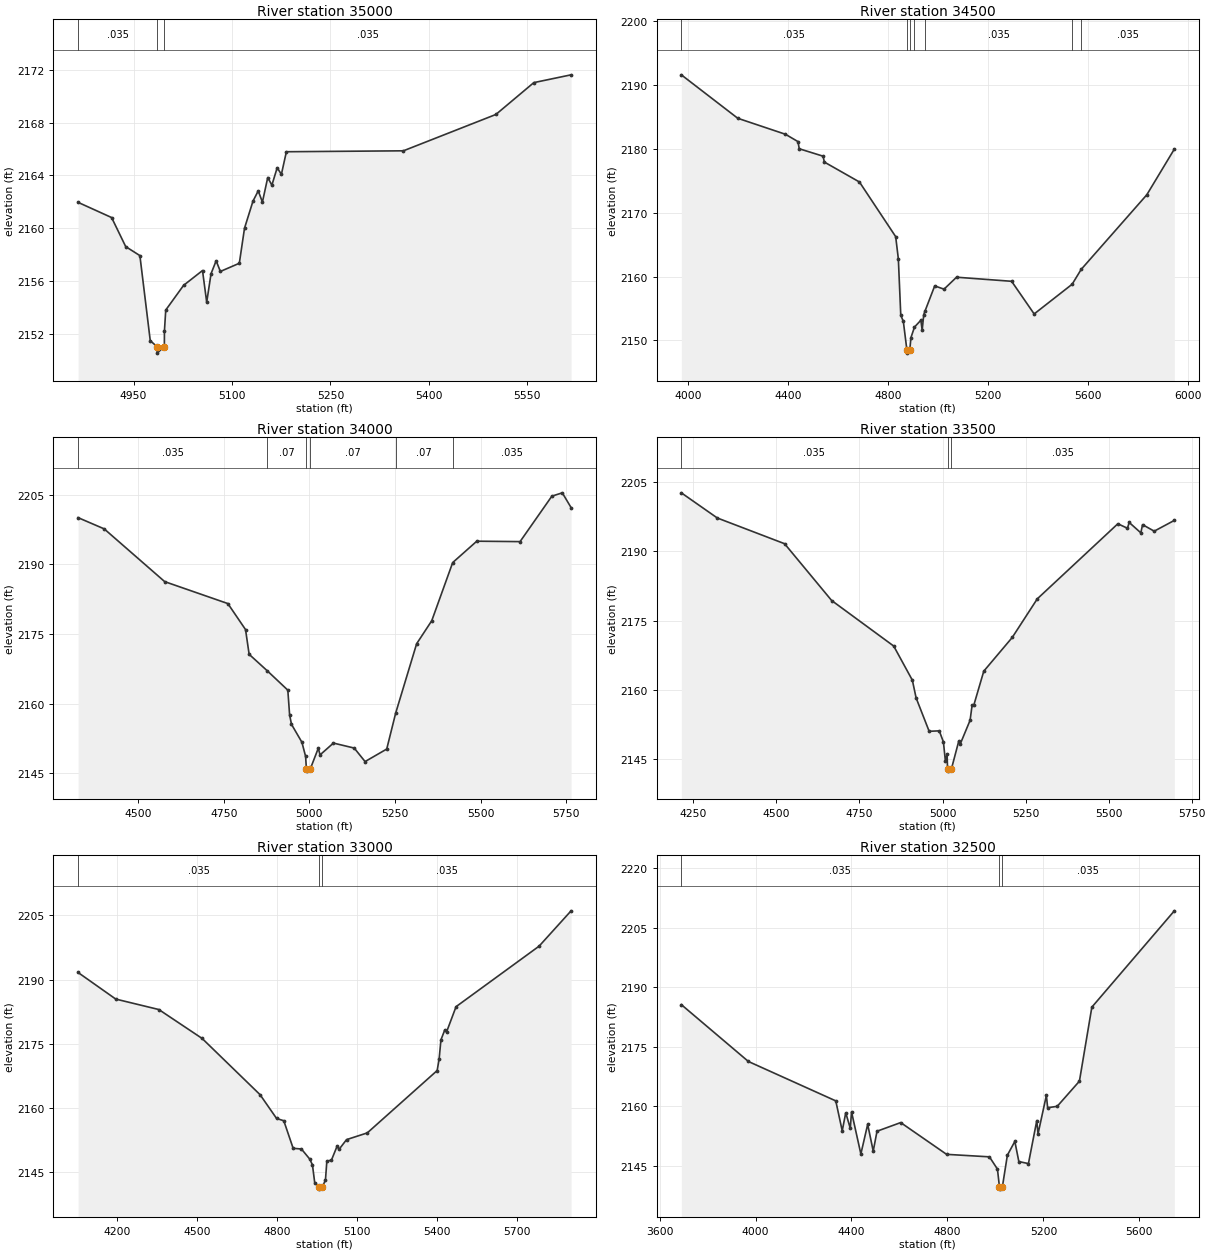
Type RM Length L Ch R = 1,35000,500,500,500
BEGIN DESCRIPTION:
Bull Creek 70.0
END DESCRIPTION:
XS GIS Cut Line= 3
      1327654.99      6919038.02      1327722.00      6918921.29
      1328104.97      6918438.04
#Sta/Elev= 30
  4865.4 2161.96  4916.5 2160.81  4938.0 2158.61  4959.6 2157.93  4975.4 2151.49
  4985.5 2151.05  4986.0 2150.55  4996.9 2151.05  4997.0 2152.23  4999.0 2153.81
  5026.2 2155.68  5055.0 2156.80  5061.4 2154.40  5068.0 2156.56  5075.8 2157.54
  5082.2 2156.73  5111.1 2157.35  5119.0 2160.00  5131.9 2162.05  5139.9 2162.83
  5146.3 2161.98  5154.4 2163.84  5160.7 2163.26  5168.8 2164.58  5175.2 2164.08
  5182.8 2165.79  5361.1 2165.86  5502.0 2168.61  5559.8 2171.02  5616.6 2171.61
#Mann=3,-1,0
  4865.4   0.035       0  4985.5   0.035       0  4996.9   0.035       0
Bank Sta=4985.5,4996.9
Exp/Cntr=0.3,0.1

Type RM Length L Ch R = 1,34500,500,500,500
BEGIN DESCRIPTION:
Bull Creek 69.0
END DESCRIPTION:
XS GIS Cut Line= 3
      1326755.03      6919337.99      1327760.83      6919129.95
      1328704.95      6919188.00
#Sta/Elev= 30
  3972.9 2191.57  4198.8 2184.77  4389.5 2182.27  4439.7 2181.12  4444.8 2180.00
  4540.1 2178.84  4545.2 2177.92  4685.7 2174.80  4830.7 2166.25  4841.4 2162.77
  4851.1 2153.94  4861.3 2153.00  4875.6 2148.52  4876.1 2148.02  4887.1 2148.52
  4891.9 2150.46  4906.0 2152.10  4931.6 2153.17  4936.7 2151.59  4943.0 2154.04
  4947.9 2154.58  4986.9 2158.54  5024.2 2158.03  5074.3 2159.90  5294.7 2159.26
  5384.9 2154.15  5536.9 2158.80  5573.0 2161.12  5835.7 2172.80  5945.9 2179.95
#Mann=7,-1,0
  3972.9   0.035       0  4875.6   0.035       0  4887.1   0.035       0
  4906.0    0.07       0  4947.9   0.035       0  5536.9    0.07       0
  5573.0   0.035       0
Bank Sta=4875.6,4887.1
Exp/Cntr=0.3,0.1

Type RM Length L Ch R = 1,34000,500,500,500
BEGIN DESCRIPTION:
Bull Creek 68.0
END DESCRIPTION:
XS GIS Cut Line= 3
      1327321.12      6919523.88      1327975.63      6919358.81
      1328730.41      6919475.20
#Sta/Elev= 30
  4325.0 2200.10  4401.2 2197.68  4577.8 2186.30  4762.1 2181.57  4813.7 2175.96
  4824.2 2170.63  4876.6 2167.11  4937.1 2162.90  4942.3 2157.57  4947.8 2155.53
  4978.2 2151.67  4989.0 2148.60  4991.3 2145.94  4991.8 2145.44  5002.8 2145.94
  5026.1 2150.39  5031.1 2148.94  5070.2 2151.49  5130.9 2150.41  5162.5 2147.50
  5225.7 2150.20  5252.0 2158.00  5313.0 2172.91  5357.1 2177.87  5418.2 2190.41
  5488.5 2195.02  5614.8 2194.93  5707.6 2204.73  5738.0 2205.45  5763.7 2202.27
#Mann=6,-1,0
  4325.0   0.035       0  4876.6    0.07       0  4991.3   0.035       0
  5002.8    0.07       0  5252.0    0.07       0  5418.2   0.035       0
Bank Sta=4991.3,5002.8
Exp/Cntr=0.3,0.1

Type RM Length L Ch R = 1,33500,500,500,500
BEGIN DESCRIPTION:
Bull Creek 67.0
END DESCRIPTION:
XS GIS Cut Line= 3
      1327328.05      6919593.32      1328104.72      6919715.99
      1328779.48      6919537.76
#Sta/Elev= 30
  4213.7 2202.64  4322.0 2197.20  4524.5 2191.64  4666.2 2179.36  4853.1 2169.51
  4909.2 2162.13  4920.5 2158.30  4959.8 2151.08  4990.2 2151.18  5002.7 2148.78
  5008.6 2144.65  5013.8 2146.17  5015.1 2142.97  5015.6 2142.47  5026.9 2142.97
  5048.9 2148.96  5054.0 2148.44  5083.0 2153.46  5089.1 2156.74  5094.3 2156.76
  5124.2 2164.08  5209.9 2171.37  5285.3 2179.72  5527.8 2195.95  5556.8 2194.98
  5561.9 2196.24  5597.0 2193.99  5602.2 2195.76  5637.3 2194.35  5697.9 2196.68
#Mann=3,-1,0
  4213.7   0.035       0  5015.1   0.035       0  5026.9   0.035       0
Bank Sta=5015.1,5026.9
Exp/Cntr=0.3,0.1

Type RM Length L Ch R = 1,33000,500,500,500
BEGIN DESCRIPTION:
Bull Creek 66.0
END DESCRIPTION:
XS GIS Cut Line= 3
      1327425.26      6920329.44      1328339.67      6920088.97
      1328953.05      6919426.68
#Sta/Elev= 30
  4054.5 2191.65  4195.8 2185.44  4357.2 2183.00  4519.5 2176.25  4736.7 2163.12
  4798.7 2157.56  4825.7 2157.03  4860.8 2150.59  4891.8 2150.43  4922.8 2148.09
  4933.1 2146.73  4941.6 2142.58  4958.2 2141.56  4958.7 2141.06  4970.1 2141.56
  4981.9 2143.18  4987.1 2147.59  5004.3 2147.83  5025.8 2151.13  5032.7 2150.34
  5061.0 2152.62  5138.7 2154.19  5400.6 2168.75  5408.0 2171.43  5414.8 2175.92
  5429.0 2178.20  5436.3 2177.83  5471.5 2183.67  5782.8 2197.80  5902.7 2206.05
#Mann=3,-1,0
  4054.5   0.035       0  4958.2   0.035       0  4970.1   0.035       0
Bank Sta=4958.2,4970.1
Exp/Cntr=0.3,0.1

Type RM Length L Ch R = 1,32500,500,500,500
BEGIN DESCRIPTION:
Bull Creek 65.0
END DESCRIPTION:
XS GIS Cut Line= 3
      1327536.44      6920489.14      1328794.34      6920126.24
      1328987.78      6919405.85
#Sta/Elev= 30
  3690.8 2185.58  3970.5 2171.24  4334.6 2161.31  4361.5 2153.76  4376.2 2158.31
  4395.1 2154.38  4400.3 2158.53  4439.2 2147.93  4467.6 2155.39  4490.7 2148.64
  4506.5 2153.66  4605.2 2155.84  4796.5 2147.83  4975.1 2147.20  5008.5 2144.11
  5017.0 2139.56  5017.5 2139.06  5028.9 2139.56  5049.9 2147.62  5081.0 2151.09
  5097.7 2146.01  5137.7 2145.50  5172.5 2156.34  5177.7 2153.00  5212.5 2162.70
  5217.7 2159.58  5257.7 2159.94  5350.2 2166.28  5402.0 2184.94  5745.9 2209.23
#Mann=3,-1,0
  3690.8   0.035       0  5017.0   0.035       0  5028.9   0.035       0
Bank Sta=5017,5028.9
Exp/Cntr=0.3,0.1

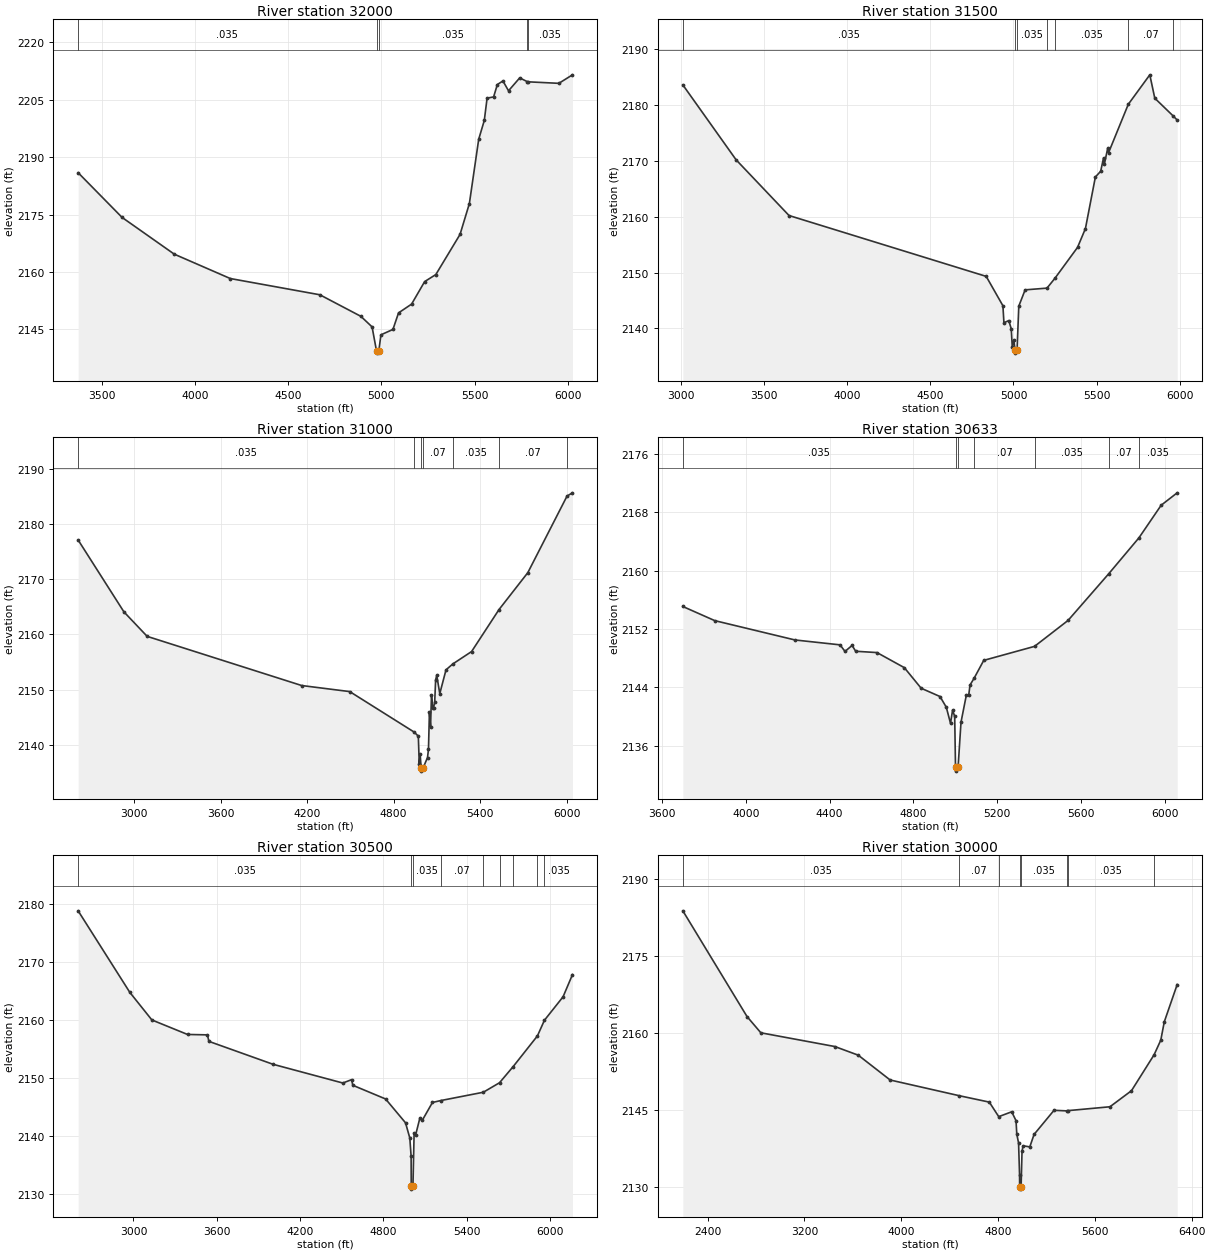
Type RM Length L Ch R = 1,32000,500,500,500
BEGIN DESCRIPTION:
Bull Creek 64.0
END DESCRIPTION:
XS GIS Cut Line= 3
      1327529.47      6920489.15      1329154.85      6920410.08
      1329182.23      6919384.95
#Sta/Elev= 30
  3372.7 2185.93  3608.5 2174.25  3888.8 2164.65  4189.2 2158.29  4669.8 2154.05
  4890.0 2148.42  4950.1 2145.66  4974.2 2139.31  4974.7 2138.81  4986.1 2139.31
  4997.6 2143.59  5062.1 2145.00  5092.1 2149.32  5162.1 2151.61  5232.2 2157.49
  5292.2 2159.33  5422.2 2169.82  5472.2 2177.87  5522.3 2194.67  5552.3 2199.57
  5567.3 2205.40  5602.3 2205.72  5622.3 2208.95  5652.3 2209.89  5682.3 2207.32
  5742.3 2210.69  5783.2 2209.70  5784.7 2209.67  5952.4 2209.27  6025.5 2211.49
#Mann=5,-1,0
  3372.7   0.035       0  4974.2   0.035       0  4986.1   0.035       0
  5783.2    0.07       0  5784.7   0.035       0
Bank Sta=4974.2,4986.1
Exp/Cntr=0.3,0.1

Type RM Length L Ch R = 1,31500,500,500,500
BEGIN DESCRIPTION:
Bull Creek 63.0
END DESCRIPTION:
XS GIS Cut Line= 4
      1327564.19      6920461.38      1329339.86      6920750.15
      1329494.48      6920638.02      1329848.89      6919718.34
#Sta/Elev= 30
  3010.0 2183.54  3330.8 2170.14  3649.1 2160.19  4836.0 2149.31  4936.6 2144.06
  4942.7 2141.02  4972.1 2141.41  4986.8 2139.93  4993.0 2136.64  5002.7 2137.98
  5009.7 2136.09  5010.2 2135.59  5021.7 2136.09  5032.2 2143.99  5070.3 2146.90
  5201.9 2147.21  5248.9 2148.94  5385.8 2154.49  5433.3 2157.86  5493.2 2167.08
  5525.1 2168.10  5542.5 2170.52  5547.8 2169.44  5567.1 2172.18  5572.5 2171.42
  5691.3 2180.07  5820.8 2185.34  5850.8 2181.16  5960.6 2178.01  5985.6 2177.26
#Mann=7,-1,0
  3010.0   0.035       0  5009.7   0.035       0  5021.7   0.035       0
  5201.9    0.07       0  5248.9   0.035       0  5691.3    0.07       0
  5960.6   0.035       0
Bank Sta=5009.7,5021.7
Exp/Cntr=0.3,0.1

Type RM Length L Ch R = 1,31000,367,367,367
BEGIN DESCRIPTION:
Bull Creek 62.0
END DESCRIPTION:
XS GIS Cut Line= 4
      1327730.83      6920551.65      1329779.45      6920857.21
      1329973.35      6920605.40      1330626.69      6919794.69
#Sta/Elev= 30
  2610.9 2177.11  2928.5 2164.10  3089.9 2159.66  4162.0 2150.76  4495.7 2149.66
  4942.6 2142.33  4971.5 2141.59  4978.0 2136.59  4984.3 2138.29  4991.2 2135.76
  4991.7 2135.26  5003.4 2135.76  5035.2 2137.71  5042.0 2139.20  5048.5 2145.90
  5056.4 2143.33  5062.9 2149.06  5070.8 2146.68  5077.2 2146.74  5085.2 2147.75
  5091.6 2151.77  5099.4 2152.60  5120.4 2149.29  5163.6 2153.60  5211.5 2154.68
  5341.1 2156.91  5531.3 2164.51  5731.4 2171.20  6003.6 2185.07  6041.2 2185.65
#Mann=7,-1,0
  2610.9   0.035       0  4942.6    0.07       0  4991.2    0.07       0
  5003.4    0.07       0  5211.5   0.035       0  5531.3    0.07       0
  6003.6   0.035       0
Bank Sta=4991.2,5003.4
Exp/Cntr=0.3,0.1

Type RM Length L Ch R = 1,30633,133,133,133
BEGIN DESCRIPTION:
Bull Creek 61.5
END DESCRIPTION:
XS GIS Cut Line= 4
      1328794.64      6920724.00      1329721.68      6920898.47
      1330131.65      6920917.96      1330705.80      6920093.42
#Sta/Elev= 30
  3699.8 2155.07  3852.2 2153.13  4234.7 2150.48  4449.7 2149.81  4473.5 2148.91
  4507.3 2149.73  4524.4 2148.93  4626.1 2148.75  4756.6 2146.68  4836.7 2143.86
  4926.8 2142.72  4956.8 2141.25  4976.8 2139.05  4986.8 2140.86  4996.8 2139.99
  5000.7 2132.99  5001.2 2132.49  5012.9 2132.99  5026.9 2139.20  5052.7 2142.96
  5063.9 2142.96  5070.0 2144.30  5089.6 2145.24  5135.4 2147.68  5377.7 2149.60
  5537.7 2153.16  5732.6 2159.59  5875.9 2164.49  5981.9 2168.96  6058.3 2170.66
#Mann=7,-1,0
  3699.8   0.035       0  5000.7   0.035       0  5012.9   0.035       0
  5089.6    0.07       0  5377.7   0.035       0  5732.6    0.07       0
  5875.9   0.035       0
Bank Sta=5000.7,5012.9
Exp/Cntr=0.3,0.1

Type RM Length L Ch R = 1,30500,500,500,500
BEGIN DESCRIPTION:
Bull Creek 61.0
END DESCRIPTION:
XS GIS Cut Line= 4
      1327667.52      6920478.75      1330004.18      6921020.78
      1330156.70      6921063.68      1330730.40      6920239.79
#Sta/Elev= 30
  2601.3 2178.85  2973.8 2164.79  3132.5 2160.04  3389.2 2157.54  3532.9 2157.47
  3543.1 2156.35  4005.1 2152.40  4508.1 2149.17  4571.1 2149.75  4580.0 2148.78
  4816.1 2146.42  4959.8 2142.31  4990.6 2139.69  5000.0 2136.55  5001.0 2131.38
  5001.5 2130.88  5013.2 2131.38  5021.6 2140.50  5032.0 2140.17  5063.2 2143.14
  5080.4 2142.74  5153.7 2145.82  5214.4 2146.15  5520.2 2147.58  5637.0 2149.22
  5735.1 2152.00  5909.9 2157.29  5960.4 2159.99  6094.6 2164.03  6162.4 2167.86
#Mann=9,-1,0
  2601.3   0.035       0  5001.0   0.035       0  5013.2   0.035       0
  5214.4    0.07       0  5520.2   0.035       0  5637.0    0.07       0
  5735.1   0.035       0  5909.9    0.07       0  5960.4   0.035       0
Bank Sta=5001,5013.2
Exp/Cntr=0.3,0.1

Type RM Length L Ch R = 1,30000,607,607,607
BEGIN DESCRIPTION:
Bull Creek 60.0
END DESCRIPTION:
XS GIS Cut Line= 4
      1327556.33      6920471.78      1330086.63      6921447.59
      1330163.13      6921394.25      1330955.02      6920387.98
#Sta/Elev= 30
  2194.8 2183.86  2725.1 2163.21  2839.6 2160.03  3450.8 2157.35  3644.5 2155.66
  3908.2 2150.81  4479.5 2147.74  4727.7 2146.49  4805.5 2143.65  4912.8 2144.60
  4948.6 2142.86  4954.7 2140.26  4969.5 2138.51  4977.9 2132.18  4978.3 2129.99
  4978.8 2129.49  4990.5 2129.99  4998.1 2136.86  5006.4 2137.96  5062.4 2137.74
  5097.7 2140.18  5262.5 2144.89  5372.9 2144.77  5375.7 2144.82  5724.8 2145.58
  5902.8 2148.72  6089.7 2155.74  6144.9 2158.59  6173.8 2162.17  6280.5 2169.46
#Mann=8,-1,0
  2194.8   0.035       0  4479.5    0.07       0  4805.5   0.035       0
  4978.3   0.035       0  4990.5   0.035       0  5372.9    0.07       0
  5375.7   0.035       0  6089.7    0.07       0
Bank Sta=4978.3,4990.5
Exp/Cntr=0.3,0.1

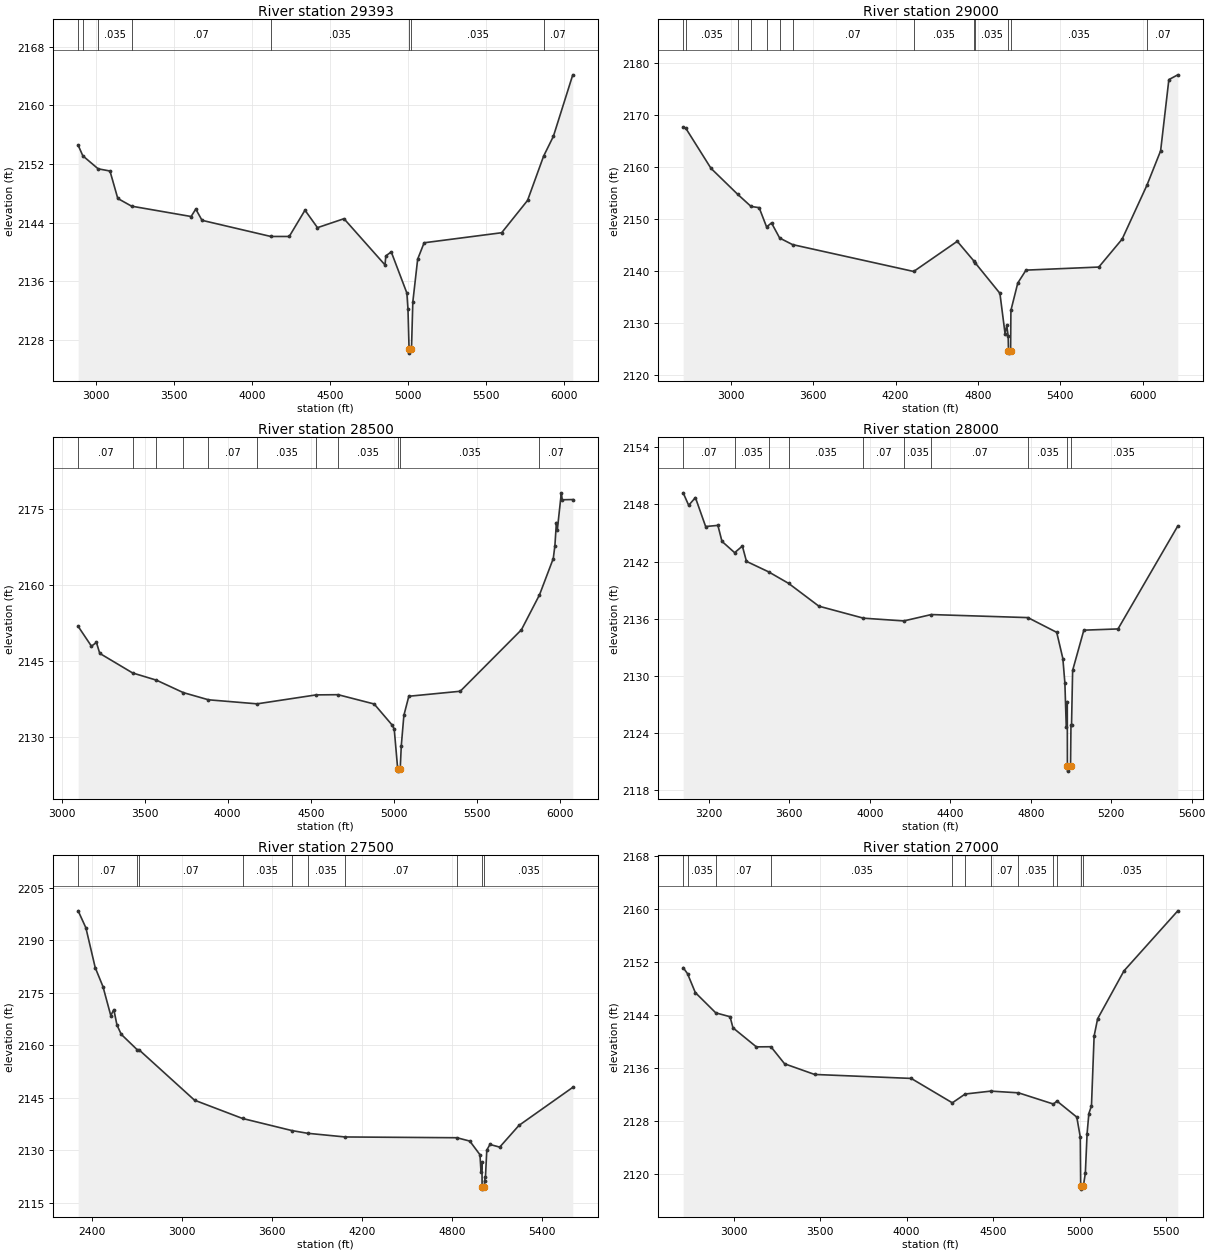
Type RM Length L Ch R = 1,29393,393,393,393
BEGIN DESCRIPTION:
Bull Creek 59.0
END DESCRIPTION:
XS GIS Cut Line= 4
      1330827.20      6923562.03      1330750.81      6921749.57
      1330674.42      6921464.85      1330954.99      6920438.05
#Sta/Elev= 30
  2885.3 2154.56  2915.4 2153.11  3013.5 2151.34  3089.5 2151.04  3139.6 2147.30
  3228.1 2146.25  3610.0 2144.84  3640.0 2145.85  3680.0 2144.32  4121.4 2142.12
  4239.6 2142.12  4340.6 2145.70  4420.7 2143.32  4590.8 2144.54  4854.0 2138.24
  4859.2 2139.47  4894.0 2140.02  4994.2 2134.41  5001.3 2132.23  5008.4 2126.72
  5008.9 2126.22  5023.8 2126.72  5032.4 2133.19  5063.5 2139.03  5104.9 2141.26
  5602.5 2142.63  5768.4 2147.03  5871.5 2153.07  5934.2 2155.77  6058.6 2164.15
#Mann=8,-1,0
  2885.3   0.035       0  2915.4    0.07       0  3013.5   0.035       0
  3228.1    0.07       0  4121.4   0.035       0  5008.4   0.035       0
  5023.8   0.035       0  5871.5    0.07       0
Bank Sta=5008.4,5023.8
Exp/Cntr=0.3,0.1

Type RM Length L Ch R = 1,29000,500,500,500
BEGIN DESCRIPTION:
Bull Creek 58.0
END DESCRIPTION:
XS GIS Cut Line= 3
      1330889.70      6923930.12      1331027.70      6921588.08
      1331014.70      6920332.95
#Sta/Elev= 30
  2653.9 2167.70  2672.7 2167.55  2856.4 2159.83  3050.3 2154.85  3148.2 2152.50
  3207.0 2152.27  3261.2 2148.57  3297.1 2149.33  3356.5 2146.43  3449.9 2145.17
  4332.1 2140.00  4649.5 2145.80  4769.4 2142.05  4781.8 2141.60  4960.0 2135.80
  4997.5 2128.03  5010.1 2129.62  5020.1 2127.59  5022.4 2124.80  5022.9 2124.30
  5037.8 2124.80  5040.1 2132.52  5090.1 2137.78  5150.1 2140.26  5680.1 2140.85
  5850.1 2146.23  6030.2 2156.57  6130.1 2163.20  6190.1 2176.89  6255.2 2177.81
#Mann=13,-1,0
  2653.9    0.07       0  2672.7   0.035       0  3050.3    0.07       0
  3148.2   0.035       0  3261.2    0.07       0  3356.5   0.035       0
  3449.9    0.07       0  4332.1   0.035       0  4769.4    0.07       0
  4781.8   0.035       0  5022.4   0.035       0  5037.8   0.035       0
  6030.2    0.07       0
Bank Sta=5022.4,5037.8
Exp/Cntr=0.3,0.1

Type RM Length L Ch R = 1,28500,500,500,500
BEGIN DESCRIPTION:
Bull Creek 57.0
END DESCRIPTION:
XS GIS Cut Line= 3
      1331505.00      6923237.96      1331402.30      6921340.34
      1331005.00      6920338.00
#Sta/Elev= 30
  3099.6 2151.84  3179.7 2147.91  3209.7 2148.66  3229.7 2146.49  3427.6 2142.62
  3571.2 2141.19  3733.0 2138.73  3884.5 2137.31  4177.3 2136.51  4532.7 2138.28
  4664.7 2138.32  4882.2 2136.48  4992.3 2132.24  5003.1 2131.47  5023.7 2123.70
  5024.2 2123.20  5039.1 2123.70  5045.5 2128.22  5061.1 2134.22  5090.8 2138.01
  5400.5 2139.00  5768.9 2151.16  5877.8 2158.07  5960.7 2165.25  5970.6 2167.81
  5979.6 2172.37  5985.0 2170.89  6009.3 2178.25  6014.7 2176.88  6078.2 2176.92
#Mann=11,-1,0
  3099.6    0.07       0  3427.6   0.035       0  3571.2    0.07       0
  3733.0   0.035       0  3884.5    0.07       0  4177.3   0.035       0
  4532.7    0.07       0  4664.7   0.035       0  5023.7   0.035       0
  5039.1   0.035       0  5877.8    0.07       0
Bank Sta=5023.7,5039.1
Exp/Cntr=0.3,0.1

Type RM Length L Ch R = 1,28000,500,500,500
BEGIN DESCRIPTION:
Bull Creek 56.0
END DESCRIPTION:
XS GIS Cut Line= 3
      1331504.99      6923188.04      1331833.68      6921288.26
      1331655.01      6920788.01
#Sta/Elev= 30
  3072.0 2149.22  3099.4 2147.91  3132.9 2148.72  3183.7 2145.68  3244.6 2145.80
  3264.9 2144.12  3328.0 2142.93  3366.3 2143.63  3386.6 2142.02  3496.5 2140.92
  3596.0 2139.71  3746.8 2137.31  3968.4 2136.05  4168.7 2135.76  4305.7 2136.43
  4786.0 2136.11  4929.2 2134.56  4959.7 2131.81  4969.8 2129.24  4976.7 2124.60
  4981.7 2127.29  4982.3 2120.48  4982.8 2119.98  4997.9 2120.48  5000.0 2124.79
  5002.8 2124.79  5008.3 2130.56  5064.0 2134.79  5233.9 2134.92  5531.2 2145.74
#Mann=10,-1,0
  3072.0    0.07       0  3328.0   0.035       0  3496.5    0.07       0
  3596.0   0.035       0  3968.4    0.07       0  4168.7   0.035       0
  4305.7    0.07       0  4786.0   0.035       0  4982.3   0.035       0
  4997.9   0.035       0
Bank Sta=4982.3,4997.9
Exp/Cntr=0.3,0.1

Type RM Length L Ch R = 1,27500,500,500,500
BEGIN DESCRIPTION:
Bull Creek 55.0
END DESCRIPTION:
XS GIS Cut Line= 3
      1331605.00      6923787.99      1332301.21      6921184.99
      1331955.00      6920687.99
#Sta/Elev= 30
  2305.5 2198.35  2357.2 2193.49  2419.4 2182.14  2471.1 2176.72  2523.2 2168.46
  2543.6 2170.15  2564.3 2165.78  2593.0 2163.10  2699.3 2158.71  2710.8 2158.71
  3081.9 2144.30  3402.1 2139.08  3733.0 2135.61  3836.4 2134.85  4086.8 2133.80
  4832.8 2133.58  4918.6 2132.62  4986.5 2128.73  4993.5 2123.83  5000.0 2126.67
  5000.7 2119.41  5001.2 2118.91  5016.3 2119.41  5017.1 2121.24  5023.2 2122.44
  5032.0 2130.04  5052.9 2131.66  5118.2 2130.90  5246.6 2137.10  5605.7 2147.96
#Mann=10,-1,0
  2305.5    0.07       0  2699.3   0.035       0  2710.8    0.07       0
  3402.1   0.035       0  3733.0    0.07       0  3836.4   0.035       0
  4086.8    0.07       0  4832.8   0.035       0  5000.7   0.035       0
  5016.3   0.035       0
Bank Sta=5000.7,5016.3
Exp/Cntr=0.3,0.1

Type RM Length L Ch R = 1,27000,500,500,500
BEGIN DESCRIPTION:
Bull Creek 54.0
END DESCRIPTION:
XS GIS Cut Line= 3
      1331773.40      6923221.10      1332778.27      6921160.68
      1332875.52      6920601.27
#Sta/Elev= 30
  2707.6 2151.15  2732.7 2150.24  2777.8 2147.38  2896.2 2144.31  2978.6 2143.73
  2995.6 2142.05  3130.8 2139.17  3215.0 2139.19  3294.1 2136.61  3467.6 2135.00
  4026.2 2134.40  4264.0 2130.71  4338.2 2132.04  4486.3 2132.48  4646.6 2132.22
  4849.0 2130.52  4868.9 2130.98  4983.7 2128.55  5003.9 2125.54  5006.2 2118.16
  5006.7 2117.66  5021.9 2118.16  5033.2 2120.09  5043.3 2126.07  5053.5 2129.09
  5068.6 2130.26  5083.9 2140.81  5104.2 2143.42  5256.5 2150.66  5567.8 2159.74
#Mann=12,-1,0
  2707.6    0.07       0  2732.7   0.035       0  2896.2    0.07       0
  3215.0   0.035       0  4264.0    0.07       0  4338.2   0.035       0
  4486.3    0.07       0  4646.6   0.035       0  4849.0    0.07       0
  4868.9   0.035       0  5006.2   0.035       0  5021.9   0.035       0
Bank Sta=5006.2,5021.9
Exp/Cntr=0.3,0.1

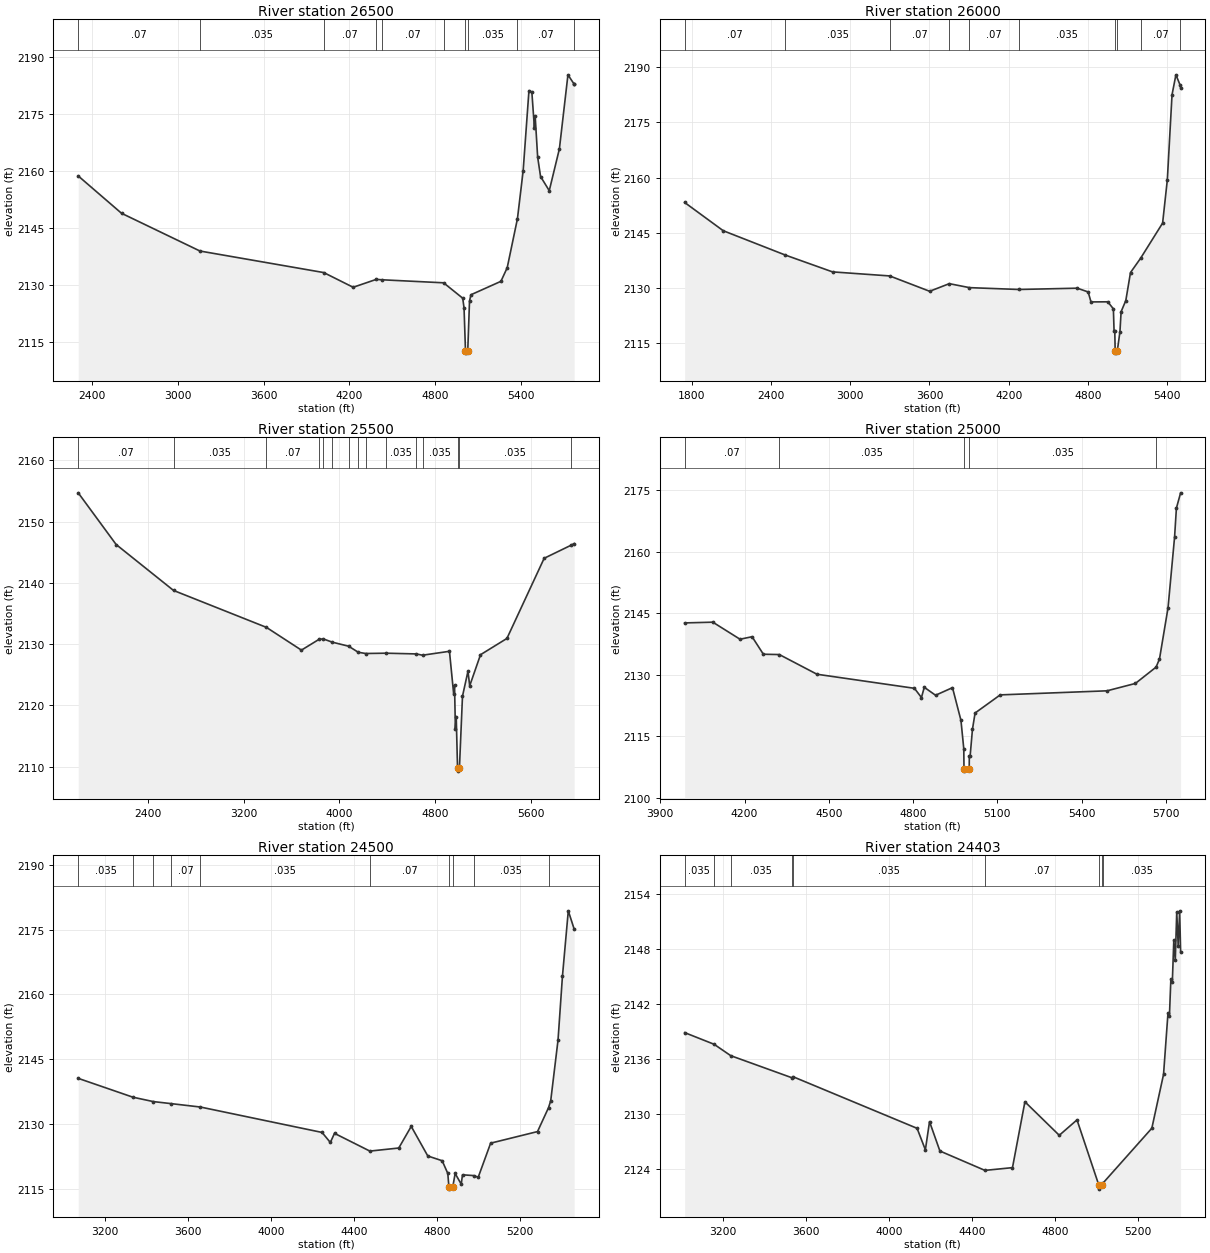
Type RM Length L Ch R = 1,26500,500,500,500
BEGIN DESCRIPTION:
Bull Creek 53.0
END DESCRIPTION:
XS GIS Cut Line= 3
      1331470.40      6923430.38      1333174.56      6921338.59
      1333043.35      6920576.20
#Sta/Elev= 30
  2301.9 2158.75  2605.1 2148.90  3154.4 2138.94  4020.8 2133.26  4226.6 2129.38
  4388.2 2131.46  4427.0 2131.36  4859.6 2130.56  4993.5 2126.50  5002.8 2123.96
  5013.0 2112.51  5013.5 2112.01  5028.7 2112.51  5041.2 2125.79  5051.3 2127.41
  5261.0 2130.95  5305.0 2134.54  5376.6 2147.46  5416.6 2160.09  5457.2 2181.26
  5477.5 2180.89  5495.6 2171.30  5500.7 2174.52  5518.1 2163.71  5538.4 2158.60
  5599.3 2154.86  5670.3 2165.90  5730.2 2185.42  5771.2 2183.09  5773.6 2183.09
#Mann=10,-1,0
  2301.9    0.07       0  3154.4   0.035       0  4020.8    0.07       0
  4388.2   0.035       0  4427.0    0.07       0  4859.6   0.035       0
  5013.0   0.035       0  5028.7   0.035       0  5376.6    0.07       0
  5771.2   0.035       0
Bank Sta=5013,5028.7
Exp/Cntr=0.3,0.1

Type RM Length L Ch R = 1,26000,500,500,500
BEGIN DESCRIPTION:
Bull Creek 52.0
END DESCRIPTION:
XS GIS Cut Line= 4
      1331449.57      6923305.37      1333543.34      6921154.30
      1333373.12      6920969.07      1333080.80      6920561.95
#Sta/Elev= 30
  1746.6 2153.25  2038.5 2145.58  2507.9 2138.98  2865.9 2134.40  3298.7 2133.30
  3601.3 2129.13  3749.9 2131.20  3902.8 2130.12  4275.8 2129.62  4718.7 2129.97
  4801.1 2128.95  4822.7 2126.24  4949.7 2126.27  4992.2 2124.36  4997.3 2118.38
  5002.7 2118.38  5005.8 2112.83  5006.3 2112.33  5021.5 2112.83  5042.0 2118.19
  5050.6 2123.58  5086.2 2126.61  5121.8 2134.22  5198.2 2138.10  5364.9 2147.66
  5400.6 2159.40  5436.2 2182.52  5465.6 2187.93  5498.4 2185.06  5501.2 2184.43
#Mann=10,-1,0
  1746.6    0.07       0  2507.9   0.035       0  3298.7    0.07       0
  3749.9   0.035       0  3902.8    0.07       0  4275.8   0.035       0
  5005.8   0.035       0  5021.5   0.035       0  5198.2    0.07       0
  5498.4   0.035       0
Bank Sta=5005.8,5021.5
Exp/Cntr=0.3,0.1

Type RM Length L Ch R = 1,25500,500,500,500
BEGIN DESCRIPTION:
Bull Creek 51.0
END DESCRIPTION:
XS GIS Cut Line= 3
      1331475.64      6923347.00      1333716.70      6921087.22
      1333631.89      6920128.26
#Sta/Elev= 30
  1817.4 2154.71  2134.4 2146.27  2613.9 2138.77  3390.3 2132.74  3683.0 2129.02
  3832.6 2130.81  3867.4 2130.84  3941.1 2130.32  4077.7 2129.66  4158.3 2128.67
  4220.5 2128.47  4391.2 2128.52  4643.8 2128.40  4695.2 2128.19  4920.5 2128.83
  4955.8 2121.84  4962.9 2123.30  4970.0 2116.16  4977.0 2118.16  4988.0 2109.76
  4988.5 2109.26  5003.8 2109.76  5029.3 2121.49  5075.3 2125.58  5089.6 2123.19
  5179.9 2128.27  5400.8 2130.93  5712.0 2144.02  5938.8 2146.17  5962.7 2146.42
#Mann=15,-1,0
  1817.4    0.07       0  2613.9   0.035       0  3390.3    0.07       0
  3832.6   0.035       0  3867.4    0.07       0  3941.1   0.035       0
  4077.7    0.07       0  4158.3   0.035       0  4220.5    0.07       0
  4391.2   0.035       0  4643.8    0.07       0  4695.2   0.035       0
  4988.0   0.035       0  5003.8   0.035       0  5938.8    0.07       0
Bank Sta=4988,5003.8
Exp/Cntr=0.3,0.1

Type RM Length L Ch R = 1,25000,500,500,500
BEGIN DESCRIPTION:
Bull Creek 50.0
END DESCRIPTION:
XS GIS Cut Line= 3
      1334080.67      6922196.81      1334178.94      6921188.38
      1333904.98      6920487.96
#Sta/Elev= 30
  3986.8 2142.63  4087.0 2142.81  4183.8 2138.66  4226.7 2139.27  4266.9 2135.01
  4323.8 2134.93  4457.8 2130.14  4804.6 2126.72  4829.6 2124.47  4839.6 2126.97
  4879.8 2125.03  4940.1 2126.88  4970.2 2118.92  4980.3 2111.99  4981.0 2107.07
  4981.5 2106.57  4999.6 2107.07  5000.0 2110.27  5002.9 2110.27  5011.2 2116.78
  5020.5 2120.71  5110.0 2125.12  5490.1 2126.11  5591.0 2127.90  5664.7 2131.87
  5676.9 2133.85  5707.3 2146.31  5730.6 2163.51  5737.1 2170.55  5752.1 2174.28
#Mann=5,-1,0
  3986.8    0.07       0  4323.8   0.035       0  4981.0   0.035       0
  4999.6   0.035       0  5664.7    0.07       0
Bank Sta=4981,4999.6
Exp/Cntr=0.3,0.1

Type RM Length L Ch R = 1,24500,97,97,97
BEGIN DESCRIPTION:
Bull Creek 49.0
END DESCRIPTION:
XS GIS Cut Line= 4
      1334445.25      6922623.89      1334372.34      6920868.71
      1334232.19      6920765.57      1333904.99      6920437.99
#Sta/Elev= 30
  3069.3 2140.61  3333.6 2136.25  3431.7 2135.24  3519.3 2134.76  3659.2 2133.98
  4246.2 2128.11  4286.2 2125.79  4306.3 2127.90  4477.0 2123.80  4616.5 2124.51
  4676.6 2129.51  4756.6 2122.67  4826.0 2121.57  4853.1 2118.64  4858.5 2115.51
  4859.0 2115.01  4877.1 2115.51  4888.6 2118.63  4917.9 2116.16  4924.1 2118.32
  4977.8 2118.14  5000.0 2117.76  5059.9 2125.63  5286.2 2128.31  5339.3 2133.83
  5349.9 2135.43  5385.2 2149.46  5406.4 2164.15  5434.7 2179.32  5463.0 2175.11
#Mann=10,-1,0
  3069.3   0.035       0  3333.6    0.07       0  3431.7   0.035       0
  3519.3    0.07       0  3659.2   0.035       0  4477.0    0.07       0
  4858.5   0.035       0  4877.1    0.07       0  4977.8   0.035       0
  5339.3    0.07       0
Bank Sta=4858.5,4877.1
Exp/Cntr=0.3,0.1

Type RM Length L Ch R = 1,24403,81,81,81
BEGIN DESCRIPTION:
Bull Creek 48.6
END DESCRIPTION:
XS GIS Cut Line= 4
      1334503.84      6922588.72      1334430.93      6920833.56
      1334290.78      6920730.41      1333963.64      6920402.89
#Sta/Elev= 30
  3013.6 2138.86  3155.7 2137.59  3235.9 2136.35  3531.9 2133.94  3535.4 2134.07
  4135.3 2128.44  4175.3 2126.10  4195.3 2129.17  4245.4 2125.97  4462.8 2123.86
  4595.7 2124.16  4655.7 2131.33  4821.5 2127.68  4907.1 2129.36  5011.5 2122.32
  5012.0 2121.82  5030.1 2122.32  5032.7 2122.48  5268.3 2128.45  5324.8 2134.31
  5346.1 2140.95  5353.1 2140.63  5360.2 2144.71  5367.3 2144.42  5374.3 2148.89
  5381.4 2146.73  5388.5 2152.02  5395.6 2148.26  5402.6 2152.12  5407.2 2147.68
#Mann=9,-1,0
  3013.6   0.035       0  3155.7    0.07       0  3235.9   0.035       0
  3531.9    0.07       0  3535.4   0.035       0  4462.8    0.07       0
  5011.5    0.07       0  5030.1    0.07       0  5032.7   0.035       0
Bank Sta=5011.5,5030.1
Exp/Cntr=0.3,0.1

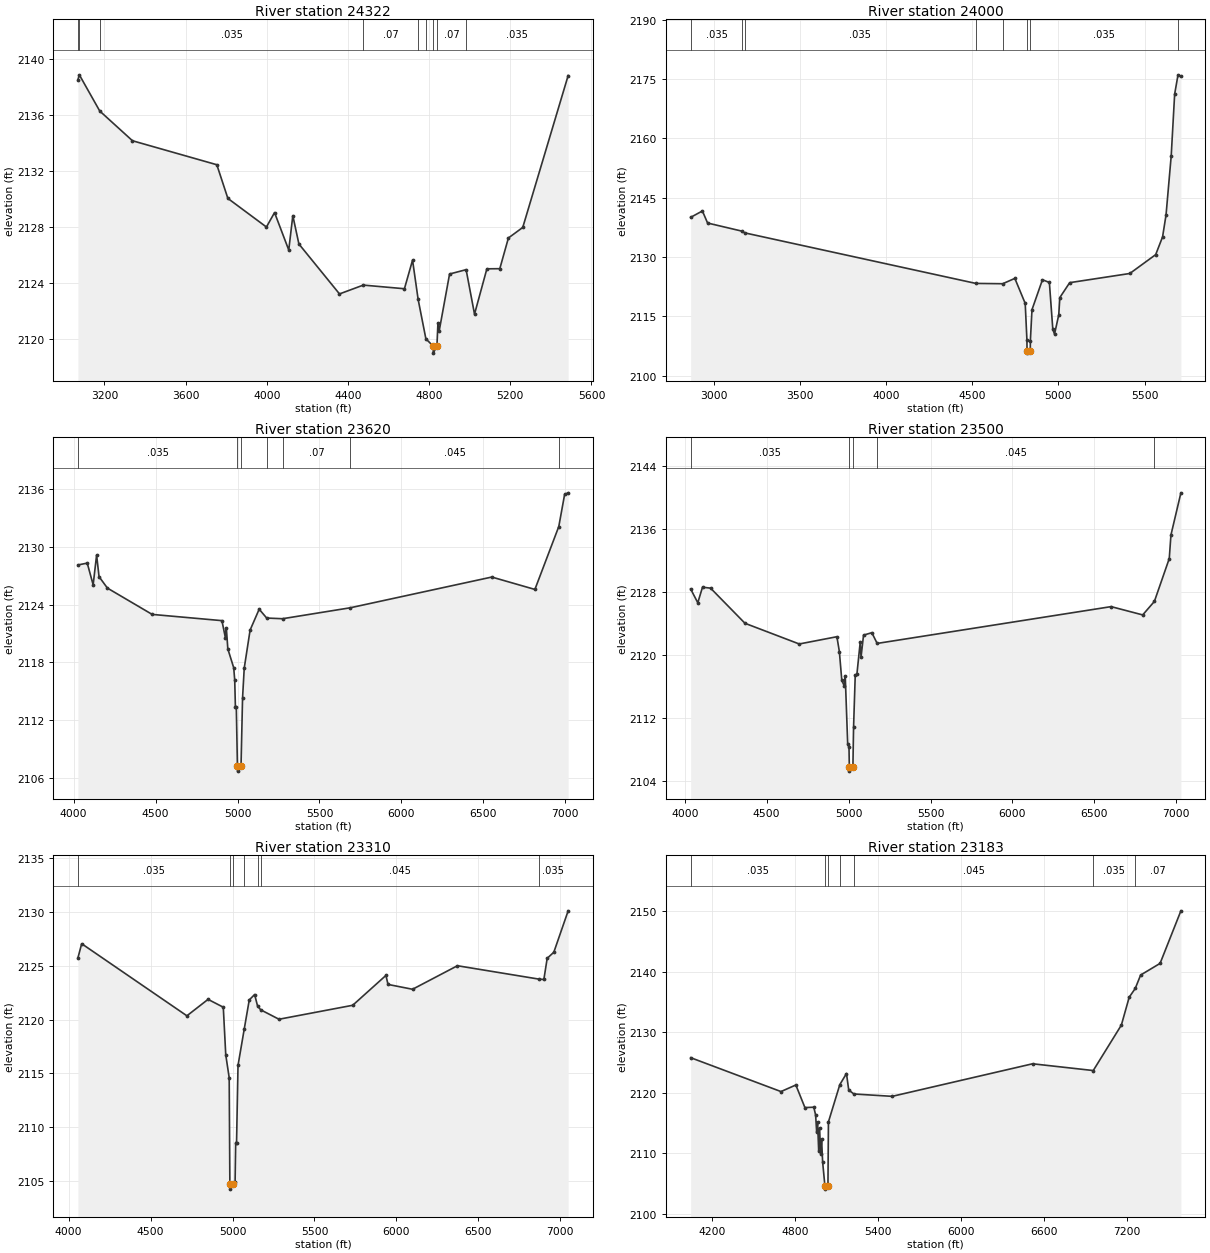
Type RM Length L Ch R = 1,24322,322,322,322
BEGIN DESCRIPTION:
Bull Creek 48.5
END DESCRIPTION:
XS GIS Cut Line= 4
      1334503.85      6922476.78      1334494.36      6920787.13
      1334290.78      6920618.44      1333964.69      6920291.96
#Sta/Elev= 30
  3069.6 2138.49  3076.5 2138.84  3177.1 2136.26  3338.4 2134.14  3754.0 2132.43
  3808.4 2130.03  3998.4 2127.99  4038.4 2129.02  4108.4 2126.35  4128.4 2128.80
  4158.4 2126.78  4358.4 2123.22  4475.7 2123.85  4678.4 2123.59  4718.4 2125.63
  4745.9 2122.83  4784.1 2120.02  4819.9 2119.50  4820.4 2119.00  4838.5 2119.50
  4843.5 2121.16  4850.0 2120.61  4900.8 2124.64  4982.3 2124.95  5023.7 2121.78
  5084.6 2125.01  5148.3 2125.02  5190.7 2127.21  5261.4 2127.96  5485.1 2138.79
#Mann=9,-1,0
  3069.6   0.035       0  3076.5    0.07       0  3177.1   0.035       0
  4475.7    0.07       0  4745.9   0.035       0  4784.1    0.07       0
  4819.9   0.035       0  4838.5    0.07       0  4982.3   0.035       0
Bank Sta=4819.9,4838.5
Exp/Cntr=0.3,0.1

Type RM Length L Ch R = 1,24000,380,380,380
BEGIN DESCRIPTION:
Bull Creek 48.0
END DESCRIPTION:
XS GIS Cut Line= 4
      1334460.88      6922675.96      1334599.67      6920545.78
      1334502.17      6920464.21      1333918.78      6920433.88
#Sta/Elev= 30
  2865.3 2140.03  2933.4 2141.64  2963.5 2138.59  3164.7 2136.52  3179.4 2136.10
  4520.7 2123.32  4676.8 2123.24  4747.2 2124.59  4807.4 2118.27  4817.4 2108.99
  4818.1 2106.19  4818.6 2105.69  4836.8 2106.19  4837.4 2108.85  4846.8 2116.68
  4907.6 2124.25  4947.7 2123.56  4967.7 2111.70  4977.7 2110.50  5002.2 2115.40
  5008.5 2119.75  5065.7 2123.51  5414.7 2125.83  5564.9 2130.60  5604.9 2135.09
  5625.0 2140.63  5655.0 2155.57  5675.0 2171.19  5694.6 2176.07  5711.3 2175.72
#Mann=8,-1,0
  2865.3   0.035       0  3164.7    0.07       0  3179.4   0.035       0
  4520.7    0.07       0  4676.8   0.035       0  4818.1   0.035       0
  4836.8   0.035       0  5694.6    0.07       0
Bank Sta=4818.1,4836.8
Exp/Cntr=0.3,0.1

Type RM Length L Ch R = 1,23620,120,120,120
BEGIN DESCRIPTION:
Bull Creek 47.5
END DESCRIPTION:
XS GIS Cut Line= 3
      1334386.97      6921498.38      1334924.57      6920698.44
      1334586.95      6918698.44
#Sta/Elev= 30
  4025.9 2128.14  4082.8 2128.33  4118.8 2126.07  4139.9 2129.17  4154.8 2126.92
  4205.8 2125.73  4478.9 2122.99  4904.8 2122.34  4925.8 2120.57  4931.9 2121.53
  4940.8 2119.40  4976.8 2117.43  4982.9 2116.14  4987.0 2113.38  4992.5 2113.38
  4999.5 2107.17  5000.0 2106.67  5021.3 2107.17  5030.7 2114.29  5040.9 2117.39
  5076.8 2121.36  5132.1 2123.53  5178.1 2122.61  5274.6 2122.54  5688.2 2123.68
  6551.9 2126.88  6815.0 2125.59  6960.8 2132.14  6996.4 2135.48  7018.0 2135.65
#Mann=7,-1,0
  4025.9   0.035       0  4999.5   0.035       0  5021.3   0.035       0
  5178.1   0.045       0  5274.6    0.07       0  5688.2   0.045       0
  6960.8    0.07       0
Bank Sta=4999.5,5021.3
Exp/Cntr=0.3,0.1

Type RM Length L Ch R = 1,23500,190,190,190
BEGIN DESCRIPTION:
Bull Creek 47.0
END DESCRIPTION:
XS GIS Cut Line= 3
      1334505.03      6921487.96      1335042.62      6920688.02
      1334705.00      6918688.02
#Sta/Elev= 30
  4036.2 2128.37  4079.6 2126.63  4108.4 2128.60  4157.7 2128.48  4367.7 2124.03
  4698.8 2121.41  4928.7 2122.33  4943.7 2120.45  4958.6 2116.80  4973.6 2116.10
  4979.7 2117.31  4994.6 2108.73  5002.5 2108.33  5004.6 2105.81  5005.1 2105.31
  5026.4 2105.81  5030.4 2110.87  5040.6 2117.45  5050.7 2117.56  5070.9 2121.62
  5076.0 2119.75  5091.3 2122.53  5142.0 2122.84  5174.4 2121.48  6602.4 2126.14
  6795.1 2125.09  6866.5 2126.80  6957.3 2132.23  6967.5 2135.21  7028.3 2140.55
#Mann=5,-1,0
  4036.2   0.035       0  5004.6   0.035       0  5026.4   0.035       0
  5174.4   0.045       0  6866.5    0.07       0
Bank Sta=5004.6,5026.4
Exp/Cntr=0.3,0.1

Type RM Length L Ch R = 1,23310,127,127,127
BEGIN DESCRIPTION:
Bull Creek 46.5
END DESCRIPTION:
XS GIS Cut Line= 3
      1334706.36      6921470.67      1335244.01      6920670.66
      1334906.59      6918671.83
#Sta/Elev= 30
  4056.7 2125.75  4079.6 2127.07  4721.6 2120.36  4850.6 2121.89  4943.6 2121.16
  4958.6 2116.73  4979.6 2114.60  4983.7 2104.73  4984.2 2104.23  5005.5 2104.73
  5015.6 2104.88  5019.2 2108.56  5024.5 2108.56  5033.4 2115.74  5071.9 2119.17
  5102.1 2121.84  5134.8 2122.34  5152.4 2121.29  5171.6 2120.92  5283.4 2120.04
  5733.2 2121.34  5936.0 2124.12  5948.5 2123.28  6098.3 2122.83  6372.1 2125.02
  6867.3 2123.78  6899.5 2123.74  6919.7 2125.71  6960.3 2126.28  7047.7 2130.13
#Mann=7,-1,0
  4056.7   0.035       0  4983.7   0.035       0  5005.5   0.035       0
  5071.9    0.07       0  5152.4   0.035       0  5171.6   0.045       0
  6867.3   0.035       0
Bank Sta=4983.7,5005.5
Exp/Cntr=0.3,0.1

Type RM Length L Ch R = 1,23183,431,431,431
BEGIN DESCRIPTION:
Bull Creek 46.0
END DESCRIPTION:
XS GIS Cut Line= 4
      1334799.07      6921509.84      1335276.69      6920816.37
      1335403.65      6920653.61      1334782.92      6918235.98
#Sta/Elev= 30
  4045.8 2125.80  4698.7 2120.19  4806.2 2121.28  4871.8 2117.54  4936.1 2117.60
  4949.2 2116.31  4956.9 2113.44  4963.2 2115.18  4971.4 2110.36  4977.7 2114.20
  4985.8 2109.87  4992.2 2112.35  4999.9 2108.55  5016.5 2104.54  5017.0 2104.04
  5038.3 2104.54  5041.9 2115.17  5124.2 2121.34  5172.3 2123.18  5188.6 2120.44
  5226.0 2119.79  5502.7 2119.40  6518.0 2124.79  6956.5 2123.67  7159.7 2131.19
  7216.5 2135.81  7260.2 2137.26  7299.1 2139.48  7439.8 2141.41  7590.3 2150.11
#Mann=7,-1,0
  4045.8   0.035       0  5016.5   0.035       0  5038.3   0.035       0
  5124.2    0.07       0  5226.0   0.045       0  6956.5   0.035       0
  7260.2    0.07       0
Bank Sta=5016.5,5038.3
Exp/Cntr=0.3,0.1