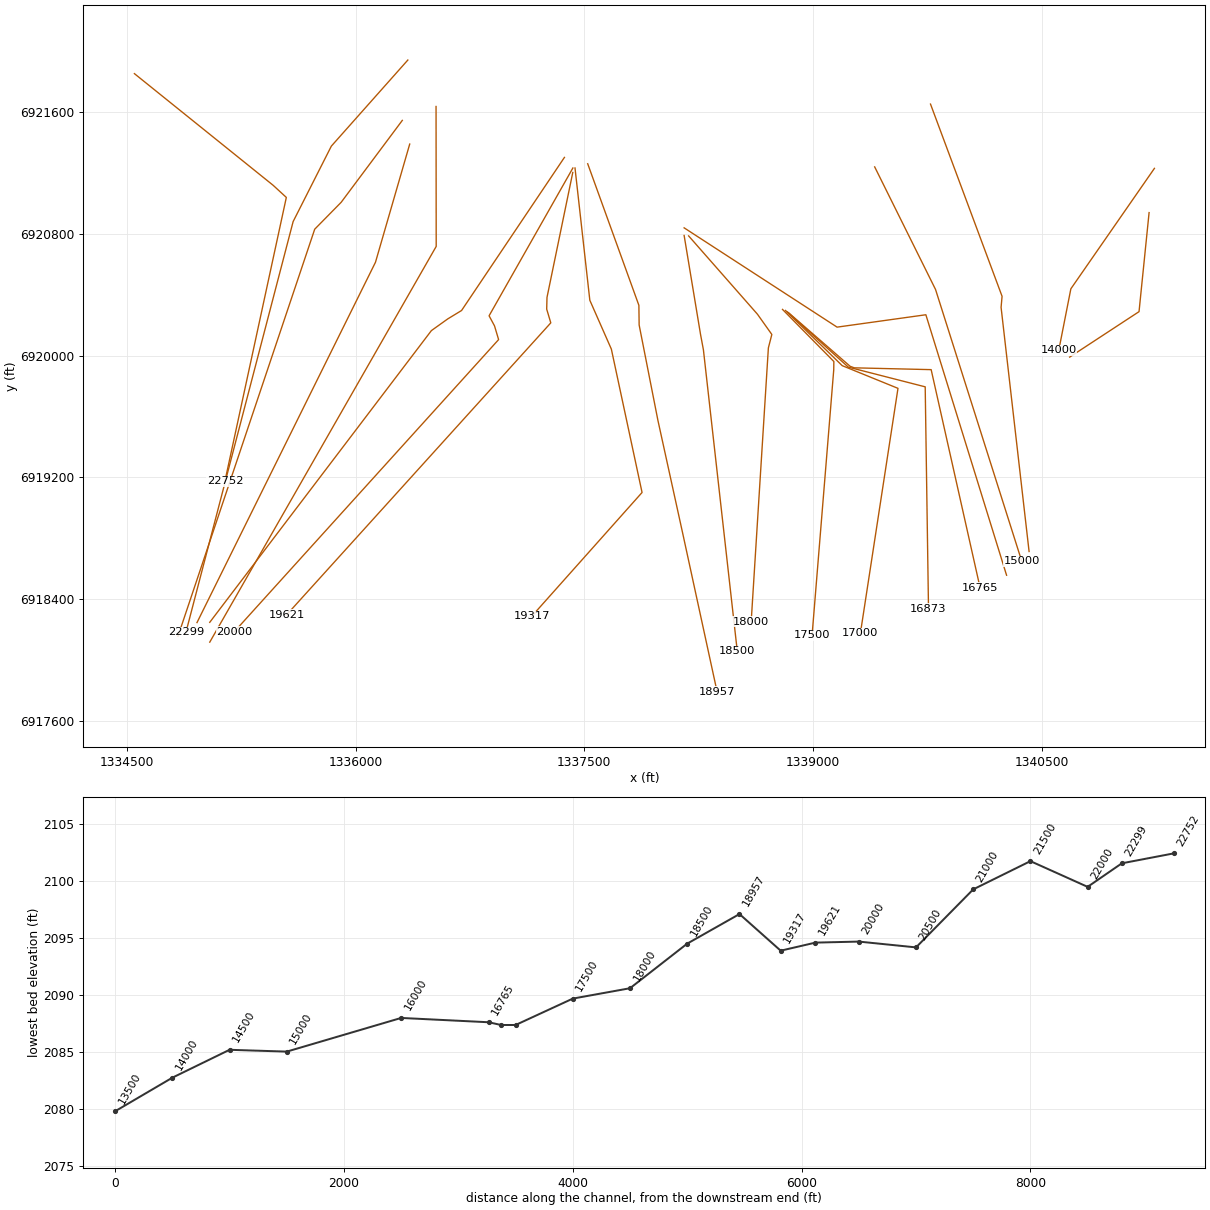
HEC-RAS study Bull Creek.prj: Bull Creek Base Level Engineering

--- Bull Creek.g01 (geometry) --- (continued)

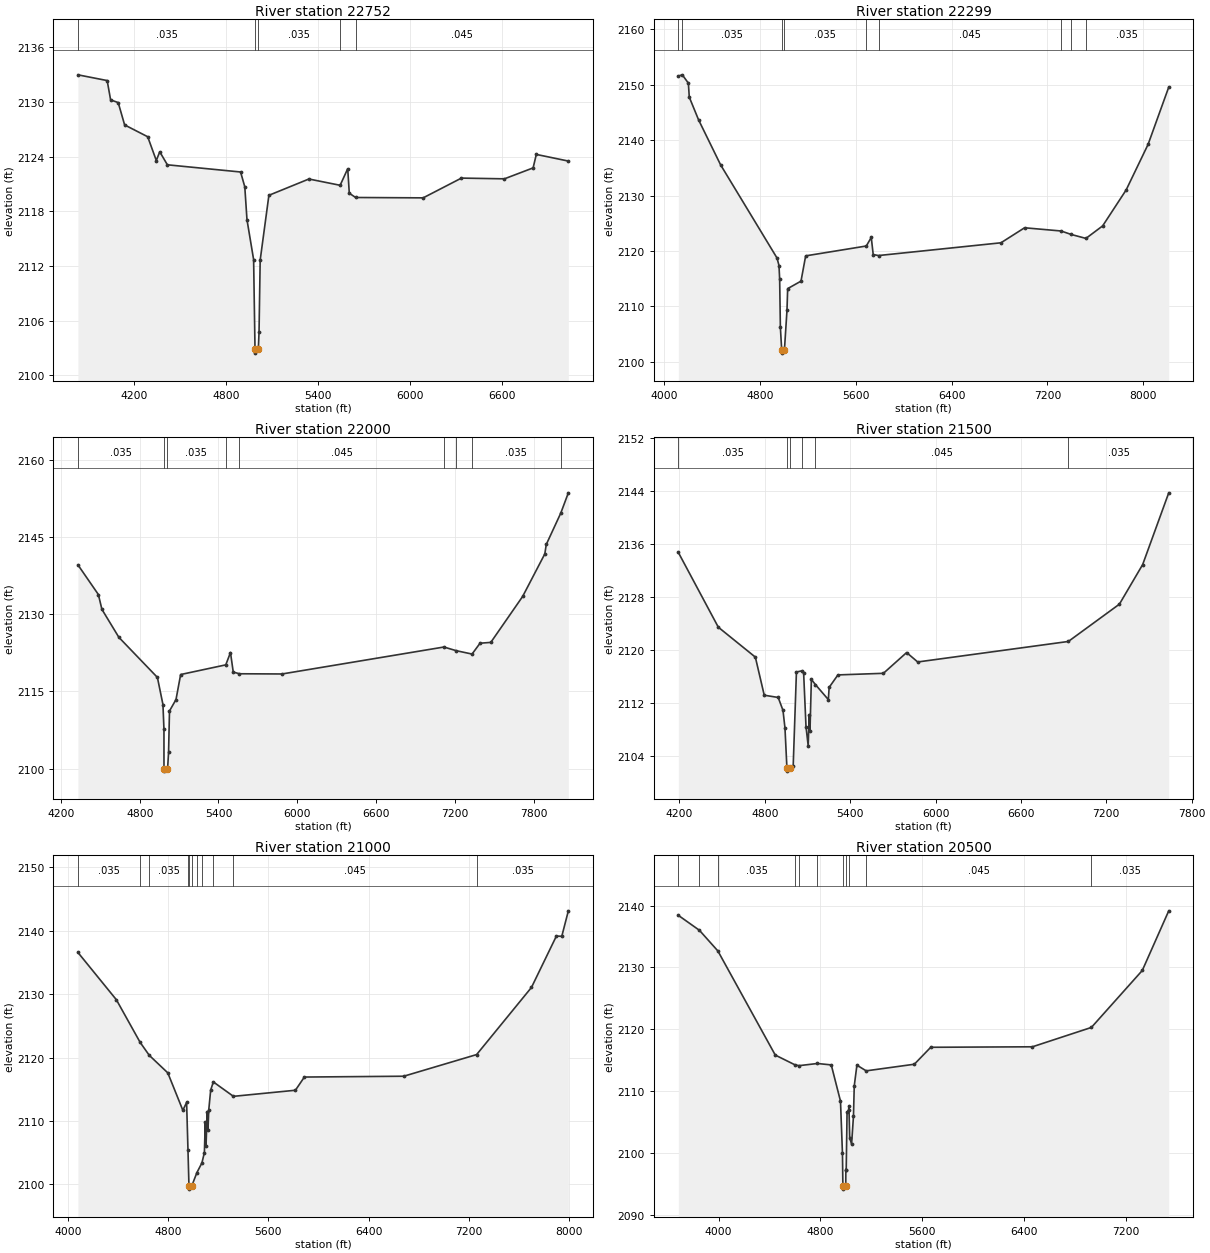
Type RM Length L Ch R = 1,22752,453,453,453
BEGIN DESCRIPTION:
Bull Creek 45.5
END DESCRIPTION:
XS GIS Cut Line= 4
      1334549.05      6921850.14      1335458.77      6921117.51
      1335545.57      6921037.65      1335142.51      6919174.14
#Sta/Elev= 30
  3837.0 2132.99  4027.3 2132.36  4049.7 2130.24  4099.2 2129.94  4140.9 2127.49
  4291.2 2126.19  4347.2 2123.58  4369.6 2124.54  4419.2 2123.11  4895.9 2122.32
  4923.2 2120.69  4937.5 2117.08  4980.7 2112.70  4989.7 2102.93  4990.2 2102.43
  5011.6 2102.93  5016.0 2104.76  5023.4 2112.64  5080.1 2119.76  5340.6 2121.55
  5543.9 2120.86  5593.3 2122.68  5603.5 2119.99  5644.7 2119.52  6084.4 2119.48
  6333.5 2121.65  6613.5 2121.57  6800.2 2122.77  6821.0 2124.25  7029.6 2123.52
#Mann=5,-1,0
  3837.0   0.035       0  4989.7   0.035       0  5011.6   0.035       0
  5543.9    0.07       0  5644.7   0.045       0
Bank Sta=4989.7,5011.6
Exp/Cntr=0.3,0.1

Type RM Length L Ch R = 1,22299,299,299,299
BEGIN DESCRIPTION:
Bull Creek 45.0
END DESCRIPTION:
XS GIS Cut Line= 4
      1336342.57      6921939.34      1335840.83      6921374.41
      1335590.22      6920879.24      1334887.09      6918183.89
#Sta/Elev= 30
  4117.2 2151.56  4150.5 2151.78  4201.1 2150.28  4208.7 2147.75  4286.4 2143.65
  4470.4 2135.53  4941.3 2118.73  4958.0 2117.37  4963.6 2114.85  4969.6 2106.19
  4980.8 2102.06  4981.3 2101.56  5003.2 2102.06  5024.8 2109.32  5030.4 2113.20
  5141.8 2114.55  5180.8 2119.11  5687.2 2120.89  5728.7 2122.44  5744.9 2119.35
  5789.2 2119.17  6811.9 2121.47  7009.2 2124.18  7314.0 2123.60  7397.8 2122.98
  7521.6 2122.26  7661.3 2124.52  7857.7 2131.01  8040.9 2139.23  8213.3 2149.56
#Mann=9,-1,0
  4117.2    0.07       0  4150.5   0.035       0  4980.8   0.035       0
  5003.2   0.035       0  5687.2    0.07       0  5789.2   0.045       0
  7314.0   0.035       0  7397.8   0.045       0  7521.6   0.035       0
Bank Sta=4980.8,5003.2
Exp/Cntr=0.3,0.1

Type RM Length L Ch R = 1,22000,500,500,500
BEGIN DESCRIPTION:
Bull Creek 44.0
END DESCRIPTION:
XS GIS Cut Line= 4
      1336306.35      6921543.28      1335905.43      6921005.85
      1335731.70      6920829.09      1334835.02      6918157.92
#Sta/Elev= 30
  4329.5 2139.59  4485.1 2133.83  4512.2 2130.94  4641.5 2125.50  4934.9 2117.71
  4977.1 2112.44  4984.8 2107.63  4985.0 2099.99  4985.5 2099.49  5007.4 2099.99
  5012.9 2100.13  5020.0 2103.19  5027.0 2111.19  5076.6 2113.41  5111.9 2118.27
  5455.7 2120.15  5491.6 2122.55  5512.7 2118.75  5559.9 2118.42  5884.4 2118.38
  7117.7 2123.62  7209.6 2122.92  7331.9 2122.25  7392.8 2124.36  7474.7 2124.52
  7717.3 2133.45  7886.1 2141.72  7897.3 2143.56  8008.0 2149.67  8065.5 2153.60
#Mann=9,-1,0
  4329.5   0.035       0  4985.0   0.035       0  5007.4   0.035       0
  5455.7    0.07       0  5559.9   0.045       0  7117.7   0.035       0
  7209.6   0.045       0  7331.9   0.035       0  8008.0    0.07       0
Bank Sta=4985,5007.4
Exp/Cntr=0.3,0.1

Type RM Length L Ch R = 1,21500,500,500,500
BEGIN DESCRIPTION:
Bull Creek 43.0
END DESCRIPTION:
XS GIS Cut Line= 3
      1336354.99      6921387.96      1336130.35      6920612.12
      1334959.56      6918247.16
#Sta/Elev= 30
  4192.3 2134.71  4473.3 2123.44  4733.6 2118.93  4796.1 2113.19  4894.2 2112.85
  4927.8 2110.91  4941.8 2108.25  4955.4 2102.25  4955.9 2101.75  4977.8 2102.25
  4999.5 2102.48  5022.3 2116.69  5064.8 2116.88  5072.8 2116.61  5089.6 2108.44
  5105.0 2105.56  5112.0 2110.28  5117.6 2107.79  5127.3 2115.57  5155.5 2114.80
  5246.6 2112.53  5252.2 2114.37  5313.9 2116.25  5633.5 2116.49  5796.8 2119.62
  5874.6 2118.20  6933.3 2121.29  7292.1 2126.91  7455.7 2132.88  7638.9 2143.69
#Mann=6,-1,0
  4192.3   0.035       0  4955.4   0.035       0  4977.8   0.035       0
  5064.8    0.07       0  5155.5   0.045       0  6933.3   0.035       0
Bank Sta=4955.4,4977.8
Exp/Cntr=0.3,0.1

Type RM Length L Ch R = 1,21000,500,500,500
BEGIN DESCRIPTION:
Bull Creek 42.0
END DESCRIPTION:
XS GIS Cut Line= 3
      1336527.72      6921634.49      1336528.66      6920715.99
      1335043.34      6918118.82
#Sta/Elev= 30
  4081.5 2136.56  4388.0 2129.11  4577.6 2122.39  4650.3 2120.35  4798.0 2117.59
  4918.0 2111.69  4948.0 2112.93  4959.0 2105.38  4966.8 2099.77  4967.3 2099.27
  4989.2 2099.77  5030.2 2101.88  5070.1 2103.40  5089.8 2105.03  5096.8 2109.85
  5102.6 2106.04  5112.6 2111.50  5118.4 2108.53  5124.4 2111.70  5140.0 2114.88
  5161.2 2116.16  5321.3 2113.89  5815.6 2114.85  5887.0 2116.93  6679.6 2117.06
  7260.5 2120.47  7697.8 2131.05  7896.4 2139.14  7939.6 2139.11  7991.9 2143.12
#Mann=11,-1,0
  4081.5   0.035       0  4577.6    0.07       0  4650.3   0.035       0
  4959.0    0.07       0  4966.8    0.07       0  4989.2    0.07       0
  5030.2   0.035       0  5070.1   0.045       0  5161.2    0.07       0
  5321.3   0.045       0  7260.5   0.035       0
Bank Sta=4966.8,4989.2
Exp/Cntr=0.3,0.1

Type RM Length L Ch R = 1,20500,500,500,500
BEGIN DESCRIPTION:
Bull Creek 41.0
END DESCRIPTION:
XS GIS Cut Line= 5
      1337369.76      6921300.28      1336695.00      6920295.46
      1336604.92      6920240.66      1336497.08      6920163.52
      1335043.32      6918249.00
#Sta/Elev= 30
  3684.2 2138.43  3850.1 2136.01  3994.6 2132.68  4445.8 2115.84  4601.7 2114.25
  4632.7 2114.13  4776.5 2114.48  4885.5 2114.25  4958.0 2108.40  4973.5 2099.95
  4976.9 2094.67  4977.4 2094.17  4999.4 2094.67  5000.0 2097.34  5003.0 2097.34
  5009.6 2106.60  5021.6 2106.99  5024.3 2107.53  5030.5 2102.47  5045.2 2101.44
  5060.0 2105.97  5066.1 2110.85  5087.0 2114.21  5159.9 2113.29  5538.1 2114.36
  5666.9 2117.10  6465.7 2117.18  6929.0 2120.31  7328.8 2129.52  7536.5 2139.16
#Mann=11,-1,0
  3684.2   0.035       0  3850.1    0.07       0  3994.6   0.035       0
  4601.7    0.07       0  4632.7   0.035       0  4776.5   0.045       0
  4976.9   0.045       0  4999.4   0.045       0  5021.6    0.07       0
  5159.9   0.045       0  6929.0   0.035       0
Bank Sta=4976.9,4999.4
Exp/Cntr=0.3,0.1

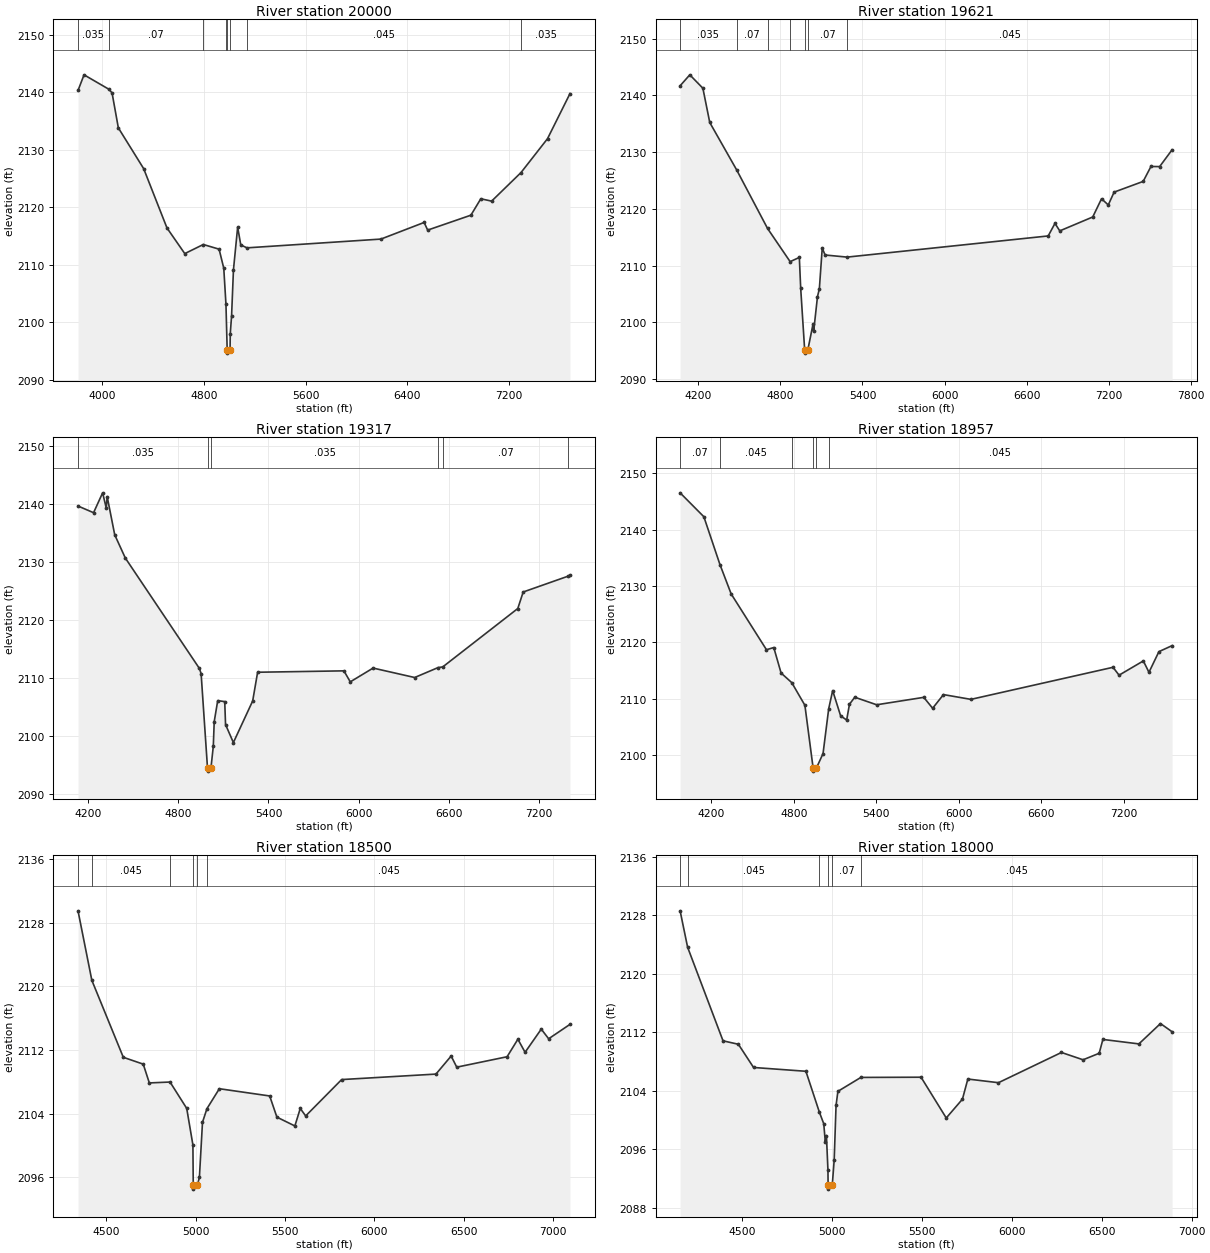
Type RM Length L Ch R = 1,20000,379,379,379
BEGIN DESCRIPTION:
Bull Creek 40.0
END DESCRIPTION:
XS GIS Cut Line= 5
      1337425.29      6921230.79      1336875.55      6920260.74
      1336911.15      6920194.60      1336938.05      6920104.49
      1335205.01      6918188.01
#Sta/Elev= 30
  3809.9 2140.28  3857.3 2143.00  4051.5 2140.51  4077.5 2139.87  4127.0 2133.79
  4326.1 2126.71  4509.4 2116.41  4649.3 2111.96  4794.9 2113.54  4919.1 2112.73
  4955.9 2109.42  4973.1 2103.15  4982.8 2095.18  4983.3 2094.68  5005.3 2095.18
  5006.9 2098.03  5017.3 2101.15  5032.0 2109.15  5065.1 2116.56  5089.6 2113.46
  5138.5 2112.96  6191.3 2114.48  6531.3 2117.37  6558.9 2116.04  6898.9 2118.63
  6976.8 2121.48  7061.8 2121.07  7293.2 2126.04  7501.2 2131.91  7677.9 2139.74
#Mann=8,-1,0
  3809.9   0.035       0  4051.5    0.07       0  4794.9   0.035       0
  4973.1    0.07       0  4982.8    0.07       0  5005.3    0.07       0
  5138.5   0.045       0  7293.2   0.035       0
Bank Sta=4982.8,5005.3
Exp/Cntr=0.3,0.1

Type RM Length L Ch R = 1,19621,304,304,304
BEGIN DESCRIPTION:
Bull Creek 39.5
END DESCRIPTION:
XS GIS Cut Line= 5
      1337424.51      6921201.26      1337255.45      6920381.35
      1337253.46      6920304.48      1337280.37      6920214.37
      1335547.30      6918297.86
#Sta/Elev= 30
  4068.7 2141.70  4139.5 2143.63  4234.9 2141.27  4285.2 2135.23  4481.7 2126.87
  4707.1 2116.56  4872.0 2110.71  4939.2 2111.45  4949.2 2105.98  4978.3 2095.09
  4978.8 2094.59  5000.8 2095.09  5038.5 2099.64  5043.7 2098.41  5071.7 2104.54
  5085.4 2105.93  5106.4 2113.10  5127.3 2111.88  5288.0 2111.51  6756.3 2115.24
  6805.6 2117.45  6840.7 2116.13  7081.4 2118.58  7145.6 2121.79  7194.9 2120.70
  7237.5 2122.96  7449.7 2124.85  7506.5 2127.48  7570.0 2127.46  7660.7 2130.42
#Mann=7,-1,0
  4068.7   0.035       0  4481.7    0.07       0  4707.1   0.035       0
  4872.0    0.07       0  4978.3    0.07       0  5000.8    0.07       0
  5288.0   0.045       0
Bank Sta=4978.3,5000.8
Exp/Cntr=0.3,0.1

Type RM Length L Ch R = 1,19317,360,360,360
BEGIN DESCRIPTION:
Bull Creek 39.0
END DESCRIPTION:
XS GIS Cut Line= 5
      1337439.17      6921230.85      1337536.40      6920362.74
      1337677.64      6920041.99      1337879.03      6919101.02
      1337154.97      6918287.97
#Sta/Elev= 30
  4132.3 2139.64  4235.8 2138.49  4296.2 2141.92  4320.4 2139.28  4326.4 2141.27
  4376.7 2134.67  4447.1 2130.67  4940.2 2111.61  4951.8 2110.71  4994.4 2094.38
  4994.9 2093.88  5017.1 2094.38  5032.9 2098.17  5039.0 2102.42  5062.3 2106.05
  5109.0 2105.88  5114.4 2101.92  5166.6 2098.81  5295.1 2106.00  5327.9 2110.95
  5902.4 2111.19  5944.7 2109.29  6096.7 2111.67  6373.4 2110.04  6528.8 2111.75
  6560.3 2111.87  7059.9 2121.95  7095.8 2124.80  7396.7 2127.55  7407.3 2127.69
#Mann=6,-1,0
  4132.3   0.035       0  4994.4   0.035       0  5017.1   0.035       0
  6528.8   0.045       0  6560.3    0.07       0  7396.7   0.035       0
Bank Sta=4994.4,5017.1
Exp/Cntr=0.3,0.1

Type RM Length L Ch R = 1,18957,457,457,457
BEGIN DESCRIPTION:
Bull Creek 38.0
END DESCRIPTION:
XS GIS Cut Line= 6
      1337522.49      6921258.62      1337858.19      6920329.38
      1337859.93      6920200.32      1337983.19      6919573.59
      1338146.39      6918829.38      1338371.21      6917793.73
#Sta/Elev= 30
  3973.7 2146.55  4146.4 2142.30  4263.5 2133.80  4345.1 2128.58  4601.7 2118.67
  4654.8 2119.06  4708.0 2114.53  4785.4 2112.83  4881.1 2108.80  4941.2 2097.60
  4941.7 2097.10  4963.9 2097.60  5013.1 2100.22  5054.3 2108.20  5083.1 2111.41
  5141.0 2106.92  5184.9 2106.18  5205.3 2108.99  5243.8 2110.23  5403.0 2108.89
  5745.5 2110.21  5810.0 2108.27  5888.8 2110.70  6088.3 2109.85  7121.7 2115.55
  7165.7 2114.15  7342.2 2116.68  7383.1 2114.66  7455.5 2118.33  7551.2 2119.40
#Mann=6,-1,0
  3973.7    0.07       0  4263.5   0.045       0  4785.4    0.07       0
  4941.2    0.07       0  4963.9    0.07       0  5054.3   0.045       0
Bank Sta=4941.2,4963.9
Exp/Cntr=0.3,0.1

Type RM Length L Ch R = 1,18500,500,500,500
BEGIN DESCRIPTION:
Bull Creek 37.0
END DESCRIPTION:
XS GIS Cut Line= 4
      1338155.00      6920788.00      1338262.71      6920138.06
      1338281.55      6920037.18      1338503.74      6918058.34
#Sta/Elev= 30
  4341.2 2129.48  4418.5 2120.75  4594.6 2111.07  4706.1 2110.21  4740.2 2107.85
  4856.1 2107.96  4949.4 2104.65  4984.1 2100.05  4986.0 2095.00  4986.5 2094.50
  5009.0 2095.00  5020.4 2095.98  5037.7 2102.90  5062.5 2104.61  5132.0 2107.12
  5413.7 2106.21  5454.0 2103.55  5554.6 2102.44  5584.8 2104.64  5615.0 2103.70
  5816.3 2108.27  6344.0 2108.96  6429.0 2111.23  6460.3 2109.83  6742.0 2111.14
  6802.4 2113.34  6842.7 2111.70  6933.2 2114.61  6974.6 2113.40  7093.9 2115.21
#Mann=6,-1,0
  4341.2    0.07       0  4418.5   0.045       0  4856.1    0.07       0
  4986.0    0.07       0  5009.0    0.07       0  5062.5   0.045       0
Bank Sta=4986,5009
Exp/Cntr=0.3,0.1

Type RM Length L Ch R = 1,18000,500,500,500
BEGIN DESCRIPTION:
Bull Creek 36.0
END DESCRIPTION:
XS GIS Cut Line= 5
      1338184.58      6920785.05      1338635.97      6920271.16
      1338730.32      6920138.23      1338707.64      6920050.01
      1338594.88      6918253.63
#Sta/Elev= 30
  4153.0 2128.60  4194.7 2123.63  4391.9 2110.84  4477.3 2110.37  4561.8 2107.20
  4853.1 2106.68  4928.0 2101.10  4952.5 2099.51  4961.1 2097.01  4967.3 2097.90
  4975.8 2093.17  4976.7 2091.08  4977.2 2090.58  4999.7 2091.08  5010.6 2094.60
  5020.9 2102.02  5031.2 2103.94  5159.0 2105.84  5493.9 2105.87  5634.2 2100.30
  5724.3 2102.87  5754.4 2105.62  5924.7 2105.12  6275.4 2109.25  6395.7 2108.25
  6485.4 2109.14  6505.9 2111.03  6706.3 2110.42  6826.5 2113.20  6891.0 2112.08
#Mann=6,-1,0
  4153.0    0.07       0  4194.7   0.045       0  4928.0    0.07       0
  4976.7    0.07       0  4999.7    0.07       0  5159.0   0.045       0
Bank Sta=4976.7,4999.7
Exp/Cntr=0.3,0.1

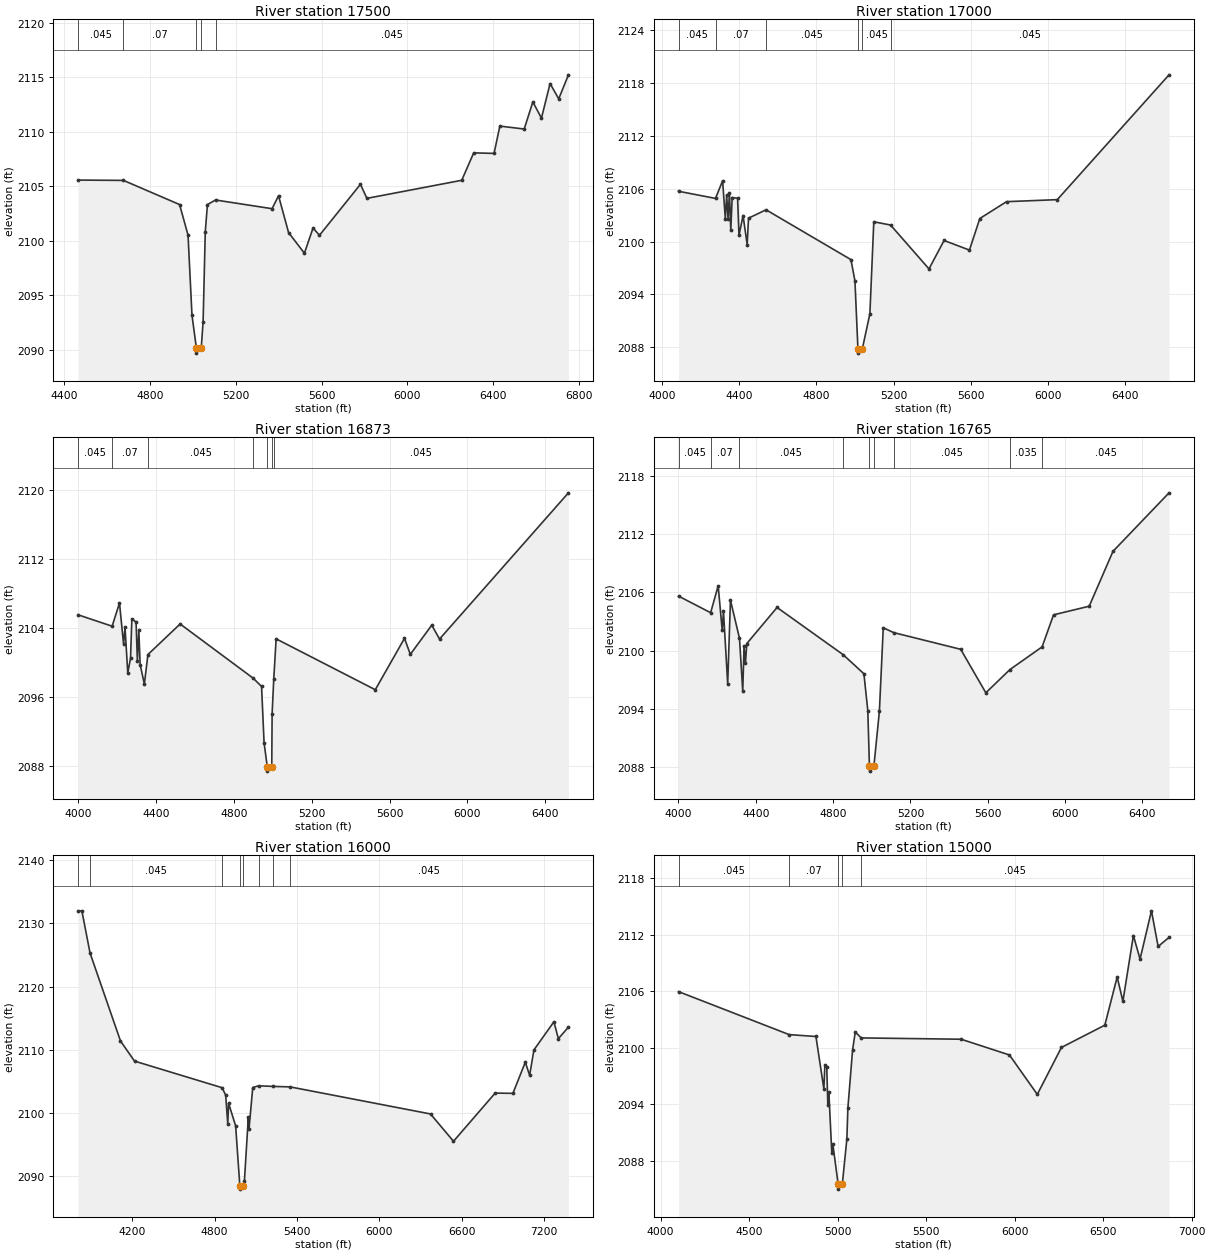
Type RM Length L Ch R = 1,17500,500,500,500
BEGIN DESCRIPTION:
Bull Creek 35.0
END DESCRIPTION:
XS GIS Cut Line= 4
      1338800.36      6920302.64      1339137.13      6919960.65
      1339136.41      6919906.53      1338994.21      6918162.81
#Sta/Elev= 30
  4465.9 2105.57  4677.9 2105.54  4939.1 2103.32  4978.5 2100.51  4996.8 2093.16
  5017.1 2090.17  5017.6 2089.67  5040.1 2090.17  5048.7 2092.57  5058.7 2100.80
  5068.8 2103.32  5106.4 2103.74  5369.7 2102.94  5399.8 2104.13  5446.5 2100.75
  5520.2 2098.85  5560.4 2101.16  5590.5 2100.50  5781.1 2105.18  5811.2 2103.89
  6252.7 2105.55  6308.5 2108.07  6403.2 2108.02  6430.2 2110.53  6543.6 2110.26
  6583.8 2112.75  6623.9 2111.26  6664.0 2114.44  6704.2 2113.03  6749.5 2115.24
#Mann=5,-1,0
  4465.9   0.045       0  4677.9    0.07       0  5017.1    0.07       0
  5040.1    0.07       0  5106.4   0.045       0
Bank Sta=5017.1,5040.1
Exp/Cntr=0.3,0.1

Type RM Length L Ch R = 1,17000,127,127,127
BEGIN DESCRIPTION:
Bull Creek 34.0
END DESCRIPTION:
XS GIS Cut Line= 4
      1338819.85      6920295.73      1339191.97      6919933.52
      1339557.81      6919784.55      1339311.03      6918175.57
#Sta/Elev= 30
  4085.7 2105.70  4277.3 2104.89  4314.1 2106.89  4328.2 2102.59  4335.2 2105.29
  4342.4 2102.57  4349.4 2105.53  4356.5 2101.26  4363.5 2104.99  4391.8 2104.90
  4399.0 2100.70  4420.1 2102.95  4441.4 2099.65  4448.4 2102.65  4539.2 2103.60
  4979.2 2097.95  5000.0 2095.54  5015.4 2087.85  5015.9 2087.35  5038.4 2087.85
  5077.4 2091.81  5097.7 2102.24  5184.7 2101.87  5383.7 2096.90  5461.9 2100.12
  5593.4 2099.03  5647.1 2102.61  5785.6 2104.52  6048.7 2104.75  6627.8 2118.90
#Mann=6,-1,0
  4085.7   0.045       0  4277.3    0.07       0  4539.2   0.045       0
  5015.4   0.045       0  5038.4   0.045       0  5184.7   0.045       0
Bank Sta=5015.4,5038.4
Exp/Cntr=0.3,0.1

Type RM Length L Ch R = 1,16873,108,108,108
BEGIN DESCRIPTION:
Bull Creek 33.6
END DESCRIPTION:
XS GIS Cut Line= 4
      1338831.77      6920286.14      1339232.12      6919923.75
      1339736.38      6919794.48      1339758.08      6918336.11
#Sta/Elev= 30
  3999.9 2105.52  4175.5 2104.19  4213.3 2106.89  4234.2 2102.12  4241.7 2104.05
  4255.8 2098.76  4270.0 2100.46  4276.8 2105.03  4298.4 2104.68  4305.2 2100.19
  4312.6 2103.71  4319.4 2099.73  4341.0 2097.48  4359.4 2100.90  4524.8 2104.45
  4899.8 2098.15  4943.0 2097.19  4955.8 2090.66  4972.3 2087.85  4972.8 2087.35
  4995.3 2087.85  4997.1 2093.98  5005.5 2098.04  5017.8 2102.72  5527.0 2096.81
  5677.0 2102.78  5707.0 2100.92  5817.0 2104.31  5857.0 2102.70  6519.0 2119.69
#Mann=7,-1,0
  3999.9   0.045       0  4175.5    0.07       0  4359.4   0.045       0
  4899.8    0.07       0  4972.3    0.07       0  4995.3    0.07       0
  5005.5   0.045       0
Bank Sta=4972.3,4995.3
Exp/Cntr=0.3,0.1

Type RM Length L Ch R = 1,16765,765,765,765
BEGIN DESCRIPTION:
Bull Creek 33.5a
END DESCRIPTION:
XS GIS Cut Line= 5
      1338839.63      6920281.28      1339244.05      6919929.18
      1339271.29      6919919.20      1339775.44      6919907.32
      1340096.62      6918475.01
#Sta/Elev= 30
  4000.5 2105.62  4166.6 2103.91  4205.5 2106.68  4226.4 2102.12  4233.0 2104.05
  4254.8 2096.58  4269.1 2105.20  4315.8 2101.27  4332.7 2095.81  4339.3 2100.45
  4346.9 2098.74  4353.6 2100.73  4510.2 2104.45  4852.5 2099.58  4959.5 2097.62
  4979.6 2093.83  4988.1 2088.09  4988.6 2087.59  5011.1 2088.09  5039.6 2093.77
  5059.6 2102.36  5113.6 2101.86  5460.2 2100.14  5590.2 2095.66  5714.6 2098.05
  5881.3 2100.39  5940.4 2103.69  6124.9 2104.58  6247.9 2110.23  6537.9 2116.26
#Mann=9,-1,0
  4000.5   0.045       0  4166.6    0.07       0  4315.8   0.045       0
  4852.5    0.07       0  4988.1    0.07       0  5011.1    0.07       0
  5113.6   0.045       0  5714.6   0.035       0  5881.3   0.045       0
Bank Sta=4988.1,5011.1
Exp/Cntr=0.3,0.1

Type RM Length L Ch R = 1,16000,1000,1000,1000
BEGIN DESCRIPTION:
Bull Creek 32.0
END DESCRIPTION:
XS GIS Cut Line= 4
      1338155.00      6920838.00      1339158.34      6920186.31
      1339740.72      6920267.57      1340270.11      6918557.88
#Sta/Elev= 30
  3803.6 2131.99  3832.3 2131.98  3891.9 2125.30  4113.6 2111.41  4215.8 2108.22
  4854.4 2104.01  4880.2 2102.83  4895.3 2098.28  4901.3 2101.55  4952.6 2097.99
  4983.5 2088.47  4984.0 2087.97  5006.6 2088.47  5016.8 2089.32  5045.2 2099.35
  5050.3 2097.51  5077.4 2104.04  5119.7 2104.31  5226.1 2104.22  5349.9 2104.14
  6372.7 2099.86  6540.2 2095.54  6843.8 2103.16  6973.2 2103.12  7063.6 2108.05
  7095.0 2105.97  7126.4 2109.99  7271.9 2114.44  7304.4 2111.77  7377.8 2113.60
#Mann=8,-1,0
  3803.6    0.07       0  3891.9   0.045       0  4854.4    0.07       0
  4983.5    0.07       0  5006.6    0.07       0  5119.7   0.045       0
  5226.1    0.07       0  5349.9   0.045       0
Bank Sta=4983.5,5006.6
Exp/Cntr=0.3,0.1

Type RM Length L Ch R = 1,15000,500,500,500
BEGIN DESCRIPTION:
Bull Creek 30.0
END DESCRIPTION:
XS GIS Cut Line= 3
      1339404.98      6921238.04      1339804.22      6920433.34
      1340370.04      6918648.69
#Sta/Elev= 30
  4101.7 2105.96  4726.6 2101.40  4877.8 2101.20  4922.6 2095.64  4928.2 2098.13
  4939.0 2097.93  4945.0 2093.90  4950.6 2095.33  4967.4 2088.85  4973.0 2089.82
  5003.4 2085.51  5003.9 2085.01  5026.6 2085.51  5052.5 2090.32  5058.1 2093.57
  5084.8 2099.78  5100.0 2101.68  5133.2 2101.05  5698.0 2100.91  5970.7 2099.24
  6128.1 2095.06  6264.5 2100.04  6509.5 2102.40  6579.3 2107.51  6611.6 2104.93
  6670.9 2111.91  6708.5 2109.41  6773.0 2114.53  6810.6 2110.75  6872.2 2111.71
#Mann=5,-1,0
  4101.7   0.045       0  4726.6    0.07       0  5003.4    0.07       0
  5026.6    0.07       0  5133.2   0.045       0
Bank Sta=5003.4,5026.6
Exp/Cntr=0.3,0.1

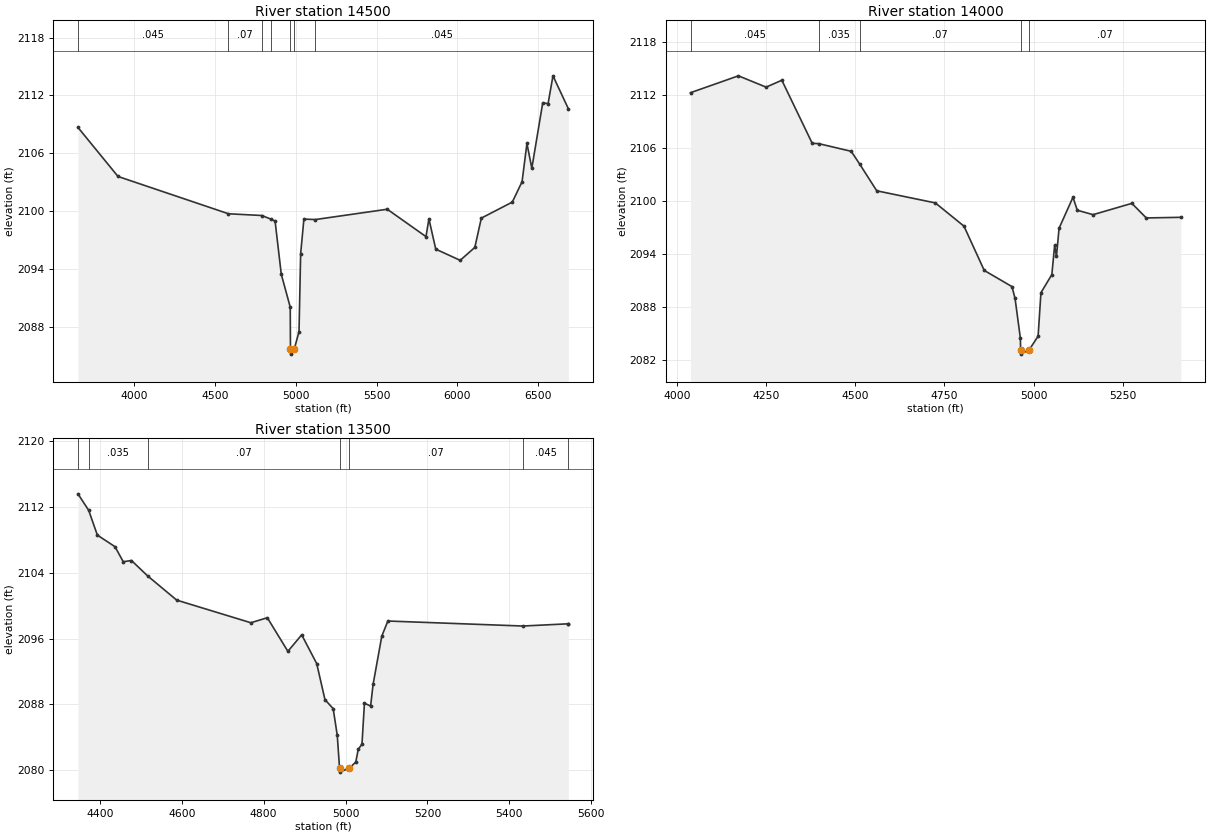
Type RM Length L Ch R = 1,14500,500,500,500
BEGIN DESCRIPTION:
Bull Creek 29.0
END DESCRIPTION:
XS GIS Cut Line= 4
      1339771.21      6921650.28      1340240.59      6920388.66
      1340234.15      6920316.15      1340417.80      6918713.74
#Sta/Elev= 30
  3653.9 2108.69  3901.7 2103.60  4584.7 2099.73  4791.3 2099.55  4845.8 2099.18
  4872.7 2098.98  4911.1 2093.45  4966.5 2090.04  4967.8 2085.67  4968.3 2085.17
  4991.0 2085.67  5020.7 2087.50  5030.8 2095.58  5050.9 2099.18  5121.5 2099.13
  5566.3 2100.20  5805.7 2097.36  5823.8 2099.20  5866.1 2096.06  6017.1 2094.90
  6107.7 2096.24  6147.9 2099.28  6339.2 2100.94  6399.6 2103.05  6429.8 2107.02
  6460.0 2104.45  6527.4 2111.23  6560.6 2111.16  6590.8 2114.04  6685.7 2110.63
#Mann=7,-1,0
  3653.9   0.045       0  4584.7    0.07       0  4791.3   0.045       0
  4845.8    0.07       0  4967.8    0.07       0  4991.0    0.07       0
  5121.5   0.045       0
Bank Sta=4967.8,4991
Exp/Cntr=0.3,0.1

Type RM Length L Ch R = 1,14000,500,500,500
BEGIN DESCRIPTION:
Bull Creek 28.0
END DESCRIPTION:
XS GIS Cut Line= 3
      1341239.94      6921228.36      1340691.84      6920437.90
      1340612.24      6920033.05
#Sta/Elev= 30
  4038.1 2112.30  4172.4 2114.21  4250.0 2112.93  4294.1 2113.71  4379.3 2106.57
  4397.0 2106.54  4488.5 2105.67  4512.0 2104.24  4560.1 2101.20  4724.3 2099.83
  4804.6 2097.20  4861.4 2092.19  4939.1 2090.36  4947.8 2089.02  4962.7 2084.51
  4963.4 2083.22  4963.9 2082.72  4987.6 2083.22  5012.4 2084.75  5020.3 2089.67
  5050.9 2091.72  5058.7 2095.02  5063.8 2093.80  5071.2 2096.97  5110.1 2100.47
  5122.2 2099.00  5166.5 2098.50  5275.1 2099.78  5315.6 2098.13  5412.6 2098.20
#Mann=5,-1,0
  4038.1   0.045       0  4397.0   0.035       0  4512.0    0.07       0
  4963.4    0.07       0  4987.6    0.07       0
Bank Sta=4963.4,4987.6
Exp/Cntr=0.3,0.1

Type RM Length L Ch R = 1,13500,500,500,500
BEGIN DESCRIPTION:
Bull Creek 27.0
END DESCRIPTION:
XS GIS Cut Line= 3
      1341205.00      6920938.01      1341139.04      6920287.95
      1340684.19      6919989.73
#Sta/Elev= 30
  4346.6 2113.62  4372.9 2111.61  4394.0 2108.60  4437.1 2107.19  4457.2 2105.36
  4477.3 2105.51  4516.9 2103.63  4587.8 2100.69  4768.8 2097.94  4809.0 2098.55
  4859.2 2094.46  4892.9 2096.47  4929.6 2092.97  4949.7 2088.59  4969.8 2087.49
  4979.8 2084.23  4985.3 2080.27  4985.8 2079.77  5009.6 2080.27  5025.0 2081.00
  5031.0 2082.54  5040.1 2083.18  5046.1 2088.15  5061.2 2087.81  5067.2 2090.43
  5088.5 2096.31  5103.3 2098.15  5432.9 2097.54  5543.4 2097.81  5543.9 2097.81
#Mann=7,-1,0
  4346.6   0.045       0  4372.9   0.035       0  4516.9    0.07       0
  4985.3    0.07       0  5009.6    0.07       0  5432.9   0.045       0
  5543.4    0.07       0
Bank Sta=4985.3,5009.6
Exp/Cntr=0.3,0.1