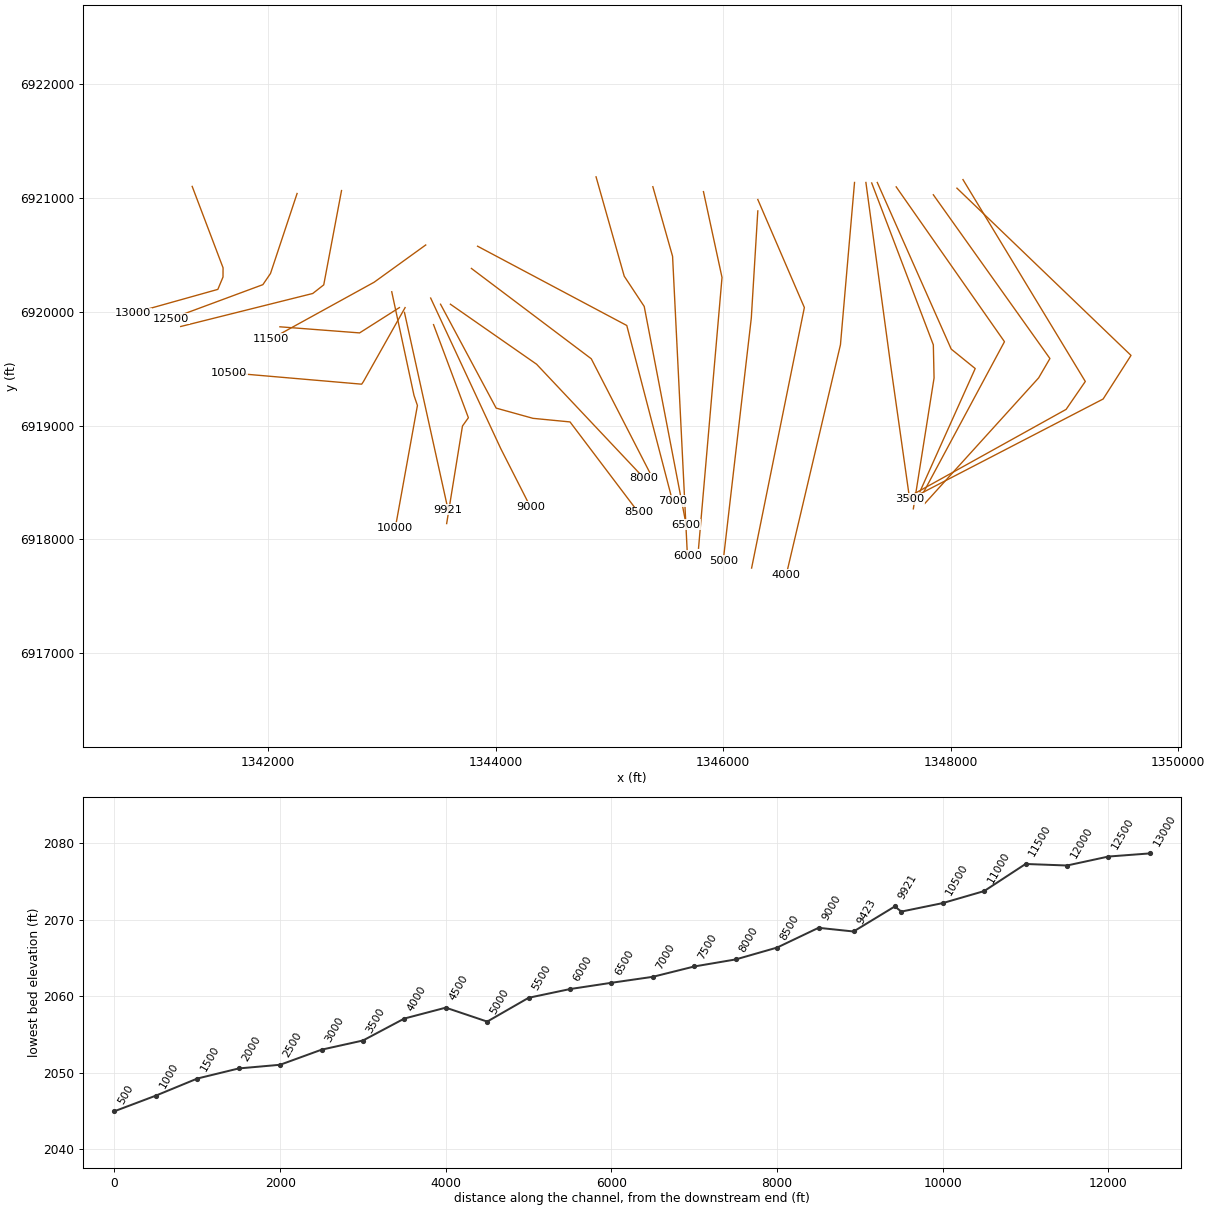
HEC-RAS study Bull Creek.prj: Bull Creek Base Level Engineering

--- Bull Creek.g01 (geometry) --- (continued)

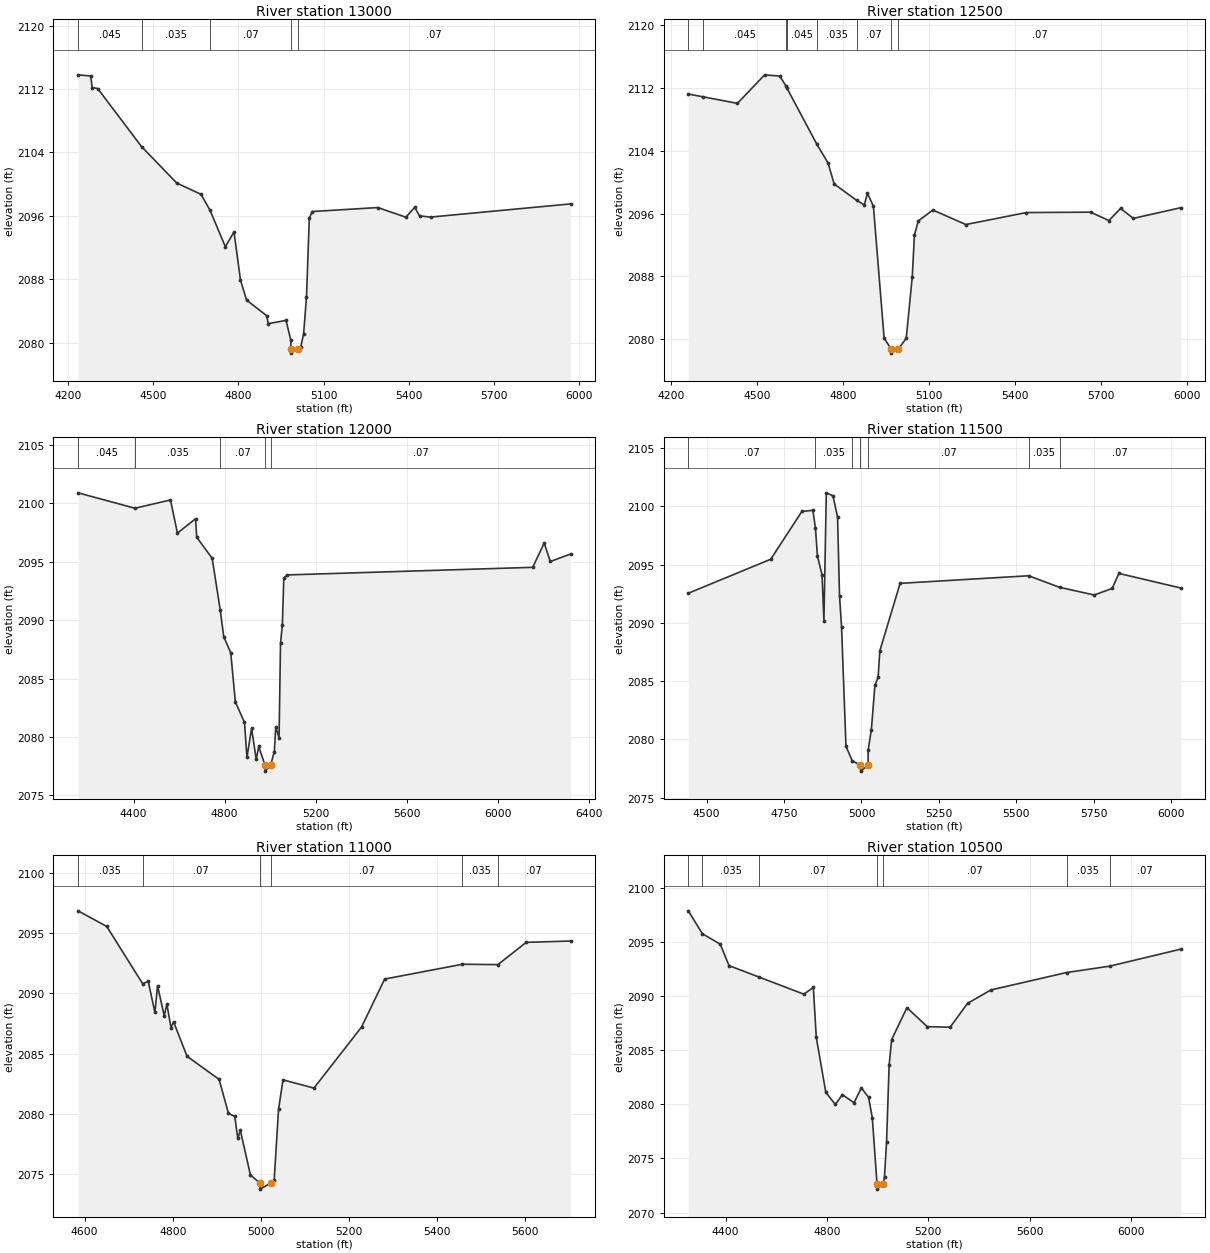
Type RM Length L Ch R = 1,13000,500,500,500
BEGIN DESCRIPTION:
Bull Creek 26.0
END DESCRIPTION:
XS GIS Cut Line= 5
      1341333.73      6921103.35      1341605.04      6920387.76
      1341604.55      6920306.52      1341559.17      6920198.04
      1340816.15      6919989.72
#Sta/Elev= 30
  4234.7 2113.78  4279.2 2113.63  4284.6 2112.18  4304.0 2112.05  4458.6 2104.72
  4582.7 2100.12  4668.2 2098.70  4700.0 2096.68  4753.8 2092.09  4784.4 2093.95
  4807.2 2087.88  4828.6 2085.36  4899.6 2083.38  4905.0 2082.38  4967.7 2082.79
  4984.7 2080.29  4985.0 2079.16  4985.5 2078.66  5009.3 2079.16  5019.8 2079.46
  5029.8 2081.13  5039.8 2085.71  5049.8 2095.68  5059.8 2096.53  5291.5 2097.03
  5390.1 2095.81  5421.3 2097.06  5438.3 2095.98  5477.6 2095.83  5970.5 2097.49
#Mann=5,-1,0
  4234.7   0.045       0  4458.6   0.035       0  4700.0    0.07       0
  4985.0    0.07       0  5009.3    0.07       0
Bank Sta=4985,5009.3
Exp/Cntr=0.3,0.1

Type RM Length L Ch R = 1,12500,500,500,500
BEGIN DESCRIPTION:
Bull Creek 25.0
END DESCRIPTION:
XS GIS Cut Line= 4
      1342255.60      6921040.93      1342022.05      6920337.91
      1341955.00      6920239.71      1341149.75      6919941.21
#Sta/Elev= 30
  4259.2 2111.19  4310.1 2110.84  4430.6 2110.00  4525.6 2113.63  4578.4 2113.47
  4600.7 2112.18  4603.2 2111.95  4707.3 2104.84  4747.0 2102.41  4768.1 2099.76
  4846.3 2097.68  4873.5 2097.09  4884.4 2098.58  4905.1 2096.94  4942.5 2080.16
  4967.3 2078.75  4967.8 2078.25  4991.6 2078.75  5019.7 2080.13  5040.7 2087.94
  5048.3 2093.24  5061.7 2095.05  5112.5 2096.44  5227.7 2094.60  5438.9 2096.12
  5662.8 2096.17  5726.8 2095.11  5767.6 2096.64  5812.1 2095.38  5977.7 2096.74
#Mann=8,-1,0
  4259.2   0.035       0  4310.1   0.045       0  4600.7    0.07       0
  4603.2   0.045       0  4707.3   0.035       0  4846.3    0.07       0
  4967.3    0.07       0  4991.6    0.07       0
Bank Sta=4967.3,4991.6
Exp/Cntr=0.3,0.1

Type RM Length L Ch R = 1,12000,500,500,500
BEGIN DESCRIPTION:
Bull Creek 24.0
END DESCRIPTION:
XS GIS Cut Line= 4
      1342646.21      6921066.92      1342489.92      6920237.72
      1342393.49      6920162.05      1341232.74      6919871.64
#Sta/Elev= 30
  4156.2 2100.91  4406.3 2099.59  4562.1 2100.30  4592.7 2097.46  4672.3 2098.69
  4677.4 2097.11  4745.3 2095.30  4780.6 2090.88  4796.2 2088.58  4826.7 2087.23
  4847.1 2083.01  4887.1 2081.25  4898.0 2078.26  4918.3 2080.75  4938.7 2078.09
  4949.8 2079.19  4977.4 2077.58  4977.9 2077.08  5001.7 2077.58  5018.2 2078.75
  5024.6 2080.87  5039.0 2079.94  5045.4 2088.01  5053.5 2089.63  5059.8 2093.60
  5074.3 2093.88  6152.8 2094.53  6203.4 2096.61  6230.1 2095.03  6319.1 2095.67
#Mann=5,-1,0
  4156.2   0.045       0  4406.3   0.035       0  4780.6    0.07       0
  4977.4    0.07       0  5001.7    0.07       0
Bank Sta=4977.4,5001.7
Exp/Cntr=0.3,0.1

Type RM Length L Ch R = 1,11500,500,500,500
BEGIN DESCRIPTION:
Bull Creek 23.0
END DESCRIPTION:
XS GIS Cut Line= 3
      1343386.26      6920588.47      1342932.98      6920261.16
      1342029.98      6919763.83
#Sta/Elev= 30
  4440.9 2092.55  4707.1 2095.47  4807.6 2099.57  4843.2 2099.67  4851.4 2098.14
  4857.9 2095.75  4872.6 2094.14  4878.8 2090.19  4886.5 2101.17  4908.2 2100.91
  4922.9 2099.07  4929.1 2092.35  4935.8 2089.61  4950.0 2079.41  4970.2 2078.17
  4996.8 2077.78  4997.3 2077.28  5021.4 2077.78  5021.6 2079.09  5031.9 2080.82
  5043.4 2084.64  5053.7 2085.33  5059.4 2087.62  5124.8 2093.40  5539.5 2094.05
  5639.4 2093.06  5751.2 2092.40  5809.3 2092.96  5831.1 2094.25  6030.9 2093.00
#Mann=7,-1,0
  4440.9    0.07       0  4851.4   0.035       0  4970.2    0.07       0
  4996.8    0.07       0  5021.4    0.07       0  5539.5   0.035       0
  5639.4    0.07       0
Bank Sta=4996.8,5021.4
Exp/Cntr=0.3,0.1

Type RM Length L Ch R = 1,11000,500,500,500
BEGIN DESCRIPTION:
Bull Creek 22.0
END DESCRIPTION:
XS GIS Cut Line= 3
      1343155.01      6920038.01      1342805.02      6919815.37
      1342104.57      6919869.02
#Sta/Elev= 30
  4585.2 2096.87  4650.4 2095.57  4731.8 2090.81  4744.4 2091.01  4759.6 2088.43
  4765.6 2090.64  4780.8 2088.14  4786.7 2089.13  4796.0 2087.17  4802.0 2087.64
  4832.5 2084.78  4905.2 2082.86  4926.4 2080.04  4940.8 2079.78  4947.6 2077.96
  4953.5 2078.62  4976.3 2074.91  4997.8 2074.24  4998.3 2073.74  5022.4 2074.24
  5030.1 2074.46  5040.1 2080.38  5050.2 2082.82  5120.4 2082.14  5228.3 2087.21
  5280.8 2091.20  5457.2 2092.43  5537.8 2092.40  5601.8 2094.25  5702.5 2094.36
#Mann=6,-1,0
  4585.2   0.035       0  4731.8    0.07       0  4997.8    0.07       0
  5022.4    0.07       0  5457.2   0.035       0  5537.8    0.07       0
Bank Sta=4997.8,5022.4
Exp/Cntr=0.3,0.1

Type RM Length L Ch R = 1,10500,500,500,500
BEGIN DESCRIPTION:
Bull Creek 21.0
END DESCRIPTION:
XS GIS Cut Line= 4
      1343205.01      6920038.02      1342838.44      6919386.81
      1342823.22      6919364.56      1341658.30      6919465.06
#Sta/Elev= 30
  4252.7 2097.88  4308.6 2095.76  4379.0 2094.80  4413.4 2092.82  4529.8 2091.78
  4708.7 2090.18  4746.2 2090.80  4757.8 2086.19  4795.4 2081.11  4833.0 2079.99
  4860.9 2080.90  4906.8 2080.15  4935.6 2081.52  4964.2 2080.65  4978.9 2078.75
  4997.4 2072.67  4997.9 2072.17  5022.1 2072.67  5027.0 2073.33  5035.2 2076.56
  5045.2 2083.60  5055.3 2085.99  5115.5 2088.93  5195.8 2087.18  5286.1 2087.13
  5354.6 2089.33  5446.7 2090.57  5745.5 2092.18  5916.1 2092.77  6196.2 2094.34
#Mann=7,-1,0
  4252.7    0.07       0  4308.6   0.035       0  4529.8    0.07       0
  4997.4    0.07       0  5022.1    0.07       0  5745.5   0.035       0
  5916.1    0.07       0
Bank Sta=4997.4,5022.1
Exp/Cntr=0.3,0.1

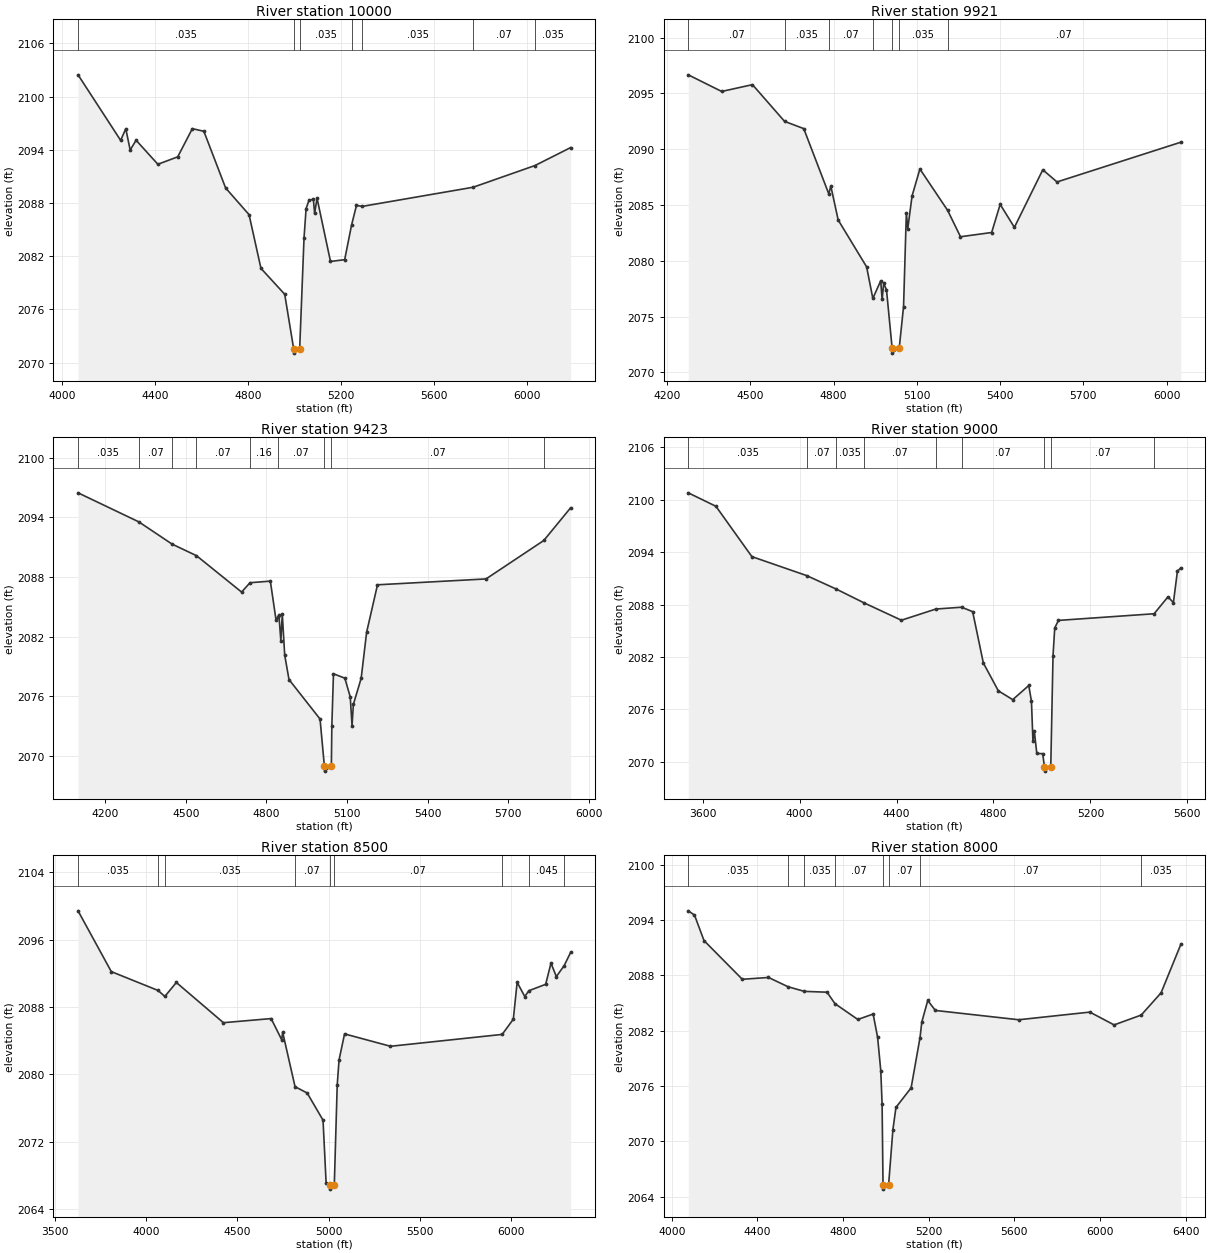
Type RM Length L Ch R = 1,10000,79,79,79
BEGIN DESCRIPTION:
Bull Creek 20.0
END DESCRIPTION:
XS GIS Cut Line= 4
      1343087.62      6920177.16      1343283.17      6919265.81
      1343313.31      6919177.15      1343119.08      6918101.90
#Sta/Elev= 30
  4067.9 2102.45  4251.1 2095.06  4273.3 2096.37  4292.1 2093.97  4317.6 2095.07
  4411.3 2092.36  4496.6 2093.20  4559.5 2096.38  4609.1 2096.08  4702.6 2089.69
  4803.4 2086.68  4854.6 2080.62  4956.8 2077.70  4995.2 2071.56  4995.7 2071.06
  5021.2 2071.56  5039.9 2084.07  5048.8 2087.37  5061.1 2088.29  5080.1 2088.42
  5085.4 2086.81  5095.8 2088.54  5153.7 2081.40  5214.7 2081.60  5244.2 2085.49
  5265.5 2087.73  5290.0 2087.61  5767.2 2089.77  6033.3 2092.22  6186.3 2094.24
#Mann=7,-1,0
  4067.9   0.035       0  4995.2   0.035       0  5021.2   0.035       0
  5244.2    0.07       0  5290.0   0.035       0  5767.2    0.07       0
  6033.3   0.035       0
Bank Sta=4995.2,5021.2
Exp/Cntr=0.3,0.1

Type RM Length L Ch R = 1,9921,498,498,498
BEGIN DESCRIPTION:
Bull Creek 19.5
END DESCRIPTION:
XS GIS Cut Line= 2
      1343199.36      6919995.62      1343582.28      6918262.42
#Sta/Elev= 30
  4276.1 2096.67  4396.6 2095.18  4507.5 2095.79  4623.2 2092.50  4692.3 2091.85
  4782.4 2086.01  4789.9 2086.70  4816.4 2083.66  4918.9 2079.46  4941.3 2076.63
  4969.7 2078.21  4974.8 2076.54  4980.3 2077.98  4990.5 2077.41  5010.6 2072.23
  5011.1 2071.73  5036.6 2072.23  5052.0 2075.90  5062.1 2084.29  5067.2 2082.89
  5082.7 2085.82  5110.9 2088.23  5210.7 2084.53  5257.2 2082.16  5369.5 2082.54
  5400.2 2085.06  5451.4 2083.00  5553.8 2088.16  5605.0 2087.07  6051.1 2090.63
#Mann=7,-1,0
  4276.1    0.07       0  4623.2   0.035       0  4782.4    0.07       0
  4941.3   0.035       0  5010.6   0.035       0  5036.6   0.035       0
  5210.7    0.07       0
Bank Sta=5010.6,5036.6
Exp/Cntr=0.3,0.1

Type RM Length L Ch R = 1,9423,423,423,423
BEGIN DESCRIPTION:
Bull Creek 19.0
END DESCRIPTION:
XS GIS Cut Line= 4
      1343455.00      6919888.01      1343761.23      6919069.51
      1343709.15      6918996.59      1343570.26      6918138.98
#Sta/Elev= 30
  4099.4 2096.45  4325.5 2093.53  4449.4 2091.29  4540.0 2090.13  4707.8 2086.47
  4739.2 2087.41  4814.8 2087.57  4836.1 2083.63  4842.7 2083.94  4846.8 2084.13
  4853.9 2081.55  4859.2 2084.27  4868.2 2080.13  4884.2 2077.67  4999.7 2073.70
  5015.8 2068.96  5016.3 2068.46  5041.8 2068.96  5043.5 2072.96  5049.6 2078.25
  5091.9 2077.81  5112.1 2075.92  5118.7 2073.04  5123.7 2075.17  5152.7 2077.80
  5172.9 2082.42  5213.4 2087.20  5617.1 2087.79  5832.2 2091.66  5931.7 2094.94
#Mann=9,-1,0
  4099.4   0.035       0  4325.5    0.07       0  4449.4   0.035       0
  4540.0    0.07       0  4739.2    0.16       0  4842.7    0.07       0
  5015.8    0.07       0  5041.8    0.07       0  5832.2   0.035       0
Bank Sta=5015.8,5041.8
Exp/Cntr=0.3,0.1

Type RM Length L Ch R = 1,9000,500,500,500
BEGIN DESCRIPTION:
Bull Creek 18.0
END DESCRIPTION:
XS GIS Cut Line= 3
      1343429.62      6920121.89      1344045.42      6918798.77
      1344304.98      6918288.04
#Sta/Elev= 30
  3540.6 2100.79  3654.8 2099.25  3803.1 2093.49  4029.0 2091.32  4151.6 2089.77
  4265.7 2088.20  4420.1 2086.21  4562.0 2087.49  4668.6 2087.70  4714.1 2087.19
  4758.2 2081.32  4820.1 2078.13  4879.5 2077.12  4945.7 2078.74  4956.7 2076.94
  4962.9 2072.37  4968.4 2073.56  4978.8 2070.96  5003.2 2070.94  5010.2 2069.44
  5010.7 2068.94  5036.4 2069.44  5045.7 2082.15  5052.8 2085.33  5068.2 2086.19
  5462.8 2086.95  5520.1 2088.89  5542.4 2088.22  5559.0 2091.82  5572.9 2092.19
#Mann=9,-1,0
  3540.6   0.035       0  4029.0    0.07       0  4151.6   0.035       0
  4265.7    0.07       0  4562.0    0.16       0  4668.6    0.07       0
  5010.2    0.07       0  5036.4    0.07       0  5462.8   0.035       0
Bank Sta=5010.2,5036.4
Exp/Cntr=0.3,0.1

Type RM Length L Ch R = 1,8500,500,500,500
BEGIN DESCRIPTION:
Bull Creek 17.0
END DESCRIPTION:
XS GIS Cut Line= 5
      1343516.43      6920067.61      1344005.16      6919154.23
      1344328.78      6919064.28      1344654.47      6919032.70
      1345254.99      6918238.01
#Sta/Elev= 30
  3628.2 2099.42  3810.1 2092.20  4066.1 2089.96  4103.2 2089.25  4166.1 2090.91
  4423.7 2086.13  4684.7 2086.62  4742.6 2084.11  4747.8 2085.00  4815.6 2078.53
  4881.9 2077.78  4968.8 2074.55  4985.7 2067.08  5004.2 2066.86  5004.7 2066.36
  5030.4 2066.86  5046.4 2078.74  5056.5 2081.72  5086.6 2084.80  5337.9 2083.33
  5949.0 2084.74  6010.0 2086.55  6030.9 2090.93  6072.6 2089.24  6095.2 2089.93
  6187.0 2090.69  6216.1 2093.21  6245.3 2091.61  6288.0 2092.90  6323.3 2094.47
#Mann=9,-1,0
  3628.2   0.035       0  4066.1    0.07       0  4103.2   0.035       0
  4815.6    0.07       0  5004.2    0.07       0  5030.4    0.07       0
  5949.0   0.035       0  6095.2   0.045       0  6288.0    0.07       0
Bank Sta=5004.2,5030.4
Exp/Cntr=0.3,0.1

Type RM Length L Ch R = 1,8000,500,500,500
BEGIN DESCRIPTION:
Bull Creek 16.0
END DESCRIPTION:
XS GIS Cut Line= 3
      1343603.21      6920067.62      1344360.48      6919540.10
      1345305.02      6918537.98
#Sta/Elev= 30
  4077.1 2095.01  4106.2 2094.55  4150.7 2091.78  4329.6 2087.58  4451.8 2087.78
  4543.2 2086.77  4619.2 2086.27  4725.2 2086.18  4762.0 2084.94  4868.9 2083.22
  4940.5 2083.81  4961.4 2081.27  4976.2 2077.65  4982.3 2074.01  4986.6 2065.31
  4987.1 2064.81  5012.8 2065.31  5032.8 2071.27  5047.0 2073.68  5117.8 2075.80
  5159.4 2081.25  5167.6 2082.93  5195.5 2085.28  5231.1 2084.20  5620.3 2083.19
  5952.5 2084.02  6065.7 2082.63  6192.3 2083.70  6285.0 2086.11  6377.1 2091.36
#Mann=8,-1,0
  4077.1   0.035       0  4543.2    0.07       0  4619.2   0.035       0
  4762.0    0.07       0  4986.6   0.035       0  5012.8    0.07       0
  5159.4    0.07       0  6192.3   0.035       0
Bank Sta=4986.6,5012.8
Exp/Cntr=0.3,0.1

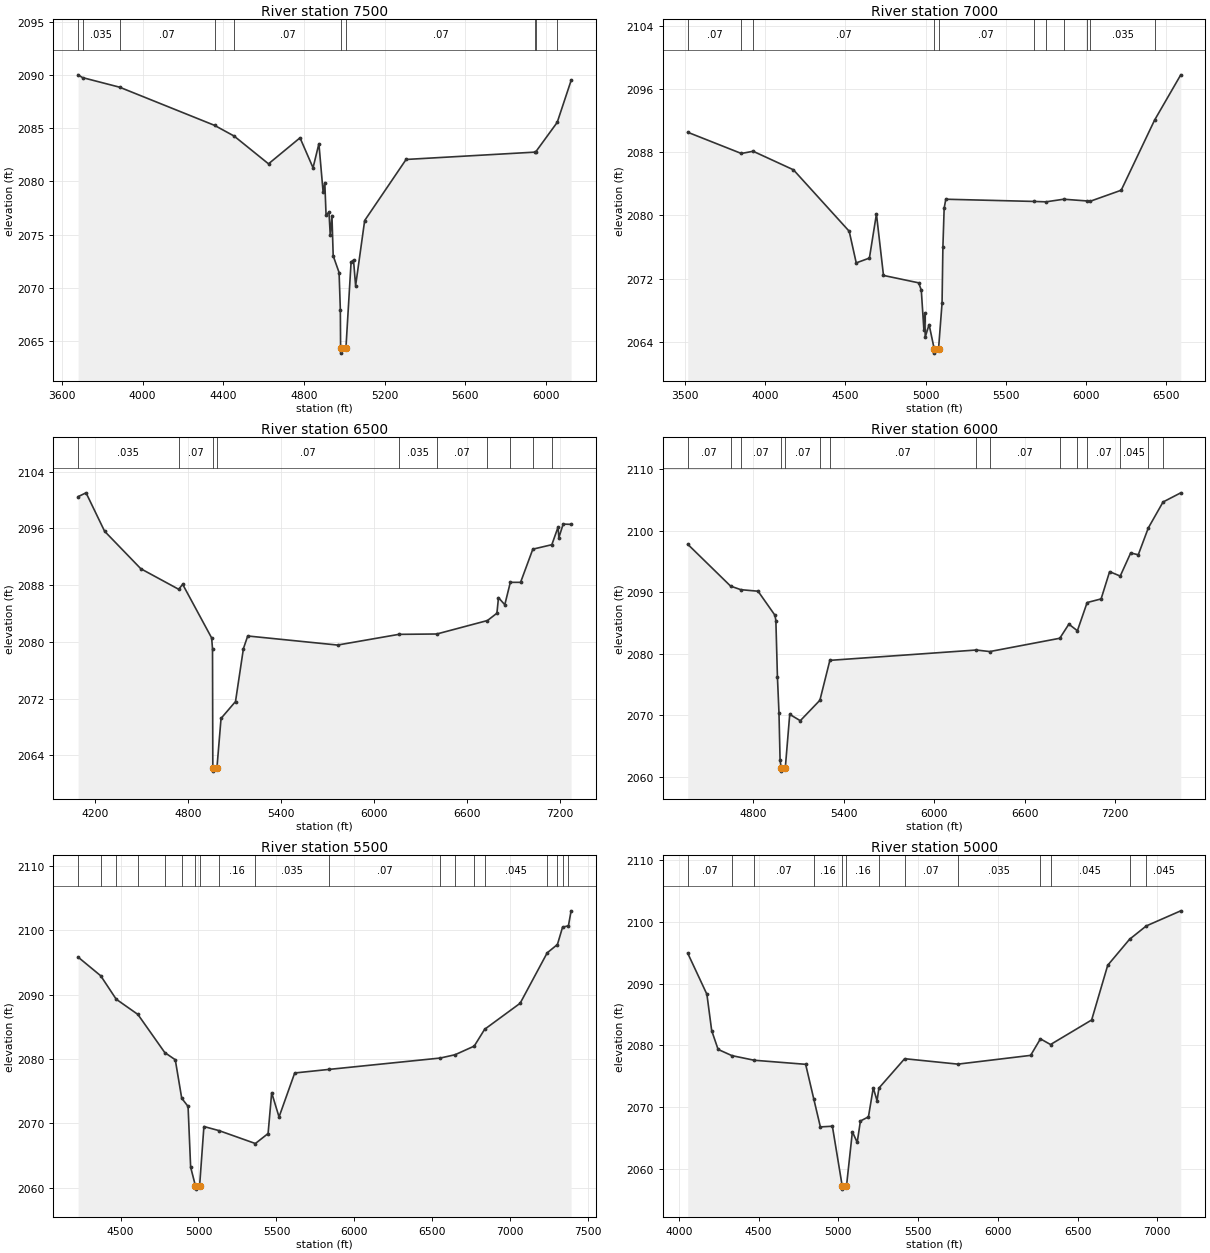
Type RM Length L Ch R = 1,7500,500,500,500
BEGIN DESCRIPTION:
Bull Creek 15.0
END DESCRIPTION:
XS GIS Cut Line= 3
      1343787.69      6920382.28      1344841.31      6919587.94
      1345355.01      6918587.98
#Sta/Elev= 30
  3680.5 2090.00  3702.5 2089.74  3886.3 2088.84  4356.8 2085.26  4453.6 2084.26
  4624.4 2081.65  4780.6 2084.09  4845.1 2081.28  4874.2 2083.54  4895.1 2078.98
  4903.4 2079.89  4909.6 2076.86  4924.2 2077.11  4930.4 2074.96  4938.8 2076.80
  4945.0 2073.02  4974.2 2071.45  4980.4 2067.98  4981.7 2064.39  4982.2 2063.89
  5008.2 2064.39  5033.7 2072.44  5045.7 2072.62  5056.1 2070.21  5101.0 2076.33
  5306.3 2082.06  5946.8 2082.75  5949.6 2082.79  6055.3 2085.54  6124.2 2089.47
#Mann=10,-1,0
  3680.5    0.07       0  3702.5   0.035       0  3886.3    0.07       0
  4356.8   0.035       0  4453.6    0.07       0  4981.7    0.07       0
  5008.2    0.07       0  5946.8   0.035       0  5949.6    0.07       0
  6055.3   0.035       0
Bank Sta=4981.7,5008.2
Exp/Cntr=0.3,0.1

Type RM Length L Ch R = 1,7000,500,500,500
BEGIN DESCRIPTION:
Bull Creek 14.0
END DESCRIPTION:
XS GIS Cut Line= 3
      1343841.92      6920577.60      1345153.38      6919880.54
      1345555.01      6918337.97
#Sta/Elev= 30
  3514.8 2090.54  3849.6 2087.85  3923.3 2088.13  4175.1 2085.78  4523.3 2077.99
  4567.2 2073.98  4649.5 2074.59  4693.4 2080.18  4737.4 2072.39  4957.2 2071.45
  4973.5 2070.53  4989.8 2065.47  4995.5 2067.61  4998.1 2064.58  5022.2 2066.16
  5054.6 2063.04  5055.1 2062.54  5081.1 2063.04  5103.2 2068.88  5108.4 2075.95
  5116.3 2080.91  5126.6 2082.05  5676.2 2081.77  5752.3 2081.72  5862.7 2082.05
  6009.5 2081.83  6029.5 2081.80  6222.0 2083.19  6430.5 2092.08  6594.0 2097.82
#Mann=11,-1,0
  3514.8    0.07       0  3849.6   0.035       0  3923.3    0.07       0
  5054.6    0.07       0  5081.1    0.07       0  5676.2   0.035       0
  5752.3    0.07       0  5862.7   0.035       0  6009.5    0.07       0
  6029.5   0.035       0  6430.5   0.045       0
Bank Sta=5054.6,5081.1
Exp/Cntr=0.3,0.1

Type RM Length L Ch R = 1,6500,500,500,500
BEGIN DESCRIPTION:
Bull Creek 13.0
END DESCRIPTION:
XS GIS Cut Line= 4
      1344883.28      6921187.55      1345130.90      6920314.07
      1345306.45      6920048.25      1345675.37      6918127.72
#Sta/Elev= 30
  4092.1 2100.49  4143.6 2101.03  4263.3 2095.61  4497.0 2090.32  4741.5 2087.42
  4767.2 2088.12  4954.3 2080.55  4959.8 2079.01  4961.8 2062.26  4962.3 2061.76
  4988.5 2062.26  5014.9 2069.20  5108.2 2071.58  5159.4 2079.06  5187.0 2080.83
  5766.9 2079.55  6162.6 2081.06  6407.3 2081.11  6734.2 2083.01  6795.3 2084.04
  6805.5 2086.24  6846.2 2085.24  6881.9 2088.40  6948.1 2088.40  7027.1 2093.08
  7149.8 2093.71  7190.1 2096.20  7195.1 2094.70  7223.0 2096.62  7274.2 2096.58
#Mann=10,-1,0
  4092.1   0.035       0  4741.5    0.07       0  4961.8    0.07       0
  4988.5    0.07       0  6162.6   0.035       0  6407.3    0.07       0
  6734.2   0.035       0  6881.9   0.045       0  7027.1    0.07       0
  7149.8   0.045       0
Bank Sta=4961.8,4988.5
Exp/Cntr=0.3,0.1

Type RM Length L Ch R = 1,6000,500,500,500
BEGIN DESCRIPTION:
Bull Creek 12.0
END DESCRIPTION:
XS GIS Cut Line= 3
      1345382.42      6921100.73      1345555.82      6920488.41
      1345686.22      6917856.44
#Sta/Elev= 30
  4363.6 2097.79  4648.2 2090.99  4716.0 2090.41  4830.4 2090.16  4942.6 2086.25
  4948.5 2085.40  4958.9 2076.22  4969.2 2070.38  4976.5 2062.69  4984.3 2061.44
  4984.8 2060.94  5011.0 2061.44  5040.5 2070.16  5110.5 2069.13  5240.6 2072.45
  5306.7 2078.93  6277.9 2080.61  6368.2 2080.36  6832.5 2082.52  6892.7 2084.81
  6949.3 2083.74  7013.9 2088.32  7106.6 2088.91  7163.1 2093.34  7233.5 2092.62
  7302.8 2096.37  7353.3 2096.08  7419.7 2100.43  7517.6 2104.65  7635.2 2106.14
#Mann=15,-1,0
  4363.6    0.07       0  4648.2   0.035       0  4716.0    0.07       0
  4984.3    0.07       0  5011.0    0.07       0  5240.6   0.035       0
  5306.7    0.07       0  6277.9   0.035       0  6368.2    0.07       0
  6832.5   0.035       0  6949.3   0.045       0  7013.9    0.07       0
  7233.5   0.045       0  7419.7    0.07       0  7517.6   0.045       0
Bank Sta=4984.3,5011
Exp/Cntr=0.3,0.1

Type RM Length L Ch R = 1,5500,500,500,500
BEGIN DESCRIPTION:
Bull Creek 11.0
END DESCRIPTION:
XS GIS Cut Line= 3
      1345827.29      6921057.35      1345990.35      6920302.66
      1345783.95      6917922.29
#Sta/Elev= 30
  4227.9 2095.82  4373.0 2092.92  4472.5 2089.28  4611.4 2086.92  4783.8 2081.00
  4851.2 2079.88  4892.5 2073.91  4933.2 2072.64  4949.7 2063.21  4980.5 2060.30
  4981.0 2059.80  5007.2 2060.30  5034.8 2069.52  5132.0 2068.88  5364.8 2066.88
  5446.3 2068.43  5469.3 2074.77  5516.6 2071.00  5617.0 2077.83  5835.3 2078.38
  6550.5 2080.15  6645.0 2080.66  6768.0 2082.00  6834.8 2084.61  7062.4 2088.65
  7236.0 2096.48  7301.5 2097.77  7334.5 2100.46  7372.1 2100.68  7389.3 2103.00
#Mann=19,-1,0
  4227.9   0.035       0  4373.0    0.07       0  4472.5   0.035       0
  4611.4    0.07       0  4783.8   0.035       0  4892.5    0.07       0
  4980.5    0.07       0  5007.2    0.07       0  5132.0    0.16       0
  5364.8   0.035       0  5835.3    0.07       0  6550.5   0.035       0
  6645.0   0.045       0  6768.0    0.07       0  6834.8   0.045       0
  7236.0    0.07       0  7301.5   0.045       0  7334.5    0.07       0
  7372.1   0.045       0
Bank Sta=4980.5,5007.2
Exp/Cntr=0.3,0.1

Type RM Length L Ch R = 1,5000,500,500,500
BEGIN DESCRIPTION:
Bull Creek 10.0
END DESCRIPTION:
XS GIS Cut Line= 3
      1346305.00      6920888.02      1346247.78      6919945.96
      1346000.89      6917813.00
#Sta/Elev= 30
  4056.2 2094.95  4176.4 2088.29  4206.5 2082.39  4246.6 2079.35  4333.1 2078.34
  4472.9 2077.59  4795.5 2076.93  4846.3 2071.33  4887.8 2066.78  4963.1 2066.89
  5024.8 2057.19  5025.3 2056.69  5051.6 2057.19  5088.5 2065.99  5118.7 2064.27
  5138.9 2067.74  5189.2 2068.41  5219.4 2073.11  5243.1 2071.04  5255.0 2073.08
  5416.2 2077.84  5750.2 2076.96  6206.0 2078.38  6267.3 2081.06  6330.8 2080.14
  6588.5 2084.12  6689.2 2092.99  6825.9 2097.20  6931.0 2099.37  7147.2 2101.82
#Mann=13,-1,0
  4056.2    0.07       0  4333.1   0.035       0  4472.9    0.07       0
  4846.3    0.16       0  5024.8    0.07       0  5051.6    0.16       0
  5255.0   0.035       0  5416.2    0.07       0  5750.2   0.035       0
  6267.3    0.07       0  6330.8   0.045       0  6825.9    0.07       0
  6931.0   0.045       0
Bank Sta=5024.8,5051.6
Exp/Cntr=0.3,0.1

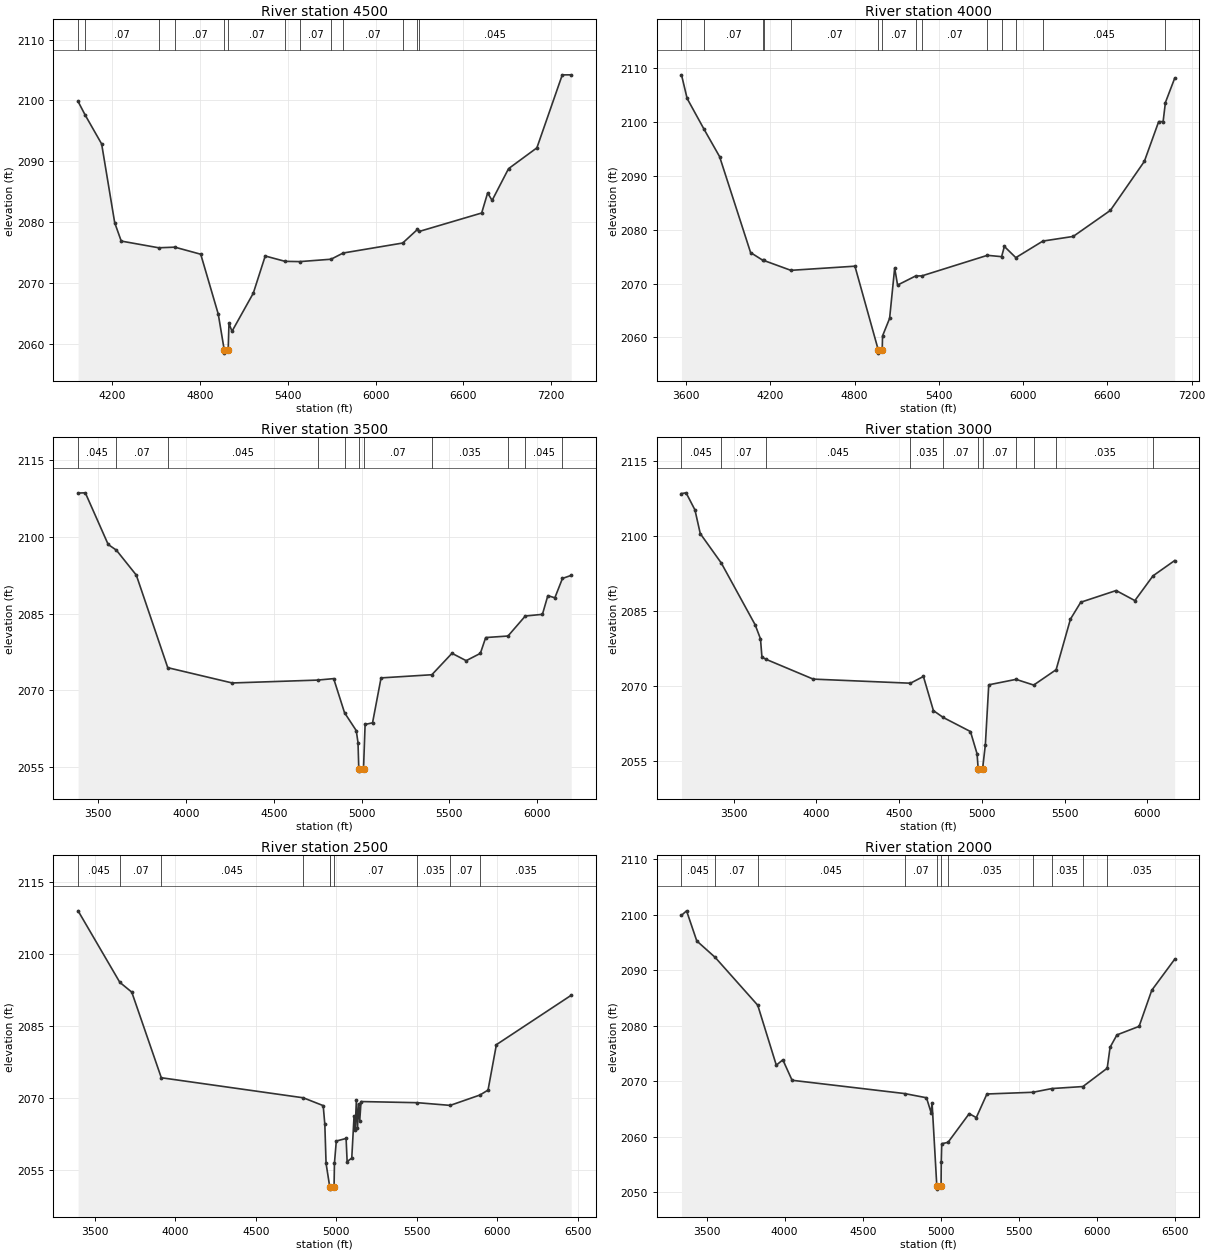
Type RM Length L Ch R = 1,4500,500,500,500
BEGIN DESCRIPTION:
Bull Creek 9.0
END DESCRIPTION:
XS GIS Cut Line= 3
      1346305.01      6920987.98      1346714.07      6920038.45
      1346250.46      6917747.89
#Sta/Elev= 30
  3966.1 2099.84  4013.8 2097.64  4127.2 2092.86  4216.5 2079.92  4261.1 2076.91
  4517.1 2075.81  4627.6 2075.91  4804.5 2074.75  4924.3 2064.92  4965.3 2059.01
  4965.8 2058.51  4992.1 2059.01  4997.5 2063.41  5018.1 2062.09  5163.7 2068.35
  5245.3 2074.46  5381.3 2073.58  5481.8 2073.54  5695.1 2073.93  5778.1 2074.95
  6184.9 2076.59  6285.8 2078.82  6297.7 2078.49  6724.7 2081.52  6765.5 2084.81
  6796.1 2083.59  6908.4 2088.80  7102.2 2092.22  7275.7 2104.20  7337.0 2104.21
#Mann=13,-1,0
  3966.1   0.035       0  4013.8    0.07       0  4517.1   0.035       0
  4627.6    0.07       0  4965.3    0.07       0  4992.1    0.07       0
  5381.3   0.035       0  5481.8    0.07       0  5695.1   0.035       0
  5778.1    0.07       0  6184.9   0.035       0  6285.8    0.07       0
  6297.7   0.045       0
Bank Sta=4965.3,4992.1
Exp/Cntr=0.3,0.1

Type RM Length L Ch R = 1,4000,500,500,500
BEGIN DESCRIPTION:
Bull Creek 8.0
END DESCRIPTION:
XS GIS Cut Line= 3
      1347155.00      6921138.02      1347031.27      6919711.27
      1346554.99      6917687.97
#Sta/Elev= 30
  3567.9 2108.82  3608.1 2104.42  3727.3 2098.76  3838.9 2093.63  4059.8 2075.78
  4149.2 2074.31  4154.3 2074.31  4346.4 2072.48  4802.5 2073.25  4969.7 2057.59
  4970.2 2057.09  4996.7 2057.59  4999.1 2060.29  5049.4 2063.55  5085.5 2072.91
  5106.1 2069.74  5234.6 2071.43  5279.1 2071.45  5745.5 2075.27  5846.7 2075.02
  5866.3 2076.92  5947.9 2074.84  6140.6 2077.92  6356.4 2078.78  6620.9 2083.62
  6862.8 2092.73  6964.9 2100.13  6996.4 2100.12  7012.7 2103.67  7078.6 2108.18
#Mann=14,-1,0
  3567.9   0.045       0  3727.3    0.07       0  4149.2   0.045       0
  4154.3   0.035       0  4346.4    0.07       0  4969.7    0.07       0
  4996.7    0.07       0  5234.6   0.035       0  5279.1    0.07       0
  5745.5   0.035       0  5846.7    0.07       0  5947.9   0.035       0
  6140.6   0.045       0  7012.7    0.07       0
Bank Sta=4969.7,4996.7
Exp/Cntr=0.3,0.1

Type RM Length L Ch R = 1,3500,500,500,500
BEGIN DESCRIPTION:
Bull Creek 7.0
END DESCRIPTION:
XS GIS Cut Line= 3
      1347255.00      6921138.00      1347471.69      6919537.60
      1347639.35      6918355.53
#Sta/Elev= 30
  3385.0 2108.60  3426.3 2108.64  3556.5 2098.54  3603.1 2097.43  3716.7 2092.55
  3895.8 2074.45  4262.9 2071.46  4748.7 2072.02  4840.8 2072.31  4902.7 2065.64
  4969.3 2062.15  4979.4 2059.81  4983.8 2054.72  4984.3 2054.22  5010.8 2054.72
  5019.8 2063.34  5062.2 2063.67  5110.7 2072.45  5400.0 2073.07  5514.7 2077.26
  5595.5 2075.82  5676.3 2077.25  5706.6 2080.34  5833.7 2080.64  5932.2 2084.55
  6029.8 2084.88  6060.6 2088.54  6100.5 2088.11  6143.8 2091.90  6193.9 2092.50
#Mann=11,-1,0
  3385.0   0.045       0  3603.1    0.07       0  3895.8   0.045       0
  4748.7   0.035       0  4902.7    0.07       0  4983.8    0.07       0
  5010.8    0.07       0  5400.0   0.035       0  5833.7    0.07       0
  5932.2   0.045       0  6143.8    0.07       0
Bank Sta=4983.8,5010.8
Exp/Cntr=0.3,0.1

Type RM Length L Ch R = 1,3000,500,500,500
BEGIN DESCRIPTION:
Bull Creek 6.0
END DESCRIPTION:
XS GIS Cut Line= 4
      1347305.94      6921133.98      1347847.60      6919710.40
      1347854.10      6919419.31      1347671.91      6918268.75
#Sta/Elev= 30
  3185.7 2108.56  3213.5 2108.70  3267.0 2105.28  3299.1 2100.54  3426.2 2094.65
  3630.8 2082.29  3662.9 2079.48  3671.7 2075.83  3698.1 2075.37  3981.5 2071.43
  4568.8 2070.61  4647.2 2071.96  4707.5 2065.13  4767.1 2063.75  4931.3 2060.94
  4971.3 2056.48  4977.8 2053.52  4978.3 2053.02  5004.8 2053.52  5021.4 2058.34
  5041.8 2070.29  5206.6 2071.38  5313.4 2070.24  5448.8 2073.31  5535.3 2083.43
  5597.6 2086.81  5811.3 2089.15  5924.5 2087.14  6034.0 2092.09  6164.9 2095.15
#Mann=11,-1,0
  3185.7   0.045       0  3426.2    0.07       0  3698.1   0.045       0
  4568.8   0.035       0  4767.1    0.07       0  4977.8    0.07       0
  5004.8    0.07       0  5206.6   0.035       0  5313.4    0.07       0
  5448.8   0.035       0  6034.0    0.07       0
Bank Sta=4977.8,5004.8
Exp/Cntr=0.3,0.1

Type RM Length L Ch R = 1,2500,500,500,500
BEGIN DESCRIPTION:
Bull Creek 5.0
END DESCRIPTION:
XS GIS Cut Line= 4
      1347355.01      6921137.98      1348004.86      6919672.94
      1348215.65      6919502.07      1347729.77      6918419.24
#Sta/Elev= 30
  3397.3 2109.04  3656.4 2094.14  3730.6 2092.10  3913.9 2074.26  4795.3 2070.08
  4918.7 2068.45  4928.8 2064.55  4936.5 2056.41  4958.6 2051.68  4959.0 2051.55
  4959.5 2051.05  4986.1 2051.55  4988.5 2056.45  5000.0 2061.07  5060.8 2061.61
  5067.2 2056.79  5096.0 2057.51  5110.3 2066.32  5116.8 2063.32  5124.7 2069.66
  5131.1 2063.69  5139.1 2068.85  5145.5 2065.34  5153.5 2069.30  5503.7 2069.06
  5706.8 2068.50  5891.6 2070.66  5941.8 2071.69  5993.6 2081.15  6458.2 2091.45
#Mann=10,-1,0
  3397.3   0.045       0  3656.4    0.07       0  3913.9   0.045       0
  4795.3   0.035       0  4958.6    0.07       0  4959.0    0.07       0
  4986.1    0.07       0  5503.7   0.035       0  5706.8    0.07       0
  5891.6   0.035       0
Bank Sta=4959,4986.1
Exp/Cntr=0.3,0.1

Type RM Length L Ch R = 1,2000,500,500,500
BEGIN DESCRIPTION:
Bull Creek 4.0
END DESCRIPTION:
XS GIS Cut Line= 3
      1347521.20      6921099.30      1348472.82      6919738.17
      1347764.24      6918418.69
#Sta/Elev= 30
  3339.2 2099.87  3371.7 2100.68  3437.1 2095.26  3554.8 2092.30  3827.6 2083.68
  3946.4 2072.89  3988.2 2073.85  4047.5 2070.17  4767.7 2067.78  4908.3 2067.02
  4937.9 2064.33  4944.0 2066.13  4974.5 2051.07  4975.0 2050.57  5001.6 2051.07
  5002.9 2055.50  5005.9 2058.75  5046.1 2058.99  5181.8 2064.16  5227.2 2063.45
  5295.3 2067.70  5589.9 2068.01  5711.5 2068.68  5910.1 2069.04  6065.7 2072.34
  6084.1 2076.11  6127.9 2078.34  6270.0 2079.88  6350.9 2086.37  6497.7 2091.96
#Mann=11,-1,0
  3339.2   0.045       0  3554.8    0.07       0  3827.6   0.045       0
  4767.7    0.07       0  4974.5    0.07       0  5001.6    0.07       0
  5046.1   0.035       0  5589.9    0.07       0  5711.5   0.035       0
  5910.1    0.07       0  6065.7   0.035       0
Bank Sta=4974.5,5001.6
Exp/Cntr=0.3,0.1

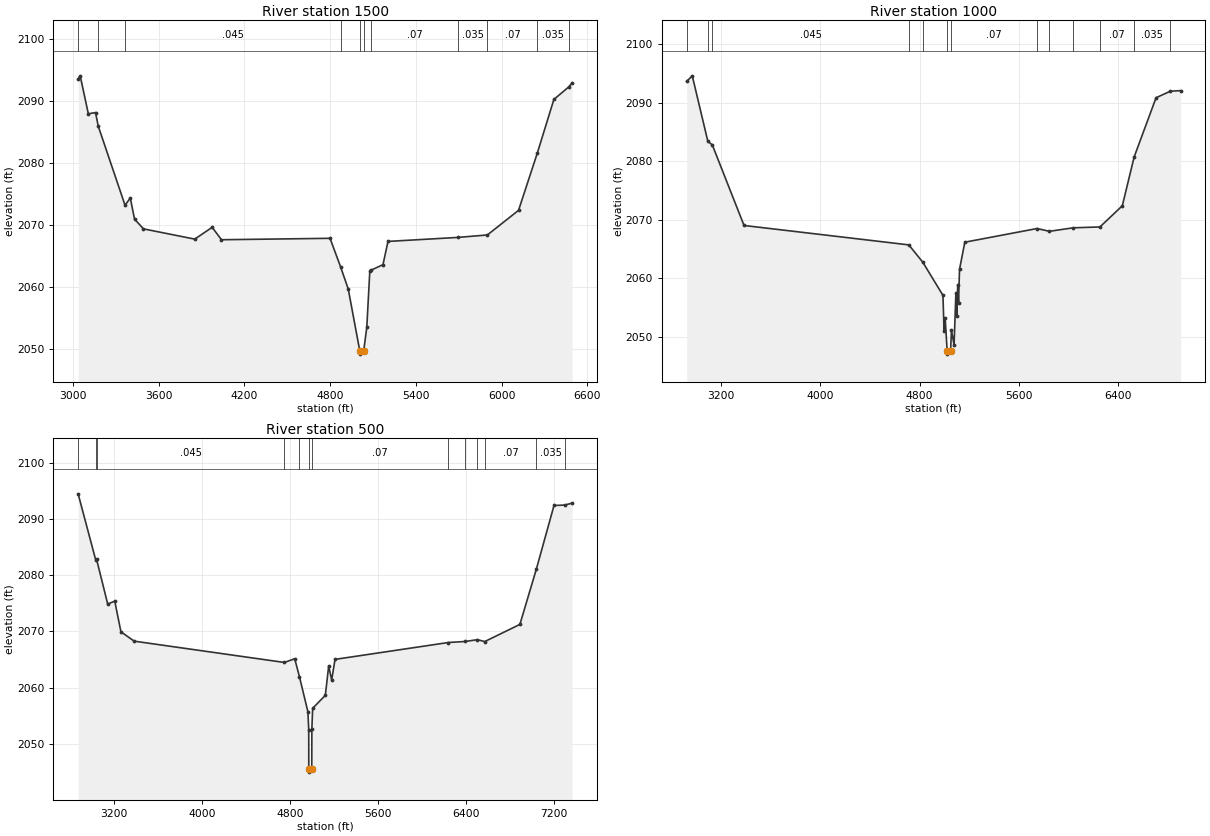
Type RM Length L Ch R = 1,1500,500,500,500
BEGIN DESCRIPTION:
Bull Creek 3.0
END DESCRIPTION:
XS GIS Cut Line= 4
      1347847.60      6921029.85      1348872.33      6919590.07
      1348773.03      6919419.83      1347770.19      6918312.83
#Sta/Elev= 30
  3035.7 2093.53  3050.2 2094.04  3107.2 2087.93  3157.6 2088.13  3176.7 2085.93
  3364.2 2073.21  3401.0 2074.38  3430.5 2070.99  3493.2 2069.41  3852.3 2067.76
  3974.0 2069.66  4039.2 2067.66  4799.1 2067.89  4872.4 2063.33  4926.7 2059.72
  5007.5 2049.75  5008.0 2049.25  5034.6 2049.75  5056.4 2053.56  5077.8 2062.70
  5088.4 2062.78  5169.7 2063.65  5204.9 2067.39  5691.7 2068.03  5900.5 2068.43
  6118.6 2072.39  6250.7 2081.65  6366.0 2090.24  6469.8 2092.25  6493.7 2092.91
#Mann=11,-1,0
  3035.7   0.045       0  3176.7    0.07       0  3364.2   0.045       0
  4872.4   0.035       0  5007.5   0.035       0  5034.6   0.035       0
  5088.4    0.07       0  5691.7   0.035       0  5900.5    0.07       0
  6250.7   0.035       0  6469.8    0.07       0
Bank Sta=5007.5,5034.6
Exp/Cntr=0.3,0.1

Type RM Length L Ch R = 1,1000,500,500,500
BEGIN DESCRIPTION:
Bull Creek 2.0
END DESCRIPTION:
XS GIS Cut Line= 4
      1348108.09      6921163.27      1349183.28      6919388.33
      1349014.58      6919142.91      1347611.49      6918363.18
#Sta/Elev= 30
  2924.8 2093.67  2969.5 2094.61  3095.0 2083.41  3130.9 2082.80  3386.4 2069.02
  4713.5 2065.70  4826.0 2062.74  4988.3 2057.07  4997.3 2050.95  5006.1 2053.14
  5022.4 2047.52  5022.9 2047.02  5049.5 2047.52  5056.9 2051.10  5077.8 2048.60
  5092.7 2057.53  5098.8 2053.61  5107.6 2058.92  5113.7 2055.76  5121.7 2061.50
  5164.4 2066.16  5746.7 2068.50  5845.6 2068.02  6036.4 2068.62  6252.6 2068.77
  6432.8 2072.39  6527.9 2080.73  6704.5 2090.86  6819.5 2091.98  6903.0 2092.08
#Mann=13,-1,0
  2924.8   0.045       0  3095.0    0.07       0  3130.9   0.045       0
  4713.5   0.035       0  4826.0    0.07       0  5022.4    0.07       0
  5049.5    0.07       0  5746.7   0.035       0  5845.6    0.07       0
  6036.4   0.035       0  6252.6    0.07       0  6527.9   0.035       0
  6819.5    0.07       0
Bank Sta=5022.4,5049.5
Exp/Cntr=0.3,0.1

Type RM Length L Ch R = 1,500,0,0,0
BEGIN DESCRIPTION:
Bull Creek 1.0
END DESCRIPTION:
XS GIS Cut Line= 4
      1348055.01      6921087.99      1349584.92      6919617.52
      1349340.01      6919234.15      1347646.23      6918356.25
#Sta/Elev= 30
  2878.0 2094.47  3037.8 2082.71  3045.6 2082.82  3146.7 2074.86  3210.5 2075.39
  3266.8 2069.93  3387.3 2068.27  4751.3 2064.48  4844.2 2065.15  4886.9 2061.97
  4964.3 2055.70  4971.5 2052.52  4972.1 2045.48  4972.6 2044.98  4999.2 2045.48
  5000.0 2052.65  5007.3 2056.33  5122.3 2058.64  5152.8 2063.86  5179.8 2061.35
  5210.3 2065.03  6238.8 2068.03  6390.2 2068.21  6502.7 2068.53  6569.6 2068.20
  6888.5 2071.25  7037.6 2081.05  7198.3 2092.40  7294.5 2092.47  7362.7 2092.81
#Mann=13,-1,0
  2878.0   0.045       0  3037.8    0.07       0  3045.6   0.045       0
  4751.3   0.035       0  4886.9    0.07       0  4972.1    0.07       0
  4999.2    0.07       0  6238.8   0.035       0  6390.2    0.07       0
  6502.7   0.035       0  6569.6    0.07       0  7037.6   0.035       0
  7294.5    0.07       0
Bank Sta=4972.1,4999.2
Exp/Cntr=0.3,0.1

Chan Stop Cuts=-1