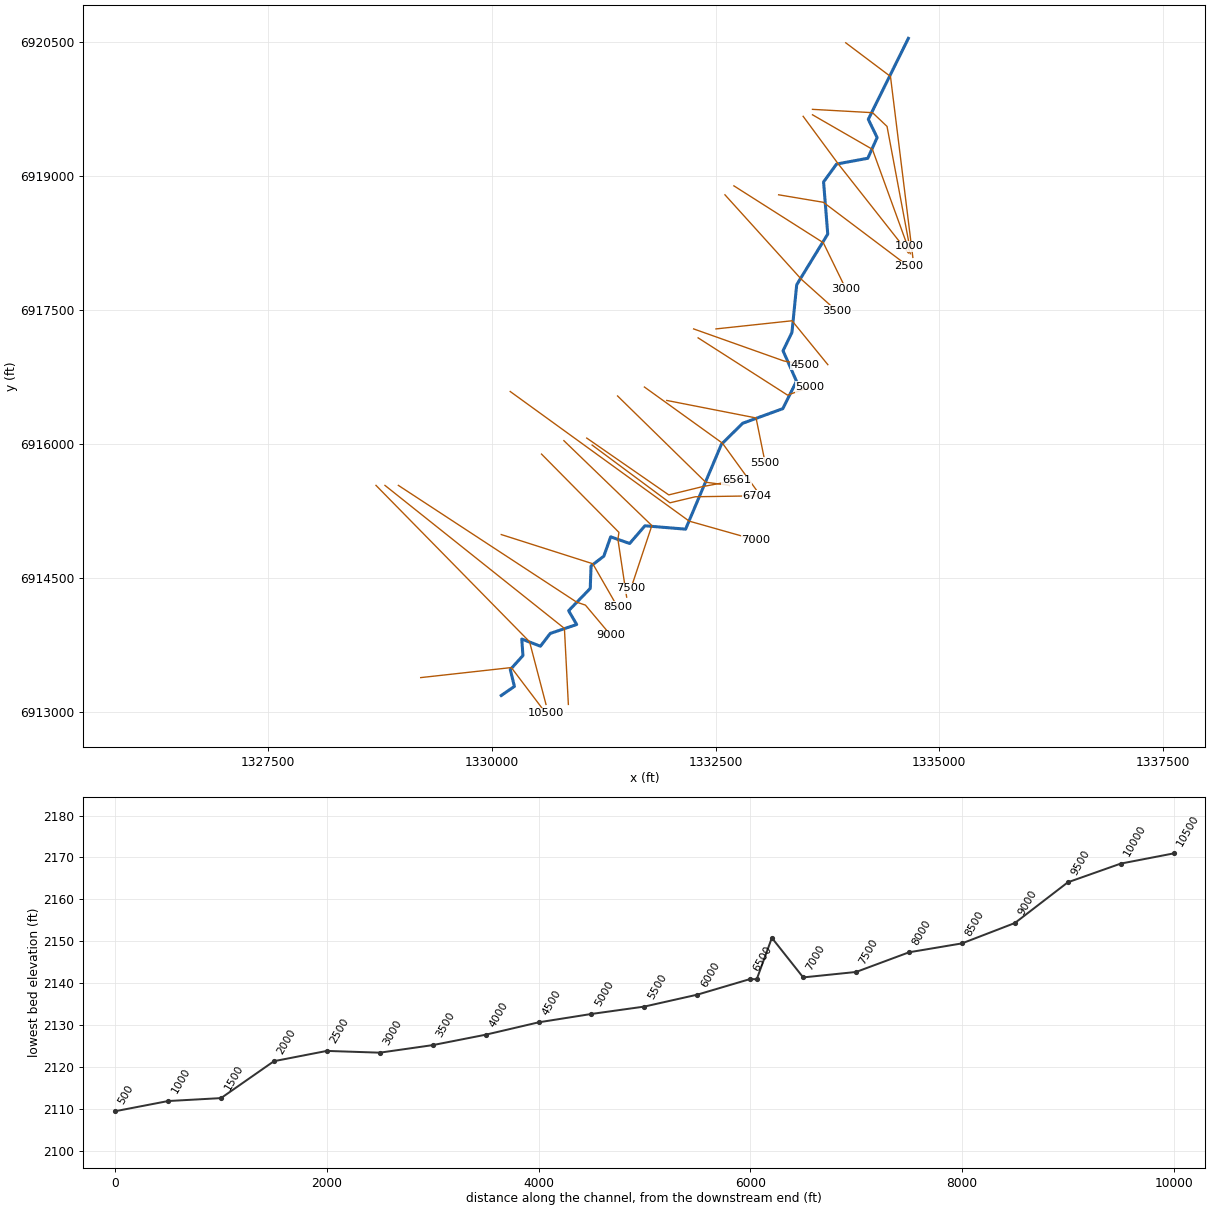
--- Bull Creek Trib03.prj (project) ---

Proj Title=Bull Creek Trib03 Base Level Engineering
Current Plan=p01
Default Exp/Contr=0.3,0.1
English Units
Geom File=g01
Flow File=f01
Plan File=p01
BEGIN DESCRIPTION:
Bull Creek Trib03
END DESCRIPTION:

--- Bull Creek Trib03.p01 (plan) ---

Plan Title=Multiple Run
Short Identifier=Multiple
Geom File=g01
Flow File=f01
Subcritical Flow
K Sum by GR= 0
Std Step Tol= 0.01
Critical Tol= 0.01
Num of Std Step Trials= 20
Max Error Tol= 0.3
Flow Tol Ratio= 0.001
Split Flow NTrial= 30
Split Flow Tol= 0.02
Split Flow Ratio= 0.02
Log Output Level= 0
Friction Slope Method= 1
Unsteady Friction Slope Method= 2
Unsteady Bridges Friction Slope Method= 1
Parabolic Critical Depth
Global Vel Dist=  1 , 1 , 1
Global Log Level= 0
CheckData=True
Encroach Param= -1, 0, 0, 0
BEGIN DESCRIPTION:
Multiple Run
END DESCRIPTION:

--- Bull Creek Trib03.f01 (steady flow) ---

Flow Title=Multiple
Number of Profiles=7
Profile Names=10-year,25-year,50-year,1pct_min,100-year,1pct_plu,500-year
River Rch & RM= Bull Creek Trib0,Reach-1,10500
     327     474     600     378     754    1505    1208
River Rch & RM= Bull Creek Trib0,Reach-1,8000
     529     786    1012     648    1292    2579    2137
River Rch & RM= Bull Creek Trib0,Reach-1,6561
     611     910    1173     751    1498    2988    2476
Boundary for River Rch & Prof#=Bull Creek Trib0,Reach-1,1
Up Type=0
Dn Type=3
Dn Slope=0.005
Boundary for River Rch & Prof#=Bull Creek Trib0,Reach-1,2
Up Type=0
Dn Type=3
Dn Slope=0.005
Boundary for River Rch & Prof#=Bull Creek Trib0,Reach-1,3
Up Type=0
Dn Type=3
Dn Slope=0.005
Boundary for River Rch & Prof#=Bull Creek Trib0,Reach-1,4
Up Type=0
Dn Type=3
Dn Slope=0.005
Boundary for River Rch & Prof#=Bull Creek Trib0,Reach-1,5
Up Type=0
Dn Type=3
Dn Slope=0.005
Boundary for River Rch & Prof#=Bull Creek Trib0,Reach-1,6
Up Type=0
Dn Type=3
Dn Slope=0.005
Boundary for River Rch & Prof#=Bull Creek Trib0,Reach-1,7
Up Type=0
Dn Type=3
Dn Slope=0.005

--- Bull Creek Trib03.g01 (geometry) ---

Geom Title=Existing Conditions

River Reach=Bull Creek Trib0,Reach-1
Reach XY= 30
      1330105.00      6913188.00      1330251.89      6913289.62
      1330205.93      6913477.52      1330347.20      6913634.58
      1330334.47      6913818.92      1330542.99      6913739.17
      1330652.69      6913882.17      1330947.80      6913981.92
      1330858.09      6914136.33      1331099.54      6914385.55
      1331108.53      6914636.55      1331251.49      6914746.48
      1331327.87      6914962.52      1331539.79      6914888.23
      1331710.68      6915086.03      1332165.18      6915048.32
      1332565.76      6915997.68      1332802.63      6916232.46
      1333251.63      6916396.15      1333404.63      6916703.17
      1333254.39      6917043.51      1333353.78      6917248.50
      1333407.07      6917782.14      1333753.95      6918348.65
      1333707.24      6918932.07      1333852.69      6919132.18
      1334201.50      6919196.46      1334305.92      6919428.25
      1334207.16      6919632.02      1334655.00      6920538.00

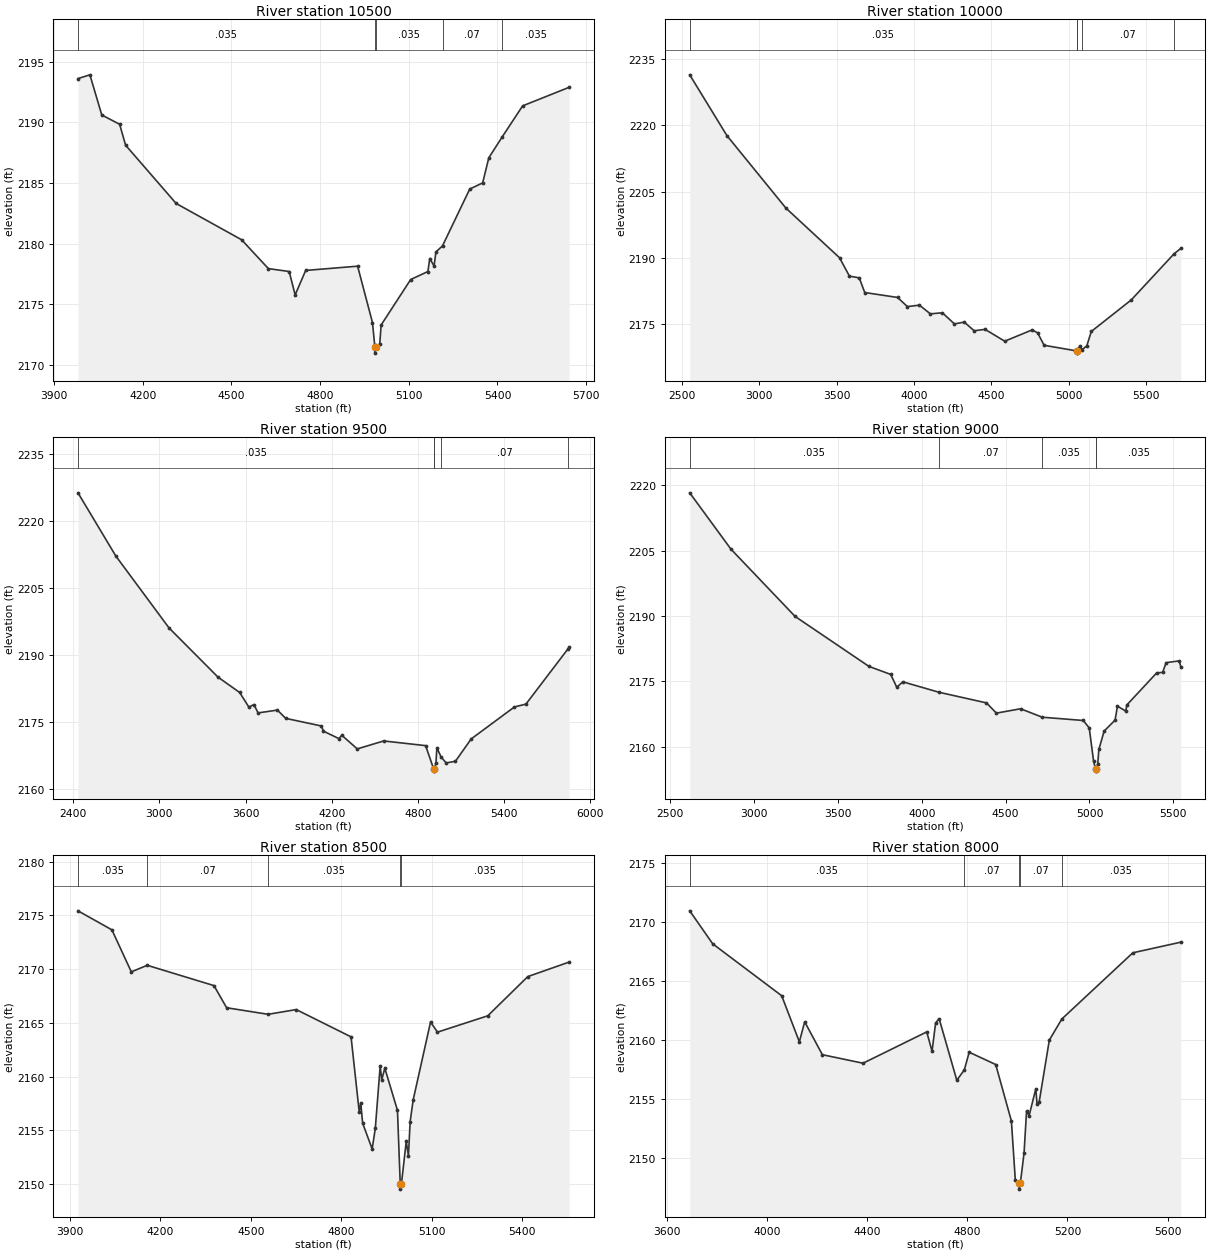
Type RM Length L Ch R = 1,10500,500,500,500
BEGIN DESCRIPTION:
Bull Creek Trib03 21.0
END DESCRIPTION:
XS GIS Cut Line= 3
      1329204.97      6913388.00      1330217.56      6913500.36
      1330605.03      6912987.97
#Sta/Elev= 30
  3981.2 2193.61  4021.5 2193.92  4061.7 2190.61  4122.2 2189.84  4142.2 2188.12
  4313.3 2183.31  4534.6 2180.32  4625.2 2177.94  4695.6 2177.70  4715.7 2175.77
  4751.4 2177.79  4927.0 2178.14  4977.3 2173.49  4985.4 2171.47  4985.6 2170.97
  4989.4 2171.47  5002.0 2171.75  5006.6 2173.29  5106.5 2177.04  5164.8 2177.70
  5171.0 2178.77  5185.6 2178.16  5191.9 2179.31  5214.2 2179.82  5306.3 2184.50
  5350.0 2185.01  5370.8 2187.08  5415.0 2188.76  5485.2 2191.36  5642.4 2192.89
#Mann=5,-1,0
  3981.2   0.035       0  4985.4   0.035       0  4989.4   0.035       0
  5214.2    0.07       0  5415.0   0.035       0
Bank Sta=4985.4,4989.4
Exp/Cntr=0.3,0.1

Type RM Length L Ch R = 1,10000,500,500,500
BEGIN DESCRIPTION:
Bull Creek Trib03 20.0
END DESCRIPTION:
XS GIS Cut Line= 3
      1328704.99      6915538.01      1330421.32      6913788.97
      1330604.99      6913088.04
#Sta/Elev= 30
  2549.5 2231.32  2789.9 2217.61  3171.8 2201.24  3518.3 2190.05  3582.0 2185.91
  3645.5 2185.52  3681.0 2182.21  3893.1 2181.10  3956.7 2179.04  4034.6 2179.36
  4105.2 2177.40  4183.0 2177.64  4260.7 2175.13  4324.5 2175.54  4388.0 2173.59
  4458.8 2173.90  4586.1 2171.23  4762.9 2173.78  4798.2 2173.13  4840.7 2170.31
  5050.7 2169.04  5050.9 2168.54  5054.7 2169.04  5070.9 2170.09  5085.6 2169.30
  5116.5 2170.18  5145.7 2173.43  5404.2 2180.55  5680.7 2190.95  5724.6 2192.17
#Mann=5,-1,0
  2549.5   0.035       0  5050.7   0.035       0  5054.7   0.035       0
  5085.6    0.07       0  5680.7   0.035       0
Bank Sta=5050.7,5054.7
Exp/Cntr=0.3,0.1

Type RM Length L Ch R = 1,9500,500,500,500
BEGIN DESCRIPTION:
Bull Creek Trib03 19.0
END DESCRIPTION:
XS GIS Cut Line= 3
      1328804.97      6915538.02      1330810.98      6913938.25
      1330855.00      6913087.99
#Sta/Elev= 30
  2434.2 2226.32  2697.7 2212.18  3067.6 2196.11  3408.6 2185.10  3559.2 2181.67
  3623.2 2178.40  3658.5 2178.97  3687.3 2177.10  3821.8 2177.73  3879.5 2175.88
  4127.6 2174.18  4142.1 2173.02  4249.4 2171.36  4270.2 2172.09  4377.5 2169.05
  4561.6 2170.83  4853.0 2169.78  4908.7 2164.58  4909.0 2164.08  4912.7 2164.58
  4925.1 2165.97  4931.5 2169.32  4959.8 2167.29  4995.6 2165.92  5060.3 2166.28
  5170.0 2171.28  5470.9 2178.43  5551.0 2179.07  5841.6 2191.34  5851.4 2191.76
#Mann=5,-1,0
  2434.2   0.035       0  4908.7    0.07       0  4912.7   0.035       0
  4959.8    0.07       0  5841.6   0.035       0
Bank Sta=4908.7,4912.7
Exp/Cntr=0.3,0.1

Type RM Length L Ch R = 1,9000,500,500,500
BEGIN DESCRIPTION:
Bull Creek Trib03 18.0
END DESCRIPTION:
XS GIS Cut Line= 4
      1328954.97      6915538.02      1330948.51      6914231.56
      1331045.89      6914198.75      1331330.39      6913860.30
#Sta/Elev= 30
  2616.5 2218.29  2862.2 2205.36  3245.1 2189.90  3685.2 2178.43  3814.8 2176.59
  3851.0 2173.65  3887.2 2174.89  4102.1 2172.50  4386.0 2170.05  4445.0 2167.70
  4589.3 2168.70  4718.5 2166.76  4963.4 2166.01  4998.7 2164.28  5024.7 2156.63
  5036.5 2154.88  5036.8 2154.38  5040.5 2154.88  5049.1 2155.99  5056.2 2159.39
  5087.7 2163.59  5152.6 2166.09  5166.9 2169.28  5216.4 2168.18  5222.9 2169.58
  5401.0 2176.95  5436.2 2177.05  5457.0 2179.29  5535.1 2179.70  5544.9 2178.31
#Mann=5,-1,0
  2616.5   0.035       0  4102.1    0.07       0  4718.5   0.035       0
  5036.5   0.035       0  5040.5   0.035       0
Bank Sta=5036.5,5040.5
Exp/Cntr=0.3,0.1

Type RM Length L Ch R = 1,8500,500,500,500
BEGIN DESCRIPTION:
Bull Creek Trib03 17.0
END DESCRIPTION:
XS GIS Cut Line= 3
      1330105.02      6914987.99      1331127.90      6914661.58
      1331404.40      6914179.09
#Sta/Elev= 30
  3926.3 2175.42  4038.9 2173.65  4103.3 2169.74  4156.2 2170.35  4377.6 2168.46
  4419.6 2166.40  4557.1 2165.79  4650.6 2166.23  4832.5 2163.69  4859.5 2156.73
  4864.7 2157.53  4871.0 2155.65  4902.5 2153.26  4913.0 2155.18  4929.1 2160.97
  4934.4 2159.69  4944.5 2160.78  4986.5 2156.85  4995.7 2150.02  4995.9 2149.52
  4999.7 2150.02  5015.6 2153.96  5022.9 2152.63  5028.6 2155.81  5038.7 2157.83
  5096.3 2165.07  5119.3 2164.13  5286.1 2165.65  5419.0 2169.30  5556.1 2170.65
#Mann=5,-1,0
  3926.3   0.035       0  4156.2    0.07       0  4557.1   0.035       0
  4995.7   0.035       0  4999.7   0.035       0
Bank Sta=4995.7,4999.7
Exp/Cntr=0.3,0.1

Type RM Length L Ch R = 1,8000,500,500,500
BEGIN DESCRIPTION:
Bull Creek Trib03 16.0
END DESCRIPTION:
XS GIS Cut Line= 4
      1330555.03      6915887.97      1331420.33      6915012.16
      1331408.82      6914934.17      1331506.32      6914288.19
#Sta/Elev= 30
  3690.0 2170.94  3781.9 2168.15  4057.6 2163.76  4128.3 2159.86  4149.6 2161.55
  4220.3 2158.77  4382.9 2158.05  4637.5 2160.70  4658.7 2159.06  4672.9 2161.45
  4687.0 2161.82  4757.7 2156.61  4787.9 2157.49  4807.2 2158.98  4913.2 2157.94
  4975.9 2153.16  4991.5 2148.18  5007.5 2147.90  5007.8 2147.40  5011.7 2147.90
  5026.5 2150.46  5036.6 2154.02  5046.7 2153.61  5073.5 2155.89  5078.5 2154.58
  5087.2 2154.81  5127.6 2160.01  5177.5 2161.79  5461.3 2167.39  5653.3 2168.29
#Mann=5,-1,0
  3690.0   0.035       0  4787.9    0.07       0  5007.5    0.07       0
  5011.7    0.07       0  5177.5   0.035       0
Bank Sta=5007.5,5011.7
Exp/Cntr=0.3,0.1

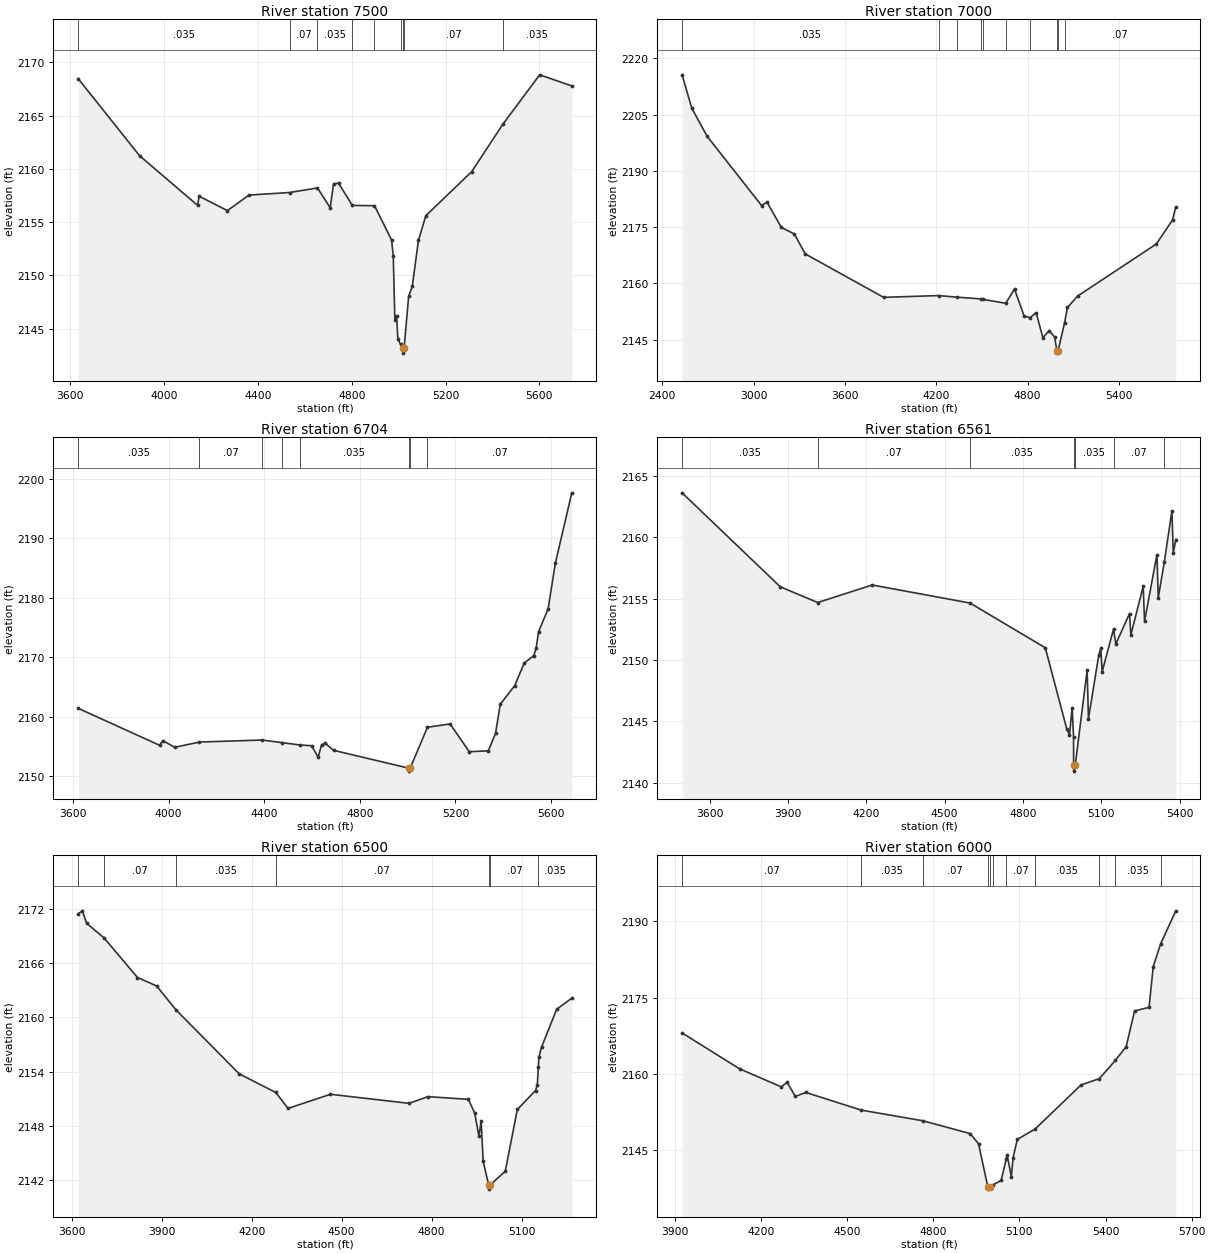
Type RM Length L Ch R = 1,7500,500,500,500
BEGIN DESCRIPTION:
Bull Creek Trib03 15.0
END DESCRIPTION:
XS GIS Cut Line= 3
      1330804.97      6916038.03      1331788.17      6915088.44
      1331555.01      6914388.02
#Sta/Elev= 30
  3633.1 2168.49  3894.9 2161.25  4142.4 2156.59  4149.3 2157.44  4269.7 2156.09
  4361.6 2157.55  4534.5 2157.79  4653.8 2158.22  4708.1 2156.35  4722.2 2158.61
  4743.6 2158.67  4802.3 2156.58  4896.9 2156.55  4969.7 2153.34  4976.9 2151.86
  4983.8 2145.79  4991.0 2146.24  4996.7 2143.99  5008.5 2143.53  5019.0 2143.21
  5019.3 2142.71  5023.2 2143.21  5042.6 2148.04  5058.0 2148.98  5084.3 2153.30
  5116.0 2155.62  5311.1 2159.74  5444.5 2164.21  5601.2 2168.84  5738.2 2167.80
#Mann=9,-1,0
  3633.1   0.035       0  4534.5    0.07       0  4653.8   0.035       0
  4802.3    0.07       0  4896.9   0.035       0  5008.5    0.07       0
  5019.0   0.035       0  5023.2    0.07       0  5444.5   0.035       0
Bank Sta=5019,5023.2
Exp/Cntr=0.3,0.1

Type RM Length L Ch R = 1,7000,296,296,296
BEGIN DESCRIPTION:
Bull Creek Trib03 14.0
END DESCRIPTION:
XS GIS Cut Line= 3
      1330205.03      6916587.98      1332205.36      6915138.14
      1332950.38      6914927.21
#Sta/Elev= 30
  2529.5 2215.59  2593.2 2206.70  2693.8 2199.21  3051.8 2180.75  3087.3 2181.67
  3181.7 2174.91  3267.5 2173.16  3338.6 2167.86  3853.6 2156.28  4215.1 2156.75
  4335.2 2156.33  4495.8 2155.86  4505.9 2155.74  4656.5 2154.70  4714.2 2158.51
  4777.2 2151.32  4817.1 2150.88  4856.5 2152.19  4900.5 2145.54  4942.3 2147.40
  4977.9 2145.68  4993.6 2141.91  4994.1 2141.41  4999.8 2141.91  5043.3 2149.49
  5062.0 2153.58  5129.3 2156.63  5646.0 2170.48  5753.1 2176.92  5774.3 2180.39
#Mann=10,-1,0
  2529.5   0.035       0  4215.1    0.07       0  4335.2   0.035       0
  4495.8    0.07       0  4505.9   0.035       0  4656.5    0.07       0
  4817.1   0.035       0  4993.6   0.035       0  4999.8   0.035       0
  5043.3    0.07       0
Bank Sta=4993.6,4999.8
Exp/Cntr=0.3,0.1

Type RM Length L Ch R = 1,6704,143,143,143
BEGIN DESCRIPTION:
Bull Creek Trib03 13.6
END DESCRIPTION:
XS GIS Cut Line= 4
      1331120.37      6915988.85      1331990.12      6915343.05
      1332273.98      6915410.75      1332964.08      6915421.17
#Sta/Elev= 30
  3621.6 2161.41  3962.2 2155.19  3976.1 2155.96  4025.9 2154.85  4129.3 2155.73
  4390.8 2156.07  4472.7 2155.64  4549.1 2155.24  4598.5 2155.11  4625.6 2153.17
  4640.2 2155.26  4654.8 2155.54  4690.2 2154.34  5004.6 2151.34  5005.1 2150.84
  5010.8 2151.34  5083.1 2158.22  5177.8 2158.78  5257.8 2154.11  5337.8 2154.25
  5367.8 2157.19  5387.8 2162.09  5447.8 2165.20  5487.8 2169.00  5527.8 2170.26
  5537.8 2171.52  5547.8 2174.28  5587.8 2178.12  5617.8 2185.76  5686.9 2197.64
#Mann=8,-1,0
  3621.6   0.035       0  4129.3    0.07       0  4390.8   0.035       0
  4472.7    0.07       0  4549.1   0.035       0  5004.6   0.035       0
  5010.8   0.035       0  5083.1    0.07       0
Bank Sta=5004.6,5010.8
Exp/Cntr=0.3,0.1

Type RM Length L Ch R = 1,6561,61,61,61
BEGIN DESCRIPTION:
Bull Creek Trib03 13.5
END DESCRIPTION:
XS GIS Cut Line= 4
      1331060.47      6916066.98      1331977.10      6915431.59
      1332353.47      6915523.79      1332734.95      6915595.66
#Sta/Elev= 30
  3494.5 2163.61  3870.6 2155.96  4014.0 2154.68  4222.6 2156.11  4597.3 2154.64
  4885.6 2151.00  4968.0 2144.38  4978.3 2143.94  4988.6 2146.11  4993.9 2143.70
  4994.2 2141.46  4994.7 2140.96  5000.4 2141.46  5045.9 2149.18  5051.0 2145.23
  5090.5 2150.41  5098.3 2150.96  5103.4 2149.05  5147.0 2152.52  5155.8 2151.31
  5208.3 2153.78  5213.4 2152.05  5260.7 2156.00  5265.8 2153.15  5313.2 2158.58
  5318.3 2155.07  5341.6 2157.99  5370.7 2162.15  5375.8 2158.73  5385.5 2159.81
#Mann=7,-1,0
  3494.5   0.035       0  4014.0    0.07       0  4597.3   0.035       0
  4994.2   0.035       0  5000.4   0.035       0  5147.0    0.07       0
  5341.6   0.035       0
Bank Sta=4994.2,5000.4
Exp/Cntr=0.3,0.1

Type RM Length L Ch R = 1,6500,500,500,500
BEGIN DESCRIPTION:
Bull Creek Trib03 13.0
END DESCRIPTION:
XS GIS Cut Line= 3
      1331404.99      6916538.01      1332389.93      6915573.27
      1332654.99      6915538.00
#Sta/Elev= 30
  3621.3 2171.42  3635.4 2171.75  3649.5 2170.38  3708.1 2168.75  3819.3 2164.39
  3883.0 2163.46  3948.1 2160.80  4158.7 2153.75  4280.4 2151.70  4321.3 2149.94
  4462.8 2151.50  4724.5 2150.50  4788.1 2151.24  4922.5 2150.94  4943.7 2149.42
  4957.8 2146.85  4965.0 2148.56  4972.0 2144.08  4990.0 2141.53  4990.5 2141.03
  4996.2 2141.53  5045.5 2143.00  5085.8 2149.82  5146.4 2151.91  5152.5 2152.52
  5155.8 2154.49  5157.6 2155.56  5166.5 2156.71  5217.0 2160.88  5267.4 2162.11
#Mann=7,-1,0
  3621.3   0.035       0  3708.1    0.07       0  3948.1   0.035       0
  4280.4    0.07       0  4990.0    0.07       0  4996.2    0.07       0
  5155.8   0.035       0
Bank Sta=4990,4996.2
Exp/Cntr=0.3,0.1

Type RM Length L Ch R = 1,6000,500,500,500
BEGIN DESCRIPTION:
Bull Creek Trib03 12.0
END DESCRIPTION:
XS GIS Cut Line= 3
      1331704.97      6916638.03      1332576.90      6916010.28
      1332955.01      6915487.98
#Sta/Elev= 30
  3925.6 2168.04  4125.7 2160.98  4270.5 2157.44  4291.4 2158.33  4319.9 2155.54
  4356.4 2156.33  4549.5 2152.85  4763.5 2150.76  4928.4 2148.24  4957.8 2146.24
  4990.0 2137.80  4990.5 2137.30  4996.8 2137.80  5009.9 2138.20  5036.5 2139.00
  5054.6 2143.28  5057.4 2144.09  5072.1 2139.75  5078.3 2143.52  5093.0 2147.09
  5154.7 2149.12  5314.9 2157.81  5378.6 2159.05  5434.2 2162.63  5471.9 2165.33
  5501.3 2172.38  5551.6 2173.08  5566.3 2181.11  5592.3 2185.63  5644.8 2192.08
#Mann=11,-1,0
  3925.6    0.07       0  4549.5   0.035       0  4763.5    0.07       0
  4990.0    0.07       0  4996.8    0.07       0  5009.9   0.035       0
  5054.6    0.07       0  5154.7   0.035       0  5378.6    0.07       0
  5434.2   0.035       0  5592.3    0.07       0
Bank Sta=4990,4996.8
Exp/Cntr=0.3,0.1

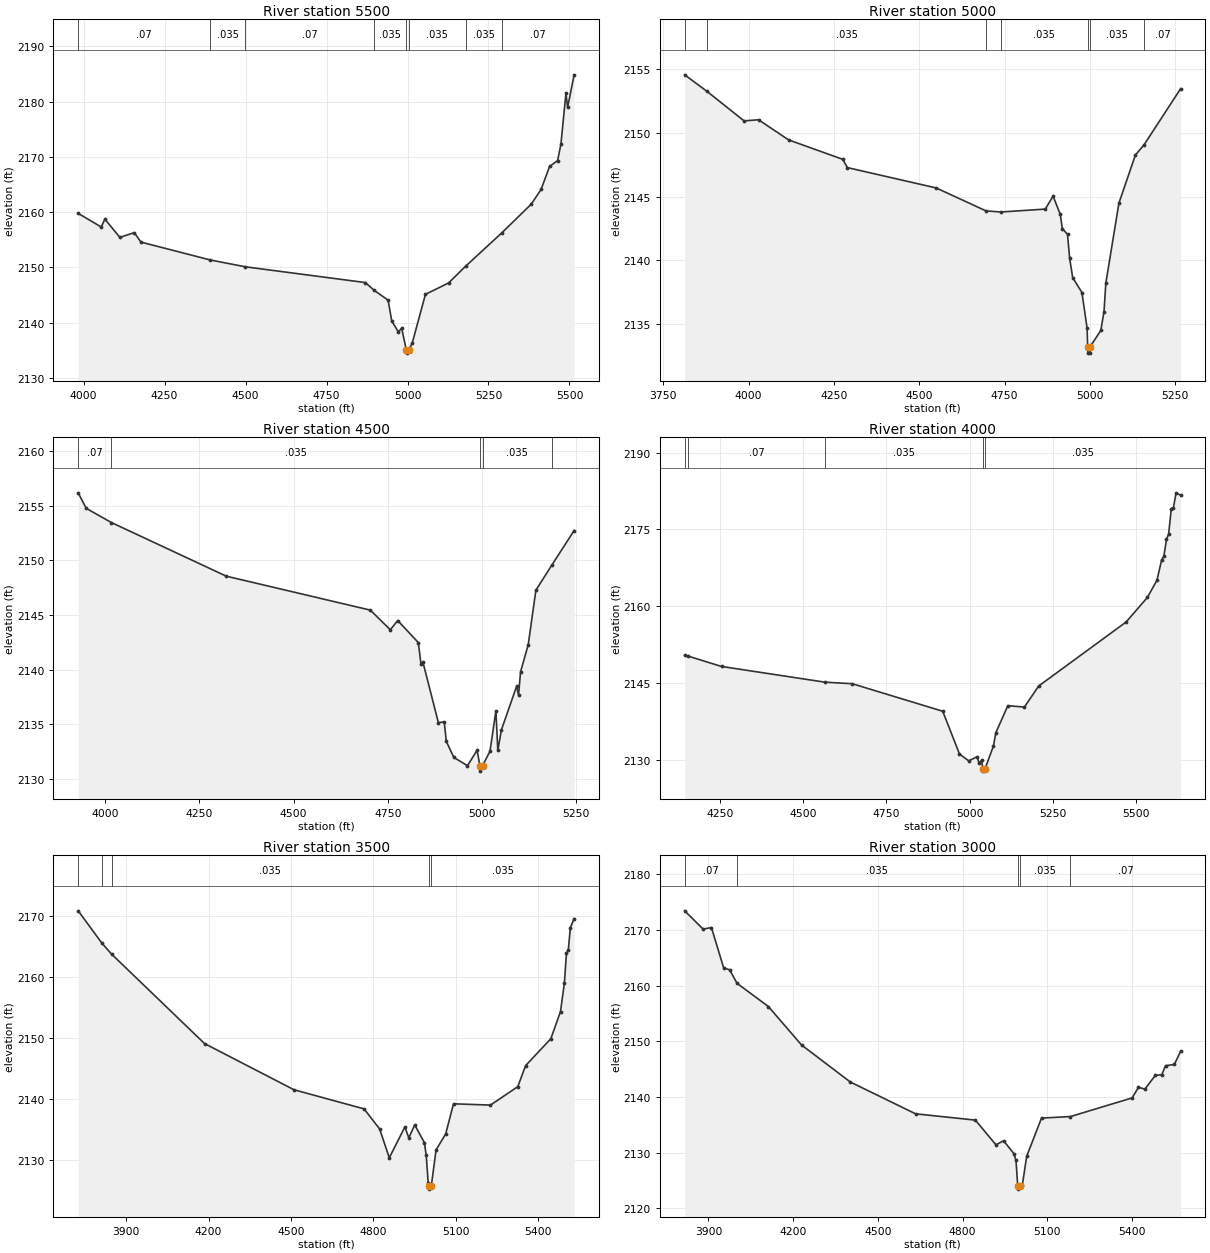
Type RM Length L Ch R = 1,5500,500,500,500
BEGIN DESCRIPTION:
Bull Creek Trib03 11.0
END DESCRIPTION:
XS GIS Cut Line= 3
      1331955.00      6916488.00      1332952.78      6916292.24
      1333055.00      6915788.00
#Sta/Elev= 30
  3983.2 2159.76  4054.5 2157.30  4065.5 2158.73  4111.8 2155.42  4156.4 2156.28
  4176.8 2154.57  4390.9 2151.33  4499.7 2150.09  4869.8 2147.24  4896.8 2145.84
  4940.1 2144.05  4951.3 2140.28  4971.7 2138.31  4981.9 2138.97  4996.6 2134.96
  4997.1 2134.46  5003.4 2134.96  5014.5 2136.26  5055.3 2145.10  5126.8 2147.17
  5179.6 2150.21  5290.9 2156.23  5381.9 2161.43  5412.5 2164.11  5438.5 2168.26
  5463.5 2169.33  5473.7 2172.33  5489.2 2181.54  5494.3 2178.96  5514.5 2184.86
#Mann=8,-1,0
  3983.2    0.07       0  4390.9   0.035       0  4499.7    0.07       0
  4896.8   0.035       0  4996.6   0.035       0  5003.4   0.035       0
  5179.6   0.035       0  5290.9    0.07       0
Bank Sta=4996.6,5003.4
Exp/Cntr=0.3,0.1

Type RM Length L Ch R = 1,5000,500,500,500
BEGIN DESCRIPTION:
Bull Creek Trib03 10.0
END DESCRIPTION:
XS GIS Cut Line= 3
      1332305.03      6917187.98      1333304.86      6916547.47
      1333554.98      6916637.99
#Sta/Elev= 30
  3812.6 2154.57  3878.0 2153.27  3986.7 2150.95  4029.0 2151.04  4116.9 2149.46
  4275.7 2147.93  4289.4 2147.28  4549.8 2145.68  4695.4 2143.88  4739.2 2143.79
  4869.5 2144.02  4892.2 2145.04  4913.3 2143.61  4919.3 2142.49  4934.5 2142.03
  4940.8 2140.14  4949.7 2138.64  4976.8 2137.46  4992.0 2134.65  4993.6 2133.20
  4994.1 2132.70  5000.2 2132.70  5000.7 2133.20  5032.1 2134.48  5041.5 2135.97
  5046.8 2138.19  5085.2 2144.49  5133.4 2148.26  5159.3 2149.09  5266.0 2153.48
#Mann=7,-1,0
  3812.6    0.07       0  3878.0   0.035       0  4695.4    0.07       0
  4739.2   0.035       0  4993.6   0.035       0  5000.7   0.035       0
  5159.3    0.07       0
Bank Sta=4993.6,5000.7
Exp/Cntr=0.3,0.1

Type RM Length L Ch R = 1,4500,500,500,500
BEGIN DESCRIPTION:
Bull Creek Trib03 9.0
END DESCRIPTION:
XS GIS Cut Line= 3
      1332254.98      6917288.01      1333264.33      6916929.28
      1333505.01      6916888.00
#Sta/Elev= 30
  3928.8 2156.18  3950.0 2154.76  4016.8 2153.46  4321.5 2148.55  4703.6 2145.44
  4756.6 2143.64  4776.2 2144.49  4830.9 2142.47  4837.9 2140.52  4843.2 2140.67
  4884.0 2135.15  4899.6 2135.20  4905.2 2133.42  4925.1 2131.95  4961.3 2131.20
  4986.8 2132.61  4994.2 2131.20  4994.7 2130.70  5001.3 2131.20  5021.0 2132.52
  5036.7 2136.23  5041.7 2132.59  5051.4 2134.49  5091.6 2138.47  5096.7 2137.66
  5102.1 2139.80  5122.4 2142.27  5142.7 2147.26  5184.4 2149.53  5244.2 2152.73
#Mann=5,-1,0
  3928.8    0.07       0  4016.8   0.035       0  4994.2   0.035       0
  5001.3   0.035       0  5184.4    0.07       0
Bank Sta=4994.2,5001.3
Exp/Cntr=0.3,0.1

Type RM Length L Ch R = 1,4000,500,500,500
BEGIN DESCRIPTION:
Bull Creek Trib03 8.0
END DESCRIPTION:
XS GIS Cut Line= 3
      1332504.98      6917288.00      1333355.01      6917379.13
      1333755.00      6916888.00
#Sta/Elev= 30
  4145.1 2150.38  4154.2 2150.25  4255.7 2148.20  4566.2 2145.13  4648.0 2144.83
  4919.5 2139.45  4969.8 2131.09  4997.5 2129.76  5022.3 2130.55  5028.7 2129.33
  5036.6 2129.84  5039.4 2128.25  5039.9 2127.75  5046.7 2128.25  5071.8 2132.68
  5078.8 2135.24  5114.9 2140.54  5164.5 2140.26  5207.6 2144.39  5469.7 2156.88
  5533.6 2161.68  5562.3 2165.03  5576.7 2169.08  5583.1 2169.72  5591.0 2173.02
  5597.5 2174.11  5605.4 2179.01  5611.9 2179.25  5619.8 2182.13  5633.4 2181.65
#Mann=5,-1,0
  4145.1   0.035       0  4154.2    0.07       0  4566.2   0.035       0
  5039.4   0.035       0  5046.7   0.035       0
Bank Sta=5039.4,5046.7
Exp/Cntr=0.3,0.1

Type RM Length L Ch R = 1,3500,500,500,500
BEGIN DESCRIPTION:
Bull Creek Trib03 7.0
END DESCRIPTION:
XS GIS Cut Line= 3
      1332605.01      6918787.99      1333459.57      6917842.43
      1333854.98      6917488.01
#Sta/Elev= 30
  3725.5 2170.87  3810.6 2165.64  3846.9 2163.78  4185.4 2149.12  4511.2 2141.55
  4766.1 2138.42  4822.8 2135.13  4858.0 2130.41  4914.8 2135.46  4929.0 2133.67
  4950.6 2135.79  4985.7 2132.89  4992.5 2130.80  4999.6 2126.28  5003.6 2125.77
  5004.1 2125.27  5010.9 2125.77  5028.3 2131.70  5063.4 2134.33  5091.8 2139.25
  5226.4 2139.04  5325.8 2142.06  5354.2 2145.50  5446.2 2149.92  5481.3 2154.37
  5495.5 2159.03  5503.0 2163.91  5509.7 2164.43  5517.2 2168.10  5531.0 2169.60
#Mann=5,-1,0
  3725.5   0.035       0  3810.6    0.07       0  3846.9   0.035       0
  5003.6   0.035       0  5010.9   0.035       0
Bank Sta=5003.6,5010.9
Exp/Cntr=0.3,0.1

Type RM Length L Ch R = 1,3000,500,500,500
BEGIN DESCRIPTION:
Bull Creek Trib03 6.0
END DESCRIPTION:
XS GIS Cut Line= 3
      1332705.00      6918888.00      1333704.05      6918252.39
      1333954.98      6917738.03
#Sta/Elev= 30
  3815.9 2173.47  3881.1 2170.19  3910.7 2170.46  3953.9 2163.23  3975.1 2162.88
  4001.3 2160.45  4112.2 2156.28  4229.9 2149.36  4402.7 2142.71  4633.7 2137.00
  4845.5 2135.87  4918.2 2131.43  4945.4 2132.16  4981.8 2129.84  4989.3 2128.62
  4995.5 2123.97  4996.0 2123.47  5003.4 2123.97  5012.0 2124.29  5027.1 2129.36
  5079.6 2136.23  5182.3 2136.51  5400.6 2139.86  5423.1 2141.77  5445.6 2141.44
  5483.3 2143.93  5505.6 2144.01  5518.8 2145.64  5550.1 2145.87  5572.3 2148.24
#Mann=5,-1,0
  3815.9    0.07       0  4001.3   0.035       0  4995.5   0.035       0
  5003.4   0.035       0  5182.3    0.07       0
Bank Sta=4995.5,5003.4
Exp/Cntr=0.3,0.1

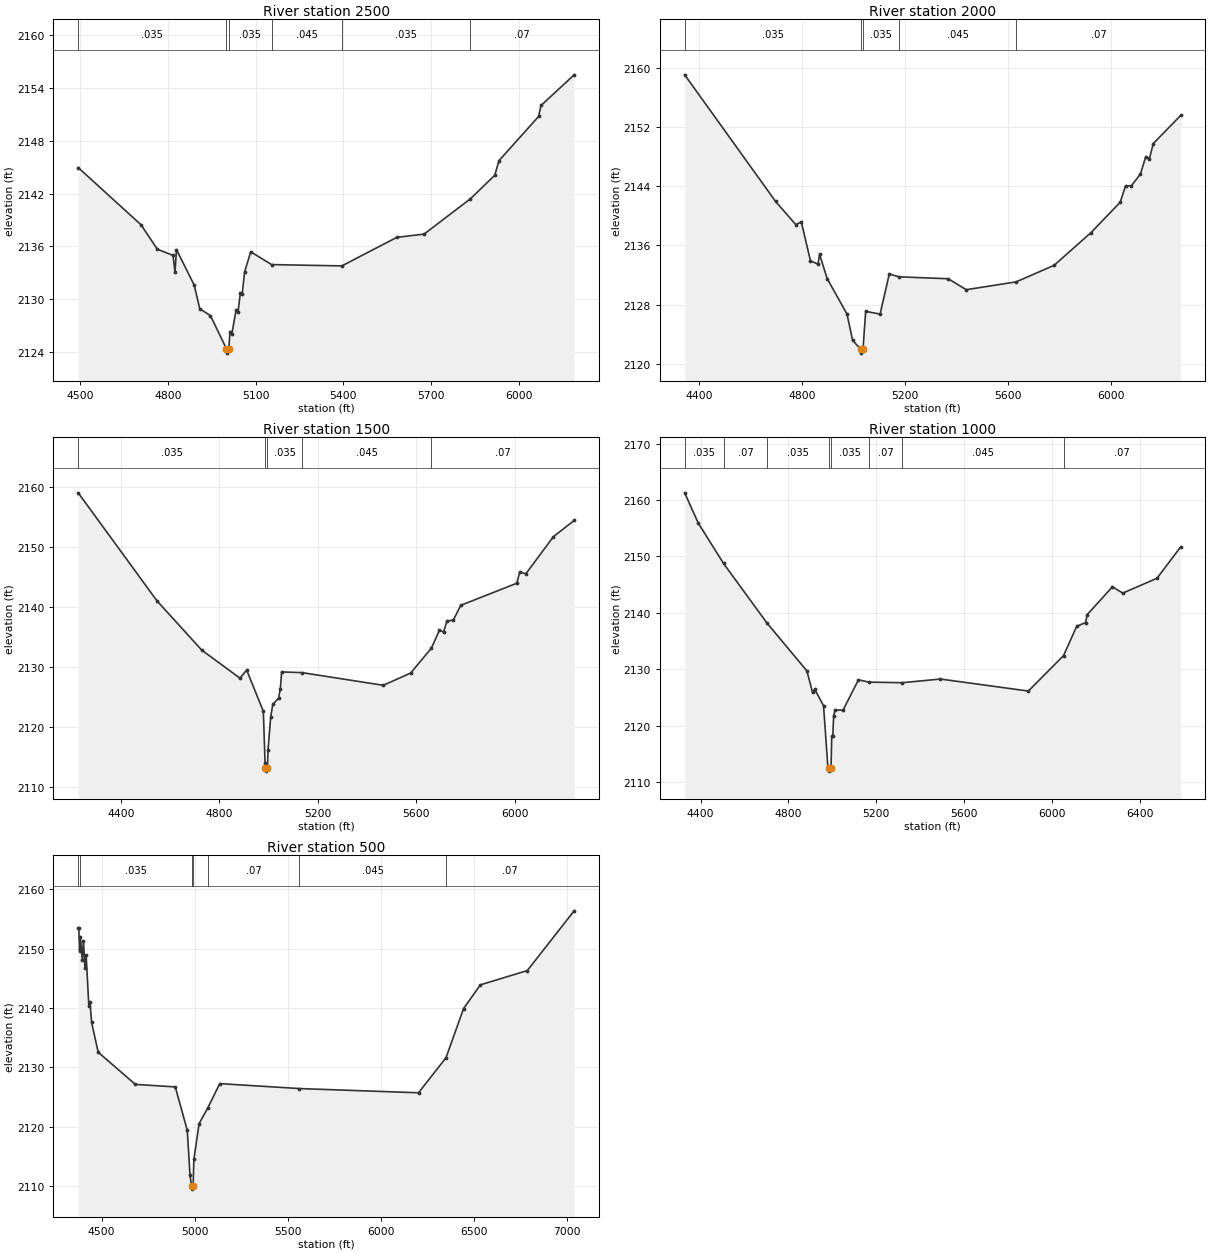
Type RM Length L Ch R = 1,2500,500,500,500
BEGIN DESCRIPTION:
Bull Creek Trib03 5.0
END DESCRIPTION:
XS GIS Cut Line= 3
      1333204.96      6918788.01      1333704.98      6918704.18
      1334654.98      6917988.02
#Sta/Elev= 30
  4493.0 2144.95  4707.9 2138.46  4763.5 2135.69  4817.5 2134.98  4824.1 2133.06
  4829.2 2135.64  4889.9 2131.61  4908.8 2128.93  4945.5 2128.14  5000.1 2124.39
  5000.6 2123.89  5008.1 2124.39  5012.4 2126.34  5018.7 2126.09  5033.3 2128.82
  5039.5 2128.51  5047.8 2130.75  5054.1 2130.64  5062.4 2133.12  5083.2 2135.39
  5154.7 2133.94  5394.9 2133.79  5582.9 2137.03  5676.3 2137.40  5834.2 2141.39
  5918.1 2144.08  5932.6 2145.74  6067.9 2150.75  6076.3 2152.00  6189.7 2155.48
#Mann=6,-1,0
  4493.0   0.035       0  5000.1   0.035       0  5008.1   0.035       0
  5154.7   0.045       0  5394.9   0.035       0  5834.2    0.07       0
Bank Sta=5000.1,5008.1
Exp/Cntr=0.3,0.1

Type RM Length L Ch R = 1,2000,500,500,500
BEGIN DESCRIPTION:
Bull Creek Trib03 4.0
END DESCRIPTION:
XS GIS Cut Line= 3
      1333479.09      6919665.60      1333868.70      6919136.96
      1334655.00      6918138.00
#Sta/Elev= 30
  4343.3 2159.04  4696.6 2141.94  4775.1 2138.81  4796.8 2139.16  4832.3 2133.91
  4861.6 2133.46  4867.8 2134.79  4897.1 2131.52  4974.3 2126.72  4996.2 2123.17
  5028.4 2121.94  5028.9 2121.44  5036.5 2121.94  5046.9 2127.08  5103.0 2126.72
  5138.7 2132.13  5176.6 2131.75  5367.7 2131.49  5438.2 2130.01  5632.2 2131.07
  5779.8 2133.31  5922.5 2137.71  6036.4 2141.82  6057.2 2144.04  6079.7 2144.04
  6115.0 2145.64  6135.8 2147.98  6150.2 2147.72  6164.7 2149.74  6271.3 2153.55
#Mann=5,-1,0
  4343.3   0.035       0  5028.4   0.035       0  5036.5   0.035       0
  5176.6   0.045       0  5632.2    0.07       0
Bank Sta=5028.4,5036.5
Exp/Cntr=0.3,0.1

Type RM Length L Ch R = 1,1500,500,500,500
BEGIN DESCRIPTION:
Bull Creek Trib03 3.0
END DESCRIPTION:
XS GIS Cut Line= 3
      1333583.31      6919682.93      1334252.93      6919296.75
      1334677.04      6918129.09
#Sta/Elev= 30
  4227.0 2158.95  4546.8 2140.99  4729.2 2132.77  4884.3 2128.11  4911.6 2129.46
  4979.3 2122.58  4986.3 2114.03  4988.0 2113.14  4988.5 2112.64  4996.1 2113.14
  4998.3 2116.18  5009.3 2121.70  5017.7 2123.75  5041.2 2124.78  5048.3 2126.34
  5053.6 2129.15  5137.1 2129.03  5466.8 2126.92  5577.9 2128.96  5662.1 2133.10
  5695.0 2136.11  5711.5 2135.79  5725.6 2137.65  5750.9 2137.75  5781.5 2140.23
  6009.4 2143.91  6021.0 2145.77  6046.3 2145.49  6158.1 2151.66  6242.3 2154.35
#Mann=5,-1,0
  4227.0   0.035       0  4988.0   0.035       0  4996.1   0.035       0
  5137.1   0.045       0  5662.1    0.07       0
Bank Sta=4988,4996.1
Exp/Cntr=0.3,0.1

Type RM Length L Ch R = 1,1000,500,500,500
BEGIN DESCRIPTION:
Bull Creek Trib03 2.0
END DESCRIPTION:
XS GIS Cut Line= 4
      1333583.29      6919743.71      1334254.56      6919706.56
      1334416.61      6919552.74      1334668.22      6918212.28
#Sta/Elev= 30
  4327.7 2161.26  4389.5 2155.90  4504.8 2148.74  4703.4 2138.15  4884.4 2129.71
  4910.3 2125.90  4920.3 2126.44  4960.4 2123.52  4980.4 2112.52  4986.4 2112.44
  4986.9 2111.94  4994.5 2112.44  4997.7 2118.11  5002.6 2118.11  5006.3 2121.74
  5013.6 2122.79  5048.8 2122.73  5119.6 2128.13  5167.3 2127.71  5318.7 2127.61
  5492.8 2128.26  5893.5 2126.13  6053.8 2132.41  6113.8 2137.61  6154.1 2138.26
  6161.3 2139.66  6276.5 2144.60  6324.0 2143.49  6479.7 2146.12  6587.3 2151.67
#Mann=8,-1,0
  4327.7   0.035       0  4504.8    0.07       0  4703.4   0.035       0
  4986.4   0.035       0  4994.5   0.035       0  5167.3    0.07       0
  5318.7   0.045       0  6053.8    0.07       0
Bank Sta=4986.4,4994.5
Exp/Cntr=0.3,0.1

Type RM Length L Ch R = 1,500,0,0,0
BEGIN DESCRIPTION:
Bull Creek Trib03 1.0
END DESCRIPTION:
XS GIS Cut Line= 3
      1333955.01      6920487.99      1334455.01      6920111.66
      1334704.99      6918088.04
#Sta/Elev= 30
  4374.2 2153.50  4377.3 2153.50  4381.5 2149.64  4386.0 2151.95  4396.0 2148.16
  4402.3 2151.33  4410.6 2146.70  4416.9 2148.92  4431.4 2140.27  4437.7 2140.95
  4446.0 2137.61  4481.4 2132.56  4681.3 2127.14  4895.8 2126.72  4960.3 2119.40
  4974.9 2111.83  4983.4 2110.01  4983.9 2109.51  4991.6 2110.01  4995.7 2114.50
  5023.8 2120.54  5070.9 2123.21  5134.7 2127.27  5562.9 2126.44  6202.7 2125.73
  6350.5 2131.63  6444.6 2139.90  6535.2 2143.90  6787.1 2146.30  7039.0 2156.36
#Mann=7,-1,0
  4374.2    0.07       0  4386.0   0.035       0  4983.4   0.035       0
  4991.6   0.035       0  5070.9    0.07       0  5562.9   0.045       0
  6350.5    0.07       0
Bank Sta=4983.4,4991.6
Exp/Cntr=0.3,0.1

Chan Stop Cuts=-1