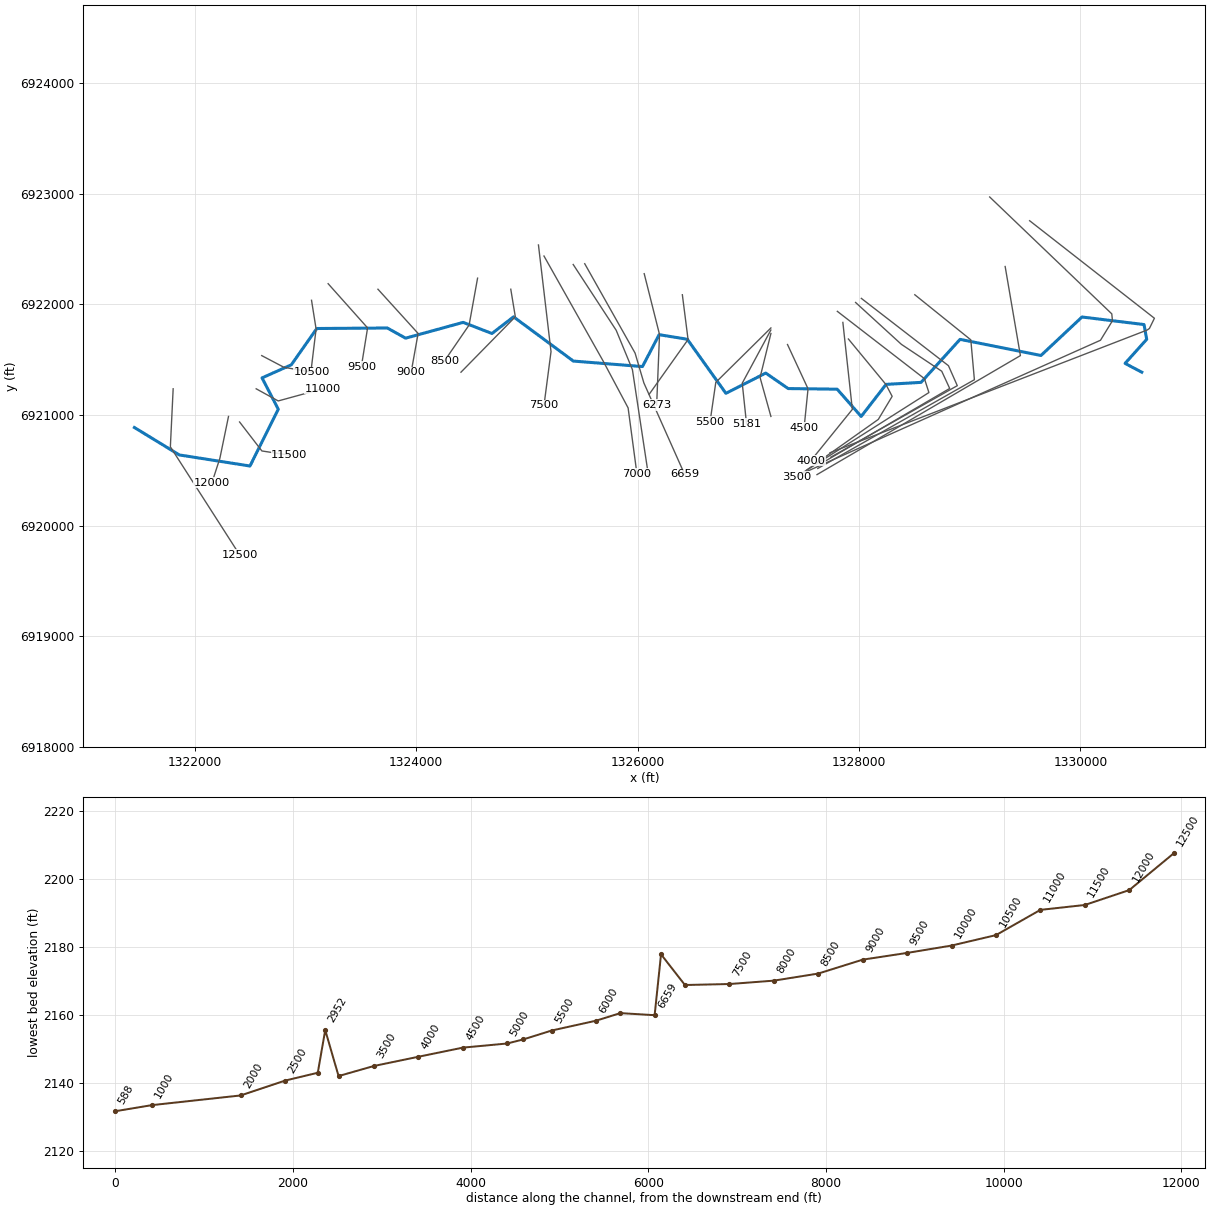
--- Bull Creek Trib04.prj (project) ---

Proj Title=Bull Creek Trib04 Base Level Engineering
Current Plan=p01
Default Exp/Contr=0.3,0.1
English Units
Geom File=g01
Flow File=f01
Plan File=p01
BEGIN DESCRIPTION:
Bull Creek Trib04
END DESCRIPTION:

--- Bull Creek Trib04.p01 (plan) ---

Plan Title=Multiple Run
Short Identifier=Multiple
Geom File=g01
Flow File=f01
Subcritical Flow
K Sum by GR= 0
Std Step Tol= 0.01
Critical Tol= 0.01
Num of Std Step Trials= 20
Max Error Tol= 0.3
Flow Tol Ratio= 0.001
Split Flow NTrial= 30
Split Flow Tol= 0.02
Split Flow Ratio= 0.02
Log Output Level= 0
Friction Slope Method= 1
Unsteady Friction Slope Method= 2
Unsteady Bridges Friction Slope Method= 1
Parabolic Critical Depth
Global Vel Dist=  1 , 1 , 1
Global Log Level= 0
CheckData=True
Encroach Param= -1, 0, 0, 0
BEGIN DESCRIPTION:
Multiple Run
END DESCRIPTION:

--- Bull Creek Trib04.f01 (steady flow) ---

Flow Title=Multiple
Number of Profiles=7
Profile Names=10-year,25-year,50-year,1pct_min,100-year,1pct_plu,500-year
River Rch & RM= Bull Creek Trib0,Reach-1,12500
     303     436     550     345     689    1374    1094
River Rch & RM= Bull Creek Trib0,Reach-1,9000
     412     599     761     480     957    1909    1536
Boundary for River Rch & Prof#=Bull Creek Trib0,Reach-1,1
Up Type=0
Dn Type=3
Dn Slope=0.005
Boundary for River Rch & Prof#=Bull Creek Trib0,Reach-1,2
Up Type=0
Dn Type=3
Dn Slope=0.005
Boundary for River Rch & Prof#=Bull Creek Trib0,Reach-1,3
Up Type=0
Dn Type=3
Dn Slope=0.005
Boundary for River Rch & Prof#=Bull Creek Trib0,Reach-1,4
Up Type=0
Dn Type=3
Dn Slope=0.005
Boundary for River Rch & Prof#=Bull Creek Trib0,Reach-1,5
Up Type=0
Dn Type=3
Dn Slope=0.005
Boundary for River Rch & Prof#=Bull Creek Trib0,Reach-1,6
Up Type=0
Dn Type=3
Dn Slope=0.005
Boundary for River Rch & Prof#=Bull Creek Trib0,Reach-1,7
Up Type=0
Dn Type=3
Dn Slope=0.005

--- Bull Creek Trib04.g01 (geometry) ---

Geom Title=Existing Conditions

River Reach=Bull Creek Trib0,Reach-1
Reach XY= 30
      1321455.00      6920888.00      1321860.86      6920640.07
      1322499.12      6920539.96      1322754.62      6921053.28
      1322608.00      6921336.60      1322872.13      6921454.45
      1323102.71      6921782.90      1323739.79      6921787.49
      1323904.99      6921695.53      1324425.14      6921838.40
      1324684.95      6921737.79      1324879.96      6921888.50
      1325420.22      6921488.52      1326044.73      6921438.96
      1326194.92      6921726.91      1326449.33      6921686.02
      1326798.31      6921196.95      1327158.23      6921380.16
      1327360.86      6921240.06      1327803.55      6921234.47
      1328020.36      6920987.89      1328245.29      6921277.82
      1328561.34      6921296.02      1328913.48      6921684.70
      1329644.57      6921539.05      1330015.43      6921886.95
      1330575.66      6921818.62      1330599.71      6921685.33
      1330404.51      6921467.53      1330555.00      6921388.00

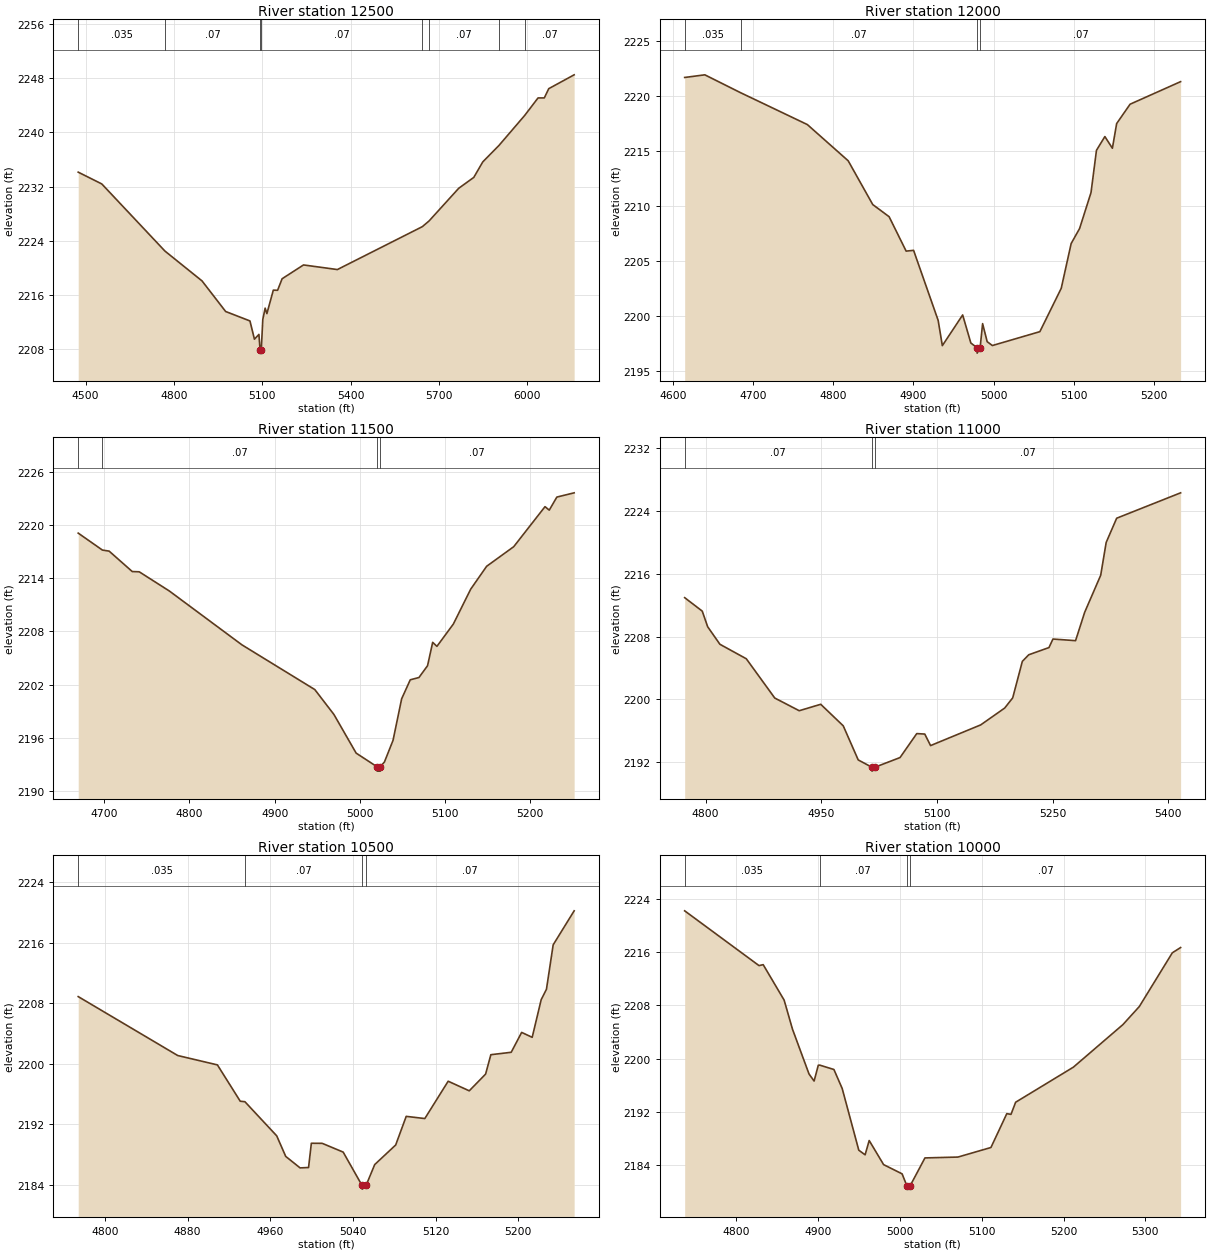
Type RM Length L Ch R = 1,12500,500,500,500
BEGIN DESCRIPTION:
Bull Creek Trib04 25.0
END DESCRIPTION:
XS GIS Cut Line= 3
      1321805.00      6921238.05      1321779.73      6920713.65
      1322404.99      6919738.02
#Sta/Elev= 30
  4475.0 2234.12  4555.1 2232.38  4769.4 2222.48  4895.5 2218.07  4975.6 2213.56
  5058.1 2212.17  5073.3 2209.48  5088.5 2210.18  5092.5 2207.92  5092.7 2207.42
  5096.5 2207.92  5101.7 2212.39  5109.7 2214.06  5115.6 2213.25  5137.4 2216.71
  5152.0 2216.69  5167.2 2218.39  5239.9 2220.43  5354.9 2219.75  5643.4 2226.08
  5666.0 2226.91  5766.9 2231.74  5818.1 2233.35  5848.5 2235.63  5903.5 2238.06
  5991.1 2242.50  6036.2 2245.07  6057.4 2245.07  6072.6 2246.44  6158.8 2248.48
#Mann=8,-1,0
  4475.0   0.035       0  4769.4    0.07       0  5092.5    0.07       0
  5096.5    0.07       0  5643.4   0.035       0  5666.0    0.07       0
  5903.5   0.035       0  5991.1    0.07       0
Bank Sta=5092.5,5096.5
Exp/Cntr=0.3,0.1

Type RM Length L Ch R = 1,12000,500,500,500
BEGIN DESCRIPTION:
Bull Creek Trib04 24.0
END DESCRIPTION:
XS GIS Cut Line= 3
      1322305.01      6920988.04      1322227.14      6920610.28
      1322155.00      6920388.00
#Sta/Elev= 30
  4614.3 2221.68  4639.5 2221.92  4684.3 2220.29  4767.5 2217.40  4818.5 2214.11
  4849.2 2210.13  4869.6 2209.03  4890.9 2205.90  4900.2 2205.97  4930.9 2199.60
  4936.1 2197.31  4961.5 2200.10  4971.7 2197.55  4979.3 2197.13  4979.6 2196.63
  4983.3 2197.13  4986.4 2199.31  4992.1 2197.67  4998.6 2197.32  5057.9 2198.58
  5084.6 2202.52  5097.0 2206.59  5107.5 2207.95  5121.8 2211.22  5128.6 2215.06
  5139.1 2216.31  5148.5 2215.25  5153.8 2217.49  5170.6 2219.25  5233.7 2221.30
#Mann=4,-1,0
  4614.3   0.035       0  4684.3    0.07       0  4979.3    0.07       0
  4983.3    0.07       0
Bank Sta=4979.3,4983.3
Exp/Cntr=0.3,0.1

Type RM Length L Ch R = 1,11500,500,500,500
BEGIN DESCRIPTION:
Bull Creek Trib04 23.0
END DESCRIPTION:
XS GIS Cut Line= 3
      1322404.99      6920938.01      1322606.54      6920676.08
      1322855.04      6920637.99
#Sta/Elev= 30
  4669.5 2219.08  4697.9 2217.17  4705.8 2217.05  4732.9 2214.75  4741.1 2214.72
  4776.4 2212.56  4861.6 2206.49  4947.1 2201.45  4969.5 2198.65  4995.6 2194.29
  5020.0 2192.76  5020.3 2192.26  5023.8 2192.26  5024.0 2192.76  5028.8 2193.29
  5038.9 2195.73  5049.0 2200.41  5059.1 2202.55  5069.3 2202.81  5079.4 2204.14
  5085.4 2206.77  5090.4 2206.32  5109.7 2208.84  5130.0 2212.76  5148.7 2215.34
  5180.5 2217.55  5217.2 2222.06  5222.2 2221.67  5231.1 2223.14  5251.4 2223.62
#Mann=4,-1,0
  4669.5   0.035       0  4697.9    0.07       0  5020.0    0.07       0
  5024.0    0.07       0
Bank Sta=5020,5024
Exp/Cntr=0.3,0.1

Type RM Length L Ch R = 1,11000,500,500,500
BEGIN DESCRIPTION:
Bull Creek Trib04 22.0
END DESCRIPTION:
XS GIS Cut Line= 3
      1322555.02      6921237.99      1322753.92      6921128.17
      1323154.96      6921237.99
#Sta/Elev= 30
  4772.8 2212.96  4795.6 2211.24  4802.6 2209.25  4818.5 2207.01  4852.7 2205.16
  4889.6 2200.15  4921.3 2198.53  4949.2 2199.35  4978.4 2196.60  4997.8 2192.25
  5015.5 2191.32  5015.7 2190.82  5019.5 2191.32  5052.0 2192.55  5073.7 2195.61
  5084.1 2195.55  5091.6 2194.08  5156.6 2196.72  5187.7 2198.87  5198.1 2200.17
  5210.6 2204.83  5218.9 2205.67  5245.1 2206.59  5250.3 2207.68  5279.6 2207.47
  5291.4 2211.09  5312.2 2215.82  5319.3 2220.01  5332.9 2223.10  5415.8 2226.34
#Mann=3,-1,0
  4772.8    0.07       0  5015.5    0.07       0  5019.5    0.07       0
Bank Sta=5015.5,5019.5
Exp/Cntr=0.3,0.1

Type RM Length L Ch R = 1,10500,500,500,500
BEGIN DESCRIPTION:
Bull Creek Trib04 21.0
END DESCRIPTION:
XS GIS Cut Line= 3
      1322605.02      6921537.99      1322804.84      6921432.82
      1323054.96      6921388.01
#Sta/Elev= 30
  4774.2 2208.88  4870.5 2201.08  4908.9 2199.84  4931.0 2195.03  4935.5 2194.97
  4966.3 2190.45  4975.0 2187.73  4988.9 2186.21  4997.1 2186.26  4999.8 2189.47
  5010.3 2189.46  5030.6 2188.30  5048.8 2183.90  5049.0 2183.40  5052.8 2183.90
  5061.1 2186.65  5081.4 2189.24  5091.6 2193.03  5109.6 2192.74  5132.2 2197.68
  5152.6 2196.41  5168.4 2198.62  5173.5 2201.19  5193.2 2201.51  5203.3 2204.14
  5213.5 2203.49  5222.2 2208.47  5227.3 2209.85  5233.8 2215.73  5254.1 2220.23
#Mann=4,-1,0
  4774.2   0.035       0  4935.5    0.07       0  5048.8    0.07       0
  5052.8    0.07       0
Bank Sta=5048.8,5052.8
Exp/Cntr=0.3,0.1

Type RM Length L Ch R = 1,10000,500,500,500
BEGIN DESCRIPTION:
Bull Creek Trib04 20.0
END DESCRIPTION:
XS GIS Cut Line= 3
      1323055.00      6922038.02      1323096.24      6921778.48
      1323055.00      6921437.97
#Sta/Elev= 30
  4737.2 2222.25  4828.0 2214.00  4833.1 2214.14  4858.7 2208.80  4868.9 2204.42
  4889.1 2197.67  4895.3 2196.61  4900.4 2198.99  4902.1 2199.01  4919.5 2198.35
  4929.6 2195.49  4949.9 2186.19  4957.6 2185.50  4962.6 2187.65  4980.2 2184.02
  5002.8 2182.63  5008.6 2180.83  5008.8 2180.33  5012.6 2180.83  5030.7 2185.03
  5071.0 2185.16  5111.3 2186.60  5130.7 2191.70  5135.8 2191.59  5141.5 2193.42
  5212.0 2198.70  5272.5 2205.11  5292.6 2207.84  5332.9 2215.93  5343.0 2216.72
#Mann=4,-1,0
  4737.2   0.035       0  4902.1    0.07       0  5008.6    0.07       0
  5012.6    0.07       0
Bank Sta=5008.6,5012.6
Exp/Cntr=0.3,0.1

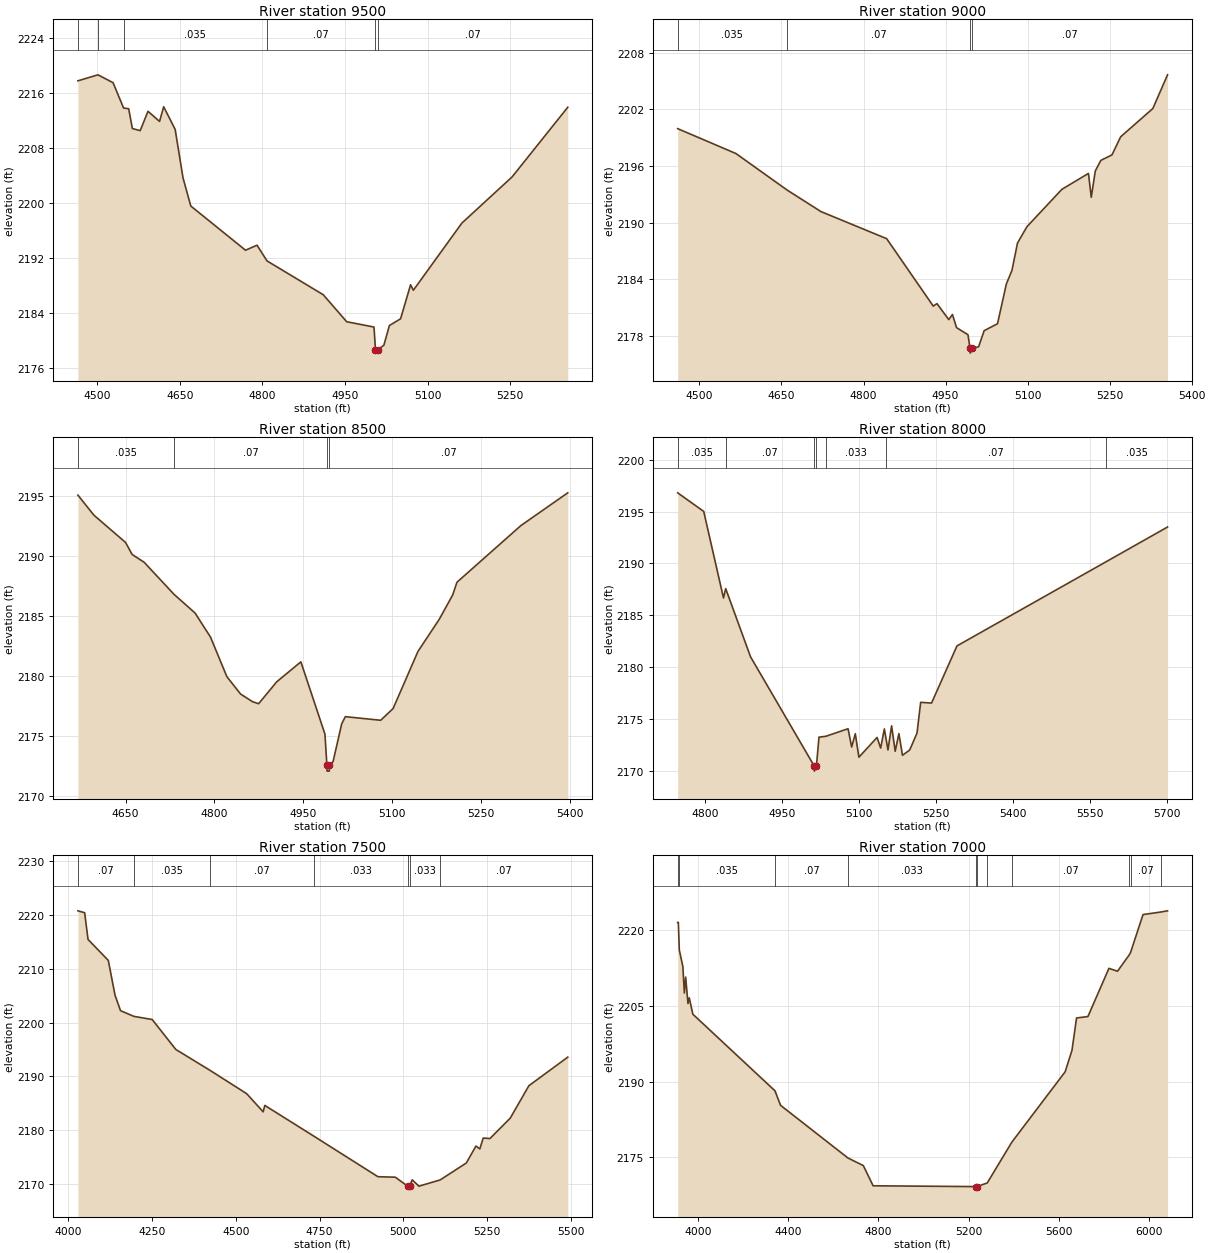
Type RM Length L Ch R = 1,9500,500,500,500
BEGIN DESCRIPTION:
Bull Creek Trib04 19.0
END DESCRIPTION:
XS GIS Cut Line= 3
      1323205.03      6922187.96      1323561.49      6921788.34
      1323504.99      6921437.97
#Sta/Elev= 30
  4464.5 2217.73  4500.9 2218.60  4528.4 2217.46  4547.5 2213.78  4556.8 2213.67
  4563.5 2210.80  4577.7 2210.49  4591.9 2213.30  4612.9 2211.83  4620.4 2213.96
  4641.3 2210.67  4655.5 2203.65  4669.7 2199.54  4769.2 2193.12  4790.1 2193.85
  4808.2 2191.57  4910.5 2186.65  4953.1 2182.73  5002.7 2181.96  5005.4 2178.67
  5005.6 2178.17  5009.4 2178.67  5020.6 2179.31  5030.7 2182.18  5051.0 2183.16
  5069.2 2188.10  5074.2 2187.30  5162.4 2197.06  5253.6 2203.76  5354.9 2213.89
#Mann=6,-1,0
  4464.5   0.035       0  4500.9    0.07       0  4547.5   0.035       0
  4808.2    0.07       0  5005.4    0.07       0  5009.4    0.07       0
Bank Sta=5005.4,5009.4
Exp/Cntr=0.3,0.1

Type RM Length L Ch R = 1,9000,500,500,500
BEGIN DESCRIPTION:
Bull Creek Trib04 18.0
END DESCRIPTION:
XS GIS Cut Line= 3
      1323655.00      6922138.00      1324017.78      6921738.27
      1323954.99      6921387.95
#Sta/Elev= 30
  4460.2 2199.96  4566.6 2197.33  4660.3 2193.46  4722.1 2191.18  4842.3 2188.31
  4927.5 2181.17  4934.3 2181.43  4955.9 2179.74  4962.6 2180.28  4970.1 2178.89
  4991.0 2178.14  4994.8 2176.69  4995.1 2176.19  4998.8 2176.69  5010.4 2176.86
  5020.6 2178.57  5045.0 2179.30  5061.2 2183.52  5071.4 2184.95  5081.5 2187.84
  5098.8 2189.58  5162.8 2193.54  5211.3 2195.22  5216.4 2192.69  5223.8 2195.48
  5233.9 2196.60  5254.3 2197.18  5270.2 2199.10  5329.0 2202.09  5355.9 2205.66
#Mann=4,-1,0
  4460.2   0.035       0  4660.3    0.07       0  4994.8    0.07       0
  4998.8    0.07       0
Bank Sta=4994.8,4998.8
Exp/Cntr=0.3,0.1

Type RM Length L Ch R = 1,8500,500,500,500
BEGIN DESCRIPTION:
Bull Creek Trib04 17.0
END DESCRIPTION:
XS GIS Cut Line= 3
      1324555.00      6922238.01      1324478.60      6921814.54
      1324254.98      6921487.97
#Sta/Elev= 30
  4569.7 2195.06  4596.5 2193.40  4650.1 2191.12  4661.2 2190.12  4681.5 2189.47
  4731.7 2186.81  4767.3 2185.25  4793.3 2183.25  4820.9 2179.96  4844.1 2178.51
  4864.4 2177.87  4874.5 2177.71  4905.0 2179.53  4945.7 2181.19  4986.3 2175.18
  4989.6 2172.60  4989.9 2172.10  4993.6 2172.10  4993.9 2172.60  5000.0 2172.89
  5014.6 2176.04  5020.7 2176.63  5080.3 2176.33  5101.3 2177.31  5143.2 2182.06
  5179.1 2184.73  5201.8 2186.76  5208.9 2187.81  5316.6 2192.52  5395.8 2195.25
#Mann=4,-1,0
  4569.7   0.035       0  4731.7    0.07       0  4989.6    0.07       0
  4993.9    0.07       0
Bank Sta=4989.6,4993.9
Exp/Cntr=0.3,0.1

Type RM Length L Ch R = 1,8000,500,500,500
BEGIN DESCRIPTION:
Bull Creek Trib04 16.0
END DESCRIPTION:
XS GIS Cut Line= 3
      1324854.99      6922138.05      1324896.12      6921888.82
      1324405.03      6921388.03
#Sta/Elev= 30
  4747.4 2196.80  4798.1 2195.01  4836.6 2186.68  4840.9 2187.58  4889.3 2181.02
  5013.2 2170.52  5013.5 2170.02  5017.6 2170.52  5022.6 2173.29  5035.8 2173.37
  5079.2 2174.10  5086.2 2172.34  5093.3 2173.62  5100.3 2171.36  5135.7 2173.26
  5142.7 2172.24  5149.9 2174.08  5153.4 2173.07  5156.9 2172.06  5164.0 2174.38
  5171.0 2171.93  5178.2 2173.63  5185.2 2171.54  5199.3 2172.06  5213.5 2173.68
  5220.6 2176.64  5241.8 2176.57  5291.3 2182.07  5581.8 2190.17  5701.4 2193.51
#Mann=7,-1,0
  4747.4   0.035       0  4840.9    0.07       0  5013.2    0.07       0
  5017.6    0.07       0  5035.8   0.033       0  5153.4    0.07       0
  5581.8   0.035       0
Bank Sta=5013.2,5017.6
Exp/Cntr=0.3,0.1

Type RM Length L Ch R = 1,7500,500,500,500
BEGIN DESCRIPTION:
Bull Creek Trib04 15.0
END DESCRIPTION:
XS GIS Cut Line= 3
      1325105.00      6922537.99      1325218.47      6921573.94
      1325155.00      6921087.97
#Sta/Elev= 30
  4029.3 2220.80  4049.4 2220.45  4059.5 2215.48  4119.9 2211.58  4140.0 2205.11
  4156.4 2202.23  4196.2 2201.17  4250.8 2200.58  4321.3 2195.01  4423.2 2191.13
  4532.7 2186.78  4581.7 2183.41  4586.7 2184.60  4734.3 2178.83  4924.0 2171.34
  4975.8 2171.25  5013.8 2169.53  5014.1 2169.03  5018.3 2169.53  5026.2 2170.76
  5046.3 2169.58  5109.6 2170.74  5187.5 2173.89  5216.3 2177.04  5227.9 2176.51
  5237.9 2178.53  5258.1 2178.44  5318.6 2182.24  5374.2 2188.27  5490.1 2193.58
#Mann=7,-1,0
  4029.3    0.07       0  4196.2   0.035       0  4423.2    0.07       0
  4734.3   0.033       0  5013.8   0.033       0  5018.3   0.033       0
  5109.6    0.07       0
Bank Sta=5013.8,5018.3
Exp/Cntr=0.3,0.1

Type RM Length L Ch R = 1,7000,269,269,269
BEGIN DESCRIPTION:
Bull Creek Trib04 14.0
END DESCRIPTION:
XS GIS Cut Line= 4
      1325155.00      6922438.01      1325689.84      6921488.02
      1325914.92      6921065.41      1325994.79      6920468.14
#Sta/Elev= 30
  3909.8 2221.46  3912.7 2221.46  3917.0 2216.00  3932.8 2212.74  3939.4 2207.51
  3945.2 2210.65  3955.4 2205.43  3961.1 2206.55  3977.0 2203.32  4341.2 2188.17
  4365.8 2185.31  4664.4 2174.90  4732.8 2173.39  4776.2 2169.40  5230.9 2169.24
  5231.3 2168.74  5235.7 2169.24  5282.1 2169.96  5391.4 2178.04  5627.5 2191.93
  5657.8 2196.19  5678.0 2202.57  5728.4 2202.85  5821.6 2212.38  5859.6 2211.81
  5911.4 2215.03  5917.3 2215.50  5972.7 2223.01  6051.0 2223.51  6081.4 2223.75
#Mann=11,-1,0
  3909.8    0.07       0  3917.0   0.035       0  4341.2    0.07       0
  4664.4   0.033       0  5230.9   0.033       0  5235.7   0.033       0
  5282.1   0.035       0  5391.4    0.07       0  5911.4   0.035       0
  5917.3    0.07       0  6051.0   0.035       0
Bank Sta=5230.9,5235.7
Exp/Cntr=0.3,0.1

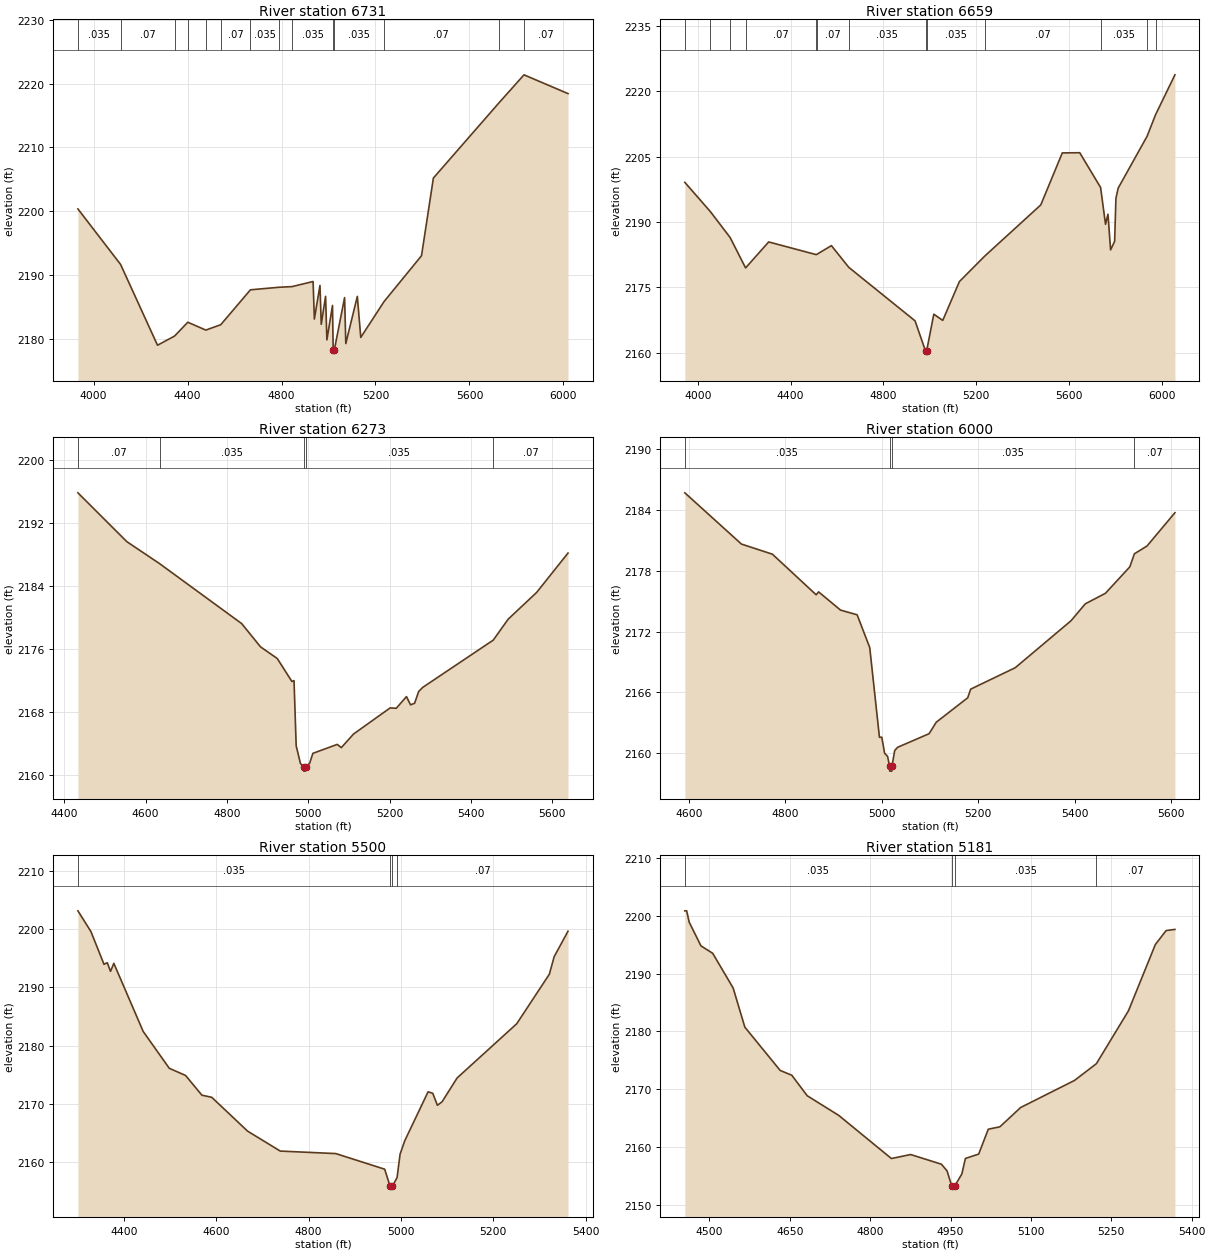
Type RM Length L Ch R = 1,6731,72,72,72
BEGIN DESCRIPTION:
Bull Creek Trib04 13.6
END DESCRIPTION:
XS GIS Cut Line= 4
      1325418.91      6922361.57      1325807.28      6921766.80
      1325953.72      6921411.63      1326102.19      6920431.53
#Sta/Elev= 30
  3933.5 2200.35  4115.2 2191.65  4272.2 2179.00  4344.8 2180.43  4401.1 2182.60
  4477.8 2181.37  4541.3 2182.21  4667.8 2187.68  4790.0 2188.08  4844.7 2188.18
  4934.4 2188.98  4939.8 2183.10  4963.7 2188.37  4969.1 2182.27  4987.6 2186.66
  4993.1 2179.84  5017.0 2185.23  5019.9 2178.26  5020.3 2177.76  5024.8 2178.26
  5068.5 2186.46  5073.6 2179.26  5122.7 2186.65  5137.3 2180.22  5235.9 2185.81
  5395.8 2193.02  5446.4 2205.19  5724.1 2216.91  5832.0 2221.36  6019.3 2218.42
#Mann=14,-1,0
  3933.5   0.035       0  4115.2    0.07       0  4344.8   0.035       0
  4401.1    0.07       0  4477.8   0.035       0  4541.3    0.07       0
  4667.8   0.035       0  4790.0   0.033       0  4844.7   0.035       0
  5019.9   0.035       0  5024.8   0.035       0  5235.9    0.07       0
  5724.1   0.035       0  5832.0    0.07       0
Bank Sta=5019.9,5024.8
Exp/Cntr=0.3,0.1

Type RM Length L Ch R = 1,6659,386,386,386
BEGIN DESCRIPTION:
Bull Creek Trib04 13.5
END DESCRIPTION:
XS GIS Cut Line= 4
      1325523.06      6922368.54      1325978.07      6921560.35
      1326057.28      6921291.10      1326425.35      6920464.69
#Sta/Elev= 30
  3944.4 2199.11  4054.3 2192.40  4139.7 2186.43  4206.3 2179.45  4305.8 2185.42
  4509.5 2182.52  4512.2 2182.53  4576.2 2184.57  4651.2 2179.58  4936.9 2167.29
  4981.9 2160.37  4982.3 2159.87  4986.8 2160.37  5017.7 2168.82  5056.3 2167.39
  5128.2 2176.32  5236.9 2182.15  5478.8 2193.92  5571.7 2205.88  5646.9 2205.92
  5736.8 2197.93  5758.0 2189.47  5768.6 2191.79  5779.9 2183.59  5797.3 2185.56
  5802.8 2195.43  5812.7 2197.80  5937.0 2209.68  5973.6 2214.64  6057.2 2223.82
#Mann=13,-1,0
  3944.4   0.035       0  4054.3    0.07       0  4139.7   0.035       0
  4206.3    0.07       0  4509.5   0.035       0  4512.2    0.07       0
  4651.2   0.035       0  4981.9   0.035       0  4986.8   0.035       0
  5236.9    0.07       0  5736.8   0.035       0  5937.0    0.07       0
  5973.6   0.035       0
Bank Sta=4981.9,4986.8
Exp/Cntr=0.3,0.1

Type RM Length L Ch R = 1,6273,273,273,273
BEGIN DESCRIPTION:
Bull Creek Trib04 13.0
END DESCRIPTION:
XS GIS Cut Line= 3
      1326060.33      6922278.50      1326198.78      6921728.60
      1326172.81      6921091.09
#Sta/Elev= 30
  4433.4 2195.87  4553.7 2189.66  4634.1 2186.87  4836.1 2179.24  4882.5 2176.28
  4923.6 2174.80  4959.6 2171.88  4964.8 2171.99  4970.1 2163.71  4980.5 2161.47
  4988.3 2160.98  4988.7 2160.48  4992.9 2160.48  4993.2 2160.98  5003.3 2161.49
  5011.1 2162.74  5071.1 2163.88  5081.1 2163.47  5111.2 2165.20  5201.2 2168.52
  5216.2 2168.47  5241.3 2169.96  5251.3 2168.91  5261.3 2169.11  5271.3 2170.61
  5281.3 2171.13  5454.7 2177.14  5491.5 2179.81  5561.5 2183.21  5638.5 2188.21
#Mann=5,-1,0
  4433.4    0.07       0  4634.1   0.035       0  4988.3   0.035       0
  4993.2   0.035       0  5454.7    0.07       0
Bank Sta=4988.3,4993.2
Exp/Cntr=0.3,0.1

Type RM Length L Ch R = 1,6000,500,500,500
BEGIN DESCRIPTION:
Bull Creek Trib04 12.0
END DESCRIPTION:
XS GIS Cut Line= 3
      1326405.00      6922088.02      1326456.56      6921683.19
      1326105.00      6921188.00
#Sta/Elev= 30
  4591.9 2185.68  4709.2 2180.63  4773.4 2179.63  4864.0 2175.63  4869.0 2175.92
  4914.5 2174.12  4948.9 2173.66  4975.0 2170.43  4995.1 2161.59  5000.0 2161.59
  5005.8 2160.01  5011.9 2159.71  5016.1 2158.75  5016.5 2158.25  5020.7 2158.25
  5021.1 2158.75  5026.7 2160.28  5032.8 2160.60  5098.0 2161.94  5112.8 2163.07
  5178.0 2165.48  5184.1 2166.33  5276.4 2168.44  5392.0 2173.07  5421.6 2174.74
  5463.4 2175.78  5513.8 2178.38  5523.3 2179.67  5549.5 2180.44  5607.3 2183.72
#Mann=4,-1,0
  4591.9   0.035       0  5016.1   0.035       0  5021.1   0.035       0
  5523.3    0.07       0
Bank Sta=5016.1,5021.1
Exp/Cntr=0.3,0.1

Type RM Length L Ch R = 1,5500,319,319,319
BEGIN DESCRIPTION:
Bull Creek Trib04 11.0
END DESCRIPTION:
XS GIS Cut Line= 3
      1327204.98      6921787.98      1326707.10      6921296.07
      1326655.01      6920938.04
#Sta/Elev= 30
  4300.1 2203.12  4328.3 2199.56  4356.6 2193.94  4363.7 2194.22  4370.7 2192.73
  4377.9 2194.11  4441.5 2182.42  4498.0 2176.10  4533.4 2174.86  4568.7 2171.48
  4590.0 2171.12  4667.7 2165.31  4738.5 2161.89  4858.7 2161.46  4964.7 2158.78
  4976.3 2155.86  4976.7 2155.36  4981.4 2155.86  4991.5 2157.34  4998.0 2161.35
  5008.2 2163.67  5058.7 2172.06  5068.8 2171.81  5078.9 2169.75  5089.0 2170.35
  5121.6 2174.44  5250.7 2183.74  5321.4 2192.24  5331.8 2195.25  5361.8 2199.62
#Mann=4,-1,0
  4300.1   0.035       0  4976.3    0.07       0  4981.4   0.035       0
  4991.5    0.07       0
Bank Sta=4976.3,4981.4
Exp/Cntr=0.3,0.1

Type RM Length L Ch R = 1,5181,181,181,181
BEGIN DESCRIPTION:
Bull Creek Trib04 10.5
END DESCRIPTION:
XS GIS Cut Line= 3
      1327204.47      6921769.09      1326945.94      6921288.63
      1326984.75      6920921.67
#Sta/Elev= 30
  4454.2 2200.86  4457.6 2200.86  4462.4 2198.89  4484.3 2194.80  4506.2 2193.52
  4544.3 2187.53  4566.2 2180.75  4632.0 2173.28  4653.9 2172.43  4682.5 2168.90
  4741.5 2165.49  4839.7 2158.04  4875.6 2158.73  4933.0 2157.06  4943.5 2155.91
  4952.5 2153.25  4952.9 2152.75  4957.6 2153.25  4971.1 2155.36  4977.8 2158.05
  5002.6 2158.81  5020.5 2163.11  5042.1 2163.52  5080.9 2166.86  5181.4 2171.54
  5222.2 2174.43  5282.0 2183.56  5332.3 2195.04  5352.4 2197.45  5368.8 2197.65
#Mann=4,-1,0
  4454.2   0.035       0  4952.5   0.035       0  4957.6   0.035       0
  5222.2    0.07       0
Bank Sta=4952.5,4957.6
Exp/Cntr=0.3,0.1

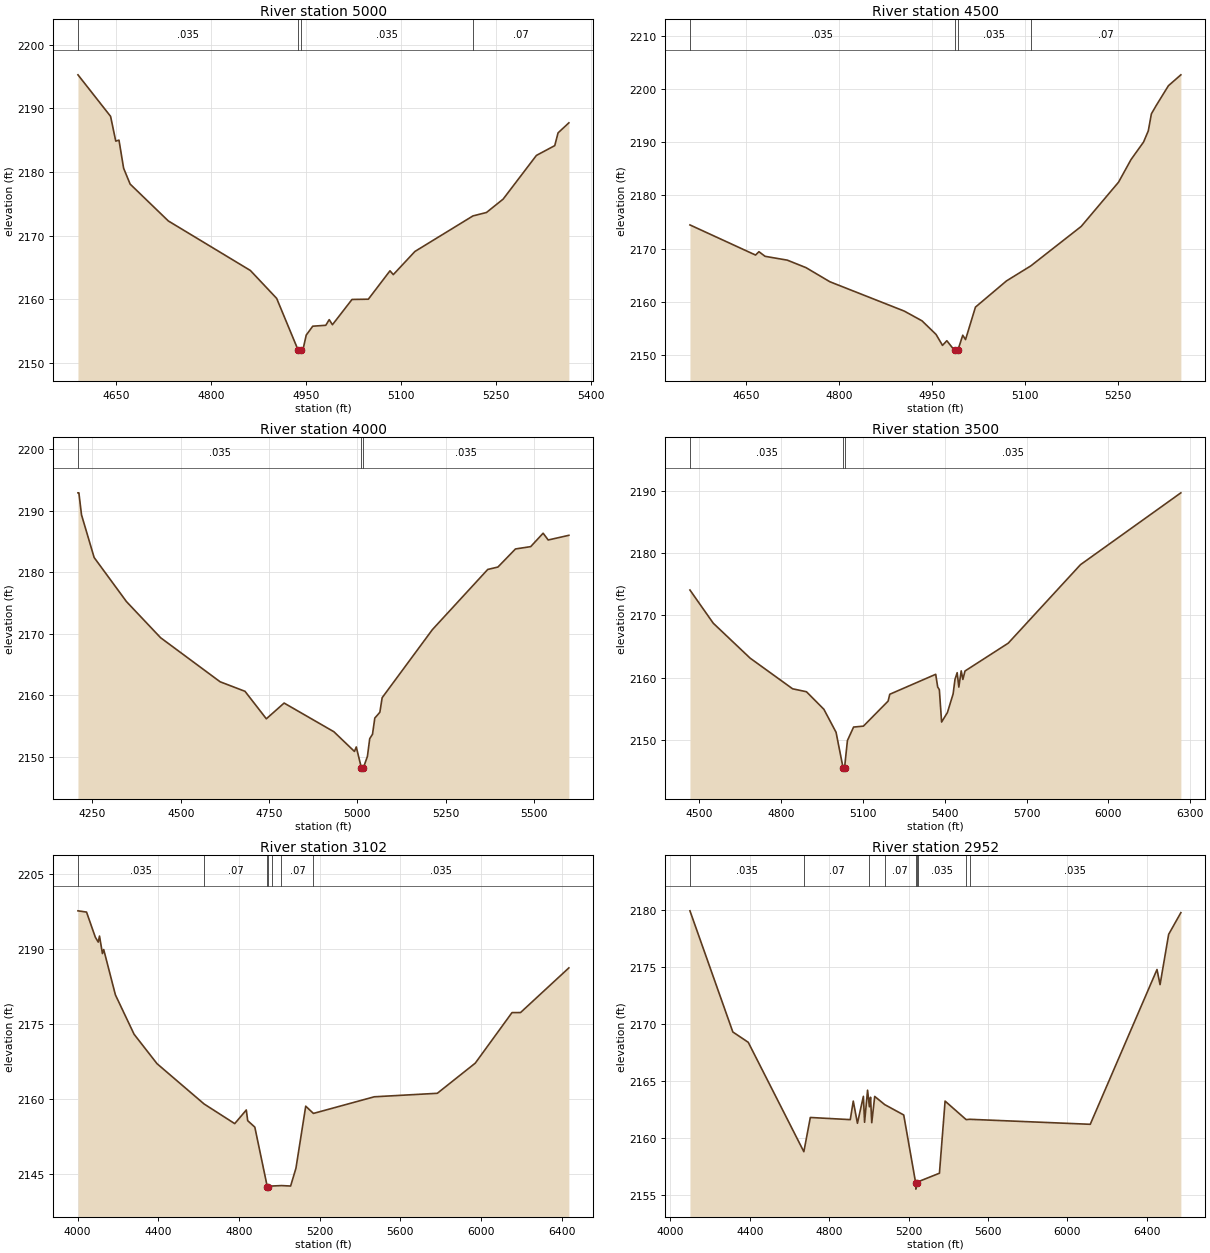
Type RM Length L Ch R = 1,5000,500,500,500
BEGIN DESCRIPTION:
Bull Creek Trib04 10.0
END DESCRIPTION:
XS GIS Cut Line= 3
      1327205.01      6921738.02      1327106.93      6921340.13
      1327204.99      6920988.03
#Sta/Elev= 30
  4590.2 2195.26  4641.7 2188.74  4649.9 2184.85  4655.0 2185.00  4662.3 2180.59
  4672.6 2178.10  4732.9 2172.31  4862.5 2164.53  4904.0 2160.15  4937.8 2152.05
  4938.2 2151.55  4942.9 2152.05  4945.5 2152.07  4950.7 2154.38  4961.0 2155.78
  4981.6 2155.92  4987.0 2156.81  4992.1 2156.01  5023.0 2159.98  5048.8 2160.02
  5083.0 2164.48  5088.2 2163.88  5122.4 2167.52  5214.0 2173.10  5235.4 2173.64
  5261.7 2175.74  5314.2 2182.60  5343.2 2184.14  5348.4 2186.14  5365.5 2187.72
#Mann=4,-1,0
  4590.2   0.035       0  4937.8   0.035       0  4942.9   0.035       0
  5214.0    0.07       0
Bank Sta=4937.8,4942.9
Exp/Cntr=0.3,0.1

Type RM Length L Ch R = 1,4500,500,500,500
BEGIN DESCRIPTION:
Bull Creek Trib04 9.0
END DESCRIPTION:
XS GIS Cut Line= 3
      1327354.99      6921638.03      1327540.33      6921237.98
      1327505.00      6920887.96
#Sta/Elev= 30
  4559.1 2174.46  4665.0 2168.79  4670.5 2169.42  4680.4 2168.55  4716.3 2167.83
  4746.5 2166.42  4785.1 2163.76  4905.2 2158.24  4933.8 2156.41  4956.5 2153.85
  4966.9 2151.79  4973.9 2152.66  4986.4 2150.83  4986.8 2150.33  4991.2 2150.33
  4991.6 2150.83  4999.6 2153.70  5004.1 2152.88  5020.1 2158.99  5070.3 2163.93
  5109.5 2166.75  5190.9 2174.18  5251.2 2182.51  5271.3 2186.76  5291.5 2190.05
  5299.2 2192.16  5304.2 2195.37  5311.6 2196.86  5331.7 2200.66  5351.8 2202.71
#Mann=4,-1,0
  4559.1   0.035       0  4986.4   0.035       0  4991.6   0.035       0
  5109.5    0.07       0
Bank Sta=4986.4,4991.6
Exp/Cntr=0.3,0.1

Type RM Length L Ch R = 1,4000,500,500,500
BEGIN DESCRIPTION:
Bull Creek Trib04 8.0
END DESCRIPTION:
XS GIS Cut Line= 3
      1327854.99      6921838.05      1327940.57      6921051.79
      1327564.16      6920586.35
#Sta/Elev= 30
  4209.1 2192.91  4211.7 2192.91  4219.2 2189.32  4254.9 2182.39  4346.4 2175.22
  4442.9 2169.35  4611.5 2162.18  4681.9 2160.63  4742.3 2156.16  4792.6 2158.72
  4933.4 2154.06  4991.7 2150.85  4996.8 2151.58  5011.5 2148.15  5011.9 2147.65
  5016.7 2148.15  5028.4 2150.05  5034.9 2152.93  5042.8 2153.65  5049.3 2156.28
  5063.6 2157.22  5070.1 2159.59  5212.4 2170.67  5369.0 2180.45  5397.8 2180.84
  5447.4 2183.78  5490.5 2184.16  5525.7 2186.34  5540.1 2185.24  5598.6 2186.00
#Mann=3,-1,0
  4209.1   0.035       0  5011.5   0.035       0  5016.7   0.035       0
Bank Sta=5011.5,5016.7
Exp/Cntr=0.3,0.1

Type RM Length L Ch R = 1,3500,398,398,398
BEGIN DESCRIPTION:
Bull Creek Trib04 7.0
END DESCRIPTION:
XS GIS Cut Line= 5
      1327904.98      6921688.03      1328244.10      6921276.83
      1328300.29      6921169.71      1328175.29      6920961.38
      1327439.55      6920440.81
#Sta/Elev= 30
  4467.0 2174.08  4552.4 2168.74  4687.4 2163.12  4842.9 2158.19  4893.8 2157.71
  4957.6 2154.89  5002.2 2151.19  5028.0 2145.44  5028.4 2144.94  5033.2 2145.44
  5043.8 2149.86  5066.4 2152.03  5102.4 2152.18  5192.9 2156.21  5199.0 2157.31
  5367.2 2160.52  5374.4 2158.48  5380.5 2158.05  5388.8 2152.84  5410.1 2154.37
  5431.0 2157.37  5437.8 2159.70  5445.8 2160.78  5451.9 2158.47  5460.6 2161.07
  5466.7 2159.69  5474.5 2161.05  5632.9 2165.53  5897.5 2178.16  6265.2 2189.72
#Mann=3,-1,0
  4467.0   0.035       0  5028.0   0.035       0  5033.2   0.035       0
Bank Sta=5028,5033.2
Exp/Cntr=0.3,0.1

Type RM Length L Ch R = 1,3102,150,150,150
BEGIN DESCRIPTION:
Bull Creek Trib04 6.0
END DESCRIPTION:
XS GIS Cut Line= 4
      1327805.03      6921937.98      1328591.95      6921329.43
      1328632.25      6921203.99      1327529.74      6920503.22
#Sta/Elev= 30
  4001.9 2197.68  4044.4 2197.43  4087.9 2192.41  4102.4 2191.42  4108.7 2192.63
  4123.2 2189.13  4129.5 2189.93  4187.5 2180.86  4280.0 2172.98  4393.7 2167.09
  4627.1 2159.02  4778.8 2155.09  4836.2 2157.82  4843.1 2155.68  4878.4 2154.39
  4940.1 2142.48  4940.5 2141.98  4945.3 2142.48  4961.5 2142.60  5010.5 2142.69
  5055.8 2142.60  5082.2 2146.16  5130.7 2158.58  5168.8 2157.13  5470.3 2160.46
  5782.8 2161.16  5970.8 2167.19  6152.9 2177.31  6195.2 2177.32  6434.8 2186.26
#Mann=7,-1,0
  4001.9   0.035       0  4627.1    0.07       0  4940.1   0.035       0
  4945.3    0.07       0  4961.5   0.035       0  5010.5    0.07       0
  5168.8   0.035       0
Bank Sta=4940.1,4945.3
Exp/Cntr=0.3,0.1

Type RM Length L Ch R = 1,2952,84,84,84
BEGIN DESCRIPTION:
Bull Creek Trib04 5.6
END DESCRIPTION:
XS GIS Cut Line= 5
      1327969.93      6922018.29      1328383.57      6921639.79
      1328748.15      6921396.73      1328820.13      6921240.99
      1327694.38      6920583.34
#Sta/Elev= 30
  4098.2 2179.96  4314.3 2169.31  4392.0 2168.40  4672.2 2158.78  4704.9 2161.79
  4906.2 2161.60  4921.3 2163.23  4942.3 2161.28  4972.3 2163.65  4978.3 2161.37
  4993.4 2164.19  5002.6 2162.73  5008.4 2163.57  5014.4 2161.33  5029.4 2163.64
  5079.9 2162.92  5175.6 2162.01  5236.3 2155.99  5236.7 2155.49  5241.5 2155.99
  5245.3 2156.12  5355.6 2156.89  5384.1 2163.23  5490.4 2161.60  5507.9 2161.63
  6115.7 2161.19  6452.1 2174.80  6467.5 2173.47  6510.8 2177.89  6572.4 2179.80
#Mann=9,-1,0
  4098.2   0.035       0  4672.2    0.07       0  5002.6   0.035       0
  5079.9    0.07       0  5236.3    0.07       0  5241.5    0.07       0
  5245.3   0.035       0  5490.4    0.07       0  5507.9   0.035       0
Bank Sta=5236.3,5241.5
Exp/Cntr=0.3,0.1

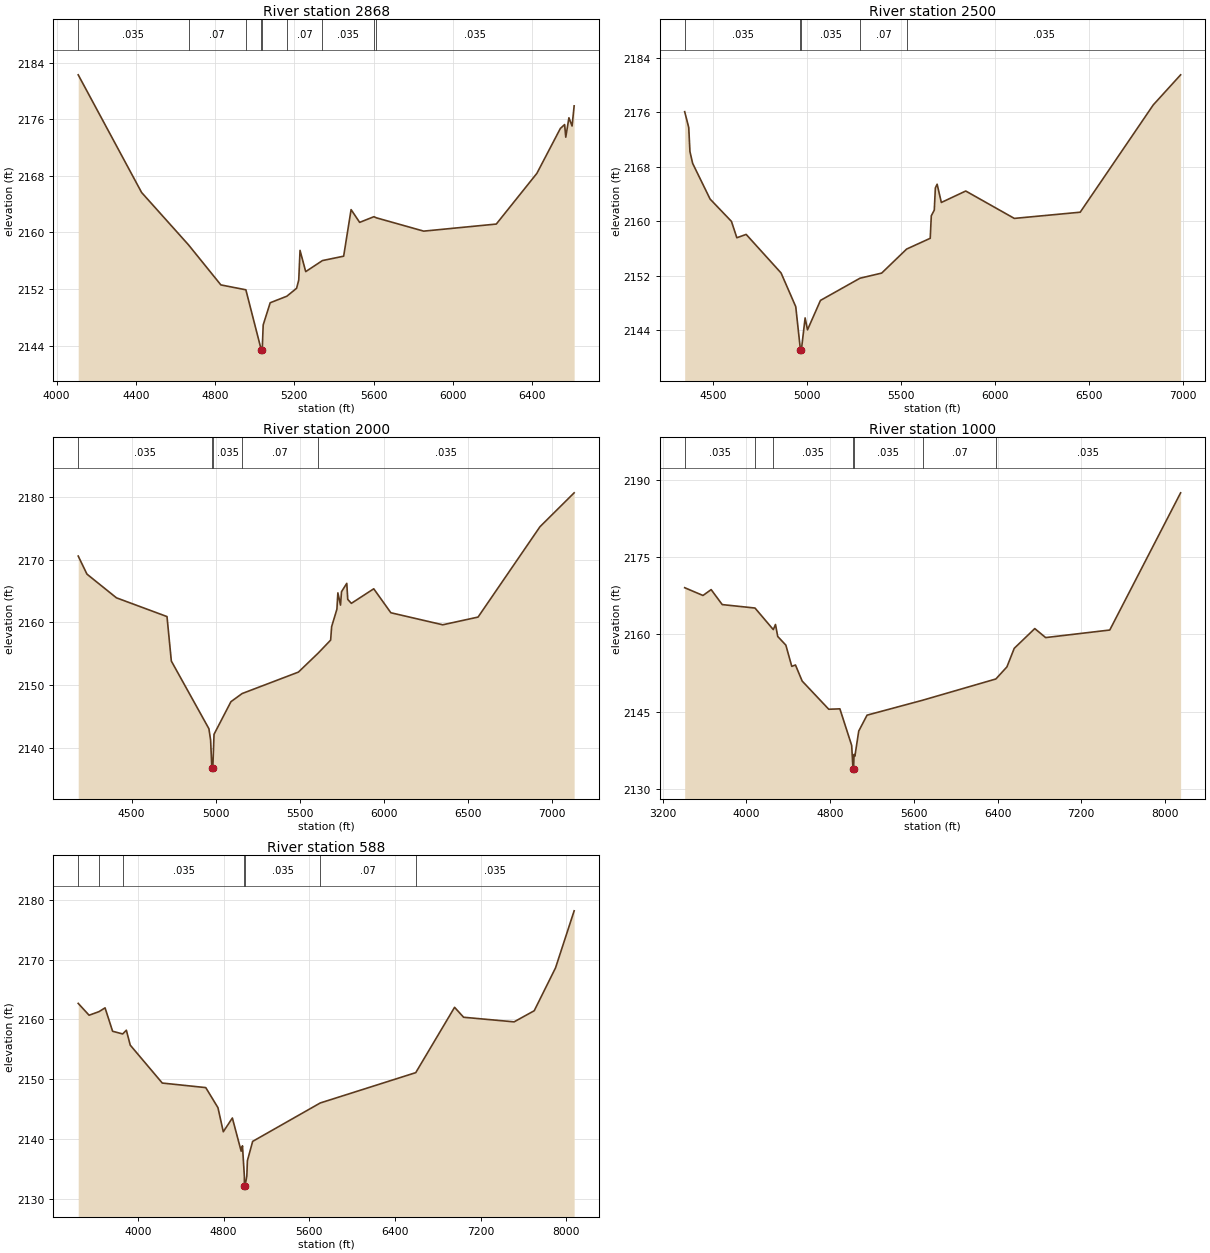
Type RM Length L Ch R = 1,2868,368,368,368
BEGIN DESCRIPTION:
Bull Creek Trib04 5.5
END DESCRIPTION:
XS GIS Cut Line= 4
      1328022.00      6922055.20      1328808.97      6921446.62
      1328888.71      6921266.16      1327746.51      6920620.25
#Sta/Elev= 30
  4108.8 2182.28  4429.0 2165.65  4665.8 2158.25  4829.2 2152.59  4955.4 2151.90
  5032.8 2143.45  5033.2 2142.95  5038.0 2143.45  5042.9 2146.94  5078.3 2150.07
  5162.2 2150.99  5211.4 2152.11  5222.4 2153.27  5228.9 2157.47  5257.6 2154.47
  5342.1 2156.03  5449.2 2156.65  5486.7 2163.23  5530.0 2161.43  5602.1 2162.23
  5614.6 2162.07  5853.4 2160.19  6220.0 2161.19  6425.0 2168.36  6543.4 2174.70
  6565.0 2175.25  6570.8 2173.47  6586.7 2176.21  6602.6 2175.05  6613.1 2177.89
#Mann=9,-1,0
  4108.8   0.035       0  4665.8    0.07       0  4955.4   0.035       0
  5032.8   0.035       0  5038.0   0.035       0  5162.2    0.07       0
  5342.1   0.035       0  5602.1    0.07       0  5614.6   0.035       0
Bank Sta=5032.8,5038
Exp/Cntr=0.3,0.1

Type RM Length L Ch R = 1,2500,500,500,500
BEGIN DESCRIPTION:
Bull Creek Trib04 5.0
END DESCRIPTION:
XS GIS Cut Line= 4
      1328504.98      6922088.02      1329010.80      6921680.44
      1329043.22      6921319.98      1327628.37      6920517.89
#Sta/Elev= 30
  4350.4 2176.09  4372.0 2173.77  4378.4 2170.23  4392.8 2168.50  4485.6 2163.26
  4599.2 2159.98  4627.9 2157.58  4677.5 2158.07  4863.1 2152.41  4941.2 2147.46
  4966.0 2141.14  4966.4 2140.64  4971.3 2141.14  4991.0 2145.81  5003.7 2144.06
  5072.7 2148.38  5283.0 2151.64  5398.2 2152.39  5531.0 2155.92  5656.5 2157.50
  5662.2 2160.81  5678.1 2161.64  5683.8 2164.90  5693.2 2165.44  5715.6 2162.76
  5845.4 2164.44  6103.7 2160.42  6454.2 2161.33  6842.7 2177.08  6988.3 2181.50
#Mann=5,-1,0
  4350.4   0.035       0  4966.0   0.035       0  4971.3   0.035       0
  5283.0    0.07       0  5531.0   0.035       0
Bank Sta=4966,4971.3
Exp/Cntr=0.3,0.1

Type RM Length L Ch R = 1,2000,1000,1000,1000
BEGIN DESCRIPTION:
Bull Creek Trib04 4.0
END DESCRIPTION:
XS GIS Cut Line= 3
      1329321.11      6922343.37      1329458.90      6921537.97
      1327621.28      6920462.28
#Sta/Elev= 30
  4182.9 2170.57  4234.8 2167.69  4410.0 2163.91  4710.4 2160.92  4736.2 2153.83
  4959.4 2143.04  4969.5 2141.23  4976.9 2136.78  4977.3 2136.28  4982.5 2136.78
  4989.8 2142.15  5090.2 2147.35  5156.8 2148.65  5491.2 2152.07  5610.3 2155.14
  5682.6 2157.17  5688.4 2159.30  5719.8 2162.10  5725.6 2164.70  5741.3 2162.75
  5747.1 2164.88  5778.5 2166.22  5784.2 2163.66  5805.7 2163.03  5938.7 2165.35
  6040.4 2161.53  6348.6 2159.61  6558.4 2160.84  6926.1 2175.24  7129.3 2180.65
#Mann=5,-1,0
  4182.9   0.035       0  4976.9   0.035       0  4982.5   0.035       0
  5156.8    0.07       0  5610.3   0.035       0
Bank Sta=4976.9,4982.5
Exp/Cntr=0.3,0.1

Type RM Length L Ch R = 1,1000,412,412,412
BEGIN DESCRIPTION:
Bull Creek Trib04 2.0
END DESCRIPTION:
XS GIS Cut Line= 5
      1329181.33      6922971.83      1330284.43      6921915.20
      1330290.25      6921852.78      1330182.37      6921676.82
      1327494.73      6920475.26
#Sta/Elev= 30
  3409.8 2169.06  3584.8 2167.55  3662.8 2168.69  3768.8 2165.78  4082.1 2165.11
  4257.0 2160.92  4277.9 2161.92  4299.3 2159.59  4377.0 2157.90  4433.6 2153.78
  4468.8 2154.05  4532.7 2150.93  4787.1 2145.45  4893.4 2145.53  5006.0 2138.43
  5018.6 2133.93  5019.1 2133.43  5024.2 2133.93  5029.1 2136.67  5036.8 2136.32
  5073.6 2141.21  5152.9 2144.30  5685.7 2147.21  6384.4 2151.33  6490.2 2153.68
  6559.8 2157.28  6756.4 2161.12  6860.2 2159.37  7473.2 2160.84  8150.4 2187.49
#Mann=7,-1,0
  3409.8   0.035       0  4082.1    0.07       0  4257.0   0.035       0
  5018.6   0.035       0  5024.2   0.035       0  5685.7    0.07       0
  6384.4   0.035       0
Bank Sta=5018.6,5024.2
Exp/Cntr=0.3,0.1

Type RM Length L Ch R = 1,588,0,0,0
BEGIN DESCRIPTION:
Bull Creek Trib04 1.0
END DESCRIPTION:
XS GIS Cut Line= 5
      1329542.23      6922757.18      1330669.48      6921875.59
      1330624.29      6921783.22      1330604.37      6921769.26
      1327738.49      6920659.90
#Sta/Elev= 30
  3442.7 2162.69  3544.2 2160.71  3637.0 2161.31  3693.4 2161.94  3763.9 2158.03
  3857.7 2157.58  3892.3 2158.20  3928.6 2155.71  4227.8 2149.37  4633.8 2148.61
  4747.8 2145.25  4797.5 2141.23  4882.2 2143.53  4964.6 2137.98  4976.6 2138.88
  4994.2 2133.83  4994.8 2132.14  4995.3 2131.64  5000.4 2132.14  5017.3 2133.83
  5022.6 2136.40  5071.8 2139.62  5702.8 2146.04  6594.7 2151.11  6957.3 2162.03
  7041.7 2160.37  7513.1 2159.60  7701.2 2161.46  7900.0 2168.62  8074.0 2178.16
#Mann=7,-1,0
  3442.7   0.035       0  3637.0    0.07       0  3857.7   0.035       0
  4994.8   0.035       0  5000.4   0.035       0  5702.8    0.07       0
  6594.7   0.035       0
Bank Sta=4994.8,5000.4
Exp/Cntr=0.3,0.1

Chan Stop Cuts=-1