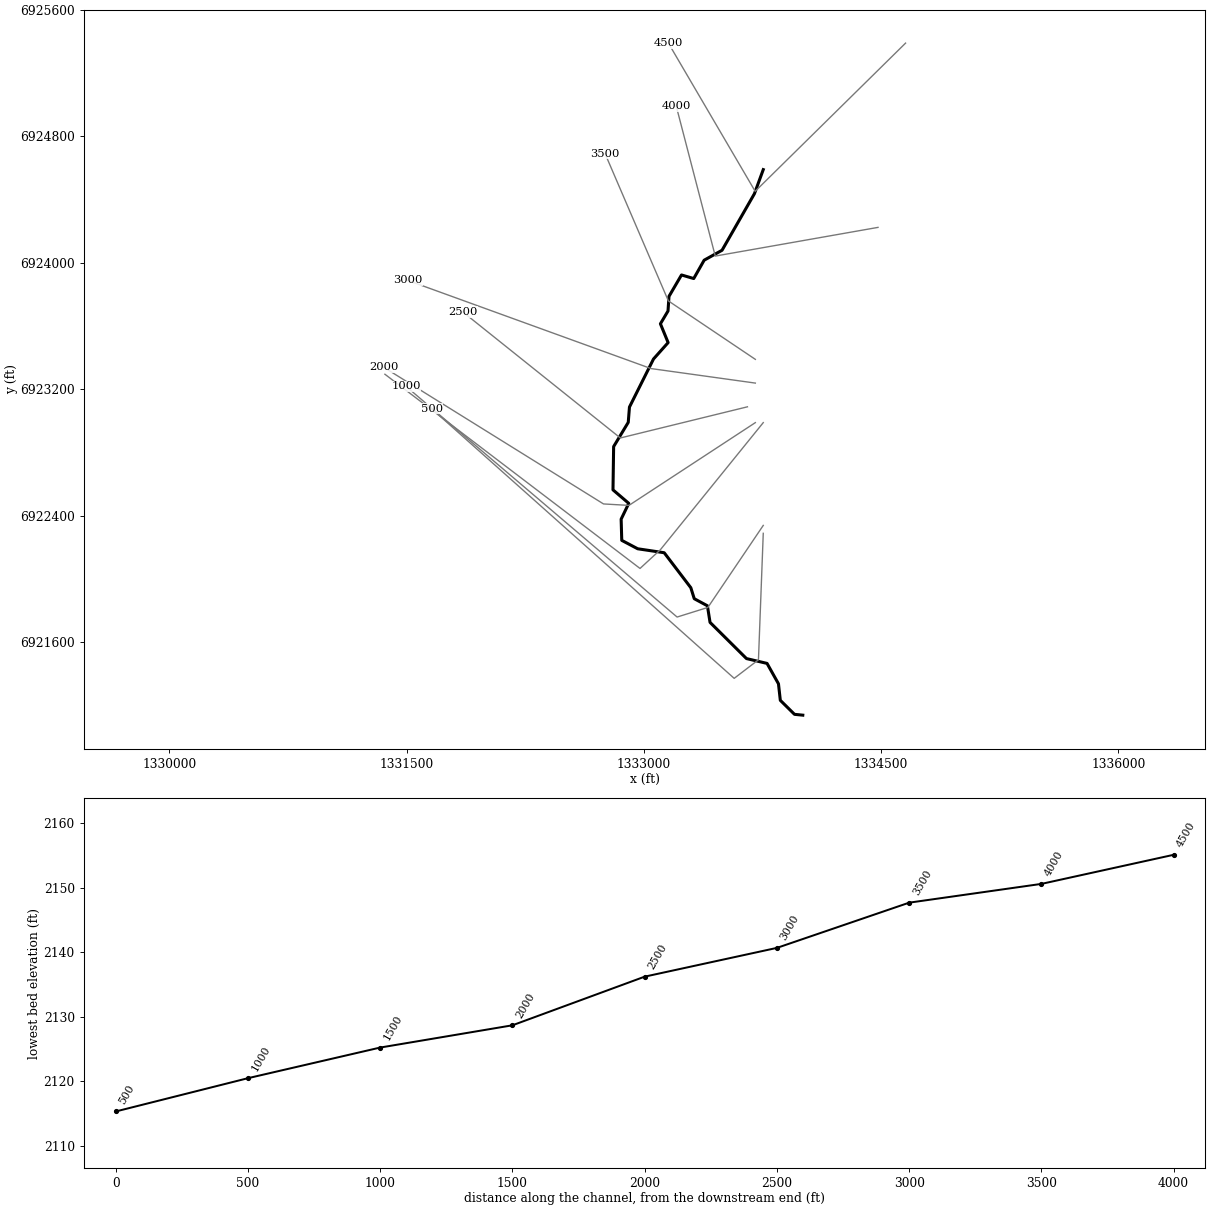
--- Bull Creek Trib05.prj (project) ---

Proj Title=Bull Creek Trib05 Base Level Engineering
Current Plan=p01
Default Exp/Contr=0.3,0.1
English Units
Geom File=g01
Flow File=f01
Plan File=p01
BEGIN DESCRIPTION:
Bull Creek Trib05
END DESCRIPTION:

--- Bull Creek Trib05.p01 (plan) ---

Plan Title=Multiple Run
Short Identifier=Multiple
Geom File=g01
Flow File=f01
Subcritical Flow
K Sum by GR= 0
Std Step Tol= 0.01
Critical Tol= 0.01
Num of Std Step Trials= 20
Max Error Tol= 0.3
Flow Tol Ratio= 0.001
Split Flow NTrial= 30
Split Flow Tol= 0.02
Split Flow Ratio= 0.02
Log Output Level= 0
Friction Slope Method= 1
Unsteady Friction Slope Method= 2
Unsteady Bridges Friction Slope Method= 1
Parabolic Critical Depth
Global Vel Dist=  1 , 1 , 1
Global Log Level= 0
CheckData=True
Encroach Param= -1, 0, 0, 0
BEGIN DESCRIPTION:
Multiple Run
END DESCRIPTION:

--- Bull Creek Trib05.f01 (steady flow) ---

Flow Title=Multiple
Number of Profiles=7
Profile Names=10-year,25-year,50-year,1pct_min,100-year,1pct_plu,500-year
River Rch & RM= Bull Creek Trib0,Reach-1,4500
     292     418     525     329     656    1309    1036
River Rch & RM= Bull Creek Trib0,Reach-1,2000
     465     683     874     555    1108    2211    1807
Boundary for River Rch & Prof#=Bull Creek Trib0,Reach-1,1
Up Type=0
Dn Type=3
Dn Slope=0.005
Boundary for River Rch & Prof#=Bull Creek Trib0,Reach-1,2
Up Type=0
Dn Type=3
Dn Slope=0.005
Boundary for River Rch & Prof#=Bull Creek Trib0,Reach-1,3
Up Type=0
Dn Type=3
Dn Slope=0.005
Boundary for River Rch & Prof#=Bull Creek Trib0,Reach-1,4
Up Type=0
Dn Type=3
Dn Slope=0.005
Boundary for River Rch & Prof#=Bull Creek Trib0,Reach-1,5
Up Type=0
Dn Type=3
Dn Slope=0.005
Boundary for River Rch & Prof#=Bull Creek Trib0,Reach-1,6
Up Type=0
Dn Type=3
Dn Slope=0.005
Boundary for River Rch & Prof#=Bull Creek Trib0,Reach-1,7
Up Type=0
Dn Type=3
Dn Slope=0.005

--- Bull Creek Trib05.g01 (geometry) ---

Geom Title=Existing Conditions

River Reach=Bull Creek Trib0,Reach-1
Reach XY= 30
      1333755.00      6924588.00      1333699.17      6924435.70
      1333494.37      6924078.00      1333381.17      6924015.13
      1333315.31      6923899.12      1333237.96      6923921.76
      1333158.82      6923786.42      1333152.62      6923693.97
      1333104.61      6923613.00      1333153.37      6923494.04
      1333060.85      6923390.29      1332908.83      6923086.42
      1332901.17      6922989.58      1332808.75      6922836.45
      1332804.68      6922562.80      1332904.45      6922477.52
      1332856.22      6922377.49      1332860.16      6922243.41
      1332960.91      6922190.24      1333128.58      6922165.16
      1333296.82      6921944.02      1333318.56      6921874.47
      1333401.81      6921829.65      1333418.42      6921724.73
      1333648.83      6921495.86      1333778.90      6921465.28
      1333851.17      6921336.42      1333862.84      6921231.81
      1333952.46      6921143.30      1334005.00      6921138.00

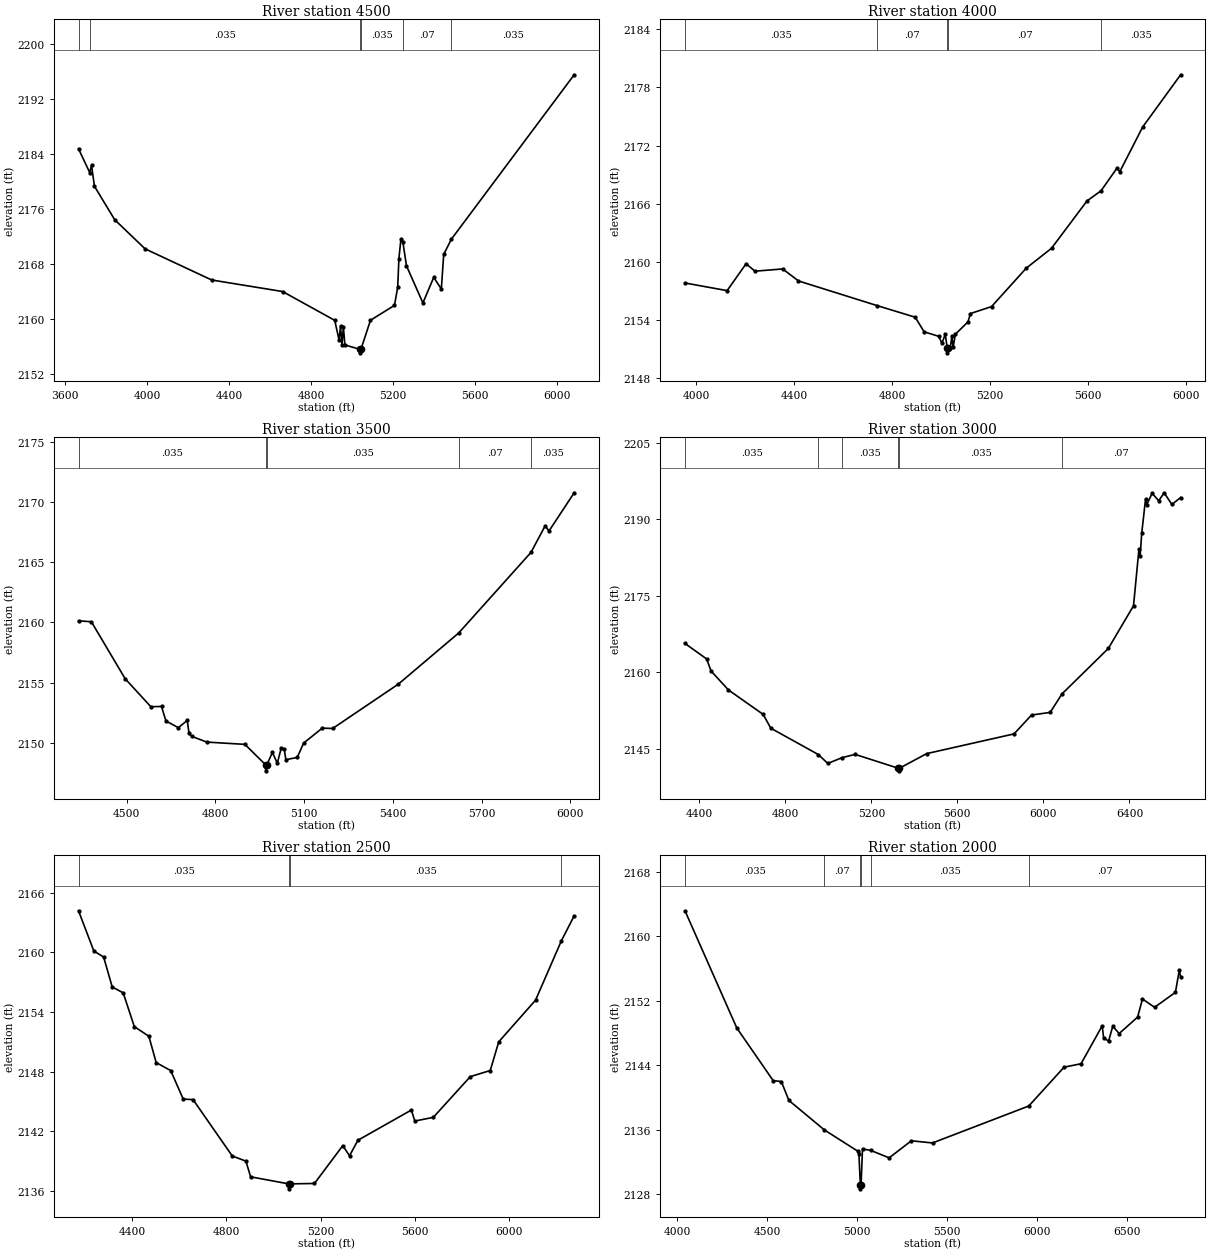
Type RM Length L Ch R = 1,4500,500,500,500
BEGIN DESCRIPTION:
Bull Creek Trib05 9.0
END DESCRIPTION:
XS GIS Cut Line= 3
      1334655.02      6925388.02      1333703.84      6924450.84
      1333155.02      6925387.96
#Sta/Elev= 30
  3664.7 2184.77  3719.5 2181.31  3728.4 2182.36  3742.5 2179.32  3841.5 2174.45
  3990.0 2170.21  4315.3 2165.68  4661.7 2164.00  4916.3 2159.81  4937.6 2156.94
  4944.6 2158.94  4951.7 2156.29  4958.7 2158.84  4965.9 2156.23  5040.2 2155.58
  5040.5 2155.08  5044.2 2155.58  5091.0 2159.82  5208.3 2161.99  5224.0 2164.65
  5229.8 2168.78  5239.7 2171.64  5249.4 2171.16  5266.9 2167.74  5347.1 2162.34
  5399.9 2166.06  5437.1 2164.37  5448.7 2169.41  5486.7 2171.64  6086.0 2195.54
#Mann=6,-1,0
  3664.7    0.07       0  3719.5   0.035       0  5040.2   0.035       0
  5044.2   0.035       0  5249.4    0.07       0  5486.7   0.035       0
Bank Sta=5040.2,5044.2
Exp/Cntr=0.3,0.1

Type RM Length L Ch R = 1,4000,500,500,500
BEGIN DESCRIPTION:
Bull Creek Trib05 8.0
END DESCRIPTION:
XS GIS Cut Line= 3
      1334480.71      6924222.66      1333451.47      6924041.24
      1333205.01      6924987.98
#Sta/Elev= 30
  3954.9 2157.79  4127.0 2157.00  4204.4 2159.78  4240.5 2159.01  4353.9 2159.24
  4418.3 2158.00  4738.3 2155.46  4894.9 2154.25  4931.3 2152.74  4990.6 2152.28
  5003.8 2151.56  5017.3 2152.47  5025.7 2151.07  5025.9 2150.57  5029.7 2151.07
  5038.0 2151.09  5044.3 2152.27  5049.5 2151.13  5058.7 2152.49  5110.3 2153.77
  5120.2 2154.63  5206.4 2155.35  5348.0 2159.32  5451.3 2161.38  5596.0 2166.27
  5653.4 2167.32  5717.6 2169.63  5730.3 2169.31  5823.3 2173.91  5978.3 2179.31
#Mann=5,-1,0
  3954.9   0.035       0  4738.3    0.07       0  5025.7    0.07       0
  5029.7    0.07       0  5653.4   0.035       0
Bank Sta=5025.7,5029.7
Exp/Cntr=0.3,0.1

Type RM Length L Ch R = 1,3500,500,500,500
BEGIN DESCRIPTION:
Bull Creek Trib05 7.0
END DESCRIPTION:
XS GIS Cut Line= 3
      1333704.98      6923388.01      1333154.91      6923757.78
      1332755.02      6924687.96
#Sta/Elev= 30
  4337.2 2160.13  4380.7 2160.05  4494.7 2155.32  4581.7 2152.99  4617.7 2153.01
  4632.7 2151.80  4674.7 2151.25  4704.7 2151.85  4710.7 2150.79  4719.6 2150.53
  4770.6 2150.05  4899.6 2149.86  4969.6 2148.16  4969.9 2147.66  4973.6 2148.16
  4992.6 2149.19  5009.1 2148.29  5022.0 2149.52  5032.6 2149.45  5038.0 2148.59
  5076.4 2148.77  5098.2 2149.97  5161.2 2151.21  5196.2 2151.18  5418.4 2154.87
  5622.3 2159.12  5866.4 2165.81  5914.6 2168.03  5927.4 2167.59  6012.5 2170.77
#Mann=5,-1,0
  4337.2   0.035       0  4969.6   0.035       0  4973.6   0.035       0
  5622.3    0.07       0  5866.4   0.035       0
Bank Sta=4969.6,4973.6
Exp/Cntr=0.3,0.1

Type RM Length L Ch R = 1,3000,500,500,500
BEGIN DESCRIPTION:
Bull Creek Trib05 6.0
END DESCRIPTION:
XS GIS Cut Line= 3
      1333704.97      6923238.00      1333044.93      6923329.86
      1331504.96      6923888.01
#Sta/Elev= 30
  4333.6 2165.65  4434.5 2162.60  4454.7 2160.25  4535.5 2156.53  4697.0 2151.73
  4732.5 2149.02  4954.0 2143.84  4997.4 2142.10  5063.5 2143.23  5124.4 2143.88
  5326.2 2141.15  5326.4 2140.65  5330.2 2141.15  5457.3 2144.03  5863.5 2147.90
  5944.8 2151.60  6031.4 2152.12  6087.2 2155.78  6301.7 2164.66  6418.9 2173.04
  6444.2 2184.15  6449.5 2182.73  6457.1 2187.29  6474.8 2193.94  6480.1 2192.85
  6505.5 2195.12  6536.1 2193.65  6561.4 2195.22  6597.3 2192.93  6638.0 2194.29
#Mann=6,-1,0
  4333.6   0.035       0  4954.0    0.07       0  5063.5   0.035       0
  5326.2    0.07       0  5330.2   0.035       0  6087.2    0.07       0
Bank Sta=5326.2,5330.2
Exp/Cntr=0.3,0.1

Type RM Length L Ch R = 1,2500,500,500,500
BEGIN DESCRIPTION:
Bull Creek Trib05 5.0
END DESCRIPTION:
XS GIS Cut Line= 3
      1333655.01      6923088.00      1332851.22      6922890.93
      1331855.03      6923687.98
#Sta/Elev= 30
  4172.4 2164.20  4237.4 2160.15  4279.0 2159.54  4315.4 2156.53  4362.1 2155.93
  4409.2 2152.53  4471.0 2151.56  4501.9 2148.91  4563.7 2148.10  4616.8 2145.23
  4658.4 2145.18  4824.8 2139.50  4882.8 2138.98  4902.8 2137.40  5064.5 2136.69
  5064.7 2136.19  5068.5 2136.69  5173.7 2136.73  5293.8 2140.54  5322.6 2139.52
  5357.8 2141.08  5585.1 2144.13  5599.5 2143.02  5678.0 2143.39  5834.8 2147.49
  5919.7 2148.11  5955.7 2151.00  6111.8 2155.19  6221.6 2161.18  6275.8 2163.69
#Mann=4,-1,0
  4172.4   0.035       0  5064.5   0.035       0  5068.5   0.035       0
  6221.6    0.07       0
Bank Sta=5064.5,5068.5
Exp/Cntr=0.3,0.1

Type RM Length L Ch R = 1,2000,500,500,500
BEGIN DESCRIPTION:
Bull Creek Trib05 4.0
END DESCRIPTION:
XS GIS Cut Line= 4
      1333704.97      6922987.98      1332905.50      6922464.52
      1332744.73      6922473.75      1331354.98      6923338.01
#Sta/Elev= 30
  4044.4 2163.19  4332.3 2148.63  4534.4 2142.09  4579.6 2141.98  4621.7 2139.63
  4819.1 2135.96  5002.8 2133.35  5010.5 2133.00  5018.5 2129.15  5018.8 2128.65
  5022.5 2129.15  5030.5 2133.61  5076.8 2133.42  5178.5 2132.50  5302.0 2134.62
  5419.3 2134.35  5954.1 2138.94  6150.0 2143.76  6244.5 2144.19  6361.9 2148.90
  6369.6 2147.44  6397.2 2146.99  6420.7 2148.85  6456.1 2147.94  6558.5 2149.98
  6585.7 2152.23  6653.0 2151.20  6768.7 2153.06  6789.9 2155.78  6797.6 2155.00
#Mann=6,-1,0
  4044.4   0.035       0  4819.1    0.07       0  5018.5    0.07       0
  5022.5    0.07       0  5076.8   0.035       0  5954.1    0.07       0
Bank Sta=5018.5,5022.5
Exp/Cntr=0.3,0.1

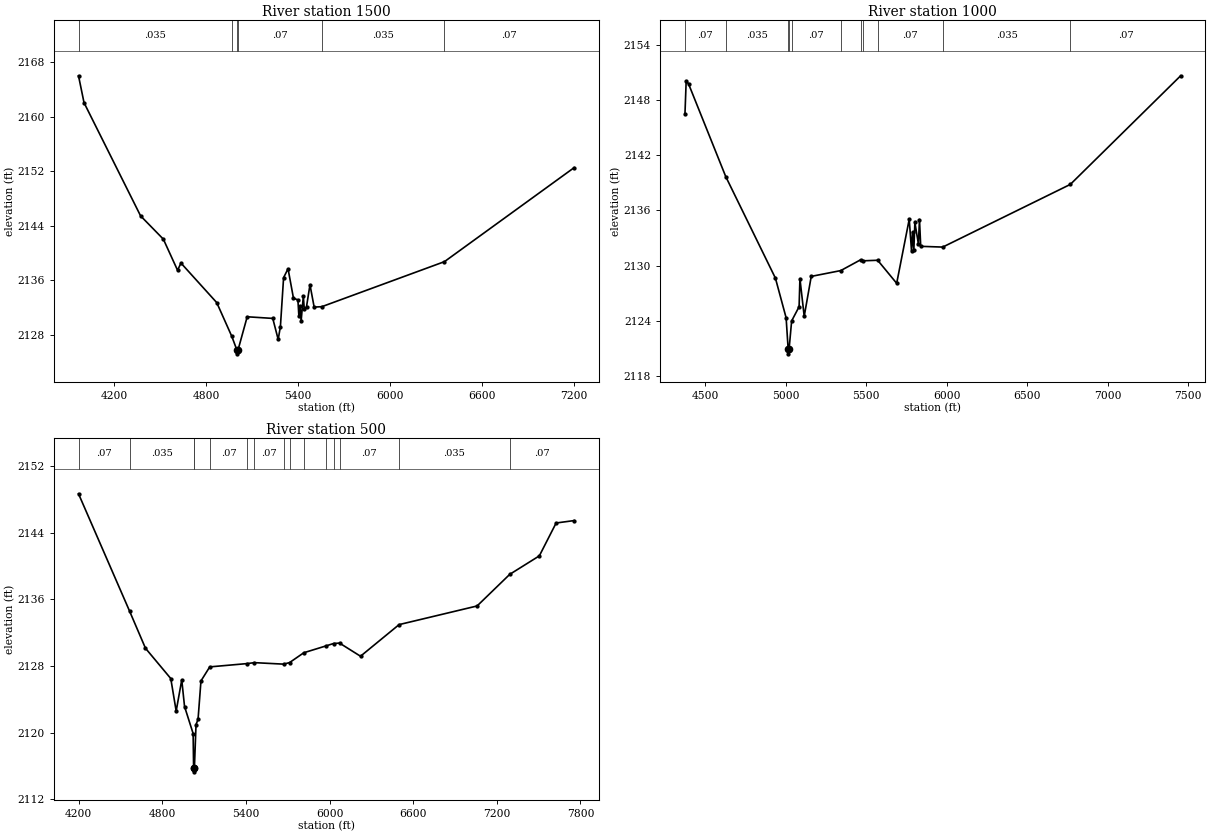
Type RM Length L Ch R = 1,1500,500,500,500
BEGIN DESCRIPTION:
Bull Creek Trib05 3.0
END DESCRIPTION:
XS GIS Cut Line= 4
      1333755.02      6922988.03      1333104.26      6922184.11
      1332975.64      6922065.76      1331362.33      6923293.95
#Sta/Elev= 30
  3965.7 2166.01  4001.7 2162.06  4371.0 2145.45  4519.7 2142.03  4612.4 2137.47
  4634.8 2138.52  4868.3 2132.72  4966.8 2127.76  5000.9 2125.70  5001.3 2125.20
  5006.6 2125.70  5067.2 2130.64  5234.2 2130.40  5269.6 2127.31  5284.1 2129.20
  5304.9 2136.38  5334.0 2137.69  5369.4 2133.36  5398.4 2133.12  5404.7 2130.75
  5413.0 2132.22  5419.3 2129.99  5433.8 2133.66  5440.1 2131.75  5454.6 2132.12
  5477.2 2135.34  5504.5 2132.06  5554.4 2132.12  6355.3 2138.73  7202.4 2152.53
#Mann=6,-1,0
  3965.7   0.035       0  4966.8    0.07       0  5000.9    0.07       0
  5006.6    0.07       0  5554.4   0.035       0  6355.3    0.07       0
Bank Sta=5000.9,5006.6
Exp/Cntr=0.3,0.1

Type RM Length L Ch R = 1,1000,500,500,500
BEGIN DESCRIPTION:
Bull Creek Trib05 2.0
END DESCRIPTION:
XS GIS Cut Line= 4
      1333755.00      6922338.00      1333404.58      6921819.15
      1333210.01      6921758.47      1331496.48      6923216.79
#Sta/Elev= 30
  4373.9 2146.51  4381.4 2150.07  4396.4 2149.72  4627.1 2139.68  4935.9 2128.66
  5002.4 2124.36  5015.1 2120.95  5015.6 2120.45  5020.8 2120.95  5036.7 2124.02
  5083.0 2125.56  5088.2 2128.61  5114.8 2124.52  5158.5 2128.85  5342.0 2129.48
  5466.3 2130.66  5480.3 2130.54  5571.3 2130.60  5689.4 2128.10  5767.4 2135.05
  5781.6 2131.65  5788.2 2133.68  5795.9 2131.66  5802.5 2134.70  5824.5 2132.36
  5831.1 2135.02  5838.8 2132.11  5975.5 2132.03  6768.6 2138.83  7453.9 2150.61
#Mann=11,-1,0
  4373.9    0.07       0  4627.1   0.035       0  5015.1   0.035       0
  5020.8   0.035       0  5036.7    0.07       0  5342.0   0.035       0
  5466.3    0.07       0  5480.3   0.035       0  5571.3    0.07       0
  5975.5   0.035       0  6768.6    0.07       0
Bank Sta=5015.1,5020.8
Exp/Cntr=0.3,0.1

Type RM Length L Ch R = 1,500,0,0,0
BEGIN DESCRIPTION:
Bull Creek Trib05 1.0
END DESCRIPTION:
XS GIS Cut Line= 4
      1333755.00      6922288.00      1333724.60      6921488.17
      1333571.10      6921370.81      1331659.00      6923075.22
#Sta/Elev= 30
  4199.6 2148.70  4566.4 2134.58  4679.9 2130.14  4861.4 2126.50  4900.1 2122.59
  4940.1 2126.34  4960.1 2123.14  5021.7 2119.89  5025.1 2115.79  5025.6 2115.29
  5030.9 2115.79  5042.5 2120.97  5057.0 2121.60  5077.8 2126.21  5140.8 2127.90
  5410.6 2128.30  5461.2 2128.41  5671.6 2128.23  5713.6 2128.42  5815.5 2129.60
  5972.6 2130.41  6028.9 2130.71  6071.8 2130.76  6222.3 2129.18  6499.0 2132.98
  7058.4 2135.22  7292.7 2139.02  7504.9 2141.24  7625.3 2145.19  7754.7 2145.48
#Mann=15,-1,0
  4199.6    0.07       0  4566.4   0.035       0  5025.1   0.035       0
  5030.9   0.035       0  5140.8    0.07       0  5410.6   0.035       0
  5461.2    0.07       0  5671.6   0.035       0  5713.6    0.07       0
  5815.5   0.035       0  5972.6    0.07       0  6028.9   0.035       0
  6071.8    0.07       0  6499.0   0.035       0  7292.7    0.07       0
Bank Sta=5025.1,5030.9
Exp/Cntr=0.3,0.1

Chan Stop Cuts=-1