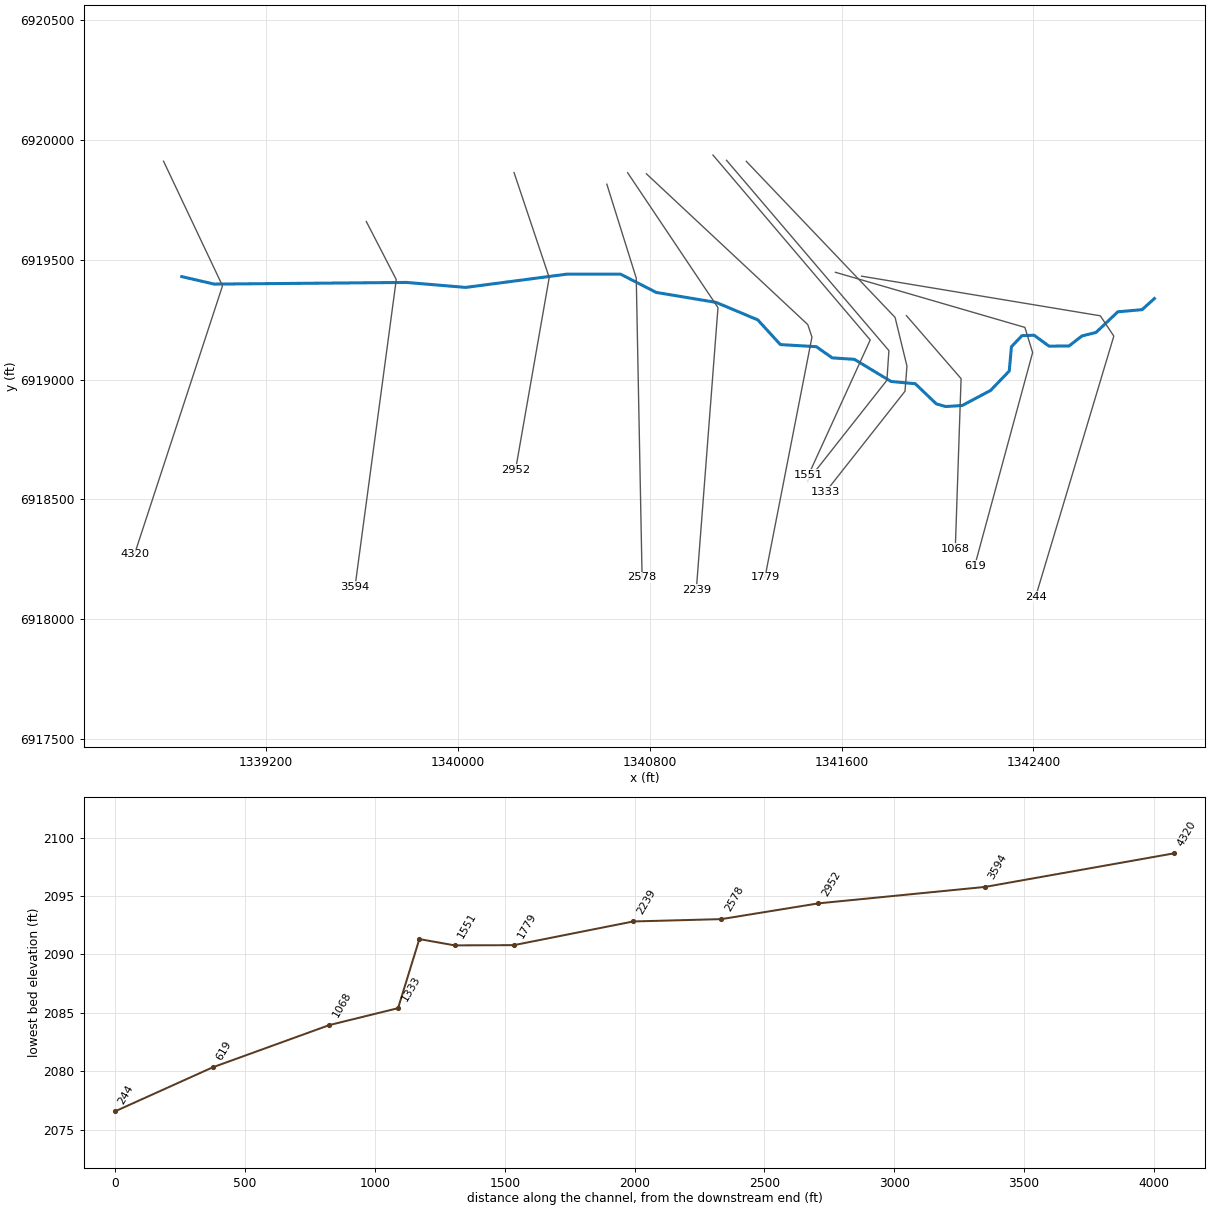
--- Bull Creek Trib07.prj (project) ---

Proj Title=Bull Creek Trib07 Base Level Engineering
Current Plan=p01
Default Exp/Contr=0.3,0.1
English Units
Geom File=g01
Flow File=f01
Plan File=p01
BEGIN DESCRIPTION:
Bull Creek Trib07
END DESCRIPTION:

--- Bull Creek Trib07.p01 (plan) ---

Plan Title=Multiple Run
Short Identifier=Multiple
Geom File=g01
Flow File=f01
Subcritical Flow
K Sum by GR= 0
Std Step Tol= 0.01
Critical Tol= 0.01
Num of Std Step Trials= 20
Max Error Tol= 0.3
Flow Tol Ratio= 0.001
Split Flow NTrial= 30
Split Flow Tol= 0.02
Split Flow Ratio= 0.02
Log Output Level= 0
Friction Slope Method= 1
Unsteady Friction Slope Method= 2
Unsteady Bridges Friction Slope Method= 1
Parabolic Critical Depth
Global Vel Dist=  1 , 1 , 1
Global Log Level= 0
CheckData=True
Encroach Param= -1, 0, 0, 0
BEGIN DESCRIPTION:
Multiple Run
END DESCRIPTION:

--- Bull Creek Trib07.f01 (steady flow) ---

Flow Title=Multiple
Number of Profiles=7
Profile Names=10-year,25-year,50-year,1pct_min,100-year,1pct_plu,500-year
River Rch & RM= Bull Creek Trib0,Reach-1,4320
     291     415     521     325     649    1295    1021
Boundary for River Rch & Prof#=Bull Creek Trib0,Reach-1,1
Up Type=0
Dn Type=3
Dn Slope=0.005
Boundary for River Rch & Prof#=Bull Creek Trib0,Reach-1,2
Up Type=0
Dn Type=3
Dn Slope=0.005
Boundary for River Rch & Prof#=Bull Creek Trib0,Reach-1,3
Up Type=0
Dn Type=3
Dn Slope=0.005
Boundary for River Rch & Prof#=Bull Creek Trib0,Reach-1,4
Up Type=0
Dn Type=3
Dn Slope=0.005
Boundary for River Rch & Prof#=Bull Creek Trib0,Reach-1,5
Up Type=0
Dn Type=3
Dn Slope=0.005
Boundary for River Rch & Prof#=Bull Creek Trib0,Reach-1,6
Up Type=0
Dn Type=3
Dn Slope=0.005
Boundary for River Rch & Prof#=Bull Creek Trib0,Reach-1,7
Up Type=0
Dn Type=3
Dn Slope=0.005

--- Bull Creek Trib07.g01 (geometry) ---

Geom Title=Existing Conditions

River Reach=Bull Creek Trib0,Reach-1
Reach XY= 30
      1338847.79      6919429.29      1338983.21      6919398.04
      1339785.29      6919404.99      1340031.82      6919384.15
      1340455.43      6919439.71      1340677.66      6919439.71
      1340826.96      6919363.32      1341076.96      6919321.65
      1341250.57      6919248.74      1341344.73      6919145.75
      1341494.58      6919136.98      1341560.97      6919090.33
      1341653.42      6919084.17      1341806.59      6918991.83
      1341907.42      6918982.46      1341995.22      6918898.46
      1342034.92      6918887.33      1342103.41      6918891.67
      1342221.71      6918954.63      1342299.48      6919035.56
      1342308.53      6919136.78      1342352.42      6919183.03
      1342403.22      6919184.67      1342465.54      6919139.12
      1342549.03      6919140.14      1342602.83      6919181.85
      1342661.05      6919196.16      1342752.57      6919282.49
      1342853.59      6919291.39      1342905.00      6919338.00

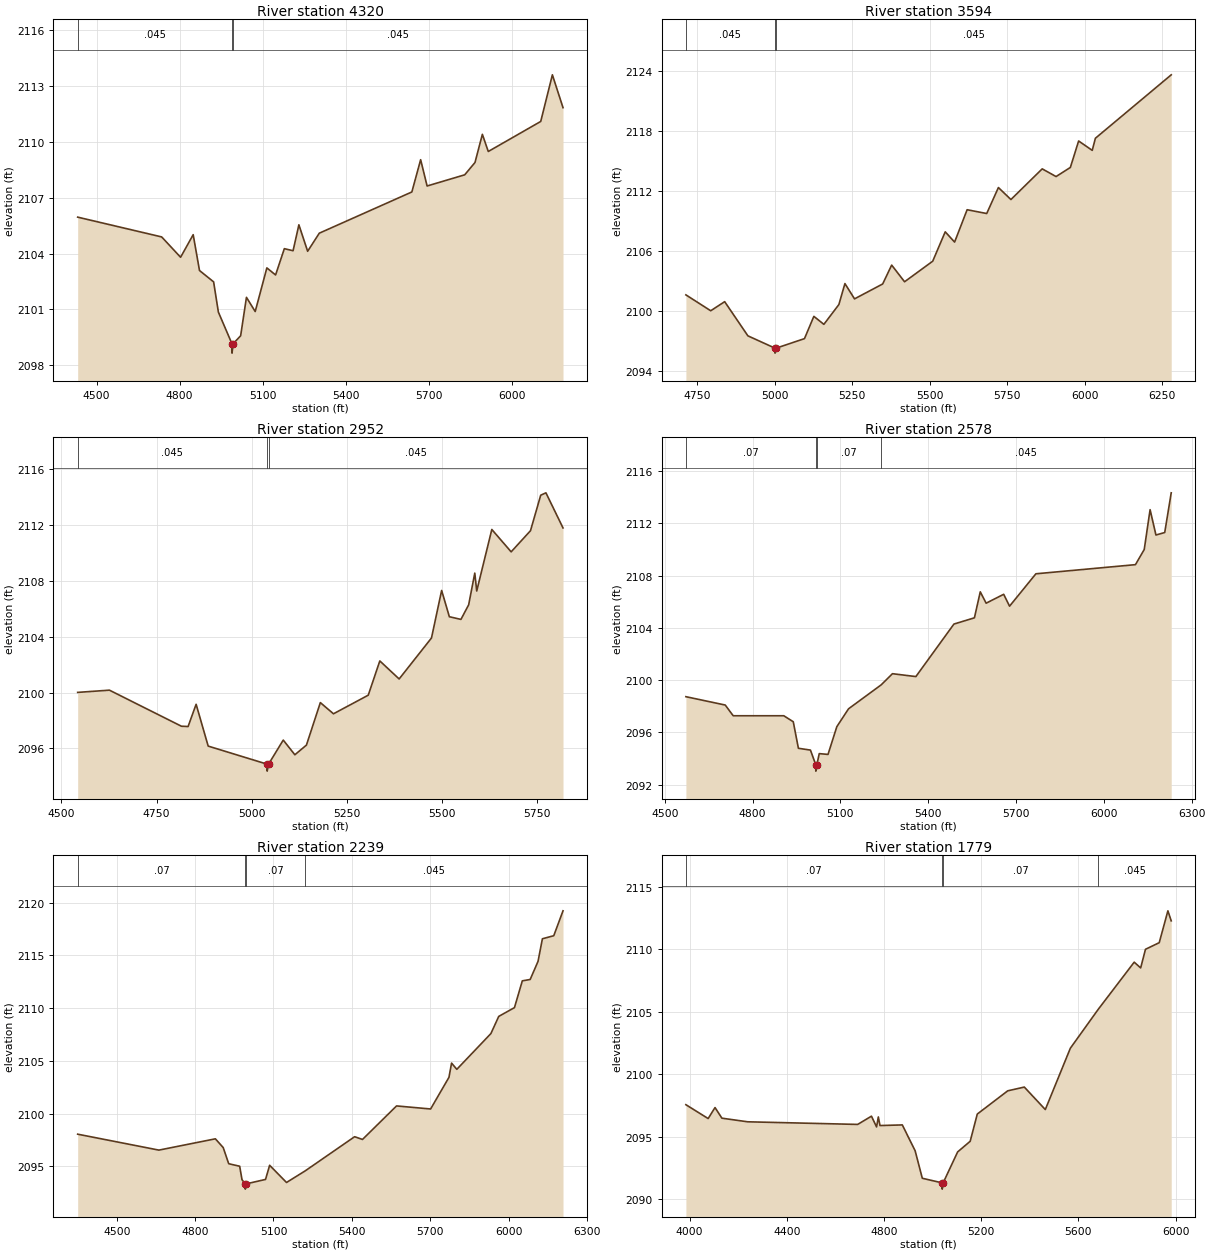
Type RM Length L Ch R = 1,4320,726,726,726
BEGIN DESCRIPTION:
Bull Creek Trib07 6.7
END DESCRIPTION:
XS GIS Cut Line= 3
      1338771.83      6919910.65      1339017.73      6919390.81
      1338650.80      6918271.49
#Sta/Elev= 30
  4431.8 2105.95  4735.2 2104.89  4803.5 2103.80  4849.0 2105.01  4871.8 2103.09
  4922.8 2102.48  4940.0 2100.86  4989.1 2099.16  4989.3 2098.66  4993.1 2099.16
  5020.4 2099.59  5041.4 2101.65  5073.0 2100.89  5115.1 2103.23  5146.6 2102.85
  5178.2 2104.26  5209.8 2104.15  5230.8 2105.54  5262.4 2104.12  5304.5 2105.09
  5638.8 2107.30  5670.6 2109.03  5693.9 2107.62  5829.8 2108.22  5866.9 2108.88
  5893.5 2110.39  5914.9 2109.47  6104.3 2111.08  6146.4 2113.58  6184.8 2111.82
#Mann=3,-1,0
  4431.8   0.045       0  4989.1   0.045       0  4993.1   0.045       0
Bank Sta=4989.1,4993.1
Exp/Cntr=0.3,0.1

Type RM Length L Ch R = 1,3594,642,642,642
BEGIN DESCRIPTION:
Bull Creek Trib07 6.6
END DESCRIPTION:
XS GIS Cut Line= 3
      1339617.54      6919659.20      1339742.56      6919416.85
      1339570.45      6918135.46
#Sta/Elev= 30
  4713.7 2101.62  4793.8 2100.03  4838.8 2100.94  4913.7 2097.52  5001.0 2096.29
  5001.2 2095.79  5005.0 2096.29  5096.2 2097.24  5126.5 2099.47  5158.8 2098.67
  5207.2 2100.65  5226.7 2102.75  5257.7 2101.22  5348.5 2102.71  5377.5 2104.60
  5419.1 2102.93  5509.9 2104.99  5550.3 2107.93  5580.5 2106.90  5620.9 2110.14
  5684.1 2109.76  5721.8 2112.36  5762.2 2111.16  5863.1 2114.23  5907.8 2113.46
  5953.9 2114.37  5980.6 2117.02  6024.5 2116.08  6034.6 2117.29  6279.3 2123.64
#Mann=3,-1,0
  4713.7   0.045       0  5001.0   0.045       0  5005.0   0.045       0
Bank Sta=5001,5005
Exp/Cntr=0.3,0.1

Type RM Length L Ch R = 1,2952,374,374,374
BEGIN DESCRIPTION:
Bull Creek Trib07 6.5
END DESCRIPTION:
XS GIS Cut Line= 3
      1340233.86      6919863.20      1340380.58      6919425.53
      1340240.16      6918623.74
#Sta/Elev= 30
  4542.8 2100.01  4626.2 2100.17  4815.5 2097.59  4833.0 2097.57  4854.1 2099.16
  4885.8 2096.17  5040.5 2094.88  5040.8 2094.38  5044.5 2094.88  5083.1 2096.60
  5113.6 2095.55  5144.0 2096.24  5180.6 2099.28  5215.1 2098.48  5306.5 2099.81
  5336.9 2102.26  5387.7 2100.97  5472.7 2103.90  5499.4 2107.30  5519.7 2105.42
  5550.1 2105.23  5570.4 2106.27  5586.5 2108.54  5591.6 2107.26  5631.3 2111.66
  5682.1 2110.06  5732.9 2111.57  5759.8 2114.11  5773.5 2114.28  5818.4 2111.77
#Mann=3,-1,0
  4542.8   0.045       0  5040.5   0.045       0  5044.5   0.045       0
Bank Sta=5040.5,5044.5
Exp/Cntr=0.3,0.1

Type RM Length L Ch R = 1,2578,339,339,339
BEGIN DESCRIPTION:
Bull Creek Trib07 6.4
END DESCRIPTION:
XS GIS Cut Line= 3
      1340620.92      6919814.74      1340743.59      6919422.92
      1340767.93      6918175.84
#Sta/Elev= 30
  4572.3 2098.73  4706.7 2098.09  4733.9 2097.27  4906.7 2097.27  4939.1 2096.81
  4956.6 2094.78  4997.8 2094.64  5015.8 2093.53  5016.1 2093.03  5019.8 2093.53
  5027.8 2094.37  5057.8 2094.31  5087.8 2096.43  5127.8 2097.80  5239.6 2099.64
  5277.9 2100.49  5357.9 2100.27  5487.9 2104.29  5557.9 2104.77  5577.9 2106.76
  5597.9 2105.89  5657.9 2106.57  5677.9 2105.66  5767.9 2108.14  6108.0 2108.84
  6138.0 2110.00  6158.0 2113.05  6178.0 2111.11  6208.0 2111.30  6230.2 2114.34
#Mann=4,-1,0
  4572.3    0.07       0  5015.8    0.07       0  5019.8    0.07       0
  5239.6   0.045       0
Bank Sta=5015.8,5019.8
Exp/Cntr=0.3,0.1

Type RM Length L Ch R = 1,2239,460,460,460
BEGIN DESCRIPTION:
Bull Creek Trib07 6.3
END DESCRIPTION:
XS GIS Cut Line= 3
      1340707.72      6919862.49      1341084.48      6919300.06
      1340994.08      6918122.68
#Sta/Elev= 30
  4350.6 2098.04  4661.5 2096.53  4877.7 2097.60  4907.7 2096.77  4928.7 2095.24
  4970.7 2095.00  4979.7 2093.72  4991.9 2093.33  4992.2 2092.83  4995.9 2093.33
  5069.7 2093.75  5085.4 2095.09  5150.0 2093.46  5220.9 2094.55  5410.7 2097.80
  5440.8 2097.54  5571.2 2100.72  5701.6 2100.43  5771.8 2103.43  5781.8 2104.78
  5801.9 2104.19  5932.3 2107.58  5962.4 2109.21  6022.5 2110.04  6052.6 2112.58
  6082.7 2112.71  6112.8 2114.43  6129.5 2116.57  6173.0 2116.86  6208.4 2119.22
#Mann=4,-1,0
  4350.6    0.07       0  4991.9    0.07       0  4995.9    0.07       0
  5220.9   0.045       0
Bank Sta=4991.9,4995.9
Exp/Cntr=0.3,0.1

Type RM Length L Ch R = 1,1779,228,228,228
BEGIN DESCRIPTION:
Bull Creek Trib07 6.0
END DESCRIPTION:
XS GIS Cut Line= 4
      1340785.88      6919858.11      1341459.09      6919229.14
      1341476.48      6919177.05      1341280.53      6918174.55
#Sta/Elev= 30
  3984.7 2097.56  4076.3 2096.45  4104.6 2097.33  4132.9 2096.48  4238.9 2096.19
  4691.8 2095.98  4748.5 2096.64  4769.5 2095.78  4776.8 2096.58  4783.6 2095.89
  4875.5 2095.94  4928.3 2093.87  4957.8 2091.67  5039.5 2091.30  5039.7 2090.80
  5043.5 2091.30  5103.3 2093.78  5154.9 2094.63  5184.1 2096.81  5309.5 2098.67
  5377.7 2098.97  5464.1 2097.17  5567.2 2102.08  5681.8 2105.19  5830.0 2108.97
  5856.6 2108.51  5876.4 2110.00  5933.0 2110.53  5968.7 2113.08  5982.4 2112.28
#Mann=4,-1,0
  3984.7    0.07       0  5039.5    0.07       0  5043.5    0.07       0
  5681.8   0.045       0
Bank Sta=5039.5,5043.5
Exp/Cntr=0.3,0.1

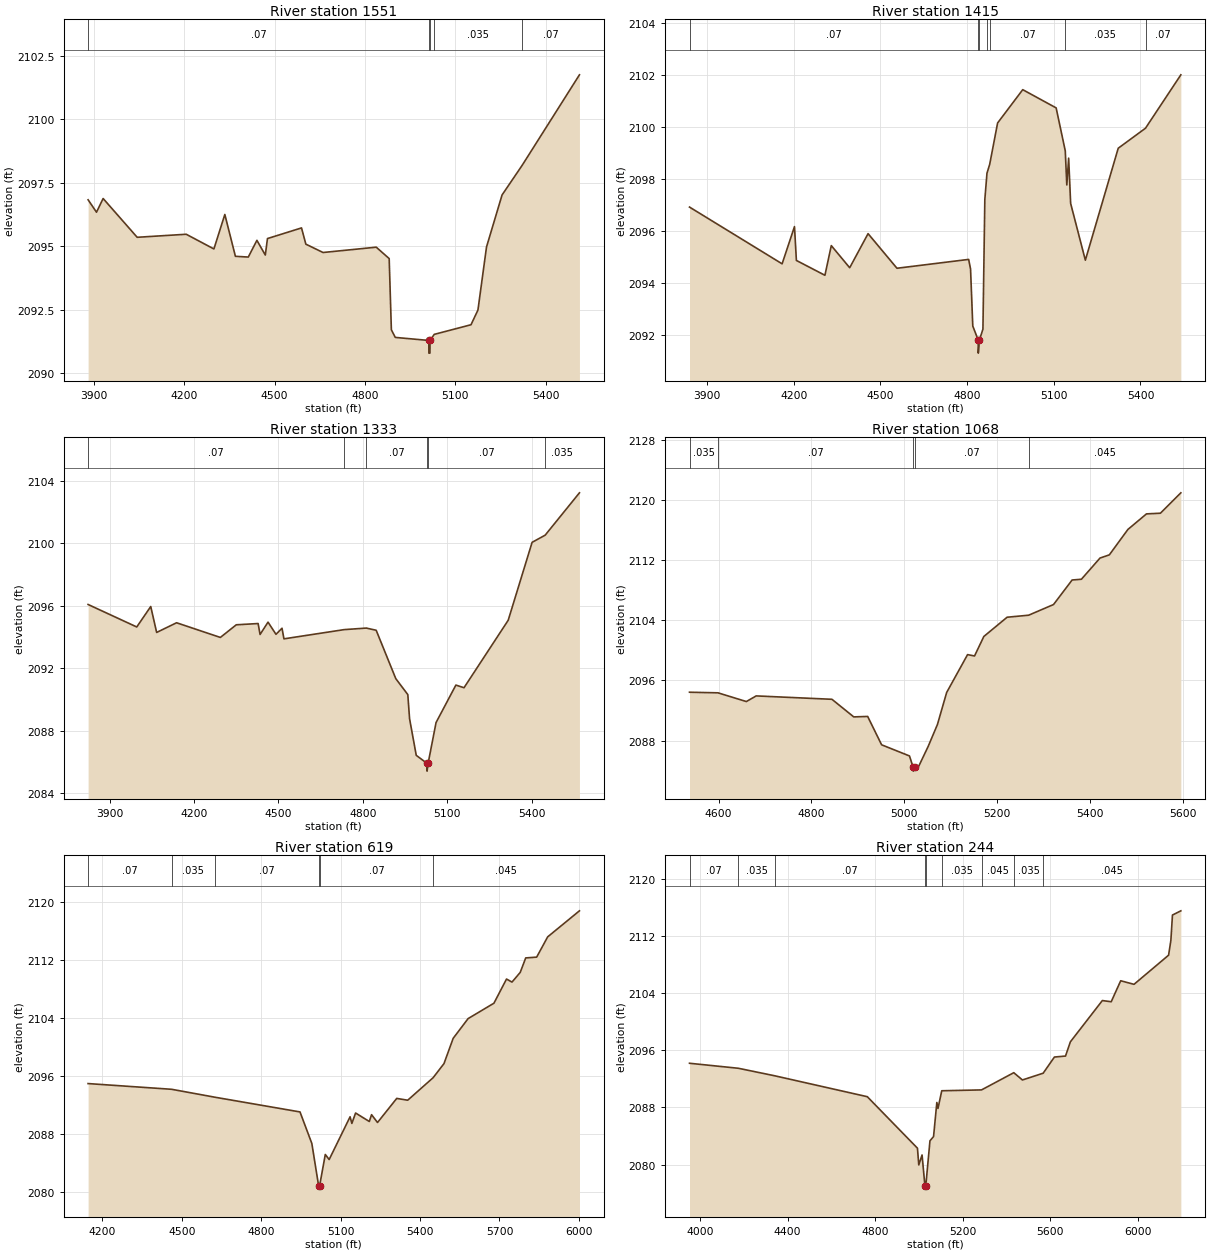
Type RM Length L Ch R = 1,1551,136,136,136
BEGIN DESCRIPTION:
Bull Creek Trib07 5.0
END DESCRIPTION:
XS GIS Cut Line= 3
      1341063.62      6919936.27      1341719.52      6919165.00
      1341462.02      6918601.72
#Sta/Elev= 30
  3880.7 2096.83  3908.6 2096.34  3930.6 2096.88  4043.7 2095.35  4206.6 2095.47
  4298.5 2094.89  4334.8 2096.25  4369.9 2094.60  4412.7 2094.57  4441.3 2095.23
  4469.2 2094.65  4476.4 2095.30  4589.5 2095.72  4603.8 2095.08  4660.9 2094.75
  4837.7 2094.96  4880.6 2094.51  4887.9 2091.70  4900.9 2091.40  5012.3 2091.28
  5012.5 2090.78  5016.0 2090.78  5016.3 2091.28  5030.3 2091.52  5152.4 2091.90
  5175.4 2092.48  5203.9 2094.97  5255.5 2097.02  5322.3 2098.19  5512.5 2101.76
#Mann=5,-1,0
  3880.7    0.07       0  5012.3    0.07       0  5016.3    0.07       0
  5030.3   0.035       0  5322.3    0.07       0
Bank Sta=5012.3,5016.3
Exp/Cntr=0.3,0.1

Type RM Length L Ch R = 1,1415,82,82,82
BEGIN DESCRIPTION:
Bull Creek Trib07 4.5
END DESCRIPTION:
XS GIS Cut Line= 4
      1341120.06      6919914.56      1341797.45      6919120.70
      1341789.16      6918996.87      1341459.27      6918578.47
#Sta/Elev= 30
  3839.2 2096.93  4159.7 2094.75  4202.5 2096.18  4209.1 2094.88  4307.9 2094.31
  4329.9 2095.45  4393.6 2094.60  4457.2 2095.91  4557.2 2094.58  4805.3 2094.92
  4811.9 2094.55  4819.6 2092.36  4838.4 2091.82  4838.7 2091.32  4842.4 2091.82
  4854.7 2092.24  4861.3 2097.22  4868.7 2098.23  4878.1 2098.57  4905.5 2100.16
  4992.5 2101.44  5108.1 2100.74  5139.7 2099.09  5145.0 2097.78  5151.4 2098.81
  5158.3 2097.07  5209.2 2094.89  5323.0 2099.19  5417.4 2099.96  5539.7 2102.01
#Mann=7,-1,0
  3839.2    0.07       0  4838.4    0.07       0  4842.4    0.07       0
  4868.7   0.035       0  4878.1    0.07       0  5139.7   0.035       0
  5417.4    0.07       0
Bank Sta=4838.4,4842.4
Exp/Cntr=0.3,0.1

Type RM Length L Ch R = 1,1333,265,265,265
BEGIN DESCRIPTION:
Bull Creek Trib07 4.0
END DESCRIPTION:
XS GIS Cut Line= 5
      1341202.55      6919910.18      1341823.18      6919259.18
      1341872.74      6919056.13      1341864.68      6918951.29
      1341534.48      6918532.50
#Sta/Elev= 30
  3823.4 2096.07  3996.4 2094.63  4046.1 2095.94  4067.1 2094.28  4137.9 2094.90
  4293.6 2093.96  4350.2 2094.77  4427.9 2094.85  4434.8 2094.15  4463.1 2094.94
  4491.4 2094.16  4512.8 2094.55  4519.7 2093.87  4733.5 2094.46  4812.4 2094.56
  4847.6 2094.42  4917.4 2091.32  4960.1 2090.30  4966.3 2088.76  4990.1 2086.41
  5028.3 2085.90  5028.5 2085.40  5032.3 2085.90  5060.5 2088.51  5131.0 2090.91
  5159.9 2090.74  5317.0 2095.06  5402.0 2100.05  5448.5 2100.51  5570.3 2103.22
#Mann=6,-1,0
  3823.4    0.07       0  4733.5   0.035       0  4812.4    0.07       0
  5028.3    0.07       0  5032.3    0.07       0  5448.5   0.035       0
Bank Sta=5028.3,5032.3
Exp/Cntr=0.3,0.1

Type RM Length L Ch R = 1,1068,449,449,449
BEGIN DESCRIPTION:
Bull Creek Trib07 3.0
END DESCRIPTION:
XS GIS Cut Line= 3
      1341870.57      6919266.44      1342098.55      6919003.71
      1342074.36      6918294.07
#Sta/Elev= 30
  4537.5 2094.44  4598.8 2094.36  4659.9 2093.20  4681.1 2093.95  4844.2 2093.50
  4891.1 2091.16  4921.1 2091.22  4951.1 2087.45  5011.1 2085.97  5019.1 2084.45
  5019.3 2083.95  5023.2 2084.45  5031.1 2084.61  5051.2 2087.21  5071.2 2090.13
  5091.2 2094.41  5136.2 2099.44  5151.2 2099.26  5171.2 2101.85  5221.3 2104.41
  5267.7 2104.68  5321.3 2106.10  5361.3 2109.36  5381.3 2109.46  5421.4 2112.28
  5441.4 2112.70  5481.4 2116.08  5521.4 2118.15  5551.4 2118.24  5595.4 2120.95
#Mann=5,-1,0
  4537.5   0.035       0  4598.8    0.07       0  5019.1    0.07       0
  5023.2    0.07       0  5267.7   0.045       0
Bank Sta=5019.1,5023.2
Exp/Cntr=0.3,0.1

Type RM Length L Ch R = 1,619,375,375,375
BEGIN DESCRIPTION:
Bull Creek Trib07 2.0
END DESCRIPTION:
XS GIS Cut Line= 4
      1341574.34      6919447.26      1342364.68      6919217.42
      1342396.94      6919112.58      1342155.20      6918222.18
#Sta/Elev= 30
  4146.5 2094.92  4461.9 2094.13  4624.6 2093.04  4946.7 2091.00  4991.4 2086.64
  5016.8 2080.83  5017.1 2080.33  5020.9 2080.83  5042.2 2085.12  5056.8 2084.42
  5135.8 2090.33  5142.5 2089.41  5156.6 2090.85  5208.4 2089.68  5216.9 2090.62
  5239.4 2089.54  5312.0 2092.87  5353.4 2092.62  5449.3 2095.73  5490.4 2097.68
  5525.0 2101.17  5581.4 2103.90  5679.0 2106.03  5726.5 2109.37  5747.2 2108.95
  5778.3 2110.29  5799.0 2112.29  5840.4 2112.40  5881.9 2115.20  6001.9 2118.80
#Mann=6,-1,0
  4146.5    0.07       0  4461.9   0.035       0  4624.6    0.07       0
  5016.8    0.07       0  5020.9    0.07       0  5449.3   0.045       0
Bank Sta=5016.8,5020.9
Exp/Cntr=0.3,0.1

Type RM Length L Ch R = 1,244,0,0,0
BEGIN DESCRIPTION:
Bull Creek Trib07 1.0
END DESCRIPTION:
XS GIS Cut Line= 4
      1341683.24      6919431.13      1342679.19      6919265.81
      1342735.65      6919181.13      1342409.60      6918094.33
#Sta/Elev= 30
  3951.7 2094.19  4174.7 2093.49  4342.2 2092.43  4764.4 2089.51  4993.7 2082.30
  4999.7 2079.96  5014.8 2081.35  5027.7 2077.07  5028.0 2076.57  5031.9 2077.07
  5050.8 2083.33  5067.3 2083.93  5082.3 2088.70  5087.6 2087.87  5104.8 2090.34
  5286.6 2090.46  5434.0 2092.87  5473.5 2091.85  5568.4 2092.80  5619.7 2095.06
  5670.5 2095.20  5692.7 2097.19  5838.9 2102.97  5879.3 2102.80  5922.8 2105.74
  5983.7 2105.24  6141.7 2109.32  6152.1 2111.39  6159.4 2114.94  6197.7 2115.53
#Mann=9,-1,0
  3951.7    0.07       0  4174.7   0.035       0  4342.2    0.07       0
  5027.7    0.07       0  5031.9    0.07       0  5104.8   0.035       0
  5286.6   0.045       0  5434.0   0.035       0  5568.4   0.045       0
Bank Sta=5027.7,5031.9
Exp/Cntr=0.3,0.1

Chan Stop Cuts=-1