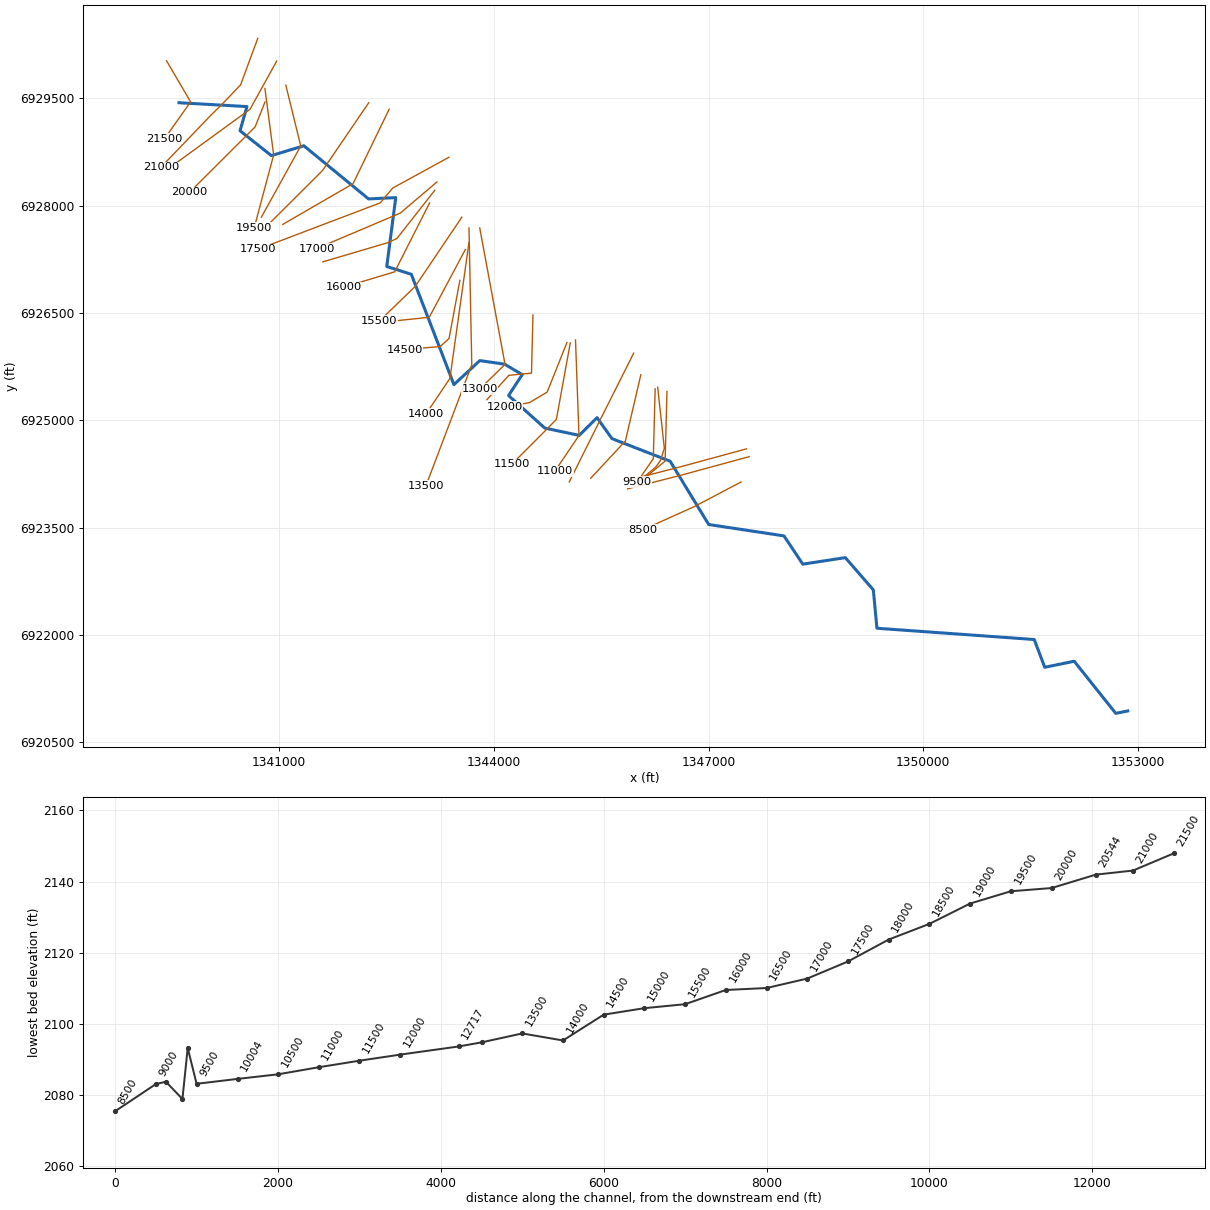
--- Bull Creek Trib097.prj (project) ---

Proj Title=Bull Creek Trib097 Base Level Engineering
Current Plan=p01
Default Exp/Contr=0.3,0.1
English Units
Geom File=g01
Flow File=f01
Plan File=p01
BEGIN DESCRIPTION:
Bull Creek Trib097
END DESCRIPTION:

--- Bull Creek Trib097.p01 (plan) ---

Plan Title=Multiple Run
Short Identifier=Multiple
Geom File=g01
Flow File=f01
Subcritical Flow
K Sum by GR= 0
Std Step Tol= 0.01
Critical Tol= 0.01
Num of Std Step Trials= 20
Max Error Tol= 0.3
Flow Tol Ratio= 0.001
Split Flow NTrial= 30
Split Flow Tol= 0.02
Split Flow Ratio= 0.02
Log Output Level= 0
Friction Slope Method= 1
Unsteady Friction Slope Method= 2
Unsteady Bridges Friction Slope Method= 1
Parabolic Critical Depth
Global Vel Dist=  1 , 1 , 1
Global Log Level= 0
CheckData=True
Encroach Param= -1, 0, 0, 0
BEGIN DESCRIPTION:
Multiple Run
END DESCRIPTION:

--- Bull Creek Trib097.f01 (steady flow) ---

Flow Title=Multiple
Number of Profiles=7
Profile Names=10-year,25-year,50-year,1pct_min,100-year,1pct_plu,500-year
River Rch & RM= Bull Creek Trib0,Reach-1,21500
     314     452     571     359     716    1429    1141
River Rch & RM= Bull Creek Trib0,Reach-1,18000
     440     642     816     516    1029    2054    1659
River Rch & RM= Bull Creek Trib0,Reach-1,9500
     527     775     991     629    1254    2503    2040
River Rch & RM= Bull Creek Trib0,Reach-1,5500
     629     931    1195     761    1519    3031    2488
River Rch & RM= Bull Creek Trib0,Reach-1,1000
     721    1074    1385     886    1767    3526    2917
Boundary for River Rch & Prof#=Bull Creek Trib0,Reach-1,1
Up Type=0
Dn Type=3
Dn Slope=0.005
Boundary for River Rch & Prof#=Bull Creek Trib0,Reach-1,2
Up Type=0
Dn Type=3
Dn Slope=0.005
Boundary for River Rch & Prof#=Bull Creek Trib0,Reach-1,3
Up Type=0
Dn Type=3
Dn Slope=0.005
Boundary for River Rch & Prof#=Bull Creek Trib0,Reach-1,4
Up Type=0
Dn Type=3
Dn Slope=0.005
Boundary for River Rch & Prof#=Bull Creek Trib0,Reach-1,5
Up Type=0
Dn Type=3
Dn Slope=0.005
Boundary for River Rch & Prof#=Bull Creek Trib0,Reach-1,6
Up Type=0
Dn Type=3
Dn Slope=0.005
Boundary for River Rch & Prof#=Bull Creek Trib0,Reach-1,7
Up Type=0
Dn Type=3
Dn Slope=0.005

--- Bull Creek Trib097.g01 (geometry) ---

Geom Title=Existing Conditions

River Reach=Bull Creek Trib0,Reach-1
Reach XY= 30
      1339605.00      6929438.00      1340553.99      6929384.39
      1340457.59      6929046.45      1340894.98      6928698.94
      1341348.96      6928836.35      1342252.57      6928093.52
      1342632.29      6928112.16      1342506.51      6927149.87
      1342849.48      6927040.46      1343444.70      6925498.87
      1343806.55      6925834.25      1344153.42      6925784.17
      1344398.02      6925638.21      1344207.89      6925346.03
      1344713.11      6924891.31      1345194.49      6924789.20
      1345442.92      6925036.90      1345652.54      6924743.46
      1346464.80      6924427.52      1347002.55      6923543.46
      1348053.54      6923384.46      1348316.81      6922989.62
      1348911.05      6923080.54      1349301.84      6922629.66
      1349352.41      6922093.71      1351549.32      6921936.12
      1351695.32      6921548.16      1352107.43      6921632.48
      1352687.85      6920904.02      1352855.00      6920938.00

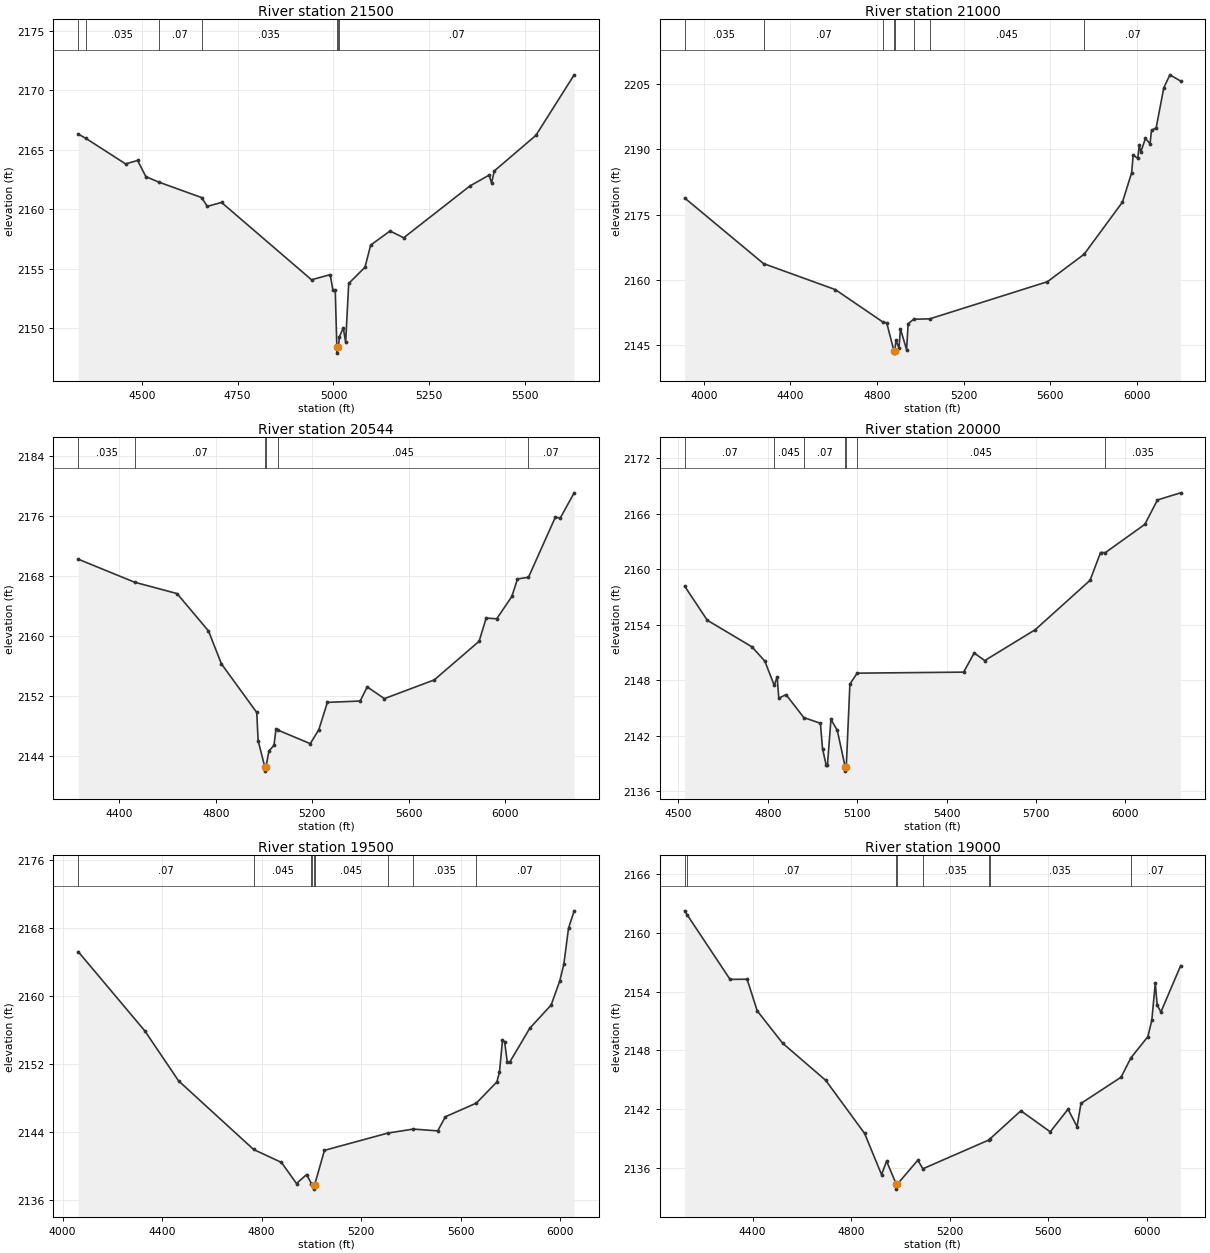
Type RM Length L Ch R = 1,21500,500,500,500
BEGIN DESCRIPTION:
Bull Creek Trib097 43.0
END DESCRIPTION:
XS GIS Cut Line= 3
      1339430.53      6930024.65      1339767.15      6929450.45
      1339405.00      6928938.00
#Sta/Elev= 30
  4334.4 2166.33  4354.8 2165.96  4458.0 2163.82  4489.3 2164.11  4510.8 2162.75
  4544.5 2162.29  4656.1 2160.99  4671.0 2160.25  4708.1 2160.58  4942.7 2154.08
  4991.5 2154.51  4998.5 2153.20  5004.6 2153.20  5008.8 2148.41  5009.0 2147.91
  5012.8 2148.41  5015.5 2149.29  5025.5 2150.04  5031.7 2148.83  5039.7 2153.77
  5082.1 2155.13  5096.9 2156.99  5147.4 2158.18  5183.1 2157.61  5355.5 2161.96
  5405.9 2162.88  5412.1 2162.21  5419.3 2163.23  5527.8 2166.22  5627.5 2171.31
#Mann=7,-1,0
  4334.4    0.07       0  4354.8   0.035       0  4544.5    0.07       0
  4656.1   0.035       0  5008.8   0.035       0  5012.8   0.035       0
  5015.5    0.07       0
Bank Sta=5008.8,5012.8
Exp/Cntr=0.3,0.1

Type RM Length L Ch R = 1,21000,456,456,456
BEGIN DESCRIPTION:
Bull Creek Trib097 42.0
END DESCRIPTION:
XS GIS Cut Line= 5
      1340705.00      6930338.00      1340465.68      6929688.66
      1340192.29      6929401.40      1340070.69      6929284.59
      1339355.02      6928538.02
#Sta/Elev= 30
  3911.4 2178.81  4275.7 2163.70  4607.3 2157.71  4830.0 2150.15  4844.8 2150.06
  4878.4 2143.58  4878.7 2143.08  4882.4 2143.58  4887.3 2146.02  4901.5 2144.29
  4908.4 2148.66  4936.7 2143.86  4943.9 2149.84  4969.4 2150.89  5043.4 2150.97
  5587.5 2159.53  5756.9 2165.85  5934.1 2177.86  5976.6 2184.63  5983.5 2188.71
  6004.9 2187.92  6011.8 2190.91  6019.0 2189.41  6040.1 2192.53  6061.5 2191.31
  6068.4 2194.40  6089.8 2194.95  6125.0 2204.18  6153.3 2207.17  6202.8 2205.74
#Mann=8,-1,0
  3911.4   0.035       0  4275.7    0.07       0  4830.0   0.045       0
  4878.4    0.07       0  4882.4   0.045       0  4969.4    0.07       0
  5043.4   0.045       0  5756.9    0.07       0
Bank Sta=4878.4,4882.4
Exp/Cntr=0.3,0.1

Type RM Length L Ch R = 1,20544,544,544,544
BEGIN DESCRIPTION:
Bull Creek Trib097 41.0
END DESCRIPTION:
XS GIS Cut Line= 3
      1340969.62      6930020.07      1340596.47      6929345.81
      1339555.02      6928588.01
#Sta/Elev= 30
  4228.7 2170.24  4463.1 2167.16  4638.9 2165.65  4769.4 2160.66  4823.2 2156.26
  4969.8 2149.77  4975.5 2146.01  5003.7 2142.44  5004.0 2141.94  5007.7 2142.44
  5020.4 2144.64  5041.3 2145.39  5049.8 2147.59  5058.2 2147.41  5191.9 2145.61
  5227.5 2147.48  5263.0 2151.12  5399.0 2151.30  5428.4 2153.19  5499.5 2151.62
  5706.6 2154.12  5892.8 2159.28  5922.2 2162.38  5965.8 2162.28  6028.8 2165.27
  6052.0 2167.60  6097.6 2167.82  6208.9 2175.82  6229.7 2175.74  6287.3 2179.10
#Mann=6,-1,0
  4228.7   0.035       0  4463.1    0.07       0  5003.7    0.07       0
  5007.7    0.07       0  5058.2   0.045       0  6097.6    0.07       0
Bank Sta=5003.7,5007.7
Exp/Cntr=0.3,0.1

Type RM Length L Ch R = 1,20000,500,500,500
BEGIN DESCRIPTION:
Bull Creek Trib097 40.0
END DESCRIPTION:
XS GIS Cut Line= 4
      1340806.18      6929448.01      1340667.95      6929100.46
      1340594.07      6929025.60      1339754.99      6928187.99
#Sta/Elev= 30
  4520.8 2158.15  4596.6 2154.47  4746.8 2151.59  4789.9 2150.05  4821.4 2147.43
  4831.3 2148.35  4836.7 2146.04  4861.0 2146.43  4920.7 2143.95  4976.4 2143.33
  4983.5 2140.60  4995.8 2138.80  5000.0 2138.80  5011.8 2143.75  5033.0 2142.58
  5059.3 2138.66  5059.5 2138.16  5063.3 2138.66  5075.4 2147.57  5099.9 2148.75
  5457.3 2148.86  5492.6 2150.93  5528.0 2150.11  5697.7 2153.45  5881.5 2158.78
  5916.9 2161.79  5933.1 2161.78  6065.4 2164.83  6107.8 2167.47  6185.6 2168.24
#Mann=7,-1,0
  4520.8    0.07       0  4821.4   0.045       0  4920.7    0.07       0
  5059.3    0.07       0  5063.3    0.07       0  5099.9   0.045       0
  5933.1   0.035       0
Bank Sta=5059.3,5063.3
Exp/Cntr=0.3,0.1

Type RM Length L Ch R = 1,19500,500,500,500
BEGIN DESCRIPTION:
Bull Creek Trib097 39.0
END DESCRIPTION:
XS GIS Cut Line= 3
      1340805.00      6929638.02      1340926.86      6928708.98
      1340654.99      6927687.95
#Sta/Elev= 30
  4063.0 2165.18  4331.2 2155.85  4466.4 2149.99  4768.2 2141.92  4880.0 2140.40
  4940.5 2137.92  4980.8 2138.97  5000.6 2137.91  5001.4 2137.91  5009.4 2137.76
  5009.6 2137.26  5013.4 2137.76  5052.8 2141.82  5307.8 2143.85  5409.8 2144.32
  5508.1 2144.11  5539.1 2145.77  5663.7 2147.38  5746.1 2149.87  5756.4 2151.03
  5768.5 2154.74  5777.1 2154.59  5787.5 2152.26  5797.8 2152.20  5878.6 2156.19
  5964.0 2158.90  5998.9 2161.75  6015.2 2163.72  6033.9 2167.93  6056.6 2169.98
#Mann=9,-1,0
  4063.0    0.07       0  4768.2   0.045       0  5000.6    0.07       0
  5001.4   0.045       0  5009.4   0.045       0  5013.4   0.045       0
  5307.8    0.07       0  5409.8   0.035       0  5663.7    0.07       0
Bank Sta=5009.4,5013.4
Exp/Cntr=0.3,0.1

Type RM Length L Ch R = 1,19000,500,500,500
BEGIN DESCRIPTION:
Bull Creek Trib097 38.0
END DESCRIPTION:
XS GIS Cut Line= 3
      1341096.75      6929684.15      1341305.08      6928833.60
      1340754.98      6927837.96
#Sta/Elev= 30
  4124.3 2162.25  4133.7 2161.87  4308.5 2155.24  4377.7 2155.26  4418.9 2152.02
  4521.9 2148.72  4696.9 2144.92  4854.5 2139.50  4923.4 2135.29  4944.0 2136.66
  4983.2 2134.30  4983.4 2133.80  4987.2 2134.30  5070.9 2136.76  5091.2 2135.88
  5360.5 2138.84  5361.7 2138.89  5489.0 2141.81  5608.2 2139.66  5680.5 2141.97
  5717.0 2140.19  5733.0 2142.56  5895.7 2145.24  5935.7 2147.22  6004.6 2149.39
  6020.6 2151.07  6034.6 2154.86  6042.4 2152.61  6057.5 2151.91  6137.5 2156.64
#Mann=8,-1,0
  4124.3   0.035       0  4133.7    0.07       0  4983.2    0.07       0
  4987.2    0.07       0  5091.2   0.035       0  5360.5   0.045       0
  5361.7   0.035       0  5935.7    0.07       0
Bank Sta=4983.2,4987.2
Exp/Cntr=0.3,0.1

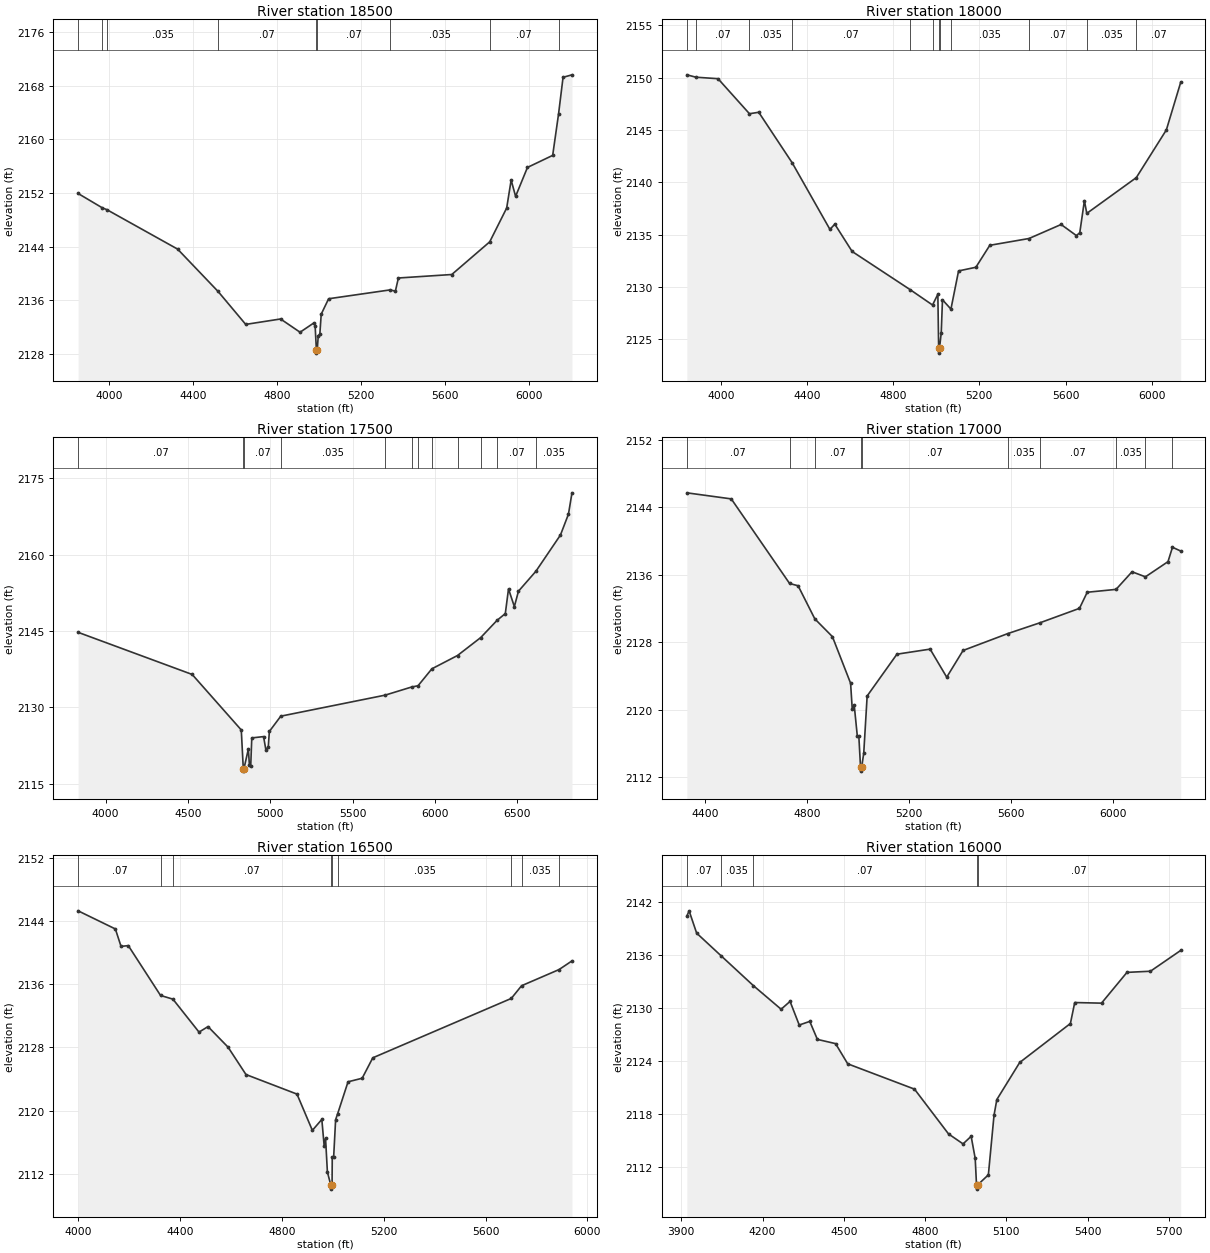
Type RM Length L Ch R = 1,18500,500,500,500
BEGIN DESCRIPTION:
Bull Creek Trib097 37.0
END DESCRIPTION:
XS GIS Cut Line= 3
      1342254.99      6929437.98      1341609.34      6928490.56
      1340754.98      6927637.98
#Sta/Elev= 30
  3853.5 2151.92  3968.1 2149.79  3990.8 2149.50  4327.8 2143.61  4520.5 2137.29
  4652.2 2132.37  4818.4 2133.18  4911.2 2131.20  4977.0 2132.59  4983.0 2132.14
  4989.0 2128.58  4989.3 2128.08  4993.0 2128.58  4997.9 2130.68  5005.4 2130.90
  5012.0 2133.90  5047.3 2136.20  5339.6 2137.52  5365.5 2137.34  5379.7 2139.30
  5634.2 2139.82  5815.0 2144.70  5895.8 2149.75  5917.1 2153.92  5938.3 2151.49
  5994.8 2155.81  6115.0 2157.61  6143.0 2163.79  6164.5 2169.27  6207.0 2169.64
#Mann=9,-1,0
  3853.5   0.035       0  3968.1    0.07       0  3990.8   0.035       0
  4520.5    0.07       0  4989.0    0.07       0  4993.0    0.07       0
  5339.6   0.035       0  5815.0    0.07       0  6143.0   0.035       0
Bank Sta=4989,4993
Exp/Cntr=0.3,0.1

Type RM Length L Ch R = 1,18000,500,500,500
BEGIN DESCRIPTION:
Bull Creek Trib097 36.0
END DESCRIPTION:
XS GIS Cut Line= 3
      1342540.49      6929348.13      1342036.10      6928306.86
      1341054.99      6927738.00
#Sta/Elev= 30
  3843.0 2150.28  3886.0 2150.05  3987.6 2149.91  4133.4 2146.56  4176.5 2146.70
  4331.3 2141.88  4506.8 2135.50  4529.4 2136.00  4609.8 2133.39  4880.3 2129.72
  4982.8 2128.27  5007.4 2129.30  5011.1 2124.17  5011.4 2123.67  5015.2 2124.17
  5023.1 2125.61  5028.9 2128.77  5068.1 2127.88  5103.5 2131.53  5183.8 2131.88
  5248.4 2133.98  5430.3 2134.63  5579.2 2135.97  5650.0 2134.91  5665.8 2135.18
  5687.3 2138.25  5698.3 2137.03  5928.0 2140.45  6067.4 2145.01  6134.1 2149.57
#Mann=12,-1,0
  3843.0   0.035       0  3886.0    0.07       0  4133.4   0.035       0
  4331.3    0.07       0  4880.3   0.035       0  4982.8    0.07       0
  5011.1    0.07       0  5015.2    0.07       0  5068.1   0.035       0
  5430.3    0.07       0  5698.3   0.035       0  5928.0    0.07       0
Bank Sta=5011.1,5015.2
Exp/Cntr=0.3,0.1

Type RM Length L Ch R = 1,17500,500,500,500
BEGIN DESCRIPTION:
Bull Creek Trib097 35.0
END DESCRIPTION:
XS GIS Cut Line= 4
      1343375.89      6928676.23      1342589.79      6928245.46
      1342416.20      6928038.65      1340705.02      6927388.01
#Sta/Elev= 30
  3833.6 2144.75  4525.8 2136.48  4823.8 2125.58  4836.0 2118.00  4836.3 2117.50
  4840.1 2118.00  4866.7 2121.83  4873.2 2118.69  4881.0 2118.41  4887.5 2124.02
  4959.1 2124.28  4973.4 2121.62  4987.7 2122.29  4994.2 2125.29  5063.5 2128.29
  5697.1 2132.42  5857.0 2134.01  5896.5 2134.26  5980.5 2137.59  6136.0 2140.20
  6277.1 2143.73  6376.5 2147.12  6426.1 2148.43  6445.5 2153.28  6481.0 2149.80
  6505.8 2152.82  6611.7 2156.74  6760.8 2163.86  6809.3 2167.95  6830.7 2172.14
#Mann=12,-1,0
  3833.6    0.07       0  4836.0    0.07       0  4840.1    0.07       0
  5063.5   0.035       0  5697.1    0.07       0  5857.0   0.035       0
  5896.5    0.07       0  5980.5   0.035       0  6136.0    0.07       0
  6277.1   0.035       0  6376.5    0.07       0  6611.7   0.035       0
Bank Sta=4836,4840.1
Exp/Cntr=0.3,0.1

Type RM Length L Ch R = 1,17000,500,500,500
BEGIN DESCRIPTION:
Bull Creek Trib097 34.0
END DESCRIPTION:
XS GIS Cut Line= 3
      1343207.93      6928331.20      1342695.56      6927895.78
      1341529.01      6927400.85
#Sta/Elev= 30
  4327.6 2145.72  4502.1 2145.00  4731.1 2134.96  4764.5 2134.69  4830.2 2130.76
  4899.3 2128.65  4970.7 2123.12  4977.2 2120.04  4984.9 2120.52  4997.1 2116.84
  5003.0 2116.84  5009.7 2113.19  5010.0 2112.69  5014.3 2113.19  5022.3 2114.81
  5035.7 2121.61  5152.7 2126.57  5283.0 2127.17  5348.2 2123.84  5412.4 2127.01
  5587.7 2129.01  5714.8 2130.30  5869.6 2132.01  5900.0 2133.92  6013.2 2134.26
  6076.0 2136.35  6128.6 2135.75  6217.2 2137.55  6234.8 2139.26  6267.2 2138.81
#Mann=10,-1,0
  4327.6    0.07       0  4731.1   0.035       0  4830.2    0.07       0
  5009.7    0.07       0  5014.3    0.07       0  5587.7   0.035       0
  5714.8    0.07       0  6013.2   0.035       0  6128.6    0.07       0
  6234.8   0.035       0
Bank Sta=5009.7,5014.3
Exp/Cntr=0.3,0.1

Type RM Length L Ch R = 1,16500,500,500,500
BEGIN DESCRIPTION:
Bull Creek Trib097 33.0
END DESCRIPTION:
XS GIS Cut Line= 4
      1343176.14      6928213.16      1342647.98      6927539.98
      1342515.09      6927480.34      1341614.35      6927214.32
#Sta/Elev= 30
  3998.7 2145.32  4145.1 2143.02  4167.4 2140.81  4195.9 2140.91  4322.6 2134.59
  4371.2 2134.12  4473.8 2129.94  4509.1 2130.64  4587.7 2128.04  4658.3 2124.56
  4858.7 2122.08  4919.1 2117.48  4956.3 2118.87  4965.4 2115.55  4970.9 2116.47
  4978.2 2112.20  4991.7 2110.53  4992.0 2110.03  4996.5 2110.53  4997.3 2114.05
  5002.7 2114.05  5010.5 2118.84  5018.6 2119.60  5059.3 2123.64  5114.8 2124.09
  5156.5 2126.68  5700.7 2134.21  5741.1 2135.82  5888.3 2137.87  5939.2 2138.97
#Mann=9,-1,0
  3998.7    0.07       0  4322.6   0.035       0  4371.2    0.07       0
  4991.7    0.07       0  4996.5    0.07       0  5018.6   0.035       0
  5700.7    0.07       0  5741.1   0.035       0  5888.3    0.07       0
Bank Sta=4991.7,4996.5
Exp/Cntr=0.3,0.1

Type RM Length L Ch R = 1,16000,500,500,500
BEGIN DESCRIPTION:
Bull Creek Trib097 32.0
END DESCRIPTION:
XS GIS Cut Line= 3
      1343105.00      6928038.00      1342617.46      6927074.86
      1341904.89      6926860.18
#Sta/Elev= 30
  3920.5 2140.44  3928.8 2141.04  3956.7 2138.51  4046.6 2135.95  4166.4 2132.55
  4268.6 2129.88  4301.6 2130.77  4335.5 2128.09  4374.4 2128.50  4402.5 2126.46
  4469.7 2125.98  4514.5 2123.69  4761.1 2120.82  4886.8 2115.74  4940.4 2114.61
  4970.3 2115.47  4985.3 2112.96  4990.1 2109.98  4990.5 2109.48  4995.1 2109.98
  5033.9 2111.10  5054.8 2117.86  5065.2 2119.64  5149.6 2123.84  5336.8 2128.26
  5352.8 2130.64  5451.7 2130.57  5545.7 2134.06  5632.4 2134.19  5744.2 2136.55
#Mann=5,-1,0
  3920.5    0.07       0  4046.6   0.035       0  4166.4    0.07       0
  4990.1    0.07       0  4995.1    0.07       0
Bank Sta=4990.1,4995.1
Exp/Cntr=0.3,0.1

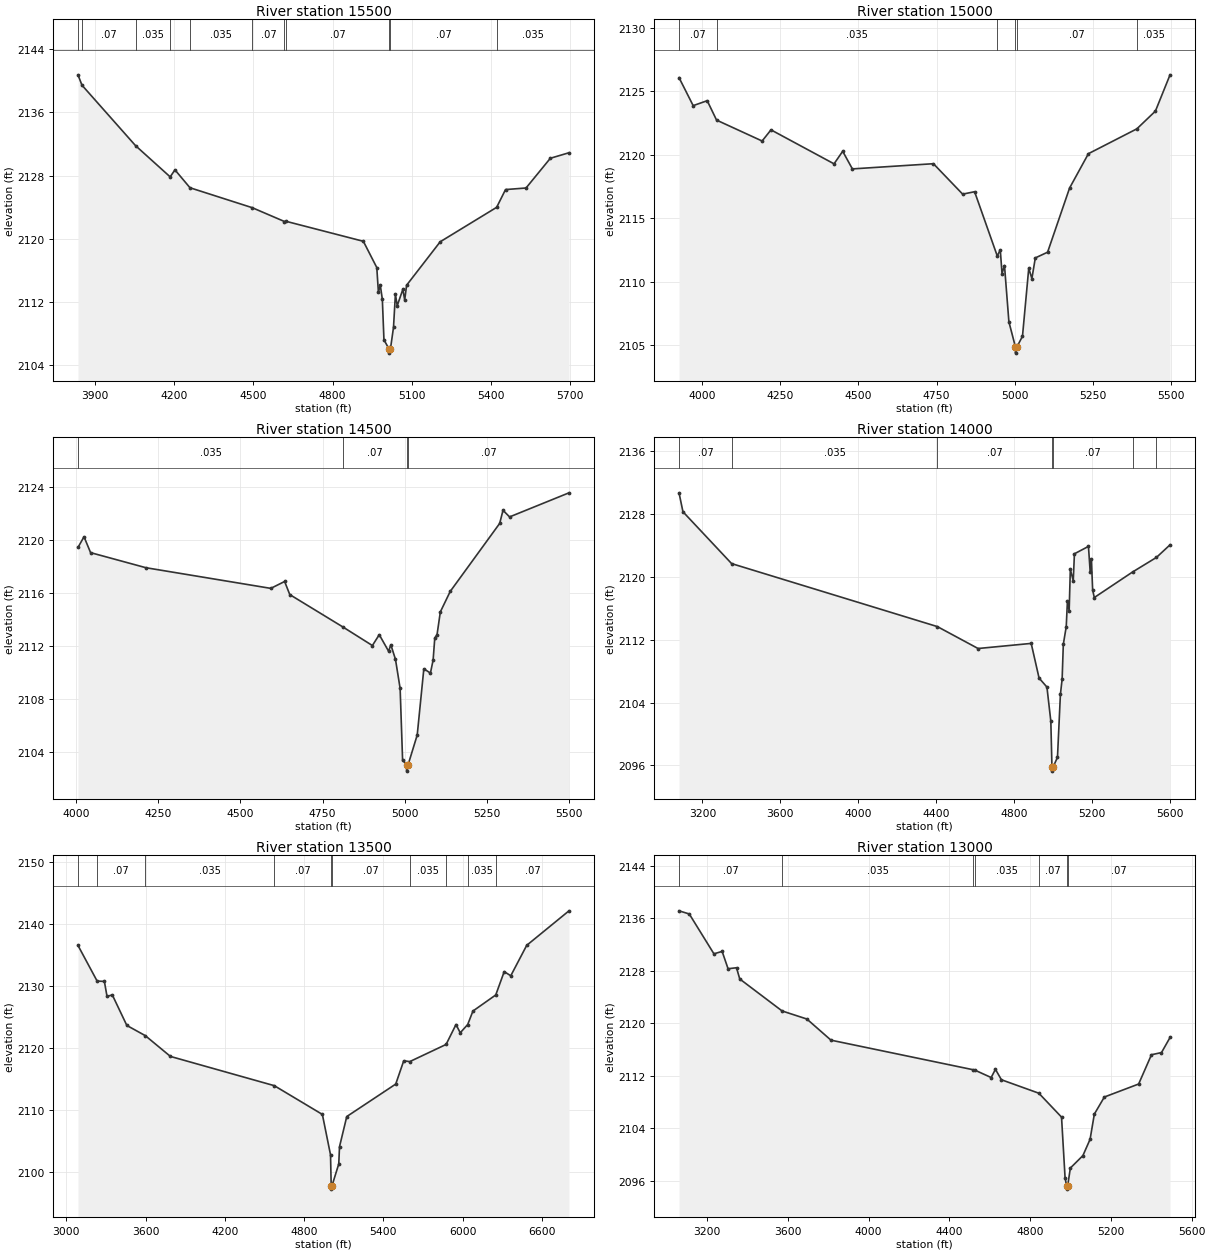
Type RM Length L Ch R = 1,15500,500,500,500
BEGIN DESCRIPTION:
Bull Creek Trib097 31.0
END DESCRIPTION:
XS GIS Cut Line= 3
      1343555.01      6927838.02      1342904.56      6926871.75
      1342405.00      6926388.00
#Sta/Elev= 30
  3835.2 2140.77  3850.3 2139.46  4053.3 2131.79  4184.5 2127.83  4202.6 2128.72
  4259.6 2126.45  4495.6 2123.92  4617.5 2122.17  4625.2 2122.18  4916.4 2119.66
  4967.3 2116.33  4973.4 2113.17  4980.4 2114.13  4988.3 2112.31  4994.4 2107.18
  5013.9 2105.98  5014.3 2105.48  5018.9 2105.98  5030.6 2108.75  5037.8 2112.95
  5044.7 2111.49  5066.1 2113.58  5073.0 2112.21  5080.2 2114.09  5207.5 2119.60
  5421.4 2123.97  5455.0 2126.22  5532.7 2126.42  5624.8 2130.19  5695.4 2130.89
#Mann=11,-1,0
  3835.2   0.035       0  3850.3    0.07       0  4053.3   0.035       0
  4184.5    0.07       0  4259.6   0.035       0  4495.6    0.07       0
  4617.5   0.035       0  4625.2    0.07       0  5013.9    0.07       0
  5018.9    0.07       0  5421.4   0.035       0
Bank Sta=5013.9,5018.9
Exp/Cntr=0.3,0.1

Type RM Length L Ch R = 1,15000,500,500,500
BEGIN DESCRIPTION:
Bull Creek Trib097 30.0
END DESCRIPTION:
XS GIS Cut Line= 3
      1343604.99      6927387.99      1343100.04      6926439.41
      1342605.00      6926388.00
#Sta/Elev= 30
  3925.4 2126.09  3970.7 2123.88  4015.7 2124.27  4045.6 2122.74  4191.5 2121.09
  4219.9 2121.97  4421.8 2119.29  4449.5 2120.28  4480.5 2118.89  4740.0 2119.30
  4833.6 2116.90  4871.9 2117.09  4944.5 2112.02  4954.1 2112.51  4959.7 2110.64
  4967.6 2111.27  4981.7 2106.83  5002.5 2104.86  5002.9 2104.36  5007.6 2104.86
  5025.2 2105.69  5045.3 2111.06  5055.3 2110.24  5066.3 2111.87  5105.6 2112.32
  5176.0 2117.38  5236.3 2120.09  5391.5 2122.05  5450.9 2123.45  5497.7 2126.31
#Mann=6,-1,0
  3925.4    0.07       0  4045.6   0.035       0  4944.5    0.07       0
  5002.5    0.07       0  5007.6    0.07       0  5391.5   0.035       0
Bank Sta=5002.5,5007.6
Exp/Cntr=0.3,0.1

Type RM Length L Ch R = 1,14500,500,500,500
BEGIN DESCRIPTION:
Bull Creek Trib097 29.0
END DESCRIPTION:
XS GIS Cut Line= 4
      1343527.87      6926956.11      1343376.82      6926143.56
      1343252.79      6926030.63      1342755.02      6925988.00
#Sta/Elev= 30
  4005.8 2119.44  4024.2 2120.25  4044.2 2119.05  4212.7 2117.91  4592.4 2116.35
  4634.5 2116.87  4650.2 2115.88  4812.0 2113.43  4901.5 2112.03  4922.4 2112.85
  4950.8 2111.60  4957.6 2112.09  4971.8 2110.98  4985.9 2108.79  4993.4 2103.37
  5005.3 2103.04  5005.7 2102.54  5010.4 2103.04  5037.9 2105.27  5058.0 2110.27
  5078.1 2109.95  5086.3 2110.94  5091.3 2112.60  5098.2 2112.85  5108.2 2114.57
  5138.3 2116.12  5288.8 2121.26  5298.9 2122.25  5318.9 2121.75  5499.6 2123.57
#Mann=4,-1,0
  4005.8   0.035       0  4812.0    0.07       0  5005.3    0.07       0
  5010.4    0.07       0
Bank Sta=5005.3,5010.4
Exp/Cntr=0.3,0.1

Type RM Length L Ch R = 1,14000,500,500,500
BEGIN DESCRIPTION:
Bull Creek Trib097 28.0
END DESCRIPTION:
XS GIS Cut Line= 3
      1343654.99      6927487.96      1343389.05      6925586.47
      1343055.03      6925088.04
#Sta/Elev= 30
  3080.0 2130.70  3100.2 2128.29  3349.9 2121.69  4405.9 2113.67  4614.8 2110.88
  4887.4 2111.53  4927.8 2107.12  4968.2 2105.97  4988.2 2101.62  4994.0 2095.77
  4994.5 2095.27  4999.4 2095.77  5022.3 2097.02  5037.3 2105.03  5046.2 2106.98
  5052.3 2111.42  5067.3 2113.66  5073.3 2116.88  5082.3 2115.70  5088.3 2120.95
  5103.3 2119.51  5109.3 2122.94  5181.3 2123.88  5190.3 2120.58  5196.3 2122.31
  5202.8 2118.33  5211.3 2117.37  5407.6 2120.62  5530.4 2122.48  5600.0 2124.08
#Mann=7,-1,0
  3080.0    0.07       0  3349.9   0.035       0  4405.9    0.07       0
  4994.0    0.07       0  4999.4    0.07       0  5407.6   0.035       0
  5530.4    0.07       0
Bank Sta=4994,4999.4
Exp/Cntr=0.3,0.1

Type RM Length L Ch R = 1,13500,500,500,500
BEGIN DESCRIPTION:
Bull Creek Trib097 27.0
END DESCRIPTION:
XS GIS Cut Line= 3
      1343655.00      6927687.95      1343694.22      6925776.35
      1343055.00      6924088.01
#Sta/Elev= 30
  3088.0 2136.50  3233.0 2130.76  3288.0 2130.70  3308.0 2128.29  3348.0 2128.53
  3458.0 2123.61  3597.7 2121.97  3788.1 2118.62  4574.5 2113.91  4938.3 2109.28
  5000.0 2102.77  5005.1 2097.75  5005.5 2097.25  5010.5 2097.75  5062.4 2101.31
  5068.1 2104.09  5123.0 2108.94  5493.7 2114.17  5554.3 2117.92  5600.1 2117.79
  5874.9 2120.55  5949.9 2123.76  5982.0 2122.43  6038.6 2123.76  6078.2 2125.93
  6250.9 2128.52  6314.9 2132.28  6364.6 2131.61  6485.2 2136.51  6805.3 2142.07
#Mann=10,-1,0
  3088.0   0.035       0  3233.0    0.07       0  3597.7   0.035       0
  4574.5    0.07       0  5005.1    0.07       0  5010.5    0.07       0
  5600.1   0.035       0  5874.9    0.07       0  6038.6   0.035       0
  6250.9    0.07       0
Bank Sta=5005.1,5010.5
Exp/Cntr=0.3,0.1

Type RM Length L Ch R = 1,13000,283,283,283
BEGIN DESCRIPTION:
Bull Creek Trib097 26.0
END DESCRIPTION:
XS GIS Cut Line= 3
      1343805.01      6927687.97      1344158.52      6925781.47
      1343805.00      6925438.00
#Sta/Elev= 30
  3061.0 2137.13  3111.8 2136.65  3233.9 2130.58  3274.5 2130.95  3303.9 2128.31
  3345.7 2128.46  3361.8 2126.75  3571.4 2121.88  3694.2 2120.65  3813.6 2117.43
  4518.5 2112.92  4524.5 2112.89  4606.9 2111.74  4628.2 2112.99  4657.7 2111.40
  4843.1 2109.35  4955.5 2105.71  4973.0 2096.49  4980.4 2095.24  4980.9 2094.74
  4985.9 2095.24  4999.2 2097.95  5061.4 2099.85  5096.9 2102.33  5118.0 2106.17
  5167.6 2108.77  5337.4 2110.75  5400.9 2115.21  5450.6 2115.54  5492.9 2117.84
#Mann=7,-1,0
  3061.0    0.07       0  3571.4   0.035       0  4518.5    0.07       0
  4524.5   0.035       0  4843.1    0.07       0  4980.4    0.07       0
  4985.9    0.07       0
Bank Sta=4980.4,4985.9
Exp/Cntr=0.3,0.1

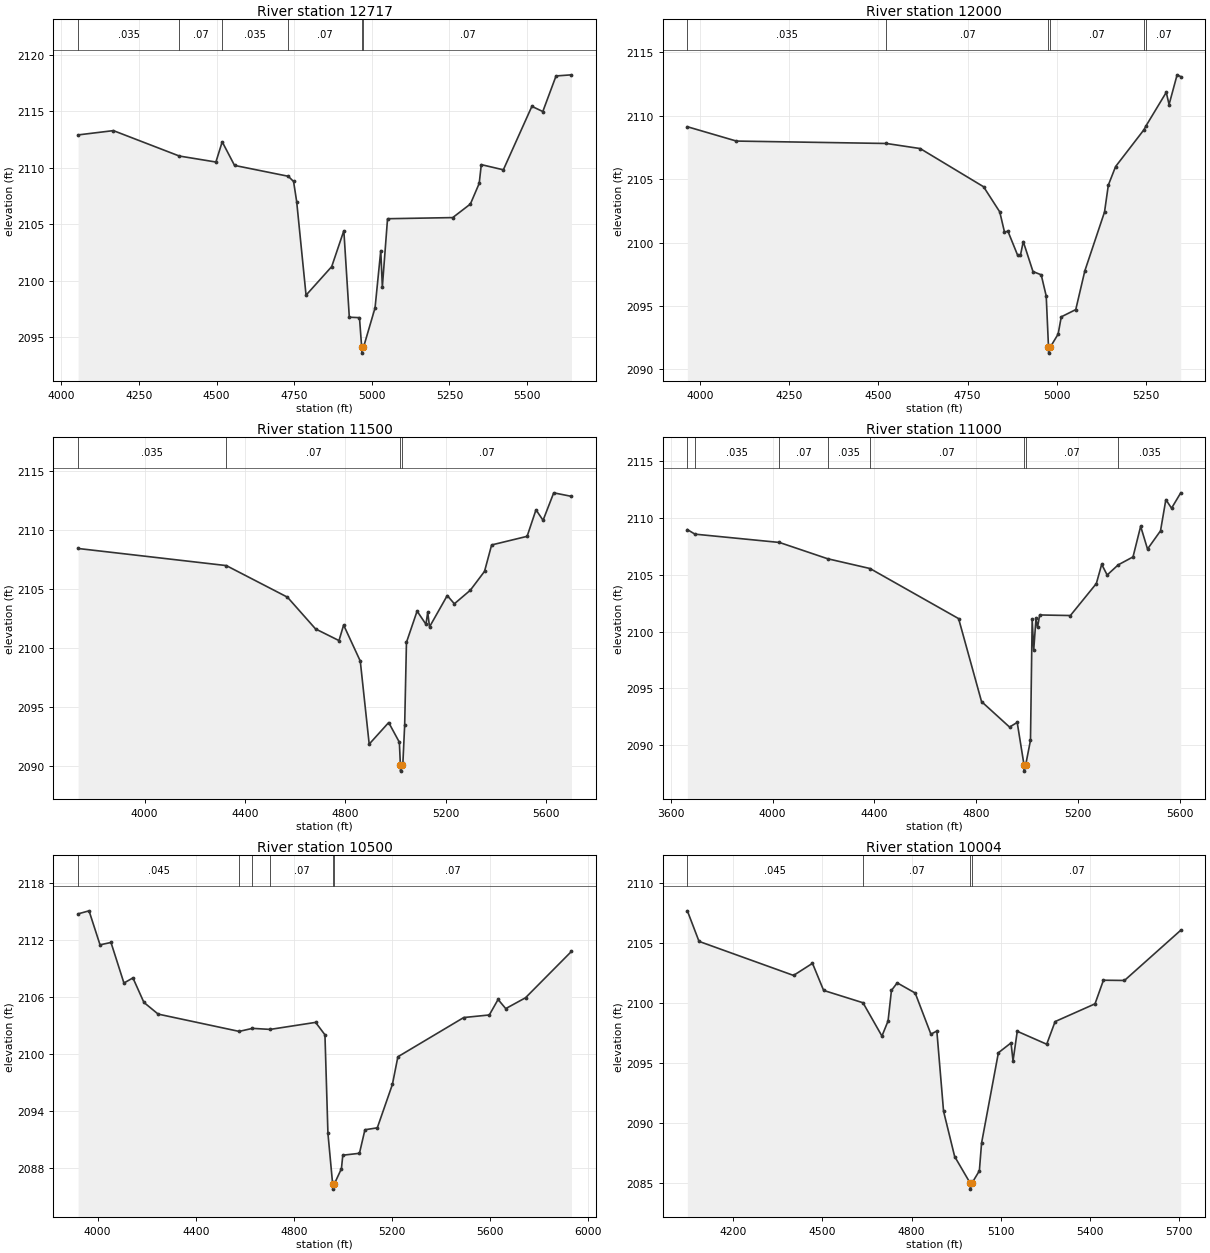
Type RM Length L Ch R = 1,12717,717,717,717
BEGIN DESCRIPTION:
Bull Creek Trib097 25.0
END DESCRIPTION:
XS GIS Cut Line= 4
      1344548.69      6926471.67      1344527.86      6925659.19
      1344210.15      6925627.94      1343905.00      6925288.00
#Sta/Elev= 30
  4054.2 2112.90  4167.9 2113.28  4380.2 2111.03  4498.0 2110.50  4518.3 2112.29
  4558.0 2110.20  4730.9 2109.24  4748.1 2108.78  4758.1 2107.00  4788.3 2098.71
  4870.9 2101.24  4910.0 2104.42  4927.6 2096.76  4960.3 2096.72  4967.5 2094.08
  4968.0 2093.58  4973.1 2094.08  5010.5 2097.59  5028.9 2102.66  5034.0 2099.45
  5050.7 2105.48  5260.6 2105.58  5317.5 2106.78  5345.9 2108.61  5352.6 2110.27
  5423.6 2109.81  5515.5 2115.43  5550.7 2114.97  5593.3 2118.12  5643.0 2118.22
#Mann=6,-1,0
  4054.2   0.035       0  4380.2    0.07       0  4518.3   0.035       0
  4730.9    0.07       0  4967.5    0.07       0  4973.1    0.07       0
Bank Sta=4967.5,4973.1
Exp/Cntr=0.3,0.1

Type RM Length L Ch R = 1,12000,500,500,500
BEGIN DESCRIPTION:
Bull Creek Trib097 24.0
END DESCRIPTION:
XS GIS Cut Line= 4
      1345022.67      6926086.31      1344746.61      6925393.56
      1344497.37      6925246.15      1344154.97      6925188.00
#Sta/Elev= 30
  3964.7 2109.13  4102.2 2108.00  4522.5 2107.81  4617.2 2107.41  4794.8 2104.40
  4840.1 2102.42  4853.3 2100.84  4863.1 2100.89  4890.4 2098.99  4898.2 2099.02
  4906.0 2100.08  4933.2 2097.72  4956.3 2097.46  4970.3 2095.79  4976.7 2091.79
  4977.2 2091.29  4982.3 2091.79  5003.7 2092.79  5012.5 2094.15  5053.1 2094.72
  5078.5 2097.77  5133.7 2102.41  5144.4 2104.53  5164.7 2105.99  5244.1 2108.89
  5249.8 2109.19  5306.7 2111.84  5314.6 2110.88  5337.1 2113.22  5347.3 2113.08
#Mann=6,-1,0
  3964.7   0.035       0  4522.5    0.07       0  4976.7    0.07       0
  4982.3    0.07       0  5244.1   0.035       0  5249.8    0.07       0
Bank Sta=4976.7,4982.3
Exp/Cntr=0.3,0.1

Type RM Length L Ch R = 1,11500,500,500,500
BEGIN DESCRIPTION:
Bull Creek Trib097 23.0
END DESCRIPTION:
XS GIS Cut Line= 4
      1345069.53      6926081.07      1344875.87      6925014.08
      1344750.61      6924884.14      1344254.98      6924387.98
#Sta/Elev= 30
  3735.1 2108.46  4325.8 2107.01  4569.5 2104.33  4681.4 2101.64  4774.9 2100.65
  4793.3 2101.97  4859.7 2098.91  4895.2 2091.87  4972.9 2093.70  5015.4 2092.03
  5019.6 2090.08  5020.1 2089.58  5025.4 2090.08  5029.5 2090.27  5036.6 2093.49
  5043.7 2100.50  5086.1 2103.15  5121.4 2102.03  5128.5 2103.06  5135.6 2101.81
  5206.3 2104.47  5234.6 2103.77  5298.2 2104.92  5354.8 2106.52  5383.1 2108.76
  5524.5 2109.49  5559.9 2111.74  5588.1 2110.85  5630.6 2113.18  5701.3 2112.88
#Mann=4,-1,0
  3735.1   0.035       0  4325.8    0.07       0  5019.6    0.07       0
  5025.4    0.07       0
Bank Sta=5019.6,5025.4
Exp/Cntr=0.3,0.1

Type RM Length L Ch R = 1,11000,500,500,500
BEGIN DESCRIPTION:
Bull Creek Trib097 22.0
END DESCRIPTION:
XS GIS Cut Line= 3
      1345142.44      6926122.73      1345191.22      6924788.72
      1344855.01      6924288.02
#Sta/Elev= 30
  3665.1 2108.96  3694.9 2108.56  4026.7 2107.83  4215.9 2106.40  4382.5 2105.54
  4730.5 2101.14  4820.6 2093.85  4930.7 2091.61  4960.7 2092.02  4987.8 2088.24
  4988.3 2087.74  4993.6 2088.24  5012.9 2090.45  5019.5 2101.08  5025.6 2098.38
  5034.5 2101.16  5040.5 2100.37  5049.0 2101.46  5169.6 2101.41  5271.6 2104.22
  5292.6 2105.91  5314.0 2104.97  5357.3 2105.86  5415.6 2106.56  5445.6 2109.25
  5472.6 2107.25  5523.6 2108.85  5544.6 2111.59  5567.0 2110.84  5603.1 2112.19
#Mann=8,-1,0
  3665.1    0.07       0  3694.9   0.035       0  4026.7    0.07       0
  4215.9   0.035       0  4382.5    0.07       0  4987.8    0.07       0
  4993.6    0.07       0  5357.3   0.035       0
Bank Sta=4987.8,4993.6
Exp/Cntr=0.3,0.1

Type RM Length L Ch R = 1,10500,496,496,496
BEGIN DESCRIPTION:
Bull Creek Trib097 21.0
END DESCRIPTION:
XS GIS Cut Line= 3
      1345954.98      6925937.97      1345470.65      6924972.88
      1345055.01      6924138.03
#Sta/Elev= 30
  3920.2 2114.72  3964.9 2115.04  4009.7 2111.46  4054.4 2111.71  4107.2 2107.44
  4143.9 2107.98  4188.7 2105.40  4246.8 2104.17  4577.2 2102.35  4631.5 2102.67
  4703.6 2102.56  4889.0 2103.30  4927.1 2101.99  4939.3 2091.61  4958.6 2086.25
  4959.1 2085.75  4964.5 2086.25  4994.3 2087.90  4999.9 2089.32  5067.8 2089.52
  5090.2 2092.00  5140.6 2092.20  5202.2 2096.77  5224.6 2099.68  5493.2 2103.81
  5597.5 2104.08  5633.2 2105.71  5664.5 2104.75  5745.1 2105.89  5932.6 2110.77
#Mann=6,-1,0
  3920.2   0.045       0  4577.2    0.07       0  4631.5   0.045       0
  4703.6    0.07       0  4958.6    0.07       0  4964.5    0.07       0
Bank Sta=4958.6,4964.5
Exp/Cntr=0.3,0.1

Type RM Length L Ch R = 1,10004,504,504,504
BEGIN DESCRIPTION:
Bull Creek Trib097 20.0
END DESCRIPTION:
XS GIS Cut Line= 3
      1346054.88      6925636.28      1345839.57      6924711.14
      1345355.14      6924189.71
#Sta/Elev= 30
  4045.0 2107.68  4084.3 2105.13  4402.6 2102.29  4466.4 2103.30  4503.9 2101.04
  4636.5 2100.01  4700.3 2097.23  4720.9 2098.49  4732.3 2101.04  4751.7 2101.67
  4812.3 2100.82  4865.2 2097.39  4885.2 2097.65  4907.8 2090.96  4945.2 2087.18
  4997.5 2084.96  4998.0 2084.46  5003.4 2084.96  5028.4 2085.99  5035.8 2088.30
  5092.5 2095.84  5135.0 2096.66  5141.8 2095.16  5156.0 2097.63  5255.2 2096.55
  5283.5 2098.44  5417.9 2099.92  5446.2 2101.89  5517.1 2101.87  5706.6 2106.06
#Mann=4,-1,0
  4045.0   0.045       0  4636.5    0.07       0  4997.5    0.07       0
  5003.4    0.07       0
Bank Sta=4997.5,5003.4
Exp/Cntr=0.3,0.1

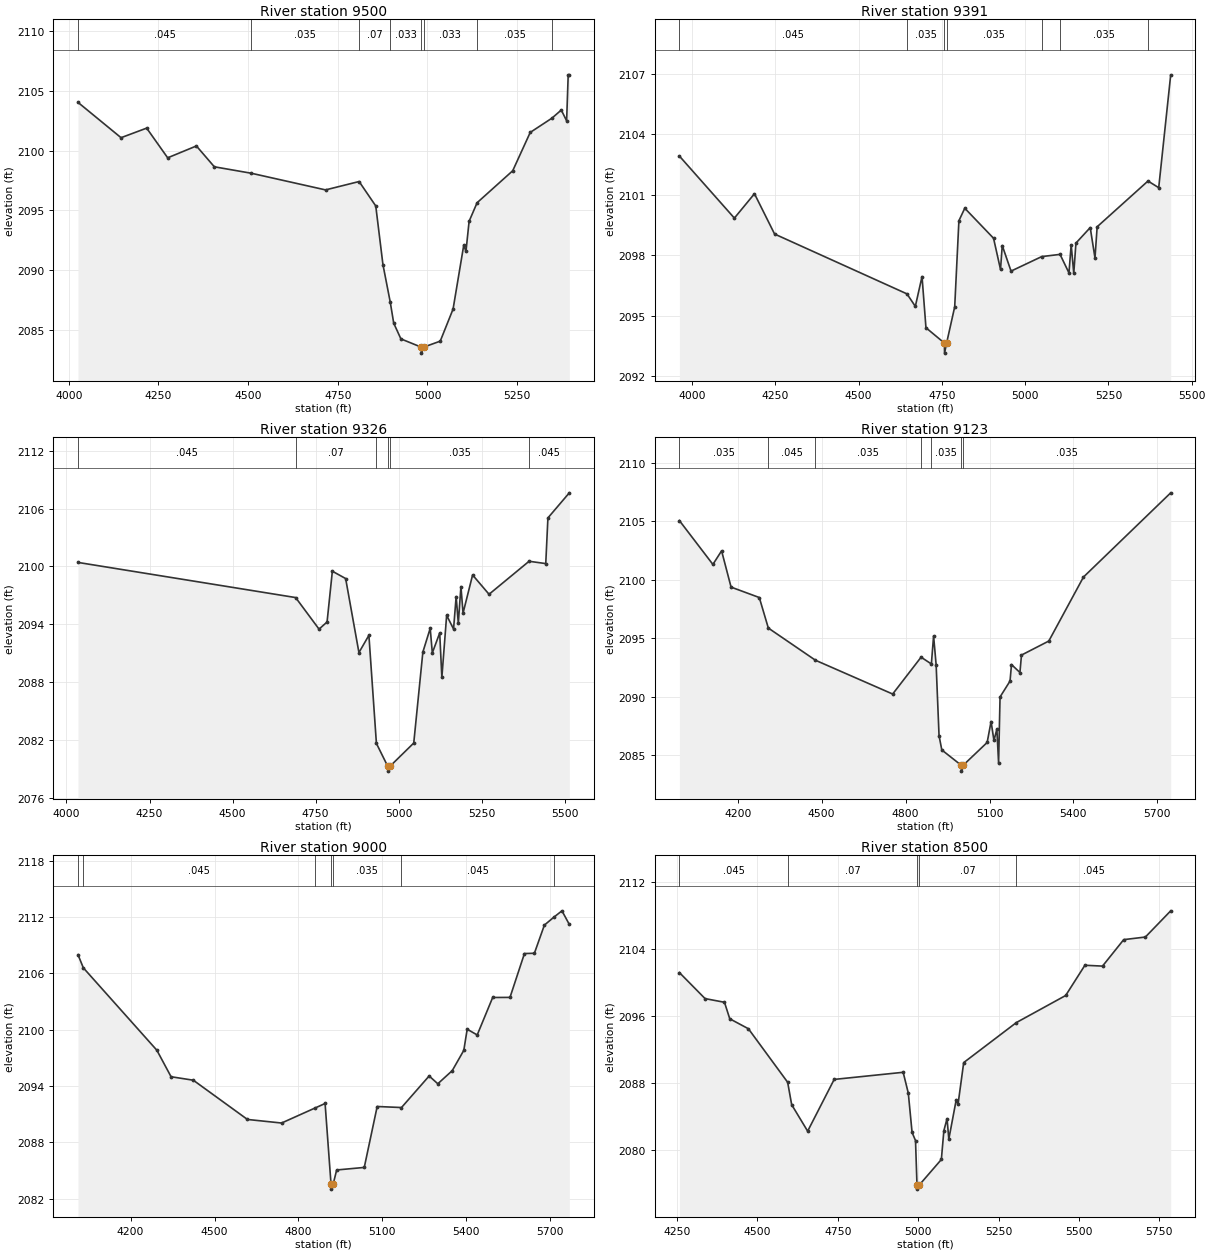
Type RM Length L Ch R = 1,9500,109,109,109
BEGIN DESCRIPTION:
Bull Creek Trib097 19.0
END DESCRIPTION:
XS GIS Cut Line= 3
      1346255.00      6925438.04      1346229.07      6924463.88
      1346004.99      6924137.98
#Sta/Elev= 30
  4025.5 2104.02  4145.6 2101.07  4217.0 2101.87  4275.6 2099.39  4355.7 2100.38
  4405.7 2098.64  4509.0 2098.10  4715.8 2096.71  4809.4 2097.41  4855.8 2095.37
  4875.8 2090.48  4896.2 2087.34  4905.9 2085.58  4925.9 2084.27  4982.5 2083.58
  4983.0 2083.08  4989.2 2083.58  5035.6 2084.08  5071.4 2086.76  5101.2 2092.10
  5107.3 2091.57  5116.1 2094.09  5138.4 2095.64  5237.7 2098.31  5286.5 2101.51
  5347.0 2102.70  5373.1 2103.38  5388.0 2102.48  5392.4 2106.32  5395.5 2106.32
#Mann=8,-1,0
  4025.5   0.045       0  4509.0   0.035       0  4809.4    0.07       0
  4896.2   0.033       0  4982.5   0.033       0  4989.2   0.033       0
  5138.4   0.035       0  5347.0   0.045       0
Bank Sta=4982.5,4989.2
Exp/Cntr=0.3,0.1

Type RM Length L Ch R = 1,9391,65,65,65
BEGIN DESCRIPTION:
Bull Creek Trib097 18.7
END DESCRIPTION:
XS GIS Cut Line= 5
      1346289.96      6925462.11      1346383.28      6924607.91
      1346328.60      6924436.04      1346259.99      6924342.95
      1346014.83      6924137.89
#Sta/Elev= 30
  3962.2 2102.93  4127.3 2099.85  4187.6 2101.06  4248.0 2099.06  4645.4 2096.09
  4670.5 2095.47  4690.6 2096.95  4702.4 2094.41  4757.7 2093.65  4758.2 2093.15
  4764.4 2093.65  4788.7 2095.45  4801.3 2099.72  4818.9 2100.34  4905.3 2098.85
  4926.2 2097.30  4931.4 2098.49  4957.8 2097.22  5049.8 2097.94  5104.9 2098.05
  5131.7 2097.13  5138.3 2098.53  5146.1 2097.11  5152.6 2098.61  5195.5 2099.38
  5209.8 2097.87  5216.3 2099.42  5368.9 2101.69  5401.1 2101.36  5437.1 2106.96
#Mann=7,-1,0
  3962.2   0.045       0  4645.4   0.035       0  4757.7   0.035       0
  4764.4   0.035       0  5049.8   0.033       0  5104.9   0.035       0
  5368.9   0.045       0
Bank Sta=4757.7,4764.4
Exp/Cntr=0.3,0.1

Type RM Length L Ch R = 1,9326,203,203,203
BEGIN DESCRIPTION:
Bull Creek Trib097 18.6
END DESCRIPTION:
XS GIS Cut Line= 3
      1346419.93      6925403.28      1346394.00      6924429.16
      1346005.23      6924107.90
#Sta/Elev= 30
  4034.7 2100.42  4689.8 2096.78  4760.2 2093.51  4784.4 2094.25  4800.3 2099.51
  4840.3 2098.75  4880.3 2091.08  4910.3 2092.87  4932.9 2081.67  4967.0 2079.30
  4967.5 2078.80  4973.7 2079.30  5045.3 2081.71  5072.7 2091.13  5094.8 2093.59
  5101.2 2091.05  5123.4 2093.11  5129.9 2088.51  5144.3 2094.94  5165.1 2093.52
  5172.9 2096.88  5179.4 2094.13  5187.3 2097.92  5193.7 2095.17  5222.4 2099.12
  5271.9 2097.12  5392.4 2100.54  5442.6 2100.30  5449.1 2105.03  5513.5 2107.63
#Mann=6,-1,0
  4034.7   0.045       0  4689.8    0.07       0  4932.9   0.035       0
  4967.0   0.035       0  4973.7   0.035       0  5392.4   0.045       0
Bank Sta=4967,4973.7
Exp/Cntr=0.3,0.1

Type RM Length L Ch R = 1,9123,123,123,123
BEGIN DESCRIPTION:
Bull Creek Trib097 18.5
END DESCRIPTION:
XS GIS Cut Line= 3
      1347530.63      6924600.97      1346577.31      6924341.09
      1345832.72      6924151.32
#Sta/Elev= 30
  3991.3 2105.08  4111.1 2101.33  4142.2 2102.49  4176.1 2099.39  4277.0 2098.50
  4309.3 2095.89  4477.7 2093.14  4753.8 2090.25  4855.4 2093.40  4892.2 2092.82
  4900.1 2095.22  4909.2 2092.75  4919.6 2086.69  4929.5 2085.47  4999.1 2084.16
  4999.6 2083.66  5005.8 2084.16  5091.6 2086.11  5105.6 2087.90  5115.9 2086.28
  5126.3 2087.25  5132.5 2084.35  5137.7 2090.00  5173.4 2091.36  5178.6 2092.77
  5208.8 2092.09  5214.3 2093.58  5312.0 2094.78  5435.9 2100.25  5747.8 2107.45
#Mann=7,-1,0
  3991.3   0.035       0  4309.3   0.045       0  4477.7   0.035       0
  4855.4    0.07       0  4892.2   0.035       0  4999.1   0.035       0
  5005.8   0.035       0
Bank Sta=4999.1,5005.8
Exp/Cntr=0.3,0.1

Type RM Length L Ch R = 1,9000,500,500,500
BEGIN DESCRIPTION:
Bull Creek Trib097 18.0
END DESCRIPTION:
XS GIS Cut Line= 3
      1347567.08      6924491.59      1346613.77      6924231.71
      1345869.56      6924042.04
#Sta/Elev= 30
  4011.9 2107.98  4031.0 2106.58  4293.9 2097.80  4344.6 2094.98  4424.1 2094.61
  4617.6 2090.43  4739.6 2090.05  4860.0 2091.66  4895.1 2092.13  4916.4 2083.51
  4916.9 2083.01  4923.7 2083.51  4936.5 2085.05  5035.1 2085.32  5081.3 2091.81
  5168.2 2091.70  5267.0 2095.06  5298.0 2094.23  5349.6 2095.63  5390.9 2097.79
  5403.0 2100.04  5438.8 2099.43  5494.1 2103.42  5556.0 2103.43  5607.6 2108.10
  5643.2 2108.13  5678.9 2111.13  5712.7 2111.97  5741.7 2112.65  5768.0 2111.20
#Mann=7,-1,0
  4011.9   0.035       0  4031.0   0.045       0  4860.0   0.035       0
  4916.4   0.035       0  4923.7   0.035       0  5168.2   0.045       0
  5712.7   0.035       0
Bank Sta=4916.4,4923.7
Exp/Cntr=0.3,0.1

Type RM Length L Ch R = 1,8500,500,500,500
BEGIN DESCRIPTION:
Bull Creek Trib097 17.0
END DESCRIPTION:
XS GIS Cut Line= 3
      1347454.97      6924137.99      1346797.92      6923791.75
      1346081.66      6923469.04
#Sta/Elev= 30
  4257.3 2101.22  4337.2 2098.11  4397.6 2097.67  4414.0 2095.70  4472.0 2094.51
  4594.1 2088.12  4606.6 2085.44  4656.3 2082.28  4738.8 2088.46  4953.4 2089.31
  4969.4 2086.82  4981.1 2082.13  4991.8 2081.16  4996.4 2075.86  4996.9 2075.36
  5003.7 2075.86  5072.2 2078.90  5080.0 2082.34  5089.9 2083.78  5095.4 2081.33
  5118.5 2086.04  5124.0 2085.47  5141.7 2090.47  5305.6 2095.25  5458.9 2098.48
  5518.7 2102.09  5573.5 2101.99  5639.4 2105.15  5706.8 2105.46  5785.6 2108.59
#Mann=5,-1,0
  4257.3   0.045       0  4594.1    0.07       0  4996.4    0.07       0
  5003.7    0.07       0  5305.6   0.045       0
Bank Sta=4996.4,5003.7
Exp/Cntr=0.3,0.1