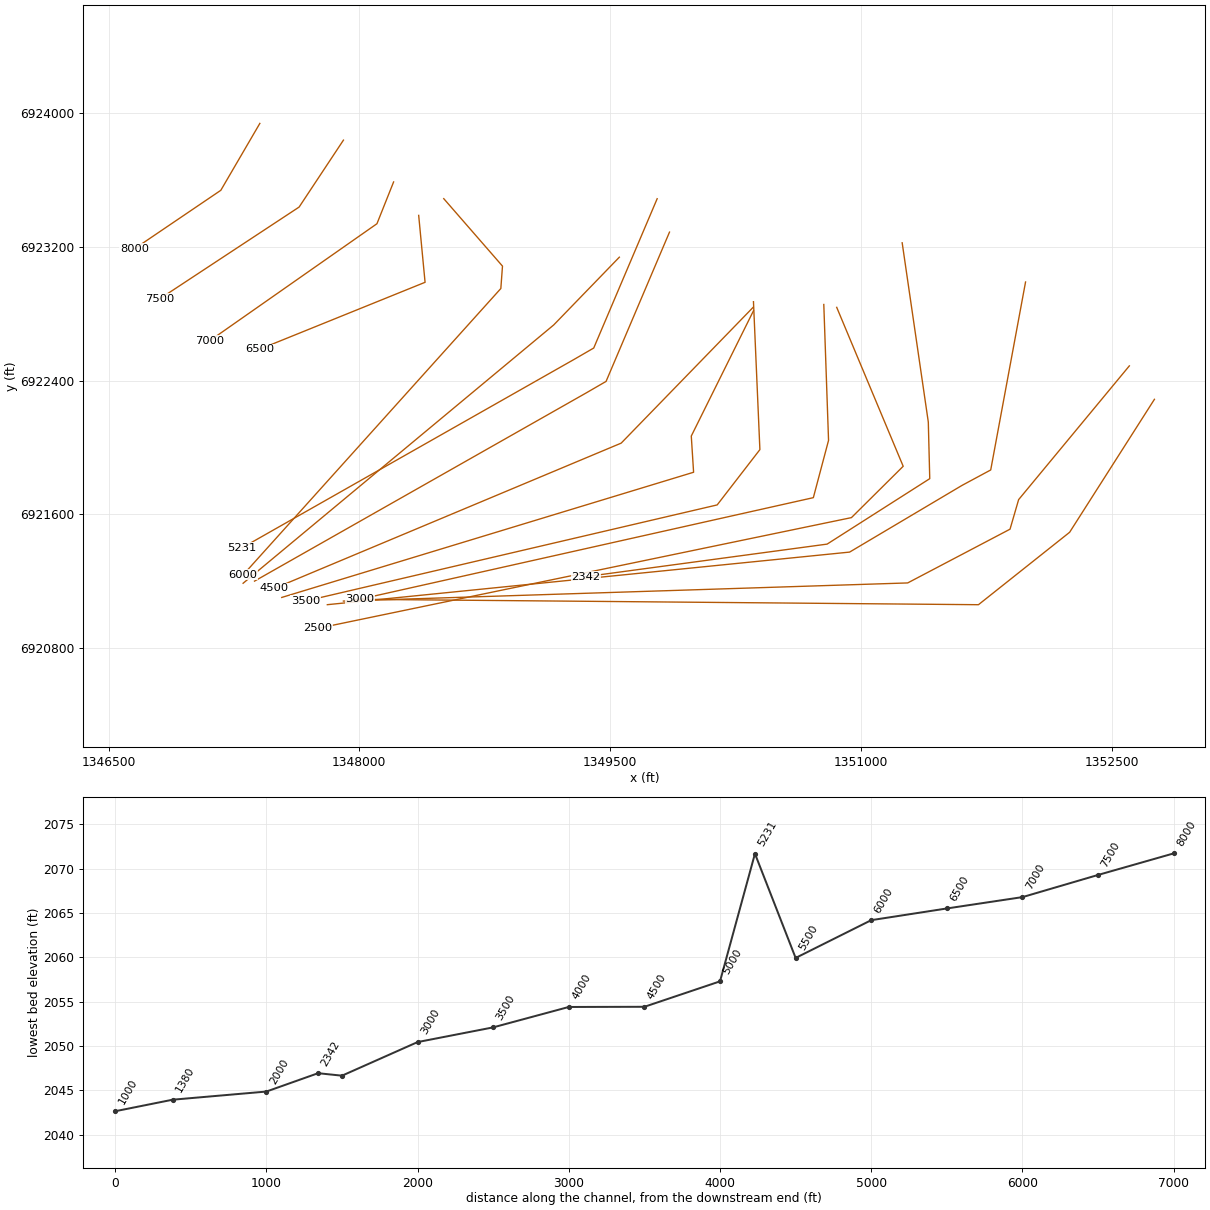
HEC-RAS study Bull Creek Trib097.prj: Bull Creek Trib097 Base Level Engineering

--- Bull Creek Trib097.g01 (geometry) --- (continued)

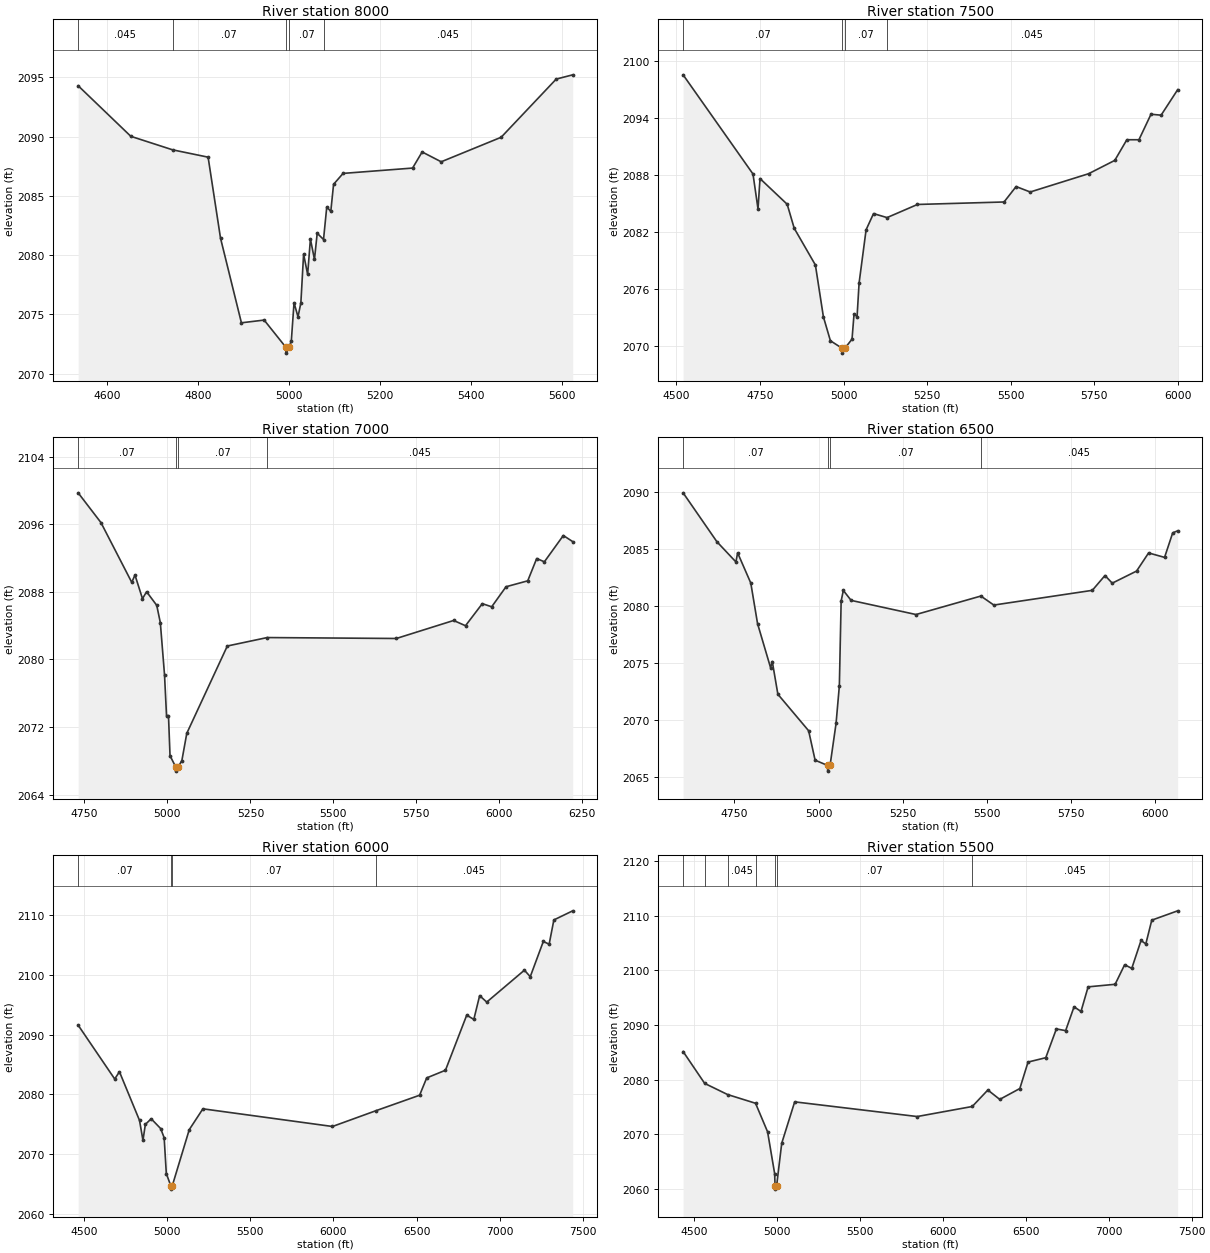
Type RM Length L Ch R = 1,8000,500,500,500
BEGIN DESCRIPTION:
Bull Creek Trib097 16.0
END DESCRIPTION:
XS GIS Cut Line= 3
      1347405.01      6923938.02      1347171.68      6923537.99
      1346654.97      6923187.98
#Sta/Elev= 30
  4536.9 2094.29  4652.7 2090.02  4744.5 2088.88  4822.6 2088.26  4849.9 2081.42
  4895.8 2074.28  4945.8 2074.51  4993.4 2072.22  4993.9 2071.72  5000.8 2072.22
  5005.5 2072.74  5011.5 2075.98  5020.2 2074.78  5026.5 2075.96  5032.5 2080.08
  5041.4 2078.36  5047.5 2081.35  5056.4 2079.63  5062.4 2081.84  5076.3 2081.31
  5083.4 2084.05  5092.3 2083.69  5098.4 2085.97  5119.3 2086.89  5272.1 2087.34
  5293.1 2088.70  5335.0 2087.87  5466.8 2089.94  5587.8 2094.85  5624.1 2095.21
#Mann=5,-1,0
  4536.9   0.045       0  4744.5    0.07       0  4993.4    0.07       0
  5000.8    0.07       0  5076.3   0.045       0
Bank Sta=4993.4,5000.8
Exp/Cntr=0.3,0.1

Type RM Length L Ch R = 1,7500,500,500,500
BEGIN DESCRIPTION:
Bull Creek Trib097 15.0
END DESCRIPTION:
XS GIS Cut Line= 3
      1347905.00      6923838.00      1347639.94      6923437.82
      1346805.02      6922888.01
#Sta/Elev= 30
  4520.0 2098.53  4729.1 2088.11  4744.1 2084.44  4750.1 2087.63  4831.4 2084.93
  4852.4 2082.41  4915.8 2078.55  4939.7 2073.11  4960.7 2070.59  4996.2 2069.79
  4996.7 2069.29  5003.7 2069.79  5025.4 2070.76  5031.4 2073.39  5040.5 2073.13
  5046.5 2076.65  5067.5 2082.25  5089.7 2083.95  5130.2 2083.53  5221.2 2084.91
  5480.2 2085.17  5516.3 2086.79  5558.5 2086.22  5733.2 2088.14  5811.5 2089.54
  5847.6 2091.71  5883.8 2091.71  5919.9 2094.39  5950.1 2094.29  5999.7 2096.97
#Mann=4,-1,0
  4520.0    0.07       0  4996.2    0.07       0  5003.7    0.07       0
  5130.2   0.045       0
Bank Sta=4996.2,5003.7
Exp/Cntr=0.3,0.1

Type RM Length L Ch R = 1,7000,500,500,500
BEGIN DESCRIPTION:
Bull Creek Trib097 14.0
END DESCRIPTION:
XS GIS Cut Line= 3
      1348205.00      6923588.00      1348105.45      6923338.20
      1347105.03      6922638.02
#Sta/Elev= 30
  4731.1 2099.71  4799.8 2096.19  4892.6 2089.12  4902.3 2089.99  4924.9 2087.19
  4937.3 2088.01  4967.9 2086.40  4978.7 2084.35  4991.3 2078.20  4997.4 2073.33
  5003.3 2073.33  5007.9 2068.61  5025.0 2067.29  5025.5 2066.79  5032.5 2067.29
  5043.6 2068.04  5058.4 2071.26  5180.5 2081.59  5300.7 2082.59  5689.7 2082.48
  5862.3 2084.61  5898.1 2083.99  5948.7 2086.60  5977.0 2086.23  6020.2 2088.60
  6085.6 2089.30  6112.6 2091.94  6135.7 2091.55  6192.8 2094.66  6221.1 2093.94
#Mann=4,-1,0
  4731.1    0.07       0  5025.0    0.07       0  5032.5    0.07       0
  5300.7   0.045       0
Bank Sta=5025,5032.5
Exp/Cntr=0.3,0.1

Type RM Length L Ch R = 1,6500,500,500,500
BEGIN DESCRIPTION:
Bull Creek Trib097 13.0
END DESCRIPTION:
XS GIS Cut Line= 3
      1348355.00      6923387.99      1348393.18      6922987.80
      1347405.00      6922588.00
#Sta/Elev= 30
  4598.0 2089.91  4698.4 2085.62  4754.8 2083.85  4759.8 2084.65  4798.9 2082.00
  4819.0 2078.44  4857.7 2074.57  4862.7 2075.12  4879.3 2072.25  4970.6 2069.05
  4989.8 2066.47  5026.7 2066.01  5027.2 2065.51  5034.2 2066.01  5052.0 2069.69
  5061.8 2073.00  5067.1 2080.42  5073.6 2081.35  5096.7 2080.48  5289.3 2079.24
  5481.8 2080.86  5520.3 2080.07  5812.6 2081.36  5850.2 2082.66  5871.8 2081.99
  5944.0 2083.05  5979.7 2084.64  6027.1 2084.25  6051.2 2086.40  6066.0 2086.58
#Mann=4,-1,0
  4598.0    0.07       0  5026.7    0.07       0  5034.2    0.07       0
  5481.8   0.045       0
Bank Sta=5026.7,5034.2
Exp/Cntr=0.3,0.1

Type RM Length L Ch R = 1,6000,500,500,500
BEGIN DESCRIPTION:
Bull Creek Trib097 12.0
END DESCRIPTION:
XS GIS Cut Line= 4
      1348505.00      6923488.00      1348856.18      6923084.65
      1348846.31      6922950.66      1347304.97      6921237.96
#Sta/Elev= 30
  4465.2 2091.57  4685.0 2082.58  4713.5 2083.79  4834.1 2075.67  4854.9 2072.33
  4869.2 2074.99  4904.3 2075.94  4961.3 2074.30  4982.3 2072.77  4995.3 2066.79
  5022.9 2064.69  5023.4 2064.19  5030.5 2064.69  5133.2 2074.12  5215.2 2077.60
  5994.1 2074.65  6253.0 2077.26  6518.0 2079.87  6560.6 2082.76  6673.5 2084.04
  6801.3 2093.24  6843.9 2092.53  6879.0 2096.50  6921.6 2095.42  7148.1 2100.75
  7183.2 2099.66  7261.7 2105.54  7296.8 2105.09  7325.2 2109.14  7438.5 2110.66
#Mann=4,-1,0
  4465.2    0.07       0  5022.9    0.07       0  5030.5    0.07       0
  6253.0   0.045       0
Bank Sta=5022.9,5030.5
Exp/Cntr=0.3,0.1

Type RM Length L Ch R = 1,5500,269,269,269
BEGIN DESCRIPTION:
Bull Creek Trib097 11.0
END DESCRIPTION:
XS GIS Cut Line= 3
      1349554.97      6923137.97      1349162.57      6922732.84
      1347305.01      6921188.01
#Sta/Elev= 30
  4436.0 2085.14  4566.0 2079.30  4704.0 2077.26  4872.5 2075.66  4945.1 2070.42
  4987.6 2062.77  4990.2 2060.43  4990.7 2059.93  4999.0 2060.43  5030.2 2068.33
  5108.3 2075.92  5846.5 2073.23  6178.2 2075.07  6272.2 2078.09  6343.9 2076.37
  6464.9 2078.36  6514.4 2083.21  6621.2 2084.01  6685.0 2089.28  6740.9 2088.97
  6791.7 2093.34  6833.4 2092.48  6876.4 2096.99  7039.1 2097.46  7096.4 2101.04
  7139.4 2100.38  7195.3 2105.49  7224.0 2104.85  7259.9 2109.21  7416.0 2110.92
#Mann=7,-1,0
  4436.0   0.045       0  4566.0    0.07       0  4704.0   0.045       0
  4872.5    0.07       0  4990.2    0.07       0  4999.0    0.07       0
  6178.2   0.045       0
Bank Sta=4990.2,4999
Exp/Cntr=0.3,0.1

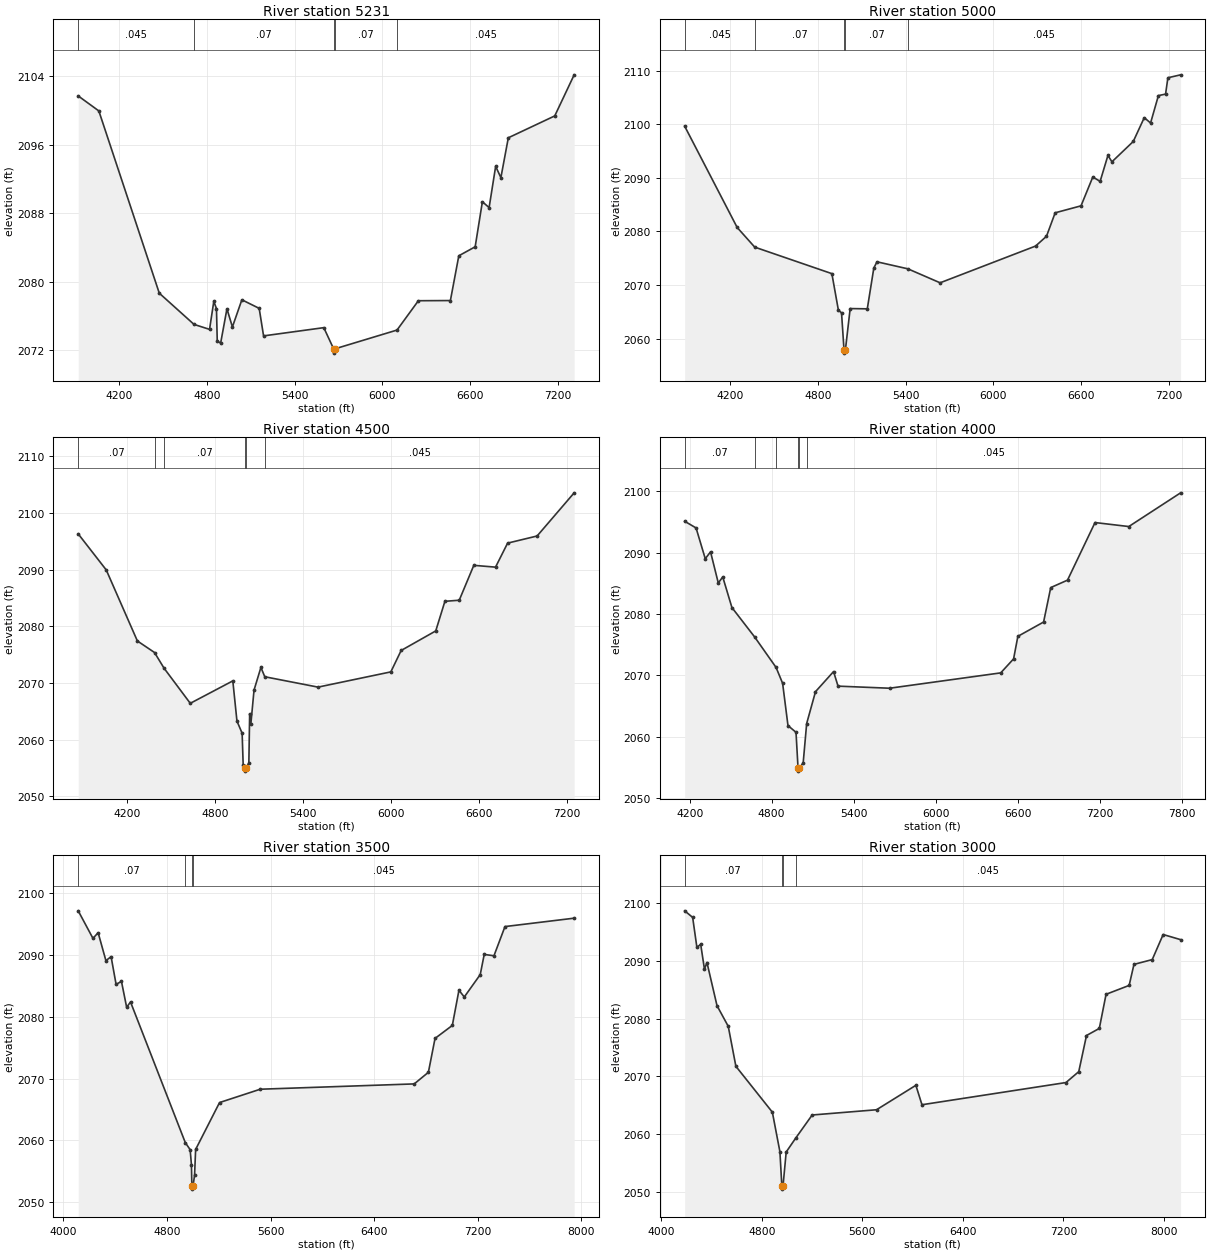
Type RM Length L Ch R = 1,5231,231,231,231
BEGIN DESCRIPTION:
Bull Creek Trib097 10.5
END DESCRIPTION:
XS GIS Cut Line= 4
      1349781.22      6923487.66      1349401.87      6922594.76
      1349281.65      6922525.13      1347299.73      6921400.59
#Sta/Elev= 30
  3922.0 2101.68  4062.9 2099.93  4475.8 2078.68  4713.0 2075.04  4819.1 2074.46
  4848.2 2077.72  4866.4 2076.88  4871.8 2073.09  4895.0 2072.86  4938.0 2076.86
  4975.3 2074.74  5039.9 2077.91  5158.2 2076.91  5188.2 2073.70  5599.6 2074.66
  5666.7 2072.19  5667.2 2071.69  5675.5 2072.19  6099.8 2074.38  6245.7 2077.80
  6464.4 2077.82  6521.9 2083.04  6633.7 2084.09  6682.9 2089.34  6728.9 2088.66
  6773.6 2093.47  6809.3 2092.15  6860.1 2096.80  7177.3 2099.35  7309.8 2104.14
#Mann=5,-1,0
  3922.0   0.045       0  4713.0    0.07       0  5666.7    0.07       0
  5675.5    0.07       0  6099.8   0.045       0
Bank Sta=5666.7,5675.5
Exp/Cntr=0.3,0.1

Type RM Length L Ch R = 1,5000,500,500,500
BEGIN DESCRIPTION:
Bull Creek Trib097 10.0
END DESCRIPTION:
XS GIS Cut Line= 4
      1349855.01      6923288.03      1349475.65      6922395.11
      1349355.44      6922325.48      1347373.19      6921200.76
#Sta/Elev= 30
  3890.9 2099.66  4249.5 2080.75  4369.5 2077.08  4896.5 2072.13  4941.0 2065.31
  4962.5 2064.82  4979.7 2057.79  4980.2 2057.29  4988.5 2057.79  5021.5 2065.61
  5138.5 2065.56  5183.1 2073.18  5204.7 2074.34  5415.7 2073.03  5635.9 2070.42
  6288.2 2077.28  6362.8 2079.11  6422.0 2083.49  6598.7 2084.79  6679.1 2090.17
  6729.2 2089.36  6782.5 2094.20  6809.9 2093.01  6955.6 2096.81  7030.6 2101.25
  7073.9 2100.26  7127.3 2105.37  7176.3 2105.65  7192.1 2108.70  7279.1 2109.25
#Mann=5,-1,0
  3890.9   0.045       0  4369.5    0.07       0  4979.7    0.07       0
  4988.5    0.07       0  5415.7   0.045       0
Bank Sta=4979.7,4988.5
Exp/Cntr=0.3,0.1

Type RM Length L Ch R = 1,4500,500,500,500
BEGIN DESCRIPTION:
Bull Creek Trib097 9.0
END DESCRIPTION:
XS GIS Cut Line= 3
      1350355.03      6922838.03      1349566.05      6922026.00
      1347492.54      6921157.35
#Sta/Elev= 30
  3867.8 2096.30  4058.8 2089.94  4271.0 2077.40  4387.9 2075.36  4452.9 2072.59
  4631.6 2066.39  4921.6 2070.35  4949.8 2063.25  4985.1 2061.11  4992.3 2055.43
  5002.7 2054.92  5003.2 2054.42  5011.6 2054.92  5030.9 2055.86  5036.4 2064.56
  5044.5 2062.73  5066.2 2068.73  5113.1 2072.73  5139.4 2071.08  5502.4 2069.25
  5998.6 2071.94  6069.0 2075.72  6304.7 2079.17  6367.2 2084.40  6464.8 2084.59
  6564.2 2090.75  6712.3 2090.43  6794.5 2094.67  6995.6 2095.93  7248.1 2103.55
#Mann=6,-1,0
  3867.8    0.07       0  4387.9   0.045       0  4452.9    0.07       0
  5002.7    0.07       0  5011.6    0.07       0  5139.4   0.045       0
Bank Sta=5002.7,5011.6
Exp/Cntr=0.3,0.1

Type RM Length L Ch R = 1,4000,500,500,500
BEGIN DESCRIPTION:
Bull Creek Trib097 8.0
END DESCRIPTION:
XS GIS Cut Line= 4
      1350357.13      6922817.49      1349985.28      6922068.41
      1349999.07      6921851.81      1347535.99      6921103.11
#Sta/Elev= 30
  4163.7 2095.09  4247.0 2094.00  4314.3 2088.99  4352.9 2090.11  4409.5 2085.04
  4442.2 2086.02  4509.2 2081.04  4675.0 2076.26  4832.4 2071.28  4880.1 2068.70
  4919.3 2061.82  4978.1 2060.72  4992.9 2054.90  4993.4 2054.40  5001.9 2054.90
  5030.5 2055.74  5056.0 2062.15  5120.6 2067.34  5252.7 2070.61  5285.5 2068.24
  5662.7 2067.90  6475.5 2070.40  6569.6 2072.68  6600.9 2076.35  6789.1 2078.68
  6841.3 2084.29  6964.0 2085.50  7165.3 2094.88  7412.3 2094.23  7791.4 2099.72
#Mann=6,-1,0
  4163.7    0.07       0  4675.0   0.045       0  4832.4    0.07       0
  4992.9    0.07       0  5001.9    0.07       0  5056.0   0.045       0
Bank Sta=4992.9,5001.9
Exp/Cntr=0.3,0.1

Type RM Length L Ch R = 1,3500,500,500,500
BEGIN DESCRIPTION:
Bull Creek Trib097 7.0
END DESCRIPTION:
XS GIS Cut Line= 4
      1350357.15      6922871.76      1350395.56      6921987.20
      1350140.13      6921656.49      1347678.50      6921081.75
#Sta/Elev= 30
  4114.6 2097.17  4228.5 2092.71  4268.5 2093.63  4328.6 2089.10  4368.6 2089.75
  4407.2 2085.26  4448.7 2085.74  4488.7 2081.56  4518.7 2082.41  4941.5 2059.65
  4979.2 2058.49  4989.2 2056.08  4992.6 2052.60  4993.1 2052.10  5001.6 2052.60
  5013.5 2054.38  5021.7 2058.53  5206.4 2066.12  5520.9 2068.28  6710.3 2069.14
  6819.7 2071.02  6871.1 2076.51  7004.6 2078.61  7055.7 2084.31  7097.0 2083.22
  7220.2 2086.84  7251.0 2090.11  7326.2 2089.89  7411.3 2094.62  7945.7 2095.98
#Mann=4,-1,0
  4114.6    0.07       0  4941.5   0.045       0  4992.6   0.045       0
  5001.6   0.045       0
Bank Sta=4992.6,5001.6
Exp/Cntr=0.3,0.1

Type RM Length L Ch R = 1,3000,500,500,500
BEGIN DESCRIPTION:
Bull Creek Trib097 6.0
END DESCRIPTION:
XS GIS Cut Line= 4
      1350777.74      6922855.18      1350806.15      6922042.47
      1350715.22      6921699.90      1348004.24      6921092.64
#Sta/Elev= 30
  4186.8 2098.72  4250.3 2097.58  4284.0 2092.37  4314.1 2092.92  4344.1 2088.61
  4364.1 2089.75  4444.1 2082.26  4533.5 2078.68  4594.2 2071.75  4884.4 2063.79
  4944.4 2056.94  4960.0 2050.94  4960.5 2050.44  4969.0 2050.94  4994.5 2056.88
  5069.1 2059.26  5201.2 2063.30  5713.3 2064.21  6026.2 2068.45  6074.7 2065.08
  7220.4 2068.93  7322.2 2070.82  7383.7 2077.09  7485.8 2078.32  7539.4 2084.24
  7723.1 2085.78  7761.4 2089.43  7906.8 2090.26  7993.6 2094.61  8132.6 2093.72
#Mann=4,-1,0
  4186.8    0.07       0  4960.0    0.07       0  4969.0    0.07       0
  5069.1   0.045       0
Bank Sta=4960,4969
Exp/Cntr=0.3,0.1

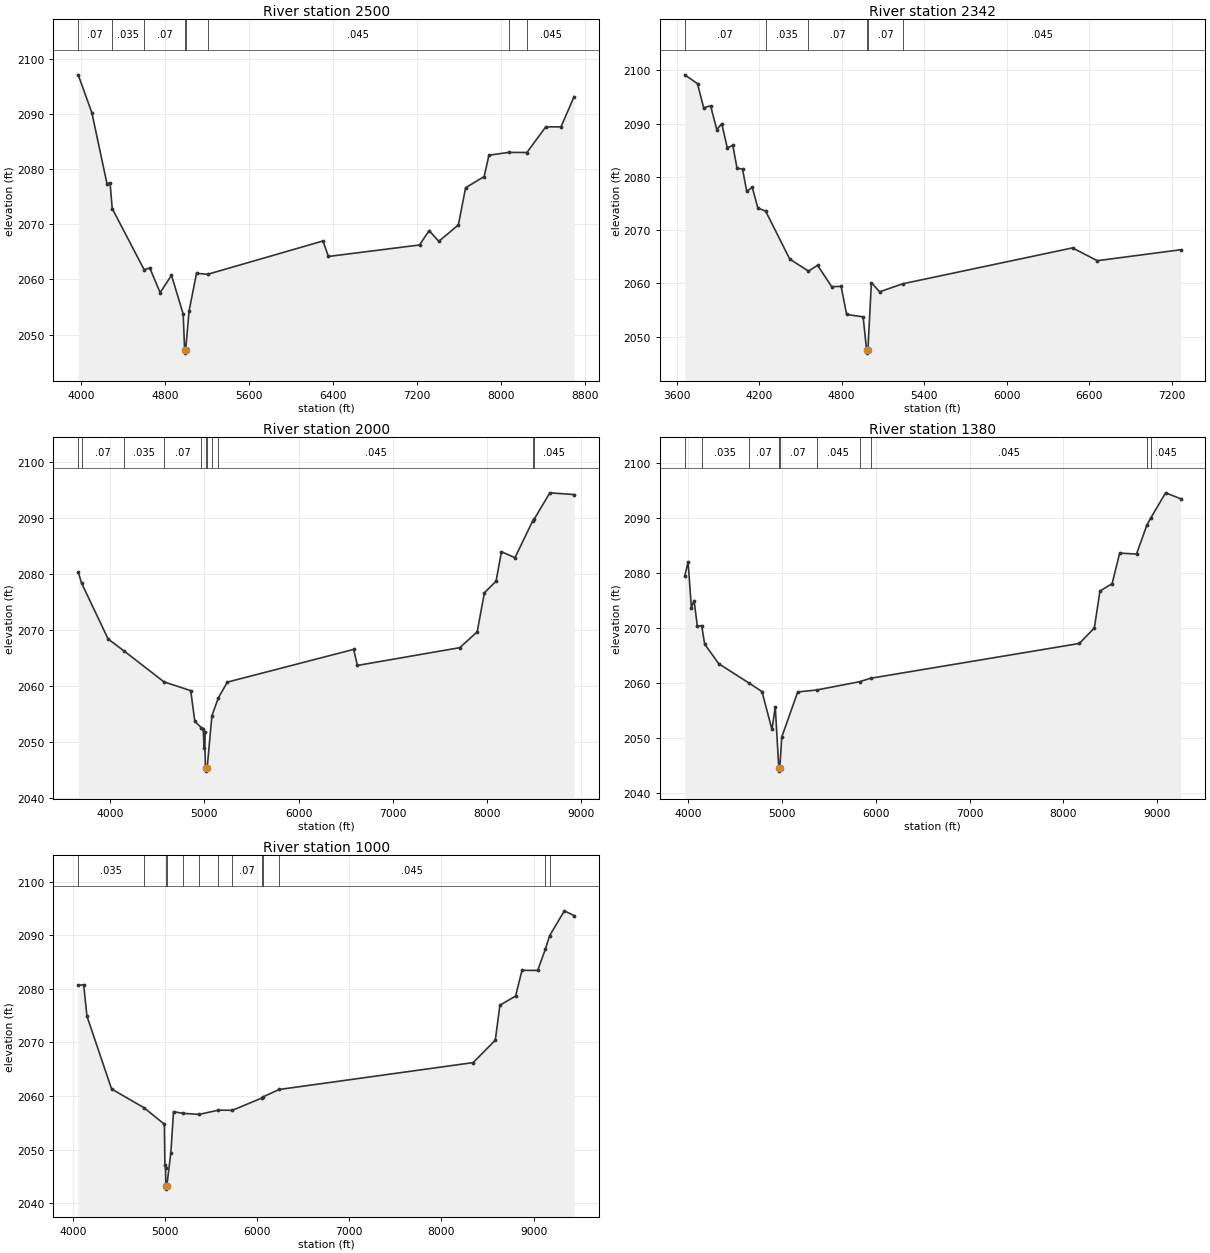
Type RM Length L Ch R = 1,2500,158,158,158
BEGIN DESCRIPTION:
Bull Creek Trib097 5.0
END DESCRIPTION:
XS GIS Cut Line= 4
      1350855.01      6922837.98      1351252.54      6921887.57
      1350943.08      6921580.54      1347752.96      6920918.64
#Sta/Elev= 30
  3969.8 2097.06  4099.9 2090.20  4244.0 2077.33  4273.3 2077.50  4293.9 2072.84
  4597.7 2061.77  4651.9 2062.07  4750.2 2057.61  4858.5 2060.75  4970.0 2053.72
  4983.8 2047.15  4984.3 2046.65  4992.8 2047.15  5026.2 2054.32  5096.9 2061.11
  5203.4 2060.93  6302.1 2066.97  6353.1 2064.16  7221.2 2066.24  7313.2 2068.84
  7405.1 2066.90  7591.8 2069.88  7660.4 2076.61  7837.4 2078.64  7882.5 2082.50
  8070.0 2083.01  8244.4 2082.99  8423.9 2087.63  8569.2 2087.64  8694.0 2093.10
#Mann=8,-1,0
  3969.8    0.07       0  4293.9   0.035       0  4597.7    0.07       0
  4983.8    0.07       0  4992.8    0.07       0  5203.4   0.045       0
  8070.0    0.07       0  8244.4   0.045       0
Bank Sta=4983.8,4992.8
Exp/Cntr=0.3,0.1

Type RM Length L Ch R = 1,2342,342,342,342
BEGIN DESCRIPTION:
Bull Creek Trib097 4.5
END DESCRIPTION:
XS GIS Cut Line= 5
      1351246.48      6923224.12      1351402.74      6922152.05
      1351411.42      6921813.51      1350797.68      6921422.12
      1349354.10      6921227.57
#Sta/Elev= 30
  3659.5 2099.16  3752.4 2097.50  3797.1 2092.97  3847.6 2093.35  3892.5 2088.88
  3928.4 2089.99  3968.9 2085.49  4009.3 2085.90  4039.6 2081.67  4080.0 2081.45
  4110.3 2077.30  4150.8 2078.05  4191.2 2074.16  4247.7 2073.59  4423.6 2064.57
  4559.5 2062.33  4625.7 2063.41  4727.9 2059.41  4797.0 2059.45  4837.0 2054.18
  4957.0 2053.74  4982.5 2047.43  4983.0 2046.93  4991.5 2047.43  5017.0 2060.15
  5076.8 2058.44  5246.2 2059.95  6479.9 2066.68  6659.8 2064.28  7266.1 2066.33
#Mann=6,-1,0
  3659.5    0.07       0  4247.7   0.035       0  4559.5    0.07       0
  4982.5    0.07       0  4991.5    0.07       0  5246.2   0.045       0
Bank Sta=4982.5,4991.5
Exp/Cntr=0.3,0.1

Type RM Length L Ch R = 1,2000,620,620,620
BEGIN DESCRIPTION:
Bull Creek Trib097 4.0
END DESCRIPTION:
XS GIS Cut Line= 5
      1351984.33      6922989.71      1351776.00      6921865.59
      1351605.03      6921773.61      1350932.23      6921374.38
      1347808.66      6921059.85
#Sta/Elev= 30
  3662.6 2080.43  3697.5 2078.46  3979.6 2068.45  4147.4 2066.33  4572.8 2060.79
  4855.8 2059.23  4899.6 2053.72  4968.2 2052.63  4988.7 2052.38  4997.2 2048.98
  5003.5 2051.85  5011.7 2045.46  5020.1 2045.36  5020.6 2044.86  5029.8 2045.36
  5080.6 2054.75  5149.0 2057.95  5244.2 2060.75  6583.6 2066.59  6623.8 2063.73
  7709.3 2066.90  7893.7 2069.72  7970.6 2076.69  8094.0 2078.77  8151.5 2084.03
  8294.3 2082.96  8484.8 2089.60  8498.2 2089.83  8664.1 2094.54  8921.7 2094.23
#Mann=11,-1,0
  3662.6    0.05       0  3697.5    0.07       0  4147.4   0.035       0
  4572.8    0.07       0  4968.2   0.045       0  5020.1   0.045       0
  5029.8   0.045       0  5080.6    0.07       0  5149.0   0.045       0
  8484.8    0.07       0  8498.2   0.045       0
Bank Sta=5020.1,5029.8
Exp/Cntr=0.3,0.1

Type RM Length L Ch R = 1,1380,380,380,380
BEGIN DESCRIPTION:
Bull Creek Trib097 3.0
END DESCRIPTION:
XS GIS Cut Line= 5
      1352604.97      6922487.97      1351942.95      6921688.25
      1351891.51      6921511.41      1351279.45      6921189.91
      1347904.90      6921081.41
#Sta/Elev= 30
  3960.6 2079.37  3996.4 2081.98  4031.5 2073.66  4060.2 2074.95  4095.4 2070.25
  4141.2 2070.41  4173.5 2067.03  4323.3 2063.47  4647.7 2059.94  4784.4 2058.41
  4891.2 2051.51  4926.4 2055.63  4964.4 2044.44  4964.9 2043.94  4974.2 2044.44
  4995.7 2050.15  5165.7 2058.33  5370.1 2058.70  5825.7 2060.20  5944.8 2060.83
  8169.9 2067.15  8330.0 2069.96  8390.1 2076.68  8520.1 2078.03  8600.2 2083.58
  8780.3 2083.41  8890.0 2088.65  8929.5 2089.89  9090.4 2094.54  9250.6 2093.47
#Mann=10,-1,0
  3960.6    0.07       0  4141.2   0.035       0  4647.7    0.07       0
  4964.4    0.07       0  4974.2    0.07       0  5370.1   0.045       0
  5825.7    0.07       0  5944.8   0.045       0  8890.0    0.07       0
  8929.5   0.045       0
Bank Sta=4964.4,4974.2
Exp/Cntr=0.3,0.1

Type RM Length L Ch R = 1,1000,0,0,0
BEGIN DESCRIPTION:
Bull Creek Trib097 2.0
END DESCRIPTION:
XS GIS Cut Line= 4
      1352754.98      6922287.97      1352247.94      6921492.89
      1351702.63      6921059.71      1347959.60      6921092.25
#Sta/Elev= 30
  4057.0 2080.64  4116.2 2080.76  4151.8 2074.90  4419.2 2061.32  4771.3 2057.82
  4992.1 2054.75  4998.0 2047.17  5005.1 2046.50  5007.9 2043.14  5008.4 2042.64
  5018.1 2043.14  5062.7 2049.46  5091.5 2057.09  5195.5 2056.77  5370.7 2056.58
  5578.5 2057.37  5729.7 2057.34  6051.5 2059.64  6062.4 2059.84  6238.2 2061.22
  8344.2 2066.24  8584.2 2070.42  8634.2 2076.94  8804.2 2078.64  8874.2 2083.44
  9044.2 2083.43  9126.7 2087.34  9174.1 2089.91  9334.2 2094.54  9439.6 2093.65
#Mann=13,-1,0
  4057.0   0.035       0  4771.3    0.07       0  5007.9    0.07       0
  5018.1    0.07       0  5195.5   0.045       0  5370.7    0.07       0
  5578.5   0.045       0  5729.7    0.07       0  6051.5   0.045       0
  6062.4    0.07       0  6238.2   0.045       0  9126.7    0.07       0
  9174.1   0.045       0
Bank Sta=5007.9,5018.1
Exp/Cntr=0.3,0.1

Chan Stop Cuts=-1