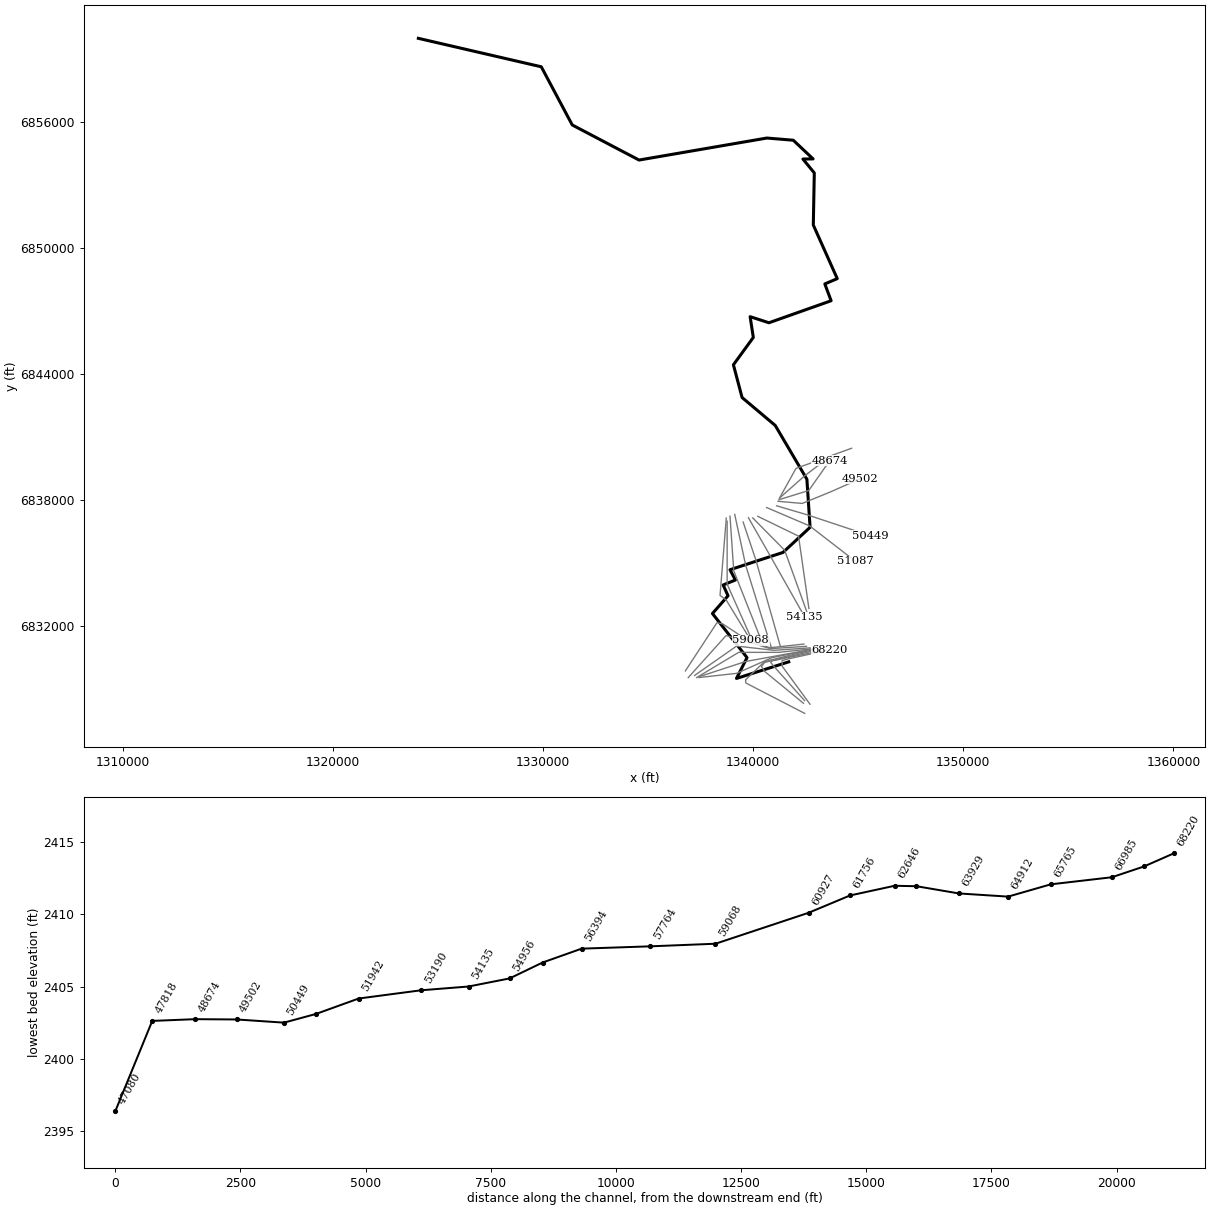
--- Cottonwood Creek Trib01.prj (project) ---

Proj Title=Cottonwood Creek Trib01 Base Level Engineering
Current Plan=p01
Default Exp/Contr=0.3,0.1
English Units
Geom File=g01
Flow File=f01
Plan File=p01
BEGIN DESCRIPTION:
Cottonwood Creek Trib01
END DESCRIPTION:

--- Cottonwood Creek Trib01.p01 (plan) ---

Plan Title=Multiple Run
Short Identifier=Multiple
Geom File=g01
Flow File=f01
Subcritical Flow
K Sum by GR= 0
Std Step Tol= 0.01
Critical Tol= 0.01
Num of Std Step Trials= 20
Max Error Tol= 0.3
Flow Tol Ratio= 0.001
Split Flow NTrial= 30
Split Flow Tol= 0.02
Split Flow Ratio= 0.02
Log Output Level= 0
Friction Slope Method= 1
Unsteady Friction Slope Method= 2
Unsteady Bridges Friction Slope Method= 1
Parabolic Critical Depth
Global Vel Dist=  1 , 1 , 1
Global Log Level= 0
CheckData=True
Encroach Param= -1, 0, 0, 0
BEGIN DESCRIPTION:
Multiple Run
END DESCRIPTION:

--- Cottonwood Creek Trib01.f01 (steady flow) ---

Flow Title=Multiple
Number of Profiles=7
Profile Names=10-year,25-year,50-year,1pct_min,100-year,1pct_plu,500-year
River Rch & RM= Cottonwood Creek,Reach-1,68220
     234     327     403     247     493     984     748
River Rch & RM= Cottonwood Creek,Reach-1,66985
     344     490     612     379     757    1510    1175
River Rch & RM= Cottonwood Creek,Reach-1,64912
     503     726     916     572    1142    2278    1801
River Rch & RM= Cottonwood Creek,Reach-1,59068
     689    1002    1270     796    1588    3169    2522
River Rch & RM= Cottonwood Creek,Reach-1,51087
     717    1043    1322     828    1653    3297    2622
River Rch & RM= Cottonwood Creek,Reach-1,48674
     713    1032    1302     813    1621    3235    2552
River Rch & RM= Cottonwood Creek,Reach-1,36415
     870    1268    1610    1009    2014    4019    3201
River Rch & RM= Cottonwood Creek,Reach-1,34798
     868    1266    1606    1006    2008    4007    3188
River Rch & RM= Cottonwood Creek,Reach-1,31038
     919    1341    1703    1068    2131    4253    3390
River Rch & RM= Cottonwood Creek,Reach-1,30195
     939    1372    1742    1093    2181    4351    3469
River Rch & RM= Cottonwood Creek,Reach-1,27353
    1103    1623    2072    1307    2607    5202    4191
River Rch & RM= Cottonwood Creek,Reach-1,21898
    1165    1720    2200    1391    2775    5537    4479
River Rch & RM= Cottonwood Creek,Reach-1,20182
    1175    1727    2203    1387    2768    5523    4437
River Rch & RM= Cottonwood Creek,Reach-1,8293
    1345    1983    2536    1601    3194    6372    5139
River Rch & RM= Cottonwood Creek,Reach-1,6174
    1331    1957    2498    1573    3139    6263    5031
Boundary for River Rch & Prof#=Cottonwood Creek,Reach-1,1
Up Type=0
Dn Type=3
Dn Slope=0.005
Boundary for River Rch & Prof#=Cottonwood Creek,Reach-1,2
Up Type=0
Dn Type=3
Dn Slope=0.005
Boundary for River Rch & Prof#=Cottonwood Creek,Reach-1,3
Up Type=0
Dn Type=3
Dn Slope=0.005
Boundary for River Rch & Prof#=Cottonwood Creek,Reach-1,4
Up Type=0
Dn Type=3
Dn Slope=0.005
Boundary for River Rch & Prof#=Cottonwood Creek,Reach-1,5
Up Type=0
Dn Type=3
Dn Slope=0.005
Boundary for River Rch & Prof#=Cottonwood Creek,Reach-1,6
Up Type=0
Dn Type=3
Dn Slope=0.005
Boundary for River Rch & Prof#=Cottonwood Creek,Reach-1,7
Up Type=0
Dn Type=3
Dn Slope=0.005

--- Cottonwood Creek Trib01.g01 (geometry) ---

Geom Title=Existing Conditions

River Reach=Cottonwood Creek,Reach-1
Reach XY= 30
      1341687.02      6830286.37      1339198.68      6829495.50
      1339701.96      6830486.64      1338055.00      6832588.00
      1338797.49      6833434.82      1338565.81      6833948.38
      1339147.42      6834184.68      1338891.66      6834674.67
      1341411.95      6835497.18      1342703.34      6836694.05
      1342551.45      6838986.53      1341044.22      6841547.68
      1339466.11      6842877.68      1339053.94      6844437.63
      1340001.63      6845739.28      1339848.80      6846730.32
      1340744.30      6846438.70      1343705.00      6847488.00
      1343405.00      6848288.00      1343997.33      6848541.65
      1342857.26      6851093.94      1342904.06      6853577.51
      1342361.98      6854238.27      1342846.06      6854244.68
      1341903.72      6855134.48      1340644.81      6855238.45
      1334560.93      6854190.24      1331381.53      6855861.01
      1329907.30      6858632.17      1324055.00      6859988.00

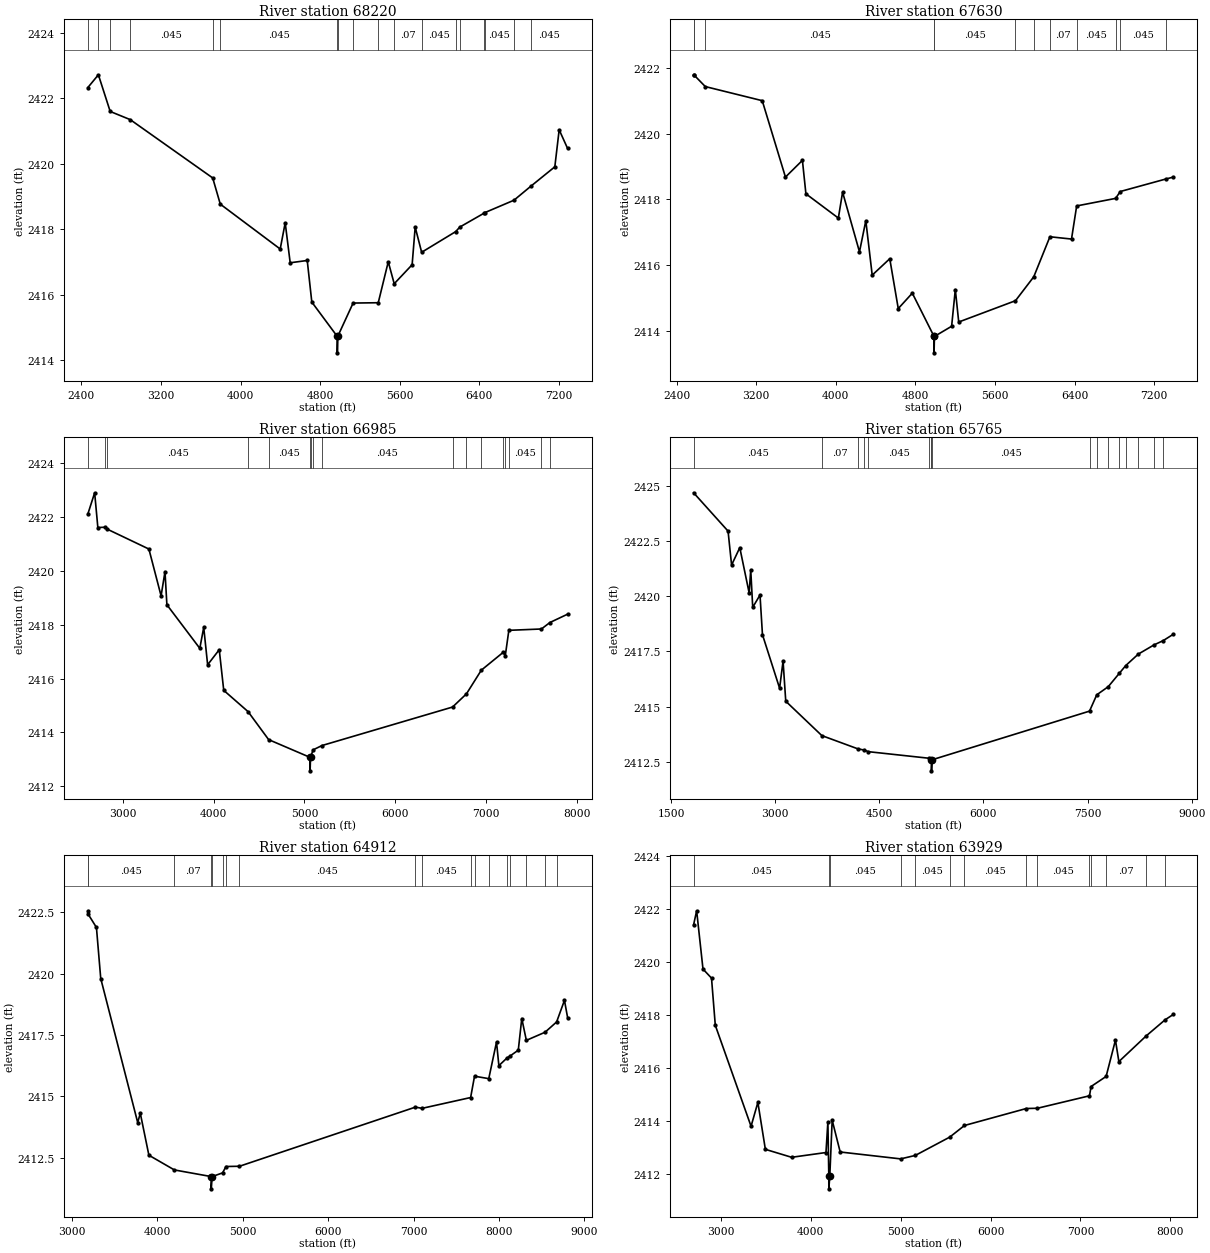
Type RM Length L Ch R = 1,68220,590,590,590
BEGIN DESCRIPTION:
Cottonwood Creek Trib01 35.0
END DESCRIPTION:
XS GIS Cut Line= 5
      1342699.21      6828268.53      1341376.96      6830075.30
      1341374.06      6830342.73      1341626.96      6830419.05
      1343631.15      6830861.63
#Sta/Elev= 30
  2464.7 2422.32  2570.7 2422.71  2689.4 2421.59  2891.2 2421.34  3719.9 2419.56
  3796.3 2418.76  4398.5 2417.39  4448.7 2418.19  4498.9 2416.97  4670.3 2417.04
  4716.3 2415.77  4972.6 2414.72  4972.9 2414.22  4976.6 2414.72  5131.4 2415.74
  5384.2 2415.75  5484.8 2417.00  5544.7 2416.33  5724.8 2416.91  5755.5 2418.06
  5820.4 2417.29  6162.1 2417.92  6203.9 2418.06  6451.3 2418.49  6454.7 2418.50
  6748.6 2418.88  6915.3 2419.30  7159.3 2419.90  7203.0 2421.03  7287.7 2420.46
#Mann=18,-1,0
  2464.7    0.07       0  2570.7   0.045       0  2689.4    0.07       0
  2891.2   0.045       0  3719.9    0.07       0  3796.3   0.045       0
  4972.6   0.045       0  4976.6   0.045       0  5131.4    0.07       0
  5384.2   0.045       0  5544.7    0.07       0  5820.4   0.045       0
  6162.1    0.07       0  6203.9   0.045       0  6451.3    0.07       0
  6454.7   0.045       0  6748.6    0.07       0  6915.3   0.045       0
Bank Sta=4972.6,4976.6
Exp/Cntr=0.3,0.1

Type RM Length L Ch R = 1,67630,645,645,645
BEGIN DESCRIPTION:
Cottonwood Creek Trib01 34.5
END DESCRIPTION:
XS GIS Cut Line= 5
      1342441.59      6828440.71      1341000.59      6830049.90
      1340831.83      6830255.85      1340875.23      6830328.77
      1343137.36      6830794.04
#Sta/Elev= 30
  2571.4 2421.79  2573.3 2421.80  2689.2 2421.44  3261.2 2421.01  3494.4 2418.68
  3664.9 2419.19  3700.0 2418.17  4026.0 2417.43  4068.6 2418.22  4238.3 2416.40
  4301.9 2417.35  4366.2 2415.69  4542.6 2416.19  4627.9 2414.67  4769.1 2415.14
  4987.5 2413.82  4987.7 2413.32  4991.5 2413.82  5164.1 2414.13  5201.3 2415.25
  5235.5 2414.26  5805.9 2414.91  5989.7 2415.64  6151.8 2416.86  6368.8 2416.79
  6420.7 2417.80  6811.6 2418.03  6859.1 2418.24  7315.1 2418.62  7392.1 2418.68
#Mann=12,-1,0
  2571.4   0.045       0  2573.3    0.07       0  2689.2   0.045       0
  4987.5   0.045       0  4991.5   0.045       0  5805.9    0.07       0
  5989.7   0.045       0  6151.8    0.07       0  6420.7   0.045       0
  6811.6    0.07       0  6859.1   0.045       0  7315.1    0.07       0
Bank Sta=4987.5,4991.5
Exp/Cntr=0.3,0.1

Type RM Length L Ch R = 1,66985,1220,1220,1220
BEGIN DESCRIPTION:
Cottonwood Creek Trib01 34.0
END DESCRIPTION:
XS GIS Cut Line= 5
      1342386.65      6828314.39      1340541.77      6829828.64
      1340389.68      6830066.69      1340535.16      6830258.45
      1342841.41      6830806.93
#Sta/Elev= 30
  2616.0 2422.11  2691.0 2422.90  2726.1 2421.61  2807.7 2421.62  2828.6 2421.55
  3288.0 2420.81  3422.2 2419.07  3465.2 2419.97  3486.0 2418.74  3848.4 2417.12
  3891.5 2417.90  3934.5 2416.51  4062.3 2417.07  4111.8 2415.56  4379.5 2414.77
  4605.9 2413.73  5062.1 2413.07  5062.4 2412.57  5066.8 2413.07  5095.6 2413.35
  5193.1 2413.51  6630.3 2414.94  6783.2 2415.43  6947.0 2416.31  7190.5 2416.98
  7209.9 2416.83  7249.9 2417.79  7608.4 2417.84  7701.8 2418.08  7896.5 2418.39
#Mann=17,-1,0
  2616.0   0.045       0  2807.7    0.07       0  2828.6   0.045       0
  4379.5    0.07       0  4605.9   0.045       0  5062.1   0.045       0
  5066.8   0.045       0  5095.6    0.07       0  5193.1   0.045       0
  6630.3    0.07       0  6783.2   0.045       0  6947.0    0.07       0
  7190.5   0.045       0  7209.9    0.07       0  7249.9   0.045       0
  7608.4    0.07       0  7701.8   0.045       0
Bank Sta=5062.1,5066.8
Exp/Cntr=0.3,0.1

Type RM Length L Ch R = 1,65765,853,853,853
BEGIN DESCRIPTION:
Cottonwood Creek Trib01 33.0
END DESCRIPTION:
XS GIS Cut Line= 5
      1342446.14      6827831.69      1339644.19      6829280.48
      1339635.86      6829431.89      1340535.16      6830298.13
      1342821.56      6830866.42
#Sta/Elev= 30
  1825.7 2424.70  2322.3 2422.96  2372.9 2421.42  2491.2 2422.21  2626.3 2420.15
  2648.8 2421.21  2677.3 2419.50  2782.4 2420.06  2817.7 2418.26  3064.6 2415.83
  3114.6 2417.06  3153.2 2415.24  3672.9 2413.68  4190.6 2413.08  4287.1 2413.02
  4342.9 2412.95  5221.4 2412.65  5245.1 2412.60  5252.1 2412.58  5252.6 2412.08
  5259.0 2412.58  7528.8 2414.79  7633.1 2415.53  7798.7 2415.90  7956.3 2416.50
  8051.2 2416.86  8232.3 2417.38  8460.4 2417.80  8590.5 2417.99  8736.3 2418.28
#Mann=17,-1,0
  1825.7   0.045       0  3672.9    0.07       0  4190.6   0.045       0
  4287.1    0.07       0  4342.9   0.045       0  5221.4    0.07       0
  5245.1   0.045       0  5252.1   0.045       0  5259.0   0.045       0
  7528.8    0.07       0  7633.1   0.045       0  7798.7    0.07       0
  7956.3   0.045       0  8051.2    0.07       0  8232.3   0.045       0
  8460.4    0.07       0  8590.5   0.045       0
Bank Sta=5252.1,5259
Exp/Cntr=0.3,0.1

Type RM Length L Ch R = 1,64912,983,983,983
BEGIN DESCRIPTION:
Cottonwood Creek Trib01 32.0
END DESCRIPTION:
XS GIS Cut Line= 4
      1337405.02      6829538.00      1339205.00      6829738.00
      1340898.67      6830490.74      1342811.08      6830868.34
#Sta/Elev= 30
  3188.8 2422.56  3194.7 2422.41  3289.4 2421.88  3339.7 2419.80  3772.3 2413.93
  3802.5 2414.31  3903.1 2412.60  4201.5 2412.00  4632.0 2411.73  4632.5 2411.23
  4643.3 2411.73  4765.3 2411.88  4805.4 2412.14  4963.2 2412.15  7022.3 2414.56
  7100.1 2414.51  7667.9 2414.95  7713.6 2415.82  7880.1 2415.72  7970.8 2417.21
  7998.5 2416.25  8092.9 2416.56  8124.1 2416.63  8225.6 2416.88  8266.4 2418.17
  8320.0 2417.28  8538.3 2417.61  8674.1 2418.03  8765.8 2418.91  8802.6 2418.21
#Mann=18,-1,0
  3188.8   0.035       0  3194.7   0.045       0  4201.5    0.07       0
  4632.0   0.045       0  4643.3    0.07       0  4765.3   0.045       0
  4805.4    0.07       0  4963.2   0.045       0  7022.3    0.07       0
  7100.1   0.045       0  7667.9    0.07       0  7713.6   0.045       0
  7880.1    0.07       0  8092.9   0.045       0  8124.1    0.07       0
  8320.0   0.045       0  8538.3    0.07       0  8674.1   0.045       0
Bank Sta=4632,4643.3
Exp/Cntr=0.3,0.1

Type RM Length L Ch R = 1,63929,847,847,847
BEGIN DESCRIPTION:
Cottonwood Creek Trib01 31.5
END DESCRIPTION:
XS GIS Cut Line= 3
      1337465.62      6829593.10      1339627.99      6830301.46
      1342638.53      6830851.38
#Sta/Elev= 30
  2697.5 2421.41  2731.5 2421.94  2802.1 2419.74  2896.8 2419.40  2938.9 2417.62
  3336.6 2413.81  3412.4 2414.71  3495.8 2412.94  3787.7 2412.64  4169.8 2412.82
  4191.1 2413.98  4201.3 2411.95  4201.8 2411.45  4212.6 2411.95  4238.8 2414.04
  4327.9 2412.84  5000.3 2412.58  5162.9 2412.71  5545.6 2413.40  5710.4 2413.84
  6397.7 2414.48  6521.6 2414.49  7100.6 2414.96  7118.3 2415.31  7285.6 2415.69
  7389.3 2417.06  7427.5 2416.25  7731.4 2417.22  7942.8 2417.83  8033.3 2418.03
#Mann=14,-1,0
  2697.5   0.045       0  4201.3   0.045       0  4212.6   0.045       0
  5000.3    0.07       0  5162.9   0.045       0  5545.6    0.07       0
  5710.4   0.045       0  6397.7    0.07       0  6521.6   0.045       0
  7100.6    0.07       0  7118.3   0.045       0  7285.6    0.07       0
  7731.4   0.045       0  7942.8    0.07       0
Bank Sta=4201.3,4212.6
Exp/Cntr=0.3,0.1

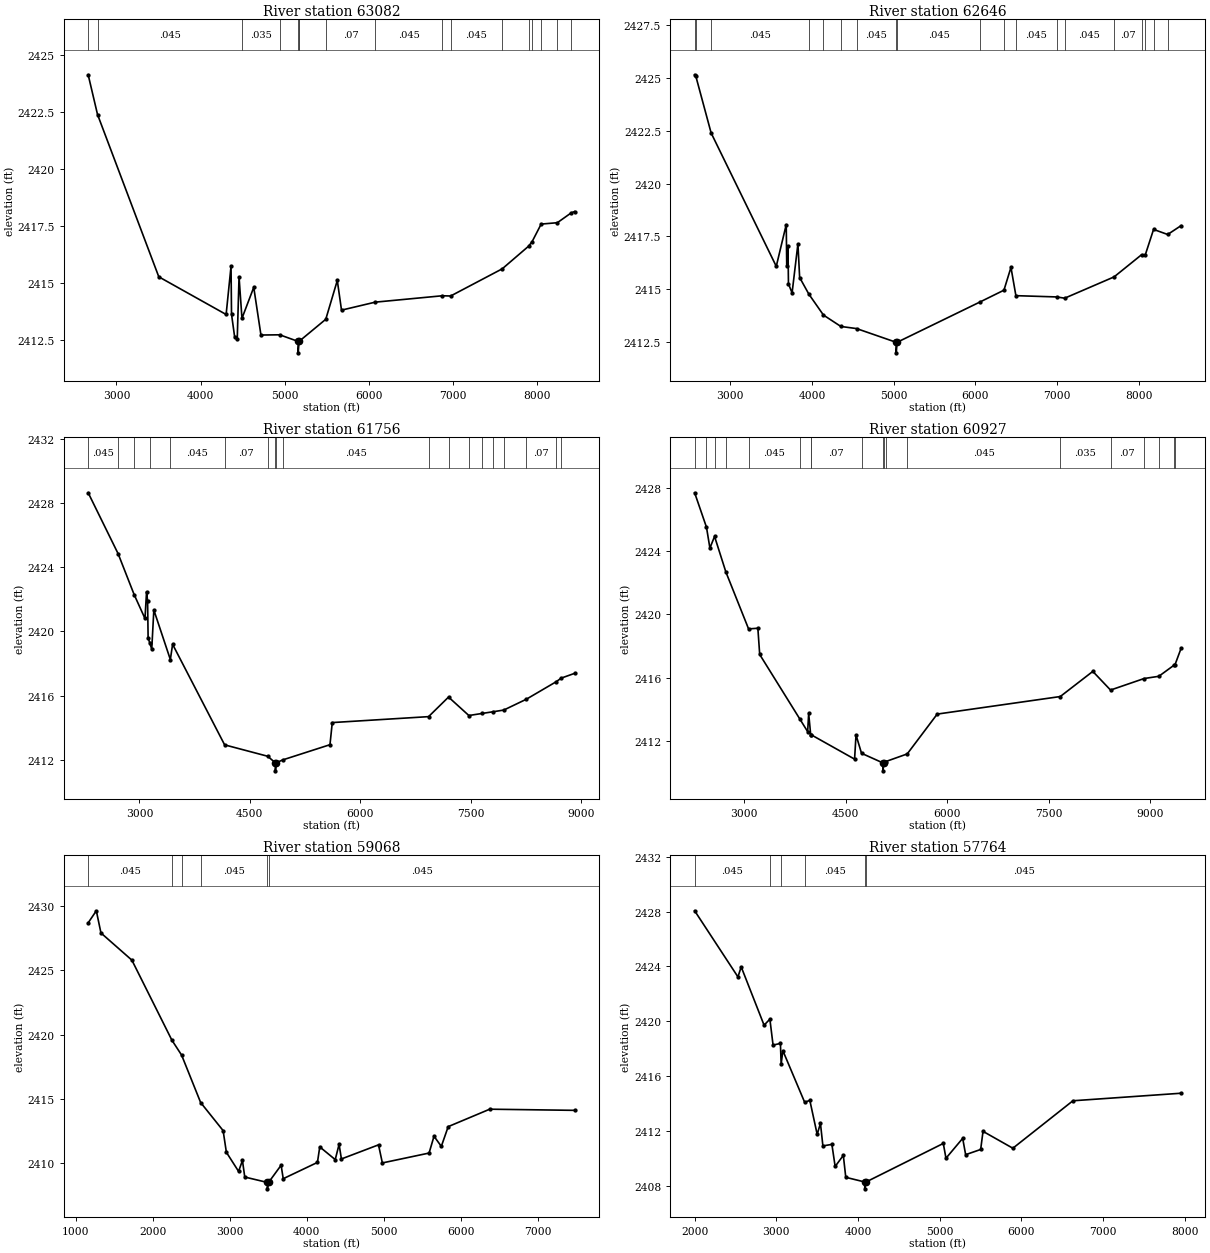
Type RM Length L Ch R = 1,63082,436,436,436
BEGIN DESCRIPTION:
Cottonwood Creek Trib01 31.0
END DESCRIPTION:
XS GIS Cut Line= 4
      1337305.01      6829538.00      1339305.00      6830738.00
      1341201.05      6830738.00      1342748.34      6830903.13
#Sta/Elev= 30
  2663.4 2424.13  2774.5 2422.39  3503.1 2415.28  4303.8 2413.63  4362.1 2415.74
  4368.0 2413.64  4404.9 2412.65  4436.0 2412.56  4457.4 2415.28  4492.1 2413.46
  4632.3 2414.82  4717.8 2412.73  4940.9 2412.74  5160.1 2412.45  5160.6 2411.95
  5171.5 2412.45  5173.9 2412.46  5488.7 2413.42  5625.8 2415.12  5675.8 2413.82
  6076.4 2414.17  6874.6 2414.45  6973.8 2414.44  7587.0 2415.63  7900.1 2416.62
  7942.2 2416.82  8049.9 2417.59  8242.3 2417.65  8406.7 2418.08  8447.9 2418.14
#Mann=17,-1,0
  2663.4   0.035       0  2774.5   0.045       0  4492.1   0.035       0
  4940.9   0.045       0  5160.1   0.045       0  5171.5   0.045       0
  5173.9   0.035       0  5488.7    0.07       0  6076.4   0.045       0
  6874.6    0.07       0  6973.8   0.045       0  7587.0    0.07       0
  7900.1   0.045       0  7942.2    0.07       0  8049.9   0.045       0
  8242.3    0.07       0  8406.7   0.045       0
Bank Sta=5160.1,5171.5
Exp/Cntr=0.3,0.1

Type RM Length L Ch R = 1,62646,890,890,890
BEGIN DESCRIPTION:
Cottonwood Creek Trib01 30.0
END DESCRIPTION:
XS GIS Cut Line= 4
      1337204.99      6829637.99      1339205.00      6831038.00
      1340982.55      6830836.06      1342700.54      6830951.85
#Sta/Elev= 30
  2563.9 2425.16  2577.9 2425.10  2765.8 2422.40  3562.7 2416.08  3684.7 2418.06
  3690.8 2416.09  3705.7 2417.06  3711.8 2415.25  3756.2 2414.82  3827.7 2417.15
  3848.7 2415.55  3961.8 2414.76  4140.1 2413.77  4353.2 2413.23  4545.3 2413.13
  5029.7 2412.48  5030.2 2411.98  5041.2 2412.48  6055.1 2414.39  6348.6 2414.95
  6434.4 2416.03  6494.8 2414.69  6992.7 2414.63  7091.7 2414.57  7696.3 2415.58
  8032.4 2416.63  8078.5 2416.63  8179.3 2417.83  8351.9 2417.59  8516.1 2418.01
#Mann=19,-1,0
  2563.9   0.045       0  2577.9   0.035       0  2765.8   0.045       0
  3961.8   0.035       0  4140.1   0.045       0  4353.2   0.035       0
  4545.3   0.045       0  5029.7   0.045       0  5041.2   0.045       0
  6055.1   0.035       0  6348.6    0.07       0  6494.8   0.045       0
  6992.7    0.07       0  7091.7   0.045       0  7696.3    0.07       0
  8032.4   0.045       0  8078.5    0.07       0  8179.3   0.045       0
  8351.9    0.07       0
Bank Sta=5029.7,5041.2
Exp/Cntr=0.3,0.1

Type RM Length L Ch R = 1,61756,829,829,829
BEGIN DESCRIPTION:
Cottonwood Creek Trib01 29.0
END DESCRIPTION:
XS GIS Cut Line= 4
      1336904.98      6829537.97      1338705.00      6831538.00
      1340811.12      6830915.77      1342529.87      6831025.15
#Sta/Elev= 30
  2303.6 2428.65  2710.4 2424.85  2929.0 2422.29  3075.3 2420.81  3097.0 2422.48
  3110.9 2421.90  3118.0 2419.60  3140.6 2419.28  3167.3 2418.90  3195.7 2421.34
  3420.0 2418.25  3450.6 2419.20  4157.5 2412.93  4742.1 2412.22  4847.0 2411.81
  4847.5 2411.31  4858.5 2411.81  4945.5 2411.99  5588.7 2412.94  5620.0 2414.32
  6928.2 2414.69  7199.6 2415.91  7475.7 2414.76  7657.1 2414.89  7798.5 2414.99
  7949.9 2415.10  8254.3 2415.77  8663.4 2416.87  8729.5 2417.09  8912.7 2417.39
#Mann=19,-1,0
  2303.6   0.045       0  2710.4   0.035       0  2929.0   0.045       0
  3140.6   0.035       0  3420.0   0.045       0  4157.5    0.07       0
  4742.1   0.035       0  4847.0   0.045       0  4858.5   0.035       0
  4945.5   0.045       0  6928.2   0.035       0  7199.6   0.045       0
  7475.7   0.035       0  7657.1   0.045       0  7798.5    0.07       0
  7949.9   0.045       0  8254.3    0.07       0  8663.4   0.045       0
  8729.5    0.07       0
Bank Sta=4847,4858.5
Exp/Cntr=0.3,0.1

Type RM Length L Ch R = 1,60927,1859,1859,1859
BEGIN DESCRIPTION:
Cottonwood Creek Trib01 28.6
END DESCRIPTION:
XS GIS Cut Line= 6
      1336766.61      6829854.08      1338267.21      6832146.91
      1338533.34      6832099.80      1339683.91      6831345.35
      1340790.24      6830957.31      1342410.01      6831134.52
#Sta/Elev= 30
  2268.7 2427.70  2443.7 2425.52  2494.2 2424.20  2562.9 2424.94  2730.1 2422.69
  3065.6 2419.09  3202.9 2419.13  3230.0 2417.47  3822.8 2413.39  3938.6 2412.59
  3953.7 2413.74  3983.4 2412.40  3991.1 2412.39  4632.2 2410.85  4653.2 2412.38
  4734.8 2411.22  5051.6 2410.61  5052.1 2410.11  5063.3 2410.61  5094.2 2410.70
  5409.9 2411.18  5853.1 2413.70  7671.4 2414.81  8152.4 2416.40  8414.3 2415.22
  8910.6 2415.95  9127.4 2416.09  9348.6 2416.78  9365.8 2416.81  9456.9 2417.86
#Mann=19,-1,0
  2268.7   0.045       0  2443.7    0.07       0  2562.9   0.035       0
  2730.1    0.07       0  3065.6   0.045       0  3822.8    0.07       0
  3983.4   0.045       0  3991.1    0.07       0  4734.8   0.045       0
  5051.6   0.045       0  5063.3   0.045       0  5094.2   0.035       0
  5409.9   0.045       0  7671.4   0.035       0  8414.3    0.07       0
  8910.6   0.045       0  9127.4    0.07       0  9348.6   0.045       0
  9365.8    0.07       0
Bank Sta=5051.6,5063.3
Exp/Cntr=0.3,0.1

Type RM Length L Ch R = 1,59068,1304,1304,1304
BEGIN DESCRIPTION:
Cottonwood Creek Trib01 28.5
END DESCRIPTION:
XS GIS Cut Line= 5
      1338714.58      6837133.31      1338416.33      6833451.77
      1338527.90      6833366.30      1338714.59      6833228.08
      1339879.66      6831308.04
#Sta/Elev= 30
  1163.2 2428.71  1268.9 2429.65  1329.0 2427.92  1730.4 2425.80  2249.6 2419.56
  2375.4 2418.40  2622.5 2414.70  2914.2 2412.51  2956.6 2410.82  3114.9 2409.33
  3165.0 2410.18  3195.1 2408.89  3488.0 2408.47  3488.5 2407.97  3504.2 2408.47
  3666.7 2409.81  3694.3 2408.76  4138.2 2410.03  4168.3 2411.24  4369.0 2410.25
  4419.1 2411.44  4449.2 2410.30  4930.7 2411.40  4980.6 2409.99  5586.8 2410.76
  5650.8 2412.07  5745.7 2411.28  5834.9 2412.82  6373.8 2414.18  7475.5 2414.09
#Mann=6,-1,0
  1163.2   0.045       0  2249.6   0.035       0  2375.4    0.07       0
  2622.5   0.045       0  3488.0   0.045       0  3504.2   0.045       0
Bank Sta=3488,3504.2
Exp/Cntr=0.3,0.1

Type RM Length L Ch R = 1,57764,1370,1370,1370
BEGIN DESCRIPTION:
Cottonwood Creek Trib01 28.0
END DESCRIPTION:
XS GIS Cut Line= 3
      1338755.00      6836988.00      1338755.00      6833988.00
      1339955.02      6831287.96
#Sta/Elev= 30
  1999.6 2428.06  2529.6 2423.24  2569.6 2423.97  2849.6 2419.72  2920.6 2420.16
  2959.6 2418.27  3049.6 2418.39  3058.6 2416.89  3079.6 2417.86  3346.3 2414.10
  3409.6 2414.24  3499.6 2411.76  3539.6 2412.56  3569.6 2410.92  3679.6 2411.03
  3719.6 2409.42  3819.6 2410.23  3849.6 2408.63  4081.5 2408.29  4082.0 2407.79
  4097.7 2408.29  5043.4 2411.10  5076.2 2410.02  5280.7 2411.47  5317.0 2410.28
  5500.9 2410.66  5529.7 2411.98  5894.9 2410.75  6630.1 2414.21  7954.3 2414.76
#Mann=6,-1,0
  1999.6   0.045       0  2920.6   0.035       0  3058.6    0.07       0
  3346.3   0.045       0  4081.5   0.045       0  4097.7   0.045       0
Bank Sta=4081.5,4097.7
Exp/Cntr=0.3,0.1

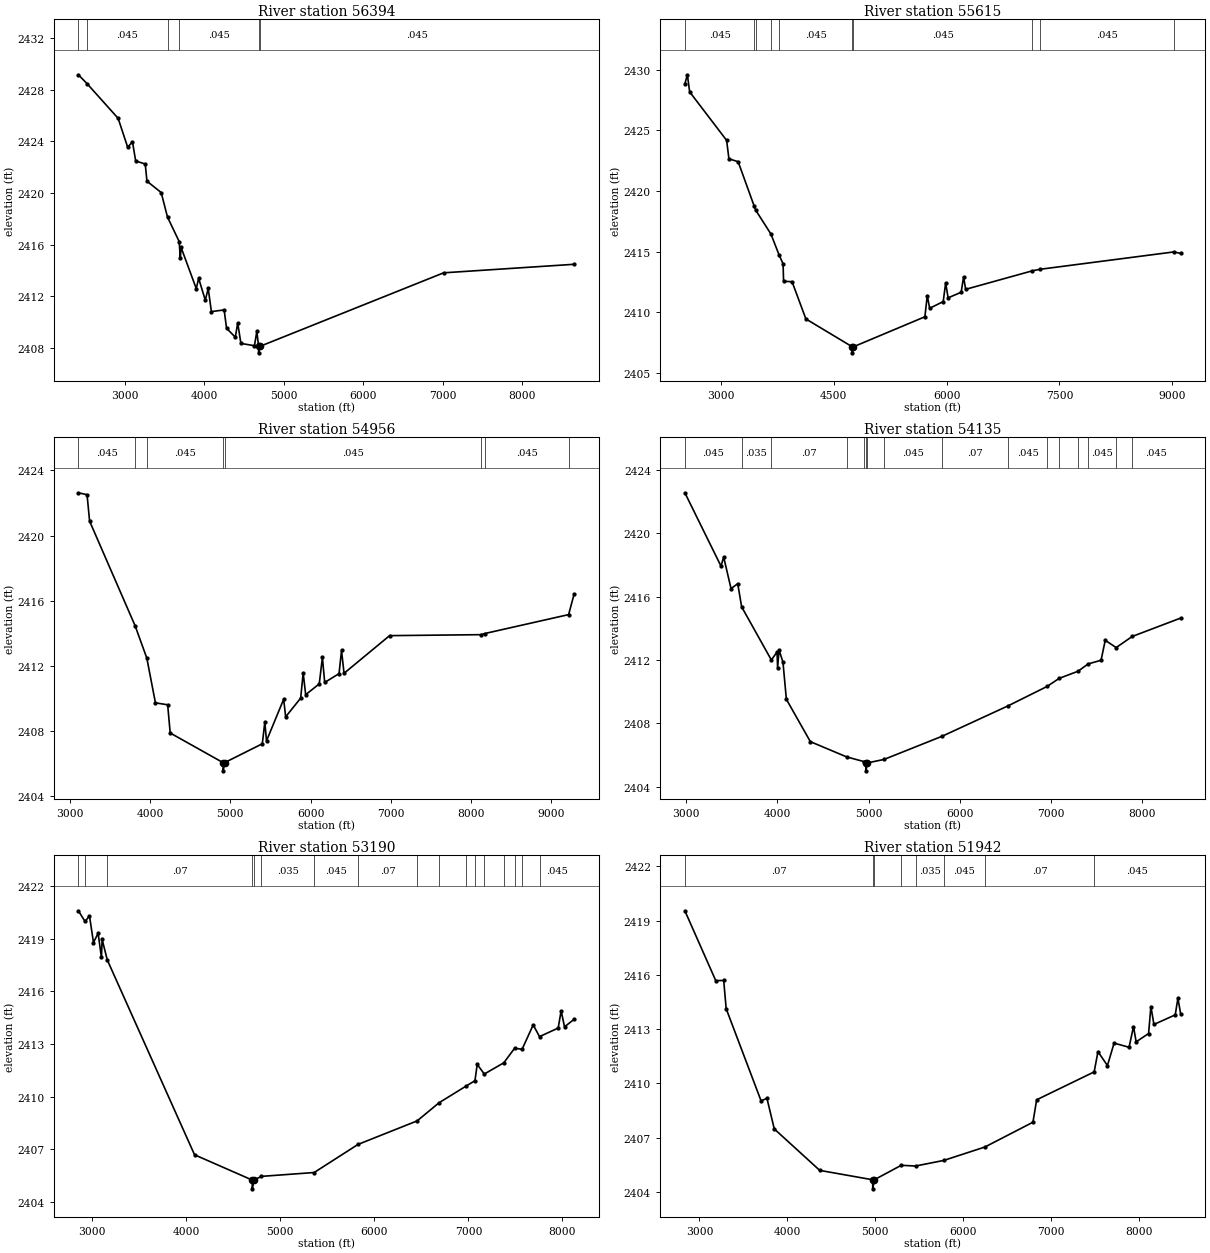
Type RM Length L Ch R = 1,56394,779,779,779
BEGIN DESCRIPTION:
Cottonwood Creek Trib01 27.4
END DESCRIPTION:
XS GIS Cut Line= 3
      1338891.67      6837226.56      1339068.76      6834626.15
      1340401.42      6831252.56
#Sta/Elev= 30
  2418.1 2429.14  2526.0 2428.46  2917.8 2425.77  3038.1 2423.53  3098.2 2423.96
  3138.3 2422.47  3258.6 2422.24  3280.1 2420.91  3459.1 2420.03  3538.6 2418.13
  3685.3 2416.24  3699.6 2414.94  3709.6 2415.78  3900.1 2412.60  3930.2 2413.39
  4013.9 2411.70  4050.4 2412.61  4090.5 2410.82  4250.9 2410.95  4281.0 2409.53
  4391.2 2408.84  4421.3 2409.94  4461.4 2408.36  4631.8 2408.18  4661.8 2409.29
  4683.7 2408.13  4684.2 2407.63  4700.2 2408.13  7010.6 2413.82  8651.8 2414.48
#Mann=6,-1,0
  2418.1    0.07       0  2526.0   0.045       0  3538.6   0.035       0
  3685.3   0.045       0  4683.7   0.045       0  4700.2   0.045       0
Bank Sta=4683.7,4700.2
Exp/Cntr=0.3,0.1

Type RM Length L Ch R = 1,55615,659,659,659
BEGIN DESCRIPTION:
Cottonwood Creek Trib01 27.3
END DESCRIPTION:
XS GIS Cut Line= 3
      1339115.37      6837310.43      1339637.31      6834887.12
      1340858.30      6830963.18
#Sta/Elev= 30
  2522.1 2428.82  2555.3 2429.57  2586.0 2428.16  3077.0 2424.17  3107.7 2422.65
  3230.4 2422.41  3443.0 2418.76  3463.4 2418.42  3665.3 2416.46  3775.1 2414.72
  3827.6 2414.00  3833.9 2412.56  3946.5 2412.53  4130.6 2409.46  4746.3 2407.17
  4746.8 2406.67  4762.8 2407.17  5711.9 2409.64  5743.6 2411.39  5775.1 2410.34
  5955.4 2410.89  5987.9 2412.42  6020.5 2411.20  6194.0 2411.66  6226.2 2412.92
  6253.5 2411.90  7137.2 2413.42  7241.0 2413.55  9019.3 2414.98  9110.5 2414.86
#Mann=10,-1,0
  2522.1   0.045       0  3443.0    0.07       0  3463.4   0.045       0
  3665.3   0.035       0  3775.1   0.045       0  4746.3   0.045       0
  4762.8   0.045       0  7137.2    0.07       0  7241.0   0.045       0
  9019.3   0.035       0
Bank Sta=4746.3,4762.8
Exp/Cntr=0.3,0.1

Type RM Length L Ch R = 1,54956,821,821,821
BEGIN DESCRIPTION:
Cottonwood Creek Trib01 27.2
END DESCRIPTION:
XS GIS Cut Line= 3
      1339516.13      6836946.98      1340121.97      6835138.77
      1341287.02      6831028.50
#Sta/Elev= 30
  3105.9 2422.62  3214.0 2422.50  3245.6 2420.88  3813.2 2414.46  3958.8 2412.48
  4066.1 2409.74  4218.6 2409.62  4250.2 2407.89  4910.5 2406.07  4911.0 2405.57
  4927.1 2406.07  5398.3 2407.23  5429.5 2408.56  5450.6 2407.41  5664.5 2409.96
  5689.3 2408.88  5876.4 2410.03  5907.6 2411.57  5938.8 2410.24  6108.0 2410.90
  6147.1 2412.52  6175.9 2410.99  6354.5 2411.53  6385.7 2412.95  6416.9 2411.55
  6984.6 2413.86  8128.2 2413.92  8172.0 2413.99  9216.1 2415.15  9285.1 2416.42
#Mann=8,-1,0
  3105.9   0.045       0  3813.2   0.035       0  3958.8   0.045       0
  4910.5   0.045       0  4927.1   0.045       0  8128.2    0.07       0
  8172.0   0.045       0  9216.1   0.035       0
Bank Sta=4910.5,4927.1
Exp/Cntr=0.3,0.1

Type RM Length L Ch R = 1,54135,945,945,945
BEGIN DESCRIPTION:
Cottonwood Creek Trib01 27.1
END DESCRIPTION:
XS GIS Cut Line= 3
      1339767.79      6837152.00      1340768.34      6835401.47
      1342452.09      6832417.20
#Sta/Elev= 30
  2983.7 2422.54  3379.9 2417.92  3410.0 2418.48  3490.7 2416.50  3564.2 2416.81
  3607.0 2415.35  3933.2 2412.00  3996.0 2412.50  4001.9 2411.50  4017.6 2412.63
  4060.7 2411.86  4098.2 2409.52  4361.6 2406.85  4759.3 2405.89  4952.2 2405.59
  4970.8 2405.51  4971.3 2405.01  4987.7 2405.51  5171.1 2405.73  5807.7 2407.19
  6536.7 2409.12  6960.1 2410.33  7093.4 2410.84  7300.8 2411.29  7410.9 2411.75
  7553.0 2411.98  7598.9 2413.24  7718.8 2412.78  7894.6 2413.48  8426.5 2414.64
#Mann=16,-1,0
  2983.7   0.045       0  3607.0   0.035       0  3933.2    0.07       0
  4759.3   0.045       0  4952.2   0.035       0  4970.8   0.035       0
  4987.7   0.035       0  5171.1   0.045       0  5807.7    0.07       0
  6536.7   0.045       0  6960.1    0.07       0  7093.4   0.045       0
  7300.8    0.07       0  7410.9   0.045       0  7718.8    0.07       0
  7894.6   0.045       0
Bank Sta=4970.8,4987.7
Exp/Cntr=0.3,0.1

Type RM Length L Ch R = 1,53190,1248,1248,1248
BEGIN DESCRIPTION:
Cottonwood Creek Trib01 27.0
END DESCRIPTION:
XS GIS Cut Line= 3
      1339972.88      6837142.63      1341492.08      6835604.79
      1342545.30      6832678.13
#Sta/Elev= 30
  2852.6 2420.59  2923.3 2419.98  2970.6 2420.30  3013.0 2418.78  3062.4 2419.31
  3097.8 2417.93  3104.9 2418.96  3159.7 2417.79  4087.8 2406.69  4701.3 2405.25
  4701.8 2404.75  4718.8 2405.25  4798.7 2405.46  5360.1 2405.68  5826.0 2407.28
  6454.6 2408.62  6687.0 2409.65  6973.9 2410.60  7069.5 2410.91  7093.9 2411.84
  7169.1 2411.29  7376.6 2411.93  7491.5 2412.76  7571.0 2412.70  7689.1 2414.09
  7756.2 2413.42  7954.8 2413.91  7986.1 2414.89  8022.2 2413.98  8124.7 2414.41
#Mann=17,-1,0
  2852.6   0.045       0  2923.3   0.035       0  3159.7    0.07       0
  4701.3   0.035       0  4718.8    0.07       0  4798.7   0.035       0
  5360.1   0.045       0  5826.0    0.07       0  6454.6   0.045       0
  6687.0    0.07       0  6973.9   0.045       0  7069.5    0.07       0
  7169.1   0.045       0  7376.6   0.035       0  7491.5   0.045       0
  7571.0   0.035       0  7756.2   0.045       0
Bank Sta=4701.3,4718.8
Exp/Cntr=0.3,0.1

Type RM Length L Ch R = 1,51942,855,855,855
BEGIN DESCRIPTION:
Cottonwood Creek Trib01 26.5
END DESCRIPTION:
XS GIS Cut Line= 3
      1340215.17      6837217.23      1342153.83      6836275.86
      1342647.81      6832827.29
#Sta/Elev= 30
  2834.5 2419.54  3186.0 2415.68  3276.3 2415.69  3304.4 2414.13  3701.4 2409.04
  3768.1 2409.18  3851.5 2407.49  4368.4 2405.20  4971.0 2404.68  4971.5 2404.18
  4988.6 2404.68  5295.6 2405.48  5458.3 2405.44  5779.5 2405.75  6247.0 2406.49
  6793.5 2407.86  6836.1 2409.10  7490.0 2410.64  7533.2 2411.76  7640.9 2410.99
  7716.6 2412.23  7886.8 2412.00  7937.3 2413.14  7967.6 2412.30  8109.0 2412.76
  8135.2 2414.25  8169.6 2413.26  8412.1 2413.79  8442.4 2414.71  8473.4 2413.86
#Mann=8,-1,0
  2834.5    0.07       0  4971.0    0.07       0  4988.6    0.07       0
  5295.6   0.045       0  5458.3   0.035       0  5779.5   0.045       0
  6247.0    0.07       0  7490.0   0.045       0
Bank Sta=4971,4988.6
Exp/Cntr=0.3,0.1

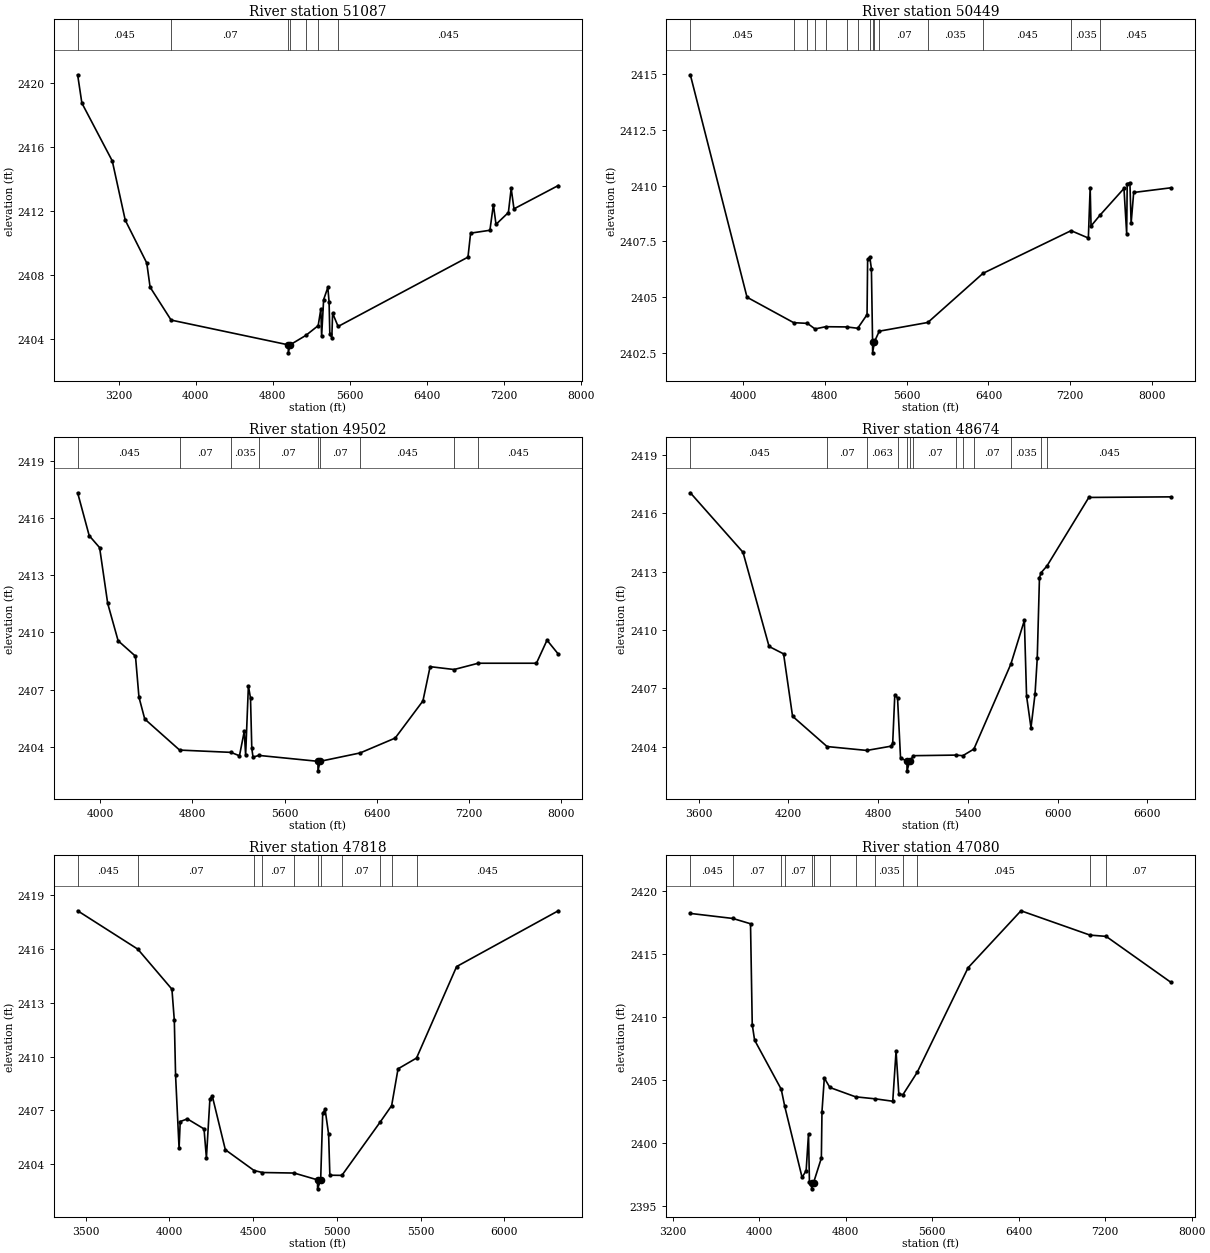
Type RM Length L Ch R = 1,51087,638,638,638
BEGIN DESCRIPTION:
Cottonwood Creek Trib01 26.0
END DESCRIPTION:
XS GIS Cut Line= 3
      1340634.64      6837636.63      1342685.09      6836760.53
      1344866.10      6835073.51
#Sta/Elev= 30
  2775.5 2420.51  2819.4 2418.74  3134.8 2415.12  3269.5 2411.41  3492.8 2408.73
  3527.3 2407.22  3745.3 2405.16  4961.1 2403.61  4961.6 2403.11  4979.5 2403.61
  5143.2 2404.20  5271.2 2404.81  5298.9 2405.85  5307.0 2404.14  5327.8 2406.44
  5371.3 2407.20  5384.4 2406.30  5392.1 2404.29  5412.9 2404.06  5421.1 2405.59
  5478.1 2404.76  6825.6 2409.10  6852.7 2410.60  7053.2 2410.78  7089.1 2412.38
  7116.4 2411.15  7244.8 2411.89  7273.8 2413.40  7302.8 2412.12  7762.6 2413.58
#Mann=7,-1,0
  2775.5   0.045       0  3745.3    0.07       0  4961.1    0.07       0
  4979.5    0.07       0  5143.2   0.035       0  5271.2   0.063       0
  5478.1   0.045       0
Bank Sta=4961.1,4979.5
Exp/Cntr=0.3,0.1

Type RM Length L Ch R = 1,50449,947,947,947
BEGIN DESCRIPTION:
Cottonwood Creek Trib01 25.5
END DESCRIPTION:
XS GIS Cut Line= 3
      1341109.91      6837720.54      1342591.89      6837282.47
      1345584.68      6836287.54
#Sta/Elev= 30
  3485.2 2414.96  4039.5 2405.00  4496.1 2403.86  4629.8 2403.83  4704.4 2403.58
  4808.5 2403.68  5013.2 2403.67  5121.9 2403.61  5213.0 2404.22  5218.7 2406.69
  5239.9 2406.80  5255.6 2406.27  5267.0 2403.01  5267.5 2402.51  5285.4 2403.01
  5332.5 2403.48  5807.5 2403.87  6346.6 2406.07  7207.7 2407.98  7376.6 2407.65
  7394.4 2409.91  7403.0 2408.19  7491.7 2408.68  7724.8 2409.87  7751.2 2407.85
  7756.5 2410.08  7782.9 2410.13  7794.8 2408.31  7819.8 2409.69  8184.4 2409.90
#Mann=15,-1,0
  3485.2   0.045       0  4496.1    0.07       0  4629.8   0.045       0
  4704.4    0.07       0  4808.5   0.045       0  5013.2    0.07       0
  5121.9   0.035       0  5239.9   0.063       0  5267.0   0.045       0
  5285.4   0.063       0  5332.5    0.07       0  5807.5   0.035       0
  6346.6   0.045       0  7207.7   0.035       0  7491.7   0.045       0
Bank Sta=5267,5285.4
Exp/Cntr=0.3,0.1

Type RM Length L Ch R = 1,49502,828,828,828
BEGIN DESCRIPTION:
Cottonwood Creek Trib01 25.0
END DESCRIPTION:
XS GIS Cut Line= 4
      1341175.19      6837934.90      1342330.92      6837832.38
      1343687.66      6838387.11      1345098.27      6839013.11
#Sta/Elev= 30
  3805.6 2417.33  3905.8 2415.08  3996.2 2414.45  4066.4 2411.52  4156.8 2409.56
  4307.4 2408.75  4337.5 2406.60  4387.7 2405.45  4690.3 2403.82  5135.7 2403.70
  5209.3 2403.52  5251.2 2404.81  5262.8 2403.55  5286.8 2407.19  5305.2 2406.55
  5316.2 2403.92  5326.8 2403.45  5377.5 2403.54  5890.1 2403.23  5890.6 2402.73
  5908.6 2403.23  6256.3 2403.67  6560.0 2404.45  6800.7 2406.40  6863.1 2408.20
  7071.1 2408.05  7280.4 2408.38  7785.3 2408.38  7877.2 2409.59  7974.9 2408.86
#Mann=9,-1,0
  3805.6   0.045       0  4690.3    0.07       0  5135.7   0.035       0
  5377.5    0.07       0  5890.1    0.07       0  5908.6    0.07       0
  6256.3   0.045       0  7071.1   0.035       0  7280.4   0.045       0
Bank Sta=5890.1,5908.6
Exp/Cntr=0.3,0.1

Type RM Length L Ch R = 1,48674,856,856,856
BEGIN DESCRIPTION:
Cottonwood Creek Trib01 24.0
END DESCRIPTION:
XS GIS Cut Line= 3
      1341221.82      6838009.48      1342638.49      6838447.53
      1343635.33      6839863.60
#Sta/Elev= 30
  3544.0 2417.06  3896.2 2414.00  4070.7 2409.15  4167.7 2408.77  4227.7 2405.56
  4458.5 2404.00  4724.5 2403.80  4887.1 2404.02  4897.6 2404.19  4911.6 2406.67
  4929.9 2406.50  4949.9 2403.41  4992.8 2403.25  4993.3 2402.75  5011.7 2403.25
  5036.2 2403.53  5318.2 2403.56  5366.6 2403.53  5440.4 2403.87  5688.0 2408.25
  5778.0 2410.49  5792.8 2406.60  5822.3 2404.97  5849.4 2406.70  5864.2 2408.54
  5879.0 2412.68  5889.1 2412.94  5929.0 2413.29  6209.2 2416.82  6758.6 2416.85
#Mann=13,-1,0
  3544.0   0.045       0  4458.5    0.07       0  4724.5   0.063       0
  4929.9   0.035       0  4992.8   0.035       0  5011.7   0.035       0
  5036.2    0.07       0  5318.2   0.035       0  5366.6   0.045       0
  5440.4    0.07       0  5688.0   0.035       0  5889.1    0.07       0
  5929.0   0.045       0
Bank Sta=4992.8,5011.7
Exp/Cntr=0.3,0.1

Type RM Length L Ch R = 1,47818,738,738,738
BEGIN DESCRIPTION:
Cottonwood Creek Trib01 23.0
END DESCRIPTION:
XS GIS Cut Line= 3
      1341287.04      6838121.32      1342442.76      6839146.56
      1343496.00      6839948.14
#Sta/Elev= 30
  3452.8 2418.13  3812.0 2415.99  4015.5 2413.76  4029.8 2412.02  4037.3 2408.95
  4058.2 2404.89  4065.0 2406.38  4107.5 2406.53  4207.1 2405.97  4221.3 2404.35
  4242.2 2407.64  4256.4 2407.80  4334.2 2404.81  4505.9 2403.65  4555.8 2403.54
  4744.9 2403.51  4884.3 2403.13  4884.8 2402.63  4903.2 2403.13  4915.4 2406.85
  4929.7 2407.06  4950.6 2405.67  4958.1 2403.39  5029.9 2403.38  5259.7 2406.37
  5326.8 2407.27  5365.0 2409.32  5475.3 2409.92  5714.5 2415.02  6321.3 2418.13
#Mann=11,-1,0
  3452.8   0.045       0  3812.0    0.07       0  4505.9   0.035       0
  4555.8    0.07       0  4744.9   0.035       0  4884.3   0.035       0
  4903.2   0.035       0  5029.9    0.07       0  5259.7   0.045       0
  5326.8    0.07       0  5475.3   0.045       0
Bank Sta=4884.3,4903.2
Exp/Cntr=0.3,0.1

Type RM Length L Ch R = 1,47080,880,880,880
BEGIN DESCRIPTION:
Cottonwood Creek Trib01 22.0
END DESCRIPTION:
XS GIS Cut Line= 3
      1341240.41      6838074.68      1342032.66      6839500.73
      1344679.70      6840460.75
#Sta/Elev= 30
  3361.5 2418.23  3755.2 2417.83  3918.4 2417.41  3934.4 2409.41  3956.1 2408.18
  4202.6 2404.28  4235.2 2402.92  4395.4 2397.29  4433.1 2397.82  4454.9 2400.75
  4463.5 2396.96  4483.1 2396.88  4483.6 2396.38  4502.1 2396.88  4573.9 2398.82
  4579.6 2402.51  4601.3 2405.17  4652.8 2404.42  4890.4 2403.68  5073.0 2403.52
  5234.4 2403.33  5265.0 2407.30  5290.3 2403.93  5327.8 2403.84  5460.3 2405.62
  5931.4 2413.92  6420.7 2418.44  7059.5 2416.51  7208.4 2416.41  7808.6 2412.76
#Mann=13,-1,0
  3361.5   0.045       0  3755.2    0.07       0  4202.6   0.035       0
  4235.2    0.07       0  4483.1    0.07       0  4502.1    0.07       0
  4652.8   0.035       0  4890.4    0.07       0  5073.0   0.035       0
  5327.8    0.07       0  5460.3   0.045       0  7059.5   0.035       0
  7208.4    0.07       0
Bank Sta=4483.1,4502.1
Exp/Cntr=0.3,0.1