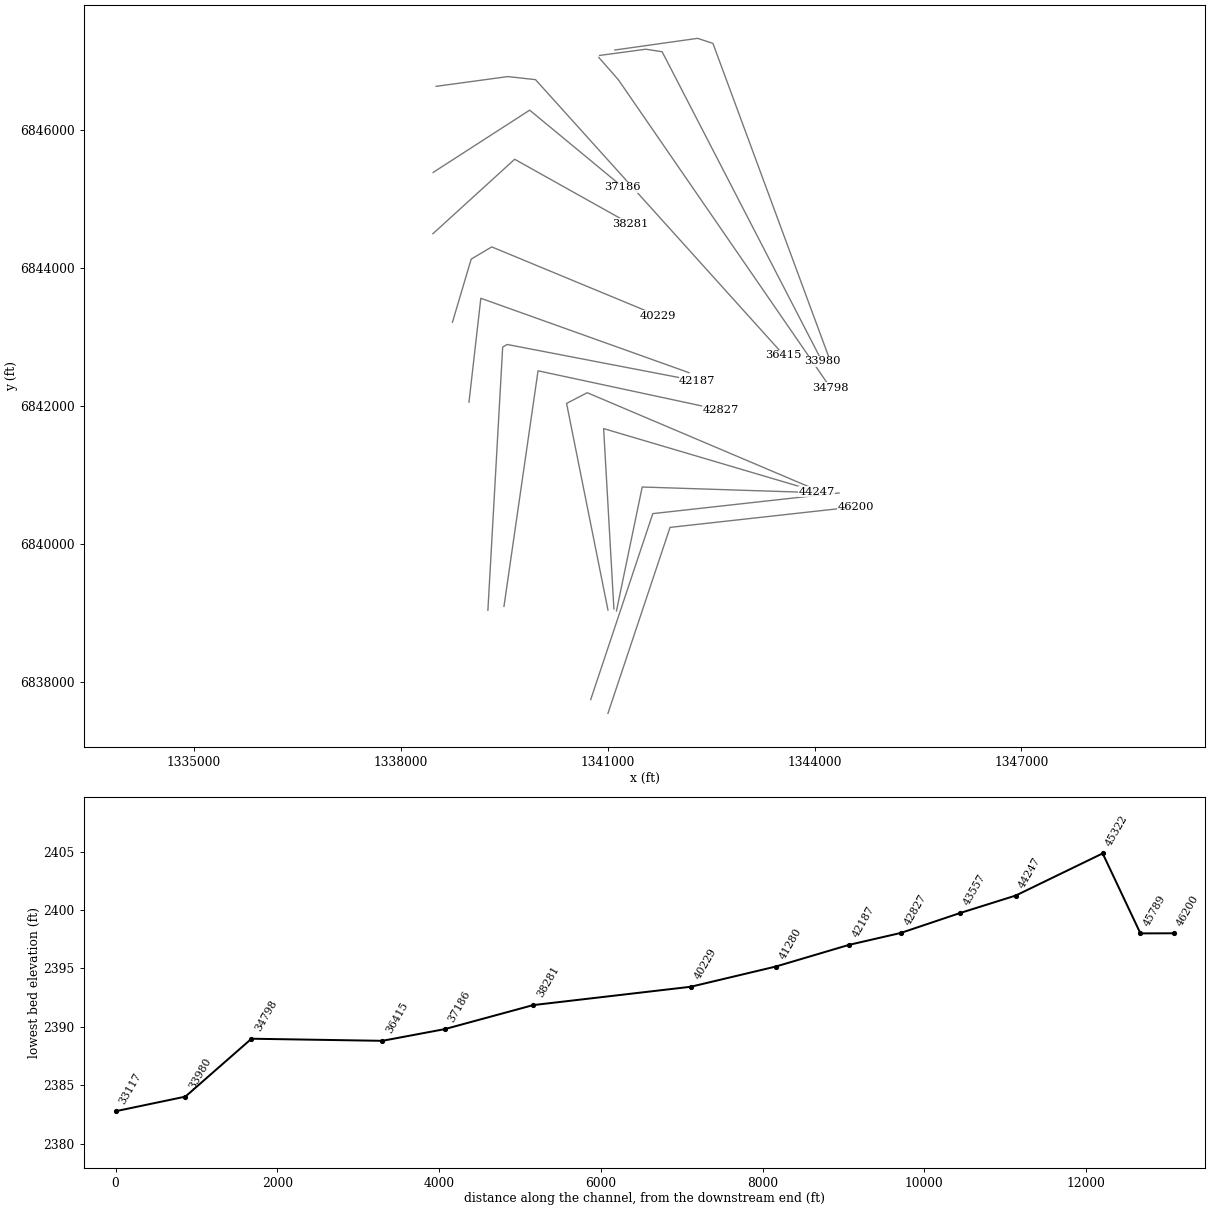
HEC-RAS study Cottonwood Creek Trib01.prj: Cottonwood Creek Trib01 Base Level Engineering

--- Cottonwood Creek Trib01.g01 (geometry) --- (continued)

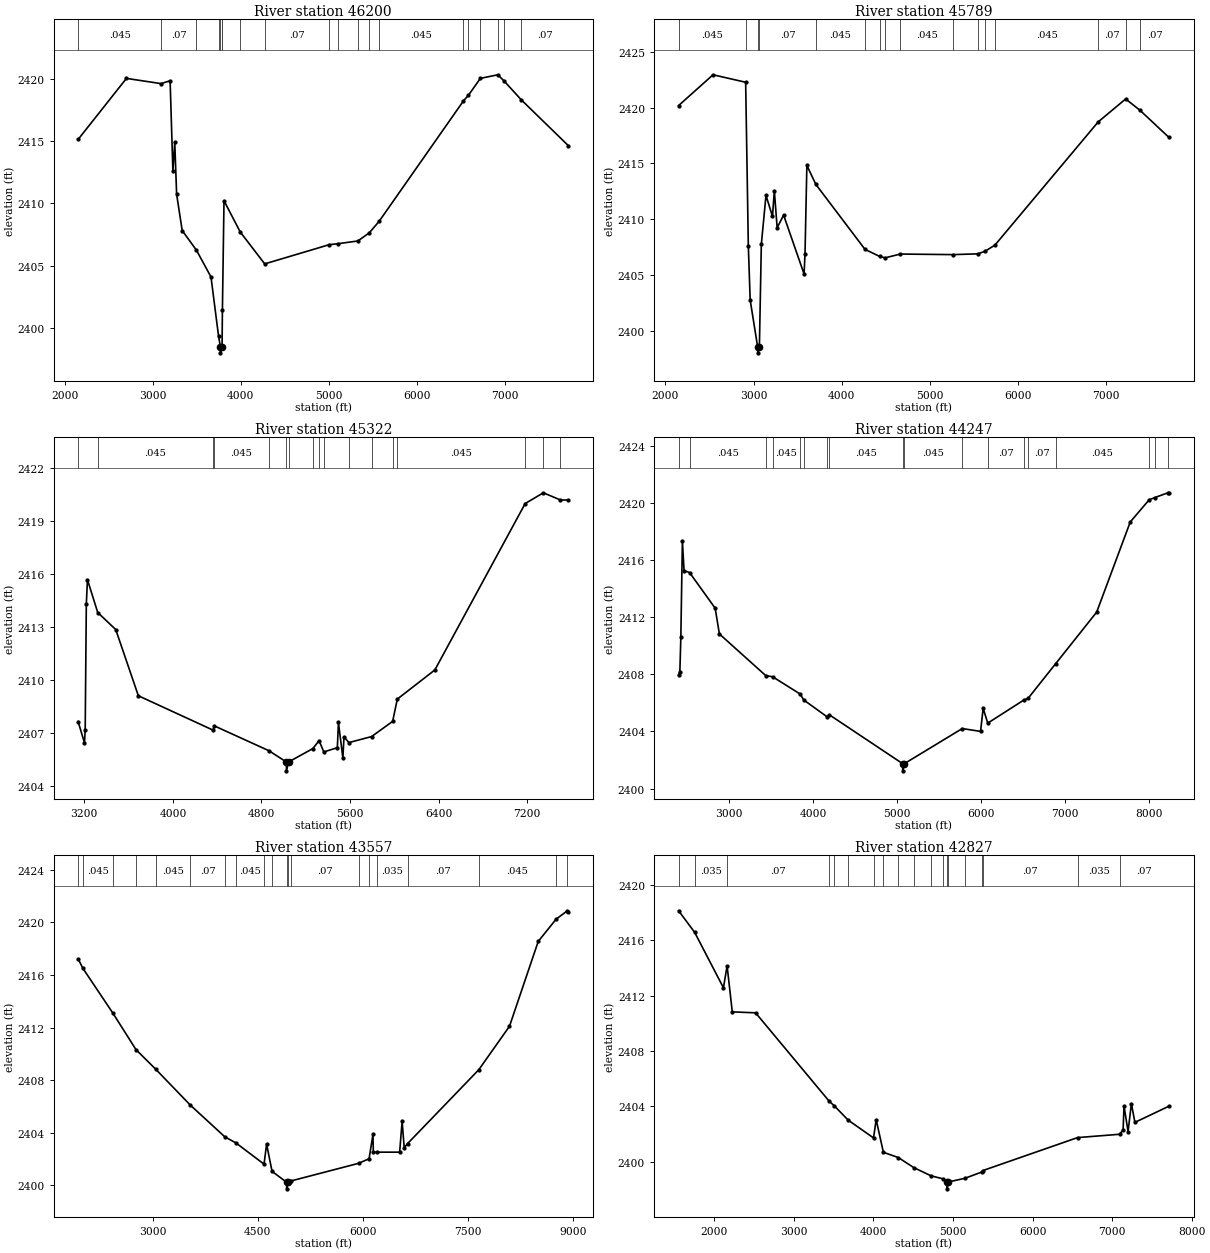
Type RM Length L Ch R = 1,46200,411,411,411
BEGIN DESCRIPTION:
Cottonwood Creek Trib01 21.0
END DESCRIPTION:
XS GIS Cut Line= 3
      1341005.00      6837537.99      1341905.00      6840238.00
      1344605.03      6840538.00
#Sta/Elev= 30
  2154.3 2415.14  2702.4 2420.04  3095.4 2419.62  3197.9 2419.85  3229.5 2412.57
  3250.6 2414.91  3271.6 2410.75  3334.9 2407.83  3496.5 2406.25  3661.7 2404.10
  3747.5 2399.34  3768.1 2398.51  3768.6 2398.01  3787.2 2398.51  3791.2 2401.45
  3809.2 2410.22  3992.6 2407.72  4270.9 2405.15  5002.2 2406.69  5101.9 2406.77
  5327.7 2406.99  5457.2 2407.64  5569.3 2408.57  6524.3 2418.22  6582.3 2418.69
  6717.7 2420.04  6915.6 2420.33  6990.8 2419.80  7180.1 2418.33  7717.0 2414.63
#Mann=20,-1,0
  2154.3   0.045       0  3095.4    0.07       0  3496.5    0.07       0
  3747.5   0.035       0  3768.1   0.045       0  3787.2   0.035       0
  3791.2    0.07       0  3992.6   0.045       0  4270.9    0.07       0
  5002.2    0.07       0  5101.9   0.035       0  5327.7   0.045       0
  5457.2    0.07       0  5569.3   0.045       0  6524.3    0.07       0
  6582.3   0.045       0  6717.7    0.07       0  6915.6   0.045       0
  6990.8   0.035       0  7180.1    0.07       0
Bank Sta=3768.1,3787.2
Exp/Cntr=0.3,0.1

Type RM Length L Ch R = 1,45789,467,467,467
BEGIN DESCRIPTION:
Cottonwood Creek Trib01 20.0
END DESCRIPTION:
XS GIS Cut Line= 3
      1340754.99      6837737.98      1341655.00      6840438.00
      1344355.02      6840738.00
#Sta/Elev= 30
  2149.6 2420.18  2539.6 2422.94  2909.9 2422.27  2940.2 2407.62  2961.3 2402.73
  3046.6 2398.50  3047.1 2398.00  3065.7 2398.50  3087.8 2407.73  3140.5 2412.12
  3214.3 2410.24  3235.3 2412.55  3267.0 2409.22  3340.7 2410.35  3572.6 2405.07
  3583.2 2406.85  3604.3 2414.81  3706.8 2413.10  4263.9 2407.28  4429.4 2406.65
  4491.6 2406.52  4664.3 2406.86  5262.5 2406.81  5545.6 2406.88  5627.5 2407.12
  5737.5 2407.66  6909.8 2418.72  7220.7 2420.77  7382.6 2419.76  7712.3 2417.32
#Mann=16,-1,0
  2149.6   0.045       0  2909.9    0.07       0  3046.6   0.045       0
  3065.7    0.07       0  3706.8   0.045       0  4263.9    0.07       0
  4429.4   0.045       0  4491.6    0.07       0  4664.3   0.045       0
  5262.5   0.035       0  5545.6   0.045       0  5627.5    0.07       0
  5737.5   0.045       0  6909.8    0.07       0  7220.7   0.035       0
  7382.6    0.07       0
Bank Sta=3046.6,3065.7
Exp/Cntr=0.3,0.1

Type RM Length L Ch R = 1,45322,1075,1075,1075
BEGIN DESCRIPTION:
Cottonwood Creek Trib01 19.2
END DESCRIPTION:
XS GIS Cut Line= 3
      1341128.59      6839025.42      1341501.40      6840824.24
      1344091.20      6840740.39
#Sta/Elev= 30
  3144.1 2407.64  3201.6 2406.43  3208.0 2407.19  3218.2 2414.29  3228.4 2415.67
  3321.3 2413.81  3483.7 2412.85  3688.0 2409.10  4364.1 2407.15  4372.2 2407.40
  4866.7 2405.99  5025.2 2405.35  5025.7 2404.85  5044.3 2405.35  5263.7 2406.11
  5320.1 2406.56  5362.8 2405.92  5485.0 2406.16  5495.0 2407.59  5535.0 2405.57
  5545.0 2406.77  5589.9 2406.45  5794.3 2406.79  5984.5 2407.65  6026.4 2408.91
  6365.5 2410.56  7181.3 2419.98  7345.6 2420.59  7500.2 2420.18  7572.3 2420.18
#Mann=17,-1,0
  3144.1    0.07       0  3321.3   0.045       0  4364.1    0.07       0
  4372.2   0.045       0  4866.7    0.07       0  5025.2    0.07       0
  5044.3    0.07       0  5263.7   0.045       0  5320.1    0.07       0
  5362.8   0.035       0  5589.9    0.07       0  5794.3   0.045       0
  5984.5    0.07       0  6026.4   0.045       0  7181.3    0.07       0
  7345.6   0.035       0  7500.2    0.07       0
Bank Sta=5025.2,5044.3
Exp/Cntr=0.3,0.1

Type RM Length L Ch R = 1,44247,690,690,690
BEGIN DESCRIPTION:
Cottonwood Creek Trib01 19.1
END DESCRIPTION:
XS GIS Cut Line= 3
      1341091.30      6839053.37      1340942.17      6841672.40
      1344027.22      6840759.00
#Sta/Elev= 30
  2399.6 2407.95  2414.3 2408.17  2425.9 2410.59  2444.3 2417.33  2464.3 2415.25
  2529.5 2415.12  2834.9 2412.62  2885.0 2410.82  3436.4 2407.91  3520.4 2407.82
  3848.3 2406.61  3889.4 2406.20  4166.0 2405.03  4195.4 2405.16  5068.4 2401.74
  5068.9 2401.24  5087.5 2401.74  5778.0 2404.20  5995.7 2404.00  6027.0 2405.61
  6081.7 2404.58  6515.5 2406.21  6561.7 2406.31  6890.4 2408.74  7379.2 2412.35
  7779.1 2418.66  8004.4 2420.21  8068.9 2420.36  8227.8 2420.70  8240.3 2420.66
#Mann=18,-1,0
  2399.6    0.07       0  2529.5   0.045       0  3436.4    0.07       0
  3520.4   0.045       0  3848.3    0.07       0  3889.4   0.045       0
  4166.0    0.07       0  4195.4   0.045       0  5068.4   0.045       0
  5087.5   0.045       0  5778.0   0.035       0  6081.7    0.07       0
  6515.5   0.045       0  6561.7    0.07       0  6890.4   0.045       0
  8004.4    0.07       0  8068.9   0.035       0  8227.8    0.07       0
Bank Sta=5068.4,5087.5
Exp/Cntr=0.3,0.1

Type RM Length L Ch R = 1,43557,730,730,730
BEGIN DESCRIPTION:
Cottonwood Creek Trib01 19.0
END DESCRIPTION:
XS GIS Cut Line= 4
      1341005.00      6839037.98      1340405.00      6842038.00
      1340704.58      6842193.32      1344024.61      6840782.85
#Sta/Elev= 30
  1936.4 2417.23  2005.9 2416.50  2431.1 2413.12  2762.9 2410.33  3046.3 2408.83
  3536.9 2406.12  4030.9 2403.70  4190.6 2403.23  4591.9 2401.62  4628.7 2403.14
  4706.4 2401.07  4914.8 2400.24  4915.3 2399.74  4934.0 2400.24  4977.0 2400.34
  5942.1 2401.68  6092.4 2402.03  6147.8 2403.88  6153.3 2402.52  6203.0 2402.53
  6528.9 2402.53  6564.3 2404.87  6594.1 2402.87  6642.1 2403.18  7659.4 2408.80
  8097.5 2412.10  8508.6 2418.56  8763.4 2420.25  8924.6 2420.89  8940.5 2420.82
#Mann=20,-1,0
  1936.4    0.07       0  2005.9   0.045       0  2431.1   0.045       0
  2762.9    0.07       0  3046.3   0.045       0  3536.9    0.07       0
  4030.9   0.045       0  4190.6   0.045       0  4591.9   0.035       0
  4706.4   0.045       0  4914.8    0.07       0  4934.0   0.045       0
  4977.0    0.07       0  5942.1   0.035       0  6092.4    0.07       0
  6203.0   0.035       0  6642.1    0.07       0  7659.4   0.045       0
  8763.4   0.035       0  8924.6    0.07       0
Bank Sta=4914.8,4934
Exp/Cntr=0.3,0.1

Type RM Length L Ch R = 1,42827,640,640,640
BEGIN DESCRIPTION:
Cottonwood Creek Trib01 18.6
END DESCRIPTION:
XS GIS Cut Line= 3
      1339497.51      6839090.68      1339991.49      6842511.24
      1342637.80      6841942.84
#Sta/Elev= 30
  1552.3 2418.12  1753.8 2416.56  2115.4 2412.56  2161.6 2414.14  2226.5 2410.82
  2519.5 2410.75  3444.0 2404.37  3509.5 2404.03  3683.3 2403.00  4001.6 2401.72
  4035.1 2403.03  4125.7 2400.68  4313.1 2400.30  4505.8 2399.58  4723.7 2398.98
  4869.7 2398.77  4924.7 2398.54  4925.2 2398.04  4943.9 2398.54  5148.9 2398.80
  5365.4 2399.26  5376.2 2399.36  6565.5 2401.74  7093.1 2401.98  7138.5 2402.30
  7149.6 2404.03  7200.7 2402.18  7242.4 2404.19  7286.7 2402.84  7715.0 2404.01
#Mann=19,-1,0
  1552.3    0.07       0  1753.8   0.035       0  2161.6    0.07       0
  3444.0   0.045       0  3509.5    0.07       0  3683.3   0.045       0
  4001.6   0.035       0  4125.7   0.045       0  4313.1    0.07       0
  4505.8   0.045       0  4723.7    0.07       0  4869.7   0.045       0
  4924.7   0.045       0  4943.9   0.045       0  5148.9    0.07       0
  5365.4   0.045       0  5376.2    0.07       0  6565.5   0.035       0
  7093.1    0.07       0
Bank Sta=4924.7,4943.9
Exp/Cntr=0.3,0.1

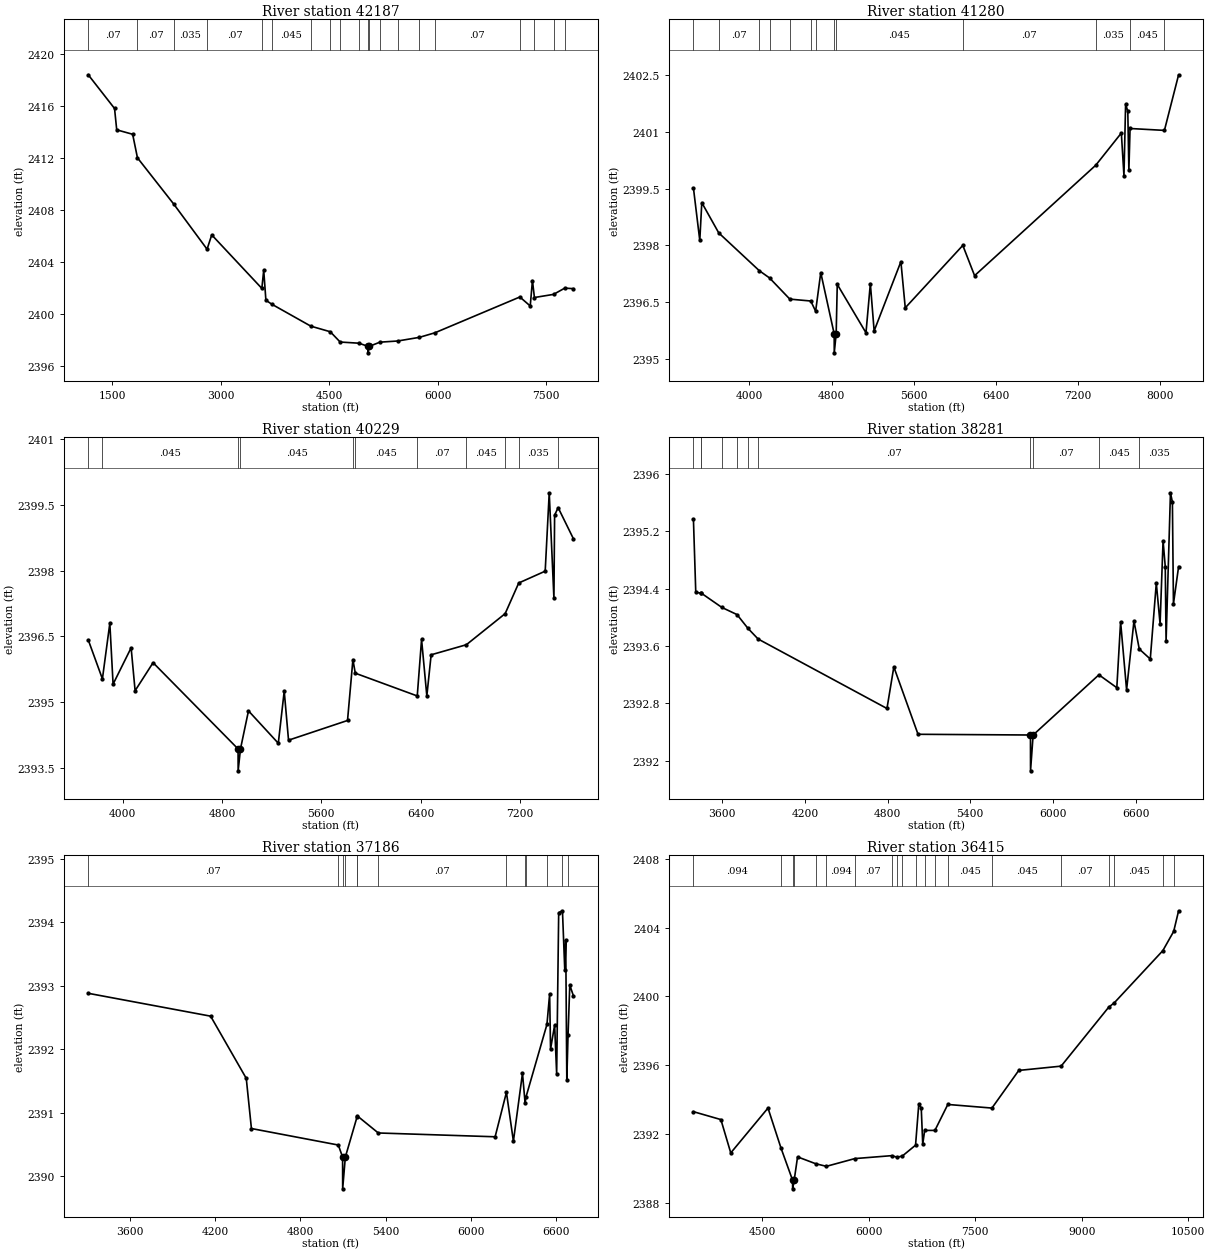
Type RM Length L Ch R = 1,42187,907,907,907
BEGIN DESCRIPTION:
Cottonwood Creek Trib01 18.5
END DESCRIPTION:
XS GIS Cut Line= 4
      1339264.49      6839034.70      1339478.86      6842856.09
      1339544.11      6842893.37      1342301.50      6842362.39
#Sta/Elev= 30
  1167.6 2418.38  1531.5 2415.79  1561.5 2414.15  1781.9 2413.81  1848.3 2412.00
  2349.9 2408.45  2811.1 2404.98  2875.7 2406.08  3568.8 2401.97  3594.7 2403.37
  3624.8 2401.06  3705.1 2400.76  4246.0 2399.07  4515.3 2398.64  4652.1 2397.85
  4912.2 2397.76  5036.2 2397.52  5036.7 2397.02  5055.4 2397.52  5201.9 2397.84
  5448.8 2397.93  5747.9 2398.21  5962.3 2398.56  7137.3 2401.31  7280.9 2400.62
  7311.5 2402.57  7338.8 2401.27  7602.9 2401.51  7758.0 2401.99  7878.2 2401.95
#Mann=20,-1,0
  1167.6    0.07       0  1848.3    0.07       0  2349.9   0.035       0
  2811.1    0.07       0  3568.8   0.035       0  3705.1   0.045       0
  4246.0   0.045       0  4515.3    0.07       0  4652.1   0.045       0
  4912.2    0.07       0  5036.2    0.07       0  5055.4    0.07       0
  5201.9   0.045       0  5448.8    0.07       0  5747.9   0.045       0
  5962.3    0.07       0  7137.3   0.035       0  7338.8   0.045       0
  7602.9    0.07       0  7758.0   0.045       0
Bank Sta=5036.2,5055.4
Exp/Cntr=0.3,0.1

Type RM Length L Ch R = 1,41280,1051,1051,1051
BEGIN DESCRIPTION:
Cottonwood Creek Trib01 18.4
END DESCRIPTION:
XS GIS Cut Line= 3
      1338990.27      6842056.54      1339161.97      6843564.45
      1342180.86      6842483.61
#Sta/Elev= 30
  3455.2 2399.52  3517.1 2398.13  3536.7 2399.13  3701.8 2398.33  4097.2 2397.33
  4196.1 2397.14  4393.8 2396.58  4597.7 2396.53  4645.1 2396.26  4695.0 2397.28
  4825.9 2395.66  4826.4 2395.16  4845.1 2395.66  4855.7 2396.97  5135.4 2395.69
  5177.9 2396.99  5214.8 2395.74  5475.3 2397.57  5517.8 2396.35  6078.2 2398.00
  6192.9 2397.20  7372.9 2400.12  7621.8 2400.97  7647.3 2399.84  7663.3 2401.73
  7684.6 2401.55  7695.2 2399.98  7706.7 2401.09  8041.3 2401.04  8179.4 2402.51
#Mann=13,-1,0
  3455.2   0.035       0  3701.8    0.07       0  4097.2   0.045       0
  4196.1    0.07       0  4393.8   0.045       0  4597.7    0.07       0
  4645.1   0.045       0  4825.9   0.045       0  4845.1   0.045       0
  6078.2    0.07       0  7372.9   0.035       0  7706.7   0.045       0
  8041.3    0.07       0
Bank Sta=4825.9,4845.1
Exp/Cntr=0.3,0.1

Type RM Length L Ch R = 1,40229,1948,1948,1948
BEGIN DESCRIPTION:
Cottonwood Creek Trib01 18.3
END DESCRIPTION:
XS GIS Cut Line= 4
      1338750.68      6843216.23      1339022.16      6844132.99
      1339320.42      6844310.08      1341724.85      6843312.89
#Sta/Elev= 30
  3723.9 2396.42  3838.0 2395.53  3897.7 2396.80  3923.9 2395.41  4069.2 2396.24
  4101.2 2395.26  4245.9 2395.90  4930.2 2393.93  4930.7 2393.43  4949.5 2393.93
  5013.9 2394.80  5254.0 2394.06  5301.7 2395.25  5336.4 2394.13  5811.3 2394.58
  5854.7 2395.97  5873.7 2395.66  6372.7 2395.14  6407.4 2396.43  6449.8 2395.14
  6484.5 2396.08  6768.1 2396.31  7080.4 2397.02  7189.7 2397.72  7402.7 2397.99
  7435.2 2399.78  7473.0 2397.37  7478.5 2399.27  7507.0 2399.44  7629.9 2398.73
#Mann=11,-1,0
  3723.9   0.035       0  3838.0   0.045       0  4930.2   0.045       0
  4949.5   0.045       0  5854.7    0.07       0  5873.7   0.045       0
  6372.7    0.07       0  6768.1   0.045       0  7080.4    0.07       0
  7189.7   0.035       0  7507.0   0.045       0
Bank Sta=4930.2,4949.5
Exp/Cntr=0.3,0.1

Type RM Length L Ch R = 1,38281,1095,1095,1095
BEGIN DESCRIPTION:
Cottonwood Creek Trib01 18.2
END DESCRIPTION:
XS GIS Cut Line= 3
      1338467.52      6844501.51      1339652.45      6845582.27
      1341324.27      6844645.64
#Sta/Elev= 30
  3391.5 2395.37  3408.5 2394.35  3447.3 2394.34  3448.0 2394.34  3597.9 2394.14
  3708.0 2394.04  3786.3 2393.85  3860.4 2393.70  4795.7 2392.73  4845.5 2393.31
  5021.1 2392.37  5836.8 2392.36  5837.3 2391.86  5856.1 2392.36  6333.4 2393.20
  6463.3 2393.02  6490.7 2393.94  6534.2 2392.99  6587.7 2393.95  6626.1 2393.56
  6706.1 2393.42  6749.8 2394.48  6777.2 2393.91  6798.9 2395.07  6814.8 2394.71
  6820.7 2393.67  6852.5 2395.74  6866.6 2395.61  6874.2 2394.19  6911.6 2394.71
#Mann=11,-1,0
  3391.5   0.035       0  3447.3   0.045       0  3448.0    0.07       0
  3597.9   0.045       0  3708.0    0.07       0  3786.3   0.045       0
  3860.4    0.07       0  5836.8    0.07       0  5856.1    0.07       0
  6333.4   0.045       0  6626.1   0.035       0
Bank Sta=5836.8,5856.1
Exp/Cntr=0.3,0.1

Type RM Length L Ch R = 1,37186,771,771,771
BEGIN DESCRIPTION:
Cottonwood Creek Trib01 18.1
END DESCRIPTION:
XS GIS Cut Line= 3
      1338470.51      6845391.17      1339870.32      6846295.33
      1341220.88      6845177.63
#Sta/Elev= 30
  3304.8 2392.88  4167.3 2392.52  4418.6 2391.54  4454.9 2390.75  5067.4 2390.49
  5097.5 2390.30  5098.0 2389.80  5116.8 2390.30  5199.0 2390.93  5200.5 2390.95
  5349.0 2390.68  6172.5 2390.62  6252.2 2391.32  6301.3 2390.55  6365.3 2391.62
  6383.8 2391.15  6389.2 2391.24  6537.8 2392.39  6556.7 2392.87  6563.2 2392.00
  6591.9 2392.38  6606.2 2391.61  6620.5 2394.15  6647.1 2394.18  6663.5 2393.24
  6670.0 2393.72  6677.7 2391.52  6686.4 2392.22  6698.7 2393.01  6724.3 2392.84
#Mann=13,-1,0
  3304.8    0.07       0  5067.4   0.063       0  5097.5    0.07       0
  5116.8   0.063       0  5199.0   0.094       0  5200.5   0.063       0
  5349.0    0.07       0  6252.2   0.094       0  6383.8   0.063       0
  6389.2   0.094       0  6537.8   0.063       0  6647.1   0.094       0
  6686.4   0.035       0
Bank Sta=5097.5,5116.8
Exp/Cntr=0.3,0.1

Type RM Length L Ch R = 1,36415,1617,1617,1617
BEGIN DESCRIPTION:
Cottonwood Creek Trib01 18.0
END DESCRIPTION:
XS GIS Cut Line= 4
      1338513.94      6846641.19      1339554.59      6846782.86
      1339955.00      6846738.00      1343554.99      6842738.01
#Sta/Elev= 30
  3530.4 2393.29  3917.2 2392.83  4056.3 2390.89  4580.6 2393.50  4765.1 2391.16
  4927.4 2389.30  4927.9 2388.80  4949.6 2389.30  4997.4 2390.66  5253.4 2390.26
  5403.3 2390.11  5804.0 2390.56  6320.7 2390.73  6402.3 2390.64  6473.6 2390.71
  6659.4 2391.34  6704.5 2393.71  6739.6 2393.51  6760.6 2391.40  6787.9 2392.20
  6932.2 2392.20  7113.9 2393.71  7735.3 2393.50  8113.4 2395.69  8710.1 2395.94
  9378.4 2399.36  9460.1 2399.63 10142.8 2402.66 10295.7 2403.78 10365.0 2404.98
#Mann=20,-1,0
  3530.4   0.094       0  4765.1   0.094       0  4927.4    0.07       0
  4949.6   0.094       0  5253.4   0.063       0  5403.3   0.094       0
  5804.0    0.07       0  6320.7   0.035       0  6402.3   0.094       0
  6473.6   0.035       0  6659.4   0.063       0  6787.9   0.063       0
  6932.2   0.045       0  7113.9   0.045       0  7735.3   0.045       0
  8710.1    0.07       0  9378.4    0.07       0  9460.1   0.045       0
 10142.8    0.07       0 10295.7   0.045       0
Bank Sta=4927.4,4949.6
Exp/Cntr=0.3,0.1

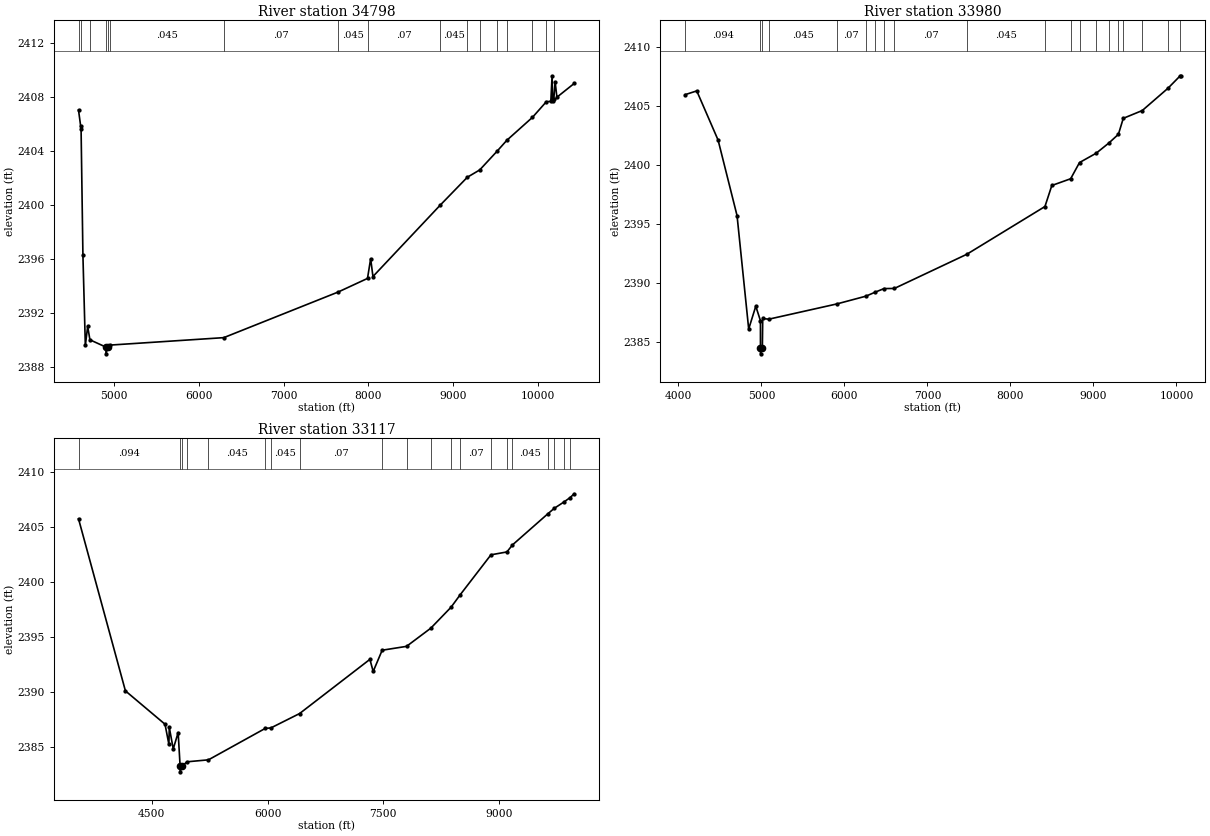
Type RM Length L Ch R = 1,34798,818,818,818
BEGIN DESCRIPTION:
Cottonwood Creek Trib01 17.0
END DESCRIPTION:
XS GIS Cut Line= 3
      1340873.16      6847059.35      1341155.00      6846738.00
      1344228.10      6842268.85
#Sta/Elev= 30
  4577.2 2407.05  4603.1 2405.84  4607.5 2405.64  4629.3 2396.27  4657.8 2389.60
  4685.4 2391.02  4711.9 2390.02  4900.8 2389.48  4901.3 2388.98  4923.5 2389.48
  4953.6 2389.63  6291.7 2390.18  7641.6 2393.56  7988.7 2394.57  8025.9 2396.03
  8053.0 2394.71  8844.0 2399.98  9167.3 2402.07  9313.1 2402.61  9517.1 2403.99
  9633.8 2404.81  9936.2 2406.51 10100.2 2407.67 10152.9 2407.69 10167.8 2409.59
 10174.6 2407.75 10187.9 2407.85 10203.6 2409.15 10224.6 2408.00 10428.4 2409.02
#Mann=17,-1,0
  4577.2   0.125       0  4603.1   0.094       0  4711.9   0.035       0
  4900.8   0.045       0  4923.5   0.035       0  4953.6   0.045       0
  6291.7    0.07       0  7641.6   0.045       0  7988.7    0.07       0
  8844.0   0.045       0  9167.3    0.07       0  9313.1   0.045       0
  9517.1    0.07       0  9633.8   0.045       0  9936.2    0.07       0
 10100.2   0.035       0 10187.9    0.07       0
Bank Sta=4900.8,4923.5
Exp/Cntr=0.3,0.1

Type RM Length L Ch R = 1,33980,863,863,863
BEGIN DESCRIPTION:
Cottonwood Creek Trib01 16.27
END DESCRIPTION:
XS GIS Cut Line= 4
      1340884.41      6847089.73      1341554.56      6847180.01
      1341790.33      6847143.49      1344108.77      6842648.57
#Sta/Elev= 30
  4078.3 2405.94  4220.2 2406.26  4477.4 2402.10  4705.8 2395.71  4846.0 2386.12
  4931.5 2388.05  4987.7 2386.82  4987.9 2384.52  4988.4 2384.02  5010.7 2384.52
  5015.2 2387.01  5087.3 2386.95  5907.7 2388.24  6259.4 2388.90  6368.1 2389.23
  6476.7 2389.54  6601.1 2389.55  7473.9 2392.44  8415.7 2396.48  8498.6 2398.26
  8725.6 2398.83  8832.2 2400.20  9033.1 2400.99  9185.6 2401.85  9300.9 2402.59
  9359.6 2403.94  9588.4 2404.60  9897.4 2406.48 10045.9 2407.54 10050.7 2407.49
#Mann=20,-1,0
  4078.3   0.094       0  4987.9    0.07       0  5010.7   0.094       0
  5087.3   0.045       0  5907.7    0.07       0  6259.4   0.045       0
  6368.1    0.07       0  6476.7   0.045       0  6601.1    0.07       0
  7473.9   0.045       0  8415.7    0.07       0  8725.6   0.045       0
  8832.2    0.07       0  9033.1   0.045       0  9185.6    0.07       0
  9300.9   0.045       0  9359.6    0.07       0  9588.4   0.045       0
  9897.4    0.07       0 10045.9   0.045       0
Bank Sta=4987.9,5010.7
Exp/Cntr=0.3,0.1

Type RM Length L Ch R = 1,33117,830,830,830
BEGIN DESCRIPTION:
Cottonwood Creek Trib01 16.26
END DESCRIPTION:
XS GIS Cut Line= 4
      1341104.73      6847168.43      1342304.56      6847337.99
      1342526.65      6847264.66      1344249.82      6842594.35
#Sta/Elev= 30
  3550.2 2405.74  4158.0 2390.12  4671.5 2387.09  4721.6 2385.26  4726.7 2386.80
  4778.0 2384.85  4841.5 2386.34  4867.1 2383.27  4867.6 2382.77  4889.9 2383.27
  4955.3 2383.68  5234.3 2383.86  5969.6 2386.71  6044.5 2386.76  6415.3 2388.06
  7326.6 2392.98  7369.2 2391.88  7485.6 2393.81  7801.3 2394.16  8115.8 2395.81
  8378.0 2397.71  8497.5 2398.85  8895.5 2402.47  9102.1 2402.73  9174.6 2403.37
  9630.5 2406.18  9715.9 2406.69  9840.5 2407.26  9922.6 2407.67  9973.9 2408.01
#Mann=20,-1,0
  3550.2   0.094       0  4867.1   0.045       0  4889.9   0.094       0
  4955.3   0.045       0  5234.3   0.045       0  5969.6    0.07       0
  6044.5   0.045       0  6415.3    0.07       0  7485.6   0.045       0
  7801.3    0.07       0  8115.8   0.045       0  8378.0   0.045       0
  8497.5    0.07       0  8895.5   0.045       0  9102.1    0.07       0
  9174.6   0.045       0  9630.5    0.07       0  9715.9   0.045       0
  9840.5    0.07       0  9922.6   0.035       0
Bank Sta=4867.1,4889.9
Exp/Cntr=0.3,0.1