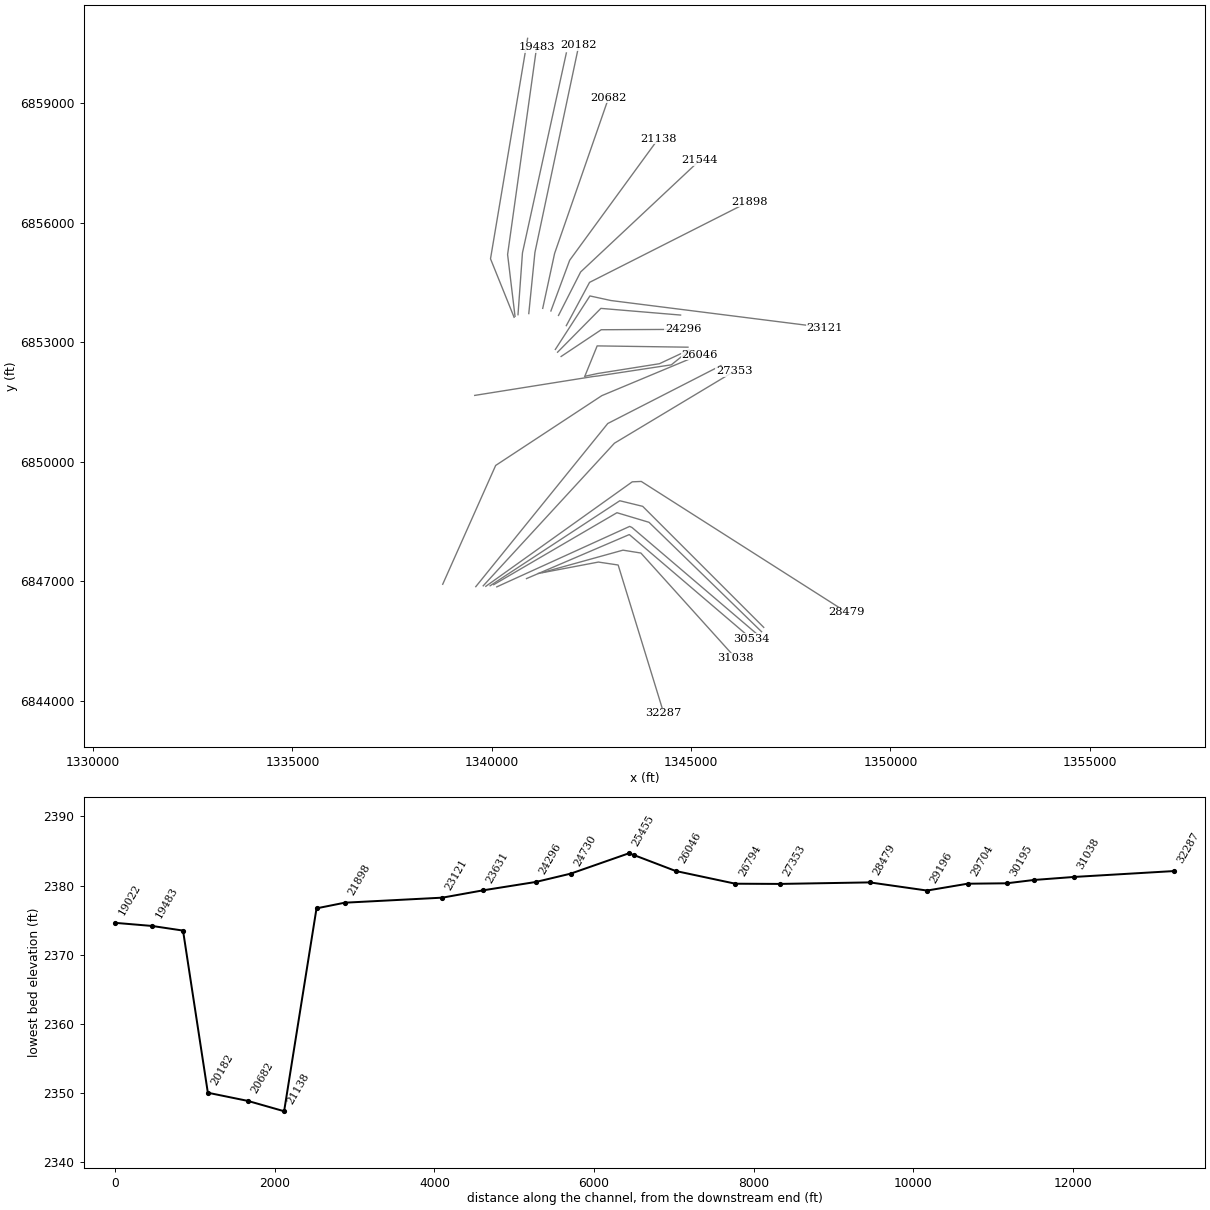
HEC-RAS study Cottonwood Creek Trib01.prj: Cottonwood Creek Trib01 Base Level Engineering

--- Cottonwood Creek Trib01.g01 (geometry) --- (continued)

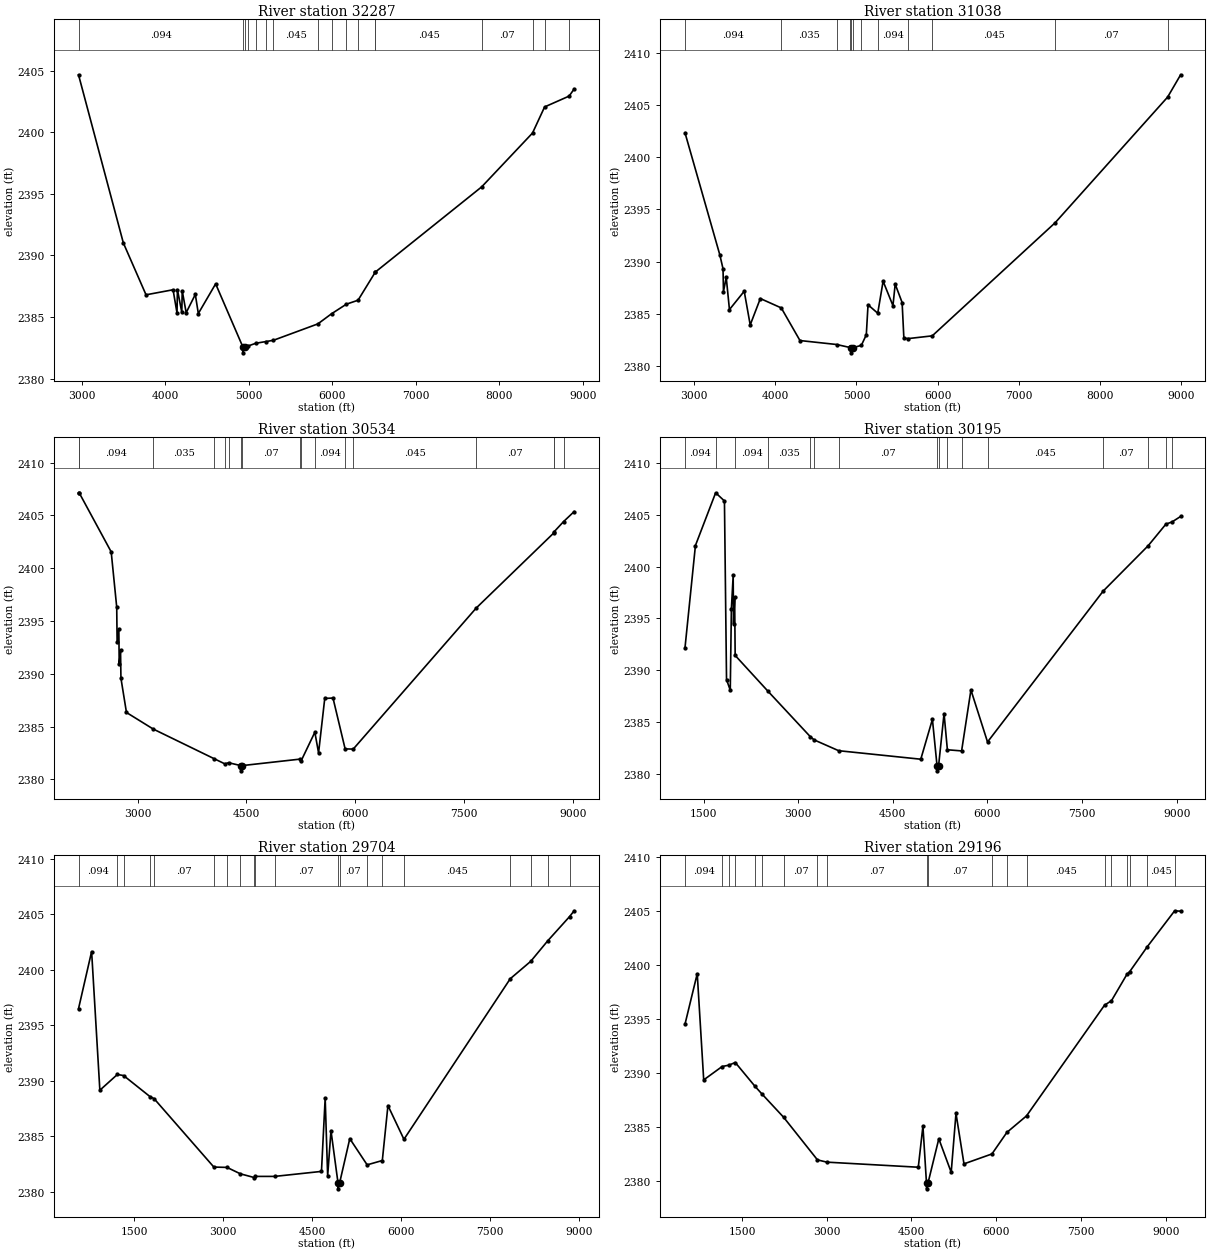
Type RM Length L Ch R = 1,32287,1249,1249,1249
BEGIN DESCRIPTION:
Cottonwood Creek Trib01 16.25
END DESCRIPTION:
XS GIS Cut Line= 4
      1341166.57      6847192.17      1342674.35      6847478.62
      1343169.76      6847404.46      1344314.37      6843681.21
#Sta/Elev= 30
  2964.0 2404.66  3500.5 2391.01  3771.9 2386.80  4095.5 2387.21  4142.6 2385.33
  4147.7 2387.22  4199.9 2385.38  4205.0 2387.13  4252.2 2385.35  4361.7 2386.83
  4397.6 2385.28  4604.9 2387.69  4929.2 2382.59  4929.7 2382.09  4952.1 2382.59
  4986.4 2382.63  5086.9 2382.87  5210.4 2383.01  5296.7 2383.11  5828.1 2384.44
  5991.3 2385.26  6169.4 2386.04  6308.7 2386.36  6516.1 2388.65  6516.4 2388.65
  7787.9 2395.56  8396.4 2399.93  8541.2 2402.05  8834.7 2402.93  8894.9 2403.51
#Mann=17,-1,0
  2964.0   0.094       0  4929.2    0.07       0  4952.1   0.094       0
  4986.4    0.07       0  5086.9   0.045       0  5210.4    0.07       0
  5296.7   0.045       0  5828.1    0.07       0  5991.3   0.045       0
  6169.4    0.07       0  6308.7   0.045       0  6516.1    0.07       0
  6516.4   0.045       0  7787.9    0.07       0  8396.4   0.045       0
  8541.2    0.07       0  8834.7   0.045       0
Bank Sta=4929.2,4952.1
Exp/Cntr=0.3,0.1

Type RM Length L Ch R = 1,31038,504,504,504
BEGIN DESCRIPTION:
Cottonwood Creek Trib01 16.24
END DESCRIPTION:
XS GIS Cut Line= 4
      1341271.38      6847217.03      1343290.92      6847777.28
      1343739.83      6847705.04      1346116.12      6845068.33
#Sta/Elev= 30
  2889.7 2402.36  3318.6 2390.64  3358.1 2389.30  3363.3 2387.12  3397.6 2388.47
  3437.0 2385.39  3618.7 2387.15  3692.5 2383.92  3817.1 2386.45  4074.8 2385.55
  4304.8 2382.42  4755.5 2382.04  4916.4 2381.76  4936.1 2381.74  4936.6 2381.24
  4960.3 2381.74  5060.5 2381.96  5121.3 2382.97  5142.5 2385.85  5262.0 2385.04
  5328.0 2388.11  5449.2 2385.77  5476.8 2387.83  5562.0 2386.07  5583.7 2382.64
  5640.1 2382.61  5932.8 2382.87  7445.1 2393.72  8829.7 2405.78  8989.7 2407.92
#Mann=12,-1,0
  2889.7   0.094       0  4074.8   0.035       0  4755.5   0.094       0
  4916.4   0.035       0  4936.1   0.035       0  4960.3   0.035       0
  5060.5   0.063       0  5262.0   0.094       0  5640.1    0.07       0
  5932.8   0.045       0  7445.1    0.07       0  8829.7   0.045       0
Bank Sta=4936.1,4960.3
Exp/Cntr=0.3,0.1

Type RM Length L Ch R = 1,30534,339,339,339
BEGIN DESCRIPTION:
Cottonwood Creek Trib01 16.23
END DESCRIPTION:
XS GIS Cut Line= 3
      1340871.02      6847063.69      1343449.37      6848168.74
      1346506.77      6845556.59
#Sta/Elev= 30
  2187.4 2407.15  2199.6 2407.11  2637.5 2401.55  2713.6 2396.31  2719.1 2393.02
  2742.6 2394.20  2748.1 2390.91  2766.2 2392.21  2771.7 2389.58  2847.8 2386.33
  3216.3 2384.76  4055.6 2381.95  4203.3 2381.46  4253.7 2381.57  4420.9 2381.30
  4421.4 2380.80  4445.1 2381.30  5238.0 2381.91  5254.5 2381.76  5442.5 2384.46
  5493.6 2382.50  5578.7 2387.66  5692.3 2387.70  5859.4 2382.88  5971.0 2382.86
  7665.2 2396.23  8734.3 2403.35  8738.3 2403.46  8868.1 2404.42  9013.9 2405.37
#Mann=17,-1,0
  2187.4   0.125       0  2199.6   0.094       0  3216.3   0.035       0
  4055.6    0.07       0  4203.3   0.035       0  4253.7    0.07       0
  4420.9    0.07       0  4445.1    0.07       0  5238.0   0.035       0
  5254.5   0.063       0  5442.5   0.094       0  5859.4    0.07       0
  5971.0   0.045       0  7665.2    0.07       0  8734.3   0.035       0
  8738.3   0.045       0  8868.1   0.035       0
Bank Sta=4420.9,4445.1
Exp/Cntr=0.3,0.1

Type RM Length L Ch R = 1,30195,491,491,491
BEGIN DESCRIPTION:
Cottonwood Creek Trib01 16.22
END DESCRIPTION:
XS GIS Cut Line= 4
      1340125.59      6846855.93      1343458.69      6848373.79
      1343517.65      6848345.43      1346658.63      6845665.14
#Sta/Elev= 30
  1205.0 2392.16  1370.7 2402.03  1691.1 2407.11  1830.7 2406.32  1863.6 2389.12
  1922.9 2388.08  1940.5 2395.90  1969.0 2399.15  1974.5 2394.49  1992.1 2397.04
  2000.5 2391.44  2520.6 2387.99  3190.2 2383.62  3252.9 2383.30  3641.1 2382.26
  4942.9 2381.44  5127.3 2385.28  5200.5 2380.82  5201.0 2380.32  5225.4 2380.82
  5311.8 2385.84  5364.6 2382.35  5590.1 2382.24  5737.8 2388.11  6001.0 2383.10
  7834.5 2397.64  8547.6 2402.01  8828.7 2404.09  8925.7 2404.30  9062.0 2404.83
#Mann=16,-1,0
  1205.0   0.094       0  1691.1   0.125       0  2000.5   0.094       0
  2520.6   0.035       0  3190.2    0.07       0  3252.9   0.035       0
  3641.1    0.07       0  5200.5    0.07       0  5225.4    0.07       0
  5364.6   0.063       0  5590.1   0.094       0  6001.0   0.045       0
  7834.5    0.07       0  8547.6   0.035       0  8828.7   0.045       0
  8925.7    0.07       0
Bank Sta=5200.5,5225.4
Exp/Cntr=0.3,0.1

Type RM Length L Ch R = 1,29704,508,508,508
BEGIN DESCRIPTION:
Cottonwood Creek Trib01 16.21
END DESCRIPTION:
XS GIS Cut Line= 4
      1340049.18      6846911.47      1343139.48      6848717.04
      1343943.35      6848476.32      1346767.19      6845730.19
#Sta/Elev= 30
   565.0 2396.48   786.0 2401.63   924.9 2389.14  1220.5 2390.56  1325.4 2390.46
  1776.4 2388.54  1837.9 2388.39  2847.1 2382.22  3068.9 2382.19  3295.1 2381.61
  3526.5 2381.28  3547.0 2381.38  3872.8 2381.38  4661.4 2381.83  4724.0 2388.43
  4765.8 2381.43  4821.8 2385.50  4941.2 2380.76  4941.7 2380.26  4966.1 2380.76
  5138.9 2384.78  5431.5 2382.42  5687.4 2382.81  5782.3 2387.76  6052.0 2384.72
  7844.6 2399.18  8190.3 2400.75  8477.3 2402.60  8843.6 2404.77  8922.2 2405.30
#Mann=20,-1,0
   565.0   0.094       0  1220.5   0.094       0  1325.4   0.125       0
  1776.4   0.035       0  1837.9    0.07       0  2847.1   0.035       0
  3068.9    0.07       0  3295.1   0.035       0  3526.5    0.07       0
  3547.0   0.035       0  3872.8    0.07       0  4941.2    0.07       0
  4966.1    0.07       0  5431.5   0.035       0  5687.4   0.094       0
  6052.0   0.045       0  7844.6    0.07       0  8190.3   0.035       0
  8477.3   0.045       0  8843.6    0.07       0
Bank Sta=4941.2,4966.1
Exp/Cntr=0.3,0.1

Type RM Length L Ch R = 1,29196,717,717,717
BEGIN DESCRIPTION:
Cottonwood Creek Trib01 16.20
END DESCRIPTION:
XS GIS Cut Line= 4
      1339958.95      6846883.73      1343211.00      6849017.22
      1343784.90      6848877.09      1346820.73      6845839.41
#Sta/Elev= 30
   490.9 2394.50   707.9 2399.18   822.4 2389.35  1148.9 2390.59  1265.1 2390.71
  1381.3 2390.96  1729.9 2388.76  1846.1 2388.09  2237.7 2385.89  2836.1 2381.95
  3002.8 2381.74  4621.2 2381.27  4703.5 2385.08  4766.7 2379.77  4767.2 2379.27
  4791.6 2379.77  4984.6 2383.90  5203.9 2380.80  5288.7 2386.26  5430.1 2381.58
  5925.4 2382.50  6189.2 2384.49  6537.3 2386.02  7917.9 2396.26  8041.5 2396.68
  8316.2 2399.13  8364.6 2399.37  8673.2 2401.66  9160.4 2405.00  9265.7 2404.96
#Mann=20,-1,0
   490.9   0.094       0  1148.9   0.125       0  1265.1   0.094       0
  1381.3   0.125       0  1729.9   0.035       0  1846.1    0.07       0
  2237.7    0.07       0  2836.1   0.035       0  3002.8    0.07       0
  4766.7    0.07       0  4791.6    0.07       0  5925.4   0.035       0
  6189.2   0.094       0  6537.3   0.045       0  7917.9    0.07       0
  8041.5   0.045       0  8316.2    0.07       0  8364.6   0.035       0
  8673.2   0.045       0  9160.4    0.07       0
Bank Sta=4766.7,4791.6
Exp/Cntr=0.3,0.1

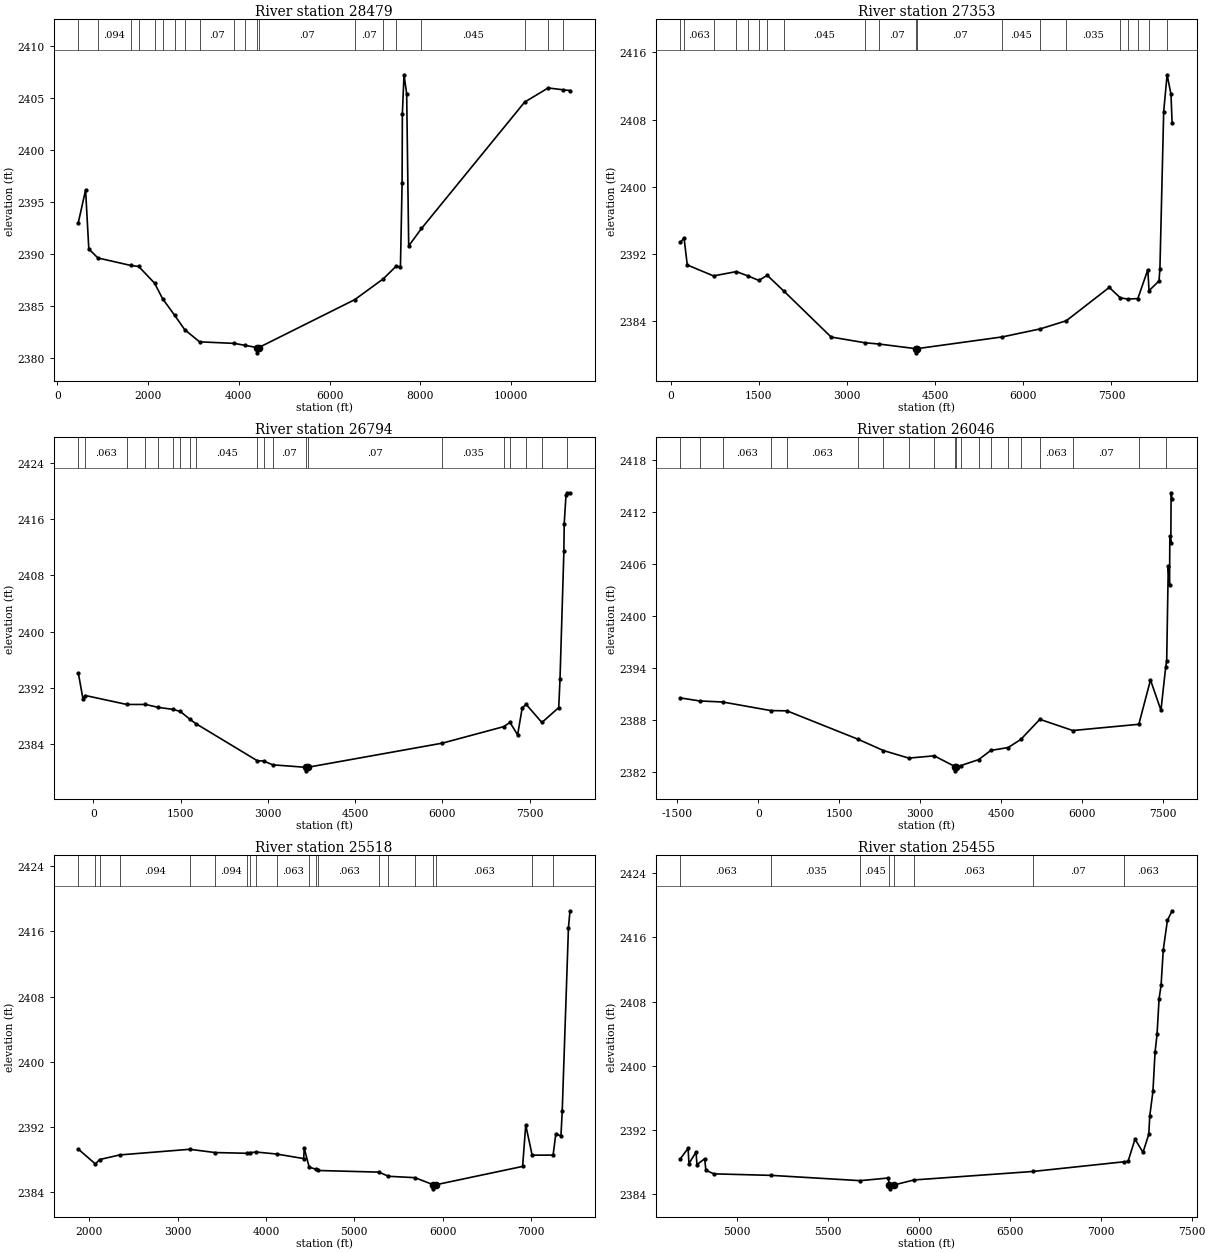
Type RM Length L Ch R = 1,28479,1126,1126,1126
BEGIN DESCRIPTION:
Cottonwood Creek Trib01 16.19
END DESCRIPTION:
XS GIS Cut Line= 4
      1339850.40      6846869.38      1343523.93      6849492.24
      1343749.82      6849501.58      1348890.09      6846223.00
#Sta/Elev= 30
   462.4 2393.00   622.6 2396.14   693.9 2390.45   895.0 2389.59  1617.9 2388.87
  1793.3 2388.77  2144.0 2387.16  2319.3 2385.67  2583.3 2384.08  2809.7 2382.67
  3135.3 2381.51  3898.9 2381.36  4140.3 2381.17  4410.2 2380.95  4410.7 2380.45
  4435.1 2380.95  6553.0 2385.57  7184.2 2387.58  7465.8 2388.79  7562.1 2388.73
  7598.4 2396.78  7604.4 2403.46  7640.8 2407.24  7699.2 2405.42  7744.0 2390.75
  8025.9 2392.43 10299.6 2404.61 10817.6 2405.97 11136.2 2405.80 11299.1 2405.72
#Mann=20,-1,0
   462.4   0.094       0   895.0   0.094       0  1617.9   0.063       0
  1793.3   0.035       0  2144.0   0.035       0  2319.3    0.07       0
  2583.3   0.035       0  2809.7   0.045       0  3135.3    0.07       0
  3898.9   0.045       0  4140.3    0.07       0  4410.2    0.07       0
  4435.1    0.07       0  6553.0    0.07       0  7184.2   0.035       0
  7465.8   0.094       0  8025.9   0.045       0 10299.6   0.045       0
 10817.6    0.07       0 11136.2   0.045       0
Bank Sta=4410.2,4435.1
Exp/Cntr=0.3,0.1

Type RM Length L Ch R = 1,27353,559,559,559
BEGIN DESCRIPTION:
Cottonwood Creek Trib01 16.18
END DESCRIPTION:
XS GIS Cut Line= 3
      1339785.33      6846882.42      1343076.55      6850461.57
      1346081.36      6852267.69
#Sta/Elev= 30
   164.8 2393.38   226.4 2393.91   281.5 2390.69   727.9 2389.39  1116.7 2389.90
  1316.8 2389.38  1500.2 2388.85  1642.0 2389.46  1925.6 2387.58  2730.4 2382.11
  3305.4 2381.43  3542.4 2381.28  4167.4 2380.73  4167.9 2380.23  4194.8 2380.73
  5645.8 2382.13  6288.4 2383.08  6732.8 2384.05  7463.8 2388.02  7652.9 2386.77
  7781.9 2386.63  7949.8 2386.69  8119.7 2390.12  8140.5 2387.63  8310.1 2388.78
  8325.6 2390.22  8389.7 2408.92  8447.7 2413.33  8513.9 2411.03  8533.0 2407.61
#Mann=20,-1,0
   164.8   0.094       0   226.4   0.063       0   727.9   0.094       0
  1116.7   0.125       0  1316.8   0.094       0  1500.2   0.035       0
  1642.0   0.035       0  1925.6   0.045       0  3305.4   0.045       0
  3542.4    0.07       0  4167.4    0.07       0  4194.8    0.07       0
  5645.8   0.045       0  6288.4    0.07       0  6732.8   0.035       0
  7652.9   0.035       0  7781.9   0.063       0  7949.8   0.063       0
  8140.5   0.035       0  8447.7   0.094       0
Bank Sta=4167.4,4194.8
Exp/Cntr=0.3,0.1

Type RM Length L Ch R = 1,26794,748,748,748
BEGIN DESCRIPTION:
Cottonwood Creek Trib01 16.17
END DESCRIPTION:
XS GIS Cut Line= 3
      1339599.32      6846861.40      1342908.78      6850955.55
      1345746.38      6852409.58
#Sta/Elev= 30
  -259.8 2394.15  -179.9 2390.47  -139.0 2390.95   573.5 2389.68   894.3 2389.68
  1113.6 2389.27  1363.2 2388.98  1492.0 2388.70  1663.0 2387.55  1762.8 2386.95
  2818.3 2381.69  2929.6 2381.65  3083.3 2381.11  3653.5 2380.76  3654.0 2380.26
  3681.0 2380.76  5998.3 2384.19  7052.1 2386.53  7161.7 2387.13  7292.6 2385.36
  7372.1 2389.22  7440.9 2389.68  7709.8 2387.12  7999.1 2389.23  8021.3 2393.27
  8087.9 2411.40  8093.5 2415.33  8124.1 2419.34  8148.2 2419.72  8193.1 2419.72
#Mann=20,-1,0
  -259.8   0.094       0  -139.0   0.063       0   573.5   0.094       0
   894.3   0.063       0  1113.6   0.094       0  1363.2    0.07       0
  1492.0    0.07       0  1663.0   0.035       0  1762.8   0.045       0
  2818.3    0.07       0  2929.6   0.045       0  3083.3    0.07       0
  3653.5    0.07       0  3681.0    0.07       0  5998.3   0.035       0
  7052.1   0.094       0  7161.7   0.063       0  7440.9   0.094       0
  7709.8   0.035       0  8148.2   0.094       0
Bank Sta=3653.5,3681
Exp/Cntr=0.3,0.1

Type RM Length L Ch R = 1,26046,528,528,528
BEGIN DESCRIPTION:
Cottonwood Creek Trib01 16.16
END DESCRIPTION:
XS GIS Cut Line= 4
      1338769.68      6846921.44      1340097.82      6849903.24
      1342759.66      6851654.58      1345214.67      6852680.83
#Sta/Elev= 30
 -1444.6 2390.51 -1088.7 2390.16  -662.3 2390.04   229.4 2389.05   529.9 2389.02
  1844.4 2385.75  2317.7 2384.44  2786.5 2383.57  3259.3 2383.83  3641.5 2382.60
  3642.0 2382.10  3669.0 2382.60  3747.1 2382.70  4081.0 2383.39  4305.9 2384.45
  4629.9 2384.79  4862.7 2385.72  5215.9 2388.04  5826.5 2386.75  7050.6 2387.47
  7266.1 2392.58  7460.4 2389.08  7548.3 2394.09  7566.5 2394.76  7595.7 2405.70
  7619.5 2403.49  7624.9 2409.13  7643.3 2408.36  7648.7 2414.17  7666.8 2413.47
#Mann=20,-1,0
 -1444.6   0.035       0 -1088.7   0.063       0  -662.3   0.063       0
   229.4   0.094       0   529.9   0.063       0  1844.4   0.094       0
  2317.7   0.063       0  2786.5   0.063       0  3259.3    0.07       0
  3641.5    0.07       0  3669.0    0.07       0  3747.1   0.035       0
  4081.0   0.035       0  4305.9   0.094       0  4629.9   0.063       0
  4862.7   0.094       0  5215.9   0.063       0  5826.5    0.07       0
  7050.6   0.063       0  7548.3   0.094       0
Bank Sta=3641.5,3669
Exp/Cntr=0.3,0.1

Type RM Length L Ch R = 1,25518,63,63,63
BEGIN DESCRIPTION:
Cottonwood Creek Trib01 16.15
END DESCRIPTION:
XS GIS Cut Line= 5
      1339572.28      6851660.86      1342540.63      6852134.59
      1342661.79      6852148.57      1344502.58      6852428.18
      1344949.97      6852787.02
#Sta/Elev= 30
  1877.6 2389.30  2070.8 2387.48  2118.2 2388.02  2346.0 2388.59  3137.8 2389.28
  3424.9 2388.88  3783.7 2388.79  3818.3 2388.87  3890.9 2388.94  4120.2 2388.70
  4428.2 2388.14  4433.3 2389.43  4489.6 2387.09  4570.9 2386.82  4590.8 2386.68
  5280.6 2386.48  5385.6 2385.97  5685.9 2385.80  5895.2 2384.93  5895.7 2384.43
  5922.7 2384.93  6904.8 2387.18  6940.0 2392.25  7012.7 2388.56  7249.8 2388.57
  7280.9 2391.21  7338.5 2390.90  7352.9 2393.97  7423.3 2416.44  7440.9 2418.53
#Mann=20,-1,0
  1877.6   0.125       0  2070.8   0.094       0  2118.2   0.125       0
  2346.0   0.094       0  3137.8   0.125       0  3424.9   0.094       0
  3783.7   0.125       0  3818.3   0.063       0  3890.9   0.125       0
  4120.2   0.063       0  4489.6   0.094       0  4570.9   0.035       0
  4590.8   0.063       0  5280.6    0.07       0  5385.6   0.035       0
  5685.9   0.063       0  5895.2   0.063       0  5922.7   0.063       0
  7012.7    0.07       0  7249.8   0.063       0
Bank Sta=5895.2,5922.7
Exp/Cntr=0.3,0.1

Type RM Length L Ch R = 1,25455,725,725,725
BEGIN DESCRIPTION:
Cottonwood Creek Trib01 16.14
END DESCRIPTION:
XS GIS Cut Line= 4
      1342349.52      6852143.90      1342647.81      6852209.15
      1344204.32      6852456.14      1344949.94      6852805.65
#Sta/Elev= 30
  4687.6 2388.41  4729.6 2389.70  4734.7 2387.81  4773.5 2389.23  4778.6 2387.67
  4821.2 2388.41  4827.6 2386.97  4871.5 2386.52  5187.4 2386.33  5676.5 2385.67
  5830.5 2386.00  5837.7 2385.15  5838.2 2384.65  5865.2 2385.15  5972.9 2385.76
  6628.2 2386.82  7126.0 2388.02  7150.0 2388.06  7188.2 2390.85  7232.3 2389.20
  7264.1 2391.45  7269.7 2393.78  7287.0 2396.81  7298.6 2401.69  7309.6 2403.92
  7320.8 2408.36  7331.7 2410.02  7343.7 2414.44  7366.5 2418.12  7392.4 2419.33
#Mann=8,-1,0
  4687.6   0.063       0  5187.4   0.035       0  5676.5   0.045       0
  5837.7   0.063       0  5865.2   0.045       0  5972.9   0.063       0
  6628.2    0.07       0  7126.0   0.063       0
Bank Sta=5837.7,5865.2
Exp/Cntr=0.3,0.1

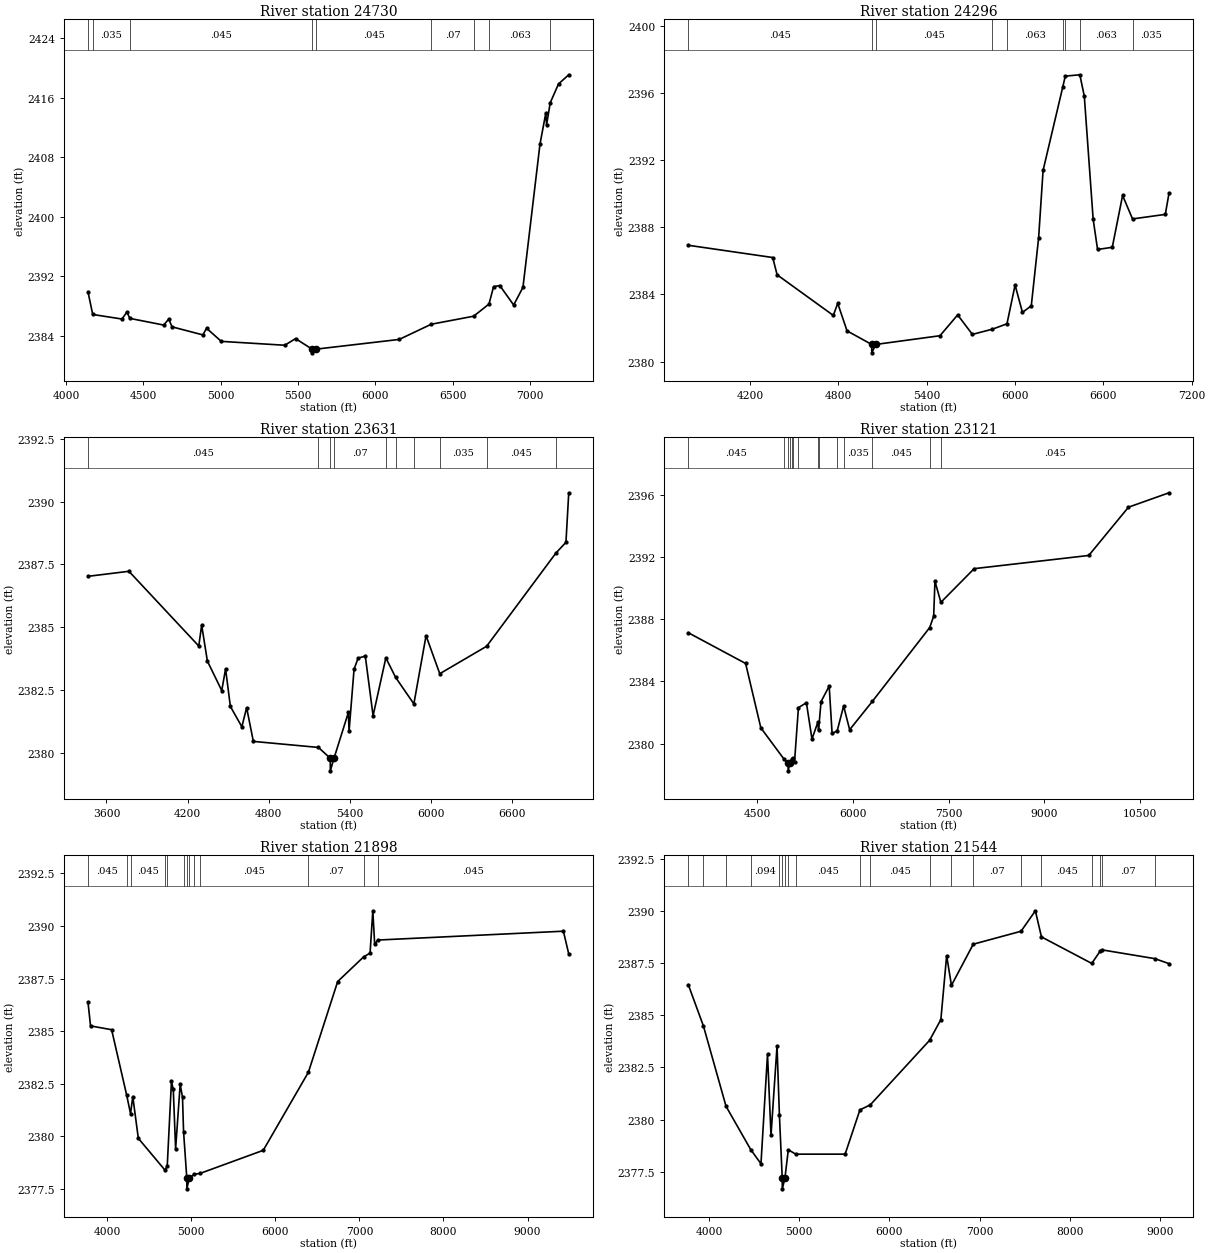
Type RM Length L Ch R = 1,24730,434,434,434
BEGIN DESCRIPTION:
Cottonwood Creek Trib01 16.13
END DESCRIPTION:
XS GIS Cut Line= 3
      1342330.90      6852134.54      1342643.15      6852903.52
      1344920.96      6852870.92
#Sta/Elev= 30
  4142.6 2389.89  4173.1 2386.87  4362.2 2386.26  4394.6 2387.21  4412.5 2386.35
  4632.0 2385.45  4664.4 2386.25  4686.0 2385.21  4885.0 2384.13  4909.1 2385.02
  5004.2 2383.26  5414.5 2382.74  5484.5 2383.63  5590.7 2382.22  5591.2 2381.72
  5618.2 2382.22  6154.5 2383.52  6361.6 2385.56  6635.9 2386.64  6734.9 2388.27
  6764.6 2390.60  6804.6 2390.76  6894.6 2388.14  6954.6 2390.52  7064.6 2409.73
  7102.3 2413.92  7107.3 2412.35  7131.1 2415.31  7184.6 2417.83  7250.6 2419.06
#Mann=9,-1,0
  4142.6   0.063       0  4173.1   0.035       0  4412.5   0.045       0
  5590.7   0.045       0  5618.2   0.045       0  6361.6    0.07       0
  6635.9   0.094       0  6734.9   0.063       0  7131.1   0.094       0
Bank Sta=5590.7,5618.2
Exp/Cntr=0.3,0.1

Type RM Length L Ch R = 1,24296,665,665,665
BEGIN DESCRIPTION:
Cottonwood Creek Trib01 16.12
END DESCRIPTION:
XS GIS Cut Line= 3
      1341739.05      6852637.88      1342745.68      6853308.96
      1344800.44      6853318.28
#Sta/Elev= 30
  3781.3 2386.93  4354.4 2386.20  4384.4 2385.17  4766.0 2382.75  4796.0 2383.47
  4859.1 2381.83  5026.7 2381.02  5027.2 2380.52  5054.2 2381.02  5490.4 2381.54
  5610.4 2382.78  5710.4 2381.62  5846.3 2381.93  5945.3 2382.25  6000.4 2384.56
  6050.4 2382.93  6110.4 2383.32  6160.4 2387.39  6190.5 2391.39  6325.0 2396.39
  6341.2 2397.01  6440.2 2397.09  6470.5 2395.81  6530.5 2388.49  6560.5 2386.68
  6660.5 2386.81  6730.5 2389.90  6797.9 2388.50  7020.5 2388.77  7045.9 2390.04
#Mann=9,-1,0
  3781.3   0.045       0  5026.7   0.045       0  5054.2   0.045       0
  5846.3   0.094       0  5945.3   0.063       0  6325.0   0.125       0
  6341.2   0.094       0  6440.2   0.063       0  6797.9   0.035       0
Bank Sta=5026.7,5054.2
Exp/Cntr=0.3,0.1

Type RM Length L Ch R = 1,23631,510,510,510
BEGIN DESCRIPTION:
Cottonwood Creek Trib01 16.11
END DESCRIPTION:
XS GIS Cut Line= 3
      1341650.54      6852745.09      1342736.36      6853844.89
      1344735.54      6853677.12
#Sta/Elev= 30
  3464.1 2387.03  3766.3 2387.23  4282.5 2384.26  4303.7 2385.09  4346.1 2383.66
  4452.2 2382.49  4480.4 2383.35  4515.8 2381.86  4600.7 2381.05  4636.0 2381.81
  4685.6 2380.47  5166.6 2380.23  5253.9 2379.80  5254.4 2379.30  5281.6 2379.80
  5387.7 2381.62  5392.7 2380.87  5429.7 2383.34  5459.8 2383.78  5512.7 2383.86
  5570.2 2381.49  5664.6 2383.79  5736.0 2383.02  5871.5 2381.96  5961.6 2384.67
  6062.9 2383.16  6409.1 2384.25  6921.8 2387.96  6995.2 2388.38  7015.8 2390.35
#Mann=10,-1,0
  3464.1   0.045       0  5166.6    0.07       0  5253.9   0.045       0
  5281.6    0.07       0  5664.6   0.063       0  5736.0   0.094       0
  5871.5   0.063       0  6062.9   0.035       0  6409.1   0.045       0
  6921.8   0.035       0
Bank Sta=5253.9,5281.6
Exp/Cntr=0.3,0.1

Type RM Length L Ch R = 1,23121,1223,1223,1223
BEGIN DESCRIPTION:
Cottonwood Creek Trib01 16.10
END DESCRIPTION:
XS GIS Cut Line= 4
      1341594.58      6852814.94      1342461.40      6854157.12
      1342987.72      6854042.02      1348346.50      6853364.93
#Sta/Elev= 30
  3418.1 2387.14  4316.7 2385.16  4555.5 2381.01  4919.7 2378.99  4983.1 2378.74
  4983.6 2378.24  5010.8 2378.74  5042.7 2379.01  5053.6 2379.07  5084.0 2378.84
  5144.7 2382.31  5269.8 2382.63  5357.3 2380.29  5450.6 2381.39  5460.2 2380.85
  5499.4 2382.70  5627.0 2383.70  5672.8 2380.65  5753.0 2380.82  5853.1 2382.42
  5947.8 2380.89  6302.8 2382.71  7202.4 2387.47  7265.4 2388.20  7285.5 2390.46
  7378.3 2389.10  7900.4 2391.27  9697.3 2392.12 10319.5 2395.23 10956.0 2396.16
#Mann=14,-1,0
  3418.1   0.045       0  4919.7   0.063       0  4983.1   0.063       0
  5010.8   0.063       0  5042.7   0.094       0  5053.6   0.063       0
  5144.7   0.094       0  5450.6   0.063       0  5460.2   0.094       0
  5753.0   0.063       0  5853.1   0.035       0  6302.8   0.045       0
  7202.4   0.035       0  7378.3   0.045       0
Bank Sta=4983.1,5010.8
Exp/Cntr=0.3,0.1

Type RM Length L Ch R = 1,21898,354,354,354
BEGIN DESCRIPTION:
Cottonwood Creek Trib01 16.9
END DESCRIPTION:
XS GIS Cut Line= 3
      1341869.54      6853411.47      1342452.08      6854497.32
      1346452.53      6856523.83
#Sta/Elev= 30
  3772.7 2386.37  3802.8 2385.25  4053.4 2385.07  4232.0 2381.97  4278.5 2381.08
  4305.1 2381.89  4370.9 2379.91  4689.7 2378.39  4715.1 2378.61  4764.8 2382.61
  4786.7 2382.23  4814.3 2379.41  4868.7 2382.48  4896.3 2381.86  4908.9 2380.23
  4947.5 2378.01  4948.0 2377.51  4976.7 2378.01  5033.2 2378.20  5103.6 2378.24
  5856.5 2379.34  6393.5 2383.05  6741.9 2387.36  7050.4 2388.53  7126.9 2388.71
  7159.5 2390.72  7181.7 2389.13  7219.1 2389.33  9425.8 2389.75  9489.4 2388.67
#Mann=13,-1,0
  3772.7   0.045       0  4232.0    0.07       0  4278.5   0.045       0
  4689.7   0.063       0  4715.1   0.094       0  4908.9   0.063       0
  4947.5   0.063       0  4976.7   0.063       0  5033.2   0.035       0
  5103.6   0.045       0  6393.5    0.07       0  7050.4   0.035       0
  7219.1   0.045       0
Bank Sta=4947.5,4976.7
Exp/Cntr=0.3,0.1

Type RM Length L Ch R = 1,21544,406,406,406
BEGIN DESCRIPTION:
Cottonwood Creek Trib01 16.8
END DESCRIPTION:
XS GIS Cut Line= 3
      1341673.82      6853667.79      1342228.39      6854758.29
      1345220.76      6857565.61
#Sta/Elev= 30
  3771.8 2386.46  3939.7 2384.48  4189.9 2380.64  4463.1 2378.57  4576.9 2377.89
  4649.3 2383.13  4688.1 2379.26  4754.9 2383.53  4781.3 2380.21  4812.6 2377.19
  4813.1 2376.69  4841.8 2377.19  4879.8 2378.56  4961.9 2378.35  5509.2 2378.35
  5673.4 2380.47  5788.0 2380.71  6445.3 2383.80  6570.1 2384.79  6634.1 2387.85
  6687.4 2386.43  6928.9 2388.40  7458.5 2389.02  7617.3 2390.00  7684.5 2388.75
  8242.1 2387.48  8336.9 2388.08  8353.8 2388.13  8939.6 2387.71  9098.3 2387.47
#Mann=20,-1,0
  3771.8   0.045       0  3939.7    0.07       0  4189.9   0.045       0
  4463.1   0.094       0  4781.3   0.063       0  4812.6   0.045       0
  4841.8   0.063       0  4879.8   0.035       0  4961.9   0.045       0
  5673.4    0.07       0  5788.0   0.045       0  6445.3    0.07       0
  6687.4   0.035       0  6928.9    0.07       0  7458.5   0.035       0
  7684.5   0.045       0  8242.1    0.07       0  8336.9   0.045       0
  8353.8    0.07       0  8939.6   0.045       0
Bank Sta=4812.6,4841.8
Exp/Cntr=0.3,0.1

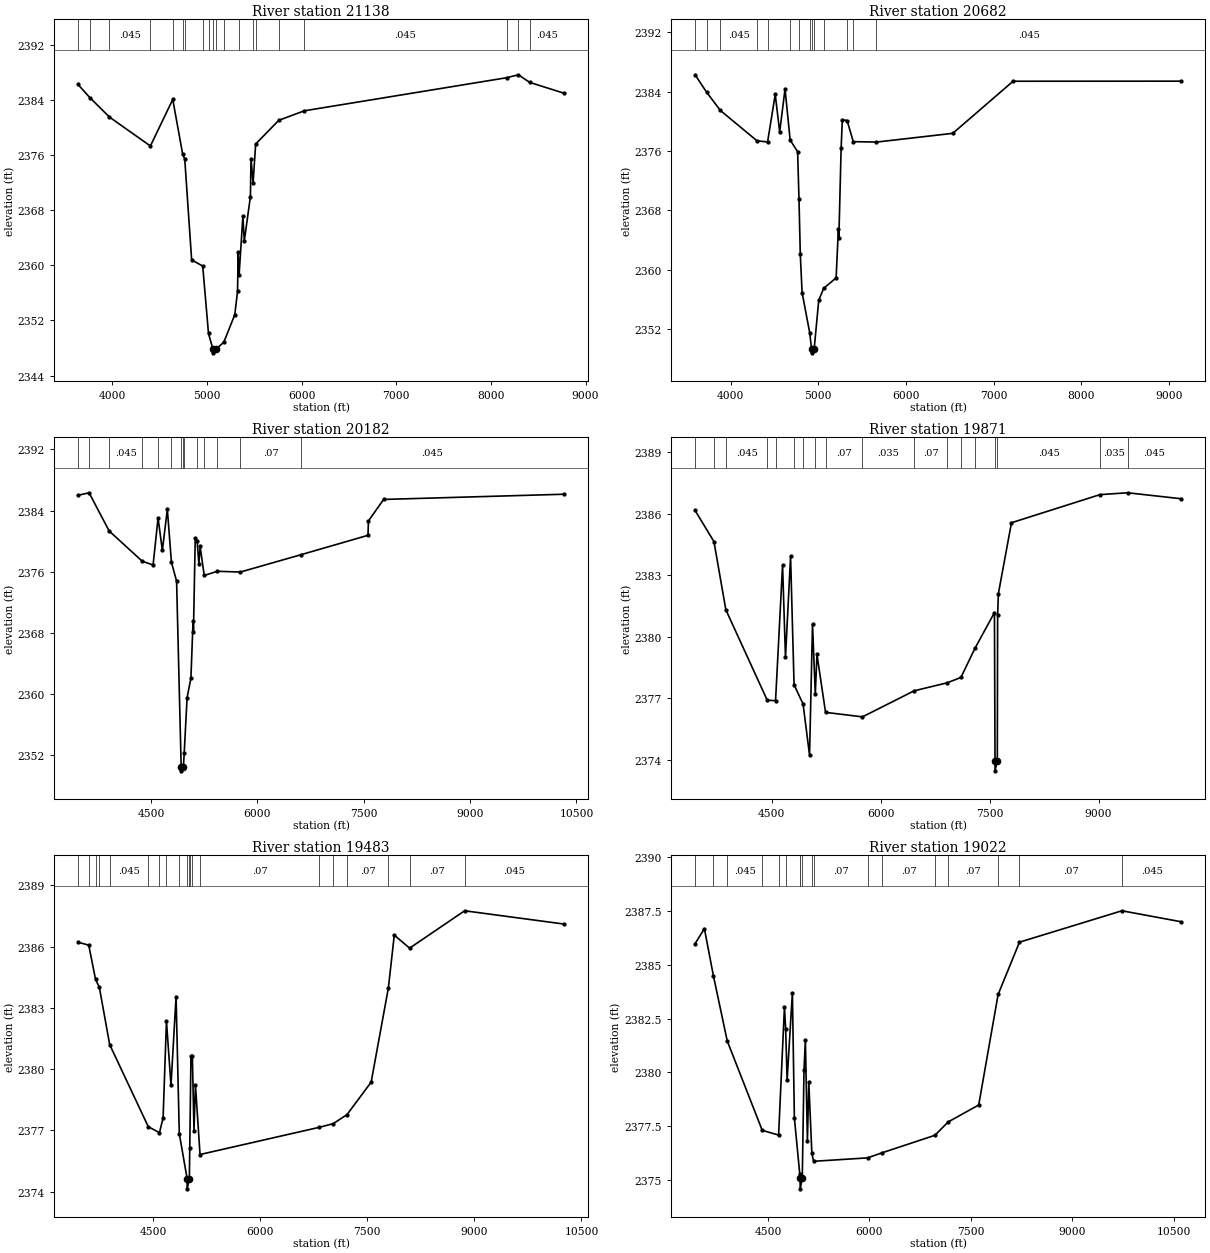
Type RM Length L Ch R = 1,21138,456,456,456
BEGIN DESCRIPTION:
Cottonwood Creek Trib01 16.7
END DESCRIPTION:
XS GIS Cut Line= 3
      1341482.76      6853779.66      1341953.44      6855051.88
      1344179.27      6858103.72
#Sta/Elev= 30
  3639.6 2386.26  3763.3 2384.37  3970.5 2381.54  4404.0 2377.33  4640.1 2384.09
  4745.5 2376.10  4766.7 2375.45  4839.7 2360.79  4956.5 2359.90  5017.7 2350.11
  5064.9 2347.80  5065.4 2347.30  5094.3 2347.80  5179.3 2348.84  5295.1 2352.83
  5324.5 2356.22  5330.7 2361.95  5340.9 2358.63  5380.9 2367.13  5395.5 2363.52
  5460.4 2369.98  5466.6 2375.45  5488.7 2372.03  5515.9 2377.62  5760.1 2381.06
  6029.6 2382.44  8166.1 2387.24  8289.8 2387.67  8411.4 2386.56  8773.4 2384.99
#Mann=20,-1,0
  3639.6   0.045       0  3763.3    0.07       0  3970.5   0.045       0
  4404.0   0.094       0  4640.1   0.035       0  4745.5   0.063       0
  4766.7   0.035       0  4956.5   0.063       0  5017.7   0.035       0
  5064.9   0.063       0  5094.3   0.035       0  5179.3   0.035       0
  5340.9    0.07       0  5488.7   0.035       0  5515.9    0.07       0
  5760.1   0.035       0  6029.6   0.045       0  8166.1   0.063       0
  8289.8   0.035       0  8411.4   0.045       0
Bank Sta=5064.9,5094.3
Exp/Cntr=0.3,0.1

Type RM Length L Ch R = 1,20682,500,500,500
BEGIN DESCRIPTION:
Cottonwood Creek Trib01 16.6
END DESCRIPTION:
XS GIS Cut Line= 3
      1341277.72      6853844.93      1341575.96      6855224.31
      1342929.84      6859128.79
#Sta/Elev= 30
  3595.0 2386.27  3725.5 2383.94  3883.8 2381.46  4301.6 2377.37  4422.1 2377.22
  4509.3 2383.62  4559.9 2378.56  4621.2 2384.35  4679.4 2377.48  4764.5 2375.91
  4780.2 2369.56  4795.2 2362.06  4815.6 2356.92  4903.0 2351.48  4923.7 2349.30
  4924.2 2348.80  4953.1 2349.30  5005.6 2355.88  5061.5 2357.49  5203.8 2358.90
  5229.7 2365.49  5235.0 2364.26  5260.8 2376.36  5274.8 2380.22  5329.2 2380.10
  5399.4 2377.26  5664.1 2377.20  6534.3 2378.38  7222.2 2385.40  9138.8 2385.41
#Mann=14,-1,0
  3595.0   0.045       0  3725.5    0.07       0  3883.8   0.045       0
  4301.6   0.063       0  4422.1   0.094       0  4679.4   0.035       0
  4780.2   0.063       0  4903.0   0.094       0  4923.7    0.07       0
  4953.1   0.094       0  5061.5   0.063       0  5329.2   0.035       0
  5399.4    0.07       0  5664.1   0.045       0
Bank Sta=4923.7,4953.1
Exp/Cntr=0.3,0.1

Type RM Length L Ch R = 1,20182,311,311,311
BEGIN DESCRIPTION:
Cottonwood Creek Trib01 16.5
END DESCRIPTION:
XS GIS Cut Line= 3
      1340928.19      6853714.35      1341081.98      6855247.61
      1342183.31      6860448.22
#Sta/Elev= 30
  3468.7 2385.99  3624.4 2386.32  3908.3 2381.32  4374.1 2377.38  4527.6 2376.88
  4597.8 2383.03  4658.3 2378.80  4728.6 2384.16  4786.1 2377.27  4859.3 2374.75
  4923.9 2350.48  4924.4 2349.98  4955.5 2350.48  4966.8 2352.35  5007.3 2359.54
  5061.2 2362.10  5091.7 2369.60  5096.8 2368.09  5122.5 2380.45  5148.4 2380.04
  5173.6 2377.05  5191.1 2379.30  5249.1 2375.51  5434.0 2376.06  5758.7 2375.96
  6611.4 2378.22  7559.4 2380.76  7565.5 2382.64  7780.2 2385.45 10325.6 2386.13
#Mann=14,-1,0
  3468.7   0.045       0  3624.4    0.07       0  3908.3   0.045       0
  4374.1   0.063       0  4597.8   0.094       0  4786.1   0.063       0
  4923.9    0.07       0  4955.5   0.063       0  4966.8    0.07       0
  5148.4   0.063       0  5249.1    0.07       0  5434.0   0.035       0
  5758.7    0.07       0  6611.4   0.045       0
Bank Sta=4923.9,4955.5
Exp/Cntr=0.3,0.1

Type RM Length L Ch R = 1,19871,388,388,388
BEGIN DESCRIPTION:
Cottonwood Creek Trib01 16.4
END DESCRIPTION:
XS GIS Cut Line= 3
      1340657.90      6853686.44      1340769.74      6855238.29
      1341870.40      6860255.40
#Sta/Elev= 30
  3444.4 2386.16  3704.4 2384.64  3867.9 2381.32  4438.3 2376.91  4552.5 2376.89
  4649.1 2383.49  4689.2 2379.00  4759.4 2383.92  4807.5 2377.66  4931.2 2376.73
  5020.5 2374.24  5061.4 2380.62  5099.6 2377.21  5122.8 2379.14  5240.8 2376.32
  5748.8 2376.10  6461.2 2377.37  6915.4 2377.76  7104.5 2378.02  7298.1 2379.44
  7566.4 2381.18  7574.3 2373.97  7574.8 2373.47  7605.9 2373.97  7610.2 2381.05
  7620.9 2382.11  7800.8 2385.56  9019.8 2386.93  9399.4 2387.02 10136.7 2386.73
#Mann=18,-1,0
  3444.4   0.045       0  3704.4    0.07       0  3867.9   0.045       0
  4438.3   0.063       0  4552.5   0.094       0  4807.5   0.063       0
  4931.2    0.07       0  5099.6   0.035       0  5240.8    0.07       0
  5748.8   0.035       0  6461.2    0.07       0  6915.4   0.035       0
  7104.5    0.07       0  7298.1   0.045       0  7574.3    0.07       0
  7605.9   0.045       0  9019.8   0.035       0  9399.4   0.045       0
Bank Sta=7574.3,7605.9
Exp/Cntr=0.3,0.1

Type RM Length L Ch R = 1,19483,461,461,461
BEGIN DESCRIPTION:
Cottonwood Creek Trib01 16.3
END DESCRIPTION:
XS GIS Cut Line= 3
      1340583.33      6853644.51      1340396.93      6855196.35
      1341124.06      6860394.54
#Sta/Elev= 30
  3445.0 2386.21  3595.0 2386.07  3690.6 2384.39  3743.5 2384.01  3888.6 2381.20
  4429.8 2377.18  4586.0 2376.89  4637.0 2377.61  4684.3 2382.35  4747.8 2379.21
  4818.9 2383.55  4864.3 2376.84  4973.7 2374.64  4974.2 2374.14  5005.3 2374.64
  5010.9 2376.13  5027.5 2380.64  5047.2 2380.64  5070.2 2376.98  5090.4 2379.23
  5154.8 2375.82  6824.1 2377.15  7020.9 2377.33  7213.9 2377.77  7552.9 2379.36
  7794.7 2383.98  7877.3 2386.56  8091.8 2385.92  8863.2 2387.75 10256.8 2387.10
#Mann=20,-1,0
  3445.0   0.045       0  3595.0    0.07       0  3690.6   0.045       0
  3743.5    0.07       0  3888.6   0.045       0  4429.8    0.07       0
  4586.0   0.063       0  4684.3   0.094       0  4864.3   0.063       0
  4973.7   0.063       0  5005.3   0.063       0  5010.9    0.07       0
  5047.2   0.063       0  5154.8    0.07       0  6824.1   0.035       0
  7020.9   0.035       0  7213.9    0.07       0  7794.7   0.045       0
  8091.8    0.07       0  8863.2   0.045       0
Bank Sta=4973.7,5005.3
Exp/Cntr=0.3,0.1

Type RM Length L Ch R = 1,19022,564,564,564
BEGIN DESCRIPTION:
Cottonwood Creek Trib01 16.2
END DESCRIPTION:
XS GIS Cut Line= 3
      1340560.03      6853621.21      1339968.19      6855089.16
      1340898.60      6860621.90
#Sta/Elev= 30
  3418.6 2385.99  3556.5 2386.69  3689.8 2384.50  3894.3 2381.47  4412.6 2377.31
  4654.7 2377.09  4741.3 2383.05  4759.1 2382.03  4780.8 2379.64  4858.7 2383.71
  4888.2 2377.89  4967.9 2375.28  4973.5 2375.09  4974.0 2374.59  5005.1 2375.09
  5030.6 2380.10  5050.9 2381.51  5081.3 2376.81  5101.6 2379.55  5147.0 2376.24
  5172.9 2375.87  5971.6 2376.03  6189.8 2376.27  6968.4 2377.08  7164.2 2377.70
  7616.4 2378.49  7903.5 2383.63  8219.7 2386.06  9735.9 2387.52 10611.8 2387.01
#Mann=18,-1,0
  3418.6   0.045       0  3689.8    0.07       0  3894.3   0.045       0
  4412.6    0.07       0  4654.7   0.063       0  4759.1   0.094       0
  4967.9   0.035       0  4973.5   0.035       0  5005.1   0.035       0
  5147.0   0.063       0  5172.9    0.07       0  5971.6   0.035       0
  6189.8    0.07       0  6968.4   0.035       0  7164.2    0.07       0
  7903.5   0.045       0  8219.7    0.07       0  9735.9   0.045       0
Bank Sta=4973.5,5005.1
Exp/Cntr=0.3,0.1