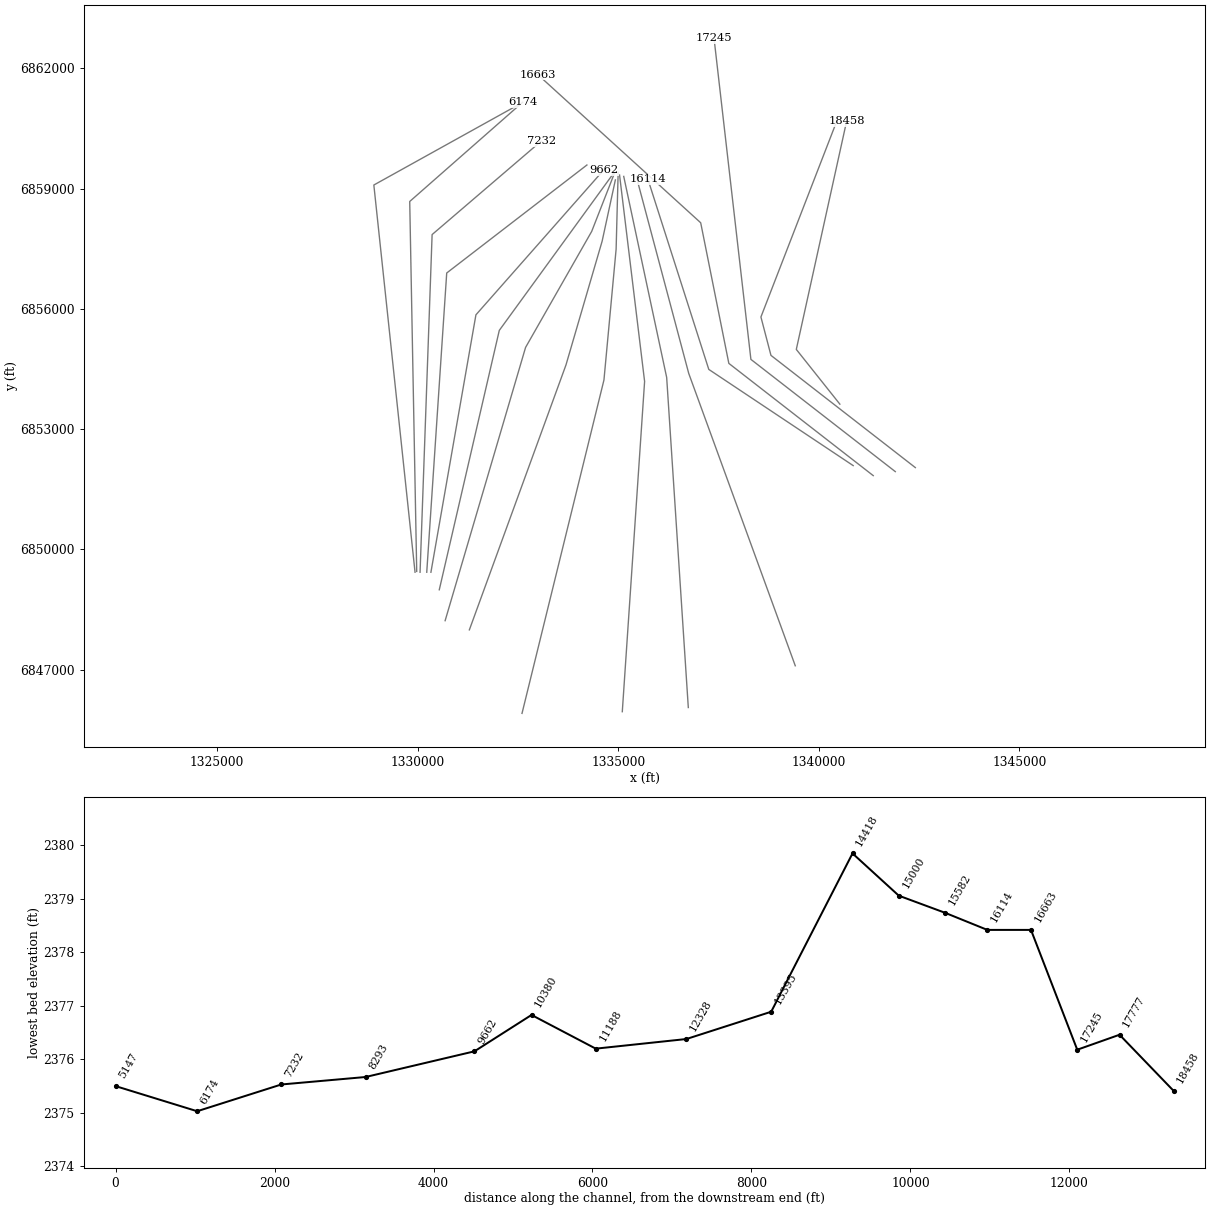
HEC-RAS study Cottonwood Creek Trib01.prj: Cottonwood Creek Trib01 Base Level Engineering

--- Cottonwood Creek Trib01.g01 (geometry) --- (continued)

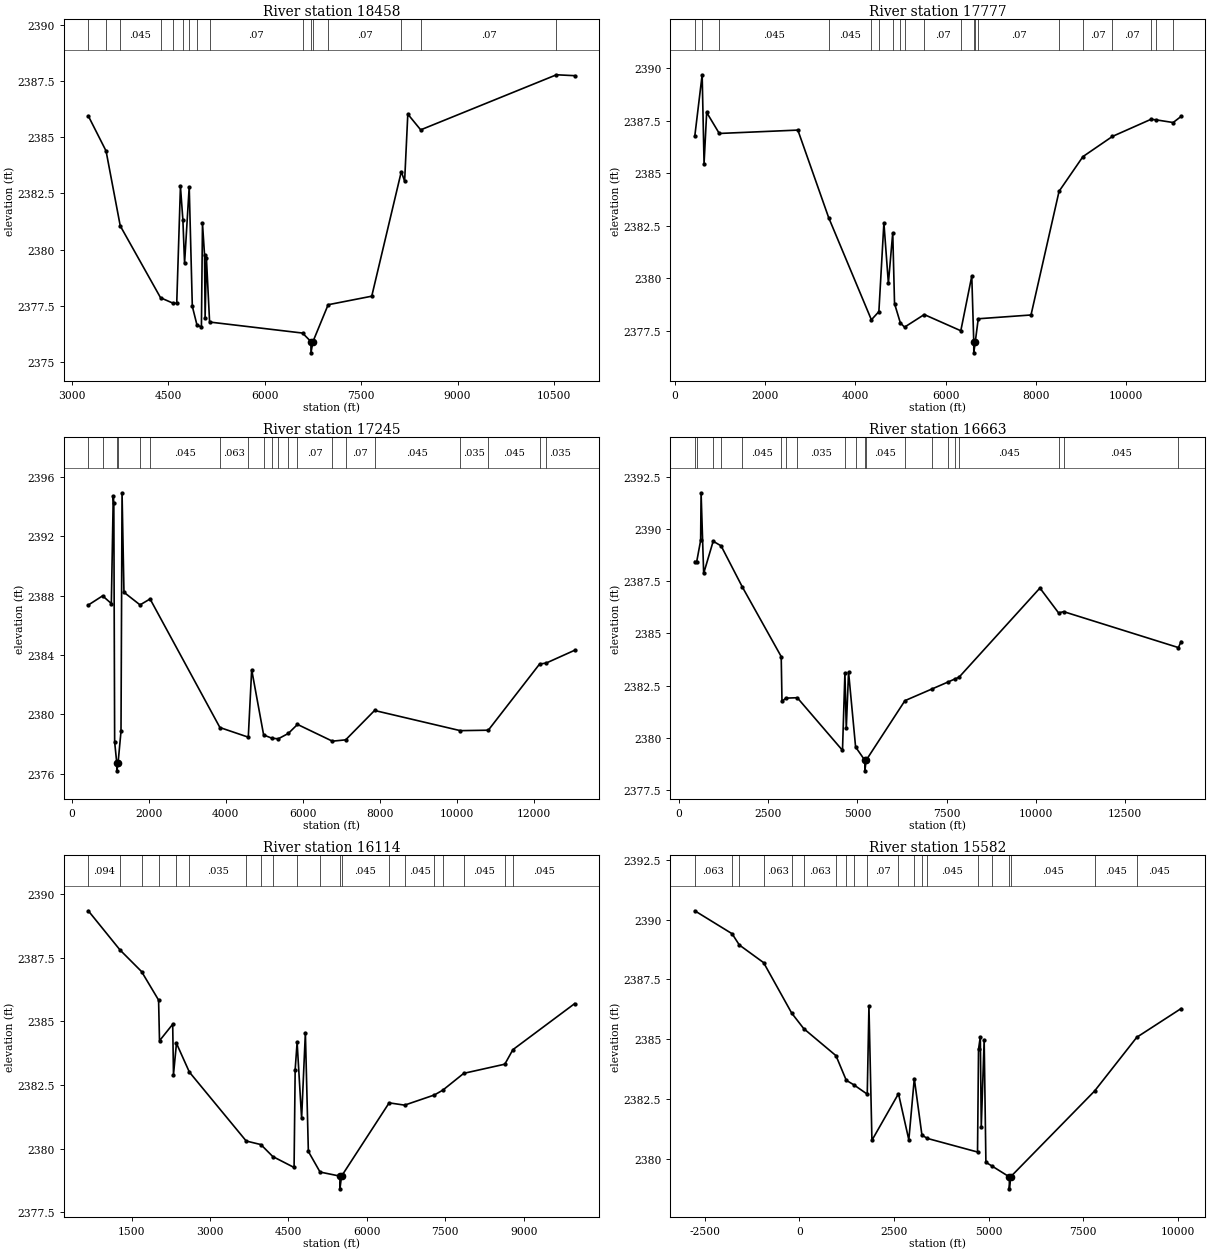
Type RM Length L Ch R = 1,18458,681,681,681
BEGIN DESCRIPTION:
Cottonwood Creek Trib01 16.1
END DESCRIPTION:
XS GIS Cut Line= 3
      1340522.76      6853621.19      1339436.92      6854986.64
      1340690.02      6860672.84
#Sta/Elev= 30
  3253.9 2385.95  3530.3 2384.39  3750.9 2381.06  4378.5 2377.86  4579.4 2377.61
  4630.0 2377.62  4687.7 2382.81  4725.9 2381.32  4751.8 2379.39  4824.1 2382.80
  4872.4 2377.48  4946.5 2376.63  5014.0 2376.57  5030.6 2381.17  5062.8 2379.76
  5071.5 2376.97  5092.0 2379.62  5141.3 2376.78  6586.9 2376.29  6718.0 2375.91
  6718.5 2375.41  6749.6 2375.91  6985.8 2377.55  7664.3 2377.93  8124.0 2383.47
  8175.9 2383.05  8225.4 2386.03  8425.8 2385.33 10538.5 2387.78 10821.1 2387.74
#Mann=16,-1,0
  3253.9   0.045       0  3530.3    0.07       0  3750.9   0.045       0
  4378.5    0.07       0  4579.4   0.063       0  4725.9   0.094       0
  4824.1   0.063       0  4946.5   0.035       0  5141.3    0.07       0
  6586.9   0.035       0  6718.0   0.035       0  6749.6   0.035       0
  6985.8    0.07       0  8124.0   0.045       0  8425.8    0.07       0
 10538.5   0.045       0
Bank Sta=6718,6749.6
Exp/Cntr=0.3,0.1

Type RM Length L Ch R = 1,17777,532,532,532
BEGIN DESCRIPTION:
Cottonwood Creek Trib01 16.0
END DESCRIPTION:
XS GIS Cut Line= 4
      1342405.02      6852037.99      1338805.00      6854838.00
      1338554.85      6855795.49      1340446.84      6860683.87
#Sta/Elev= 30
   435.1 2386.75   599.2 2389.68   641.4 2385.46   699.4 2387.89   979.1 2386.89
  2722.7 2387.05  3406.2 2382.89  4354.5 2378.03  4520.7 2378.42  4632.1 2382.64
  4731.6 2379.77  4828.6 2382.17  4868.2 2378.80  4996.4 2377.89  5089.6 2377.68
  5527.2 2378.28  6338.9 2377.51  6582.4 2380.11  6626.5 2376.96  6627.0 2376.46
  6658.1 2376.96  6726.1 2378.08  7896.8 2378.26  8519.1 2384.14  9049.4 2385.79
  9704.1 2386.75 10556.3 2387.56 10662.5 2387.54 11051.0 2387.41 11227.2 2387.70
#Mann=20,-1,0
   435.1   0.063       0   599.2   0.035       0   979.1   0.045       0
  3406.2   0.045       0  4354.5   0.035       0  4520.7   0.094       0
  4828.6   0.063       0  4996.4    0.07       0  5089.6   0.035       0
  5527.2    0.07       0  6338.9   0.035       0  6626.5    0.07       0
  6658.1   0.063       0  6726.1    0.07       0  8519.1   0.045       0
  9049.4    0.07       0  9704.1    0.07       0 10556.3   0.045       0
 10662.5   0.035       0 11051.0   0.035       0
Bank Sta=6626.5,6658.1
Exp/Cntr=0.3,0.1

Type RM Length L Ch R = 1,17245,582,582,582
BEGIN DESCRIPTION:
Cottonwood Creek Trib01 15.0
END DESCRIPTION:
XS GIS Cut Line= 3
      1341905.03      6851937.97      1338305.00      6854738.00
      1337386.09      6862747.22
#Sta/Elev= 30
   434.9 2387.36   806.3 2387.98  1033.1 2387.46  1082.9 2394.71  1097.3 2394.22
  1119.0 2378.13  1174.7 2376.68  1175.2 2376.18  1206.3 2376.68  1283.7 2378.84
  1310.9 2394.93  1360.7 2388.22  1778.1 2387.37  2038.1 2387.77  3850.9 2379.10
  4587.3 2378.45  4675.3 2383.00  4985.6 2378.60  5200.0 2378.38  5364.9 2378.34
  5625.5 2378.70  5864.4 2379.31  6770.1 2378.18  7115.3 2378.27  7865.2 2380.25
 10089.6 2378.89 10817.0 2378.92 12147.3 2383.38 12321.2 2383.45 13057.4 2384.31
#Mann=20,-1,0
   434.9   0.063       0   806.3   0.063       0  1174.7    0.07       0
  1206.3   0.125       0  1778.1   0.063       0  2038.1   0.045       0
  3850.9   0.063       0  4587.3   0.094       0  4985.6    0.07       0
  5200.0   0.035       0  5364.9    0.07       0  5625.5   0.094       0
  5864.4    0.07       0  6770.1   0.035       0  7115.3    0.07       0
  7865.2   0.045       0 10089.6   0.035       0 10817.0   0.045       0
 12147.3   0.045       0 12321.2   0.035       0
Bank Sta=1174.7,1206.3
Exp/Cntr=0.3,0.1

Type RM Length L Ch R = 1,16663,549,549,549
BEGIN DESCRIPTION:
Cottonwood Creek Trib01 14.0
END DESCRIPTION:
XS GIS Cut Line= 4
      1341354.98      6851838.01      1337755.00      6854638.00
      1337053.35      6858146.23      1332991.08      6861843.67
#Sta/Elev= 30
   439.0 2388.44   491.1 2388.41   603.7 2389.45   616.3 2391.73   688.7 2387.87
   954.9 2389.41  1176.9 2389.19  1772.7 2387.22  2861.8 2383.89  2884.0 2381.74
  2990.1 2381.90  3312.1 2381.92  4579.8 2379.40  4647.5 2383.11  4685.7 2380.45
  4749.9 2383.15  4947.0 2379.56  5208.2 2378.92  5208.7 2378.42  5239.8 2378.92
  6330.2 2381.78  7076.5 2382.33  7548.5 2382.68  7746.3 2382.83  7845.6 2382.90
 10113.8 2387.17 10636.1 2385.98 10778.9 2386.04 13995.0 2384.32 14070.4 2384.61
#Mann=20,-1,0
   439.0   0.125       0   491.1   0.094       0   954.9   0.063       0
  1176.9   0.035       0  1772.7   0.045       0  2861.8   0.063       0
  2990.1   0.063       0  3312.1   0.035       0  4647.5   0.094       0
  4947.0    0.07       0  5208.2    0.07       0  5239.8   0.045       0
  6330.2    0.07       0  7076.5   0.035       0  7548.5   0.045       0
  7746.3   0.035       0  7845.6   0.045       0 10636.1   0.035       0
 10778.9   0.045       0 13995.0   0.035       0
Bank Sta=5208.2,5239.8
Exp/Cntr=0.3,0.1

Type RM Length L Ch R = 1,16114,532,532,532
BEGIN DESCRIPTION:
Cottonwood Creek Trib01 13.0
END DESCRIPTION:
XS GIS Cut Line= 3
      1340855.00      6852088.00      1337255.00      6854488.00
      1335738.00      6859230.83
#Sta/Elev= 30
   669.2 2389.35  1276.0 2387.81  1688.7 2386.96  2014.2 2385.84  2031.8 2384.24
  2284.2 2384.89  2299.2 2382.91  2356.3 2384.14  2603.1 2383.01  3690.8 2380.30
  3971.4 2380.16  4199.2 2379.69  4606.8 2379.26  4627.8 2383.11  4665.1 2384.18
  4751.0 2381.19  4823.1 2384.56  4880.2 2379.89  5104.2 2379.08  5483.8 2378.92
  5484.3 2378.42  5515.4 2378.92  6425.9 2381.80  6721.9 2381.71  7291.9 2382.11
  7453.7 2382.30  7853.9 2382.96  8639.5 2383.32  8793.8 2383.89  9975.4 2385.70
#Mann=20,-1,0
   669.2   0.094       0  1276.0   0.035       0  1688.7   0.045       0
  2014.2   0.035       0  2356.3   0.063       0  2603.1   0.035       0
  3690.8    0.07       0  3971.4   0.035       0  4199.2   0.045       0
  4665.1   0.094       0  5104.2   0.045       0  5483.8    0.07       0
  5515.4   0.045       0  6425.9    0.07       0  6721.9   0.045       0
  7291.9    0.07       0  7453.7   0.045       0  7853.9   0.045       0
  8639.5    0.07       0  8793.8   0.045       0
Bank Sta=5483.8,5515.4
Exp/Cntr=0.3,0.1

Type RM Length L Ch R = 1,15582,582,582,582
BEGIN DESCRIPTION:
Cottonwood Creek Trib01 12.0
END DESCRIPTION:
XS GIS Cut Line= 3
      1339411.24      6847094.27      1336755.00      6854388.00
      1335447.21      6859302.41
#Sta/Elev= 30
 -2762.0 2390.37 -1776.0 2389.41 -1585.1 2388.94  -942.7 2388.20  -201.2 2386.09
   117.3 2385.44   968.5 2384.31  1240.4 2383.28  1440.7 2383.09  1794.7 2382.70
  1839.5 2386.38  1918.3 2380.77  2620.0 2382.72  2893.1 2380.79  3037.5 2383.35
  3239.0 2380.99  3380.3 2380.85  4707.9 2380.28  4734.3 2384.58  4781.7 2385.10
  4806.9 2381.33  4883.3 2384.98  4929.2 2379.85  5093.6 2379.69  5548.5 2379.24
  5549.0 2378.74  5580.1 2379.24  7799.6 2382.83  8915.7 2385.08 10085.8 2386.28
#Mann=20,-1,0
 -2762.0   0.063       0 -1776.0   0.094       0 -1585.1   0.094       0
  -942.7   0.063       0  -201.2   0.063       0   117.3   0.063       0
   968.5   0.094       0  1240.4   0.094       0  1440.7   0.063       0
  1794.7    0.07       0  2620.0   0.094       0  3037.5   0.094       0
  3239.0   0.035       0  3380.3   0.045       0  4707.9   0.094       0
  5093.6   0.045       0  5548.5   0.035       0  5580.1   0.045       0
  7799.6   0.045       0  8915.7   0.045       0
Bank Sta=5548.5,5580.1
Exp/Cntr=0.3,0.1

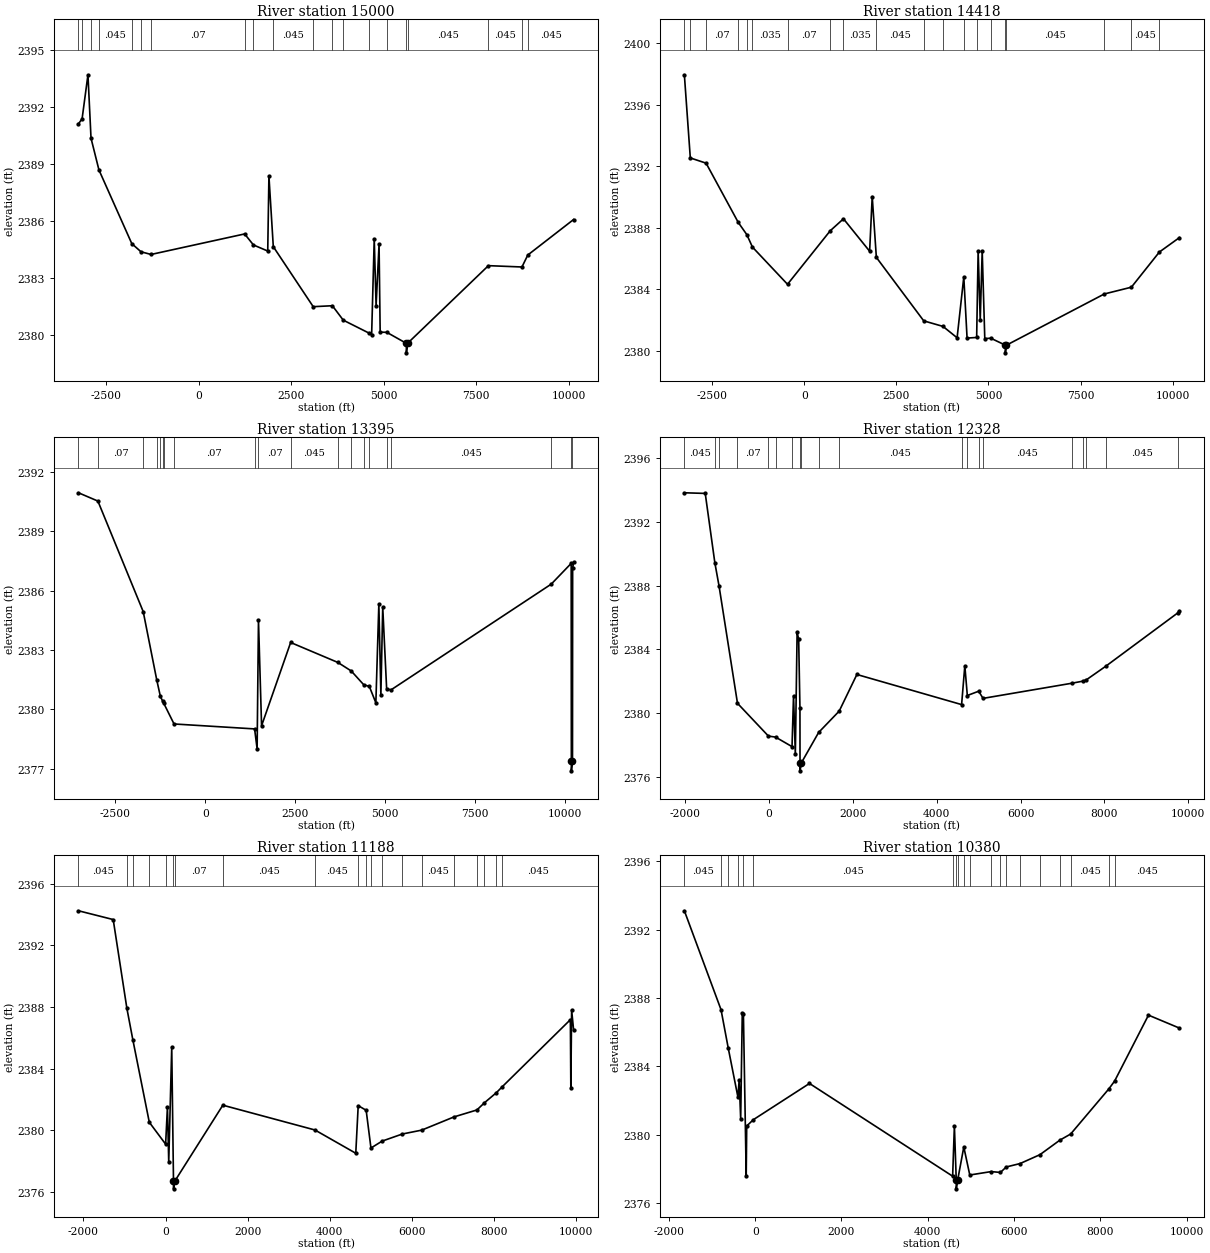
Type RM Length L Ch R = 1,15000,582,582,582
BEGIN DESCRIPTION:
Cottonwood Creek Trib01 11.0
END DESCRIPTION:
XS GIS Cut Line= 3
      1336744.57      6846052.62      1336205.00      6854288.00
      1335134.71      6859302.42
#Sta/Elev= 30
 -3248.6 2391.12 -3151.0 2391.38 -2992.7 2393.70 -2909.9 2390.36 -2695.8 2388.69
 -1807.8 2384.81 -1559.0 2384.38 -1286.1 2384.24  1241.4 2385.32  1479.5 2384.74
  1865.8 2384.42  1897.8 2388.37  2016.1 2384.65  3094.8 2381.49  3612.7 2381.54
  3907.4 2380.78  4602.6 2380.10  4673.7 2380.01  4743.9 2385.06  4794.0 2381.54
  4874.2 2384.77  4904.2 2380.15  5083.2 2380.14  5612.4 2379.56  5612.9 2379.06
  5644.0 2379.56  7829.6 2383.65  8736.0 2383.58  8894.0 2384.21 10131.8 2386.08
#Mann=20,-1,0
 -3248.6   0.045       0 -3151.0   0.094       0 -2909.9   0.035       0
 -2695.8   0.045       0 -1807.8    0.07       0 -1559.0   0.035       0
 -1286.1    0.07       0  1241.4   0.094       0  1479.5    0.07       0
  2016.1   0.045       0  3094.8   0.045       0  3612.7   0.094       0
  3907.4   0.045       0  4602.6   0.094       0  5083.2   0.045       0
  5612.4   0.035       0  5644.0   0.045       0  7829.6   0.045       0
  8736.0    0.07       0  8894.0   0.045       0
Bank Sta=5612.4,5644
Exp/Cntr=0.3,0.1

Type RM Length L Ch R = 1,14418,1023,1023,1023
BEGIN DESCRIPTION:
Cottonwood Creek Trib01 10.0
END DESCRIPTION:
XS GIS Cut Line= 3
      1335098.74      6845948.45      1335655.00      6854188.00
      1335030.54      6859337.16
#Sta/Elev= 30
 -3258.3 2397.94 -3096.8 2392.53 -2668.6 2392.19 -1793.8 2388.33 -1562.3 2387.54
 -1409.7 2386.73  -457.3 2384.31   702.2 2387.79  1062.3 2388.57  1772.7 2386.46
  1842.8 2390.02  1955.3 2386.06  3242.0 2381.93  3764.4 2381.57  4148.1 2380.83
  4329.9 2384.79  4418.7 2380.81  4679.0 2380.85  4719.4 2386.49  4775.9 2381.98
  4829.6 2386.48  4899.8 2380.78  5064.5 2380.80  5457.7 2380.35  5458.2 2379.85
  5489.3 2380.35  8145.9 2383.68  8880.2 2384.12  9641.2 2386.41 10186.9 2387.35
#Mann=20,-1,0
 -3258.3   0.094       0 -3096.8   0.035       0 -2668.6    0.07       0
 -1793.8    0.07       0 -1562.3   0.045       0 -1409.7   0.035       0
  -457.3    0.07       0   702.2   0.035       0  1062.3   0.035       0
  1955.3   0.045       0  3242.0   0.045       0  3764.4   0.045       0
  4329.9   0.063       0  4679.0   0.094       0  5064.5   0.045       0
  5457.7   0.035       0  5489.3   0.045       0  8145.9   0.045       0
  8880.2   0.045       0  9641.2   0.035       0
Bank Sta=5457.7,5489.3
Exp/Cntr=0.3,0.1

Type RM Length L Ch R = 1,13395,1067,1067,1067
BEGIN DESCRIPTION:
Cottonwood Creek Trib01 9.8
END DESCRIPTION:
XS GIS Cut Line= 4
      1332598.74      6845906.76      1334641.52      6854223.28
      1334944.91      6857487.78      1334995.77      6859404.81
#Sta/Elev= 30
 -3527.2 2390.95 -2987.8 2390.53 -1728.2 2384.94 -1350.2 2381.47 -1250.7 2380.65
 -1188.9 2380.42 -1155.8 2380.30  -871.9 2379.26  1367.3 2379.01  1437.3 2378.00
  1474.8 2384.51  1560.9 2379.17  2369.0 2383.38  3682.6 2382.37  4052.7 2381.94
  4401.8 2381.24  4555.0 2381.16  4737.2 2380.33  4820.3 2385.33  4876.6 2380.73
  4928.1 2385.17  5037.3 2381.02  5163.9 2380.99  9610.6 2386.33 10166.0 2387.38
 10170.1 2377.39 10170.6 2376.89 10201.8 2377.39 10206.0 2387.13 10232.8 2387.44
#Mann=20,-1,0
 -3527.2   0.045       0 -2987.8    0.07       0 -1728.2   0.045       0
 -1350.2    0.07       0 -1250.7   0.045       0 -1188.9    0.07       0
 -1155.8   0.045       0  -871.9    0.07       0  1367.3   0.094       0
  1474.8    0.07       0  2369.0   0.045       0  3682.6   0.045       0
  4052.7   0.035       0  4401.8   0.045       0  4555.0   0.063       0
  5037.3    0.07       0  5163.9   0.045       0  9610.6   0.035       0
 10170.1   0.063       0 10201.8   0.035       0
Bank Sta=10170.1,10201.8
Exp/Cntr=0.3,0.1

Type RM Length L Ch R = 1,12328,1140,1140,1140
BEGIN DESCRIPTION:
Cottonwood Creek Trib01 9.7
END DESCRIPTION:
XS GIS Cut Line= 4
      1331286.26      6847990.15      1333694.93      6854599.49
      1334596.51      6857687.85      1334926.37      6859215.61
#Sta/Elev= 30
 -2022.2 2393.84 -1524.2 2393.80 -1293.9 2389.43 -1195.5 2388.00  -754.5 2380.62
   -15.4 2378.56   153.0 2378.50   546.9 2377.90   582.9 2381.10   625.7 2377.41
   668.3 2385.07   705.2 2384.66   735.7 2380.35   737.6 2376.88   738.1 2376.38
   769.3 2376.88  1181.9 2378.79  1672.2 2380.13  2094.5 2382.43  4593.5 2380.54
  4670.2 2382.98  4729.8 2381.11  5001.5 2381.38  5104.6 2380.93  7222.0 2381.88
  7483.0 2382.01  7572.8 2382.10  8029.0 2382.94  9747.9 2386.29  9792.6 2386.43
#Mann=20,-1,0
 -2022.2   0.045       0 -1293.9    0.07       0 -1195.5   0.045       0
  -754.5    0.07       0   -15.4   0.094       0   153.0    0.07       0
   546.9   0.094       0   737.6   0.063       0   769.3    0.07       0
  1181.9    0.07       0  1672.2   0.045       0  4593.5   0.035       0
  4729.8   0.094       0  5001.5    0.07       0  5104.6   0.045       0
  7222.0   0.045       0  7483.0   0.045       0  7572.8    0.07       0
  8029.0   0.045       0  9747.9   0.035       0
Bank Sta=737.6,769.3
Exp/Cntr=0.3,0.1

Type RM Length L Ch R = 1,11188,808,808,808
BEGIN DESCRIPTION:
Cottonwood Creek Trib01 9.6
END DESCRIPTION:
XS GIS Cut Line= 4
      1330682.07      6848219.25      1332687.67      6855036.37
      1334336.10      6857930.90      1334926.38      6859441.33
#Sta/Elev= 30
 -2121.0 2394.25 -1275.4 2393.68  -941.9 2387.91  -796.7 2385.87  -396.1 2380.52
     1.3 2379.10    45.8 2381.53    77.1 2377.93   150.1 2385.39   192.9 2376.70
   193.4 2376.20   224.6 2376.70  1394.6 2381.63  3638.4 2380.02  4632.3 2378.51
  4691.6 2381.60  4885.3 2381.30  5002.0 2378.85  5275.6 2379.30  5768.0 2379.76
  6236.5 2380.01  7025.6 2380.87  7582.7 2381.32  7767.1 2381.79  8056.3 2382.44
  8204.4 2382.84  9859.0 2387.18  9870.2 2382.73  9889.3 2387.81  9937.7 2386.51
#Mann=20,-1,0
 -2121.0   0.045       0  -941.9   0.063       0  -796.7   0.045       0
  -396.1    0.07       0     1.3   0.063       0   192.9   0.035       0
   224.6    0.07       0  1394.6   0.045       0  3638.4   0.045       0
  4691.6   0.063       0  4885.3   0.035       0  5002.0    0.07       0
  5275.6   0.035       0  5768.0    0.07       0  6236.5   0.045       0
  7025.6    0.07       0  7582.7   0.045       0  7767.1    0.07       0
  8056.3   0.045       0  8204.4   0.045       0
Bank Sta=192.9,224.6
Exp/Cntr=0.3,0.1

Type RM Length L Ch R = 1,10380,718,718,718
BEGIN DESCRIPTION:
Cottonwood Creek Trib01 9.5
END DESCRIPTION:
XS GIS Cut Line= 3
      1330536.23      6848990.07      1332032.34      6855461.12
      1334874.30      6859371.89
#Sta/Elev= 30
 -1641.7 2393.11  -792.1 2387.32  -624.6 2385.07  -400.1 2382.20  -371.1 2383.21
  -336.4 2380.92  -299.3 2387.13  -273.1 2387.06  -208.2 2377.60  -196.6 2380.51
   -42.0 2380.88  1258.2 2383.00  4576.5 2377.57  4617.1 2380.52  4660.4 2377.33
  4660.9 2376.83  4692.1 2377.33  4835.2 2379.28  4973.8 2377.64  5470.6 2377.84
  5684.9 2377.79  5818.4 2378.11  6139.5 2378.31  6600.1 2378.83  7061.5 2379.68
  7312.2 2380.04  8196.5 2382.68  8330.8 2383.14  9115.7 2387.00  9834.4 2386.24
#Mann=20,-1,0
 -1641.7   0.045       0  -792.1   0.063       0  -624.6   0.045       0
  -400.1   0.063       0  -273.1    0.07       0   -42.0   0.045       0
  4576.5   0.063       0  4660.4   0.045       0  4692.1   0.063       0
  4835.2   0.035       0  4973.8   0.045       0  5470.6   0.045       0
  5684.9   0.035       0  5818.4   0.045       0  6139.5    0.07       0
  6600.1    0.07       0  7061.5    0.07       0  7312.2   0.045       0
  8196.5   0.035       0  8330.8   0.045       0
Bank Sta=4660.4,4692.1
Exp/Cntr=0.3,0.1

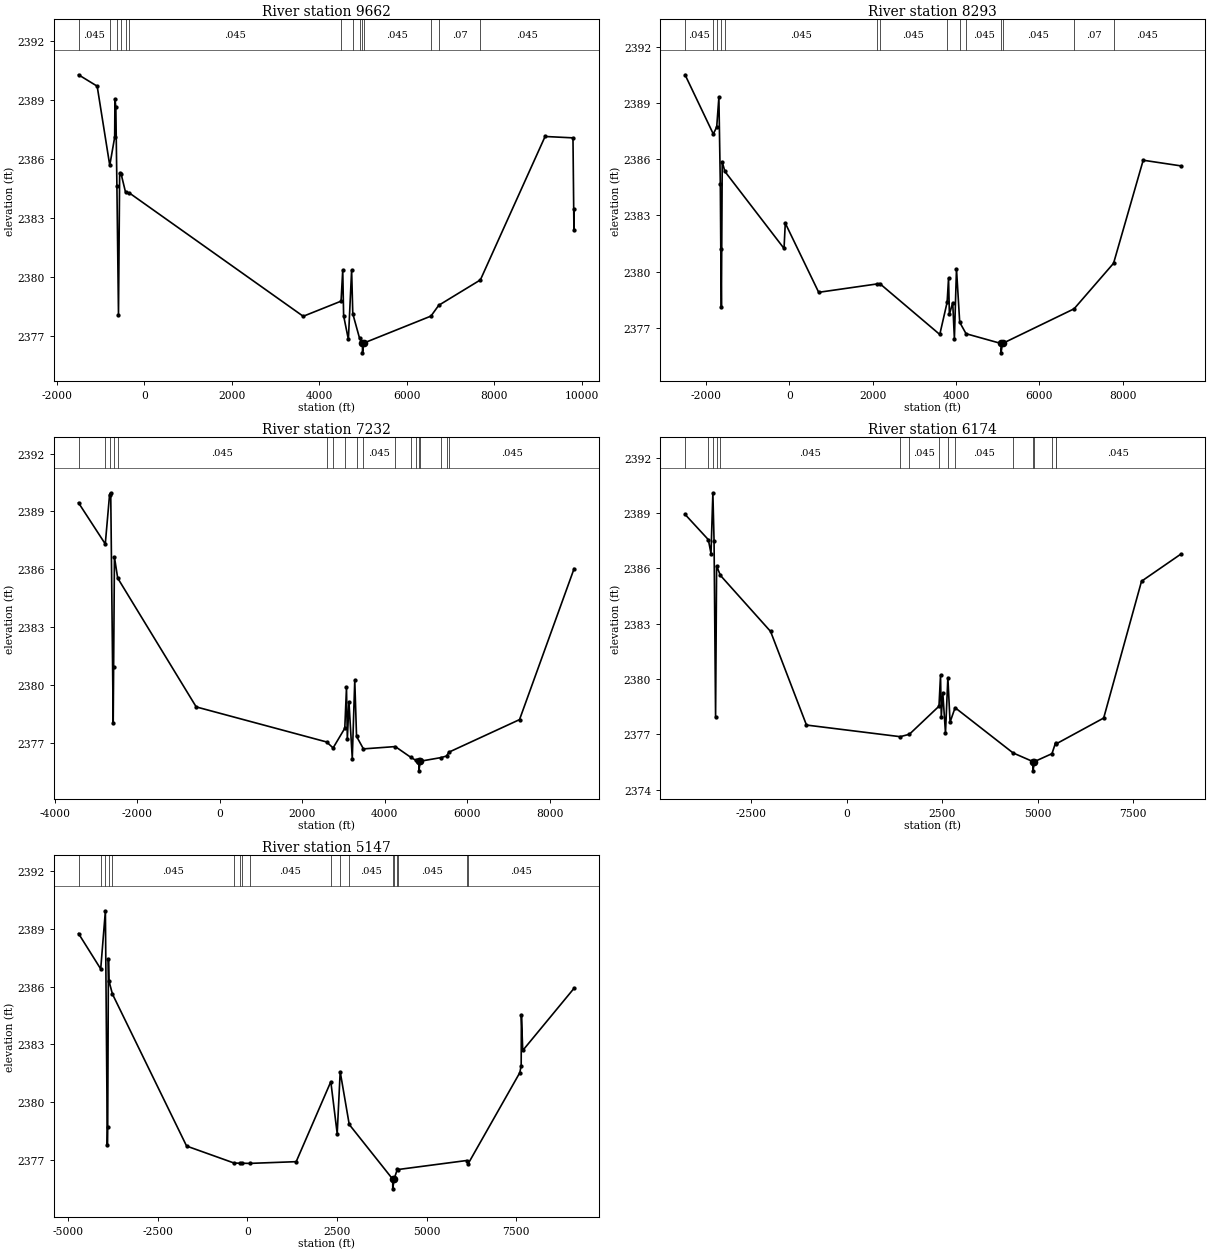
Type RM Length L Ch R = 1,9662,1369,1369,1369
BEGIN DESCRIPTION:
Cottonwood Creek Trib01 9.4
END DESCRIPTION:
XS GIS Cut Line= 3
      1330327.91      6849427.64      1331449.83      6855849.46
      1334630.64      6859458.00
#Sta/Elev= 30
 -1505.2 2390.30 -1078.5 2389.72  -790.9 2385.69  -678.5 2387.12  -672.4 2389.06
  -652.1 2388.67  -627.3 2384.63  -591.2 2378.08  -564.6 2385.29  -530.7 2385.25
  -430.8 2384.33  -339.6 2384.28  3631.8 2378.01  4497.0 2378.78  4535.3 2380.37
  4555.6 2378.04  4664.2 2376.83  4738.3 2380.36  4765.1 2378.14  4921.2 2376.88
  4986.4 2376.65  4986.9 2376.15  5018.1 2376.65  6551.8 2378.02  6730.4 2378.57
  7681.5 2379.86  9161.1 2387.16  9798.6 2387.09  9820.4 2382.41  9824.2 2383.47
#Mann=14,-1,0
 -1505.2   0.045       0  -790.9   0.063       0  -627.3    0.07       0
  -530.7   0.035       0  -430.8    0.07       0  -339.6   0.045       0
  4497.0   0.063       0  4765.1   0.035       0  4921.2   0.045       0
  4986.4   0.045       0  5018.1   0.045       0  6551.8   0.035       0
  6730.4    0.07       0  7681.5   0.045       0
Bank Sta=4986.4,5018.1
Exp/Cntr=0.3,0.1

Type RM Length L Ch R = 1,8293,1061,1061,1061
BEGIN DESCRIPTION:
Cottonwood Creek Trib01 9.3
END DESCRIPTION:
XS GIS Cut Line= 3
      1330223.74      6849427.61      1330721.68      6856893.13
      1334216.74      6859587.24
#Sta/Elev= 30
 -2502.0 2390.51 -1824.0 2387.35 -1742.4 2387.72 -1689.8 2389.31 -1655.7 2384.68
 -1644.1 2381.21 -1629.7 2378.13 -1609.6 2385.86 -1545.7 2385.35  -126.3 2381.24
   -96.3 2382.59   705.5 2378.90  2116.5 2379.35  2169.5 2379.37  3611.9 2376.65
  3788.5 2378.37  3822.4 2379.66  3842.5 2377.72  3922.6 2378.35  3962.7 2376.42
  4012.8 2380.16  4090.4 2377.30  4243.0 2376.69  5081.3 2376.17  5082.1 2375.67
  5117.5 2376.17  6835.9 2378.02  7783.1 2380.45  8494.3 2385.95  9393.0 2385.65
#Mann=14,-1,0
 -2502.0   0.045       0 -1824.0   0.063       0 -1742.4    0.07       0
 -1644.1   0.035       0 -1545.7   0.045       0  2116.5    0.07       0
  2169.5   0.045       0  3788.5   0.063       0  4090.4   0.035       0
  4243.0   0.045       0  5081.3   0.045       0  5117.5   0.045       0
  6835.9    0.07       0  7783.1   0.045       0
Bank Sta=5081.3,5117.5
Exp/Cntr=0.3,0.1

Type RM Length L Ch R = 1,7232,1058,1058,1058
BEGIN DESCRIPTION:
Cottonwood Creek Trib01 9.2
END DESCRIPTION:
XS GIS Cut Line= 3
      1330057.07      6849427.59      1330357.61      6857851.85
      1333076.03      6860181.93
#Sta/Elev= 30
 -3423.2 2389.45 -2774.4 2387.31 -2670.1 2389.88 -2642.3 2389.97 -2582.3 2378.00
 -2572.0 2380.92 -2552.2 2386.63 -2473.9 2385.54  -571.0 2378.85  2588.7 2377.03
  2746.5 2376.72  3029.8 2377.74  3071.3 2379.87  3091.4 2377.16  3131.4 2379.08
  3211.4 2376.17  3271.5 2380.23  3314.8 2377.32  3481.6 2376.67  4253.7 2376.79
  4630.9 2376.23  4756.6 2376.07  4824.1 2376.03  4825.0 2375.53  4860.9 2376.03
  5366.7 2376.22  5496.2 2376.30  5553.2 2376.50  7264.4 2378.19  8586.8 2386.03
#Mann=18,-1,0
 -3423.2   0.045       0 -2774.4   0.063       0 -2670.1    0.07       0
 -2572.0   0.035       0 -2473.9   0.045       0  2588.7   0.035       0
  2746.5   0.045       0  3029.8   0.063       0  3314.8   0.035       0
  3481.6   0.045       0  4253.7    0.07       0  4630.9   0.045       0
  4756.6    0.07       0  4824.1    0.07       0  4860.9    0.07       0
  5366.7   0.045       0  5496.2   0.035       0  5553.2   0.045       0
Bank Sta=4824.1,4860.9
Exp/Cntr=0.3,0.1

Type RM Length L Ch R = 1,6174,1027,1027,1027
BEGIN DESCRIPTION:
Cottonwood Creek Trib01 9.1
END DESCRIPTION:
XS GIS Cut Line= 3
      1329973.74      6849448.46      1329799.37      6858677.08
      1332614.86      6861152.77
#Sta/Elev= 30
 -4238.7 2388.92 -3628.7 2387.55 -3559.0 2386.80 -3510.2 2390.09 -3479.0 2387.49
 -3439.0 2377.93 -3412.4 2386.13 -3314.5 2385.62 -1998.8 2382.58 -1058.6 2377.51
  1395.3 2376.88  1636.2 2377.01  2411.9 2378.53  2452.0 2380.21  2472.0 2377.96
  2512.0 2379.24  2582.1 2377.08  2644.4 2380.08  2702.1 2377.67  2833.8 2378.45
  4352.0 2376.00  4873.8 2375.53  4874.7 2375.03  4911.2 2375.53  5370.9 2375.96
  5466.9 2376.56  5480.8 2376.49  6725.2 2377.89  7716.7 2385.30  8740.7 2386.76
#Mann=16,-1,0
 -4238.7   0.045       0 -3628.7   0.063       0 -3510.2    0.07       0
 -3412.4   0.035       0 -3314.5   0.045       0  1395.3   0.035       0
  1636.2   0.045       0  2411.9   0.063       0  2644.4   0.035       0
  2833.8   0.045       0  4352.0    0.07       0  4873.8    0.07       0
  4911.2    0.07       0  5370.9   0.045       0  5466.9    0.07       0
  5480.8   0.045       0
Bank Sta=4873.8,4911.2
Exp/Cntr=0.3,0.1

Type RM Length L Ch R = 1,5147,547,547,547
BEGIN DESCRIPTION:
Cottonwood Creek Trib01 9.0
END DESCRIPTION:
XS GIS Cut Line= 3
      1329932.07      6849427.65      1328905.00      6859088.00
      1332505.04      6861088.02
#Sta/Elev= 30
 -4714.8 2388.75 -4094.9 2386.91 -3964.4 2389.93 -3909.9 2377.79 -3899.9 2378.71
 -3879.8 2387.42 -3866.3 2386.30 -3768.1 2385.61 -1697.5 2377.72  -374.2 2376.84
  -219.9 2376.83  -156.0 2376.83    60.4 2376.82  1361.5 2376.91  2327.8 2381.06
  2506.0 2378.36  2589.3 2381.58  2842.0 2378.84  4056.1 2376.00  4057.0 2375.50
  4093.6 2376.00  4183.3 2376.51  4193.8 2376.50  6119.9 2376.97  6160.6 2376.80
  7603.6 2381.53  7641.4 2381.90  7647.1 2384.54  7684.9 2382.68  9118.3 2385.91
#Mann=18,-1,0
 -4714.8   0.045       0 -4094.9   0.063       0 -3964.4    0.07       0
 -3866.3   0.035       0 -3768.1   0.045       0  -374.2   0.035       0
  -219.9   0.045       0  -156.0   0.035       0    60.4   0.045       0
  2327.8   0.063       0  2589.3   0.035       0  2842.0   0.045       0
  4056.1   0.045       0  4093.6   0.045       0  4183.3    0.07       0
  4193.8   0.045       0  6119.9   0.035       0  6160.6   0.045       0
Bank Sta=4056.1,4093.6
Exp/Cntr=0.3,0.1