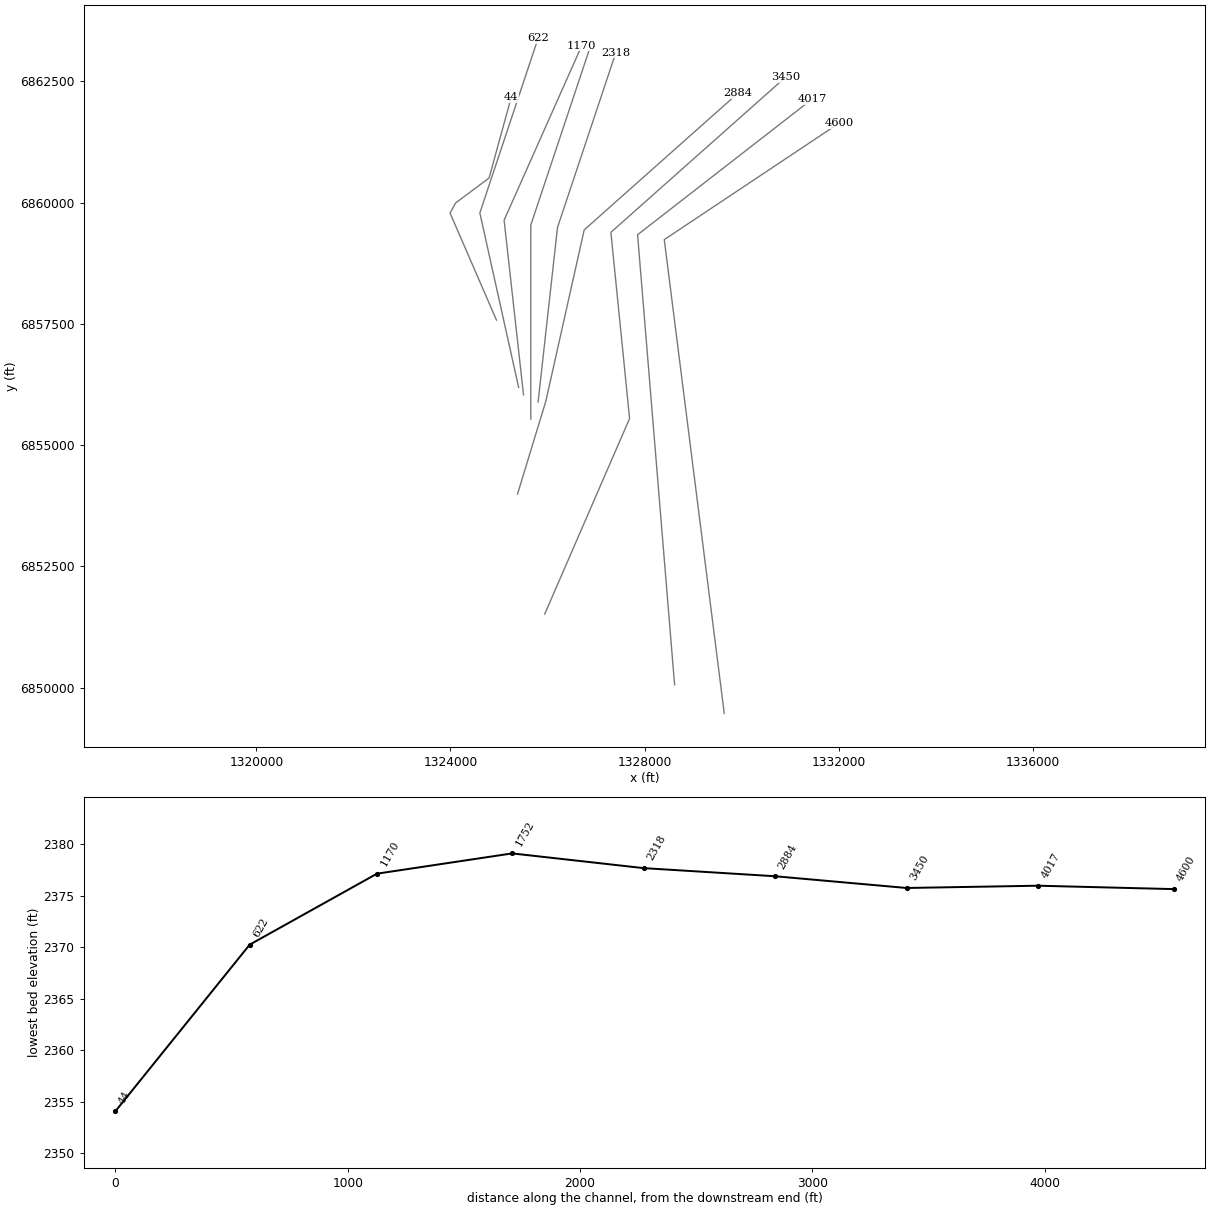
HEC-RAS study Cottonwood Creek Trib01.prj: Cottonwood Creek Trib01 Base Level Engineering

--- Cottonwood Creek Trib01.g01 (geometry) --- (continued)

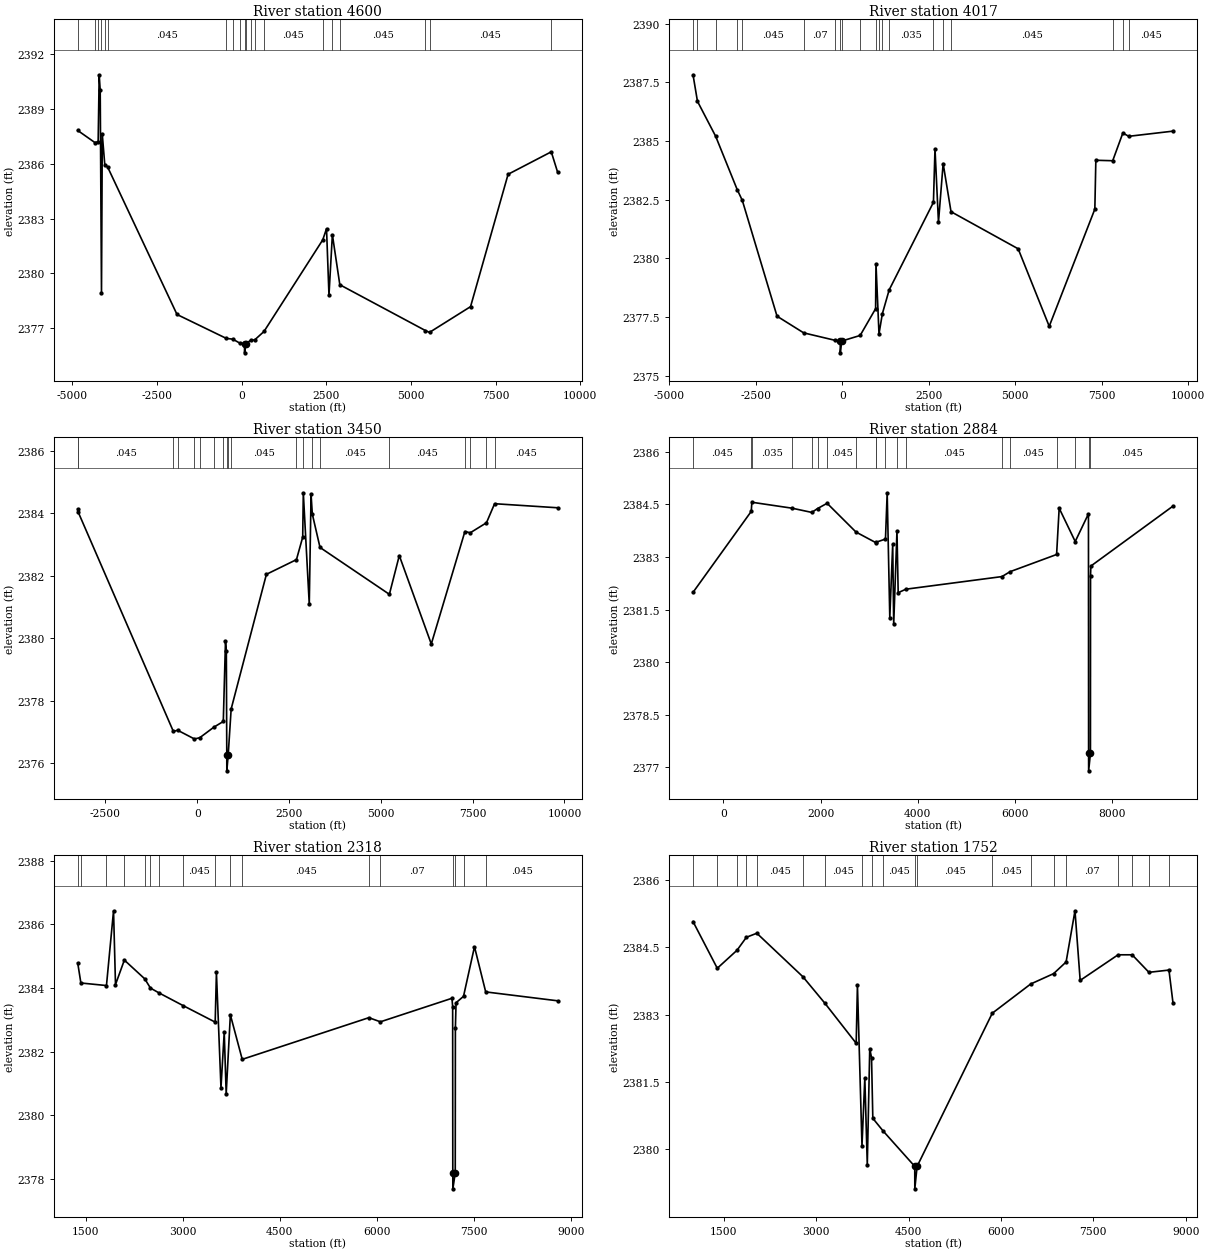
Type RM Length L Ch R = 1,4600,583,583,583
BEGIN DESCRIPTION:
Cottonwood Creek Trib01 8.0
END DESCRIPTION:
XS GIS Cut Line= 3
      1329640.41      6849469.30      1328405.00      6859238.00
      1332005.02      6861638.02
#Sta/Elev= 30
 -4841.5 2387.83 -4336.5 2387.17 -4238.2 2387.21 -4207.8 2390.88 -4177.6 2390.02
 -4139.8 2378.91 -4116.5 2387.62 -4041.5 2385.93 -3962.1 2385.84 -1909.6 2377.75
  -452.5 2376.44  -263.4 2376.40   -53.8 2376.18    83.4 2376.15    84.4 2375.65
   121.2 2376.15   266.4 2376.34   384.5 2376.36   658.9 2376.82  2394.3 2381.84
  2505.3 2382.45  2577.5 2378.81  2678.1 2382.12  2898.0 2379.38  5426.0 2376.87
  5546.1 2376.77  6758.2 2378.18  7866.9 2385.43  9141.9 2386.66  9331.7 2385.53
#Mann=20,-1,0
 -4841.5   0.045       0 -4336.5   0.035       0 -4238.2    0.07       0
 -4139.8   0.063       0 -4041.5   0.035       0 -3962.1   0.045       0
  -452.5    0.07       0  -263.4   0.045       0   -53.8    0.07       0
    83.4   0.045       0   121.2   0.045       0   266.4    0.07       0
   384.5   0.045       0   658.9   0.045       0  2394.3   0.063       0
  2678.1   0.035       0  2898.0   0.045       0  5426.0   0.035       0
  5546.1   0.045       0  9141.9   0.035       0
Bank Sta=83.4,121.2
Exp/Cntr=0.3,0.1

Type RM Length L Ch R = 1,4017,567,567,567
BEGIN DESCRIPTION:
Cottonwood Creek Trib01 7.0
END DESCRIPTION:
XS GIS Cut Line= 3
      1328617.57      6850057.81      1327855.00      6859338.00
      1331455.03      6862138.02
#Sta/Elev= 30
 -4312.1 2387.82 -4183.8 2386.69 -3657.3 2385.20 -3035.0 2382.93 -2887.2 2382.47
 -1883.8 2377.54 -1113.4 2376.83  -197.8 2376.51   -56.5 2376.48   -55.5 2375.98
   -18.7 2376.48   518.5 2376.72   964.9 2377.86   975.8 2379.77  1063.0 2376.79
  1161.0 2377.65  1357.0 2378.66  2636.6 2382.39  2681.6 2384.67  2781.9 2381.54
  2917.1 2384.04  3144.4 2381.99  5085.3 2380.41  5983.0 2377.11  7301.4 2382.10
  7330.4 2384.18  7817.7 2384.16  8110.7 2385.34  8281.6 2385.20  9560.1 2385.42
#Mann=20,-1,0
 -4312.1    0.07       0 -4183.8   0.045       0 -3657.3   0.045       0
 -3035.0   0.035       0 -2887.2   0.045       0 -1113.4    0.07       0
  -197.8   0.035       0   -56.5   0.045       0   -18.7    0.07       0
   518.5   0.045       0   964.9    0.07       0  1063.0   0.045       0
  1161.0   0.094       0  1357.0   0.035       0  2636.6   0.063       0
  2917.1   0.035       0  3144.4   0.045       0  7817.7   0.035       0
  8110.7   0.035       0  8281.6   0.045       0
Bank Sta=-56.5,-18.7
Exp/Cntr=0.3,0.1

Type RM Length L Ch R = 1,3450,566,566,566
BEGIN DESCRIPTION:
Cottonwood Creek Trib01 6.0
END DESCRIPTION:
XS GIS Cut Line= 4
      1325941.55      6851516.66      1327690.35      6855549.49
      1327305.00      6859388.00      1330904.98      6862587.98
#Sta/Elev= 30
 -3253.4 2384.14 -3243.6 2384.05  -648.7 2377.02  -533.8 2377.06   -74.7 2376.78
    69.1 2376.82   456.9 2377.16   710.4 2377.34   770.1 2379.90   793.4 2379.60
   805.6 2376.26   806.6 2375.76   843.5 2376.26   924.6 2377.74  1884.5 2382.05
  2702.5 2382.52  2873.0 2383.24  2889.5 2384.66  3051.6 2381.09  3100.6 2384.61
  3134.4 2383.98  3344.3 2382.91  5233.0 2381.41  5503.1 2382.65  6374.4 2379.82
  7289.7 2383.42  7436.2 2383.38  7876.8 2383.70  8098.2 2384.31  9816.7 2384.18
#Mann=20,-1,0
 -3253.4   0.063       0 -3243.6   0.045       0  -648.7   0.035       0
  -533.8    0.07       0   -74.7   0.035       0    69.1    0.07       0
   456.9   0.045       0   710.4    0.07       0   805.6   0.045       0
   843.5    0.07       0   924.6   0.045       0  2702.5    0.07       0
  2873.0   0.063       0  3134.4   0.035       0  3344.3   0.045       0
  5233.0   0.045       0  7289.7   0.035       0  7436.2   0.045       0
  7876.8    0.07       0  8098.2   0.045       0
Bank Sta=805.6,843.5
Exp/Cntr=0.3,0.1

Type RM Length L Ch R = 1,2884,566,566,566
BEGIN DESCRIPTION:
Cottonwood Creek Trib01 5.0
END DESCRIPTION:
XS GIS Cut Line= 4
      1325381.22      6853991.06      1325964.05      6855903.30
      1326755.00      6859438.00      1329926.38      6862259.61
#Sta/Elev= 30
  -621.2 2381.99   576.1 2384.30   588.3 2384.56  1416.4 2384.39  1820.3 2384.27
  1938.3 2384.38  2135.3 2384.53  2729.0 2383.71  3133.7 2383.41  3142.6 2383.42
  3334.8 2383.51  3369.9 2384.83  3423.6 2381.27  3483.4 2383.36  3503.9 2381.08
  3571.2 2383.74  3596.1 2381.98  3753.1 2382.08  5729.2 2382.44  5896.8 2382.58
  6852.5 2383.07  6905.2 2384.39  7235.1 2383.44  7507.3 2384.23  7510.1 2377.40
  7511.1 2376.90  7548.0 2377.40  7549.9 2382.47  7556.6 2382.74  9244.9 2384.45
#Mann=19,-1,0
  -621.2   0.045       0   576.1    0.07       0   588.3   0.035       0
  1416.4    0.07       0  1820.3   0.035       0  1938.3    0.07       0
  2135.3   0.045       0  2729.0    0.07       0  3133.7   0.045       0
  3142.6    0.07       0  3334.8   0.063       0  3571.2   0.035       0
  3753.1   0.045       0  5729.2   0.035       0  5896.8   0.045       0
  6852.5   0.035       0  7235.1   0.045       0  7510.1   0.045       0
  7548.0   0.045       0
Bank Sta=7510.1,7548
Exp/Cntr=0.3,0.1

Type RM Length L Ch R = 1,2318,566,566,566
BEGIN DESCRIPTION:
Cottonwood Creek Trib01 4.0
END DESCRIPTION:
XS GIS Cut Line= 3
      1325805.00      6855887.96      1326205.00      6859488.00
      1327404.99      6863087.97
#Sta/Elev= 30
  1377.8 2384.79  1426.5 2384.16  1821.8 2384.08  1931.2 2386.43  1961.4 2384.11
  2098.2 2384.88  2413.7 2384.29  2501.7 2384.00  2632.5 2383.85  3005.7 2383.45
  3501.9 2382.93  3521.0 2384.49  3591.4 2380.87  3641.7 2382.61  3671.9 2380.68
  3736.4 2383.16  3919.7 2381.76  5876.5 2383.07  6055.1 2382.94  7160.9 2383.68
  7171.4 2383.41  7173.6 2378.19  7174.6 2377.69  7211.5 2378.19  7213.6 2382.73
  7224.1 2383.54  7339.2 2383.74  7508.7 2385.30  7682.0 2383.88  8794.7 2383.60
#Mann=17,-1,0
  1377.8   0.035       0  1426.5    0.07       0  1821.8   0.035       0
  2098.2   0.045       0  2413.7    0.07       0  2501.7   0.045       0
  2632.5    0.07       0  3005.7   0.045       0  3501.9   0.063       0
  3736.4   0.035       0  3919.7   0.045       0  5876.5   0.035       0
  6055.1    0.07       0  7173.6   0.045       0  7211.5    0.07       0
  7339.2   0.035       0  7682.0   0.045       0
Bank Sta=7173.6,7211.5
Exp/Cntr=0.3,0.1

Type RM Length L Ch R = 1,1752,582,582,582
BEGIN DESCRIPTION:
Cottonwood Creek Trib01 3.0
END DESCRIPTION:
XS GIS Cut Line= 3
      1325655.00      6855538.01      1325655.00      6859538.00
      1326854.99      6863137.98
#Sta/Elev= 30
  1000.1 2385.07  1394.1 2384.03  1713.9 2384.43  1867.0 2384.72  2036.4 2384.81
  2785.6 2383.84  3142.7 2383.25  3650.1 2382.36  3670.1 2383.66  3744.1 2380.08
  3790.1 2381.59  3830.1 2379.66  3870.1 2382.24  3899.2 2382.04  3920.1 2380.69
  4086.0 2380.41  4601.1 2379.62  4602.1 2379.12  4639.1 2379.62  5860.3 2383.03
  6483.9 2383.68  6855.1 2383.91  7059.0 2384.17  7203.1 2385.31  7287.5 2383.76
  7902.8 2384.33  8131.4 2384.33  8404.2 2383.94  8729.2 2383.99  8794.8 2383.26
#Mann=20,-1,0
  1000.1    0.07       0  1394.1   0.035       0  1713.9    0.07       0
  1867.0   0.035       0  2036.4   0.045       0  2785.6    0.07       0
  3142.7   0.045       0  3744.1   0.063       0  3899.2   0.035       0
  4086.0   0.045       0  4601.1   0.045       0  4639.1   0.045       0
  5860.3   0.045       0  6483.9    0.07       0  6855.1   0.045       0
  7059.0    0.07       0  7902.8   0.045       0  8131.4   0.045       0
  8404.2   0.035       0  8729.2   0.045       0
Bank Sta=4601.1,4639.1
Exp/Cntr=0.3,0.1

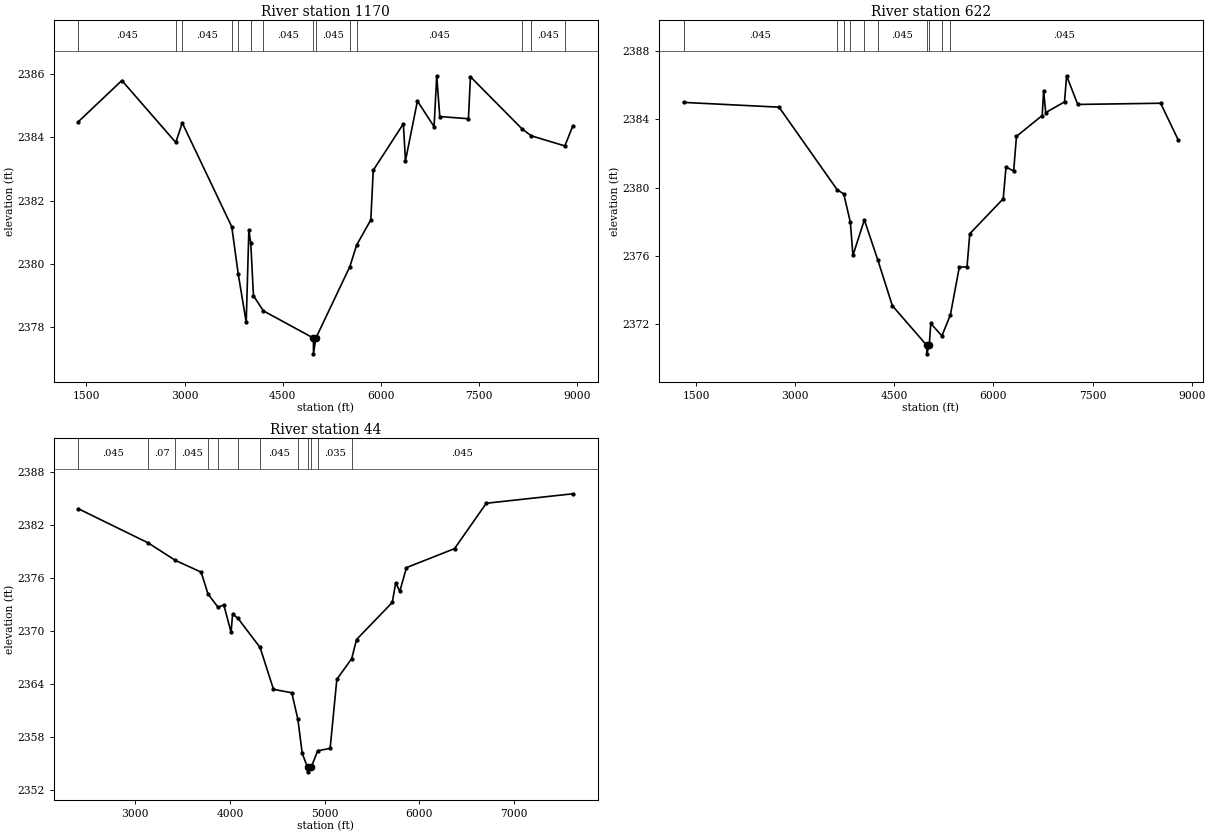
Type RM Length L Ch R = 1,1170,548,548,548
BEGIN DESCRIPTION:
Cottonwood Creek Trib01 2.0
END DESCRIPTION:
XS GIS Cut Line= 3
      1325505.00      6856038.02      1325105.00      6859638.00
      1326705.01      6863238.02
#Sta/Elev= 30
  1378.2 2384.50  2042.2 2385.80  2867.1 2383.84  2966.0 2384.46  3723.1 2381.17
  3821.3 2379.68  3943.9 2378.15  3984.1 2381.06  4013.6 2380.65  4054.5 2378.99
  4206.4 2378.51  4971.3 2377.65  4972.3 2377.15  5009.3 2377.65  5528.8 2379.91
  5632.0 2380.59  5849.1 2381.39  5886.7 2382.96  6347.0 2384.43  6379.2 2383.26
  6561.8 2385.15  6816.9 2384.34  6857.3 2385.95  6903.8 2384.66  7342.2 2384.59
  7372.9 2385.92  8166.4 2384.26  8304.0 2384.05  8816.7 2383.73  8939.9 2384.37
#Mann=14,-1,0
  1378.2   0.045       0  2867.1    0.07       0  2966.0   0.045       0
  3723.1   0.035       0  3821.3   0.063       0  4013.6   0.035       0
  4206.4   0.045       0  4971.3   0.045       0  5009.3   0.045       0
  5528.8   0.035       0  5632.0   0.045       0  8166.4    0.07       0
  8304.0   0.045       0  8816.7   0.035       0
Bank Sta=4971.3,5009.3
Exp/Cntr=0.3,0.1

Type RM Length L Ch R = 1,622,578,578,578
BEGIN DESCRIPTION:
Cottonwood Creek Trib01 1.0
END DESCRIPTION:
XS GIS Cut Line= 3
      1325405.01      6856187.97      1324605.00      6859788.00
      1325805.01      6863388.02
#Sta/Elev= 30
  1311.8 2384.99  2756.2 2384.71  3636.0 2379.87  3735.7 2379.62  3835.4 2377.96
  3874.1 2376.02  4047.2 2378.10  4249.5 2375.77  4470.8 2373.07  4991.2 2370.75
  4992.2 2370.25  5029.2 2370.75  5052.4 2372.03  5220.6 2371.30  5349.5 2372.54
  5484.5 2375.34  5600.5 2375.34  5642.6 2377.29  6148.6 2379.34  6190.8 2381.20
  6306.7 2380.97  6348.9 2383.00  6738.9 2384.22  6760.0 2385.68  6791.6 2384.39
  7076.2 2385.02  7107.8 2386.55  7276.5 2384.87  8530.9 2384.94  8794.4 2382.81
#Mann=10,-1,0
  1311.8   0.045       0  3636.0    0.07       0  3735.7   0.035       0
  3835.4   0.063       0  4047.2   0.035       0  4249.5   0.045       0
  4991.2   0.045       0  5029.2   0.045       0  5220.6   0.035       0
  5349.5   0.045       0
Bank Sta=4991.2,5029.2
Exp/Cntr=0.3,0.1

Type RM Length L Ch R = 1,44,0,0,0
BEGIN DESCRIPTION:
Cottonwood Creek Trib01 0.5
END DESCRIPTION:
XS GIS Cut Line= 5
      1324947.52      6857578.39      1323991.77      6859785.06
      1324105.06      6859992.09      1324795.60      6860508.10
      1325251.34      6862168.29
#Sta/Elev= 30
  2399.3 2383.84  3135.7 2379.98  3423.2 2378.00  3695.7 2376.67  3768.3 2374.19
  3873.8 2372.70  3935.4 2372.95  4011.7 2369.87  4028.3 2371.92  4084.5 2371.44
  4318.4 2368.14  4460.1 2363.40  4653.4 2363.01  4717.3 2360.03  4763.7 2356.16
  4819.9 2354.56  4820.9 2354.06  4858.0 2354.56  4926.7 2356.44  5058.5 2356.72
  5129.4 2364.53  5286.5 2366.88  5337.8 2369.04  5715.1 2373.24  5751.5 2375.46
  5794.3 2374.49  5865.1 2377.18  6372.9 2379.33  6708.8 2384.47  7623.7 2385.54
#Mann=12,-1,0
  2399.3   0.045       0  3135.7    0.07       0  3423.2   0.045       0
  3768.3   0.035       0  3873.8   0.063       0  4084.5   0.035       0
  4318.4   0.045       0  4717.3    0.07       0  4819.9   0.035       0
  4858.0    0.07       0  4926.7   0.035       0  5286.5   0.045       0
Bank Sta=4819.9,4858
Exp/Cntr=0.3,0.1

Chan Stop Cuts=-1