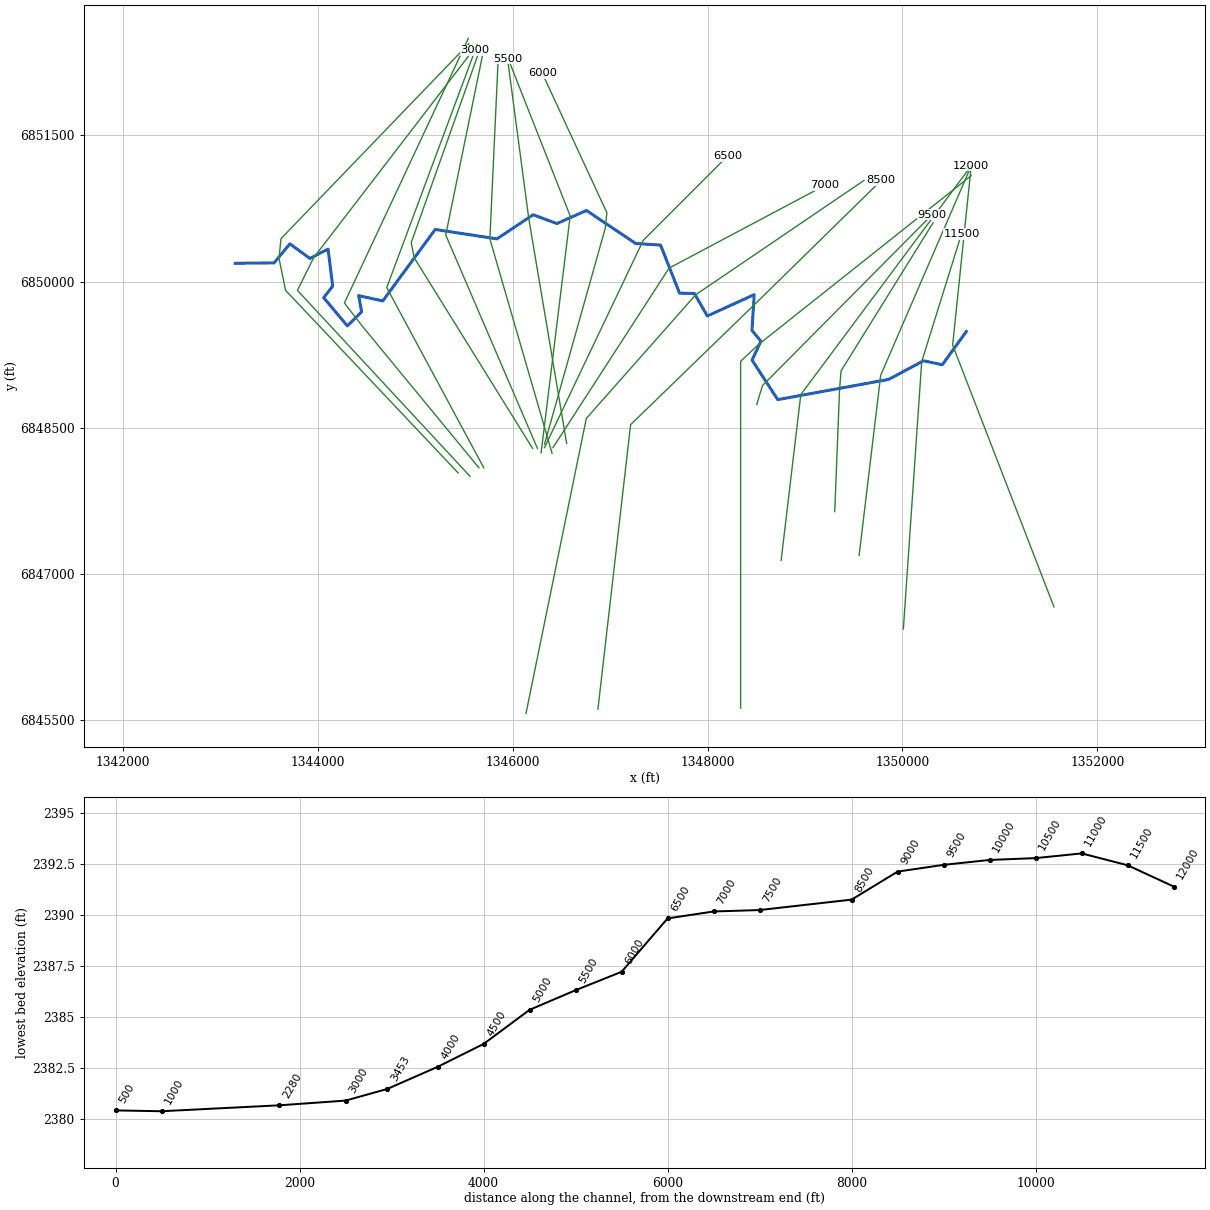
--- Cottonwood Creek Trib01_10.prj (project) ---

Proj Title=Cottonwood Creek Trib01_10 Base Level Engineering
Current Plan=p01
Default Exp/Contr=0.3,0.1
English Units
Geom File=g01
Flow File=f01
Plan File=p01
BEGIN DESCRIPTION:
Cottonwood Creek Trib01_10
END DESCRIPTION:

--- Cottonwood Creek Trib01_10.p01 (plan) ---

Plan Title=Multiple Run
Short Identifier=Multiple
Geom File=g01
Flow File=f01
Subcritical Flow
K Sum by GR= 0
Std Step Tol= 0.01
Critical Tol= 0.01
Num of Std Step Trials= 20
Max Error Tol= 0.3
Flow Tol Ratio= 0.001
Split Flow NTrial= 30
Split Flow Tol= 0.02
Split Flow Ratio= 0.02
Log Output Level= 0
Friction Slope Method= 1
Unsteady Friction Slope Method= 2
Unsteady Bridges Friction Slope Method= 1
Parabolic Critical Depth
Global Vel Dist=  1 , 1 , 1
Global Log Level= 0
CheckData=True
Encroach Param= -1, 0, 0, 0
BEGIN DESCRIPTION:
Multiple Run
END DESCRIPTION:

--- Cottonwood Creek Trib01_10.f01 (steady flow) ---

Flow Title=Multiple
Number of Profiles=7
Profile Names=10-year,25-year,50-year,1pct_min,100-year,1pct_plu,500-year
River Rch & RM= Cottonwood Creek,Reach-1,12000
      98     126     147      85     170     339     230
River Rch & RM= Cottonwood Creek,Reach-1,9500
     161     213     253     149     297     593     417
River Rch & RM= Cottonwood Creek,Reach-1,1000
     166     220     262     154     308     614     432
Boundary for River Rch & Prof#=Cottonwood Creek,Reach-1,1
Up Type=0
Dn Type=3
Dn Slope=0.005
Boundary for River Rch & Prof#=Cottonwood Creek,Reach-1,2
Up Type=0
Dn Type=3
Dn Slope=0.005
Boundary for River Rch & Prof#=Cottonwood Creek,Reach-1,3
Up Type=0
Dn Type=3
Dn Slope=0.005
Boundary for River Rch & Prof#=Cottonwood Creek,Reach-1,4
Up Type=0
Dn Type=3
Dn Slope=0.005
Boundary for River Rch & Prof#=Cottonwood Creek,Reach-1,5
Up Type=0
Dn Type=3
Dn Slope=0.005
Boundary for River Rch & Prof#=Cottonwood Creek,Reach-1,6
Up Type=0
Dn Type=3
Dn Slope=0.005
Boundary for River Rch & Prof#=Cottonwood Creek,Reach-1,7
Up Type=0
Dn Type=3
Dn Slope=0.005

--- Cottonwood Creek Trib01_10.g01 (geometry) ---

Geom Title=Existing Conditions

River Reach=Cottonwood Creek,Reach-1
Reach XY= 30
      1350655.00      6849488.00      1350408.45      6849145.79
      1350215.50      6849186.81      1349858.40      6848995.83
      1348720.36      6848788.01      1348456.63      6849194.04
      1348547.70      6849388.08      1348455.61      6849498.62
      1348478.83      6849865.82      1347998.01      6849646.82
      1347864.70      6849877.80      1347712.81      6849881.17
      1347518.36      6850374.60      1347263.50      6850390.72
      1346758.23      6850729.77      1346454.92      6850595.30
      1346210.94      6850685.75      1345839.97      6850438.33
      1345206.65      6850534.90      1344668.72      6849801.16
      1344421.22      6849855.60      1344451.87      6849689.63
      1344305.00      6849545.07      1344062.84      6849834.77
      1344154.62      6849953.16      1344107.61      6850333.04
      1343920.36      6850237.89      1343715.49      6850387.52
      1343553.54      6850191.52      1343155.00      6850188.00

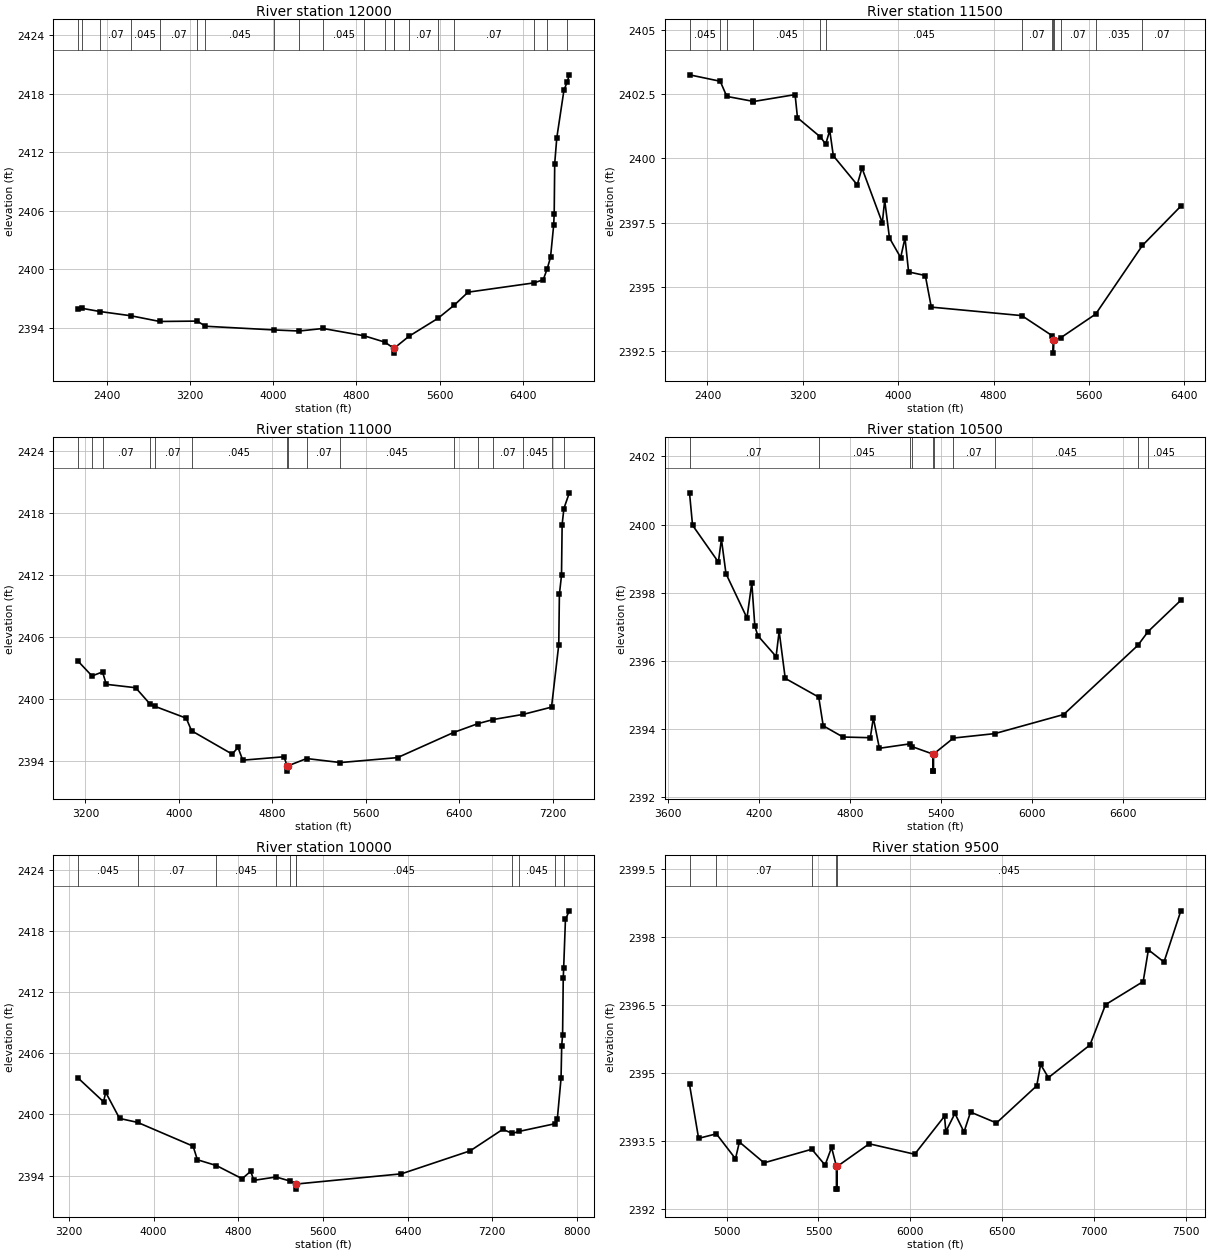
Type RM Length L Ch R = 1,12000,500,500,500
BEGIN DESCRIPTION:
Cottonwood Creek Trib01_10 23.0
END DESCRIPTION:
XS GIS Cut Line= 3
      1351553.98      6846660.02      1350514.50      6849348.25
      1350705.00      6851188.01
#Sta/Elev= 30
  2117.8 2395.95  2151.9 2395.99  2331.0 2395.65  2626.1 2395.22  2905.5 2394.63
  3265.9 2394.67  3345.6 2394.14  4010.3 2393.76  4247.1 2393.65  4477.8 2393.91
  4873.7 2393.16  5072.9 2392.51  5158.6 2391.88  5158.9 2391.38  5162.6 2391.88
  5305.3 2393.11  5585.5 2394.96  5743.7 2396.33  5874.4 2397.64  6506.7 2398.59
  6598.3 2398.91  6637.5 2400.07  6668.6 2401.23  6698.8 2404.51  6703.9 2405.65
  6708.9 2410.85  6728.9 2413.49  6797.7 2418.37  6829.7 2419.25  6849.6 2419.96
#Mann=20,-1,0
  2117.8   0.035       0  2151.9   0.045       0  2331.0    0.07       0
  2626.1   0.045       0  2905.5    0.07       0  3265.9   0.035       0
  3345.6   0.045       0  4010.3    0.07       0  4247.1   0.045       0
  4477.8   0.045       0  4873.7    0.07       0  5072.9   0.035       0
  5158.6    0.07       0  5162.6   0.035       0  5305.3    0.07       0
  5585.5   0.035       0  5743.7    0.07       0  6506.7   0.045       0
  6637.5   0.035       0  6829.7   0.094       0
Bank Sta=5158.6,5162.6
Exp/Cntr=0.3,0.1

Type RM Length L Ch R = 1,11500,500,500,500
BEGIN DESCRIPTION:
Cottonwood Creek Trib01_10 22.0
END DESCRIPTION:
XS GIS Cut Line= 3
      1350008.83      6846434.30      1350197.11      6849178.55
      1350605.00      6850487.99
#Sta/Elev= 30
  2249.3 2403.25  2506.9 2403.00  2562.0 2402.41  2780.9 2402.22  2783.5 2402.21
  3135.1 2402.48  3155.1 2401.58  3347.7 2400.83  3392.0 2400.55  3425.8 2401.09
  3455.8 2400.10  3656.3 2398.97  3696.4 2399.62  3866.8 2397.49  3886.8 2398.37
  3926.9 2396.90  4020.8 2396.14  4057.2 2396.90  4087.3 2395.58  4227.6 2395.44
  4277.8 2394.21  5036.9 2393.88  5294.6 2393.09  5301.2 2392.92  5301.4 2392.42
  5305.2 2392.92  5364.4 2393.02  5657.0 2393.94  6048.9 2396.61  6371.5 2398.14
#Mann=14,-1,0
  2249.3   0.045       0  2506.9    0.07       0  2562.0   0.045       0
  2780.9    0.07       0  2783.5   0.045       0  3347.7   0.035       0
  3392.0   0.045       0  5036.9    0.07       0  5294.6   0.035       0
  5301.2   0.045       0  5305.2   0.035       0  5364.4    0.07       0
  5657.0   0.035       0  6048.9    0.07       0
Bank Sta=5301.2,5305.2
Exp/Cntr=0.3,0.1

Type RM Length L Ch R = 1,11000,500,500,500
BEGIN DESCRIPTION:
Cottonwood Creek Trib01_10 21.0
END DESCRIPTION:
XS GIS Cut Line= 3
      1349555.00      6847188.01      1349776.24      6849038.13
      1350705.00      6851187.99
#Sta/Elev= 30
  3136.7 2403.66  3256.5 2402.22  3346.8 2402.61  3378.4 2401.41  3630.2 2401.08
  3752.6 2399.51  3794.3 2399.28  4063.2 2398.13  4108.7 2396.91  4456.0 2394.65
  4506.4 2395.29  4546.7 2394.06  4899.2 2394.39  4927.4 2393.50  4927.6 2393.00
  4931.4 2393.50  5093.9 2394.22  5382.8 2393.83  5871.8 2394.31  6350.9 2396.74
  6559.5 2397.60  6691.3 2398.00  6948.1 2398.50  7189.6 2399.20  7251.5 2405.24
  7256.9 2410.13  7275.0 2411.96  7280.4 2416.89  7295.6 2418.44  7341.9 2419.96
#Mann=16,-1,0
  3136.7    0.07       0  3256.5   0.045       0  3346.8    0.07       0
  3752.6   0.045       0  3794.3    0.07       0  4108.7   0.045       0
  4927.4   0.045       0  4931.4   0.045       0  5093.9    0.07       0
  5382.8   0.045       0  6350.9    0.07       0  6559.5   0.045       0
  6691.3    0.07       0  6948.1   0.045       0  7189.6   0.035       0
  7295.6   0.094       0
Bank Sta=4927.4,4931.4
Exp/Cntr=0.3,0.1

Type RM Length L Ch R = 1,10500,500,500,500
BEGIN DESCRIPTION:
Cottonwood Creek Trib01_10 20.0
END DESCRIPTION:
XS GIS Cut Line= 4
      1349305.00      6847638.00      1349354.32      6848892.63
      1349369.95      6849083.63      1350313.94      6850603.73
#Sta/Elev= 30
  3744.4 2400.93  3764.4 2399.98  3934.5 2398.90  3954.6 2399.57  3984.6 2398.56
  4123.0 2397.26  4154.7 2398.29  4174.7 2397.02  4194.7 2396.74  4314.8 2396.13
  4334.9 2396.87  4374.9 2395.49  4595.5 2394.94  4625.1 2394.10  4755.2 2393.77
  4935.3 2393.75  4955.3 2394.33  4995.2 2393.44  5197.2 2393.57  5209.4 2393.49
  5347.8 2393.27  5348.1 2392.77  5351.6 2392.77  5351.8 2393.27  5483.3 2393.74
  5755.2 2393.87  6209.1 2394.43  6698.2 2396.46  6764.7 2396.86  6981.0 2397.78
#Mann=10,-1,0
  3744.4    0.07       0  4595.5   0.045       0  5197.2    0.07       0
  5209.4   0.045       0  5347.8   0.045       0  5351.8   0.045       0
  5483.3    0.07       0  5755.2   0.045       0  6698.2    0.07       0
  6764.7   0.045       0
Bank Sta=5347.8,5351.8
Exp/Cntr=0.3,0.1

Type RM Length L Ch R = 1,10000,500,500,500
BEGIN DESCRIPTION:
Cottonwood Creek Trib01_10 19.0
END DESCRIPTION:
XS GIS Cut Line= 3
      1348755.00      6847138.04      1348956.86      6848840.01
      1350705.00      6851188.01
#Sta/Elev= 30
  3286.1 2403.58  3527.7 2401.24  3547.9 2402.17  3678.8 2399.61  3849.8 2399.22
  4373.6 2396.89  4413.9 2395.56  4593.9 2394.99  4836.9 2393.70  4917.4 2394.43
  4947.6 2393.54  5157.0 2393.87  5286.9 2393.48  5344.6 2393.18  5344.8 2392.68
  5348.6 2393.18  6341.3 2394.18  6992.0 2396.44  7298.5 2398.54  7389.7 2398.14
  7449.5 2398.33  7795.3 2399.10  7813.7 2399.53  7849.1 2403.54  7855.3 2406.74
  7863.7 2407.76  7869.9 2413.33  7873.8 2414.33  7890.8 2419.13  7927.3 2419.96
#Mann=11,-1,0
  3286.1   0.045       0  3849.8    0.07       0  4593.9   0.045       0
  5157.0    0.07       0  5286.9   0.045       0  5344.6   0.045       0
  5348.6   0.045       0  7389.7    0.07       0  7449.5   0.045       0
  7795.3   0.035       0  7873.8   0.094       0
Bank Sta=5344.6,5348.6
Exp/Cntr=0.3,0.1

Type RM Length L Ch R = 1,9500,500,500,500
BEGIN DESCRIPTION:
Cottonwood Creek Trib01_10 18.0
END DESCRIPTION:
XS GIS Cut Line= 3
      1348504.99      6848737.98      1348563.31      6848931.69
      1350305.01      6850688.01
#Sta/Elev= 30
  4797.7 2394.75  4847.2 2393.56  4943.9 2393.66  5048.1 2393.11  5069.3 2393.48
  5203.7 2393.02  5463.7 2393.32  5536.0 2392.97  5571.4 2393.36  5597.7 2392.94
  5597.9 2392.44  5601.4 2392.44  5601.7 2392.94  5776.4 2393.44  6023.9 2393.21
  6186.5 2394.05  6193.6 2393.71  6243.1 2394.11  6292.6 2393.70  6328.0 2394.14
  6469.4 2393.90  6688.6 2394.72  6709.8 2395.19  6752.2 2394.90  6978.5 2395.62
  7063.4 2396.51  7268.4 2397.02  7296.7 2397.72  7381.6 2397.45  7473.5 2398.58
#Mann=5,-1,0
  4797.7   0.045       0  4943.9    0.07       0  5463.7   0.045       0
  5597.7    0.07       0  5601.7   0.045       0
Bank Sta=5597.7,5601.7
Exp/Cntr=0.3,0.1

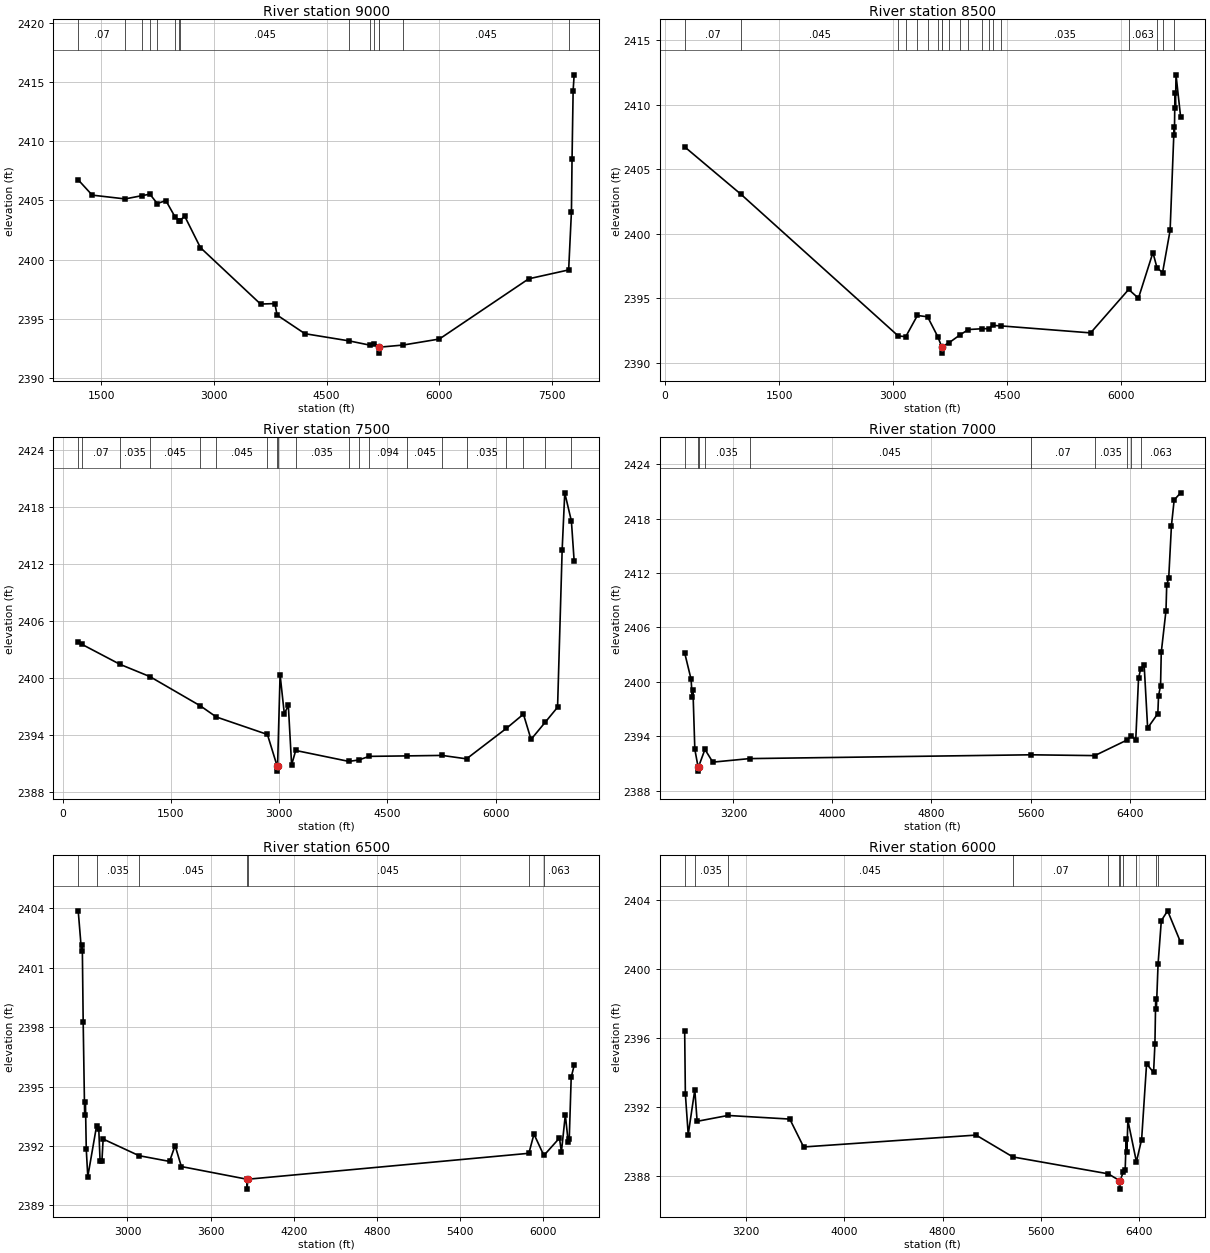
Type RM Length L Ch R = 1,9000,500,500,500
BEGIN DESCRIPTION:
Cottonwood Creek Trib01_10 17.0
END DESCRIPTION:
XS GIS Cut Line= 4
      1348339.52      6845621.90      1348339.52      6849180.97
      1348518.31      6849349.83      1350705.03      6851088.03
#Sta/Elev= 30
  1195.0 2406.73  1381.1 2405.44  1819.9 2405.12  2037.5 2405.39  2148.9 2405.52
  2246.8 2404.73  2361.1 2404.98  2481.7 2403.62  2541.1 2403.29  2547.3 2403.28
  2611.1 2403.67  2821.1 2401.01  3621.1 2396.25  3811.1 2396.29  3841.1 2395.32
  4211.1 2393.75  4801.5 2393.14  5078.1 2392.78  5134.5 2392.91  5193.9 2392.61
  5194.1 2392.11  5197.9 2392.61  5515.5 2392.79  6000.0 2393.30  7188.6 2398.38
  7720.2 2399.13  7757.3 2404.05  7765.3 2408.47  7779.8 2414.26  7793.4 2415.59
#Mann=15,-1,0
  1195.0    0.07       0  1819.9   0.045       0  2037.5    0.07       0
  2148.9   0.045       0  2246.8    0.07       0  2481.7   0.045       0
  2541.1    0.07       0  2547.3   0.045       0  4801.5    0.07       0
  5078.1   0.045       0  5134.5    0.07       0  5193.9    0.07       0
  5197.9    0.07       0  5515.5   0.045       0  7720.2   0.035       0
Bank Sta=5193.9,5197.9
Exp/Cntr=0.3,0.1

Type RM Length L Ch R = 1,8500,1000,1000,1000
BEGIN DESCRIPTION:
Cottonwood Creek Trib01_10 16.0
END DESCRIPTION:
XS GIS Cut Line= 4
      1346875.68      6845610.88      1347211.05      6848531.09
      1348505.41      6849787.26      1349780.68      6851037.94
#Sta/Elev= 30
   256.9 2406.74   998.5 2403.06  3068.9 2392.07  3167.8 2392.02  3320.6 2393.66
  3454.8 2393.56  3589.0 2392.02  3640.4 2391.24  3640.7 2390.74  3644.5 2391.24
  3733.6 2391.53  3878.3 2392.14  3991.6 2392.57  4167.8 2392.63  4259.9 2392.64
  4312.6 2392.89  4426.9 2392.85  5601.4 2392.31  6102.2 2395.68  6230.7 2395.00
  6421.6 2398.54  6475.5 2397.36  6548.7 2396.99  6647.9 2400.27  6700.5 2408.29
  6704.5 2407.69  6711.5 2410.90  6718.6 2409.73  6725.6 2412.33  6786.2 2409.06
#Mann=20,-1,0
   256.9    0.07       0   998.5   0.045       0  3068.9   0.063       0
  3167.8   0.063       0  3320.6   0.063       0  3454.8   0.063       0
  3589.0   0.063       0  3640.4   0.035       0  3644.5   0.063       0
  3733.6   0.063       0  3878.3   0.063       0  3991.6   0.035       0
  4167.8   0.094       0  4259.9   0.035       0  4312.6   0.094       0
  4426.9   0.035       0  6102.2   0.063       0  6475.5   0.035       0
  6548.7   0.094       0  6700.5   0.063       0
Bank Sta=3640.4,3644.5
Exp/Cntr=0.3,0.1

Type RM Length L Ch R = 1,7500,500,500,500
BEGIN DESCRIPTION:
Cottonwood Creek Trib01_10 14.0
END DESCRIPTION:
XS GIS Cut Line= 4
      1346137.83      6845567.44      1346756.32      6848594.79
      1347878.96      6849864.86      1349605.02      6851038.02
#Sta/Elev= 30
   215.0 2403.84   268.3 2403.54   792.9 2401.45  1207.8 2400.16  1908.5 2397.08
  2127.8 2395.92  2836.8 2394.08  2972.6 2390.73  2972.9 2390.23  2977.4 2390.73
  3012.2 2400.36  3070.9 2396.25  3126.5 2397.13  3171.9 2390.88  3228.5 2392.40
  3965.7 2391.25  4101.2 2391.40  4245.9 2391.78  4769.6 2391.83  5257.8 2391.88
  5595.9 2391.52  6149.4 2394.73  6384.2 2396.21  6489.7 2393.56  6685.7 2395.36
  6857.2 2396.94  6920.9 2413.50  6956.8 2419.46  7048.9 2416.49  7087.0 2412.29
#Mann=20,-1,0
   215.0   0.045       0   268.3    0.07       0   792.9   0.035       0
  1207.8   0.045       0  1908.5    0.07       0  2127.8   0.045       0
  2836.8   0.063       0  2972.6   0.045       0  2977.4   0.094       0
  3228.5   0.035       0  3965.7   0.094       0  4101.2   0.094       0
  4245.9   0.094       0  4769.6   0.045       0  5257.8   0.035       0
  5595.9   0.035       0  6149.4   0.094       0  6384.2   0.035       0
  6685.7   0.063       0  7048.9   0.094       0
Bank Sta=2972.6,2977.4
Exp/Cntr=0.3,0.1

Type RM Length L Ch R = 1,7000,500,500,500
BEGIN DESCRIPTION:
Cottonwood Creek Trib01_10 13.0
END DESCRIPTION:
XS GIS Cut Line= 3
      1346414.59      6848295.53      1347604.91      6850137.73
      1349205.03      6850988.01
#Sta/Elev= 30
  2806.7 2403.19  2858.4 2400.28  2867.6 2398.30  2873.5 2399.08  2888.7 2392.56
  2914.3 2390.66  2914.7 2390.16  2919.2 2390.66  2970.3 2392.55  3033.8 2391.15
  3330.2 2391.54  5605.0 2391.96  6118.9 2391.87  6377.9 2393.58  6412.9 2394.08
  6449.6 2393.59  6472.2 2400.40  6488.3 2401.36  6517.5 2401.86  6545.7 2394.91
  6628.0 2396.50  6633.6 2398.44  6650.0 2399.59  6655.6 2403.24  6693.9 2407.86
  6699.6 2410.65  6715.9 2411.45  6737.9 2417.22  6759.9 2420.04  6812.0 2420.83
#Mann=10,-1,0
  2806.7   0.094       0  2914.3   0.045       0  2919.2   0.094       0
  2970.3   0.035       0  3330.2   0.045       0  5605.0    0.07       0
  6118.9   0.035       0  6377.9   0.063       0  6412.9   0.094       0
  6488.3   0.063       0
Bank Sta=2914.3,2919.2
Exp/Cntr=0.3,0.1

Type RM Length L Ch R = 1,6500,500,500,500
BEGIN DESCRIPTION:
Cottonwood Creek Trib01_10 12.0
END DESCRIPTION:
XS GIS Cut Line= 3
      1346327.81      6848295.57      1347339.83      6850422.37
      1348205.03      6851288.03
#Sta/Elev= 30
  2644.7 2403.88  2668.5 2401.84  2674.1 2402.17  2680.6 2398.25  2691.2 2393.54
  2696.8 2394.24  2702.8 2391.84  2713.8 2390.45  2776.9 2393.00  2793.2 2392.84
  2802.4 2391.26  2815.9 2391.25  2824.6 2392.35  3083.5 2391.51  3303.9 2391.22
  3343.8 2392.02  3389.2 2390.96  3863.1 2390.32  3863.5 2389.82  3868.0 2390.32
  5897.1 2391.63  5933.9 2392.60  6005.4 2391.52  6117.8 2392.40  6131.9 2391.70
  6160.2 2393.57  6181.4 2392.18  6188.5 2392.34  6202.6 2395.47  6223.9 2396.07
#Mann=7,-1,0
  2644.7   0.094       0  2776.9   0.035       0  3083.5   0.045       0
  3863.1   0.045       0  3868.0   0.045       0  5897.1    0.07       0
  6005.4   0.063       0
Bank Sta=3863.1,3868
Exp/Cntr=0.3,0.1

Type RM Length L Ch R = 1,6000,500,500,500
BEGIN DESCRIPTION:
Cottonwood Creek Trib01_10 11.0
END DESCRIPTION:
XS GIS Cut Line= 4
      1346327.80      6848330.29      1346950.19      6850545.10
      1346967.56      6850706.72      1346305.02      6852137.96
#Sta/Elev= 30
  2699.4 2396.37  2704.9 2392.75  2728.2 2390.38  2781.8 2392.98  2800.9 2391.15
  3051.9 2391.49  3555.8 2391.28  3668.4 2389.66  5073.3 2390.35  5373.0 2389.08
  6149.5 2388.10  6241.4 2387.71  6241.8 2387.21  6246.3 2387.71  6273.1 2388.20
  6287.9 2388.32  6296.4 2390.13  6301.9 2389.35  6310.0 2391.21  6379.6 2388.80
  6422.0 2390.09  6462.4 2394.49  6519.4 2393.99  6530.4 2395.66  6536.6 2398.28
  6542.2 2397.67  6556.0 2400.29  6582.5 2402.81  6633.8 2403.38  6739.7 2401.55
#Mann=11,-1,0
  2699.4   0.094       0  2781.8   0.035       0  3051.9   0.045       0
  5373.0    0.07       0  6149.5   0.035       0  6241.4   0.045       0
  6246.3   0.035       0  6273.1   0.063       0  6379.6   0.094       0
  6542.2   0.063       0  6556.0   0.094       0
Bank Sta=6241.4,6246.3
Exp/Cntr=0.3,0.1

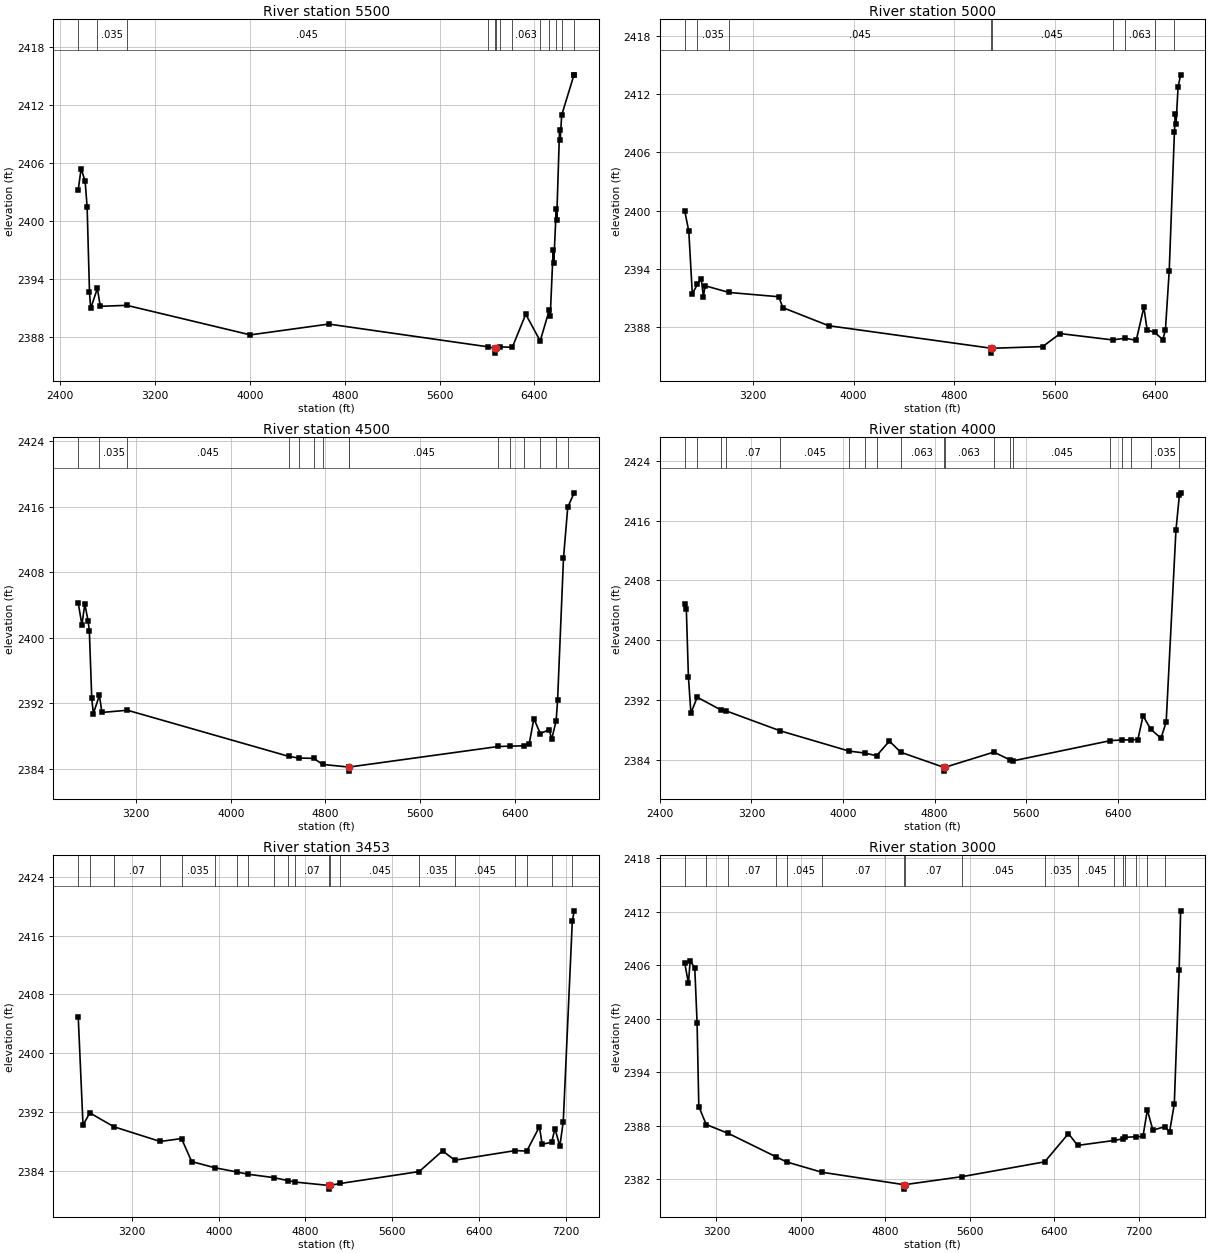
Type RM Length L Ch R = 1,5500,500,500,500
BEGIN DESCRIPTION:
Cottonwood Creek Trib01_10 10.0
END DESCRIPTION:
XS GIS Cut Line= 3
      1346293.08      6848243.47      1346591.06      6850673.78
      1345955.01      6852287.98
#Sta/Elev= 30
  2551.5 2403.22  2576.2 2405.43  2609.9 2404.11  2626.6 2401.46  2646.7 2392.62
  2656.8 2390.94  2713.2 2393.02  2737.4 2391.16  2961.7 2391.26  4003.5 2388.20
  4664.7 2389.32  6005.0 2386.97  6067.9 2386.81  6068.3 2386.31  6072.9 2386.81
  6109.1 2386.96  6213.3 2386.91  6326.6 2390.34  6448.6 2387.57  6525.6 2390.78
  6533.3 2390.13  6557.7 2396.96  6563.1 2395.68  6583.9 2401.24  6587.5 2400.08
  6611.8 2409.42  6617.2 2408.35  6629.7 2410.96  6733.8 2415.14  6735.0 2415.14
#Mann=13,-1,0
  2551.5   0.094       0  2713.2   0.035       0  2961.7   0.045       0
  6005.0   0.094       0  6067.9   0.045       0  6072.9   0.094       0
  6109.1   0.035       0  6213.3   0.063       0  6448.6   0.035       0
  6525.6   0.063       0  6583.9   0.035       0  6629.7   0.063       0
  6733.8   0.094       0
Bank Sta=6067.9,6072.9
Exp/Cntr=0.3,0.1

Type RM Length L Ch R = 1,5000,500,500,500
BEGIN DESCRIPTION:
Cottonwood Creek Trib01_10 9.0
END DESCRIPTION:
XS GIS Cut Line= 3
      1346555.00      6848338.03      1346165.83      6850649.90
      1345955.00      6852237.97
#Sta/Elev= 30
  2655.6 2400.00  2688.4 2397.88  2716.4 2391.45  2757.2 2392.43  2787.4 2393.00
  2804.4 2391.15  2817.8 2392.28  3009.5 2391.59  3404.8 2391.15  3436.4 2390.03
  3801.5 2388.17  5096.5 2385.85  5096.9 2385.35  5101.5 2385.85  5503.9 2386.02
  5643.7 2387.36  6060.6 2386.71  6159.0 2386.88  6249.0 2386.67  6309.5 2390.07
  6335.4 2387.74  6394.6 2387.48  6460.8 2386.75  6481.0 2387.74  6511.2 2393.79
  6552.7 2408.07  6560.3 2409.92  6565.4 2408.92  6581.9 2412.73  6602.0 2413.98
#Mann=9,-1,0
  2655.6   0.094       0  2757.2   0.035       0  3009.5   0.045       0
  5096.5   0.045       0  5101.5   0.045       0  6060.6   0.035       0
  6159.0   0.063       0  6394.6   0.035       0  6552.7   0.063       0
Bank Sta=5096.5,5101.5
Exp/Cntr=0.3,0.1

Type RM Length L Ch R = 1,4500,500,500,500
BEGIN DESCRIPTION:
Cottonwood Creek Trib01_10 8.0
END DESCRIPTION:
XS GIS Cut Line= 3
      1346405.00      6848238.01      1345767.17      6850437.81
      1345855.00      6852337.98
#Sta/Elev= 30
  2709.6 2404.24  2740.8 2401.55  2765.2 2404.10  2792.9 2402.07  2803.9 2400.77
  2824.1 2392.56  2837.5 2390.72  2889.1 2392.94  2909.9 2390.85  3125.8 2391.12
  4490.4 2385.48  4573.2 2385.28  4702.0 2385.24  4775.2 2384.50  4994.9 2384.18
  4995.3 2383.68  5000.0 2384.18  6261.2 2386.69  6357.4 2386.73  6474.1 2386.78
  6521.8 2387.00  6561.9 2390.09  6615.9 2388.27  6692.0 2388.75  6712.0 2387.56
  6750.0 2389.83  6762.1 2392.34  6812.1 2409.72  6848.1 2415.93  6902.2 2417.69
#Mann=15,-1,0
  2709.6   0.094       0  2889.1   0.035       0  3125.8   0.045       0
  4490.4   0.035       0  4573.2   0.045       0  4702.0   0.035       0
  4775.2   0.045       0  4994.9   0.045       0  5000.0   0.045       0
  6261.2   0.063       0  6357.4   0.035       0  6474.1   0.063       0
  6615.9   0.035       0  6750.0   0.063       0  6848.1   0.094       0
Bank Sta=4994.9,5000
Exp/Cntr=0.3,0.1

Type RM Length L Ch R = 1,4000,547,547,547
BEGIN DESCRIPTION:
Cottonwood Creek Trib01_10 7.0
END DESCRIPTION:
XS GIS Cut Line= 3
      1346255.00      6848288.00      1345314.40      6850478.27
      1345705.01      6852388.04
#Sta/Elev= 30
  2616.3 2404.83  2630.8 2404.14  2648.9 2395.16  2670.7 2390.31  2725.8 2392.42
  2931.3 2390.74  2978.2 2390.60  3450.6 2387.94  4054.0 2385.23  4187.8 2384.98
  4293.1 2384.61  4404.8 2386.57  4503.7 2385.08  4882.3 2383.06  4882.7 2382.56
  4887.5 2383.06  5318.0 2385.10  5462.1 2384.03  5485.4 2383.93  6335.7 2386.63
  6436.2 2386.72  6511.6 2386.73  6575.8 2386.78  6621.2 2389.94  6688.0 2388.16
  6777.7 2386.95  6823.1 2389.11  6908.4 2414.69  6938.8 2419.44  6949.3 2419.70
#Mann=19,-1,0
  2616.3   0.094       0  2725.8   0.035       0  2931.3   0.045       0
  2978.2    0.07       0  3450.6   0.045       0  4054.0   0.035       0
  4187.8   0.045       0  4293.1   0.035       0  4503.7   0.063       0
  4882.3   0.063       0  4887.5   0.063       0  5318.0   0.045       0
  5462.1   0.035       0  5485.4   0.045       0  6335.7   0.063       0
  6436.2   0.035       0  6511.6   0.063       0  6688.0   0.035       0
  6938.8   0.063       0
Bank Sta=4882.3,4887.5
Exp/Cntr=0.3,0.1

Type RM Length L Ch R = 1,3453,453,453,453
BEGIN DESCRIPTION:
Cottonwood Creek Trib01_10 6.0
END DESCRIPTION:
XS GIS Cut Line= 4
      1346204.97      6848288.04      1344991.00      6850244.34
      1344960.61      6850400.59      1345668.08      6852392.77
#Sta/Elev= 30
  2703.1 2404.97  2747.4 2390.20  2810.2 2391.86  3032.5 2389.97  3459.3 2387.97
  3656.2 2388.36  3750.1 2385.23  3964.0 2384.39  4165.4 2383.82  4269.7 2383.51
  4505.3 2383.05  4640.7 2382.63  4705.2 2382.44  5016.7 2381.98  5017.1 2381.48
  5022.1 2381.98  5120.8 2382.25  5849.0 2383.87  6064.2 2386.69  6177.7 2385.42
  6736.8 2386.73  6841.4 2386.66  6958.2 2389.97  6983.7 2387.58  7071.3 2387.87
  7101.8 2389.73  7146.3 2387.32  7178.1 2390.63  7261.6 2417.92  7278.7 2419.37
#Mann=20,-1,0
  2703.1   0.094       0  2810.2   0.035       0  3032.5    0.07       0
  3459.3   0.035       0  3656.2   0.035       0  3964.0   0.045       0
  4165.4    0.07       0  4269.7    0.07       0  4505.3    0.07       0
  4640.7   0.045       0  4705.2    0.07       0  5016.7    0.07       0
  5022.1    0.07       0  5120.8   0.045       0  5849.0   0.035       0
  6177.7   0.045       0  6736.8   0.063       0  6841.4   0.063       0
  7071.3   0.035       0  7261.6   0.063       0
Bank Sta=5016.7,5022.1
Exp/Cntr=0.3,0.1

Type RM Length L Ch R = 1,3000,720,720,720
BEGIN DESCRIPTION:
Cottonwood Creek Trib01_10 5.0
END DESCRIPTION:
XS GIS Cut Line= 3
      1345704.99      6848088.01      1344709.41      6849938.15
      1345615.54      6852374.18
#Sta/Elev= 30
  2899.0 2406.28  2934.7 2403.98  2950.9 2406.51  2994.7 2405.69  3016.6 2399.54
  3032.9 2390.17  3103.0 2388.15  3313.5 2387.15  3767.3 2384.52  3864.1 2383.96
  4200.0 2382.80  4977.5 2381.41  4977.9 2380.91  4983.0 2381.41  5527.9 2382.31
  6311.4 2383.97  6536.2 2387.14  6622.5 2385.81  6966.9 2386.36  7051.7 2386.55
  7072.5 2386.72  7178.0 2386.78  7242.4 2386.82  7283.6 2389.78  7336.4 2387.52
  7450.7 2387.91  7494.2 2387.30  7539.2 2390.46  7585.2 2405.46  7599.1 2412.10
#Mann=17,-1,0
  2899.0   0.094       0  3103.0   0.035       0  3313.5    0.07       0
  3767.3   0.035       0  3864.1   0.045       0  4200.0    0.07       0
  4977.5    0.07       0  4983.0    0.07       0  5527.9   0.045       0
  6311.4   0.035       0  6622.5   0.045       0  6966.9   0.035       0
  7051.7   0.045       0  7072.5   0.063       0  7178.0   0.035       0
  7283.6   0.063       0  7450.7   0.035       0
Bank Sta=4977.5,4983
Exp/Cntr=0.3,0.1

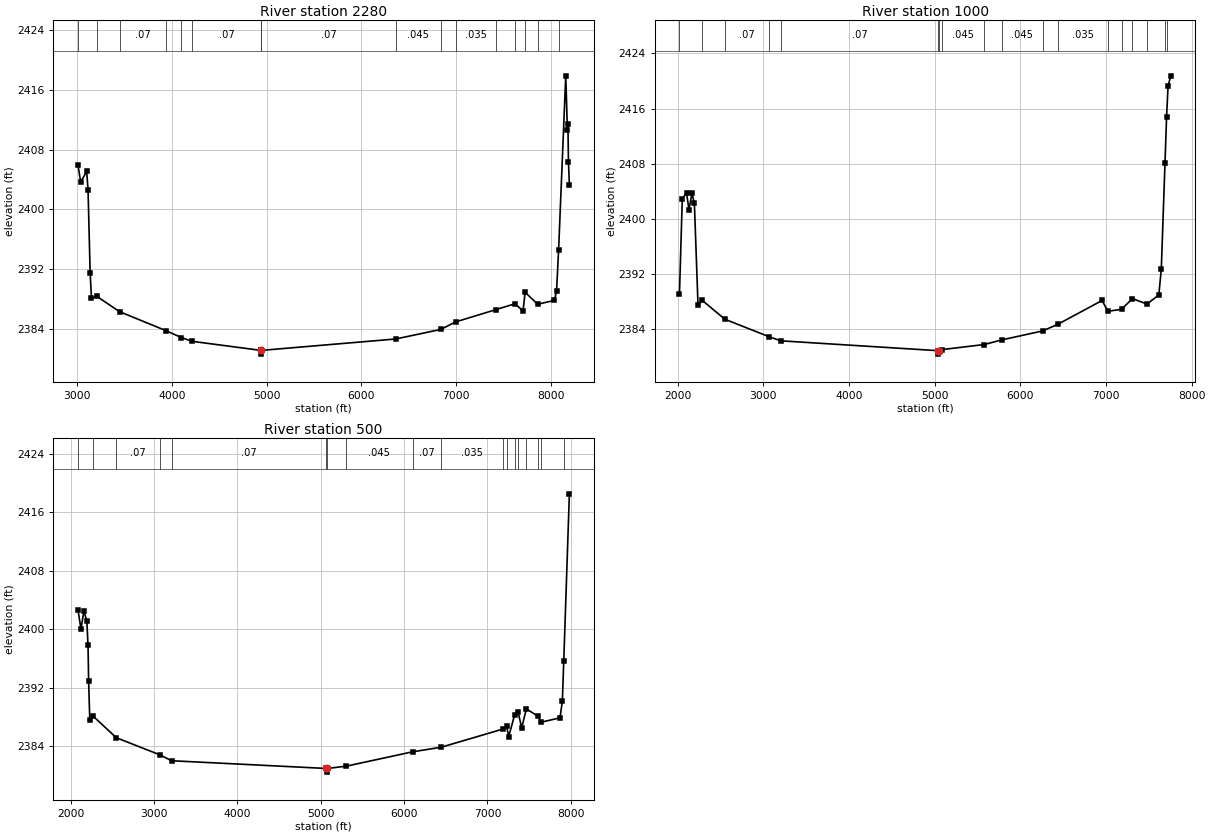
Type RM Length L Ch R = 1,2280,1280,1280,1280
BEGIN DESCRIPTION:
Cottonwood Creek Trib01_10 4.0
END DESCRIPTION:
XS GIS Cut Line= 4
      1345654.99      6848088.01      1344452.80      6849549.89
      1344274.85      6849779.93      1345546.53      6852496.90
#Sta/Elev= 30
  3010.6 2405.95  3038.6 2403.67  3102.4 2405.08  3116.8 2402.56  3139.0 2391.49
  3153.0 2388.12  3208.9 2388.40  3449.5 2386.35  3943.4 2383.79  4100.6 2382.90
  4214.2 2382.39  4940.1 2381.18  4940.5 2380.68  4945.7 2381.18  6360.6 2382.70
  6837.9 2383.98  6993.4 2384.98  7420.5 2386.63  7617.7 2387.40  7705.3 2386.48
  7727.2 2388.94  7859.5 2387.34  8036.1 2387.86  8058.9 2389.14  8080.2 2394.56
  8155.8 2417.85  8173.1 2410.64  8178.6 2411.37  8184.2 2406.35  8194.0 2403.31
#Mann=16,-1,0
  3010.6   0.094       0  3208.9   0.035       0  3449.5    0.07       0
  3943.4   0.035       0  4100.6   0.045       0  4214.2    0.07       0
  4940.1    0.07       0  4945.7    0.07       0  6360.6   0.045       0
  6837.9    0.07       0  6993.4   0.035       0  7420.5   0.063       0
  7617.7   0.035       0  7727.2   0.063       0  7859.5   0.035       0
  8080.2   0.094       0
Bank Sta=4940.1,4945.7
Exp/Cntr=0.3,0.1

Type RM Length L Ch R = 1,1000,500,500,500
BEGIN DESCRIPTION:
Cottonwood Creek Trib01_10 2.0
END DESCRIPTION:
XS GIS Cut Line= 4
      1345563.93      6848000.40      1343793.08      6849910.14
      1343959.00      6850244.18      1345637.82      6852431.23
#Sta/Elev= 30
  2022.6 2389.10  2055.6 2402.90  2104.9 2403.81  2133.3 2401.36  2169.0 2403.70
  2196.8 2402.28  2239.3 2387.46  2285.5 2388.22  2552.4 2385.45  3069.7 2382.91
  3204.3 2382.32  5039.6 2380.89  5040.1 2380.39  5045.7 2380.89  5086.7 2381.05
  5577.8 2381.78  5786.5 2382.46  6262.2 2383.76  6438.3 2384.72  6954.2 2388.17
  7022.4 2386.61  7181.3 2386.89  7307.5 2388.44  7478.7 2387.66  7616.8 2388.97
  7645.8 2392.77  7688.8 2408.12  7707.1 2414.76  7724.7 2419.30  7757.1 2420.76
#Mann=18,-1,0
  2022.6   0.094       0  2285.5   0.035       0  2552.4    0.07       0
  3069.7   0.035       0  3204.3    0.07       0  5039.6    0.07       0
  5045.7    0.07       0  5086.7   0.045       0  5577.8    0.07       0
  5786.5   0.045       0  6262.2    0.07       0  6438.3   0.035       0
  7022.4   0.063       0  7181.3   0.035       0  7307.5   0.063       0
  7478.7   0.035       0  7688.8   0.094       0  7707.1   0.063       0
Bank Sta=5039.6,5045.7
Exp/Cntr=0.3,0.1

Type RM Length L Ch R = 1,500,0,0,0
BEGIN DESCRIPTION:
Cottonwood Creek Trib01_10 1.0
END DESCRIPTION:
XS GIS Cut Line= 5
      1345442.39      6848035.13      1343671.55      6849910.14
      1343604.49      6850236.77      1343623.81      6850439.65
      1345550.54      6852441.60
#Sta/Elev= 30
  2087.5 2402.64  2123.0 2400.03  2158.6 2402.47  2193.8 2401.10  2207.9 2397.77
  2215.2 2392.86  2229.0 2387.57  2272.8 2388.05  2546.8 2385.14  3073.1 2382.78
  3210.2 2381.99  5068.5 2380.93  5069.0 2380.43  5074.6 2380.93  5303.6 2381.24
  6101.7 2383.21  6442.0 2383.83  7187.0 2386.33  7228.2 2386.75  7254.6 2385.30
  7326.6 2388.31  7366.8 2388.68  7409.9 2386.49  7466.3 2389.08  7605.9 2388.09
  7644.0 2387.26  7869.7 2387.86  7898.0 2390.15  7914.7 2395.58  7982.3 2418.51
#Mann=18,-1,0
  2087.5   0.094       0  2272.8   0.035       0  2546.8    0.07       0
  3073.1   0.035       0  3210.2    0.07       0  5068.5    0.07       0
  5074.6    0.07       0  5303.6   0.045       0  6101.7    0.07       0
  6442.0   0.035       0  7187.0   0.063       0  7228.2   0.035       0
  7326.6   0.063       0  7366.8   0.035       0  7466.3   0.094       0
  7605.9   0.063       0  7644.0   0.035       0  7914.7   0.094       0
Bank Sta=5068.5,5074.6
Exp/Cntr=0.3,0.1

Chan Stop Cuts=-1