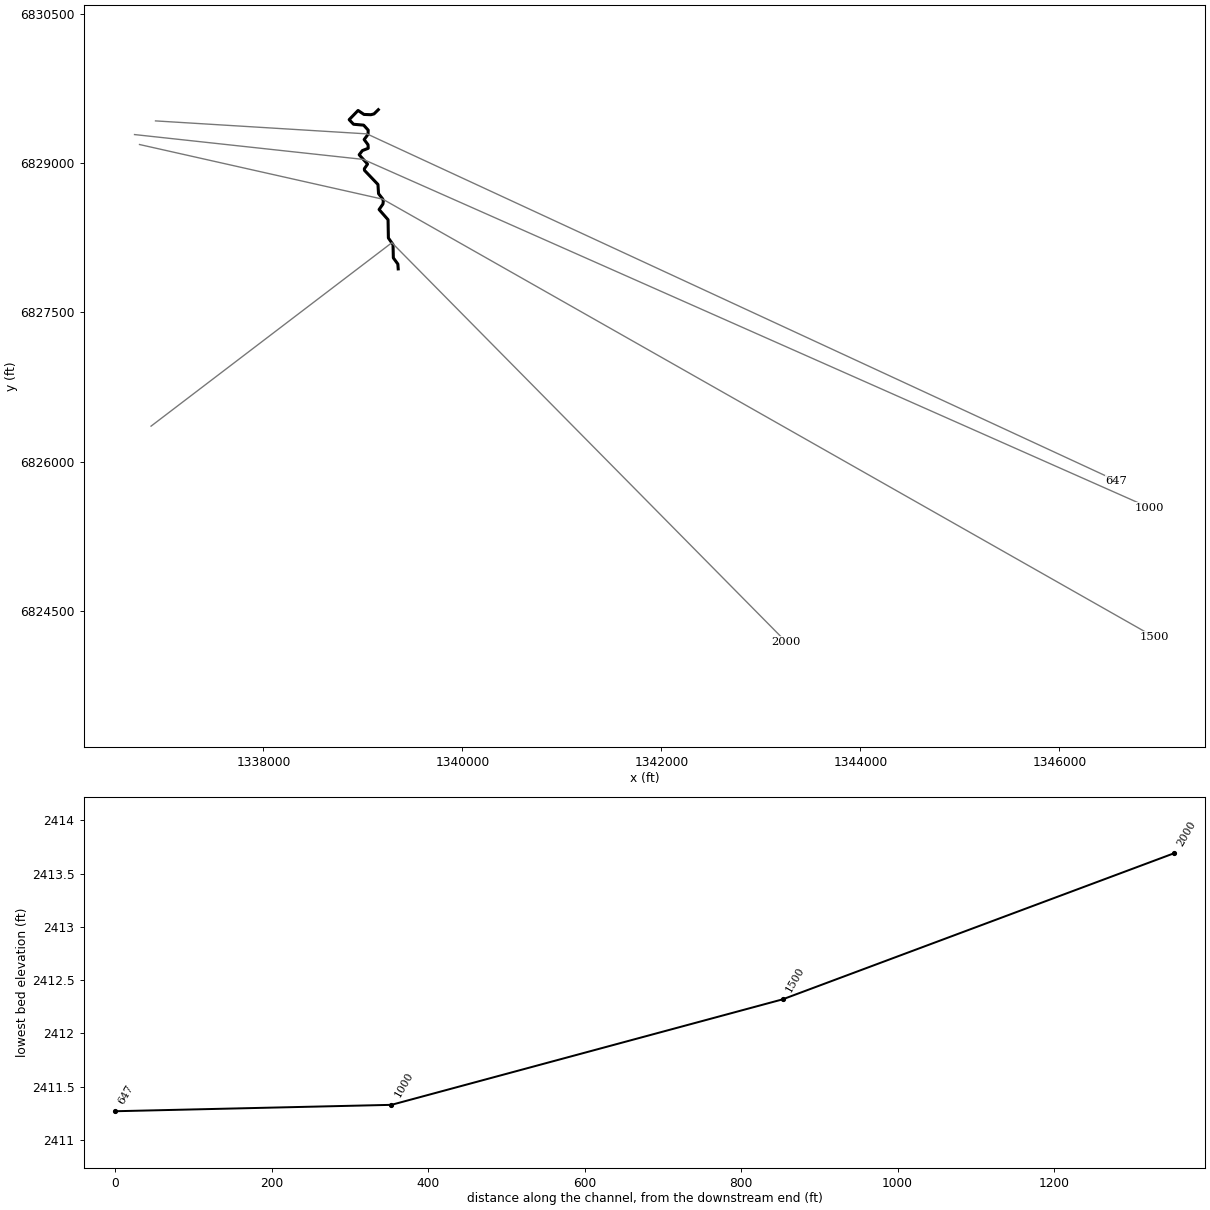
--- Cottonwood Creek Trib01_31.prj (project) ---

Proj Title=Cottonwood Creek Trib01_31 Base Level Engineering
Current Plan=p01
Default Exp/Contr=0.3,0.1
English Units
Geom File=g01
Flow File=f01
Plan File=p01
BEGIN DESCRIPTION:
Cottonwood Creek Trib01_31
END DESCRIPTION:

--- Cottonwood Creek Trib01_31.p01 (plan) ---

Plan Title=Multiple Run
Short Identifier=Multiple
Geom File=g01
Flow File=f01
Subcritical Flow
K Sum by GR= 0
Std Step Tol= 0.01
Critical Tol= 0.01
Num of Std Step Trials= 20
Max Error Tol= 0.3
Flow Tol Ratio= 0.001
Split Flow NTrial= 30
Split Flow Tol= 0.02
Split Flow Ratio= 0.02
Log Output Level= 0
Friction Slope Method= 1
Unsteady Friction Slope Method= 2
Unsteady Bridges Friction Slope Method= 1
Parabolic Critical Depth
Global Vel Dist=  1 , 1 , 1
Global Log Level= 0
CheckData=True
Encroach Param= -1, 0, 0, 0
BEGIN DESCRIPTION:
Multiple Run
END DESCRIPTION:

--- Cottonwood Creek Trib01_31.f01 (steady flow) ---

Flow Title=Multiple
Number of Profiles=7
Profile Names=10-year,25-year,50-year,1pct_min,100-year,1pct_plu,500-year
River Rch & RM= Cottonwood Creek,Reach-1,2000
     281     397     494     305     609    1214     937
Boundary for River Rch & Prof#=Cottonwood Creek,Reach-1,1
Up Type=0
Dn Type=3
Dn Slope=0.005
Boundary for River Rch & Prof#=Cottonwood Creek,Reach-1,2
Up Type=0
Dn Type=3
Dn Slope=0.005
Boundary for River Rch & Prof#=Cottonwood Creek,Reach-1,3
Up Type=0
Dn Type=3
Dn Slope=0.005
Boundary for River Rch & Prof#=Cottonwood Creek,Reach-1,4
Up Type=0
Dn Type=3
Dn Slope=0.005
Boundary for River Rch & Prof#=Cottonwood Creek,Reach-1,5
Up Type=0
Dn Type=3
Dn Slope=0.005
Boundary for River Rch & Prof#=Cottonwood Creek,Reach-1,6
Up Type=0
Dn Type=3
Dn Slope=0.005
Boundary for River Rch & Prof#=Cottonwood Creek,Reach-1,7
Up Type=0
Dn Type=3
Dn Slope=0.005

--- Cottonwood Creek Trib01_31.g01 (geometry) ---

Geom Title=Existing Conditions

River Reach=Cottonwood Creek,Reach-1
Reach XY= 30
      1339355.00      6827938.00      1339351.35      6827986.49
      1339306.13      6828048.47      1339302.73      6828182.06
      1339256.22      6828248.51      1339252.92      6828432.15
      1339162.83      6828534.60      1339201.38      6828589.63
      1339205.21      6828617.79      1339199.60      6828640.17
      1339157.38      6828693.97      1339151.39      6828786.50
      1339016.24      6828928.00      1339014.62      6828944.67
      1339046.97      6828991.33      1338962.57      6829084.84
      1338994.91      6829127.11      1339053.74      6829150.03
      1339051.57      6829185.99      1339012.64      6829237.97
      1339051.44      6829289.68      1339053.43      6829332.15
      1339007.74      6829382.58      1338906.01      6829391.62
      1338861.97      6829437.78      1338951.55      6829530.21
      1339010.88      6829490.37      1339080.00      6829487.53
      1339111.32      6829495.36      1339155.00      6829538.00

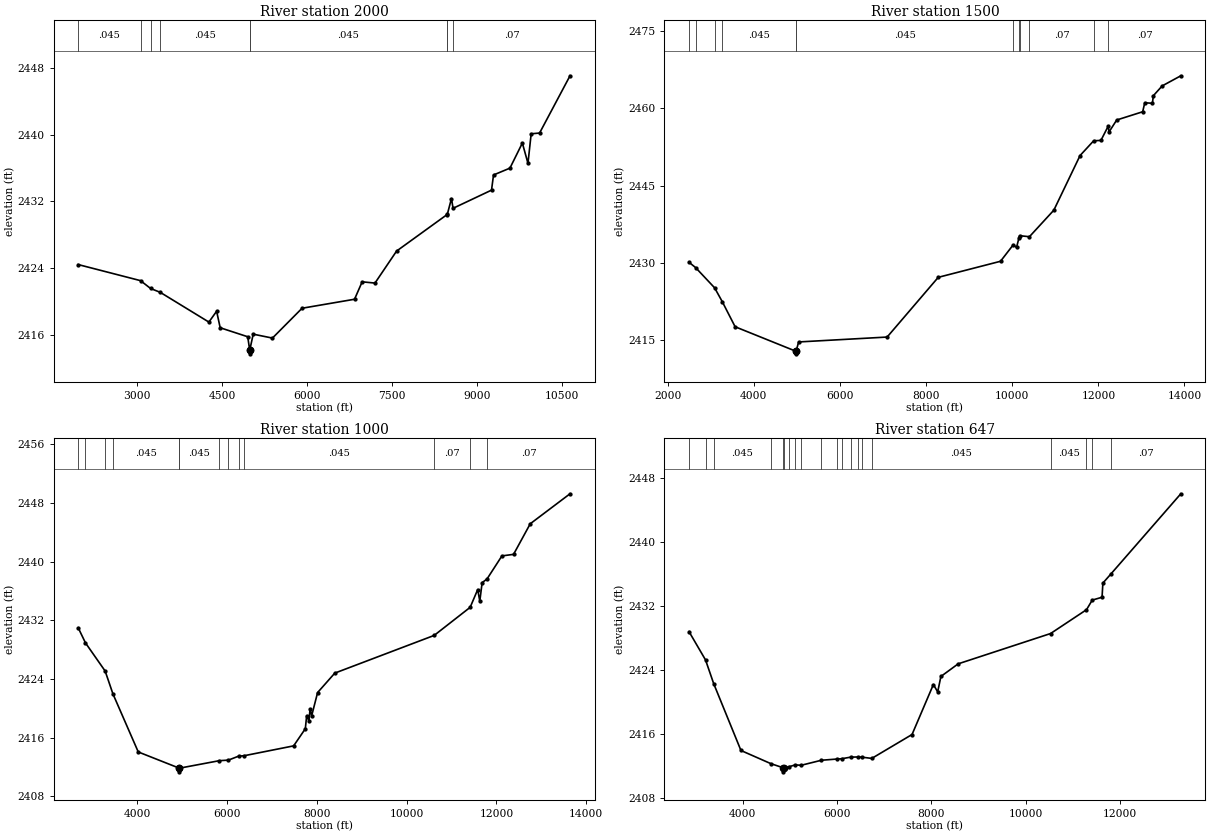
Type RM Length L Ch R = 1,2000,500,500,500
BEGIN DESCRIPTION:
Cottonwood Creek Trib01_31 4.0
END DESCRIPTION:
XS GIS Cut Line= 3
      1336870.98      6826357.59      1339291.22      6828201.12
      1343254.98      6824188.02
#Sta/Elev= 30
  1957.6 2424.40  3058.4 2422.47  3235.8 2421.53  3405.9 2421.07  4264.9 2417.50
  4401.4 2418.80  4464.5 2416.82  4950.9 2415.74  4984.2 2414.19  4984.5 2413.69
  4988.2 2414.19  5047.3 2416.05  5386.7 2415.58  5910.0 2419.16  6836.3 2420.24
  6970.7 2422.33  7197.0 2422.18  7578.8 2426.02  8462.1 2430.36  8474.4 2430.43
  8547.5 2432.32  8575.8 2431.15  9254.7 2433.33  9290.1 2435.15  9579.9 2435.97
  9799.1 2438.98  9898.1 2436.55  9954.7 2440.09 10103.2 2440.18 10640.6 2447.05
#Mann=9,-1,0
  1957.6   0.045       0  3058.4   0.035       0  3235.8    0.07       0
  3405.9   0.045       0  4984.2   0.045       0  4988.2   0.045       0
  8462.1    0.07       0  8474.4   0.035       0  8575.8    0.07       0
Bank Sta=4984.2,4988.2
Exp/Cntr=0.3,0.1

Type RM Length L Ch R = 1,1500,500,500,500
BEGIN DESCRIPTION:
Cottonwood Creek Trib01_31 3.0
END DESCRIPTION:
XS GIS Cut Line= 3
      1336754.99      6829188.00      1339200.57      6828638.27
      1346954.99      6824238.01
#Sta/Elev= 30
  2493.4 2430.11  2647.0 2429.07  3088.3 2425.14  3266.3 2422.45  3564.7 2417.58
  4976.7 2412.82  4976.9 2412.32  4980.7 2412.82  5039.6 2414.63  7094.8 2415.58
  8282.0 2427.18  9728.4 2430.30 10025.1 2433.51 10100.4 2432.98 10155.3 2434.80
 10170.9 2435.27 10399.6 2435.07 10967.2 2440.23 11575.9 2450.84 11891.5 2453.70
 12060.5 2453.78 12227.3 2456.51 12249.4 2455.43 12426.8 2457.74 13029.7 2459.34
 13078.7 2461.09 13256.1 2460.99 13277.7 2462.46 13482.5 2464.36 13915.9 2466.33
#Mann=12,-1,0
  2493.4    0.07       0  2647.0   0.045       0  3088.3   0.035       0
  3266.3   0.045       0  4976.7   0.045       0  4980.7   0.045       0
 10025.1   0.035       0 10155.3    0.07       0 10170.9   0.035       0
 10399.6    0.07       0 11891.5   0.035       0 12227.3    0.07       0
Bank Sta=4976.7,4980.7
Exp/Cntr=0.3,0.1

Type RM Length L Ch R = 1,1000,353,353,353
BEGIN DESCRIPTION:
Cottonwood Creek Trib01_31 2.0
END DESCRIPTION:
XS GIS Cut Line= 3
      1336705.00      6829288.00      1339004.78      6829038.21
      1346905.01      6825538.00
#Sta/Elev= 30
  2686.7 2430.97  2848.8 2428.91  3287.2 2425.07  3460.2 2421.96  4024.5 2414.04
  4937.9 2411.83  4938.1 2411.33  4941.9 2411.83  5830.2 2412.85  6032.7 2412.93
  6260.3 2413.47  6377.2 2413.52  7485.0 2414.87  7745.6 2417.21  7775.3 2418.99
  7827.4 2418.25  7850.7 2419.91  7887.8 2419.00  8019.0 2422.14  8401.8 2424.79
 10615.1 2429.93 11416.7 2433.76 11584.8 2436.18 11631.4 2434.60 11683.4 2437.12
 11792.8 2437.63 12124.3 2440.77 12383.1 2440.98 12755.0 2445.15 13640.9 2449.24
#Mann=13,-1,0
  2686.7    0.07       0  2848.8   0.045       0  3287.2   0.035       0
  3460.2   0.045       0  4937.9   0.045       0  4941.9   0.045       0
  5830.2    0.07       0  6032.7   0.045       0  6260.3    0.07       0
  6377.2   0.045       0 10615.1    0.07       0 11416.7   0.035       0
 11792.8    0.07       0
Bank Sta=4937.9,4941.9
Exp/Cntr=0.3,0.1

Type RM Length L Ch R = 1,647,0,0,0
BEGIN DESCRIPTION:
Cottonwood Creek Trib01_31 1.0
END DESCRIPTION:
XS GIS Cut Line= 3
      1336915.71      6829425.35      1339040.80      6829294.86
      1346570.87      6825809.40
#Sta/Elev= 30
  2859.1 2428.81  3209.4 2425.27  3382.7 2422.30  3960.5 2413.94  4596.5 2412.29
  4860.2 2411.77  4860.4 2411.27  4864.2 2411.77  4973.3 2411.90  5113.7 2412.14
  5236.7 2412.09  5667.0 2412.72  5994.9 2412.87  6097.4 2412.91  6287.7 2413.11
  6447.4 2413.13  6518.9 2413.11  6734.1 2412.95  7587.7 2415.94  8039.7 2422.19
  8131.4 2421.27  8199.4 2423.20  8566.1 2424.78 10524.9 2428.57 11286.1 2431.55
 11408.1 2432.75 11615.9 2433.11 11633.3 2434.88 11800.8 2436.00 13285.8 2446.05
#Mann=20,-1,0
  2859.1   0.045       0  3209.4   0.035       0  3382.7   0.045       0
  4596.5    0.07       0  4860.2   0.045       0  4864.2    0.07       0
  4973.3   0.045       0  5113.7    0.07       0  5236.7   0.045       0
  5667.0   0.045       0  5994.9    0.07       0  6097.4   0.045       0
  6287.7    0.07       0  6447.4   0.045       0  6518.9    0.07       0
  6734.1   0.045       0 10524.9   0.045       0 11286.1    0.07       0
 11408.1   0.035       0 11800.8    0.07       0
Bank Sta=4860.2,4864.2
Exp/Cntr=0.3,0.1

Chan Stop Cuts=-1