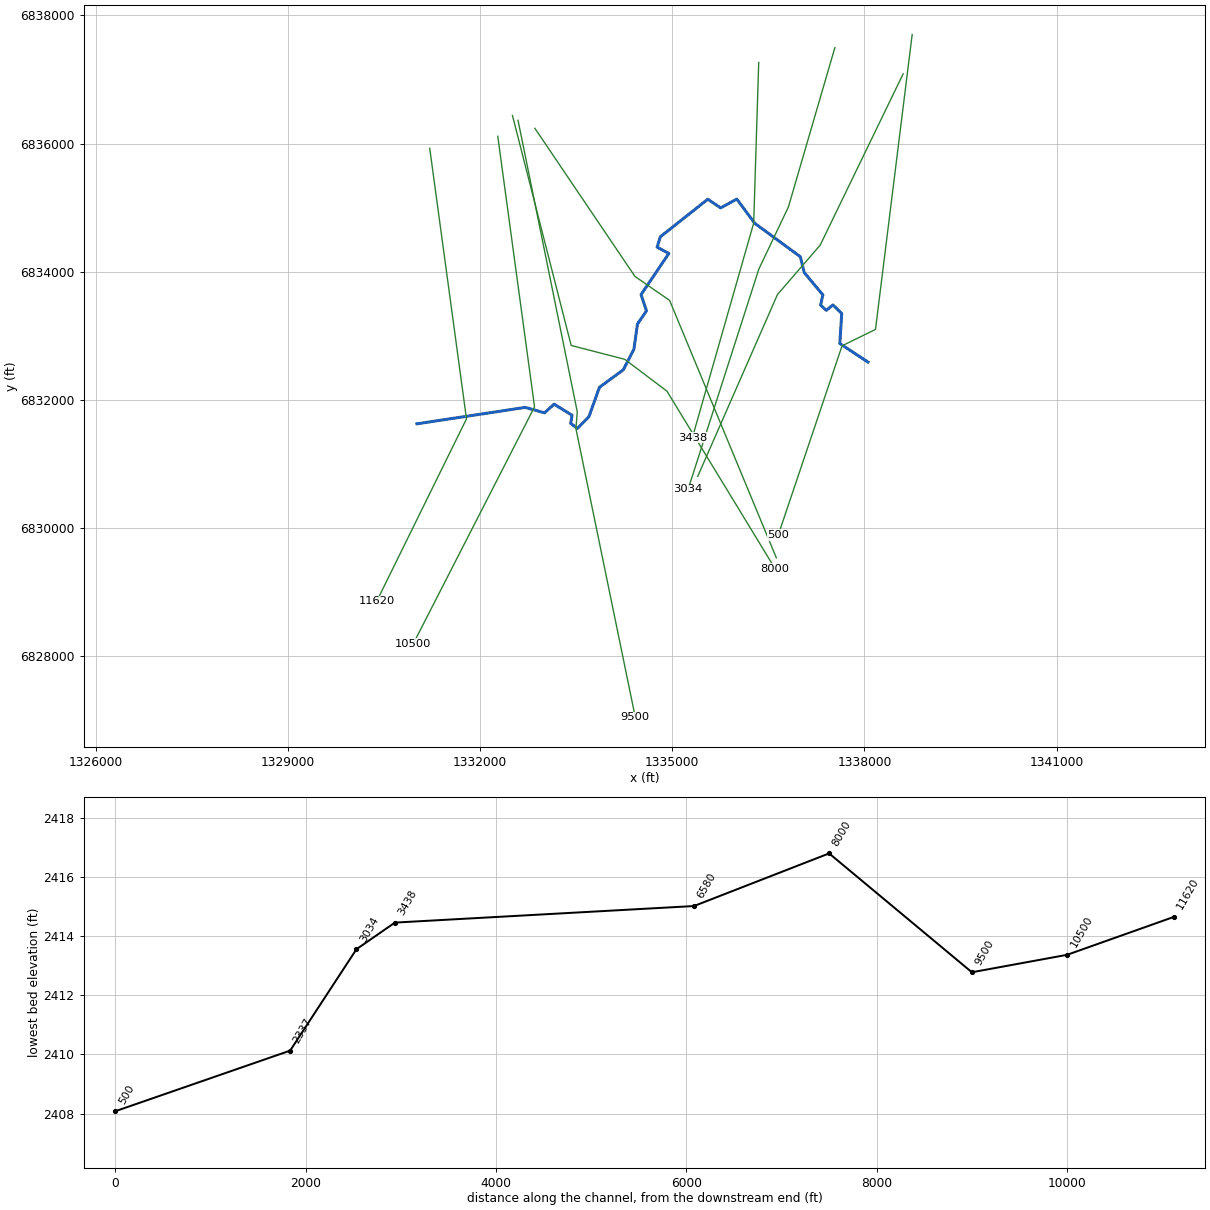
--- Cottonwood Creek Trib01_4.prj (project) ---

Proj Title=Cottonwood Creek Trib01_4 Base Level Engineering
Current Plan=p01
Default Exp/Contr=0.3,0.1
English Units
Geom File=g01
Flow File=f01
Plan File=p01
BEGIN DESCRIPTION:
Cottonwood Creek Trib01_4
END DESCRIPTION:

--- Cottonwood Creek Trib01_4.p01 (plan) ---

Plan Title=Multiple Run
Short Identifier=Multiple
Geom File=g01
Flow File=f01
Subcritical Flow
K Sum by GR= 0
Std Step Tol= 0.01
Critical Tol= 0.01
Num of Std Step Trials= 20
Max Error Tol= 0.3
Flow Tol Ratio= 0.001
Split Flow NTrial= 30
Split Flow Tol= 0.02
Split Flow Ratio= 0.02
Log Output Level= 0
Friction Slope Method= 1
Unsteady Friction Slope Method= 2
Unsteady Bridges Friction Slope Method= 1
Parabolic Critical Depth
Global Vel Dist=  1 , 1 , 1
Global Log Level= 0
CheckData=True
Encroach Param= -1, 0, 0, 0
BEGIN DESCRIPTION:
Multiple Run
END DESCRIPTION:

--- Cottonwood Creek Trib01_4.f01 (steady flow) ---

Flow Title=Multiple
Number of Profiles=7
Profile Names=10-year,25-year,50-year,1pct_min,100-year,1pct_plu,500-year
River Rch & RM= Cottonwood Creek,Reach-1,11620
     192     262     318     192     382     763     561
River Rch & RM= Cottonwood Creek,Reach-1,8000
     222     303     366     220     439     875     638
River Rch & RM= Cottonwood Creek,Reach-1,500
     236     321     390     234     467     933     682
Boundary for River Rch & Prof#=Cottonwood Creek,Reach-1,1
Up Type=0
Dn Type=3
Dn Slope=0.005
Boundary for River Rch & Prof#=Cottonwood Creek,Reach-1,2
Up Type=0
Dn Type=3
Dn Slope=0.005
Boundary for River Rch & Prof#=Cottonwood Creek,Reach-1,3
Up Type=0
Dn Type=3
Dn Slope=0.005
Boundary for River Rch & Prof#=Cottonwood Creek,Reach-1,4
Up Type=0
Dn Type=3
Dn Slope=0.005
Boundary for River Rch & Prof#=Cottonwood Creek,Reach-1,5
Up Type=0
Dn Type=3
Dn Slope=0.005
Boundary for River Rch & Prof#=Cottonwood Creek,Reach-1,6
Up Type=0
Dn Type=3
Dn Slope=0.005
Boundary for River Rch & Prof#=Cottonwood Creek,Reach-1,7
Up Type=0
Dn Type=3
Dn Slope=0.005

--- Cottonwood Creek Trib01_4.g01 (geometry) ---

Geom Title=Existing Conditions

River Reach=Cottonwood Creek,Reach-1
Reach XY= 30
      1331013.40      6831623.82      1332704.99      6831880.53
      1333005.01      6831795.08      1333154.91      6831930.71
      1333435.58      6831758.13      1333414.15      6831631.23
      1333518.32      6831551.41      1333699.17      6831735.70
      1333863.14      6832194.06      1334235.83      6832467.52
      1334401.46      6832789.46      1334456.67      6833181.95
      1334597.25      6833388.09      1334512.67      6833641.66
      1334947.47      6834284.87      1334763.83      6834381.01
      1334814.30      6834544.67      1335554.92      6835130.70
      1335755.00      6834995.08      1336007.67      6835132.71
      1336288.33      6834754.65      1336999.89      6834232.89
      1337060.52      6833985.56      1337351.53      6833636.50
      1337316.10      6833477.89      1337404.98      6833395.10
      1337508.33      6833480.39      1337645.70      6833344.67
      1337616.24      6832878.00      1338055.00      6832588.00

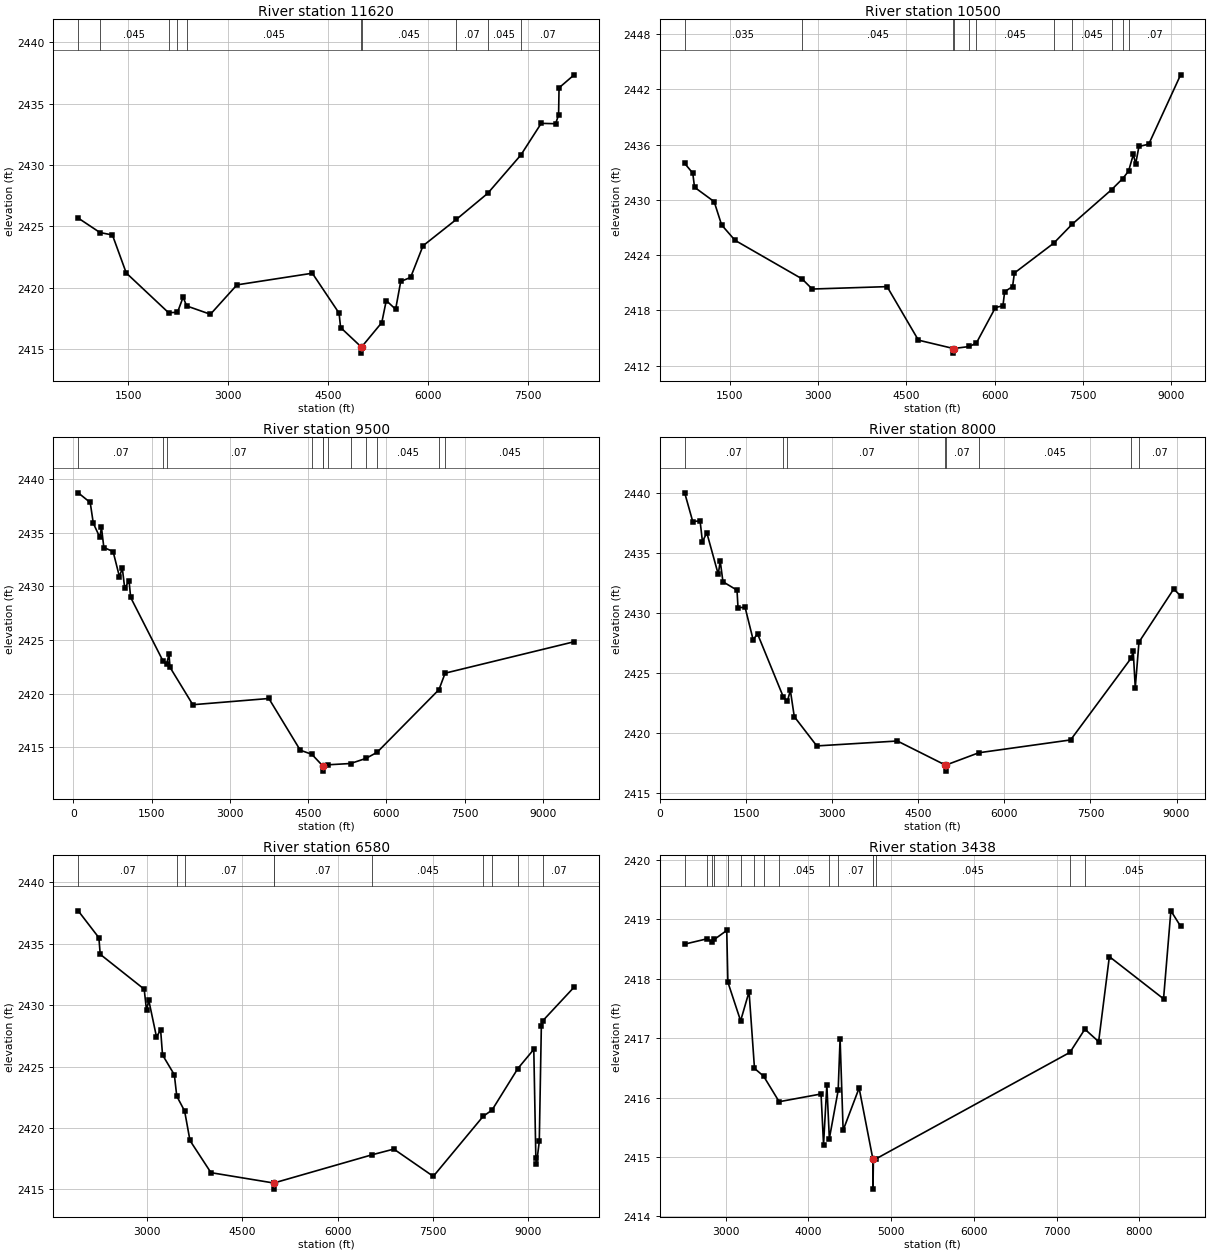
Type RM Length L Ch R = 1,11620,1120,1120,1120
BEGIN DESCRIPTION:
Cottonwood Creek Trib01_4 22
END DESCRIPTION:
XS GIS Cut Line= 3
      1331212.96      6835926.31      1331787.04      6831701.26
      1330386.33      6828854.80
#Sta/Elev= 30
   752.7 2425.67  1078.8 2424.49  1265.7 2424.29  1473.0 2421.19  2107.0 2417.95
  2241.2 2417.98  2325.3 2419.21  2379.1 2418.50  2735.1 2417.82  3132.7 2420.22
  4263.0 2421.17  4664.4 2417.91  4686.8 2416.74  4997.7 2415.15  4997.9 2414.65
  5001.7 2415.15  5304.3 2417.14  5371.8 2418.94  5512.1 2418.23  5588.6 2420.50
  5736.8 2420.83  5923.0 2423.41  6424.5 2425.57  6893.1 2427.69  7390.4 2430.82
  7695.0 2433.40  7910.6 2433.37  7955.6 2434.08  7962.5 2436.30  8189.0 2437.36
#Mann=10,-1,0
   752.7    0.07       0  1078.8   0.045       0  2107.0    0.07       0
  2241.2   0.035       0  2379.1   0.045       0  4997.7   0.045       0
  5001.7   0.045       0  6424.5    0.07       0  6893.1   0.045       0
  7390.4    0.07       0
Bank Sta=4997.7,5001.7
Exp/Cntr=0.3,0.1

Type RM Length L Ch R = 1,10500,1000,1000,1000
BEGIN DESCRIPTION:
Cottonwood Creek Trib01_4 21.0
END DESCRIPTION:
XS GIS Cut Line= 3
      1332275.46      6836113.84      1332849.54      6831888.76
      1330955.01      6828188.01
#Sta/Elev= 30
   736.1 2433.97   873.2 2432.92   903.5 2431.38  1236.5 2429.82  1363.3 2427.29
  1590.8 2425.62  2727.5 2421.44  2901.7 2420.33  4173.2 2420.59  4704.7 2414.78
  5300.4 2413.87  5300.6 2413.37  5304.4 2413.87  5570.3 2414.09  5689.6 2414.47
  6013.0 2418.32  6140.6 2418.51  6169.2 2420.04  6304.0 2420.60  6334.9 2422.07
  7003.0 2425.31  7312.9 2427.35  7985.1 2431.12  8172.3 2432.31  8273.2 2433.13
  8355.4 2434.95  8393.6 2433.91  8449.8 2435.81  8616.3 2436.06  9157.5 2443.59
#Mann=11,-1,0
   736.1   0.035       0  2727.5   0.045       0  5300.4   0.045       0
  5304.4   0.045       0  5570.3    0.07       0  5689.6   0.045       0
  7003.0    0.07       0  7312.9   0.045       0  7985.1    0.07       0
  8172.3   0.035       0  8273.2    0.07       0
Bank Sta=5300.4,5304.4
Exp/Cntr=0.3,0.1

Type RM Length L Ch R = 1,9500,1500,1500,1500
BEGIN DESCRIPTION:
Cottonwood Creek Trib01_4 19.0
END DESCRIPTION:
XS GIS Cut Line= 4
      1332591.90      6836363.41      1333516.89      6831811.37
      1333495.92      6831548.37      1334422.63      6827043.10
#Sta/Elev= 30
    91.1 2438.72   321.1 2437.82   380.1 2435.89   504.8 2434.58   537.0 2435.49
   582.5 2433.62   759.9 2433.25   881.1 2430.91   936.9 2431.69   982.4 2429.83
  1066.0 2430.52  1096.6 2428.97  1716.5 2423.05  1786.0 2422.76  1831.4 2423.66
  1851.8 2422.45  2288.3 2418.97  3746.1 2419.55  4348.4 2414.73  4569.9 2414.35
  4777.3 2413.28  4777.6 2412.78  4782.1 2413.28  4878.3 2413.37  5312.9 2413.49
  5604.7 2413.96  5820.8 2414.53  7008.2 2420.38  7125.4 2421.91  9599.6 2424.84
#Mann=12,-1,0
    91.1    0.07       0  1716.5   0.035       0  1786.0    0.07       0
  4569.9   0.045       0  4777.3    0.07       0  4782.1   0.045       0
  4878.3    0.07       0  5312.9   0.045       0  5604.7    0.07       0
  5820.8   0.045       0  7008.2   0.035       0  7125.4   0.045       0
Bank Sta=4777.3,4782.1
Exp/Cntr=0.3,0.1

Type RM Length L Ch R = 1,8000,1420,1420,1420
BEGIN DESCRIPTION:
Cottonwood Creek Trib01_4 16.0
END DESCRIPTION:
XS GIS Cut Line= 5
      1332505.00      6836438.01      1333421.41      6832847.82
      1334257.28      6832631.16      1334917.40      6832133.96
      1336604.92      6829363.10
#Sta/Elev= 30
   431.2 2439.99   571.6 2437.60   699.5 2437.65   740.8 2435.92   816.8 2436.66
  1015.9 2433.20  1050.4 2434.31  1097.6 2432.58  1342.8 2431.88  1360.1 2430.43
  1483.9 2430.44  1623.6 2427.75  1700.2 2428.24  2148.8 2422.99  2220.5 2422.63
  2272.2 2423.53  2340.5 2421.34  2732.7 2418.90  4136.5 2419.31  4974.5 2417.30
  4974.9 2416.80  4979.4 2417.30  5554.5 2418.33  7154.3 2419.40  8207.8 2426.21
  8245.4 2426.77  8280.5 2423.75  8345.1 2427.55  8949.8 2431.97  9070.7 2431.41
#Mann=8,-1,0
   431.2    0.07       0  2148.8   0.035       0  2220.5    0.07       0
  4974.5    0.07       0  4979.4    0.07       0  5554.5   0.045       0
  8207.8   0.035       0  8345.1    0.07       0
Bank Sta=4974.5,4979.4
Exp/Cntr=0.3,0.1

Type RM Length L Ch R = 1,6580,3142,3142,3142
BEGIN DESCRIPTION:
Cottonwood Creek Trib01_4 11.0
END DESCRIPTION:
XS GIS Cut Line= 4
      1332854.99      6836238.01      1334417.40      6833925.63
      1334959.07      6833550.63      1336625.07      6829531.38
#Sta/Elev= 30
  1920.2 2437.68  2245.3 2435.49  2266.3 2434.14  2958.1 2431.30  2994.3 2429.58
  3030.5 2430.39  3151.2 2427.42  3216.4 2427.98  3246.3 2425.95  3432.2 2424.33
  3470.3 2422.59  3593.9 2421.38  3677.9 2418.98  4008.1 2416.36  4992.7 2415.52
  4993.1 2415.02  4997.7 2415.52  6544.5 2417.82  6884.8 2418.28  7505.1 2416.06
  8288.0 2420.94  8429.2 2421.46  8835.2 2424.84  9085.8 2426.40  9118.1 2417.53
  9128.1 2417.06  9172.2 2418.90  9204.7 2428.33  9225.7 2428.72  9720.6 2431.47
#Mann=10,-1,0
  1920.2    0.07       0  3470.3   0.035       0  3593.9    0.07       0
  4992.7    0.07       0  4997.7    0.07       0  6544.5   0.045       0
  8288.0   0.035       0  8429.2   0.045       0  8835.2   0.035       0
  9225.7    0.07       0
Bank Sta=4992.7,4997.7
Exp/Cntr=0.3,0.1

Type RM Length L Ch R = 1,3438,404,404,404
BEGIN DESCRIPTION:
Cottonwood Creek Trib01_4 8.0
END DESCRIPTION:
XS GIS Cut Line= 3
      1336349.86      6837266.23      1336271.57      6834758.96
      1335313.23      6831404.78
#Sta/Elev= 30
  2503.1 2418.58  2775.3 2418.67  2828.5 2418.62  2862.5 2418.66  3011.6 2418.81
  3025.6 2417.94  3179.5 2417.29  3281.7 2417.78  3347.3 2416.49  3457.3 2416.36
  3645.5 2415.93  4152.1 2416.06  4182.2 2415.21  4222.2 2416.21  4252.4 2415.31
  4359.0 2416.12  4382.3 2416.99  4419.1 2415.45  4612.4 2416.16  4779.6 2414.96
  4780.0 2414.46  4785.3 2414.96  4817.2 2414.97  7162.0 2416.76  7342.1 2417.15
  7508.6 2416.94  7638.4 2418.37  8293.6 2417.66  8382.2 2419.14  8500.0 2418.88
#Mann=16,-1,0
  2503.1   0.045       0  2775.3    0.07       0  2828.5   0.045       0
  2862.5    0.07       0  3025.6   0.045       0  3179.5    0.07       0
  3347.3   0.045       0  3457.3    0.07       0  3645.5   0.045       0
  4252.4   0.035       0  4359.0    0.07       0  4779.6   0.045       0
  4785.3    0.07       0  4817.2   0.045       0  7162.0    0.07       0
  7342.1   0.045       0
Bank Sta=4779.6,4785.3
Exp/Cntr=0.3,0.1

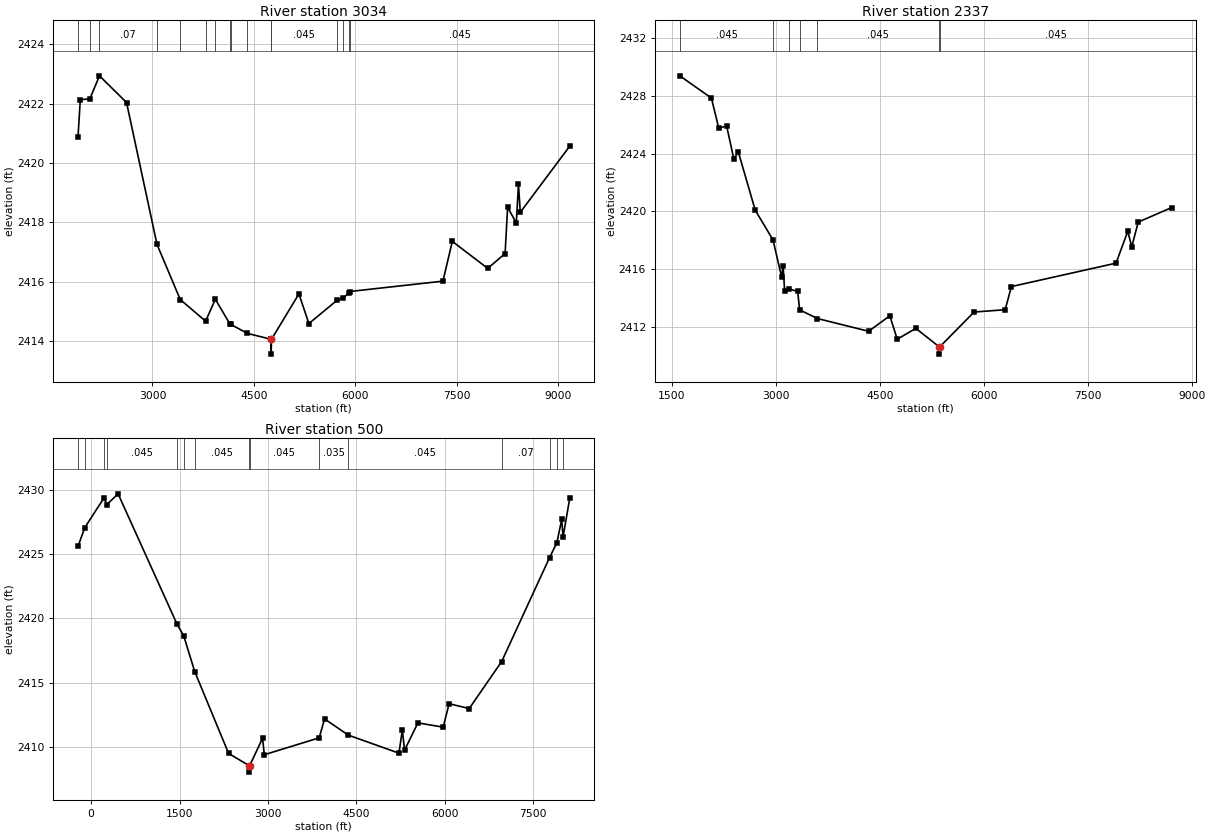
Type RM Length L Ch R = 1,3034,697,697,697
BEGIN DESCRIPTION:
Cottonwood Creek Trib01_4 3.5
END DESCRIPTION:
XS GIS Cut Line= 4
      1337538.95      6837497.52      1336813.23      6835008.96
      1336351.45      6834039.20      1335247.50      6830602.36
#Sta/Elev= 30
  1898.5 2420.88  1932.5 2422.14  2072.8 2422.16  2216.3 2422.94  2616.7 2422.04
  3067.1 2417.26  3411.2 2415.40  3787.0 2414.67  3930.3 2415.41  4150.7 2414.56
  4159.9 2414.56  4404.7 2414.26  4755.7 2414.06  4756.2 2413.56  4761.5 2414.06
  5167.3 2415.59  5314.6 2414.59  5729.1 2415.37  5812.5 2415.44  5905.4 2415.61
  5916.2 2415.67  7298.2 2416.02  7437.1 2417.36  7961.3 2416.45  8218.1 2416.95
  8255.5 2418.51  8383.9 2417.98  8416.0 2419.28  8442.9 2418.34  9174.6 2420.57
#Mann=16,-1,0
  1898.5    0.07       0  2072.8   0.045       0  2216.3    0.07       0
  3067.1   0.045       0  3411.2    0.07       0  3787.0   0.035       0
  3930.3    0.07       0  4150.7   0.045       0  4159.9    0.07       0
  4404.7   0.045       0  4755.7   0.045       0  4761.5   0.045       0
  5729.1    0.07       0  5812.5   0.035       0  5905.4    0.07       0
  5916.2   0.045       0
Bank Sta=4755.7,4761.5
Exp/Cntr=0.3,0.1

Type RM Length L Ch R = 1,2337,1837,1837,1837
BEGIN DESCRIPTION:
Cottonwood Creek Trib01_4 3.0
END DESCRIPTION:
XS GIS Cut Line= 4
      1338605.01      6837088.02      1337309.79      6834414.20
      1336643.12      6833643.37      1335397.08      6830801.80
#Sta/Elev= 30
  1616.7 2429.37  2072.3 2427.83  2178.3 2425.74  2291.2 2425.91  2394.5 2423.64
  2461.2 2424.09  2703.2 2420.09  2961.0 2418.02  3083.4 2415.48  3105.7 2416.24
  3127.9 2414.51  3196.9 2414.63  3316.8 2414.46  3344.1 2413.19  3601.5 2412.59
  4339.7 2411.71  4645.4 2412.78  4751.7 2411.16  5020.5 2411.91  5358.7 2410.63
  5359.2 2410.13  5364.5 2410.63  5861.0 2413.04  6309.0 2413.20  6398.9 2414.80
  7908.3 2416.42  8077.4 2418.62  8135.0 2417.55  8228.5 2419.26  8709.6 2420.26
#Mann=7,-1,0
  1616.7   0.045       0  2961.0   0.035       0  3196.9   0.045       0
  3344.1   0.035       0  3601.5   0.045       0  5358.7   0.045       0
  5364.5   0.045       0
Bank Sta=5358.7,5364.5
Exp/Cntr=0.3,0.1

Type RM Length L Ch R = 1,500,0,0,0
BEGIN DESCRIPTION:
Cottonwood Creek Trib01_4 1.0
END DESCRIPTION:
XS GIS Cut Line= 4
      1338746.10      6837702.54      1338173.24      6833097.89
      1337650.93      6832841.49      1336655.00      6829887.99
#Sta/Elev= 30
  -222.0 2425.59  -108.1 2427.04   218.1 2429.35   267.0 2428.84   457.7 2429.67
  1454.2 2419.59  1571.7 2418.64  1759.0 2415.86  2332.1 2409.53  2681.2 2408.58
  2681.7 2408.08  2688.3 2408.58  2908.5 2410.71  2936.7 2409.43  3868.4 2410.74
  3959.0 2412.21  4362.2 2410.95  5221.0 2409.55  5278.1 2411.36  5315.4 2409.78
  5541.9 2411.90  5971.2 2411.57  6070.9 2413.39  6411.9 2413.01  6962.5 2416.66
  7774.2 2424.72  7898.9 2425.88  7980.5 2427.68  8003.2 2426.32  8116.9 2429.33
#Mann=15,-1,0
  -222.0    0.07       0  -108.1   0.045       0   218.1    0.07       0
   267.0   0.045       0  1454.2   0.035       0  1571.7    0.07       0
  1759.0   0.045       0  2681.2   0.045       0  2688.3   0.045       0
  3868.4   0.035       0  4362.2   0.045       0  6962.5    0.07       0
  7774.2   0.035       0  7898.9    0.07       0  8003.2   0.045       0
Bank Sta=2681.2,2688.3
Exp/Cntr=0.3,0.1

Chan Stop Cuts=-1