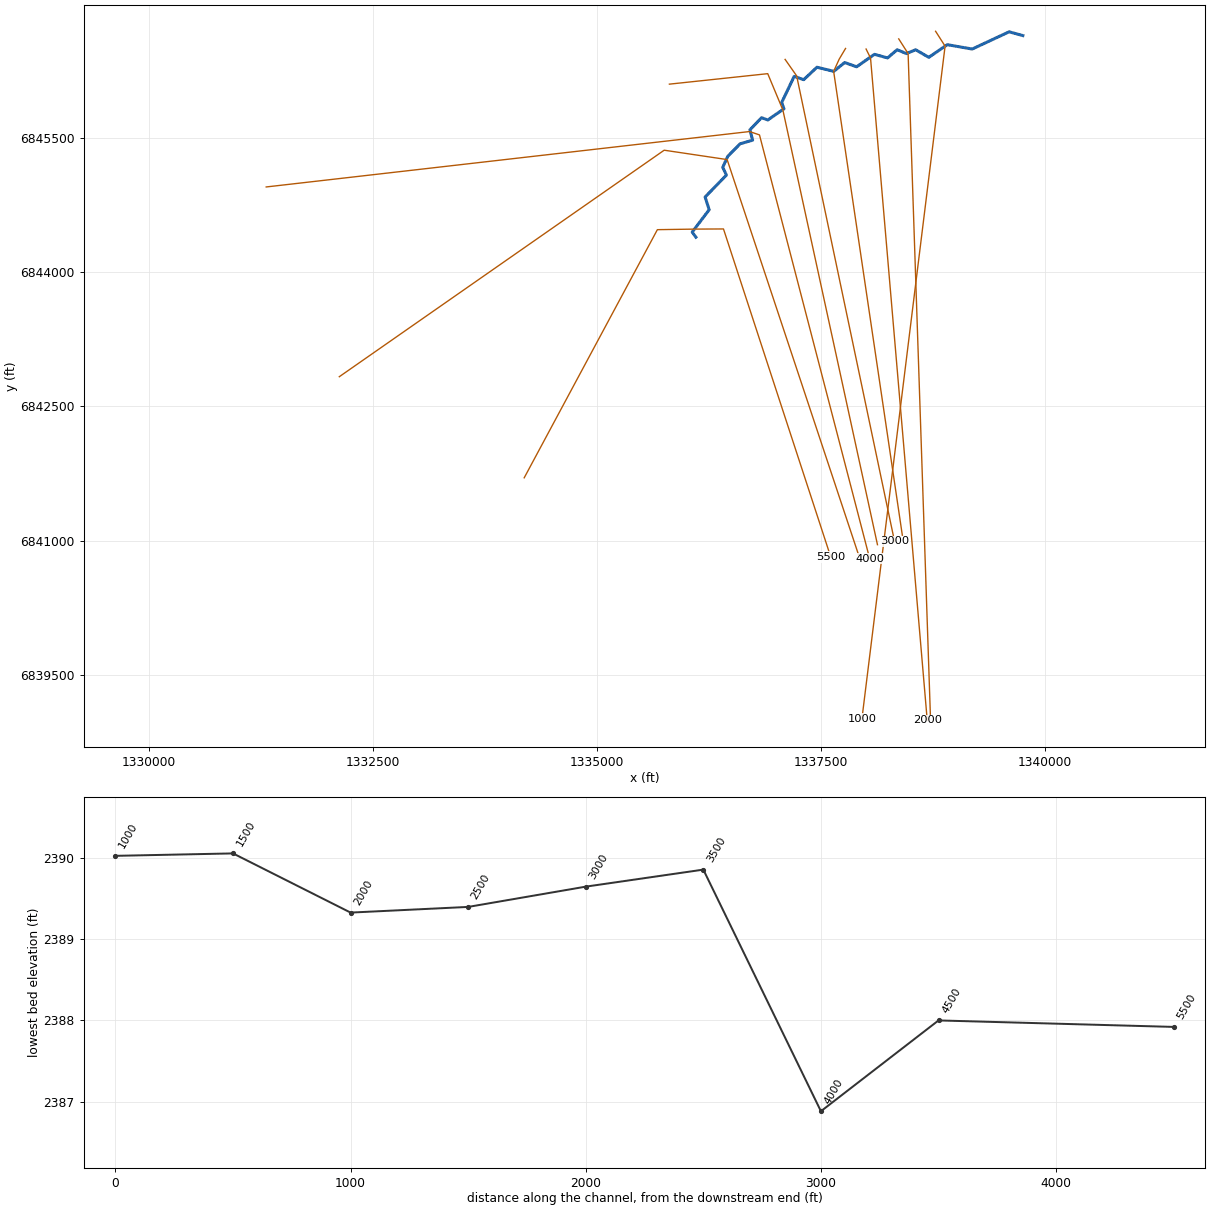
--- Cottonwood Creek Trib01_6.prj (project) ---

Proj Title=Cottonwood Creek Trib01_6 Base Level Engineering
Current Plan=p01
Default Exp/Contr=0.3,0.1
English Units
Geom File=g01
Flow File=f01
Plan File=p01
BEGIN DESCRIPTION:
Cottonwood Creek Trib01_6
END DESCRIPTION:

--- Cottonwood Creek Trib01_6.p01 (plan) ---

Plan Title=Multiple Run
Short Identifier=Multiple
Geom File=g01
Flow File=f01
Subcritical Flow
K Sum by GR= 0
Std Step Tol= 0.01
Critical Tol= 0.01
Num of Std Step Trials= 20
Max Error Tol= 0.3
Flow Tol Ratio= 0.001
Split Flow NTrial= 30
Split Flow Tol= 0.02
Split Flow Ratio= 0.02
Log Output Level= 0
Friction Slope Method= 1
Unsteady Friction Slope Method= 2
Unsteady Bridges Friction Slope Method= 1
Parabolic Critical Depth
Global Vel Dist=  1 , 1 , 1
Global Log Level= 0
CheckData=True
Encroach Param= -1, 0, 0, 0
BEGIN DESCRIPTION:
Multiple Run
END DESCRIPTION:

--- Cottonwood Creek Trib01_6.f01 (steady flow) ---

Flow Title=Multiple
Number of Profiles=7
Profile Names=10-year,25-year,50-year,1pct_min,100-year,1pct_plu,500-year
River Rch & RM= Cottonwood Creek,Reach-1,5500
     296     414     511     312     623    1243     942
Boundary for River Rch & Prof#=Cottonwood Creek,Reach-1,1
Up Type=0
Dn Type=3
Dn Slope=0.005
Boundary for River Rch & Prof#=Cottonwood Creek,Reach-1,2
Up Type=0
Dn Type=3
Dn Slope=0.005
Boundary for River Rch & Prof#=Cottonwood Creek,Reach-1,3
Up Type=0
Dn Type=3
Dn Slope=0.005
Boundary for River Rch & Prof#=Cottonwood Creek,Reach-1,4
Up Type=0
Dn Type=3
Dn Slope=0.005
Boundary for River Rch & Prof#=Cottonwood Creek,Reach-1,5
Up Type=0
Dn Type=3
Dn Slope=0.005
Boundary for River Rch & Prof#=Cottonwood Creek,Reach-1,6
Up Type=0
Dn Type=3
Dn Slope=0.005
Boundary for River Rch & Prof#=Cottonwood Creek,Reach-1,7
Up Type=0
Dn Type=3
Dn Slope=0.005

--- Cottonwood Creek Trib01_6.g01 (geometry) ---

Geom Title=Existing Conditions

River Reach=Cottonwood Creek,Reach-1
Reach XY= 30
      1336105.00      6844388.00      1336063.79      6844444.66
      1336253.37      6844694.04      1336208.34      6844836.28
      1336445.97      6845080.99      1336404.78      6845167.79
      1336460.83      6845290.30      1336598.83      6845430.14
      1336738.89      6845470.84      1336708.16      6845586.35
      1336838.33      6845721.61      1336908.23      6845696.25
      1337088.62      6845821.30      1337063.03      6845891.33
      1337202.46      6846182.99      1337308.41      6846145.82
      1337456.63      6846284.87      1337644.52      6846238.94
      1337765.63      6846337.39      1337898.89      6846289.80
      1338098.27      6846428.85      1338244.52      6846388.95
      1338351.59      6846480.19      1338455.00      6846437.25
      1338558.32      6846479.95      1338705.00      6846395.50
      1338911.05      6846536.34      1339189.61      6846488.08
      1339601.59      6846680.23      1339755.00      6846638.00

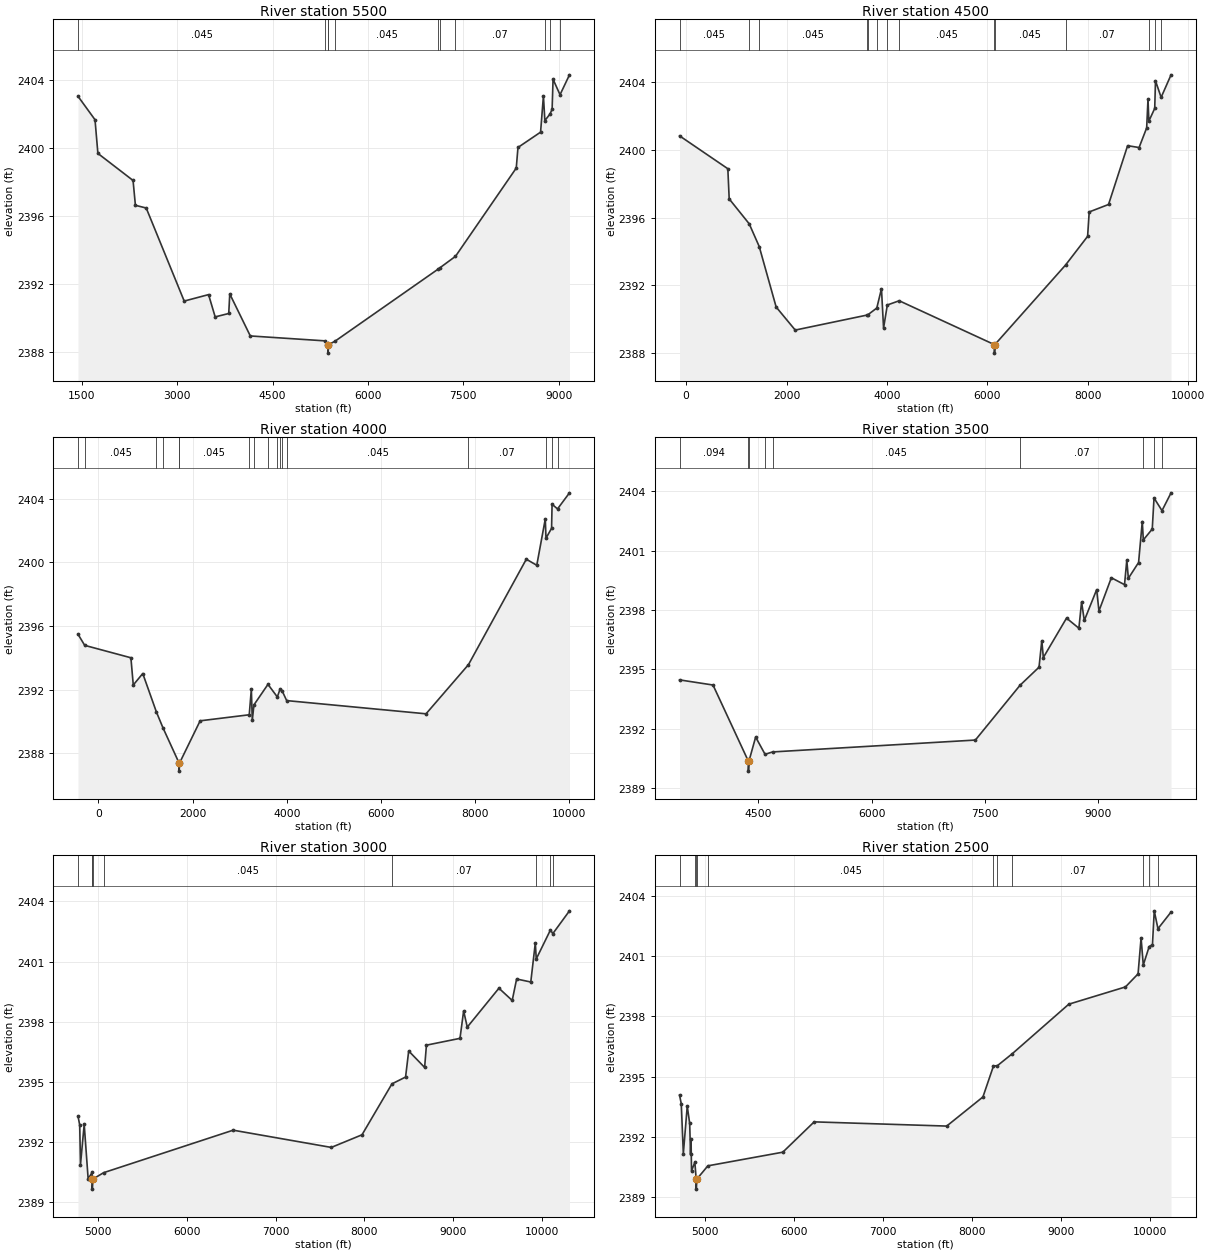
Type RM Length L Ch R = 1,5500,1000,1000,1000
BEGIN DESCRIPTION:
Cottonwood Creek Trib01_6 11.0
END DESCRIPTION:
XS GIS Cut Line= 5
      1334188.85      6841702.03      1335675.35      6844471.76
      1336094.68      6844478.08      1336413.25      6844479.74
      1337610.59      6840818.31
#Sta/Elev= 30
  1437.2 2403.02  1705.0 2401.64  1750.4 2399.66  2303.7 2398.07  2340.6 2396.61
  2510.8 2396.45  3108.4 2390.98  3491.7 2391.36  3595.6 2390.05  3809.2 2390.25
  3825.4 2391.40  4148.6 2388.93  5328.0 2388.64  5372.0 2388.42  5372.5 2387.92
  5378.8 2388.42  5481.1 2388.62  7104.6 2392.86  7125.9 2392.92  7377.1 2393.61
  8333.5 2398.80  8360.2 2400.01  8716.0 2400.91  8760.8 2403.04  8783.4 2401.59
  8865.2 2401.98  8897.6 2402.26  8912.4 2404.02  9022.1 2403.11  9170.8 2404.28
#Mann=11,-1,0
  1437.2   0.045       0  5328.0    0.07       0  5372.0   0.045       0
  5378.8    0.07       0  5481.1   0.045       0  7104.6    0.07       0
  7125.9   0.045       0  7377.1    0.07       0  8783.4   0.035       0
  8865.2    0.07       0  9022.1   0.045       0
Bank Sta=5372,5378.8
Exp/Cntr=0.3,0.1

Type RM Length L Ch R = 1,4500,500,500,500
BEGIN DESCRIPTION:
Cottonwood Creek Trib01_6 9.0
END DESCRIPTION:
XS GIS Cut Line= 4
      1332125.06      6842830.43      1335751.35      6845358.72
      1336454.04      6845254.05      1337923.68      6840833.86
#Sta/Elev= 30
  -131.1 2400.82   830.4 2398.88   857.4 2397.10  1256.0 2395.63  1455.4 2394.29
  1792.8 2390.72  2172.8 2389.36  3594.1 2390.24  3613.8 2390.25  3797.3 2390.66
  3890.3 2391.80  3932.1 2389.48  4007.0 2390.84  4243.6 2391.09  6141.1 2388.50
  6141.6 2388.00  6148.0 2388.50  7557.4 2393.20  7996.1 2394.89  8027.8 2396.33
  8412.9 2396.77  8792.8 2400.24  9021.4 2400.13  9172.6 2401.29  9199.0 2403.00
  9216.2 2401.69  9332.9 2402.44  9348.1 2404.07  9460.4 2403.09  9658.1 2404.42
#Mann=14,-1,0
  -131.1   0.045       0  1256.0    0.07       0  1455.4   0.045       0
  3594.1   0.035       0  3613.8   0.045       0  3797.3   0.035       0
  4007.0    0.07       0  4243.6   0.045       0  6141.1   0.045       0
  6148.0   0.045       0  7557.4    0.07       0  9216.2   0.035       0
  9332.9    0.07       0  9460.4   0.045       0
Bank Sta=6141.1,6148
Exp/Cntr=0.3,0.1

Type RM Length L Ch R = 1,4000,500,500,500
BEGIN DESCRIPTION:
Cottonwood Creek Trib01_6 8.0
END DESCRIPTION:
XS GIS Cut Line= 4
      1331309.11      6844948.49      1336704.67      6845567.09
      1336815.14      6845529.31      1338044.69      6840801.12
#Sta/Elev= 30
  -430.9 2395.48  -288.6 2394.78   692.3 2394.00   742.6 2392.29   943.9 2393.01
  1235.6 2390.58  1371.6 2389.61  1716.4 2387.38  1716.9 2386.88  1723.4 2387.38
  2161.9 2390.04  3204.5 2390.42  3248.9 2392.03  3269.1 2390.07  3303.8 2391.04
  3601.7 2392.33  3800.3 2391.54  3857.5 2392.02  3899.7 2391.94  3999.0 2391.31
  6957.3 2390.48  7858.4 2393.57  9085.8 2400.19  9308.0 2399.81  9488.8 2402.72
  9503.5 2401.51  9622.0 2402.13  9632.9 2403.64  9748.8 2403.35 10002.2 2404.36
#Mann=17,-1,0
  -430.9    0.07       0  -288.6   0.045       0  1235.6    0.07       0
  1371.6   0.045       0  1716.4   0.045       0  1723.4   0.045       0
  3204.5    0.07       0  3303.8   0.125       0  3601.7   0.063       0
  3800.3    0.07       0  3857.5   0.063       0  3899.7    0.07       0
  3999.0   0.045       0  7858.4    0.07       0  9503.5   0.035       0
  9632.9    0.07       0  9748.8   0.045       0
Bank Sta=1716.4,1723.4
Exp/Cntr=0.3,0.1

Type RM Length L Ch R = 1,3500,500,500,500
BEGIN DESCRIPTION:
Cottonwood Creek Trib01_6 7.0
END DESCRIPTION:
XS GIS Cut Line= 4
      1335809.47      6846096.08      1336907.11      6846213.07
      1337076.04      6845808.04      1338132.00      6840955.41
#Sta/Elev= 30
  3457.3 2394.47  3900.2 2394.21  4368.8 2390.36  4369.3 2389.86  4375.9 2390.36
  4464.8 2391.58  4589.6 2390.71  4690.1 2390.83  7374.8 2391.43  7966.8 2394.20
  8217.7 2395.11  8254.5 2396.45  8274.9 2395.60  8582.0 2397.59  8745.7 2397.08
  8781.3 2398.41  8817.3 2397.47  8981.1 2399.03  9011.4 2397.95  9175.5 2399.63
  9350.0 2399.28  9380.2 2400.52  9400.7 2399.60  9536.2 2400.40  9585.3 2402.47
  9598.9 2401.54  9717.2 2402.09  9740.8 2403.66  9846.3 2403.02  9966.2 2403.92
#Mann=9,-1,0
  3457.3   0.094       0  4368.8   0.045       0  4375.9   0.094       0
  4589.6   0.035       0  4690.1   0.045       0  7966.8    0.07       0
  9598.9   0.035       0  9740.8    0.07       0  9846.3   0.045       0
Bank Sta=4368.8,4375.9
Exp/Cntr=0.3,0.1

Type RM Length L Ch R = 1,3000,500,500,500
BEGIN DESCRIPTION:
Cottonwood Creek Trib01_6 6.0
END DESCRIPTION:
XS GIS Cut Line= 3
      1337101.17      6846372.14      1337230.03      6846188.43
      1338322.68      6840991.56
#Sta/Elev= 30
  4775.6 2393.29  4795.0 2392.85  4803.7 2390.87  4845.5 2392.88  4890.0 2390.16
  4933.5 2390.48  4935.9 2390.15  4936.4 2389.65  4943.0 2390.15  5064.0 2390.47
  6523.0 2392.59  7628.1 2391.73  7974.1 2392.36  8311.1 2394.90  8464.6 2395.24
  8499.8 2396.54  8679.2 2395.72  8699.6 2396.83  9077.5 2397.17  9118.6 2398.54
  9159.4 2397.73  9515.9 2399.67  9665.5 2399.06  9715.3 2400.13  9874.7 2399.98
  9925.8 2401.93  9936.3 2401.13 10096.7 2402.58 10122.4 2402.39 10310.5 2403.53
#Mann=9,-1,0
  4775.6   0.094       0  4933.5   0.035       0  4935.9   0.035       0
  4943.0   0.035       0  5064.0   0.045       0  8311.1    0.07       0
  9936.3   0.035       0 10096.7    0.07       0 10122.4   0.045       0
Bank Sta=4935.9,4943
Exp/Cntr=0.3,0.1

Type RM Length L Ch R = 1,2500,500,500,500
BEGIN DESCRIPTION:
Cottonwood Creek Trib01_6 5.0
END DESCRIPTION:
XS GIS Cut Line= 4
      1337775.64      6846494.50      1337704.78      6846374.99
      1337642.93      6846238.71      1338409.53      6841061.26
#Sta/Elev= 30
  4711.4 2394.08  4730.6 2393.65  4753.8 2391.17  4797.7 2393.53  4825.0 2392.68
  4834.8 2391.13  4840.6 2391.89  4845.7 2390.31  4883.2 2390.74  4898.3 2389.90
  4898.8 2389.40  4905.5 2389.90  5029.4 2390.56  5871.4 2391.24  6223.9 2392.75
  7713.0 2392.54  8120.0 2393.99  8238.5 2395.53  8283.3 2395.55  8451.4 2396.15
  9084.8 2398.61  9721.6 2399.47  9863.2 2400.12  9897.1 2401.91  9921.9 2400.56
  9988.2 2401.48 10024.9 2401.57 10045.1 2403.26 10086.8 2402.37 10233.9 2403.20
#Mann=11,-1,0
  4711.4   0.094       0  4883.2   0.035       0  4898.3   0.035       0
  4905.5   0.035       0  5029.4   0.045       0  8238.5    0.07       0
  8283.3   0.045       0  8451.4    0.07       0  9921.9   0.035       0
  9988.2    0.07       0 10086.8   0.045       0
Bank Sta=4898.3,4905.5
Exp/Cntr=0.3,0.1

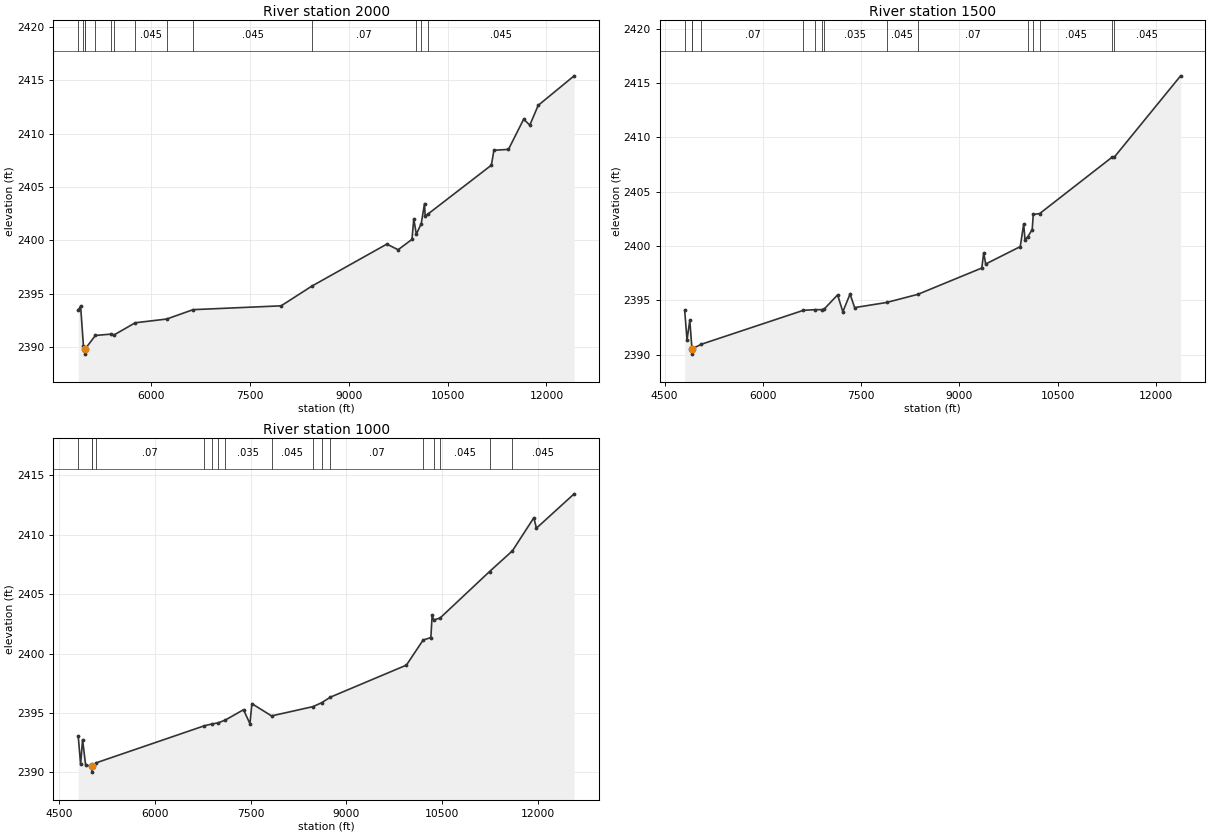
Type RM Length L Ch R = 1,2000,500,500,500
BEGIN DESCRIPTION:
Cottonwood Creek Trib01_6 4.0
END DESCRIPTION:
XS GIS Cut Line= 3
      1338005.01      6846487.97      1338054.60      6846387.77
      1338687.56      6838993.61
#Sta/Elev= 30
  4888.2 2393.45  4924.6 2393.84  4967.9 2390.07  4988.3 2389.83  4988.8 2389.33
  4995.5 2389.83  5149.3 2391.08  5392.5 2391.21  5432.3 2391.13  5754.2 2392.27
  6231.1 2392.62  6633.4 2393.50  7970.6 2393.86  8437.3 2395.71  9576.4 2399.65
  9747.1 2399.12  9957.8 2400.09  9985.3 2402.01 10024.1 2400.57 10098.8 2401.58
 10148.5 2403.45 10158.6 2402.24 10196.9 2402.45 11163.7 2407.05 11202.4 2408.45
 11423.2 2408.53 11654.0 2411.36 11747.9 2410.81 11874.8 2412.66 12421.2 2415.43
#Mann=14,-1,0
  4888.2   0.094       0  4967.9   0.035       0  4988.3   0.035       0
  4995.5   0.035       0  5149.3   0.094       0  5392.5   0.035       0
  5432.3   0.094       0  5754.2   0.045       0  6231.1    0.07       0
  6633.4   0.045       0  8437.3    0.07       0 10024.1   0.035       0
 10098.8    0.07       0 10196.9   0.045       0
Bank Sta=4988.3,4995.5
Exp/Cntr=0.3,0.1

Type RM Length L Ch R = 1,1500,500,500,500
BEGIN DESCRIPTION:
Cottonwood Creek Trib01_6 3.0
END DESCRIPTION:
XS GIS Cut Line= 3
      1338369.41      6846601.28      1338474.09      6846437.47
      1338722.28      6839063.05
#Sta/Elev= 30
  4805.6 2394.08  4841.5 2391.39  4883.8 2393.16  4916.6 2390.56  4917.1 2390.06
  4923.8 2390.56  5060.4 2390.97  6618.4 2394.09  6800.3 2394.15  6898.2 2394.15
  6936.3 2394.21  7140.7 2395.51  7220.7 2393.96  7330.8 2395.59  7400.8 2394.34
  7887.6 2394.81  8366.5 2395.56  9342.4 2397.98  9371.9 2399.38  9402.0 2398.35
  9929.9 2399.95  9982.3 2402.03 10002.3 2400.59 10041.9 2400.83 10112.4 2401.52
 10128.5 2402.91 10226.4 2402.99 11326.8 2408.15 11364.3 2408.17 12378.6 2415.66
#Mann=15,-1,0
  4805.6   0.094       0  4916.6    0.07       0  4923.8   0.094       0
  5060.4    0.07       0  6618.4   0.045       0  6800.3    0.07       0
  6898.2   0.045       0  6936.3   0.035       0  7887.6   0.045       0
  8366.5    0.07       0 10041.9   0.035       0 10128.5    0.07       0
 10226.4   0.045       0 11326.8    0.07       0 11364.3   0.045       0
Bank Sta=4916.6,4923.8
Exp/Cntr=0.3,0.1

Type RM Length L Ch R = 1,1000,0,0,0
BEGIN DESCRIPTION:
Cottonwood Creek Trib01_6 2.0
END DESCRIPTION:
XS GIS Cut Line= 3
      1338780.87      6846686.35      1338886.78      6846520.24
      1337958.51      6839012.01
#Sta/Elev= 30
  4803.0 2393.08  4840.6 2390.68  4871.0 2392.76  4919.6 2390.61  5018.8 2390.53
  5019.3 2390.03  5026.1 2390.53  5082.4 2390.81  6778.2 2393.93  6893.0 2394.08
  6992.0 2394.17  7104.9 2394.41  7390.3 2395.28  7491.1 2394.10  7521.3 2395.79
  7829.0 2394.76  8477.2 2395.54  8613.3 2395.87  8751.3 2396.34  9939.6 2399.03
 10201.5 2401.14 10322.5 2401.35 10342.6 2403.21 10366.5 2402.83 10466.2 2402.99
 11240.5 2406.90 11598.4 2408.64 11934.6 2411.43 11974.9 2410.55 12565.4 2413.44
#Mann=17,-1,0
  4803.0   0.094       0  5018.8    0.07       0  5026.1   0.094       0
  5082.4    0.07       0  6778.2   0.045       0  6893.0    0.07       0
  6992.0   0.045       0  7104.9   0.035       0  7829.0   0.045       0
  8477.2    0.07       0  8613.3   0.045       0  8751.3    0.07       0
 10201.5   0.035       0 10366.5    0.07       0 10466.2   0.045       0
 11240.5    0.07       0 11598.4   0.045       0
Bank Sta=5018.8,5026.1
Exp/Cntr=0.3,0.1

Chan Stop Cuts=-1