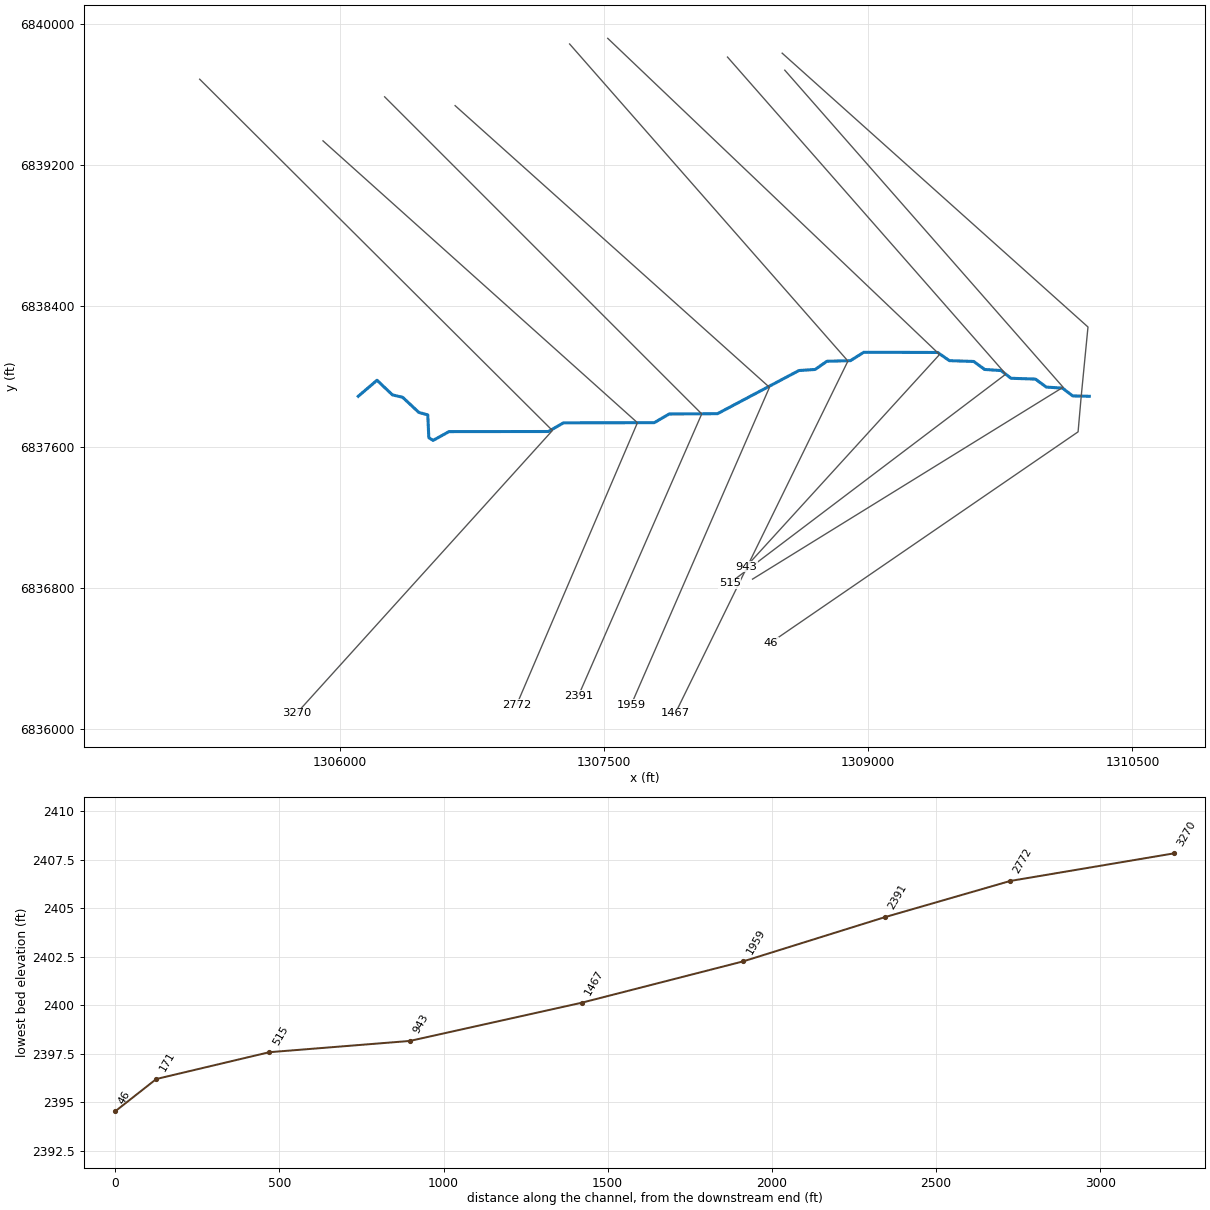
--- Cottonwood Creek Trib023.prj (project) ---

Proj Title=Cottonwood Creek Trib023 Base Level Engineering
Current Plan=p01
Default Exp/Contr=0.3,0.1
English Units
Geom File=g01
Flow File=f01
Plan File=p01
BEGIN DESCRIPTION:
Cottonwood Creek Trib023
END DESCRIPTION:

--- Cottonwood Creek Trib023.p01 (plan) ---

Plan Title=Multiple Run
Short Identifier=Multiple
Geom File=g01
Flow File=f01
Subcritical Flow
K Sum by GR= 0
Std Step Tol= 0.01
Critical Tol= 0.01
Num of Std Step Trials= 20
Max Error Tol= 0.3
Flow Tol Ratio= 0.001
Split Flow NTrial= 30
Split Flow Tol= 0.02
Split Flow Ratio= 0.02
Log Output Level= 0
Friction Slope Method= 1
Unsteady Friction Slope Method= 2
Unsteady Bridges Friction Slope Method= 1
Parabolic Critical Depth
Global Vel Dist=  1 , 1 , 1
Global Log Level= 0
CheckData=True
Encroach Param= -1, 0, 0, 0
BEGIN DESCRIPTION:
Multiple Run
END DESCRIPTION:

--- Cottonwood Creek Trib023.f01 (steady flow) ---

Flow Title=Multiple
Number of Profiles=7
Profile Names=10-year,25-year,50-year,1pct_min,100-year,1pct_plu,500-year
River Rch & RM= Cottonwood Creek,Reach-1,3270
     226     312     382     232     463     924     689
Boundary for River Rch & Prof#=Cottonwood Creek,Reach-1,1
Up Type=0
Dn Type=3
Dn Slope=0.005
Boundary for River Rch & Prof#=Cottonwood Creek,Reach-1,2
Up Type=0
Dn Type=3
Dn Slope=0.005
Boundary for River Rch & Prof#=Cottonwood Creek,Reach-1,3
Up Type=0
Dn Type=3
Dn Slope=0.005
Boundary for River Rch & Prof#=Cottonwood Creek,Reach-1,4
Up Type=0
Dn Type=3
Dn Slope=0.005
Boundary for River Rch & Prof#=Cottonwood Creek,Reach-1,5
Up Type=0
Dn Type=3
Dn Slope=0.005
Boundary for River Rch & Prof#=Cottonwood Creek,Reach-1,6
Up Type=0
Dn Type=3
Dn Slope=0.005
Boundary for River Rch & Prof#=Cottonwood Creek,Reach-1,7
Up Type=0
Dn Type=3
Dn Slope=0.005

--- Cottonwood Creek Trib023.g01 (geometry) ---

Geom Title=Existing Conditions

River Reach=Cottonwood Creek,Reach-1
Reach XY= 30
      1306105.00      6837888.00      1306211.66      6837979.08
      1306298.95      6837896.20      1306357.28      6837882.13
      1306449.31      6837796.32      1306499.81      6837782.55
      1306505.68      6837653.28      1306529.67      6837637.38
      1306620.19      6837687.46      1307184.97      6837688.07
      1307270.22      6837737.48      1307784.97      6837738.07
      1307870.22      6837787.48      1308144.50      6837789.20
      1308606.58      6838034.17      1308699.02      6838040.36
      1308765.51      6838086.77      1308899.06      6838090.27
      1308975.03      6838137.93      1309394.50      6838136.78
      1309460.94      6838090.27      1309599.06      6838085.73
      1309660.98      6838040.36      1309753.40      6838034.14
      1309810.94      6837990.27      1309949.06      6837985.73
      1310010.98      6837940.35      1310103.42      6837934.17
      1310160.87      6837890.10      1310255.00      6837888.00

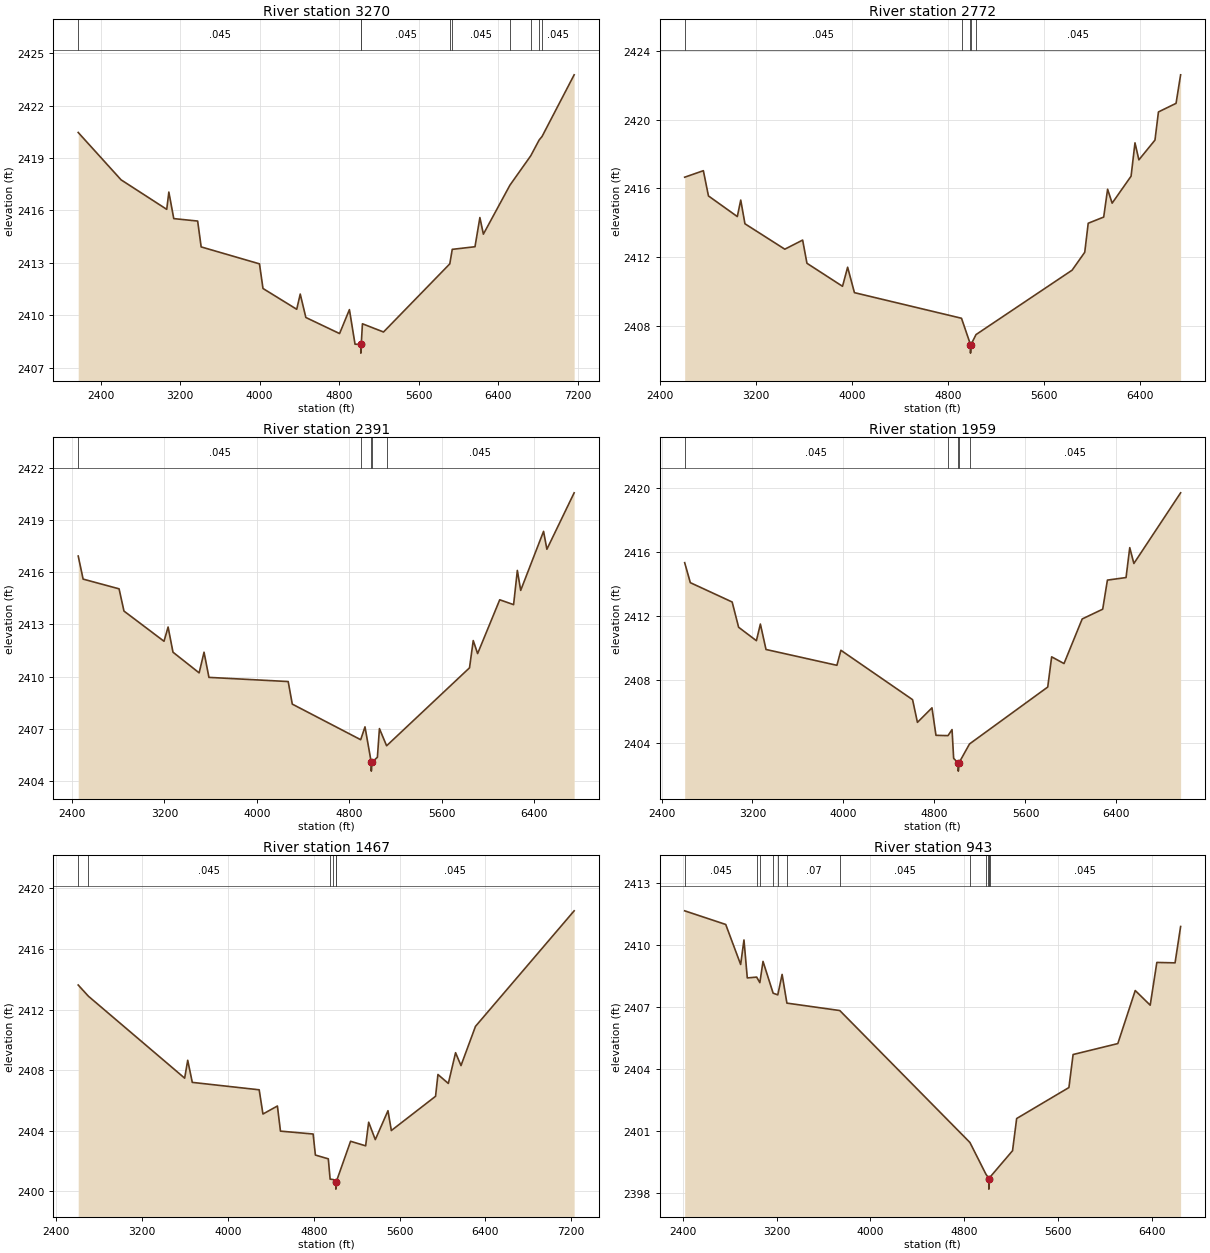
Type RM Length L Ch R = 1,3270,498,498,498
BEGIN DESCRIPTION:
Cottonwood Creek Trib023 5.0
END DESCRIPTION:
XS GIS Cut Line= 3
      1305205.01      6839687.99      1307207.33      6837693.75
      1305755.01      6836088.01
#Sta/Elev= 30
  2174.0 2420.46  2605.3 2417.75  3064.9 2416.06  3086.2 2417.05  3135.6 2415.53
  3376.1 2415.39  3411.4 2413.91  3998.3 2412.94  4033.7 2411.53  4373.1 2410.34
  4408.4 2411.21  4465.0 2409.87  4804.4 2408.95  4903.4 2410.32  4960.0 2408.34
  5017.9 2408.33  5018.2 2407.83  5022.4 2408.33  5034.4 2409.51  5246.6 2409.04
  5913.6 2412.94  5938.3 2413.77  6167.2 2413.92  6216.5 2415.59  6251.6 2414.64
  6518.4 2417.44  6728.7 2419.13  6812.8 2420.03  6842.0 2420.23  7165.1 2423.76
#Mann=9,-1,0
  2174.0   0.045       0  5017.9   0.045       0  5022.4   0.045       0
  5913.6    0.07       0  5938.3   0.045       0  6518.4    0.07       0
  6728.7   0.045       0  6812.8    0.07       0  6842.0   0.045       0
Bank Sta=5017.9,5022.4
Exp/Cntr=0.3,0.1

Type RM Length L Ch R = 1,2772,381,381,381
BEGIN DESCRIPTION:
Cottonwood Creek Trib023 4.0
END DESCRIPTION:
XS GIS Cut Line= 3
      1305904.98      6839338.02      1307690.02      6837737.96
      1307005.01      6836138.03
#Sta/Elev= 30
  2602.8 2416.65  2758.7 2417.03  2801.3 2415.56  3042.0 2414.36  3070.5 2415.32
  3105.6 2413.94  3438.2 2412.46  3587.0 2412.99  3622.9 2411.64  3919.7 2410.30
  3962.3 2411.41  4019.1 2409.93  4912.4 2408.44  4987.2 2406.91  4987.5 2406.41
  4991.7 2406.91  5033.6 2407.49  5835.3 2411.24  5940.5 2412.28  5969.5 2413.97
  6098.6 2414.33  6131.3 2415.95  6169.1 2415.14  6327.1 2416.71  6359.7 2418.65
  6392.2 2417.66  6526.4 2418.81  6555.5 2420.45  6702.3 2420.95  6740.4 2422.61
#Mann=5,-1,0
  2602.8   0.045       0  4912.4    0.07       0  4987.2    0.07       0
  4991.7    0.07       0  5033.6   0.045       0
Bank Sta=4987.2,4991.7
Exp/Cntr=0.3,0.1

Type RM Length L Ch R = 1,2391,432,432,432
BEGIN DESCRIPTION:
Cottonwood Creek Trib023 3.0
END DESCRIPTION:
XS GIS Cut Line= 3
      1306254.97      6839588.03      1308055.03      6837787.92
      1307354.99      6836187.97
#Sta/Elev= 30
  2454.3 2416.94  2496.8 2415.61  2807.9 2415.05  2850.3 2413.77  3196.8 2412.03
  3232.2 2412.85  3274.6 2411.40  3500.9 2410.21  3543.3 2411.40  3585.7 2409.95
  4271.6 2409.71  4307.0 2408.41  4899.1 2406.36  4936.3 2407.10  4990.6 2405.05
  4990.9 2404.55  4995.1 2405.05  5043.6 2405.35  5061.2 2407.00  5123.3 2406.01
  5840.8 2410.50  5873.1 2412.07  5911.0 2411.32  6102.4 2414.42  6222.4 2414.14
  6254.8 2416.11  6283.7 2414.96  6481.7 2418.36  6510.5 2417.33  6746.4 2420.58
#Mann=5,-1,0
  2454.3   0.045       0  4899.1    0.07       0  4990.6    0.07       0
  4995.1    0.07       0  5123.3   0.045       0
Bank Sta=4990.6,4995.1
Exp/Cntr=0.3,0.1

Type RM Length L Ch R = 1,1959,492,492,492
BEGIN DESCRIPTION:
Cottonwood Creek Trib023 2.0
END DESCRIPTION:
XS GIS Cut Line= 3
      1306655.01      6839537.99      1308439.61      6837938.94
      1307655.01      6836138.03
#Sta/Elev= 30
  2603.8 2415.31  2653.5 2414.06  3021.3 2412.85  3078.1 2411.27  3234.4 2410.43
  3269.5 2411.47  3318.9 2409.88  3942.4 2408.89  3977.5 2409.83  4607.7 2406.74
  4650.3 2405.32  4778.2 2406.23  4813.3 2404.51  4919.2 2404.49  4954.6 2404.87
  4968.8 2403.07  5009.5 2402.77  5009.8 2402.27  5014.4 2402.77  5108.3 2403.97
  5796.0 2407.53  5830.4 2409.42  5939.1 2409.00  6099.0 2411.79  6279.3 2412.40
  6320.7 2414.22  6484.5 2414.38  6517.2 2416.25  6553.4 2415.26  6964.4 2419.68
#Mann=5,-1,0
  2603.8   0.045       0  4919.2    0.07       0  5009.5    0.07       0
  5014.4    0.07       0  5108.3   0.045       0
Bank Sta=5009.5,5014.4
Exp/Cntr=0.3,0.1

Type RM Length L Ch R = 1,1467,524,524,524
BEGIN DESCRIPTION:
Cottonwood Creek Trib023 1.0
END DESCRIPTION:
XS GIS Cut Line= 3
      1307304.99      6839888.01      1308884.96      6838088.09
      1307904.98      6836087.97
#Sta/Elev= 30
  2605.0 2413.62  2700.2 2412.88  3597.1 2407.47  3625.6 2408.65  3668.3 2407.19
  4291.7 2406.70  4326.8 2405.10  4461.6 2405.63  4490.0 2403.97  4794.6 2403.78
  4815.5 2402.39  4936.0 2402.14  4952.9 2400.80  4983.2 2400.77  5006.0 2400.64
  5006.3 2400.14  5011.0 2400.64  5143.5 2403.30  5284.0 2403.00  5312.1 2404.56
  5374.0 2403.41  5492.1 2405.32  5523.5 2404.01  5935.5 2406.27  5957.8 2407.71
  6054.6 2407.12  6122.1 2409.15  6172.7 2408.30  6307.7 2410.89  7227.3 2418.52
#Mann=6,-1,0
  2605.0    0.07       0  2700.2   0.045       0  4952.9    0.07       0
  4983.2   0.045       0  5006.0   0.045       0  5011.0   0.045       0
Bank Sta=5006,5011
Exp/Cntr=0.3,0.1

Type RM Length L Ch R = 1,943,428,428,428
BEGIN DESCRIPTION:
Cottonwood Creek Trib023 0.7
END DESCRIPTION:
XS GIS Cut Line= 3
      1307521.41      6839920.07      1309405.14      6838125.25
      1308306.32      6836919.80
#Sta/Elev= 30
  2415.2 2411.65  2765.6 2410.99  2893.0 2409.05  2921.3 2410.24  2949.6 2408.40
  3029.7 2408.44  3056.8 2408.17  3083.9 2409.20  3170.3 2407.66  3209.9 2407.58
  3246.9 2408.57  3287.7 2407.18  3739.1 2406.82  4849.8 2400.43  4987.7 2398.88
  5006.6 2398.74  5010.9 2398.67  5011.3 2398.17  5016.1 2398.67  5021.2 2398.75
  5213.6 2400.03  5248.8 2401.59  5694.7 2403.09  5730.5 2404.69  6112.2 2405.22
  6260.9 2407.79  6388.6 2407.08  6445.3 2409.15  6600.7 2409.13  6648.2 2410.89
#Mann=13,-1,0
  2415.2   0.045       0  3029.7    0.07       0  3056.8   0.045       0
  3170.3    0.07       0  3209.9   0.045       0  3287.7    0.07       0
  3739.1   0.045       0  4849.8    0.07       0  4987.7   0.045       0
  5006.6    0.07       0  5010.9   0.045       0  5016.1    0.07       0
  5021.2   0.045       0
Bank Sta=5010.9,5016.1
Exp/Cntr=0.3,0.1

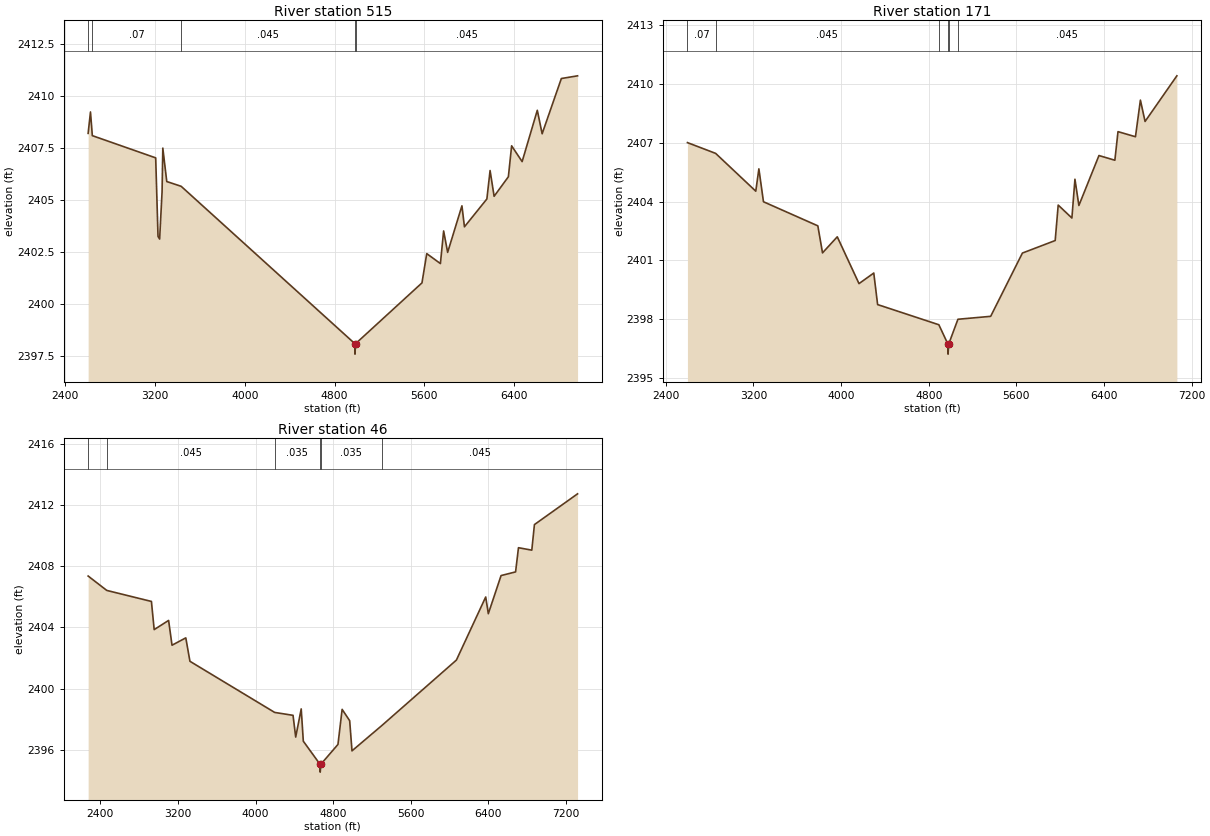
Type RM Length L Ch R = 1,515,344,344,344
BEGIN DESCRIPTION:
Cottonwood Creek Trib023 0.6
END DESCRIPTION:
XS GIS Cut Line= 3
      1308201.38      6839813.68      1309781.34      6838013.78
      1308213.39      6836826.87
#Sta/Elev= 30
  2603.5 2408.22  2624.4 2409.25  2640.8 2408.11  3205.5 2407.04  3226.3 2403.26
  3240.6 2403.13  3262.4 2405.41  3269.0 2407.51  3304.2 2405.90  3432.6 2405.67
  4981.1 2398.09  4981.5 2397.59  4986.3 2398.09  5578.4 2401.02  5621.0 2402.43
  5742.7 2401.95  5771.5 2403.52  5807.2 2402.49  5934.5 2404.73  5957.0 2403.72
  6156.8 2405.06  6185.4 2406.43  6221.3 2405.19  6348.4 2406.13  6377.4 2407.62
  6471.0 2406.86  6606.2 2409.33  6649.4 2408.20  6820.5 2410.86  6965.0 2410.99
#Mann=5,-1,0
  2603.5   0.045       0  2640.8    0.07       0  3432.6   0.045       0
  4981.1   0.045       0  4986.3   0.045       0
Bank Sta=4981.1,4986.3
Exp/Cntr=0.3,0.1

Type RM Length L Ch R = 1,171,125,125,125
BEGIN DESCRIPTION:
Cottonwood Creek Trib023 0.5
END DESCRIPTION:
XS GIS Cut Line= 3
      1308526.52      6839739.34      1310106.45      6837939.47
      1308343.49      6836850.13
#Sta/Elev= 30
  2597.3 2407.01  2854.6 2406.46  3221.0 2404.53  3249.4 2405.67  3291.2 2403.99
  3787.5 2402.76  3830.2 2401.38  3964.9 2402.20  4163.2 2399.81  4298.0 2400.35
  4333.1 2398.74  4892.2 2397.71  4975.6 2396.71  4976.1 2396.21  4981.0 2396.71
  5066.2 2397.99  5365.1 2398.14  5654.7 2401.37  5953.9 2402.01  5981.4 2403.82
  6106.4 2403.16  6134.2 2405.14  6170.2 2403.80  6353.5 2406.35  6498.6 2406.11
  6527.2 2407.57  6686.7 2407.31  6731.8 2409.18  6774.3 2408.09  7064.6 2410.42
#Mann=6,-1,0
  2597.3    0.07       0  2854.6   0.045       0  4892.2   0.035       0
  4975.6   0.035       0  4981.0   0.035       0  5066.2   0.045       0
Bank Sta=4975.6,4981
Exp/Cntr=0.3,0.1

Type RM Length L Ch R = 1,46,0,0,0
BEGIN DESCRIPTION:
Cottonwood Creek Trib023 0.25
END DESCRIPTION:
XS GIS Cut Line= 5
      1308511.64      6839835.78      1310247.74      6838281.35
      1310208.86      6837883.64      1310191.50      6837686.16
      1308446.48      6836489.44
#Sta/Elev= 30
  2273.9 2407.36  2465.9 2406.42  2926.1 2405.70  2954.5 2403.86  3103.2 2404.46
  3138.4 2402.84  3280.4 2403.32  3323.1 2401.79  4196.3 2398.45  4385.5 2398.26
  4413.1 2396.84  4469.9 2398.68  4491.6 2396.57  4665.2 2395.05  4665.6 2394.55
  4670.6 2395.05  4848.7 2396.36  4891.6 2398.65  4969.3 2397.91  4993.3 2395.94
  5302.0 2397.60  6069.4 2401.87  6371.3 2405.99  6398.3 2404.90  6529.6 2407.39
  6679.2 2407.63  6709.0 2409.21  6846.4 2409.05  6873.4 2410.72  7318.0 2412.73
#Mann=6,-1,0
  2273.9    0.07       0  2465.9   0.045       0  4196.3   0.035       0
  4665.2   0.035       0  4670.6   0.035       0  5302.0   0.045       0
Bank Sta=4665.2,4670.6
Exp/Cntr=0.3,0.1

Chan Stop Cuts=-1