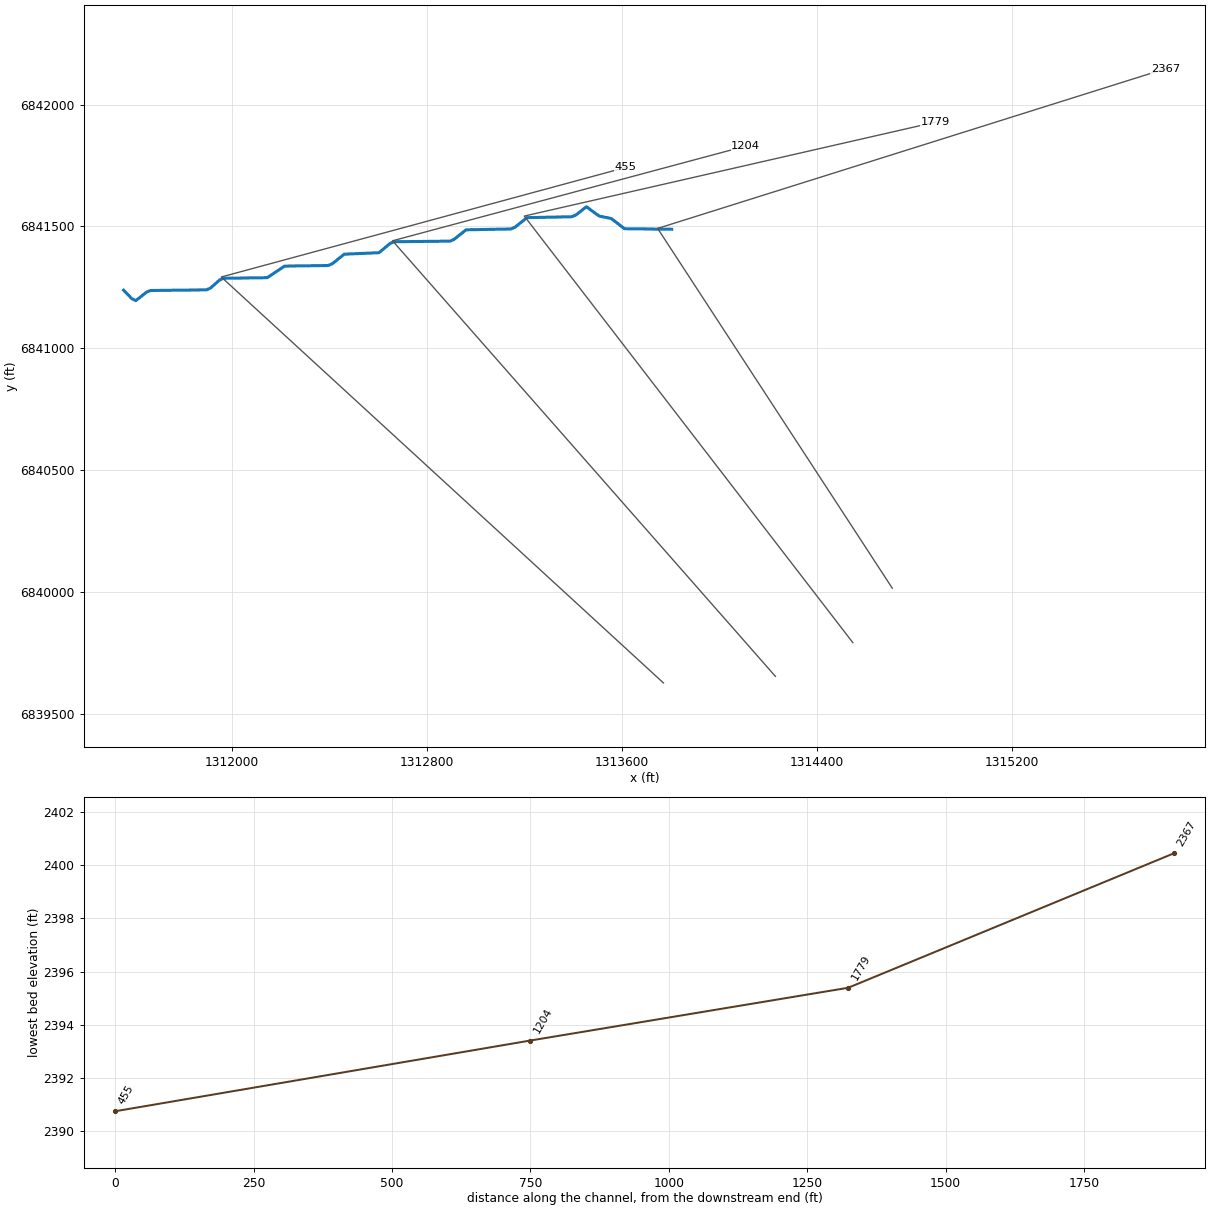
--- Cottonwood Creek Trib025.prj (project) ---

Proj Title=Cottonwood Creek Trib025 Base Level Engineering
Current Plan=p01
Default Exp/Contr=0.3,0.1
English Units
Geom File=g01
Flow File=f01
Plan File=p01
BEGIN DESCRIPTION:
Cottonwood Creek Trib025
END DESCRIPTION:

--- Cottonwood Creek Trib025.p01 (plan) ---

Plan Title=Multiple Run
Short Identifier=Multiple
Geom File=g01
Flow File=f01
Subcritical Flow
K Sum by GR= 0
Std Step Tol= 0.01
Critical Tol= 0.01
Num of Std Step Trials= 20
Max Error Tol= 0.3
Flow Tol Ratio= 0.001
Split Flow NTrial= 30
Split Flow Tol= 0.02
Split Flow Ratio= 0.02
Log Output Level= 0
Friction Slope Method= 1
Unsteady Friction Slope Method= 2
Unsteady Bridges Friction Slope Method= 1
Parabolic Critical Depth
Global Vel Dist=  1 , 1 , 1
Global Log Level= 0
CheckData=True
Encroach Param= -1, 0, 0, 0
BEGIN DESCRIPTION:
Multiple Run
END DESCRIPTION:

--- Cottonwood Creek Trib025.f01 (steady flow) ---

Flow Title=Multiple
Number of Profiles=7
Profile Names=10-year,25-year,50-year,1pct_min,100-year,1pct_plu,500-year
River Rch & RM= Cottonwood Creek,Reach-1,2367
     224     312     385     236     470     938     712
Boundary for River Rch & Prof#=Cottonwood Creek,Reach-1,1
Up Type=0
Dn Type=3
Dn Slope=0.005
Boundary for River Rch & Prof#=Cottonwood Creek,Reach-1,2
Up Type=0
Dn Type=3
Dn Slope=0.005
Boundary for River Rch & Prof#=Cottonwood Creek,Reach-1,3
Up Type=0
Dn Type=3
Dn Slope=0.005
Boundary for River Rch & Prof#=Cottonwood Creek,Reach-1,4
Up Type=0
Dn Type=3
Dn Slope=0.005
Boundary for River Rch & Prof#=Cottonwood Creek,Reach-1,5
Up Type=0
Dn Type=3
Dn Slope=0.005
Boundary for River Rch & Prof#=Cottonwood Creek,Reach-1,6
Up Type=0
Dn Type=3
Dn Slope=0.005
Boundary for River Rch & Prof#=Cottonwood Creek,Reach-1,7
Up Type=0
Dn Type=3
Dn Slope=0.005

--- Cottonwood Creek Trib025.g01 (geometry) ---

Geom Title=Existing Conditions

River Reach=Cottonwood Creek,Reach-1
Reach XY= 30
      1313805.00      6841488.00      1313610.92      6841490.23
      1313557.17      6841531.91      1313506.64      6841542.42
      1313455.01      6841580.47      1313411.19      6841546.46
      1313394.56      6841539.38      1313210.94      6841535.74
      1313161.06      6841496.14      1313144.49      6841489.22
      1312960.94      6841485.74      1312911.06      6841446.14
      1312894.50      6841439.22      1312665.50      6841436.78
      1312648.94      6841429.86      1312603.43      6841391.79
      1312460.94      6841385.73      1312411.06      6841346.14
      1312394.49      6841339.22      1312215.51      6841336.78
      1312144.49      6841289.22      1311965.51      6841286.78
      1311948.94      6841279.86      1311911.06      6841246.14
      1311894.50      6841239.22      1311665.42      6841236.69
      1311648.78      6841229.71      1311604.86      6841194.91
      1311588.16      6841203.54      1311555.00      6841238.00

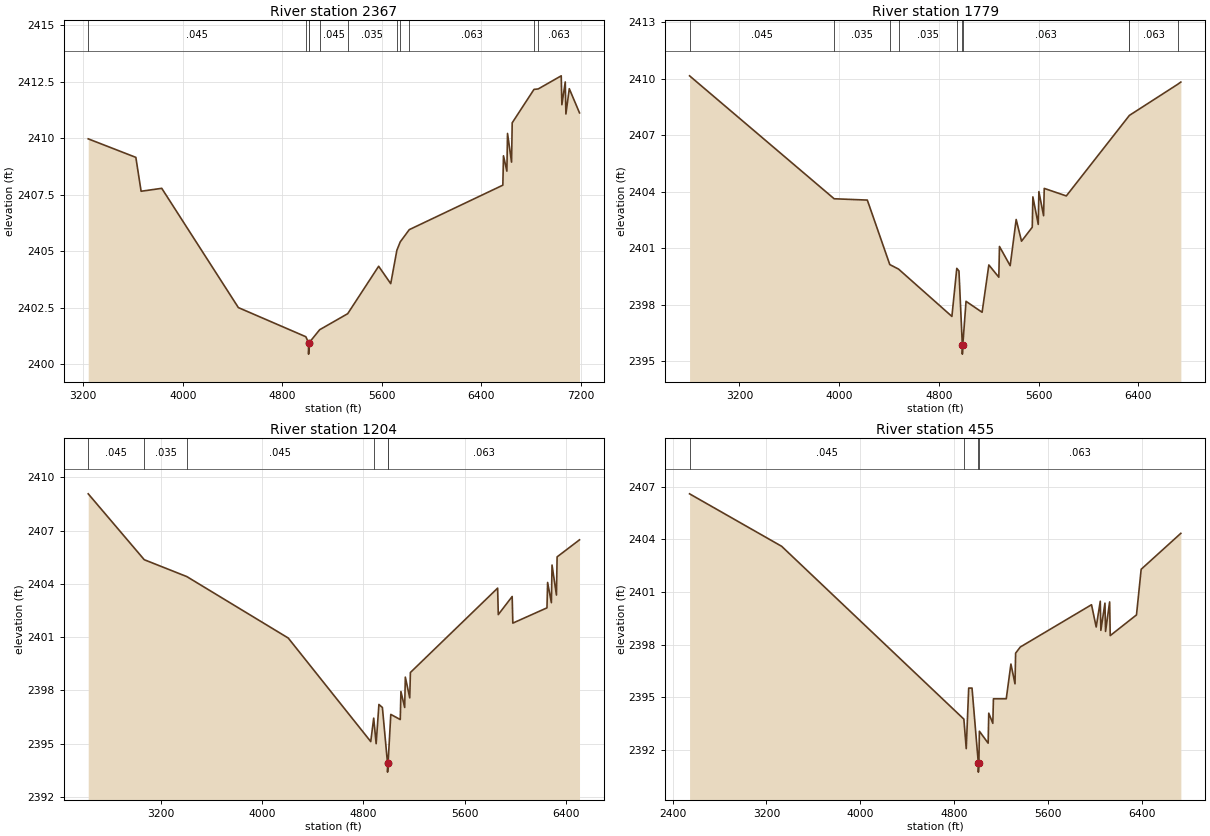
Type RM Length L Ch R = 1,2367,588,588,588
BEGIN DESCRIPTION:
Cottonwood Creek Trib025 4.0
END DESCRIPTION:
XS GIS Cut Line= 3
      1314710.39      6840014.52      1313747.17      6841491.45
      1315831.22      6842146.72
#Sta/Elev= 30
  3240.9 2409.98  3623.6 2409.16  3665.8 2407.66  3831.7 2407.79  4447.4 2402.51
  4989.7 2401.22  5011.5 2400.95  5011.7 2400.45  5015.5 2400.95  5100.7 2401.53
  5326.0 2402.24  5574.7 2404.34  5671.8 2403.57  5721.2 2405.05  5748.3 2405.42
  5820.7 2405.96  6572.7 2407.93  6577.9 2409.23  6605.1 2408.55  6610.3 2410.22
  6642.7 2408.95  6647.9 2410.69  6823.1 2412.17  6857.2 2412.19  7041.9 2412.77
  7047.1 2411.49  7074.3 2412.50  7079.5 2411.08  7106.7 2412.20  7188.8 2411.13
#Mann=11,-1,0
  3240.9   0.045       0  4989.7   0.035       0  5011.5   0.035       0
  5015.5   0.035       0  5100.7   0.045       0  5326.0   0.035       0
  5721.2   0.045       0  5748.3   0.035       0  5820.7   0.063       0
  6823.1   0.094       0  6857.2   0.063       0
Bank Sta=5011.5,5015.5
Exp/Cntr=0.3,0.1

Type RM Length L Ch R = 1,1779,575,575,575
BEGIN DESCRIPTION:
Cottonwood Creek Trib025 3.0
END DESCRIPTION:
XS GIS Cut Line= 3
      1314548.18      6839791.42      1313199.65      6841542.14
      1314886.13      6841927.43
#Sta/Elev= 30
  2800.5 2410.15  3960.0 2403.63  4226.0 2403.56  4406.1 2400.14  4476.4 2399.90
  4904.2 2397.39  4943.5 2399.94  4960.8 2399.80  4987.8 2395.89  4988.1 2395.39
  4991.8 2395.89  5017.6 2398.19  5146.5 2397.61  5200.5 2400.12  5280.5 2399.47
  5285.7 2401.10  5371.6 2400.08  5419.7 2402.53  5462.6 2401.38  5548.6 2402.12
  5553.7 2403.73  5596.7 2402.27  5601.8 2404.01  5639.6 2402.73  5644.8 2404.18
  5821.8 2403.78  6322.8 2408.01  6327.4 2408.05  6714.9 2409.70  6740.3 2409.82
#Mann=10,-1,0
  2800.5   0.045       0  3960.0   0.035       0  4406.1   0.045       0
  4476.4   0.035       0  4943.5   0.063       0  4987.8   0.063       0
  4991.8   0.063       0  6322.8   0.035       0  6327.4   0.063       0
  6714.9   0.094       0
Bank Sta=4987.8,4991.8
Exp/Cntr=0.3,0.1

Type RM Length L Ch R = 1,1204,749,749,749
BEGIN DESCRIPTION:
Cottonwood Creek Trib025 2.0
END DESCRIPTION:
XS GIS Cut Line= 3
      1314230.51      6839652.82      1312658.89      6841440.75
      1314108.82      6841829.43
#Sta/Elev= 30
  2625.6 2409.07  3068.3 2405.36  3404.6 2404.41  4205.9 2400.95  4857.8 2395.12
  4881.1 2396.44  4900.5 2395.00  4922.3 2397.21  4949.8 2397.04  4990.3 2393.90
  4990.6 2393.40  4994.7 2393.90  5016.2 2396.65  5091.0 2396.36  5096.2 2397.94
  5125.9 2397.04  5131.0 2398.75  5165.9 2397.58  5171.1 2399.01  5860.3 2403.76
  5865.5 2402.27  5975.2 2403.29  5980.4 2401.79  6250.1 2402.65  6255.3 2404.08
  6285.0 2402.94  6290.1 2405.06  6325.0 2403.37  6330.2 2405.52  6507.2 2406.48
#Mann=6,-1,0
  2625.6   0.045       0  3068.3   0.035       0  3404.6   0.045       0
  4881.1   0.063       0  4990.3   0.063       0  4994.7   0.063       0
Bank Sta=4990.3,4994.7
Exp/Cntr=0.3,0.1

Type RM Length L Ch R = 1,455,0,0,0
BEGIN DESCRIPTION:
Cottonwood Creek Trib025 1.0
END DESCRIPTION:
XS GIS Cut Line= 3
      1313770.86      6839625.80      1311955.90      6841292.04
      1313615.37      6841741.55
#Sta/Elev= 30
  2545.0 2406.60  3329.0 2403.61  4880.6 2393.76  4900.7 2392.08  4921.7 2395.53
  4950.0 2395.53  5003.8 2391.24  5004.1 2390.74  5008.3 2391.24  5012.8 2393.07
  5087.3 2392.39  5092.5 2394.10  5127.1 2393.52  5132.3 2394.92  5241.5 2394.92
  5281.3 2396.90  5316.0 2395.77  5321.2 2397.52  5361.0 2397.87  5967.5 2400.28
  6007.3 2399.01  6042.0 2400.48  6047.1 2398.82  6081.8 2400.37  6087.0 2398.76
  6121.7 2400.44  6126.8 2398.52  6350.4 2399.70  6390.2 2402.30  6728.1 2404.35
#Mann=4,-1,0
  2545.0   0.045       0  4880.6   0.063       0  5003.8   0.063       0
  5008.3   0.063       0
Bank Sta=5003.8,5008.3
Exp/Cntr=0.3,0.1

Chan Stop Cuts=-1