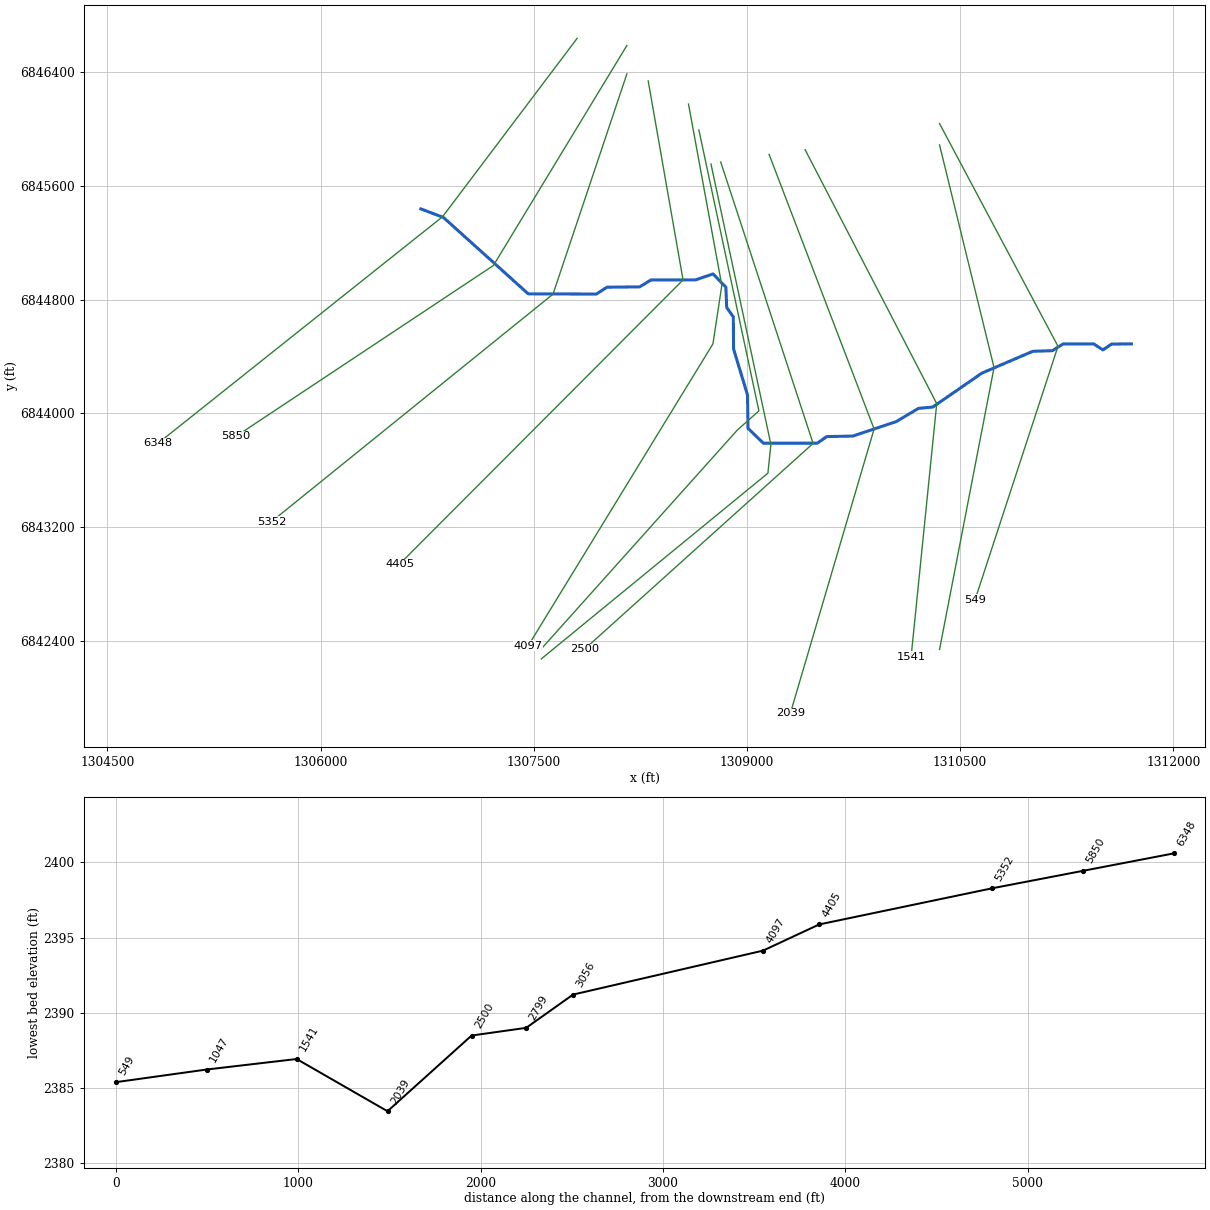
--- Cottonwood Creek Trib026.prj (project) ---

Proj Title=Cottonwood Creek Trib026 Base Level Engineering
Current Plan=p01
Default Exp/Contr=0.3,0.1
English Units
Geom File=g01
Flow File=f01
Plan File=p01
BEGIN DESCRIPTION:
Cottonwood Creek Trib026
END DESCRIPTION:

--- Cottonwood Creek Trib026.p01 (plan) ---

Plan Title=Multiple Run
Short Identifier=Multiple
Geom File=g01
Flow File=f01
Subcritical Flow
K Sum by GR= 0
Std Step Tol= 0.01
Critical Tol= 0.01
Num of Std Step Trials= 20
Max Error Tol= 0.3
Flow Tol Ratio= 0.001
Split Flow NTrial= 30
Split Flow Tol= 0.02
Split Flow Ratio= 0.02
Log Output Level= 0
Friction Slope Method= 1
Unsteady Friction Slope Method= 2
Unsteady Bridges Friction Slope Method= 1
Parabolic Critical Depth
Global Vel Dist=  1 , 1 , 1
Global Log Level= 0
CheckData=True
Encroach Param= -1, 0, 0, 0
BEGIN DESCRIPTION:
Multiple Run
END DESCRIPTION:

--- Cottonwood Creek Trib026.f01 (steady flow) ---

Flow Title=Multiple
Number of Profiles=7
Profile Names=10-year,25-year,50-year,1pct_min,100-year,1pct_plu,500-year
River Rch & RM= Cottonwood Creek,Reach-1,6348
     206     284     347     211     421     840     627
River Rch & RM= Cottonwood Creek,Reach-1,2799
     318     449     558     344     687    1370    1054
River Rch & RM= Cottonwood Creek,Reach-1,2039
     327     461     573     353     704    1405    1080
Boundary for River Rch & Prof#=Cottonwood Creek,Reach-1,1
Up Type=0
Dn Type=3
Dn Slope=0.005
Boundary for River Rch & Prof#=Cottonwood Creek,Reach-1,2
Up Type=0
Dn Type=3
Dn Slope=0.005
Boundary for River Rch & Prof#=Cottonwood Creek,Reach-1,3
Up Type=0
Dn Type=3
Dn Slope=0.005
Boundary for River Rch & Prof#=Cottonwood Creek,Reach-1,4
Up Type=0
Dn Type=3
Dn Slope=0.005
Boundary for River Rch & Prof#=Cottonwood Creek,Reach-1,5
Up Type=0
Dn Type=3
Dn Slope=0.005
Boundary for River Rch & Prof#=Cottonwood Creek,Reach-1,6
Up Type=0
Dn Type=3
Dn Slope=0.005
Boundary for River Rch & Prof#=Cottonwood Creek,Reach-1,7
Up Type=0
Dn Type=3
Dn Slope=0.005

--- Cottonwood Creek Trib026.g01 (geometry) ---

Geom Title=Existing Conditions

River Reach=Cottonwood Creek,Reach-1
Reach XY= 30
      1306705.00      6845438.00      1306864.69      6845377.25
      1307460.85      6844840.06      1307939.78      6844838.52
      1308015.50      6844886.78      1308244.50      6844889.22
      1308325.03      6844937.93      1308639.79      6844938.54
      1308761.08      6844980.53      1308851.46      6844886.55
      1308857.27      6844743.94      1308903.78      6844677.50
      1308905.52      6844453.22      1309003.78      6844127.50
      1309007.05      6843893.84      1309115.43      6843789.04
      1309494.50      6843789.22      1309560.94      6843835.74
      1309744.50      6843839.22      1310049.03      6843940.33
      1310206.59      6844034.17      1310307.42      6844043.54
      1310652.71      6844282.16      1311010.93      6844435.75
      1311149.06      6844440.27      1311225.03      6844487.93
      1311439.84      6844487.34      1311505.00      6844445.56
      1311565.41      6844486.66      1311705.00      6844488.00

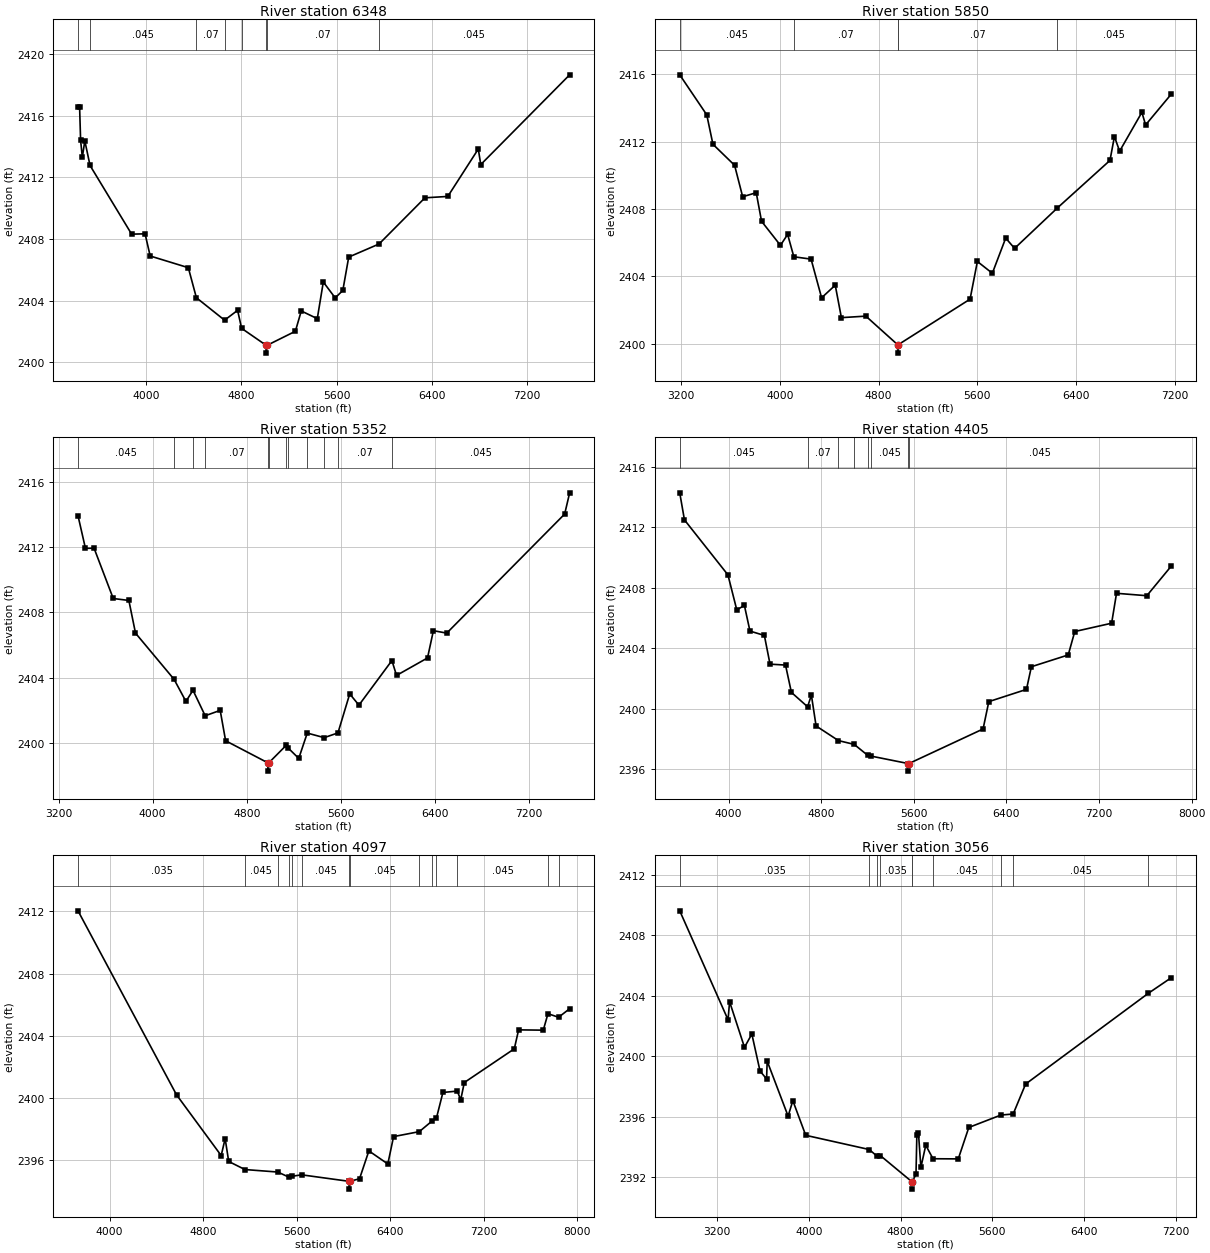
Type RM Length L Ch R = 1,6348,498,498,498
BEGIN DESCRIPTION:
Cottonwood Creek Trib026 9.0
END DESCRIPTION:
XS GIS Cut Line= 3
      1307805.01      6846638.02      1306857.31      6845382.18
      1304855.02      6843788.01
#Sta/Elev= 30
  3426.7 2416.61  3440.3 2416.55  3448.6 2414.41  3463.1 2413.32  3484.0 2414.38
  3527.9 2412.78  3877.4 2408.32  3990.5 2408.34  4033.5 2406.90  4354.1 2406.14
  4421.8 2404.19  4658.8 2402.73  4768.3 2403.37  4802.0 2402.20  5009.9 2401.09
  5010.1 2400.59  5014.2 2401.09  5253.9 2402.01  5303.5 2403.33  5438.1 2402.83
  5488.7 2405.21  5588.6 2404.18  5652.7 2404.66  5702.3 2406.83  5957.3 2407.68
  6343.0 2410.68  6535.2 2410.77  6791.5 2413.85  6812.3 2412.84  7559.4 2418.67
#Mann=8,-1,0
  3426.7    0.07       0  3527.9   0.045       0  4421.8    0.07       0
  4658.8   0.035       0  4802.0    0.07       0  5009.9    0.07       0
  5014.2    0.07       0  5957.3   0.045       0
Bank Sta=5009.9,5014.2
Exp/Cntr=0.3,0.1

Type RM Length L Ch R = 1,5850,498,498,498
BEGIN DESCRIPTION:
Cottonwood Creek Trib026 8.0
END DESCRIPTION:
XS GIS Cut Line= 3
      1308155.00      6846588.00      1307215.64      6845039.55
      1305405.04      6843838.03
#Sta/Elev= 30
  3188.9 2415.98  3407.9 2413.60  3457.9 2411.85  3633.4 2410.60  3698.8 2408.73
  3808.8 2408.97  3851.9 2407.27  4005.0 2405.84  4063.2 2406.49  4113.5 2405.16
  4253.2 2405.02  4338.5 2402.72  4449.0 2403.47  4498.9 2401.54  4697.1 2401.63
  4954.8 2399.93  4955.1 2399.43  4959.2 2399.93  5541.6 2402.64  5600.8 2404.88
  5722.0 2404.18  5830.3 2406.27  5902.5 2405.66  6247.2 2408.05  6675.3 2410.89
  6711.4 2412.31  6753.5 2411.44  6934.0 2413.75  6964.0 2413.00  7173.0 2414.84
#Mann=5,-1,0
  3188.9   0.045       0  4113.5    0.07       0  4954.8    0.07       0
  4959.2    0.07       0  6247.2   0.045       0
Bank Sta=4954.8,4959.2
Exp/Cntr=0.3,0.1

Type RM Length L Ch R = 1,5352,947,947,947
BEGIN DESCRIPTION:
Cottonwood Creek Trib026 7.0
END DESCRIPTION:
XS GIS Cut Line= 3
      1308155.00      6846388.00      1307635.00      6844838.00
      1305654.97      6843237.98
#Sta/Elev= 30
  3365.1 2413.91  3428.4 2411.91  3501.8 2411.92  3664.7 2408.84  3797.6 2408.72
  3854.0 2406.72  4182.1 2403.89  4282.8 2402.54  4343.0 2403.22  4446.5 2401.66
  4574.2 2401.99  4620.3 2400.13  4981.9 2398.77  4982.3 2398.27  4986.5 2398.77
  5135.7 2399.85  5151.5 2399.69  5242.2 2399.05  5314.6 2400.60  5458.5 2400.32
  5575.6 2400.61  5675.6 2403.00  5753.9 2402.31  6034.3 2405.04  6073.7 2404.13
  6337.1 2405.20  6387.1 2406.87  6500.7 2406.72  7503.3 2414.01  7545.7 2415.31
#Mann=12,-1,0
  3365.1   0.045       0  4182.1    0.07       0  4343.0   0.045       0
  4446.5    0.07       0  4981.9    0.07       0  4986.5    0.07       0
  5135.7   0.035       0  5151.5    0.07       0  5314.6   0.035       0
  5458.5   0.045       0  5575.6    0.07       0  6034.3   0.045       0
Bank Sta=4981.9,4986.5
Exp/Cntr=0.3,0.1

Type RM Length L Ch R = 1,4405,308,308,308
BEGIN DESCRIPTION:
Cottonwood Creek Trib026 6.0
END DESCRIPTION:
XS GIS Cut Line= 3
      1308305.01      6846337.96      1308550.03      6844937.94
      1306554.98      6842937.98
#Sta/Elev= 30
  3578.7 2414.29  3619.3 2412.50  3994.9 2408.86  4071.4 2406.54  4137.0 2406.84
  4185.2 2405.14  4309.6 2404.85  4358.5 2402.95  4492.3 2402.89  4543.1 2401.08
  4682.9 2400.13  4715.7 2400.90  4756.3 2398.86  4949.5 2397.89  5085.4 2397.64
  5203.0 2396.91  5227.7 2396.87  5552.8 2396.37  5553.1 2395.87  5557.4 2396.37
  6198.5 2398.66  6248.0 2400.47  6573.3 2401.28  6615.7 2402.78  6933.9 2403.56
  6990.5 2405.11  7308.7 2405.66  7351.1 2407.64  7612.7 2407.48  7824.9 2409.45
#Mann=8,-1,0
  3578.7   0.045       0  4682.9    0.07       0  4949.5   0.035       0
  5085.4    0.07       0  5203.0   0.035       0  5227.7   0.045       0
  5552.8   0.035       0  5557.4   0.045       0
Bank Sta=5552.8,5557.4
Exp/Cntr=0.3,0.1

Type RM Length L Ch R = 1,4097,1041,1041,1041
BEGIN DESCRIPTION:
Cottonwood Creek Trib026 5.7
END DESCRIPTION:
XS GIS Cut Line= 4
      1308588.50      6846175.51      1308822.87      6844899.48
      1308760.37      6844488.02      1307460.43      6842363.64
#Sta/Elev= 30
  3729.3 2412.04  4571.8 2400.20  4953.7 2396.29  4987.5 2397.38  5018.0 2395.91
  5157.0 2395.39  5437.5 2395.23  5530.4 2394.91  5561.0 2394.96  5642.0 2395.05
  6049.3 2394.63  6049.6 2394.13  6054.0 2394.63  6136.9 2394.80  6216.6 2396.59
  6378.6 2395.75  6427.7 2397.51  6647.8 2397.83  6756.5 2398.51  6793.6 2398.68
  6849.7 2400.35  6972.4 2400.44  7002.1 2399.88  7032.6 2400.99  7460.2 2403.16
  7497.0 2404.38  7707.9 2404.36  7748.1 2405.42  7838.7 2405.19  7933.4 2405.74
#Mann=14,-1,0
  3729.3   0.035       0  5157.0   0.045       0  5437.5    0.07       0
  5530.4   0.045       0  5561.0    0.07       0  5642.0   0.045       0
  6049.3   0.035       0  6054.0   0.045       0  6647.8    0.07       0
  6756.5   0.045       0  6793.6    0.07       0  6972.4   0.045       0
  7748.1    0.07       0  7838.7   0.045       0
Bank Sta=6049.3,6054
Exp/Cntr=0.3,0.1

Type RM Length L Ch R = 1,3056,257,257,257
BEGIN DESCRIPTION:
Cottonwood Creek Trib026 5.6
END DESCRIPTION:
XS GIS Cut Line= 4
      1308661.40      6845993.26      1309083.87      6844016.62
      1308932.07      6843881.68      1307553.41      6842342.81
#Sta/Elev= 30
  2872.7 2409.62  3294.4 2402.41  3307.6 2403.61  3437.8 2400.59  3501.9 2401.47
  3573.4 2399.02  3630.6 2398.50  3635.7 2399.68  3818.3 2396.04  3859.8 2397.06
  3972.2 2394.77  4526.5 2393.83  4595.9 2393.38  4623.2 2393.43  4896.9 2391.71
  4897.3 2391.21  4901.6 2391.71  4934.4 2392.19  4941.9 2394.77  4956.2 2394.89
  4977.1 2392.65  5019.7 2394.11  5082.9 2393.22  5303.4 2393.21  5395.3 2395.29
  5675.2 2396.11  5782.5 2396.18  5891.0 2398.16  6963.0 2404.17  7163.2 2405.20
#Mann=10,-1,0
  2872.7   0.035       0  4526.5    0.07       0  4595.9   0.045       0
  4623.2   0.035       0  4896.9   0.035       0  4901.6   0.035       0
  5082.9   0.045       0  5675.2    0.07       0  5782.5   0.045       0
  6963.0    0.07       0
Bank Sta=4896.9,4901.6
Exp/Cntr=0.3,0.1

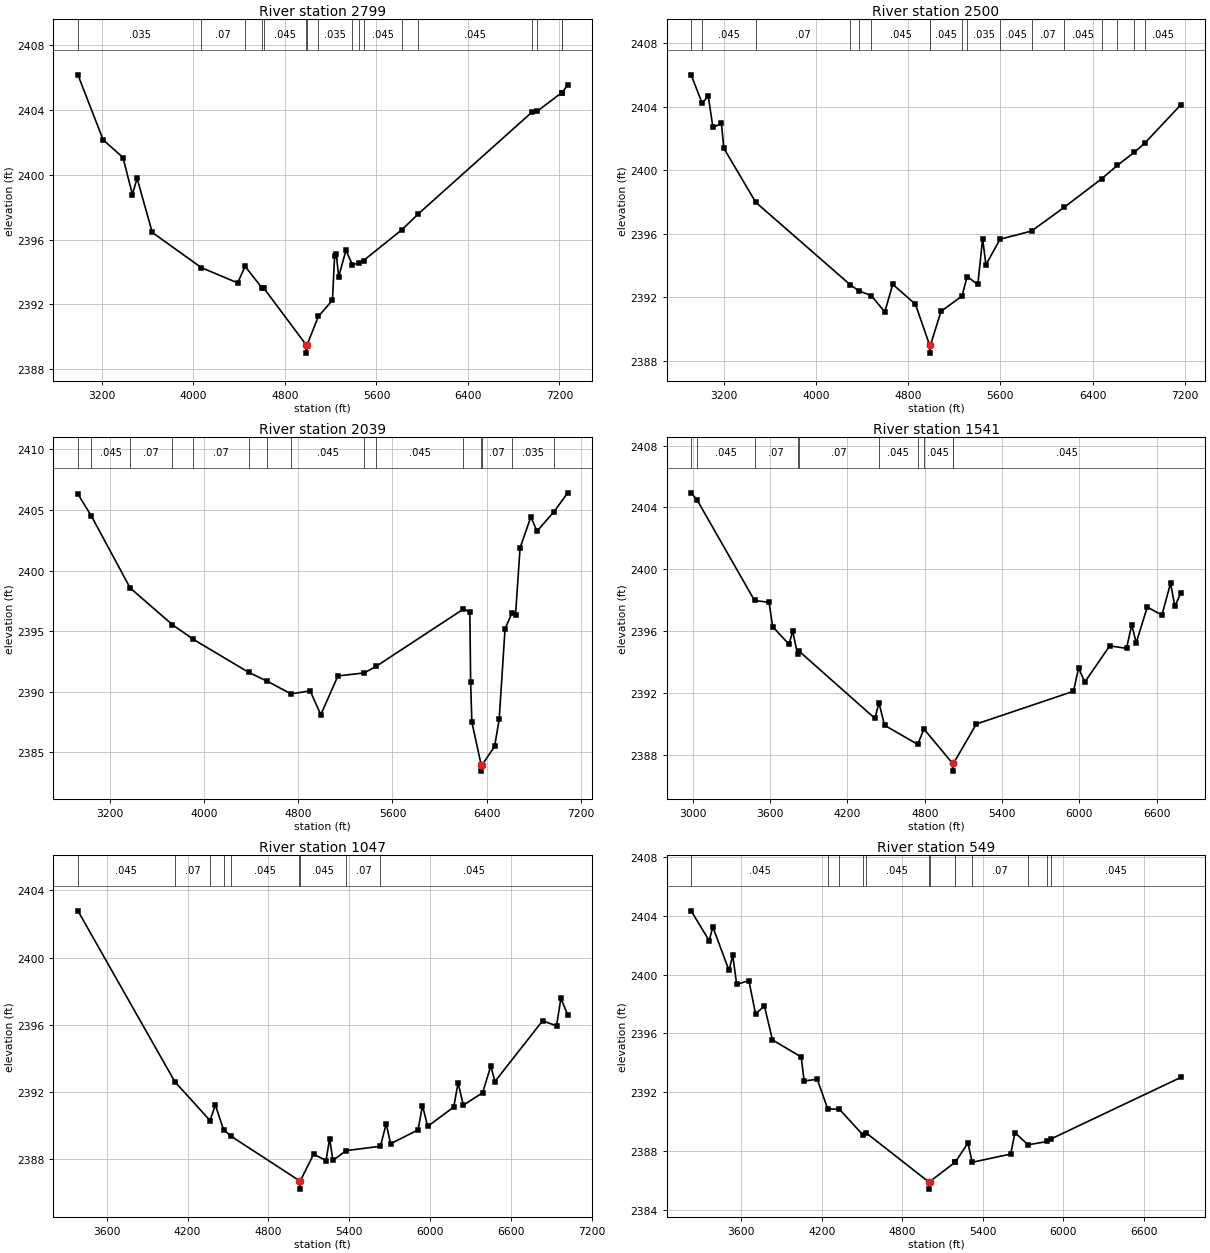
Type RM Length L Ch R = 1,2799,299,299,299
BEGIN DESCRIPTION:
Cottonwood Creek Trib026 5.5
END DESCRIPTION:
XS GIS Cut Line= 4
      1308746.54      6845753.86      1309168.20      6843780.48
      1309147.12      6843578.08      1307552.89      6842271.75
#Sta/Elev= 30
  2989.4 2406.16  3210.1 2402.15  3383.8 2401.06  3465.8 2398.78  3506.7 2399.78
  3639.6 2396.44  4069.1 2394.27  4386.1 2393.33  4451.2 2394.35  4601.6 2393.00
  4612.5 2393.03  4986.0 2389.50  4986.5 2389.00  4992.8 2389.50  5091.5 2391.26
  5214.8 2392.26  5233.8 2394.97  5248.1 2395.13  5269.0 2393.70  5332.8 2395.34
  5389.3 2394.45  5444.1 2394.55  5487.1 2394.71  5820.9 2396.60  5964.6 2397.58
  6962.4 2403.88  7003.7 2403.91  7218.0 2405.05  7224.2 2405.07  7271.9 2405.55
#Mann=17,-1,0
  2989.4   0.035       0  4069.1    0.07       0  4451.2   0.045       0
  4601.6   0.035       0  4612.5   0.045       0  4986.0   0.045       0
  4992.8   0.045       0  5091.5   0.035       0  5389.3   0.045       0
  5444.1    0.07       0  5487.1   0.045       0  5820.9    0.07       0
  5964.6   0.045       0  6962.4    0.07       0  7003.7   0.045       0
  7218.0    0.07       0  7224.2   0.045       0
Bank Sta=4986,4992.8
Exp/Cntr=0.3,0.1

Type RM Length L Ch R = 1,2500,461,461,461
BEGIN DESCRIPTION:
Cottonwood Creek Trib026 5.0
END DESCRIPTION:
XS GIS Cut Line= 3
      1308814.99      6845767.94      1309465.19      6843787.55
      1307855.03      6842338.03
#Sta/Elev= 30
  2915.6 2406.00  3012.0 2404.20  3064.0 2404.68  3105.0 2402.69  3178.7 2402.94
  3199.7 2401.38  3476.6 2397.98  4298.4 2392.78  4371.4 2392.41  4479.6 2392.11
  4596.5 2391.08  4665.4 2392.82  4862.7 2391.56  4985.6 2388.99  4986.1 2388.49
  4992.4 2388.99  5084.6 2391.12  5266.5 2392.08  5311.3 2393.31  5403.8 2392.81
  5445.6 2395.69  5474.0 2394.05  5597.5 2395.66  5869.7 2396.17  6152.6 2397.66
  6480.2 2399.47  6614.3 2400.30  6760.7 2401.12  6851.0 2401.69  7166.5 2404.12
#Mann=17,-1,0
  2915.6    0.07       0  3012.0   0.045       0  3476.6    0.07       0
  4298.4   0.045       0  4371.4    0.07       0  4479.6   0.045       0
  4985.6   0.045       0  4992.4   0.045       0  5266.5    0.07       0
  5311.3   0.035       0  5597.5   0.045       0  5869.7    0.07       0
  6152.6   0.045       0  6480.2    0.07       0  6614.3   0.045       0
  6760.7    0.07       0  6851.0   0.045       0
Bank Sta=4985.6,4992.4
Exp/Cntr=0.3,0.1

Type RM Length L Ch R = 1,2039,498,498,498
BEGIN DESCRIPTION:
Cottonwood Creek Trib026 4.0
END DESCRIPTION:
XS GIS Cut Line= 3
      1309155.55      6845821.36      1309894.45      6843889.33
      1309305.01      6841888.03
#Sta/Elev= 30
  2931.5 2406.31  3045.0 2404.51  3374.9 2398.56  3732.6 2395.54  3911.7 2394.32
  4380.7 2391.60  4534.1 2390.89  4739.4 2389.83  4901.6 2390.08  4991.8 2388.11
  5136.9 2391.31  5361.2 2391.56  5464.1 2392.12  6201.1 2396.82  6256.1 2396.60
  6262.8 2390.80  6273.2 2387.50  6352.6 2383.96  6353.1 2383.46  6359.5 2383.96
  6466.5 2385.51  6505.0 2387.75  6554.7 2395.19  6613.0 2396.50  6643.6 2396.34
  6682.1 2401.87  6773.6 2404.42  6825.9 2403.25  6969.5 2404.85  7086.3 2406.41
#Mann=15,-1,0
  2931.5    0.07       0  3045.0   0.045       0  3374.9    0.07       0
  3732.6   0.045       0  3911.7    0.07       0  4380.7   0.045       0
  4534.1    0.07       0  4739.4   0.045       0  5361.2    0.07       0
  5464.1   0.045       0  6201.1    0.07       0  6352.6   0.045       0
  6359.5    0.07       0  6613.0   0.035       0  6969.5   0.045       0
Bank Sta=6352.6,6359.5
Exp/Cntr=0.3,0.1

Type RM Length L Ch R = 1,1541,494,494,494
BEGIN DESCRIPTION:
Cottonwood Creek Trib026 3.0
END DESCRIPTION:
XS GIS Cut Line= 3
      1309408.55      6845855.09      1310335.17      6844067.59
      1310155.00      6842287.99
#Sta/Elev= 30
  2986.6 2404.95  3033.5 2404.48  3478.9 2397.98  3591.6 2397.86  3619.8 2396.28
  3746.9 2395.14  3774.7 2396.00  3813.2 2394.49  3824.3 2394.70  4413.8 2390.34
  4444.3 2391.37  4488.0 2389.90  4745.7 2388.66  4793.6 2389.66  5016.1 2387.43
  5016.6 2386.93  5023.2 2387.43  5200.6 2389.98  5954.4 2392.10  5994.7 2393.61
  6042.0 2392.69  6235.9 2395.04  6366.5 2394.88  6406.7 2396.40  6441.6 2395.24
  6527.4 2397.55  6641.4 2397.04  6708.3 2399.10  6741.3 2397.60  6788.7 2398.48
#Mann=10,-1,0
  2986.6    0.07       0  3033.5   0.045       0  3478.9    0.07       0
  3813.2   0.045       0  3824.3    0.07       0  4444.3   0.045       0
  4745.7    0.07       0  4793.6   0.045       0  5016.1   0.045       0
  5023.2   0.045       0
Bank Sta=5016.1,5023.2
Exp/Cntr=0.3,0.1

Type RM Length L Ch R = 1,1047,498,498,498
BEGIN DESCRIPTION:
Cottonwood Creek Trib026 2.0
END DESCRIPTION:
XS GIS Cut Line= 3
      1310354.99      6845888.04      1310738.40      6844321.17
      1310355.00      6842337.99
#Sta/Elev= 30
  3386.9 2402.78  4105.7 2392.62  4367.0 2390.31  4406.2 2391.23  4467.1 2389.77
  4524.2 2389.37  5030.2 2386.73  5030.7 2386.23  5037.3 2386.73  5135.6 2388.31
  5227.3 2387.93  5253.9 2389.23  5278.2 2387.94  5376.9 2388.52  5631.0 2388.78
  5673.4 2390.12  5706.0 2388.93  5909.7 2389.75  5942.6 2391.20  5981.0 2389.96
  6174.5 2391.11  6206.7 2392.55  6245.8 2391.22  6388.4 2391.96  6449.5 2393.55
  6480.1 2392.63  6833.5 2396.24  6937.1 2395.94  6969.0 2397.57  7019.9 2396.60
#Mann=9,-1,0
  3386.9   0.045       0  4105.7    0.07       0  4367.0   0.045       0
  4467.1    0.07       0  4524.2   0.045       0  5030.2   0.045       0
  5037.3   0.045       0  5376.9    0.07       0  5631.0   0.045       0
Bank Sta=5030.2,5037.3
Exp/Cntr=0.3,0.1

Type RM Length L Ch R = 1,549,0,0,0
BEGIN DESCRIPTION:
Cottonwood Creek Trib026 1.0
END DESCRIPTION:
XS GIS Cut Line= 3
      1310354.98      6846038.04      1311188.43      6844471.11
      1310605.01      6842688.03
#Sta/Elev= 30
  3225.2 2404.36  3359.6 2402.33  3387.2 2403.26  3507.7 2400.30  3535.4 2401.32
  3565.0 2399.34  3655.7 2399.61  3705.5 2397.34  3771.4 2397.87  3831.7 2395.56
  4045.8 2394.40  4067.7 2392.76  4165.4 2392.88  4243.8 2390.85  4329.8 2390.84
  4504.3 2389.10  4527.3 2389.24  4995.3 2385.89  4995.8 2385.39  5002.6 2385.89
  5193.7 2387.23  5195.8 2387.25  5288.5 2388.53  5320.3 2387.22  5607.1 2387.78
  5639.0 2389.24  5736.8 2388.41  5880.6 2388.64  5907.6 2388.81  6876.1 2393.01
#Mann=13,-1,0
  3225.2   0.045       0  4243.8    0.07       0  4329.8   0.045       0
  4504.3    0.07       0  4527.3   0.045       0  4995.3   0.045       0
  5002.6   0.045       0  5193.7    0.07       0  5195.8   0.045       0
  5320.3    0.07       0  5736.8   0.045       0  5880.6    0.07       0
  5907.6   0.045       0
Bank Sta=4995.3,5002.6
Exp/Cntr=0.3,0.1

Chan Stop Cuts=-1