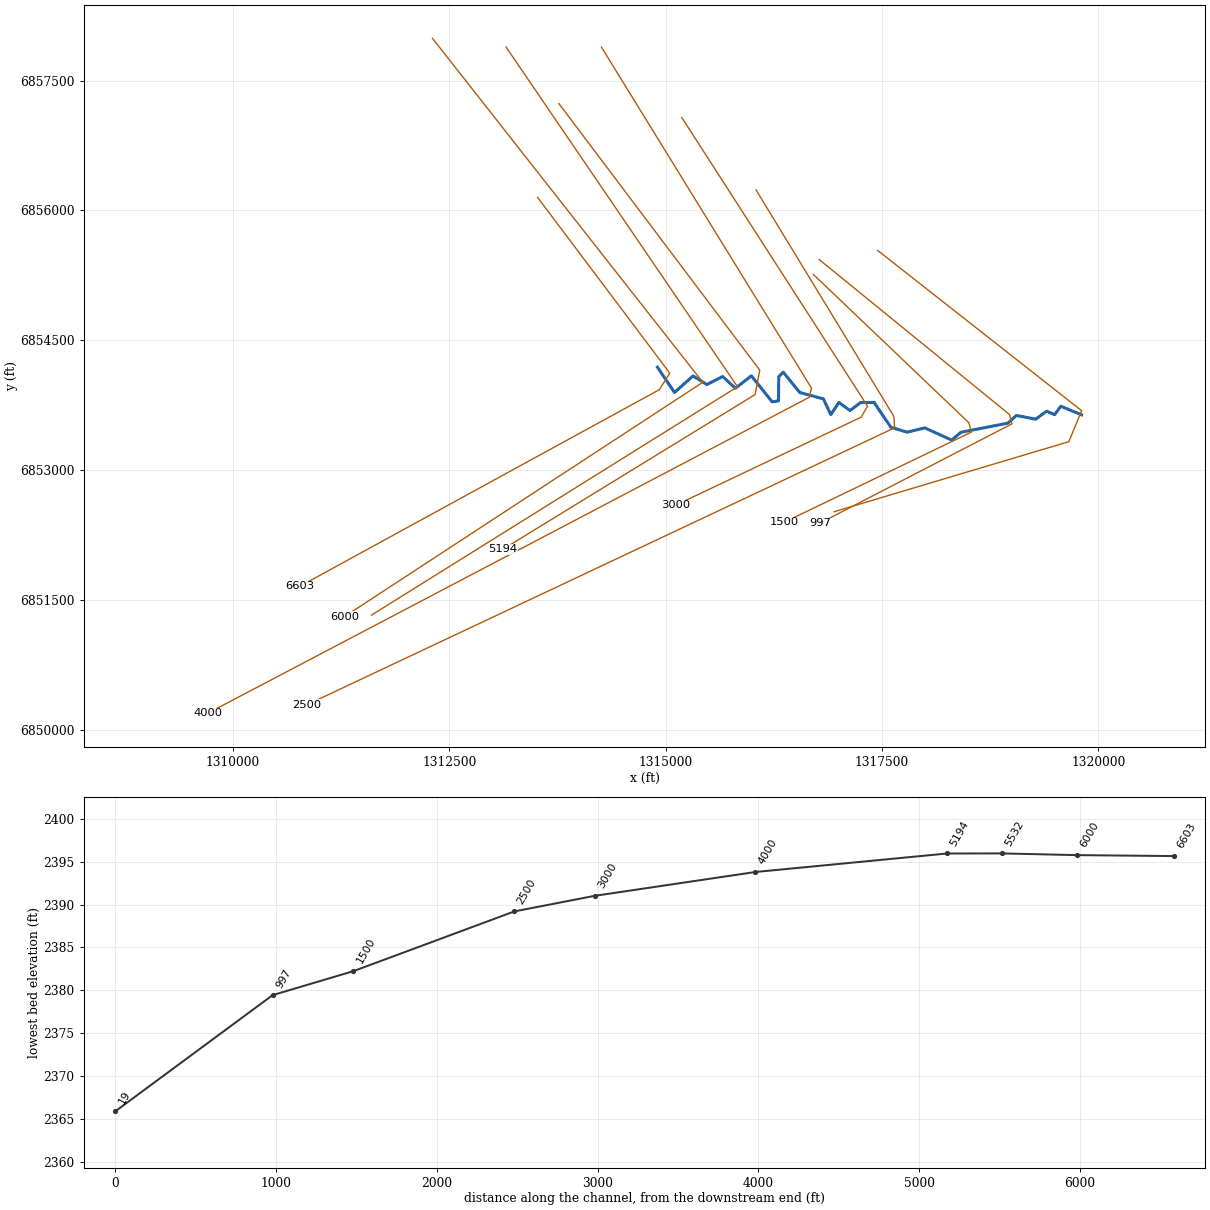
--- Cottonwood Creek Trib029.prj (project) ---

Proj Title=Cottonwood Creek Trib029 Base Level Engineering
Current Plan=p01
Default Exp/Contr=0.3,0.1
English Units
Geom File=g01
Flow File=f01
Plan File=p01
BEGIN DESCRIPTION:
Cottonwood Creek Trib029
END DESCRIPTION:

--- Cottonwood Creek Trib029.p01 (plan) ---

Plan Title=Multiple Run
Short Identifier=Multiple
Geom File=g01
Flow File=f01
Subcritical Flow
K Sum by GR= 0
Std Step Tol= 0.01
Critical Tol= 0.01
Num of Std Step Trials= 20
Max Error Tol= 0.3
Flow Tol Ratio= 0.001
Split Flow NTrial= 30
Split Flow Tol= 0.02
Split Flow Ratio= 0.02
Log Output Level= 0
Friction Slope Method= 1
Unsteady Friction Slope Method= 2
Unsteady Bridges Friction Slope Method= 1
Parabolic Critical Depth
Global Vel Dist=  1 , 1 , 1
Global Log Level= 0
CheckData=True
Encroach Param= -1, 0, 0, 0
BEGIN DESCRIPTION:
Multiple Run
END DESCRIPTION:

--- Cottonwood Creek Trib029.f01 (steady flow) ---

Flow Title=Multiple
Number of Profiles=7
Profile Names=10-year,25-year,50-year,1pct_min,100-year,1pct_plu,500-year
River Rch & RM= Cottonwood Creek,Reach-1,6603
     211     290     354     215     429     856     637
River Rch & RM= Cottonwood Creek,Reach-1,19
    1042    1527    1944    1222    2438    4864    3893
Boundary for River Rch & Prof#=Cottonwood Creek,Reach-1,1
Up Type=0
Dn Type=3
Dn Slope=0.005
Boundary for River Rch & Prof#=Cottonwood Creek,Reach-1,2
Up Type=0
Dn Type=3
Dn Slope=0.005
Boundary for River Rch & Prof#=Cottonwood Creek,Reach-1,3
Up Type=0
Dn Type=3
Dn Slope=0.005
Boundary for River Rch & Prof#=Cottonwood Creek,Reach-1,4
Up Type=0
Dn Type=3
Dn Slope=0.005
Boundary for River Rch & Prof#=Cottonwood Creek,Reach-1,5
Up Type=0
Dn Type=3
Dn Slope=0.005
Boundary for River Rch & Prof#=Cottonwood Creek,Reach-1,6
Up Type=0
Dn Type=3
Dn Slope=0.005
Boundary for River Rch & Prof#=Cottonwood Creek,Reach-1,7
Up Type=0
Dn Type=3
Dn Slope=0.005

--- Cottonwood Creek Trib029.g01 (geometry) ---

Geom Title=Existing Conditions

River Reach=Cottonwood Creek,Reach-1
Reach XY= 30
      1314905.00      6854188.00      1315101.67      6853895.59
      1315315.64      6854087.45      1315475.13      6853987.60
      1315658.41      6854080.23      1315805.00      6853945.07
      1315989.64      6854088.11      1316230.17      6853787.40
      1316303.50      6853799.43      1316306.05      6854077.91
      1316358.13      6854130.50      1316548.66      6853896.02
      1316822.22      6853821.76      1316906.84      6853640.82
      1317001.38      6853780.52      1317130.00      6853687.42
      1317251.60      6853780.17      1317408.41      6853780.18
      1317602.29      6853493.40      1317789.94      6853437.29
      1317994.45      6853486.90      1318305.08      6853345.30
      1318410.85      6853435.92      1318953.50      6853541.64
      1319051.59      6853630.19      1319275.18      6853587.57
      1319401.62      6853680.16      1319492.96      6853639.24
      1319565.34      6853737.11      1319805.00      6853638.00

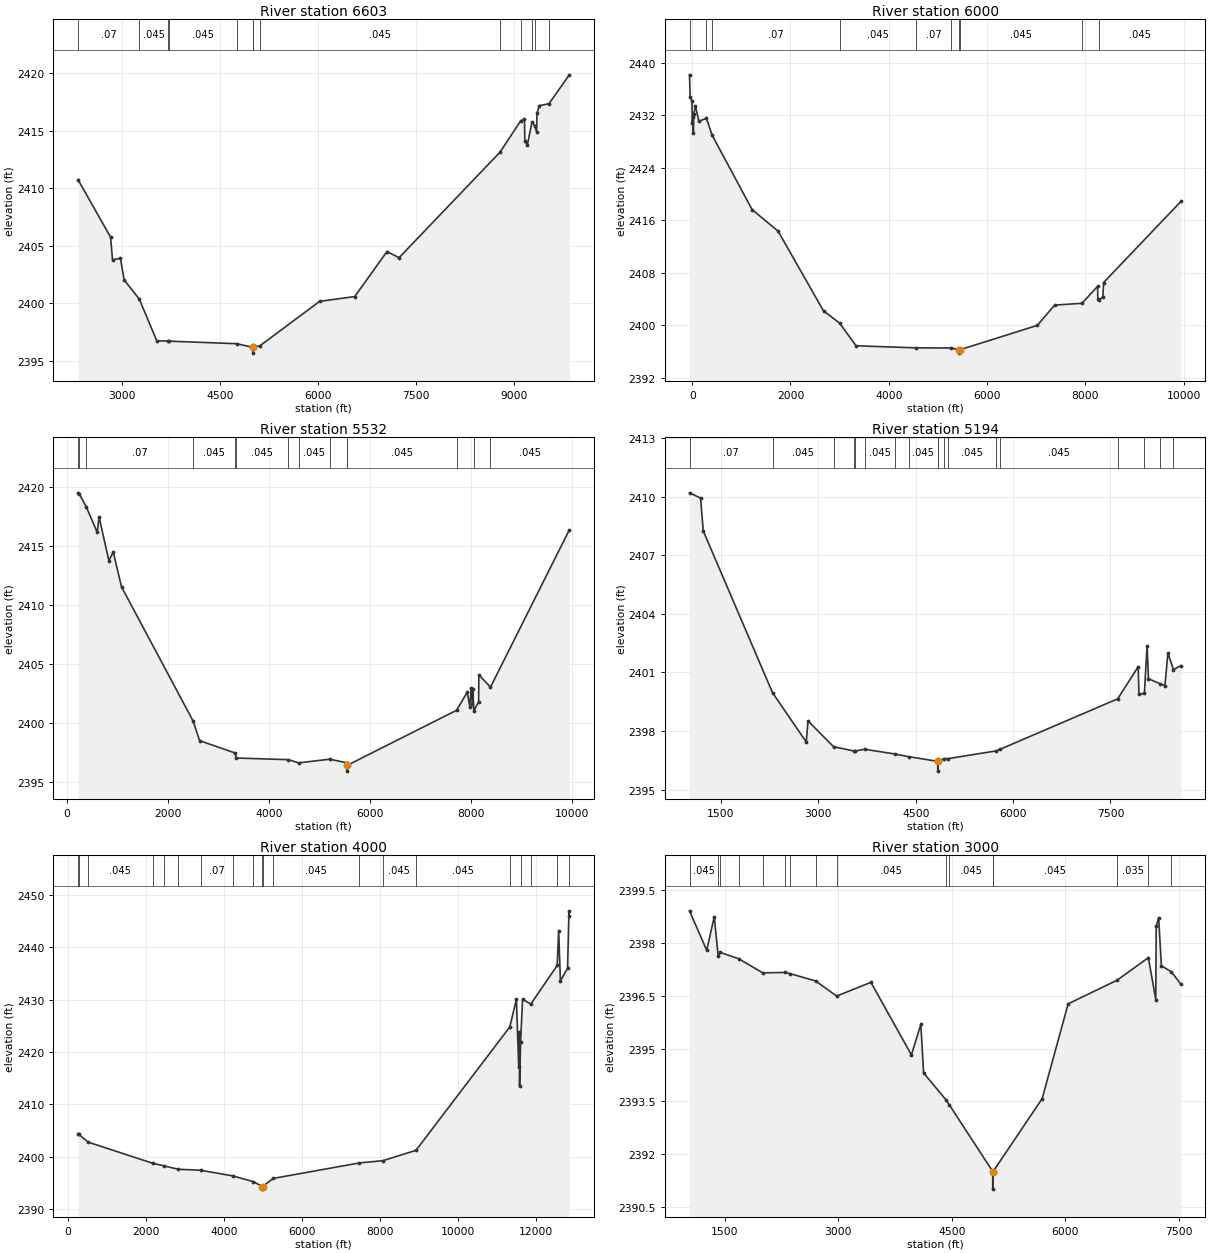
Type RM Length L Ch R = 1,6603,603,603,603
BEGIN DESCRIPTION:
Cottonwood Creek Trib029 13.0
END DESCRIPTION:
XS GIS Cut Line= 4
      1313519.62      6856150.22      1315047.38      6854118.99
      1314925.85      6853928.02      1310768.95      6851654.31
#Sta/Elev= 30
  2332.3 2410.74  2830.7 2405.73  2859.8 2403.76  2980.6 2403.91  3036.9 2402.02
  3267.8 2400.36  3536.7 2396.72  3712.8 2396.70  3728.3 2396.69  4758.4 2396.47
  5003.4 2396.15  5003.7 2395.65  5007.6 2396.15  5115.3 2396.30  6023.2 2400.15
  6560.2 2400.57  7052.4 2404.48  7237.4 2403.95  8782.2 2413.14  9097.8 2415.87
  9153.4 2415.97  9159.1 2414.06  9197.0 2413.76  9268.8 2415.76  9312.9 2415.39
  9338.3 2414.90  9344.0 2416.52  9382.0 2417.17  9527.9 2417.34  9838.4 2419.85
#Mann=13,-1,0
  2332.3    0.07       0  3267.8   0.045       0  3712.8    0.07       0
  3728.3   0.045       0  4758.4    0.07       0  5003.4    0.07       0
  5007.6    0.07       0  5115.3   0.045       0  8782.2   0.035       0
  9097.8    0.07       0  9268.8   0.035       0  9312.9    0.07       0
  9527.9   0.045       0
Bank Sta=5003.4,5007.6
Exp/Cntr=0.3,0.1

Type RM Length L Ch R = 1,6000,468,468,468
BEGIN DESCRIPTION:
Cottonwood Creek Trib029 12.0
END DESCRIPTION:
XS GIS Cut Line= 3
      1312304.97      6857988.04      1315428.51      6854013.81
      1311289.35      6851306.92
#Sta/Elev= 30
   -54.8 2438.13   -41.2 2434.75    -4.2 2434.13     2.2 2430.75    16.6 2431.68
    23.0 2429.30    31.1 2432.15    66.3 2433.38   136.9 2431.06   288.0 2431.52
   407.9 2428.91  1219.6 2417.60  1747.3 2414.34  2672.8 2402.19  2998.2 2400.35
  3335.2 2396.88  4564.6 2396.56  5275.1 2396.54  5438.0 2396.26  5438.3 2395.76
  5442.3 2396.26  7023.5 2399.98  7376.3 2403.07  7933.5 2403.35  8251.0 2405.92
  8256.9 2403.93  8286.3 2403.87  8359.5 2404.36  8373.7 2406.51  9945.7 2418.85
#Mann=10,-1,0
   -54.8    0.07       0   288.0   0.035       0   407.9    0.07       0
  2998.2   0.045       0  4564.6    0.07       0  5275.1   0.045       0
  5438.0    0.07       0  5442.3   0.045       0  7933.5   0.035       0
  8286.3   0.045       0
Bank Sta=5438,5442.3
Exp/Cntr=0.3,0.1

Type RM Length L Ch R = 1,5532,338,338,338
BEGIN DESCRIPTION:
Cottonwood Creek Trib029 11.0
END DESCRIPTION:
XS GIS Cut Line= 3
      1313155.01      6857887.98      1315829.87      6853961.92
      1311601.16      6851323.83
#Sta/Elev= 30
   218.0 2419.53   244.5 2419.44   383.5 2418.33   599.5 2416.18   635.4 2417.48
   829.9 2413.79   916.6 2414.51  1081.3 2411.56  2496.9 2400.22  2628.3 2398.54
  3328.1 2397.50  3356.9 2397.07  4383.9 2396.93  4593.2 2396.66  5205.0 2396.97
  5541.4 2396.67  5552.9 2396.46  5553.2 2395.96  5557.2 2396.46  7718.0 2401.11
  7929.9 2402.64  7979.9 2401.42  8008.9 2403.03  8030.1 2401.62  8045.5 2402.90
  8059.7 2401.07  8155.2 2401.82  8161.1 2404.12  8390.8 2403.07  9952.8 2416.39
#Mann=15,-1,0
   218.0   0.045       0   244.5   0.035       0   383.5    0.07       0
  2496.9   0.045       0  3328.1    0.07       0  3356.9   0.045       0
  4383.9    0.07       0  4593.2   0.045       0  5205.0    0.07       0
  5541.4   0.045       0  5552.9   0.045       0  5557.2   0.045       0
  7718.0   0.035       0  8059.7    0.07       0  8390.8   0.045       0
Bank Sta=5552.9,5557.2
Exp/Cntr=0.3,0.1

Type RM Length L Ch R = 1,5194,1194,1194,1194
BEGIN DESCRIPTION:
Cottonwood Creek Trib029 10.0
END DESCRIPTION:
XS GIS Cut Line= 4
      1313764.84      6857235.29      1316086.87      6854153.71
      1316032.62      6853871.60      1313115.19      6852082.10
#Sta/Elev= 30
  1016.1 2410.19  1186.3 2409.92  1227.9 2408.24  2295.1 2399.96  2814.4 2397.44
  2841.5 2398.52  3235.2 2397.20  3550.1 2396.98  3559.8 2396.97  3712.6 2397.07
  4174.9 2396.83  4389.9 2396.69  4840.1 2396.45  4840.4 2395.95  4844.4 2396.45
  4938.4 2396.59  4999.3 2396.59  5730.5 2396.98  5794.4 2397.06  7611.5 2399.65
  7927.1 2401.29  7939.4 2399.88  8022.7 2399.93  8064.4 2402.37  8085.7 2400.68
  8257.0 2400.43  8339.1 2400.32  8385.2 2402.00  8470.3 2401.14  8584.4 2401.35
#Mann=18,-1,0
  1016.1    0.07       0  2295.1   0.045       0  3235.2    0.07       0
  3550.1   0.045       0  3559.8    0.07       0  3712.6   0.045       0
  4174.9    0.07       0  4389.9   0.045       0  4840.1   0.045       0
  4844.4   0.045       0  4938.4    0.07       0  4999.3   0.045       0
  5730.5    0.07       0  5794.4   0.045       0  7611.5   0.035       0
  8022.7   0.045       0  8257.0    0.07       0  8470.3   0.045       0
Bank Sta=4840.1,4844.4
Exp/Cntr=0.3,0.1

Type RM Length L Ch R = 1,4000,1000,1000,1000
BEGIN DESCRIPTION:
Cottonwood Creek Trib029 8.0
END DESCRIPTION:
XS GIS Cut Line= 4
      1314257.47      6857886.32      1316684.76      6853946.16
      1316659.39      6853840.78      1309705.04      6850188.02
#Sta/Elev= 30
   263.8 2404.42   287.0 2404.24   527.4 2402.77  2173.5 2398.75  2458.6 2398.25
  2832.6 2397.59  3408.7 2397.40  4240.8 2396.30  4756.6 2395.22  4990.3 2394.29
  4990.6 2393.79  4994.6 2394.29  5268.2 2395.84  7477.3 2398.80  8076.8 2399.23
  8924.5 2401.20 11329.5 2424.80 11499.9 2430.09 11558.1 2417.13 11574.5 2423.81
 11580.2 2413.54 11606.9 2421.98 11657.1 2430.11 11867.6 2429.17 12544.2 2436.56
 12582.6 2443.22 12626.7 2433.61 12810.2 2436.01 12845.8 2447.01 12855.3 2446.02
#Mann=20,-1,0
   263.8    0.07       0   287.0    0.07       0   527.4   0.045       0
  2173.5   0.045       0  2458.6    0.07       0  2832.6   0.045       0
  3408.7    0.07       0  4240.8   0.045       0  4756.6    0.07       0
  4990.3    0.07       0  4994.6    0.07       0  5268.2   0.045       0
  7477.3   0.035       0  8076.8   0.045       0  8924.5   0.045       0
 11329.5    0.07       0 11606.9   0.094       0 11867.6   0.035       0
 12544.2   0.035       0 12845.8    0.07       0
Bank Sta=4990.3,4994.6
Exp/Cntr=0.3,0.1

Type RM Length L Ch R = 1,3000,500,500,500
BEGIN DESCRIPTION:
Cottonwood Creek Trib029 6.0
END DESCRIPTION:
XS GIS Cut Line= 4
      1315186.26      6857072.55      1317332.36      6853737.85
      1317258.75      6853611.18      1315110.27      6852591.20
#Sta/Elev= 30
  1034.4 2398.91  1261.4 2397.79  1361.1 2398.74  1413.2 2397.63  1440.0 2397.73
  1682.8 2397.55  2002.2 2397.15  2296.3 2397.16  2358.2 2397.13  2699.4 2396.92
  2978.4 2396.49  3430.5 2396.88  3966.0 2394.82  4090.1 2395.69  4126.5 2394.31
  4423.8 2393.54  4467.4 2393.40  5040.1 2391.51  5040.4 2391.01  5044.7 2391.51
  5693.1 2393.58  6036.2 2396.27  6682.3 2396.94  7095.6 2397.58  7193.6 2396.39
  7199.1 2398.47  7231.8 2398.72  7267.3 2397.35  7398.3 2397.18  7524.8 2396.83
#Mann=16,-1,0
  1034.4   0.045       0  1413.2    0.07       0  1440.0   0.045       0
  1682.8    0.07       0  2002.2   0.045       0  2296.3    0.07       0
  2358.2   0.045       0  2699.4    0.07       0  2978.4   0.045       0
  4423.8    0.07       0  4467.4   0.045       0  5040.1   0.045       0
  5044.7   0.045       0  6682.3   0.035       0  7095.6    0.07       0
  7398.3   0.045       0
Bank Sta=5040.1,5044.7
Exp/Cntr=0.3,0.1

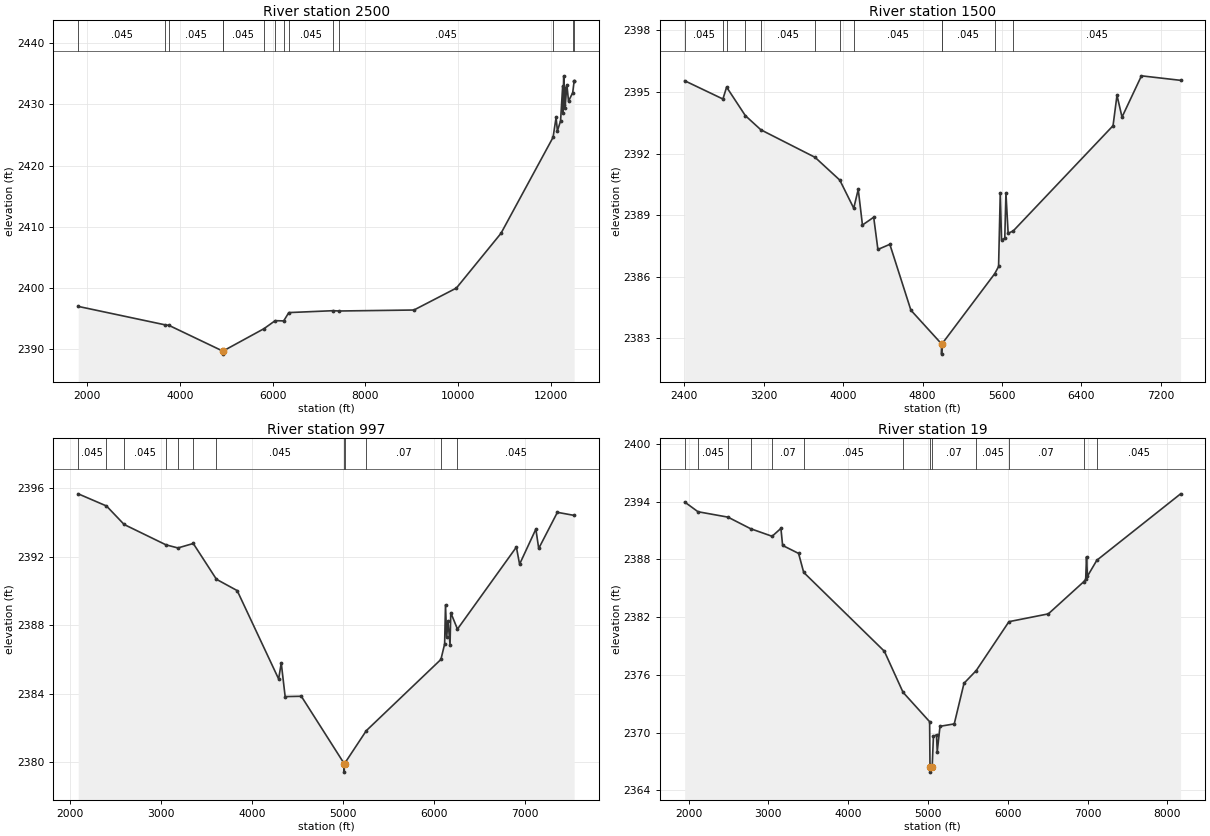
Type RM Length L Ch R = 1,2500,1000,1000,1000
BEGIN DESCRIPTION:
Cottonwood Creek Trib029 5.0
END DESCRIPTION:
XS GIS Cut Line= 4
      1316043.46      6856237.06      1317635.58      6853621.02
      1317645.34      6853487.81      1310855.00      6850288.00
#Sta/Elev= 30
  1804.0 2396.99  3683.1 2393.97  3762.6 2393.89  4923.5 2389.69  4923.8 2389.19
  4928.1 2389.69  5810.7 2393.34  6054.9 2394.66  6238.5 2394.62  6348.4 2395.98
  7305.5 2396.29  7437.2 2396.24  9049.1 2396.40  9965.3 2399.99 10927.1 2408.93
 12051.6 2424.63 12116.7 2427.87 12145.1 2425.67 12213.4 2427.31 12259.0 2433.02
 12264.5 2428.65 12281.8 2434.68 12287.3 2429.86 12304.5 2432.73 12310.1 2429.45
 12350.1 2433.21 12384.9 2430.54 12475.3 2431.92 12506.1 2433.84 12506.5 2433.84
#Mann=14,-1,0
  1804.0   0.045       0  3683.1    0.07       0  3762.6   0.045       0
  4923.5   0.045       0  4928.1   0.045       0  5810.7   0.035       0
  6054.9   0.045       0  6238.5   0.035       0  6348.4   0.045       0
  7305.5    0.07       0  7437.2   0.045       0 12051.6    0.07       0
 12475.3   0.035       0 12506.1    0.07       0
Bank Sta=4923.5,4928.1
Exp/Cntr=0.3,0.1

Type RM Length L Ch R = 1,1500,503,503,503
BEGIN DESCRIPTION:
Cottonwood Creek Trib029 3.0
END DESCRIPTION:
XS GIS Cut Line= 4
      1316705.37      6855260.48      1318503.97      6853545.40
      1318531.81      6853437.79      1316369.52      6852396.16
#Sta/Elev= 30
  2403.6 2395.55  2788.9 2394.66  2826.0 2395.24  3014.8 2393.85  3171.2 2393.16
  3716.8 2391.82  3966.2 2390.71  4106.8 2389.34  4152.2 2390.26  4194.6 2388.52
  4307.9 2388.90  4350.3 2387.33  4470.5 2387.58  4682.8 2384.37  4991.4 2382.73
  4991.7 2382.23  4996.1 2382.73  5527.4 2386.15  5566.1 2386.50  5583.1 2390.09
  5595.8 2387.80  5628.4 2387.87  5640.2 2390.08  5662.4 2388.12  5713.2 2388.23
  6719.3 2393.36  6759.0 2394.84  6809.8 2393.78  7005.5 2395.79  7400.1 2395.57
#Mann=12,-1,0
  2403.6   0.045       0  2788.9    0.07       0  2826.0   0.045       0
  3014.8    0.07       0  3171.2   0.045       0  3716.8   0.035       0
  3966.2   0.063       0  4106.8   0.045       0  4991.4   0.045       0
  4996.1   0.045       0  5527.4   0.035       0  5713.2   0.045       0
Bank Sta=4991.4,4996.1
Exp/Cntr=0.3,0.1

Type RM Length L Ch R = 1,997,978,978,978
BEGIN DESCRIPTION:
Cottonwood Creek Trib029 2.0
END DESCRIPTION:
XS GIS Cut Line= 4
      1316772.85      6855432.66      1318972.72      6853640.89
      1319000.56      6853533.28      1316781.46      6852385.79
#Sta/Elev= 30
  2092.6 2395.68  2403.2 2394.97  2597.0 2393.89  3057.0 2392.70  3187.8 2392.52
  3356.2 2392.78  3610.8 2390.69  3838.4 2390.03  4293.7 2384.87  4322.5 2385.80
  4365.3 2383.84  4542.9 2383.86  5013.1 2379.93  5013.4 2379.43  5017.8 2379.93
  5256.4 2381.85  6076.0 2386.01  6116.7 2386.91  6126.3 2389.20  6139.2 2387.31
  6154.0 2388.23  6176.2 2386.88  6184.3 2388.74  6257.6 2387.78  6904.8 2392.57
  6939.9 2391.57  7118.7 2393.62  7150.1 2392.49  7355.1 2394.60  7539.2 2394.42
#Mann=12,-1,0
  2092.6   0.045       0  2403.2    0.07       0  2597.0   0.045       0
  3057.0   0.063       0  3187.8   0.035       0  3356.2    0.07       0
  3610.8   0.045       0  5013.1   0.045       0  5017.8   0.045       0
  5256.4    0.07       0  6076.0   0.035       0  6257.6   0.045       0
Bank Sta=5013.1,5017.8
Exp/Cntr=0.3,0.1

Type RM Length L Ch R = 1,19,0,0,0
BEGIN DESCRIPTION:
Cottonwood Creek Trib029 1.0
END DESCRIPTION:
XS GIS Cut Line= 4
      1317449.94      6855536.82      1319805.82      6853685.78
      1319658.25      6853327.70      1316944.92      6852517.81
#Sta/Elev= 30
  1951.7 2393.95  2118.5 2392.94  2493.9 2392.38  2777.1 2391.18  3047.3 2390.39
  3157.8 2391.21  3179.0 2389.44  3379.2 2388.61  3443.1 2386.64  4453.8 2378.45
  4688.4 2374.18  5021.1 2371.13  5026.0 2366.39  5026.5 2365.89  5053.1 2366.39
  5068.9 2369.60  5107.6 2369.77  5116.8 2368.02  5151.5 2370.65  5329.9 2370.90
  5452.2 2375.12  5605.3 2376.44  6015.2 2381.52  6508.9 2382.33  6950.2 2385.65
  6976.9 2385.91  6987.4 2388.26  6998.9 2386.24  7116.8 2387.90  8166.7 2394.80
#Mann=13,-1,0
  1951.7   0.035       0  2118.5   0.045       0  2493.9    0.07       0
  2777.1   0.045       0  3047.3    0.07       0  3443.1   0.045       0
  4688.4    0.07       0  5026.0    0.07       0  5053.1    0.07       0
  5605.3   0.045       0  6015.2    0.07       0  6950.2   0.035       0
  7116.8   0.045       0
Bank Sta=5026,5053.1
Exp/Cntr=0.3,0.1

Chan Stop Cuts=-1