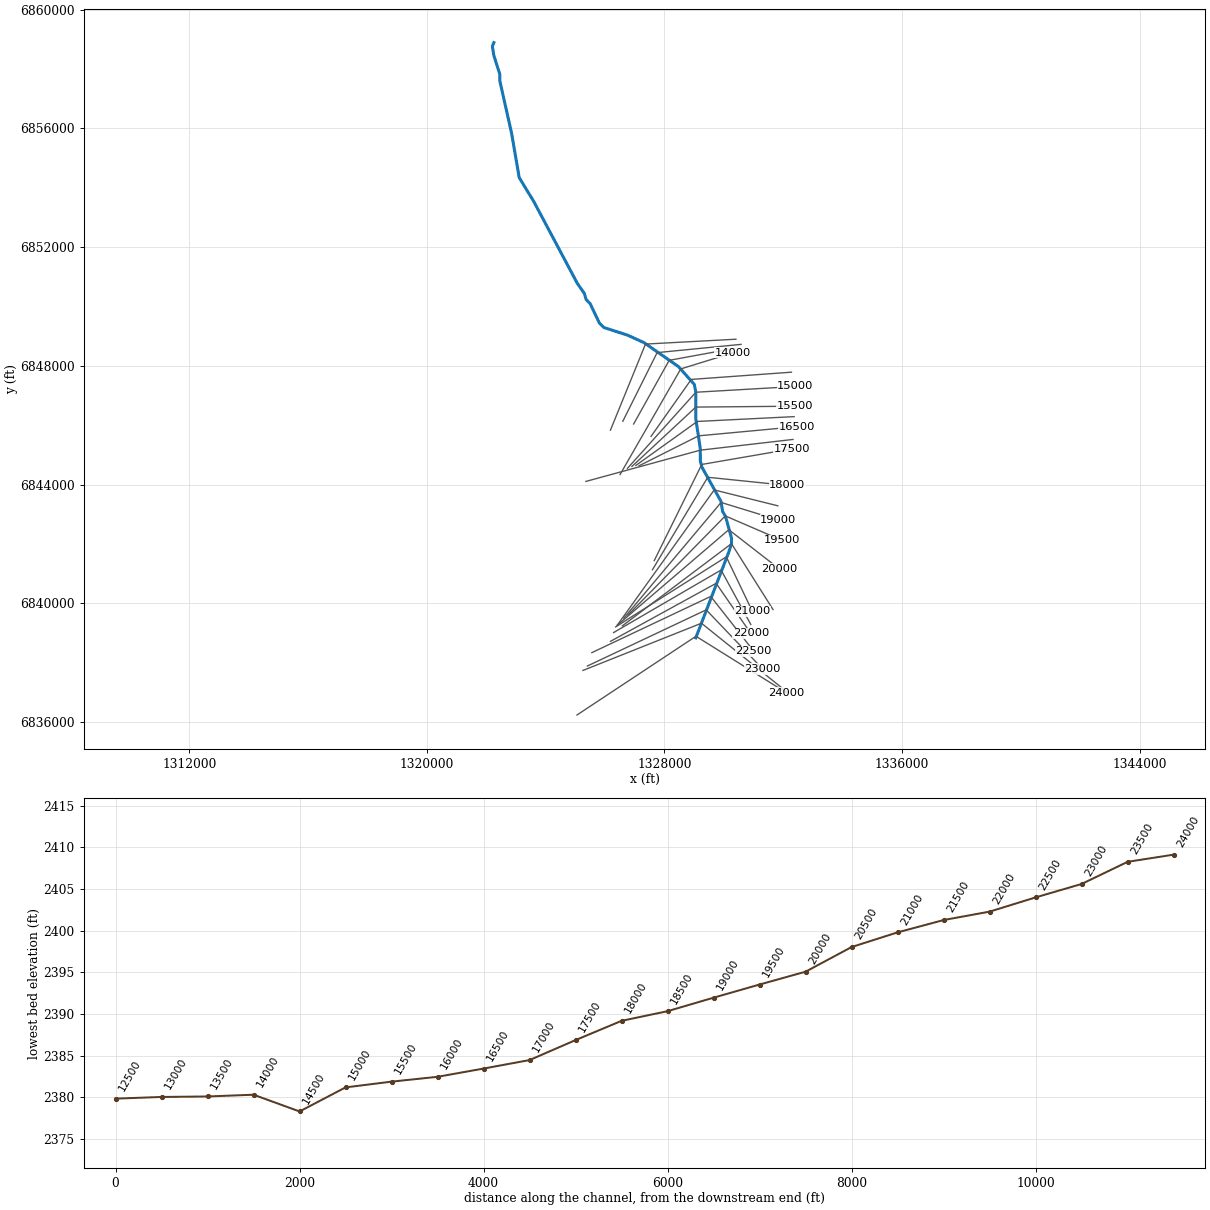
--- Cottonwood Creek Trib030.prj (project) ---

Proj Title=Cottonwood Creek Trib030 Base Level Engineering
Current Plan=p01
Default Exp/Contr=0.3,0.1
English Units
Geom File=g01
Flow File=f01
Plan File=p01
BEGIN DESCRIPTION:
Cottonwood Creek Trib030
END DESCRIPTION:

--- Cottonwood Creek Trib030.p01 (plan) ---

Plan Title=Multiple Run
Short Identifier=Multiple
Geom File=g01
Flow File=f01
Subcritical Flow
K Sum by GR= 0
Std Step Tol= 0.01
Critical Tol= 0.01
Num of Std Step Trials= 20
Max Error Tol= 0.3
Flow Tol Ratio= 0.001
Split Flow NTrial= 30
Split Flow Tol= 0.02
Split Flow Ratio= 0.02
Log Output Level= 0
Friction Slope Method= 1
Unsteady Friction Slope Method= 2
Unsteady Bridges Friction Slope Method= 1
Parabolic Critical Depth
Global Vel Dist=  1 , 1 , 1
Global Log Level= 0
CheckData=True
Encroach Param= -1, 0, 0, 0
BEGIN DESCRIPTION:
Multiple Run
END DESCRIPTION:

--- Cottonwood Creek Trib030.f01 (steady flow) ---

Flow Title=Multiple
Number of Profiles=7
Profile Names=10-year,25-year,50-year,1pct_min,100-year,1pct_plu,500-year
River Rch & RM= Cottonwood Creek,Reach-1,24000
     201     274     332     200     399     796     583
River Rch & RM= Cottonwood Creek,Reach-1,18000
     266     369     453     275     550    1097     821
River Rch & RM= Cottonwood Creek,Reach-1,17000
     435     616     766     471     940    1876    1440
River Rch & RM= Cottonwood Creek,Reach-1,11500
     497     709     885     547    1091    2177    1684
River Rch & RM= Cottonwood Creek,Reach-1,10500
     508     721     898     553    1103    2201    1691
River Rch & RM= Cottonwood Creek,Reach-1,3500
     557     795     996     616    1230    2454    1905
Boundary for River Rch & Prof#=Cottonwood Creek,Reach-1,1
Up Type=0
Dn Type=3
Dn Slope=0.005
Boundary for River Rch & Prof#=Cottonwood Creek,Reach-1,2
Up Type=0
Dn Type=3
Dn Slope=0.005
Boundary for River Rch & Prof#=Cottonwood Creek,Reach-1,3
Up Type=0
Dn Type=3
Dn Slope=0.005
Boundary for River Rch & Prof#=Cottonwood Creek,Reach-1,4
Up Type=0
Dn Type=3
Dn Slope=0.005
Boundary for River Rch & Prof#=Cottonwood Creek,Reach-1,5
Up Type=0
Dn Type=3
Dn Slope=0.005
Boundary for River Rch & Prof#=Cottonwood Creek,Reach-1,6
Up Type=0
Dn Type=3
Dn Slope=0.005
Boundary for River Rch & Prof#=Cottonwood Creek,Reach-1,7
Up Type=0
Dn Type=3
Dn Slope=0.005

--- Cottonwood Creek Trib030.g01 (geometry) ---

Geom Title=Existing Conditions

River Reach=Cottonwood Creek,Reach-1
Reach XY= 30
      1329055.00      6838838.00      1330151.17      6841689.58
      1330253.78      6841998.50      1330255.43      6842203.18
      1330052.75      6842932.07      1329957.25      6843093.93
      1329901.45      6843436.53      1329260.44      6844585.54
      1329206.89      6844793.78      1329204.48      6845222.78
      1329055.07      6846208.03      1329055.20      6847113.08
      1329003.04      6847376.03      1328468.21      6847974.37
      1327311.16      6848780.12      1326753.42      6849034.17
      1325956.50      6849291.61      1325810.83      6849435.70
      1325499.17      6850090.30      1325360.83      6850235.70
      1325299.46      6850440.42      1325060.85      6850785.71
      1323601.81      6853529.65      1323108.75      6854339.55
      1322853.78      6855827.50      1322456.22      6857598.50
      1322453.78      6857827.50      1322256.22      6858448.50
      1322204.53      6858763.00      1322255.00      6858888.00

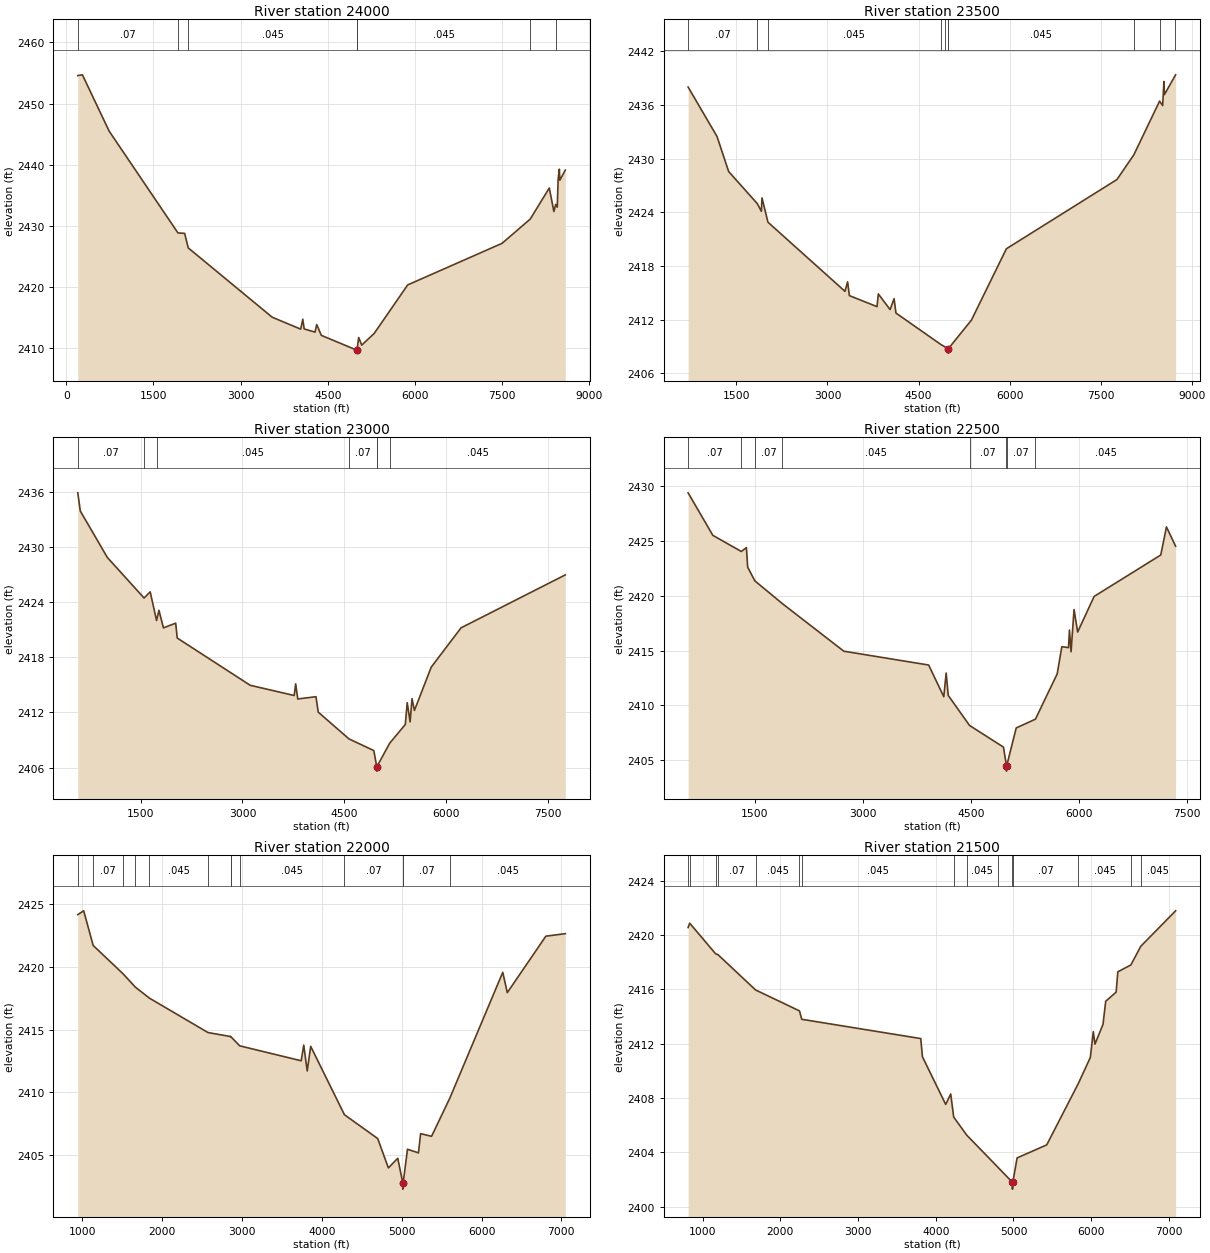
Type RM Length L Ch R = 1,24000,500,500,500
BEGIN DESCRIPTION:
Cottonwood Creek Trib030 48.0
END DESCRIPTION:
XS GIS Cut Line= 3
      1325055.00      6836238.00      1329060.27      6838889.50
      1332104.99      6836988.01
#Sta/Elev= 30
   196.6 2454.58   276.3 2454.70   736.6 2445.48  1921.4 2428.81  2036.4 2428.74
  2098.4 2426.36  3543.8 2415.01  4034.3 2413.06  4070.3 2414.69  4094.2 2413.09
  4280.9 2412.57  4310.1 2413.81  4389.2 2412.04  4997.8 2409.63  4998.1 2409.13
  5001.8 2409.63  5033.1 2411.68  5085.0 2410.44  5300.8 2412.37  5876.4 2420.30
  7501.7 2427.11  7985.9 2431.08  8314.3 2436.17  8393.3 2432.32  8424.4 2433.47
  8451.1 2433.03  8466.5 2437.60  8487.7 2439.25  8495.4 2437.44  8589.7 2439.10
#Mann=7,-1,0
   196.6    0.07       0  1921.4   0.035       0  2098.4   0.045       0
  4997.8   0.045       0  5001.8   0.045       0  7985.9    0.07       0
  8424.4   0.035       0
Bank Sta=4997.8,5001.8
Exp/Cntr=0.3,0.1

Type RM Length L Ch R = 1,23500,500,500,500
BEGIN DESCRIPTION:
Cottonwood Creek Trib030 47.0
END DESCRIPTION:
XS GIS Cut Line= 3
      1325254.96      6837737.98      1329244.56      6839328.88
      1332154.98      6836988.01
#Sta/Elev= 30
   704.9 2438.02  1180.7 2432.50  1372.4 2428.58  1845.1 2424.98  1911.2 2424.13
  1921.5 2425.63  2020.1 2422.91  3288.7 2415.18  3331.8 2416.24  3361.5 2414.70
  3816.2 2413.47  3837.8 2414.89  4031.6 2413.14  4097.4 2414.36  4128.5 2412.75
  4867.5 2409.24  4942.5 2408.94  4987.6 2408.77  4987.9 2408.27  4991.8 2408.77
  5371.3 2411.96  5947.3 2419.94  7767.9 2427.68  8046.4 2430.44  8470.9 2436.45
  8521.4 2435.95  8542.5 2438.64  8550.2 2437.18  8723.1 2439.25  8735.0 2439.39
#Mann=10,-1,0
   704.9    0.07       0  1845.1   0.035       0  2020.1   0.045       0
  4867.5    0.07       0  4942.5   0.045       0  4987.6   0.045       0
  4991.8   0.045       0  8046.4    0.07       0  8470.9   0.035       0
  8723.1    0.07       0
Bank Sta=4987.6,4991.8
Exp/Cntr=0.3,0.1

Type RM Length L Ch R = 1,23000,500,500,500
BEGIN DESCRIPTION:
Cottonwood Creek Trib030 46.0
END DESCRIPTION:
XS GIS Cut Line= 3
      1325405.02      6837888.01      1329405.09      6839778.94
      1331305.00      6837788.00
#Sta/Elev= 30
   575.5 2435.93   612.4 2433.95  1010.4 2428.89  1551.4 2424.47  1641.5 2425.14
  1735.3 2422.02  1770.1 2423.13  1836.4 2421.22  2016.7 2421.73  2039.5 2420.11
  3114.1 2414.96  3761.1 2413.85  3783.2 2415.12  3813.5 2413.47  4081.8 2413.72
  4114.9 2412.04  4567.7 2409.12  4933.5 2407.85  4975.6 2406.11  4975.9 2405.61
  4980.0 2406.11  5166.7 2408.65  5396.7 2410.69  5425.0 2413.07  5467.5 2410.98
  5495.8 2413.51  5531.0 2412.22  5778.5 2416.94  6217.3 2421.22  7752.0 2426.99
#Mann=7,-1,0
   575.5    0.07       0  1551.4   0.035       0  1735.3   0.045       0
  4567.7    0.07       0  4975.6    0.07       0  4980.0    0.07       0
  5166.7   0.045       0
Bank Sta=4975.6,4980
Exp/Cntr=0.3,0.1

Type RM Length L Ch R = 1,22500,500,500,500
BEGIN DESCRIPTION:
Cottonwood Creek Trib030 45.0
END DESCRIPTION:
XS GIS Cut Line= 3
      1325555.03      6838338.01      1329557.14      6840231.18
      1331004.97      6838388.03
#Sta/Elev= 30
   572.7 2429.39   916.4 2425.51  1311.5 2424.04  1382.6 2424.39  1399.8 2422.61
  1499.6 2421.36  1882.2 2419.28  2735.6 2414.94  3913.5 2413.68  4123.7 2410.79
  4156.9 2412.95  4185.2 2410.91  4481.1 2408.17  4952.7 2406.19  4993.9 2404.50
  4994.2 2404.00  4998.3 2404.50  5129.5 2407.94  5396.5 2408.74  5698.9 2412.87
  5763.1 2415.35  5856.0 2415.27  5868.9 2416.87  5891.4 2414.89  5933.0 2418.74
  5983.2 2416.69  6212.1 2419.94  7137.8 2423.72  7216.4 2426.28  7343.8 2424.52
#Mann=8,-1,0
   572.7    0.07       0  1311.5   0.035       0  1499.6    0.07       0
  1882.2   0.045       0  4481.1    0.07       0  4993.9    0.07       0
  4998.3    0.07       0  5396.5   0.045       0
Bank Sta=4993.9,4998.3
Exp/Cntr=0.3,0.1

Type RM Length L Ch R = 1,22000,500,500,500
BEGIN DESCRIPTION:
Cottonwood Creek Trib030 44.0
END DESCRIPTION:
XS GIS Cut Line= 3
      1326182.32      6838718.92      1329738.64      6840672.34
      1330905.03      6838987.96
#Sta/Elev= 30
   942.5 2424.17  1016.5 2424.47  1135.2 2421.71  1508.2 2419.46  1664.9 2418.38
  1840.4 2417.51  2573.1 2414.77  2856.0 2414.45  2856.9 2414.46  2970.7 2413.71
  3740.8 2412.52  3772.6 2413.77  3816.2 2411.71  3859.8 2413.67  4282.4 2408.22
  4699.2 2406.32  4832.8 2403.98  4950.2 2404.75  5013.4 2402.79  5013.7 2402.29
  5018.0 2402.79  5072.4 2405.47  5209.6 2405.18  5236.6 2406.71  5373.8 2406.50
  5601.7 2409.53  6265.7 2419.57  6322.4 2417.95  6805.5 2422.45  7048.8 2422.65
#Mann=13,-1,0
   942.5   0.035       0  1135.2    0.07       0  1508.2   0.045       0
  1664.9    0.07       0  1840.4   0.045       0  2573.1    0.07       0
  2856.0   0.045       0  2856.9    0.07       0  2970.7   0.045       0
  4282.4    0.07       0  5013.4    0.07       0  5018.0    0.07       0
  5601.7   0.045       0
Bank Sta=5013.4,5018
Exp/Cntr=0.3,0.1

Type RM Length L Ch R = 1,21500,500,500,500
BEGIN DESCRIPTION:
Cottonwood Creek Trib030 43.0
END DESCRIPTION:
XS GIS Cut Line= 3
      1326286.56      6839014.10      1329905.46      6841120.53
      1330905.00      6839288.00
#Sta/Elev= 30
   812.7 2420.55   833.1 2420.87  1165.9 2418.62  1197.0 2418.55  1681.2 2415.95
  2245.9 2414.41  2275.5 2413.79  3807.1 2412.37  3828.6 2411.03  4128.1 2407.52
  4192.6 2408.29  4230.8 2406.59  4398.2 2405.26  4800.5 2402.89  4987.0 2401.78
  4987.4 2401.28  4991.7 2401.78  5047.0 2403.58  5428.6 2404.54  5836.8 2409.08
  5989.6 2410.98  6027.6 2412.88  6049.4 2411.96  6152.9 2413.42  6187.5 2415.12
  6321.8 2415.79  6343.7 2417.29  6511.3 2417.79  6639.2 2419.17  7087.4 2421.78
#Mann=15,-1,0
   812.7   0.035       0   833.1    0.07       0  1165.9   0.045       0
  1197.0    0.07       0  1681.2   0.045       0  2245.9    0.07       0
  2275.5   0.045       0  4230.8    0.07       0  4398.2   0.045       0
  4800.5    0.07       0  4987.0    0.07       0  4991.7    0.07       0
  5836.8   0.045       0  6511.3    0.07       0  6639.2   0.045       0
Bank Sta=4987,4991.7
Exp/Cntr=0.3,0.1

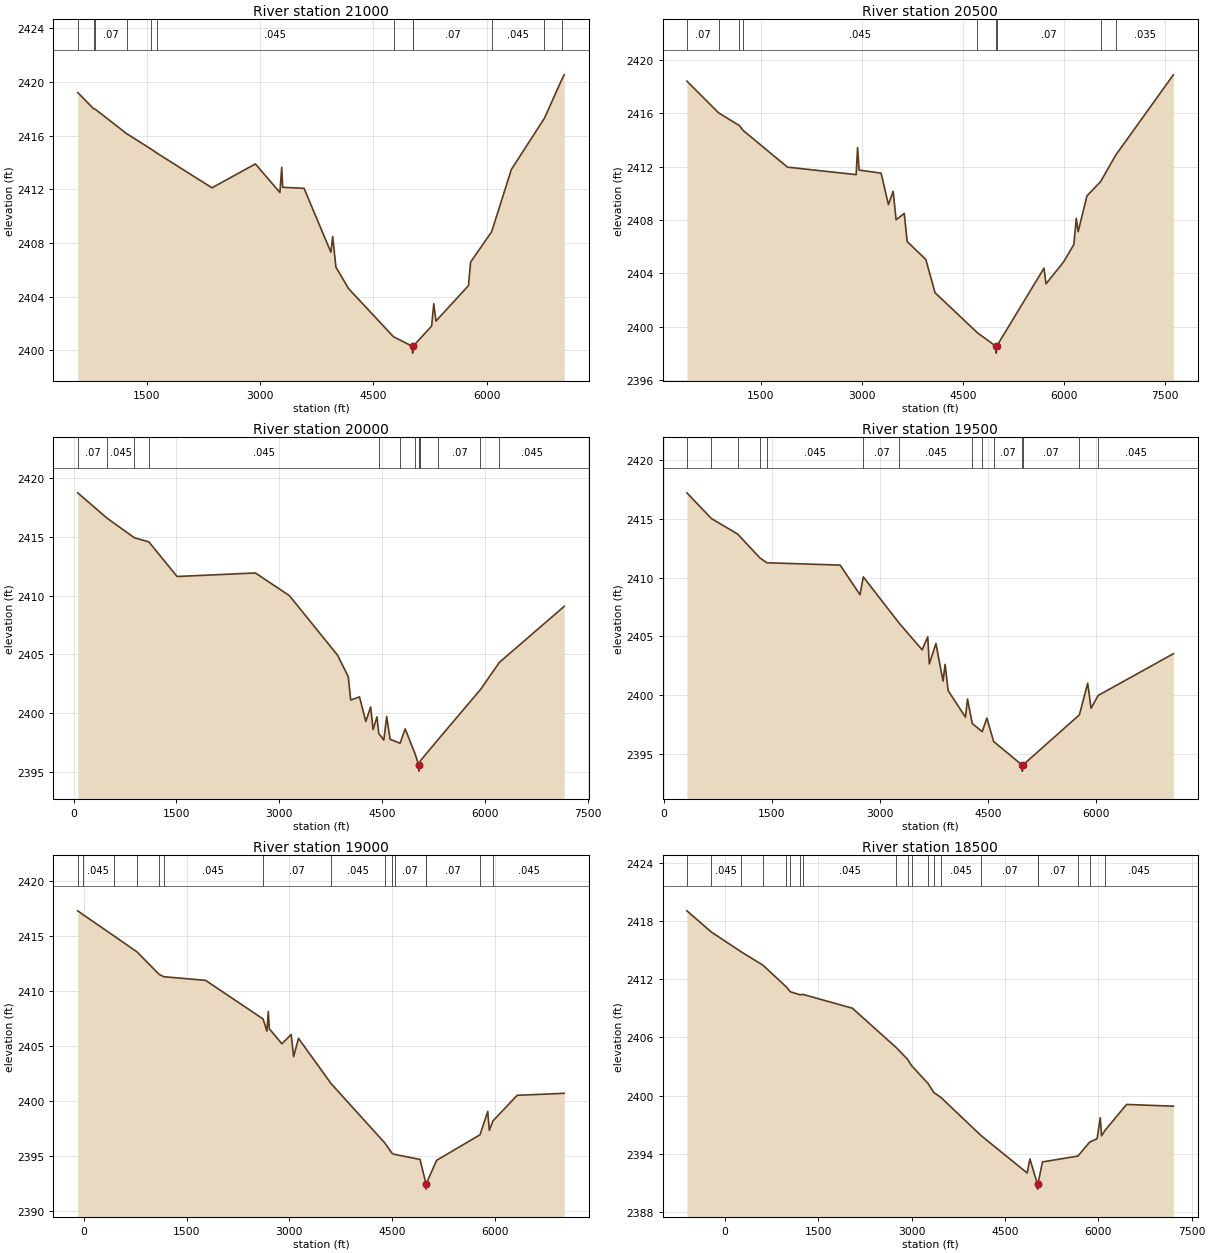
Type RM Length L Ch R = 1,21000,500,500,500
BEGIN DESCRIPTION:
Cottonwood Creek Trib030 42.0
END DESCRIPTION:
XS GIS Cut Line= 3
      1326355.98      6839205.05      1330081.26      6841564.47
      1330955.00      6839738.00
#Sta/Elev= 30
   590.4 2419.22   803.3 2418.00   819.0 2417.99  1236.3 2416.16  1560.0 2415.01
  1639.9 2414.70  2366.4 2412.12  2940.2 2413.90  3264.7 2411.77  3288.1 2413.64
  3301.2 2412.16  3584.0 2412.08  3939.1 2407.32  3962.8 2408.48  4005.5 2406.21
  4172.4 2404.61  4767.1 2401.02  5019.7 2400.30  5020.0 2399.80  5024.4 2400.30
  5271.4 2401.82  5299.6 2403.48  5328.6 2402.19  5758.6 2404.83  5786.8 2406.58
  6065.4 2408.85  6326.3 2413.49  6763.8 2417.31  6993.1 2420.19  7024.7 2420.54
#Mann=12,-1,0
   590.4    0.07       0   803.3   0.045       0   819.0    0.07       0
  1236.3   0.045       0  1560.0    0.07       0  1639.9   0.045       0
  4767.1    0.07       0  5019.7    0.07       0  5024.4    0.07       0
  6065.4   0.045       0  6763.8    0.07       0  6993.1   0.094       0
Bank Sta=5019.7,5024.4
Exp/Cntr=0.3,0.1

Type RM Length L Ch R = 1,20500,500,500,500
BEGIN DESCRIPTION:
Cottonwood Creek Trib030 41.0
END DESCRIPTION:
XS GIS Cut Line= 3
      1326581.66      6839239.77      1330255.00      6842009.30
      1331655.01      6839787.98
#Sta/Elev= 30
   399.6 2418.40   871.8 2416.02  1179.6 2415.07  1234.4 2414.71  1893.9 2411.96
  2914.0 2411.40  2934.8 2413.42  2957.7 2411.74  3284.6 2411.51  3392.8 2409.16
  3463.6 2410.15  3507.3 2408.02  3628.1 2408.50  3671.8 2406.39  3948.7 2405.05
  4085.8 2402.56  4716.0 2399.56  4994.5 2398.54  4994.8 2398.04  4999.3 2398.54
  5704.1 2404.40  5734.4 2403.23  5994.5 2404.86  6147.8 2406.17  6183.6 2408.13
  6211.4 2407.13  6342.1 2409.81  6543.8 2410.87  6771.2 2412.87  7625.7 2418.87
#Mann=9,-1,0
   399.6    0.07       0   871.8   0.045       0  1179.6    0.07       0
  1234.4   0.045       0  4716.0    0.07       0  4994.5    0.07       0
  4999.3    0.07       0  6543.8   0.045       0  6771.2   0.035       0
Bank Sta=4994.5,4999.3
Exp/Cntr=0.3,0.1

Type RM Length L Ch R = 1,20000,500,500,500
BEGIN DESCRIPTION:
Cottonwood Creek Trib030 40.0
END DESCRIPTION:
XS GIS Cut Line= 3
      1326414.96      6839265.20      1330165.16      6842479.35
      1331866.35      6841157.62
#Sta/Elev= 30
    60.9 2418.73   489.8 2416.57   887.4 2414.91  1098.3 2414.56  1509.7 2411.62
  2651.7 2411.92  3147.8 2409.99  3850.2 2404.93  4006.1 2403.10  4041.2 2401.12
  4169.6 2401.39  4261.8 2399.30  4332.1 2400.53  4367.6 2398.62  4424.3 2399.69
  4450.7 2398.28  4524.2 2397.72  4565.9 2399.72  4616.4 2397.78  4761.4 2397.45
  4835.9 2398.67  4977.9 2396.58  5034.8 2395.58  5035.1 2395.08  5039.7 2395.58
  5056.4 2395.95  5319.6 2397.79  5933.1 2402.01  6209.0 2404.32  7154.3 2409.08
#Mann=13,-1,0
    60.9    0.07       0   489.8   0.045       0   887.4    0.07       0
  1098.3   0.045       0  4450.7    0.07       0  4761.4   0.035       0
  4977.9    0.07       0  5034.8    0.07       0  5039.7    0.07       0
  5056.4   0.035       0  5319.6    0.07       0  5933.1   0.035       0
  6209.0   0.045       0
Bank Sta=5034.8,5039.7
Exp/Cntr=0.3,0.1

Type RM Length L Ch R = 1,19500,500,500,500
BEGIN DESCRIPTION:
Cottonwood Creek Trib030 39.0
END DESCRIPTION:
XS GIS Cut Line= 3
      1326770.90      6839603.78      1330047.25      6842943.53
      1331951.63      6842121.81
#Sta/Elev= 30
   321.5 2417.22   661.6 2415.03  1024.5 2413.72  1335.4 2411.68  1432.0 2411.27
  2448.8 2411.07  2724.5 2408.55  2770.1 2410.07  3270.9 2406.11  3587.3 2403.86
  3665.0 2404.97  3686.3 2402.66  3778.2 2404.40  3877.2 2401.20  3905.5 2402.62
  3947.9 2400.39  4188.4 2398.13  4216.7 2399.67  4282.7 2397.59  4420.6 2396.90
  4485.4 2398.05  4579.4 2396.06  4977.8 2394.04  4978.2 2393.54  4982.8 2394.04
  5769.7 2398.33  5885.0 2401.02  5932.0 2398.89  6030.4 2399.98  7074.1 2403.53
#Mann=14,-1,0
   321.5   0.045       0   661.6    0.07       0  1024.5   0.045       0
  1335.4    0.07       0  1432.0   0.045       0  2770.1    0.07       0
  3270.9   0.045       0  4282.7    0.07       0  4420.6   0.045       0
  4579.4    0.07       0  4977.8    0.07       0  4982.8    0.07       0
  5769.7   0.035       0  6030.4   0.045       0
Bank Sta=4977.8,4982.8
Exp/Cntr=0.3,0.1

Type RM Length L Ch R = 1,19000,500,500,500
BEGIN DESCRIPTION:
Cottonwood Creek Trib030 38.0
END DESCRIPTION:
XS GIS Cut Line= 3
      1326632.03      6839499.64      1329905.44      6843397.18
      1331830.86      6842807.15
#Sta/Elev= 30
   -89.8 2417.26   -15.9 2416.93   432.8 2415.01   773.1 2413.54  1100.2 2411.48
  1166.4 2411.27  1777.5 2410.94  2616.4 2407.43  2672.4 2406.32  2693.2 2408.11
  2707.5 2406.54  2892.2 2405.17  3027.5 2406.02  3062.6 2404.00  3133.6 2405.67
  3609.1 2401.56  4398.2 2396.13  4502.7 2395.19  4537.4 2395.12  4908.5 2394.66
  4994.8 2392.46  4995.1 2391.96  4999.8 2392.46  5151.0 2394.58  5784.7 2396.90
  5897.7 2399.02  5919.9 2397.31  5975.0 2398.17  6327.8 2400.49  7013.8 2400.67
#Mann=15,-1,0
   -89.8    0.07       0   -15.9   0.045       0   432.8    0.07       0
   773.1   0.045       0  1100.2    0.07       0  1166.4   0.045       0
  2616.4    0.07       0  3609.1   0.045       0  4398.2    0.07       0
  4502.7   0.045       0  4537.4    0.07       0  4994.8    0.07       0
  4999.8    0.07       0  5784.7   0.035       0  5975.0   0.045       0
Bank Sta=4994.8,4999.8
Exp/Cntr=0.3,0.1

Type RM Length L Ch R = 1,18500,500,500,500
BEGIN DESCRIPTION:
Cottonwood Creek Trib030 37.0
END DESCRIPTION:
XS GIS Cut Line= 3
      1326406.30      6839256.54      1329674.20      6843818.93
      1331814.34      6843284.32
#Sta/Elev= 30
  -612.0 2419.06  -218.6 2416.87   263.0 2414.82   610.2 2413.45   988.3 2411.19
  1048.0 2410.71  1203.6 2410.40  1257.2 2410.43  2046.7 2409.01  2750.4 2404.96
  2933.9 2403.74  2999.3 2403.08  3265.4 2401.23  3356.6 2400.31  3468.5 2399.81
  4120.2 2395.84  4856.4 2392.01  4900.5 2393.45  5022.9 2390.84  5023.3 2390.34
  5028.2 2390.84  5102.9 2393.15  5671.5 2393.75  5862.0 2395.20  5980.0 2395.54
  6031.6 2397.71  6051.5 2395.84  6107.3 2396.40  6454.1 2399.08  7205.9 2398.90
#Mann=20,-1,0
  -612.0    0.07       0  -218.6   0.045       0   263.0    0.07       0
   610.2   0.045       0   988.3    0.07       0  1048.0   0.045       0
  1203.6    0.07       0  1257.2   0.045       0  2750.4    0.07       0
  2933.9   0.045       0  2999.3    0.07       0  3265.4   0.045       0
  3356.6    0.07       0  3468.5   0.045       0  4120.2    0.07       0
  5022.9    0.07       0  5028.2    0.07       0  5671.5   0.045       0
  5862.0   0.035       0  6107.3   0.045       0
Bank Sta=5022.9,5028.2
Exp/Cntr=0.3,0.1

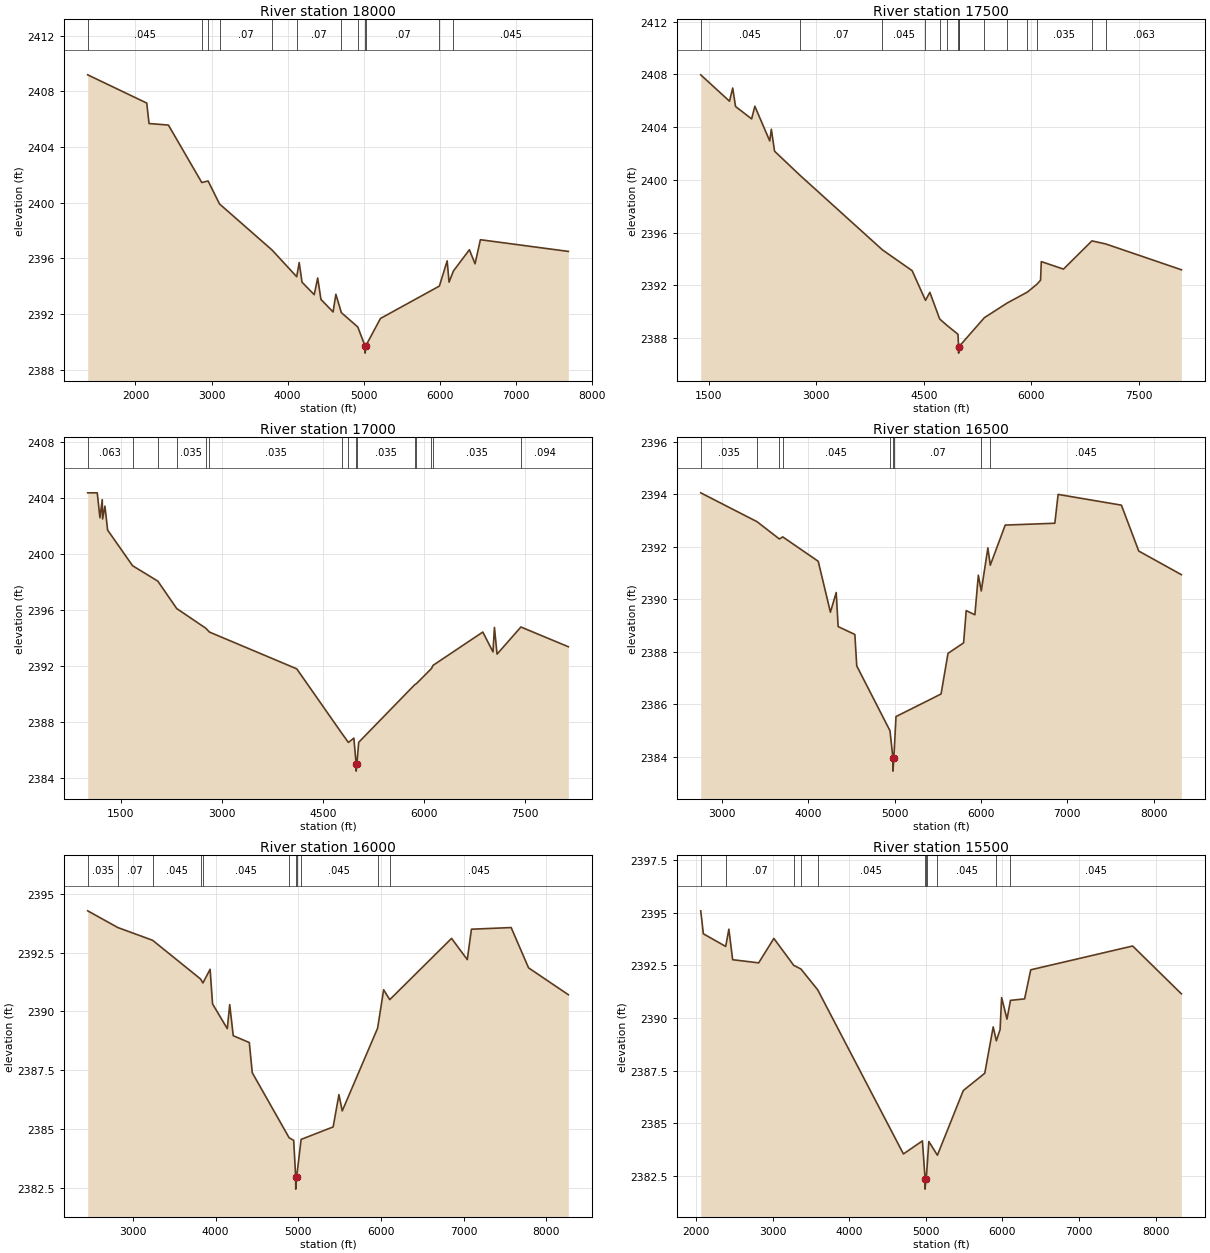
Type RM Length L Ch R = 1,18000,500,500,500
BEGIN DESCRIPTION:
Cottonwood Creek Trib030 36.0
END DESCRIPTION:
XS GIS Cut Line= 3
      1327595.56      6841131.56      1329457.39      6844245.40
      1332135.48      6843970.09
#Sta/Elev= 30
  1372.0 2409.18  2148.5 2407.15  2178.6 2405.68  2433.4 2405.57  2872.0 2401.44
  2955.4 2401.55  3105.6 2399.90  3796.2 2396.59  4120.4 2394.67  4153.0 2395.69
  4190.0 2394.28  4350.6 2393.38  4396.2 2394.58  4439.0 2393.04  4598.5 2392.14
  4635.4 2393.41  4707.2 2392.09  4923.5 2391.06  5019.8 2389.68  5020.3 2389.18
  5026.3 2389.68  5221.4 2391.67  5996.5 2394.00  6098.8 2395.81  6123.5 2394.28
  6180.7 2395.08  6391.2 2396.61  6465.3 2395.60  6535.7 2397.33  7692.2 2396.49
#Mann=12,-1,0
  1372.0   0.045       0  2872.0    0.07       0  2955.4   0.045       0
  3105.6    0.07       0  3796.2   0.045       0  4120.4    0.07       0
  4707.2   0.045       0  4923.5    0.07       0  5019.8    0.07       0
  5026.3    0.07       0  5996.5   0.035       0  6180.7   0.045       0
Bank Sta=5019.8,5026.3
Exp/Cntr=0.3,0.1

Type RM Length L Ch R = 1,17500,500,500,500
BEGIN DESCRIPTION:
Cottonwood Creek Trib030 35.0
END DESCRIPTION:
XS GIS Cut Line= 3
      1327655.00      6841438.00      1329254.81      6844677.06
      1332300.18      6845202.69
#Sta/Elev= 30
  1387.4 2407.97  1788.9 2405.97  1833.5 2406.97  1872.7 2405.57  2097.2 2404.63
  2142.1 2405.59  2349.6 2402.96  2372.1 2403.84  2417.0 2402.18  2770.2 2400.36
  3921.2 2394.70  4335.9 2393.12  4521.8 2390.87  4582.7 2391.48  4719.7 2389.46
  4820.1 2388.98  4974.9 2388.30  4983.3 2387.37  4983.8 2386.87  4990.2 2387.37
  5343.4 2389.56  5661.4 2390.67  5943.2 2391.50  6073.1 2392.08  6126.6 2392.40
  6136.8 2393.81  6446.1 2393.24  6842.8 2395.38  7034.6 2395.15  8090.4 2393.19
#Mann=15,-1,0
  1387.4   0.045       0  2770.2    0.07       0  3921.2   0.045       0
  4521.8    0.07       0  4719.7   0.045       0  4820.1    0.07       0
  4974.9   0.063       0  4983.3   0.063       0  4990.2   0.063       0
  5343.4    0.07       0  5661.4   0.035       0  5943.2   0.063       0
  6073.1   0.035       0  6842.8    0.07       0  7034.6   0.063       0
Bank Sta=4983.3,4990.2
Exp/Cntr=0.3,0.1

Type RM Length L Ch R = 1,17000,500,500,500
BEGIN DESCRIPTION:
Cottonwood Creek Trib030 34.0
END DESCRIPTION:
XS GIS Cut Line= 3
      1325353.68      6844105.40      1329205.17      6845158.21
      1332326.43      6845519.57
#Sta/Elev= 30
  1007.2 2404.36  1149.2 2404.36  1188.8 2402.58  1223.4 2403.87  1228.5 2402.49
  1263.1 2403.41  1302.8 2401.70  1673.7 2399.15  2048.0 2398.05  2328.6 2396.09
  2761.1 2394.68  2814.0 2394.41  4110.7 2391.78  4775.6 2387.20  4877.4 2386.52
  4958.4 2386.83  4991.9 2384.97  4992.4 2384.47  5002.8 2384.97  5030.0 2386.53
  5864.4 2390.66  5884.2 2390.71  6109.3 2391.80  6133.8 2392.03  6872.5 2394.41
  7023.3 2392.99  7045.0 2394.74  7083.7 2392.83  7437.7 2394.77  8142.1 2393.36
#Mann=15,-1,0
  1007.2   0.063       0  1673.7   0.035       0  2048.0   0.063       0
  2328.6   0.035       0  2761.1   0.063       0  2814.0   0.035       0
  4775.6   0.045       0  4877.4   0.035       0  4991.9   0.035       0
  5002.8   0.035       0  5864.4   0.063       0  5884.2   0.035       0
  6109.3   0.063       0  6133.8   0.035       0  7437.7   0.094       0
Bank Sta=4991.9,5002.8
Exp/Cntr=0.3,0.1

Type RM Length L Ch R = 1,16500,500,500,500
BEGIN DESCRIPTION:
Cottonwood Creek Trib030 33.0
END DESCRIPTION:
XS GIS Cut Line= 3
      1327143.17      6844631.45      1329148.81      6845641.02
      1332456.68      6845949.26
#Sta/Elev= 30
  2754.6 2394.06  3406.6 2392.96  3665.6 2392.30  3704.7 2392.38  4115.8 2391.45
  4256.8 2389.51  4324.0 2390.26  4346.4 2388.96  4539.8 2388.66  4562.1 2387.46
  4946.8 2384.99  4980.7 2383.95  4981.2 2383.45  4991.7 2383.95  5016.3 2385.53
  5538.5 2386.39  5618.9 2387.94  5799.6 2388.34  5829.8 2389.57  5930.2 2389.41
  5970.4 2390.92  6004.3 2390.32  6080.8 2391.96  6108.5 2391.30  6281.7 2392.83
  6856.4 2392.90  6894.4 2394.00  7627.5 2393.59  7828.5 2391.84  8322.2 2390.94
#Mann=9,-1,0
  2754.6   0.035       0  3406.6   0.045       0  3665.6   0.035       0
  3704.7   0.045       0  4946.8    0.07       0  4980.7   0.045       0
  4991.7    0.07       0  6004.3   0.035       0  6108.5   0.045       0
Bank Sta=4980.7,4991.7
Exp/Cntr=0.3,0.1

Type RM Length L Ch R = 1,16000,500,500,500
BEGIN DESCRIPTION:
Cottonwood Creek Trib030 32.0
END DESCRIPTION:
XS GIS Cut Line= 3
      1327034.68      6844642.31      1329104.02      6846125.87
      1332365.50      6846287.80
#Sta/Elev= 30
  2453.8 2394.27  2818.5 2393.56  3238.6 2393.02  3817.7 2391.38  3847.3 2391.21
  3933.9 2391.79  3963.4 2390.32  4141.5 2389.27  4171.0 2390.29  4213.7 2388.97
  4408.0 2388.68  4443.6 2387.40  4889.3 2384.64  4944.7 2384.53  4968.6 2382.96
  4969.1 2382.46  4979.7 2382.96  5034.2 2384.57  5421.5 2385.10  5491.6 2386.47
  5531.6 2385.78  5959.2 2389.29  6032.2 2390.92  6105.8 2390.50  6853.3 2393.10
  7043.5 2392.20  7093.6 2393.49  7574.1 2393.56  7784.4 2391.85  8265.5 2390.71
#Mann=11,-1,0
  2453.8   0.035       0  2818.5    0.07       0  3238.6   0.045       0
  3817.7    0.07       0  3847.3   0.045       0  4889.3    0.07       0
  4968.6    0.07       0  4979.7    0.07       0  5034.2   0.045       0
  5959.2   0.035       0  6105.8   0.045       0
Bank Sta=4968.6,4979.7
Exp/Cntr=0.3,0.1

Type RM Length L Ch R = 1,15500,500,500,500
BEGIN DESCRIPTION:
Cottonwood Creek Trib030 31.0
END DESCRIPTION:
XS GIS Cut Line= 3
      1326904.48      6844609.78      1329055.00      6846609.79
      1332390.77      6846639.36
#Sta/Elev= 30
  2063.2 2395.09  2097.7 2394.00  2389.1 2393.40  2430.4 2394.22  2479.8 2392.77
  2819.3 2392.62  3017.7 2393.78  3277.3 2392.50  3370.6 2392.33  3589.9 2391.34
  4708.7 2383.55  4956.4 2384.17  4991.0 2382.38  4991.5 2381.88  5002.1 2382.38
  5010.2 2382.57  5040.0 2384.14  5151.9 2383.49  5490.0 2386.56  5770.0 2387.38
  5880.0 2389.58  5921.2 2388.92  5970.0 2389.45  5990.0 2390.97  6060.0 2389.95
  6105.6 2390.84  6290.0 2390.91  6370.1 2392.29  7700.1 2393.42  8335.9 2391.15
#Mann=11,-1,0
  2063.2   0.035       0  2389.1    0.07       0  3277.3   0.045       0
  3370.6    0.07       0  3589.9   0.045       0  4991.0   0.045       0
  5002.1   0.045       0  5010.2    0.07       0  5151.9   0.045       0
  5921.2   0.035       0  6105.6   0.045       0
Bank Sta=4991,5002.1
Exp/Cntr=0.3,0.1

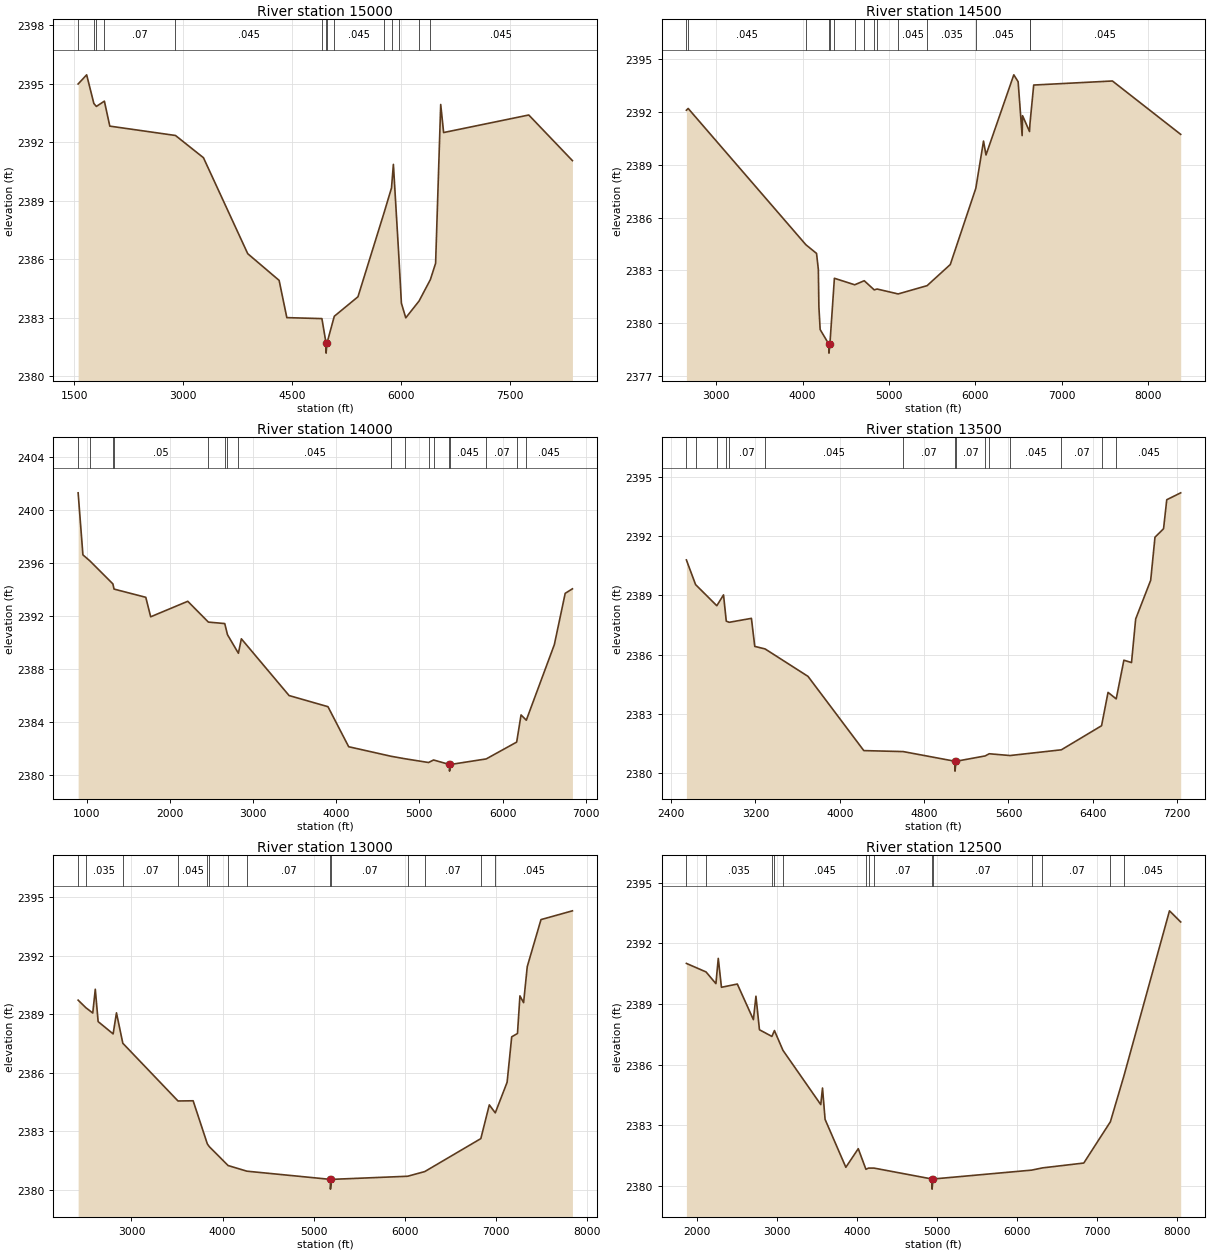
Type RM Length L Ch R = 1,15000,500,500,500
BEGIN DESCRIPTION:
Cottonwood Creek Trib030 30.0
END DESCRIPTION:
XS GIS Cut Line= 3
      1326752.56      6844544.67      1329055.30      6847109.79
      1332404.61      6847303.43
#Sta/Elev= 30
  1552.9 2394.99  1670.2 2395.46  1769.3 2393.99  1804.2 2393.84  1914.1 2394.11
  1988.7 2392.83  2892.6 2392.35  3277.5 2391.21  3886.6 2386.29  4318.7 2384.92
  4424.8 2383.01  4907.5 2382.96  4965.0 2381.69  4965.5 2381.19  4976.1 2381.69
  5078.0 2383.08  5403.7 2384.08  5766.2 2388.43  5865.2 2389.66  5891.2 2390.87
  5964.2 2386.28  6001.4 2383.75  6061.5 2383.00  6244.2 2383.86  6400.0 2384.96
  6472.2 2385.80  6542.3 2393.94  6582.3 2392.50  7754.3 2393.40  8354.9 2391.06
#Mann=14,-1,0
  1552.9   0.035       0  1769.3    0.05       0  1804.2   0.035       0
  1914.1    0.07       0  2892.6   0.045       0  4907.5    0.07       0
  4965.0    0.07       0  4976.1    0.07       0  5078.0   0.045       0
  5766.2   0.063       0  5865.2   0.035       0  5964.2    0.07       0
  6244.2   0.063       0  6400.0   0.045       0
Bank Sta=4965,4976.1
Exp/Cntr=0.3,0.1

Type RM Length L Ch R = 1,14500,500,500,500
BEGIN DESCRIPTION:
Cottonwood Creek Trib030 29.0
END DESCRIPTION:
XS GIS Cut Line= 3
      1327547.84      6845623.78      1328901.57      6847541.76
      1332274.39      6847785.20
#Sta/Elev= 30
  2652.4 2392.09  2673.0 2392.19  4038.0 2384.45  4160.9 2383.96  4181.8 2383.05
  4188.0 2380.94  4202.7 2379.64  4304.4 2378.80  4304.9 2378.30  4315.5 2378.80
  4367.8 2382.55  4603.3 2382.18  4713.5 2382.41  4829.8 2381.89  4862.6 2381.94
  5106.8 2381.66  5442.1 2382.13  5711.0 2383.33  6007.0 2387.66  6096.3 2390.34
  6124.9 2389.55  6447.2 2394.10  6497.3 2393.71  6543.8 2390.65  6548.8 2391.78
  6629.4 2390.88  6634.0 2391.30  6677.8 2393.52  7590.2 2393.75  8381.6 2390.72
#Mann=15,-1,0
  2652.4    0.07       0  2673.0   0.045       0  4038.0    0.07       0
  4304.4   0.035       0  4315.5    0.07       0  4367.8   0.035       0
  4603.3   0.045       0  4713.5   0.035       0  4829.8   0.045       0
  4862.6   0.035       0  5106.8   0.045       0  5442.1   0.035       0
  6007.0   0.045       0  6629.4    0.07       0  6634.0   0.045       0
Bank Sta=4304.4,4315.5
Exp/Cntr=0.3,0.1

Type RM Length L Ch R = 1,14000,500,500,500
BEGIN DESCRIPTION:
Cottonwood Creek Trib030 28.0
END DESCRIPTION:
XS GIS Cut Line= 3
      1326505.02      6844338.03      1328547.86      6847895.16
      1330305.02      6848438.01
#Sta/Elev= 30
   898.0 2401.30   955.6 2396.62  1038.8 2396.17  1316.0 2394.43  1329.7 2394.04
  1711.1 2393.42  1770.0 2391.95  2215.8 2393.12  2463.6 2391.55  2660.2 2391.44
  2693.2 2390.60  2824.3 2389.20  2859.9 2390.29  3433.6 2386.01  3900.9 2385.17
  4149.9 2382.15  4659.5 2381.43  4829.3 2381.24  5109.8 2380.96  5170.2 2381.15
  5361.4 2380.81  5361.9 2380.31  5372.5 2380.81  5802.6 2381.23  6169.0 2382.50
  6221.6 2384.55  6284.6 2384.15  6621.7 2389.85  6752.2 2393.72  6839.1 2394.06
#Mann=17,-1,0
   898.0   0.063       0  1038.8   0.035       0  1316.0    0.07       0
  1329.7    0.05       0  2463.6    0.07       0  2660.2   0.035       0
  2693.2    0.07       0  2824.3   0.045       0  4659.5   0.035       0
  4829.3   0.045       0  5109.8   0.035       0  5170.2   0.045       0
  5361.4   0.045       0  5372.5   0.045       0  5802.6    0.07       0
  6169.0   0.035       0  6284.6   0.045       0
Bank Sta=5361.4,5372.5
Exp/Cntr=0.3,0.1

Type RM Length L Ch R = 1,13500,500,500,500
BEGIN DESCRIPTION:
Cottonwood Creek Trib030 27.0
END DESCRIPTION:
XS GIS Cut Line= 3
      1326961.86      6846040.39      1328158.04      6848184.60
      1330355.01      6848588.00
#Sta/Elev= 30
  2544.7 2390.80  2631.9 2389.55  2833.2 2388.48  2896.9 2389.03  2922.9 2387.70
  2950.8 2387.64  3161.4 2387.84  3193.3 2386.42  3291.6 2386.29  3698.5 2384.90
  4227.5 2381.14  4601.7 2381.09  5092.1 2380.60  5092.6 2380.10  5103.2 2380.60
  5379.1 2380.87  5417.4 2380.98  5614.2 2380.89  6101.7 2381.18  6483.0 2382.40
  6544.5 2384.09  6621.9 2383.76  6694.8 2385.72  6767.1 2385.60  6806.7 2387.81
  6949.0 2389.77  6989.7 2391.95  7071.0 2392.38  7101.5 2393.85  7233.7 2394.20
#Mann=15,-1,0
  2544.7    0.07       0  2631.9   0.035       0  2833.2    0.07       0
  2922.9   0.035       0  2950.8    0.07       0  3291.6   0.045       0
  4601.7    0.07       0  5092.1    0.07       0  5103.2    0.07       0
  5379.1   0.045       0  5417.4    0.07       0  5614.2   0.045       0
  6101.7    0.07       0  6483.0   0.035       0  6621.9   0.045       0
Bank Sta=5092.1,5103.2
Exp/Cntr=0.3,0.1

Type RM Length L Ch R = 1,13000,500,500,500
BEGIN DESCRIPTION:
Cottonwood Creek Trib030 26.0
END DESCRIPTION:
XS GIS Cut Line= 3
      1326597.28      6846131.53      1327751.77      6848444.41
      1330578.45      6848722.15
#Sta/Elev= 30
  2415.0 2389.73  2500.5 2389.34  2575.5 2389.07  2603.4 2390.29  2634.6 2388.63
  2799.2 2388.00  2835.8 2389.08  2905.5 2387.52  3511.2 2384.56  3677.3 2384.57
  3833.2 2382.36  3854.4 2382.22  4060.9 2381.25  4267.0 2380.96  5183.8 2380.54
  5184.3 2380.04  5195.5 2380.54  6031.2 2380.70  6219.4 2380.94  6834.9 2382.63
  6928.0 2384.36  6993.5 2383.95  7123.4 2385.52  7173.7 2387.85  7237.2 2388.02
  7264.1 2389.95  7304.3 2389.60  7344.5 2391.45  7495.2 2393.86  7840.3 2394.31
#Mann=14,-1,0
  2415.0    0.07       0  2500.5   0.035       0  2905.5    0.07       0
  3511.2   0.045       0  3833.2   0.035       0  3854.4   0.045       0
  4060.9   0.035       0  4267.0    0.07       0  5183.8    0.07       0
  5195.5    0.07       0  6031.2   0.045       0  6219.4    0.07       0
  6834.9   0.035       0  6993.5   0.045       0
Bank Sta=5183.8,5195.5
Exp/Cntr=0.3,0.1

Type RM Length L Ch R = 1,12500,500,500,500
BEGIN DESCRIPTION:
Cottonwood Creek Trib030 25.0
END DESCRIPTION:
XS GIS Cut Line= 3
      1326180.61      6845832.04      1327360.60      6848732.28
      1330404.91      6848895.77
#Sta/Elev= 30
  1868.9 2391.00  2114.1 2390.58  2237.9 2390.00  2267.4 2391.25  2307.2 2389.82
  2505.5 2389.98  2706.6 2388.22  2738.3 2389.38  2782.2 2387.72  2937.7 2387.39
  2969.6 2387.68  3076.5 2386.70  3548.7 2384.02  3570.6 2384.84  3602.7 2383.29
  3862.3 2380.92  4017.5 2381.84  4113.4 2380.82  4145.8 2380.88  4215.0 2380.88
  4940.2 2380.34  4940.7 2379.84  4951.9 2380.34  6186.5 2380.78  6320.5 2380.89
  6837.0 2381.13  7169.6 2383.17  7337.5 2385.42  7908.6 2393.60  8048.7 2393.05
#Mann=14,-1,0
  1868.9    0.07       0  2114.1   0.035       0  2937.7    0.07       0
  2969.6   0.035       0  3076.5   0.045       0  4113.4   0.035       0
  4145.8   0.045       0  4215.0    0.07       0  4940.2    0.07       0
  4951.9    0.07       0  6186.5   0.045       0  6320.5    0.07       0
  7169.6   0.035       0  7337.5   0.045       0
Bank Sta=4940.2,4951.9
Exp/Cntr=0.3,0.1