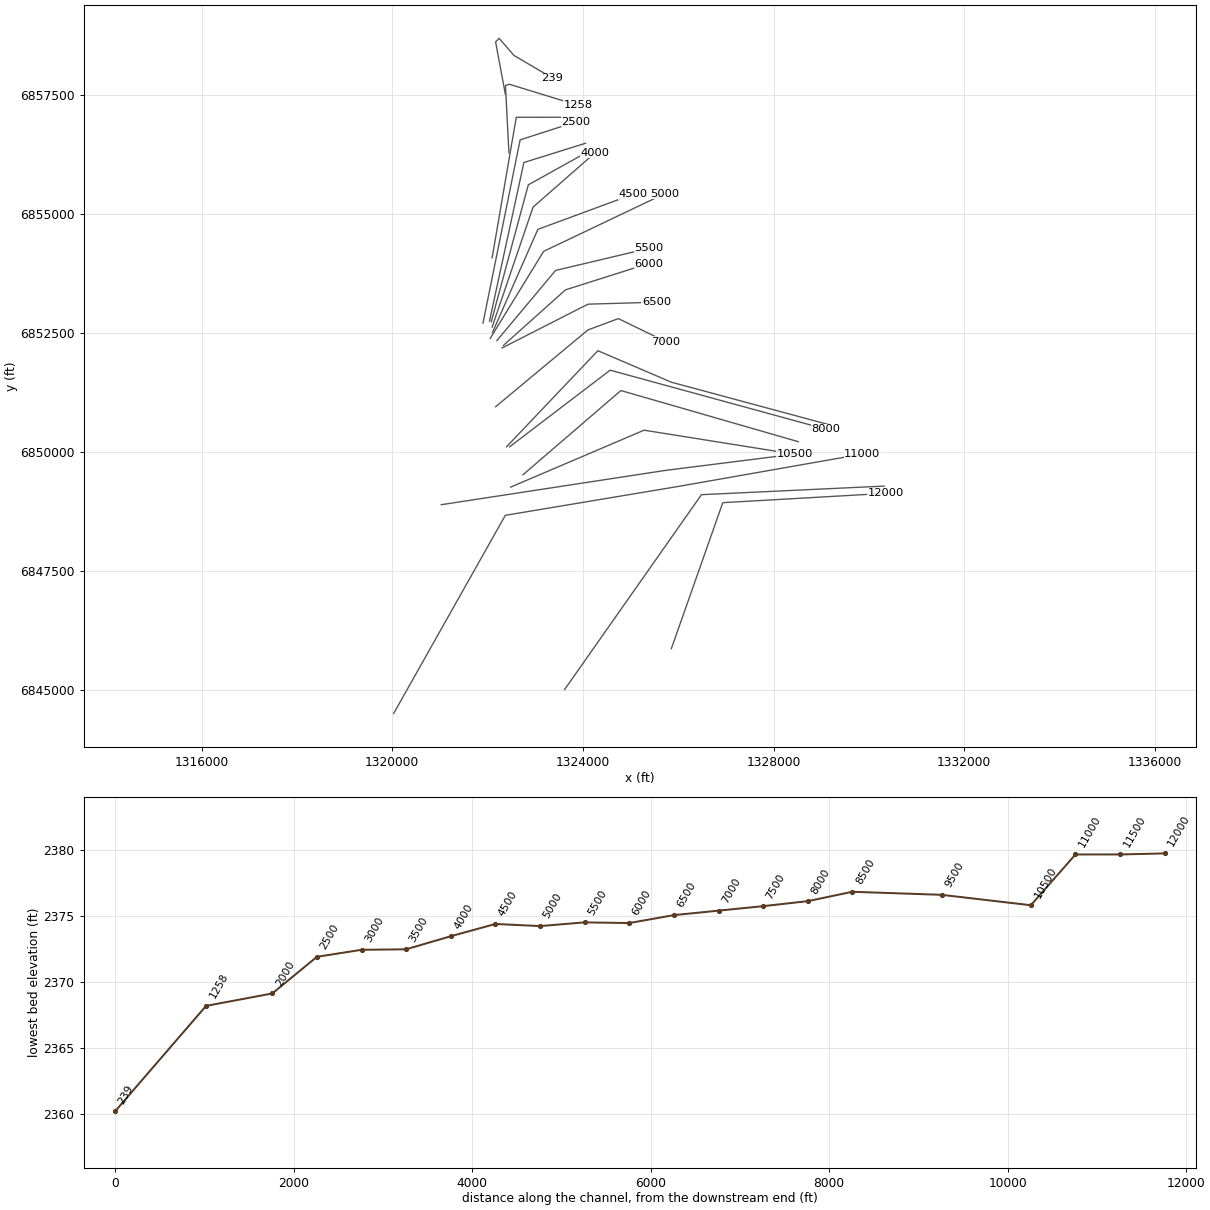
HEC-RAS study Cottonwood Creek Trib030.prj: Cottonwood Creek Trib030 Base Level Engineering

--- Cottonwood Creek Trib030.g01 (geometry) --- (continued)

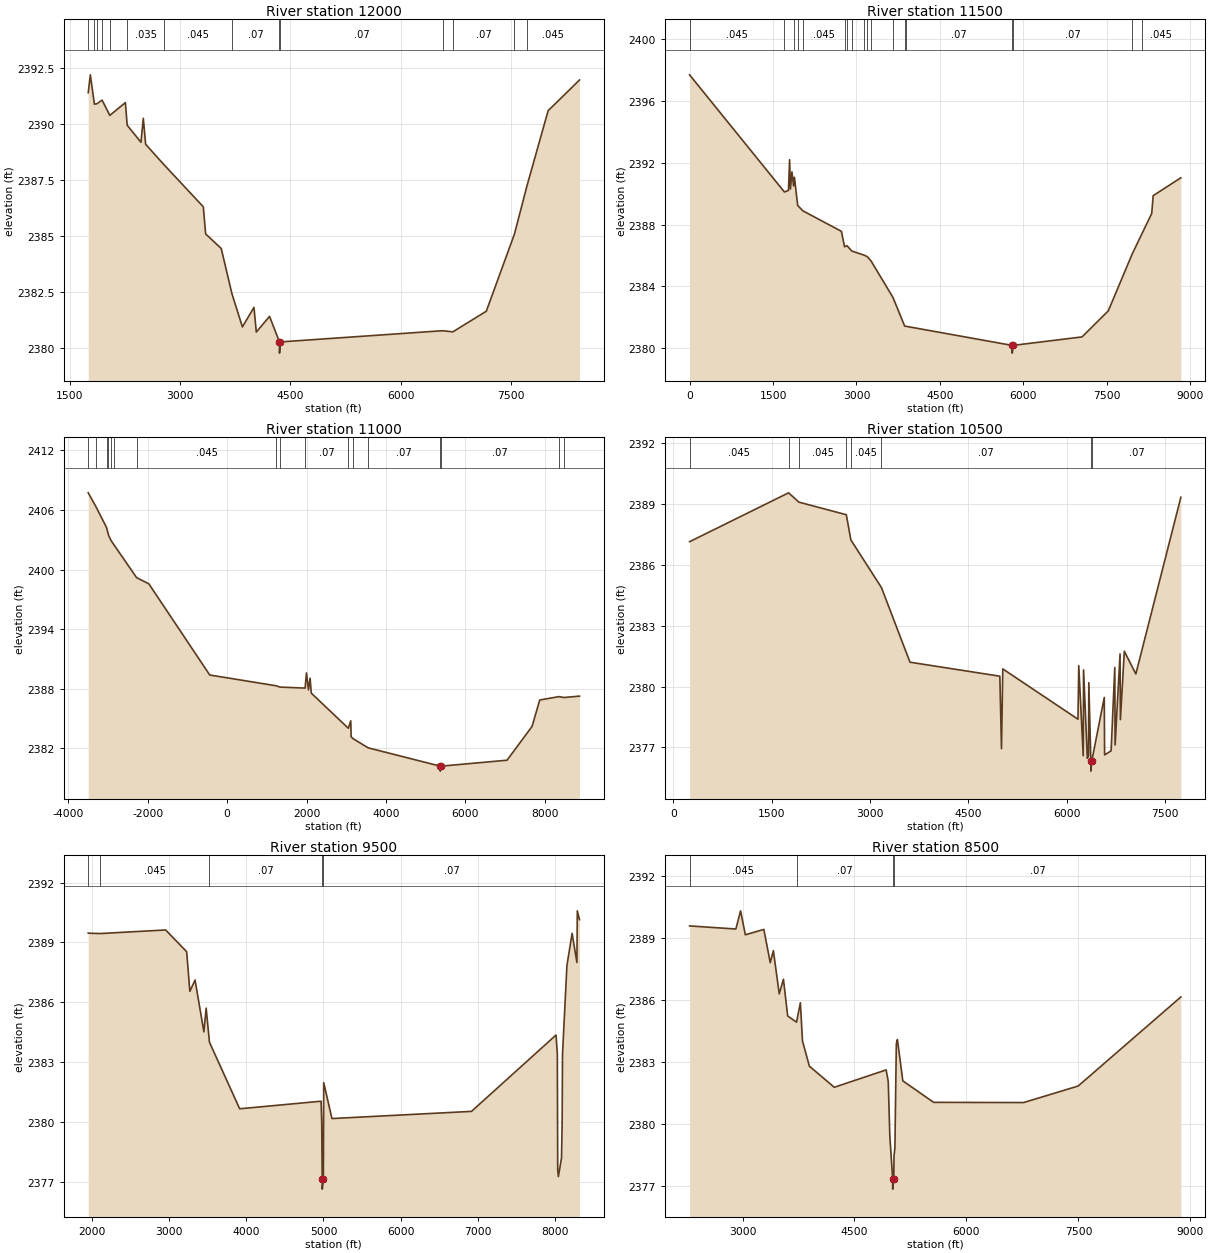
Type RM Length L Ch R = 1,12000,500,500,500
BEGIN DESCRIPTION:
Cottonwood Creek Trib030 24.0
END DESCRIPTION:
XS GIS Cut Line= 3
      1325855.10      6845871.14      1326934.21      6848937.93
      1330360.78      6849134.44
#Sta/Elev= 30
  1748.9 2391.38  1777.4 2392.18  1832.9 2390.87  1867.1 2390.89  1937.8 2391.05
  2042.6 2390.37  2254.4 2390.94  2278.9 2389.93  2466.4 2389.17  2498.2 2390.24
  2530.0 2389.08  2776.5 2388.18  3314.5 2386.29  3346.3 2385.08  3558.3 2384.43
  3703.1 2382.42  3846.2 2380.93  4003.6 2381.80  4035.4 2380.70  4215.6 2381.40
  4350.5 2380.26  4351.0 2379.76  4362.9 2380.26  6569.2 2380.76  6709.4 2380.71
  7164.3 2381.63  7546.8 2385.07  7718.7 2387.24  8005.7 2390.58  8432.2 2391.95
#Mann=14,-1,0
  1748.9    0.07       0  1832.9   0.035       0  1867.1    0.07       0
  1937.8   0.035       0  2042.6    0.07       0  2278.9   0.035       0
  2776.5   0.045       0  3703.1    0.07       0  4350.5    0.07       0
  4362.9    0.07       0  6569.2   0.045       0  6709.4    0.07       0
  7546.8   0.035       0  7718.7   0.045       0
Bank Sta=4350.5,4362.9
Exp/Cntr=0.3,0.1

Type RM Length L Ch R = 1,11500,500,500,500
BEGIN DESCRIPTION:
Cottonwood Creek Trib030 23.0
END DESCRIPTION:
XS GIS Cut Line= 3
      1323615.54      6845011.79      1326487.07      6849106.22
      1330318.04      6849286.39
#Sta/Elev= 30
    -1.0 2397.71  1704.9 2390.12  1777.4 2390.22  1798.3 2392.21  1813.1 2390.31
  1840.1 2391.42  1870.5 2390.51  1884.6 2391.08  1943.5 2389.25  2036.1 2388.90
  2730.3 2387.57  2786.2 2386.57  2829.8 2386.64  2919.4 2386.29  3144.5 2386.02
  3195.1 2385.93  3265.2 2385.64  3656.9 2383.29  3867.9 2381.43  3888.8 2381.42
  5802.3 2380.18  5802.8 2379.68  5815.4 2380.18  7057.7 2380.73  7530.7 2382.42
  7958.6 2386.09  8133.5 2387.40  8311.6 2388.73  8337.0 2389.88  8835.2 2391.04
#Mann=18,-1,0
    -1.0   0.045       0  1704.9   0.063       0  1870.5   0.035       0
  1943.5    0.07       0  2036.1   0.045       0  2786.2    0.07       0
  2829.8   0.045       0  2919.4    0.07       0  3144.5   0.045       0
  3195.1    0.07       0  3265.2   0.045       0  3656.9    0.07       0
  3867.9   0.045       0  3888.8    0.07       0  5802.3    0.07       0
  5815.4    0.07       0  7958.6   0.035       0  8133.5   0.045       0
Bank Sta=5802.3,5815.4
Exp/Cntr=0.3,0.1

Type RM Length L Ch R = 1,11000,500,500,500
BEGIN DESCRIPTION:
Cottonwood Creek Trib030 22.0
END DESCRIPTION:
XS GIS Cut Line= 4
      1320031.62      6844512.10      1322372.82      6848672.28
      1326045.30      6849286.49      1329861.20      6849958.93
#Sta/Elev= 30
 -3497.2 2407.73 -3311.4 2406.40 -3033.9 2404.22 -2988.1 2403.48 -2924.0 2402.93
 -2854.3 2402.52 -2278.6 2399.18 -1970.6 2398.56  -437.2 2389.37  1238.0 2388.28
  1333.8 2388.15  1964.9 2388.05  1998.6 2389.58  2049.3 2387.87  2089.8 2389.05
  2120.2 2387.54  3053.1 2384.00  3113.9 2384.75  3124.0 2383.14  3173.9 2382.95
  3550.0 2382.03  5368.8 2380.18  5369.3 2379.68  5382.0 2380.18  7050.0 2380.78
  7680.4 2384.19  7873.3 2386.85  8359.4 2387.19  8482.1 2387.10  8874.7 2387.24
#Mann=17,-1,0
 -3497.2   0.045       0 -3311.4    0.07       0 -3033.9   0.045       0
 -2988.1    0.07       0 -2924.0   0.045       0 -2854.3    0.07       0
 -2278.6   0.045       0  1238.0    0.07       0  1333.8   0.045       0
  1964.9    0.07       0  3053.1   0.063       0  3173.9   0.045       0
  3550.0    0.07       0  5368.8    0.07       0  5382.0    0.07       0
  8359.4   0.035       0  8482.1   0.045       0
Bank Sta=5368.8,5382
Exp/Cntr=0.3,0.1

Type RM Length L Ch R = 1,10500,1000,1000,1000
BEGIN DESCRIPTION:
Cottonwood Creek Trib030 21.0
END DESCRIPTION:
XS GIS Cut Line= 3
      1321029.84      6848895.76      1325727.51      6849615.63
      1328450.84      6849959.02
#Sta/Elev= 30
   247.5 2387.14  1758.7 2389.55  1916.2 2389.09  2639.7 2388.47  2708.8 2387.23
  3175.6 2384.88  3611.5 2381.20  4982.5 2380.51  5007.6 2376.94  5027.7 2380.87
  6174.9 2378.39  6186.8 2381.03  6255.1 2376.59  6260.2 2380.82  6317.8 2376.46
  6335.4 2376.60  6340.5 2380.19  6371.1 2376.33  6371.6 2375.83  6385.5 2376.33
  6576.3 2379.46  6581.3 2376.63  6680.7 2376.83  6736.8 2380.94  6741.9 2377.12
  6817.1 2381.61  6822.2 2378.37  6882.3 2381.74  7058.0 2380.62  7744.9 2389.33
#Mann=8,-1,0
   247.5   0.045       0  1758.7   0.035       0  1916.2   0.045       0
  2639.7    0.07       0  2708.8   0.045       0  3175.6    0.07       0
  6371.1    0.07       0  6385.5    0.07       0
Bank Sta=6371.1,6385.5
Exp/Cntr=0.3,0.1

Type RM Length L Ch R = 1,9500,1000,1000,1000
BEGIN DESCRIPTION:
Cottonwood Creek Trib030 19.0
END DESCRIPTION:
XS GIS Cut Line= 3
      1322483.88      6849264.69      1325282.90      6850460.59
      1328555.04      6849937.99
#Sta/Elev= 30
  1956.2 2389.46  2108.0 2389.44  2957.9 2389.62  3229.8 2388.53  3271.6 2386.54
  3338.5 2387.11  3453.1 2384.51  3482.1 2385.70  3525.0 2383.99  3916.0 2380.65
  4969.7 2381.03  4977.9 2379.95  4984.1 2377.12  4984.6 2376.62  4998.8 2377.12
  5003.6 2381.96  5110.0 2380.16  6916.1 2380.52  8009.8 2384.35  8026.6 2383.41
  8031.7 2377.58  8040.1 2377.25  8080.6 2378.18  8088.7 2379.90  8093.7 2383.39
  8150.8 2387.84  8217.9 2389.45  8280.0 2387.99  8285.1 2390.58  8313.6 2390.14
#Mann=5,-1,0
  1956.2   0.035       0  2108.0   0.045       0  3525.0    0.07       0
  4984.1    0.07       0  4998.8    0.07       0
Bank Sta=4984.1,4998.8
Exp/Cntr=0.3,0.1

Type RM Length L Ch R = 1,8500,500,500,500
BEGIN DESCRIPTION:
Cottonwood Creek Trib030 17.0
END DESCRIPTION:
XS GIS Cut Line= 3
      1322744.26      6849525.08      1324796.84      6851293.48
      1328516.83      6850219.56
#Sta/Elev= 30
  2290.7 2389.59  2910.6 2389.44  2974.2 2390.32  3037.8 2389.16  3285.8 2389.42
  3371.4 2387.81  3413.6 2388.39  3492.0 2386.30  3548.0 2387.01  3605.1 2385.23
  3723.7 2384.93  3775.1 2385.87  3803.6 2384.02  3895.8 2382.80  4229.3 2381.78
  4923.8 2382.62  4952.3 2382.06  4973.2 2379.42  5011.5 2377.35  5012.0 2376.85
  5026.3 2377.35  5029.3 2378.45  5041.3 2378.84  5060.5 2383.89  5075.0 2384.09
  5147.5 2382.09  5560.1 2381.05  6765.3 2381.04  7496.1 2381.84  8871.9 2386.15
#Mann=4,-1,0
  2290.7   0.045       0  3723.7    0.07       0  5011.5    0.07       0
  5026.3    0.07       0
Bank Sta=5011.5,5026.3
Exp/Cntr=0.3,0.1

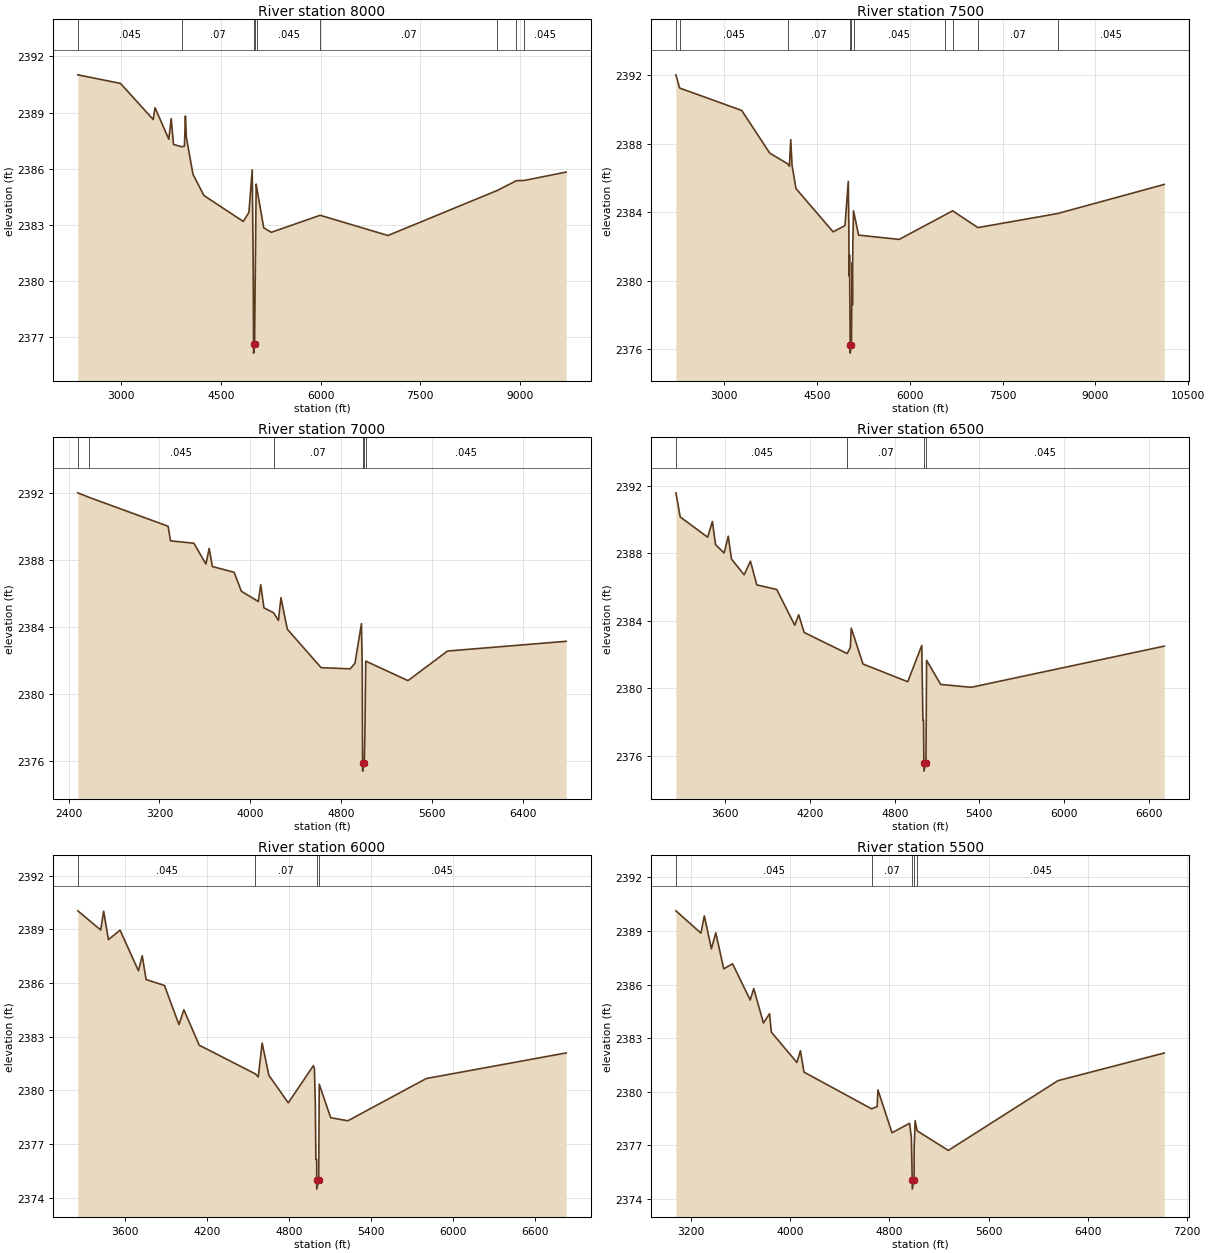
Type RM Length L Ch R = 1,8000,500,500,500
BEGIN DESCRIPTION:
Cottonwood Creek Trib030 16.0
END DESCRIPTION:
XS GIS Cut Line= 3
      1322462.21      6850111.07      1324571.95      6851721.42
      1329101.40      6850480.35
#Sta/Elev= 30
  2345.9 2391.02  2988.3 2390.56  3480.8 2388.63  3507.9 2389.26  3715.7 2387.58
  3751.1 2388.68  3786.4 2387.30  3912.1 2387.17  3950.6 2387.21  3965.1 2388.82
  3979.7 2387.68  4079.4 2385.70  4243.6 2384.57  4835.9 2383.18  4921.1 2383.66
  4971.0 2385.94  4985.5 2380.94  4991.4 2376.64  4991.9 2376.14  5006.2 2376.64
  5030.5 2385.18  5045.8 2384.85  5144.3 2382.84  5258.0 2382.60  5993.1 2383.51
  7014.7 2382.43  8661.6 2384.84  8947.8 2385.36  9063.1 2385.37  9696.4 2385.82
#Mann=9,-1,0
  2345.9   0.045       0  3912.1    0.07       0  4991.4    0.07       0
  5006.2    0.07       0  5045.8   0.045       0  5993.1    0.07       0
  8661.6   0.045       0  8947.8    0.07       0  9063.1   0.045       0
Bank Sta=4991.4,5006.2
Exp/Cntr=0.3,0.1

Type RM Length L Ch R = 1,7500,500,500,500
BEGIN DESCRIPTION:
Cottonwood Creek Trib030 15.0
END DESCRIPTION:
XS GIS Cut Line= 4
      1322397.10      6850111.08      1324314.49      6852130.11
      1325854.16      6851469.12      1329171.81      6850573.77
#Sta/Elev= 30
  2215.6 2392.01  2275.3 2391.24  3280.0 2389.93  3732.7 2387.44  4025.1 2386.81
  4051.0 2386.67  4072.4 2388.23  4093.5 2386.73  4157.0 2385.37  4758.4 2382.84
  4949.4 2383.21  5003.0 2385.79  5011.4 2383.33  5017.4 2380.26  5022.9 2381.49
  5033.6 2376.26  5034.1 2375.76  5048.4 2376.26  5055.0 2376.51  5064.6 2381.03
  5070.0 2378.57  5076.7 2382.22  5087.5 2384.07  5169.7 2382.65  5825.7 2382.40
  6566.8 2383.83  6690.5 2384.07  7099.2 2383.09  8387.7 2383.91 10111.9 2385.61
#Mann=10,-1,0
  2215.6   0.035       0  2275.3   0.045       0  4025.1    0.07       0
  5033.6    0.07       0  5048.4    0.07       0  5087.5   0.045       0
  6566.8    0.07       0  6690.5   0.063       0  7099.2    0.07       0
  8387.7   0.045       0
Bank Sta=5033.6,5048.4
Exp/Cntr=0.3,0.1

Type RM Length L Ch R = 1,7000,500,500,500
BEGIN DESCRIPTION:
Cottonwood Creek Trib030 14.0
END DESCRIPTION:
XS GIS Cut Line= 4
      1322169.03      6850953.34      1324104.73      6852565.78
      1324743.05      6852804.72      1325735.02      6852322.39
#Sta/Elev= 30
  2480.7 2391.99  2580.4 2391.72  3276.4 2390.00  3297.3 2389.13  3503.6 2388.99
  3609.7 2387.75  3638.3 2388.68  3667.0 2387.60  3858.3 2387.26  3922.1 2386.13
  4071.8 2385.52  4092.6 2386.52  4121.3 2385.14  4205.9 2384.85  4248.8 2384.39
  4271.0 2385.75  4327.0 2383.87  4625.1 2381.58  4881.5 2381.51  4923.2 2381.84
  4980.4 2384.20  4987.3 2381.77  4990.4 2375.92  4990.9 2375.42  5005.2 2375.92
  5011.0 2377.69  5018.3 2381.97  5390.7 2380.81  5739.3 2382.57  6784.6 2383.15
#Mann=6,-1,0
  2480.7   0.035       0  2580.4   0.045       0  4205.9    0.07       0
  4990.4    0.07       0  5005.2    0.07       0  5018.3   0.045       0
Bank Sta=4990.4,5005.2
Exp/Cntr=0.3,0.1

Type RM Length L Ch R = 1,6500,500,500,500
BEGIN DESCRIPTION:
Cottonwood Creek Trib030 13.0
END DESCRIPTION:
XS GIS Cut Line= 4
      1322305.02      6852188.01      1323862.43      6852983.69
      1324111.10      6853108.01      1325540.78      6853149.65
#Sta/Elev= 30
  3251.1 2391.58  3281.6 2390.15  3475.7 2388.95  3509.4 2389.88  3531.8 2388.51
  3592.7 2388.01  3621.7 2389.01  3644.1 2387.66  3734.0 2386.72  3778.9 2387.53
  3823.8 2386.12  3964.8 2385.85  4092.5 2383.73  4120.3 2384.35  4159.2 2383.30
  4464.1 2382.05  4486.3 2382.42  4492.4 2383.56  4575.7 2381.43  4892.4 2380.38
  4991.7 2382.53  5000.0 2378.10  5004.2 2378.10  5006.7 2375.58  5007.2 2375.08
  5021.5 2375.58  5025.8 2381.65  5125.9 2380.22  5341.9 2380.05  6708.3 2382.49
#Mann=4,-1,0
  3251.1   0.045       0  4464.1    0.07       0  5006.7    0.07       0
  5021.5   0.045       0
Bank Sta=5006.7,5021.5
Exp/Cntr=0.3,0.1

Type RM Length L Ch R = 1,6000,500,500,500
BEGIN DESCRIPTION:
Cottonwood Creek Trib030 12.0
END DESCRIPTION:
XS GIS Cut Line= 3
      1322333.65      6852242.78      1323634.21      6853408.46
      1325378.90      6853962.01
#Sta/Elev= 30
  3253.5 2390.03  3420.9 2388.96  3442.6 2390.01  3477.7 2388.42  3563.0 2388.95
  3697.5 2386.68  3725.3 2387.52  3753.6 2386.19  3888.1 2385.86  3994.3 2383.67
  4030.2 2384.50  4143.1 2382.52  4553.9 2380.92  4575.2 2380.75  4603.6 2382.64
  4652.9 2380.84  4795.0 2379.30  4978.9 2381.38  4986.4 2381.23  4993.1 2379.29
  4997.2 2376.13  5003.0 2376.13  5003.1 2374.98  5003.6 2374.48  5017.9 2374.98
  5021.8 2380.34  5105.7 2378.47  5231.6 2378.30  5806.0 2380.66  6830.4 2382.09
#Mann=4,-1,0
  3253.5   0.045       0  4553.9    0.07       0  5003.1    0.07       0
  5017.9   0.045       0
Bank Sta=5003.1,5017.9
Exp/Cntr=0.3,0.1

Type RM Length L Ch R = 1,5500,500,500,500
BEGIN DESCRIPTION:
Cottonwood Creek Trib030 11.0
END DESCRIPTION:
XS GIS Cut Line= 3
      1322196.46      6852343.36      1323427.14      6853816.42
      1325388.01      6854282.07
#Sta/Elev= 30
  3080.5 2390.13  3282.0 2388.88  3309.5 2389.85  3366.7 2388.00  3401.9 2388.90
  3465.7 2386.88  3537.2 2387.16  3679.1 2385.13  3707.7 2385.77  3785.8 2383.84
  3835.2 2384.36  3849.6 2383.33  4055.2 2381.63  4083.8 2382.29  4112.4 2381.09
  4657.7 2379.03  4702.0 2379.16  4708.5 2380.09  4821.7 2377.69  4963.6 2378.22
  4977.9 2377.41  4984.7 2375.03  4985.2 2374.53  4999.7 2375.03  5000.0 2376.78
  5008.1 2378.37  5024.2 2377.80  5275.3 2376.70  6159.2 2380.61  7015.4 2382.16
#Mann=5,-1,0
  3080.5   0.045       0  4657.7    0.07       0  4984.7    0.07       0
  4999.7    0.07       0  5024.2   0.045       0
Bank Sta=4984.7,4999.7
Exp/Cntr=0.3,0.1

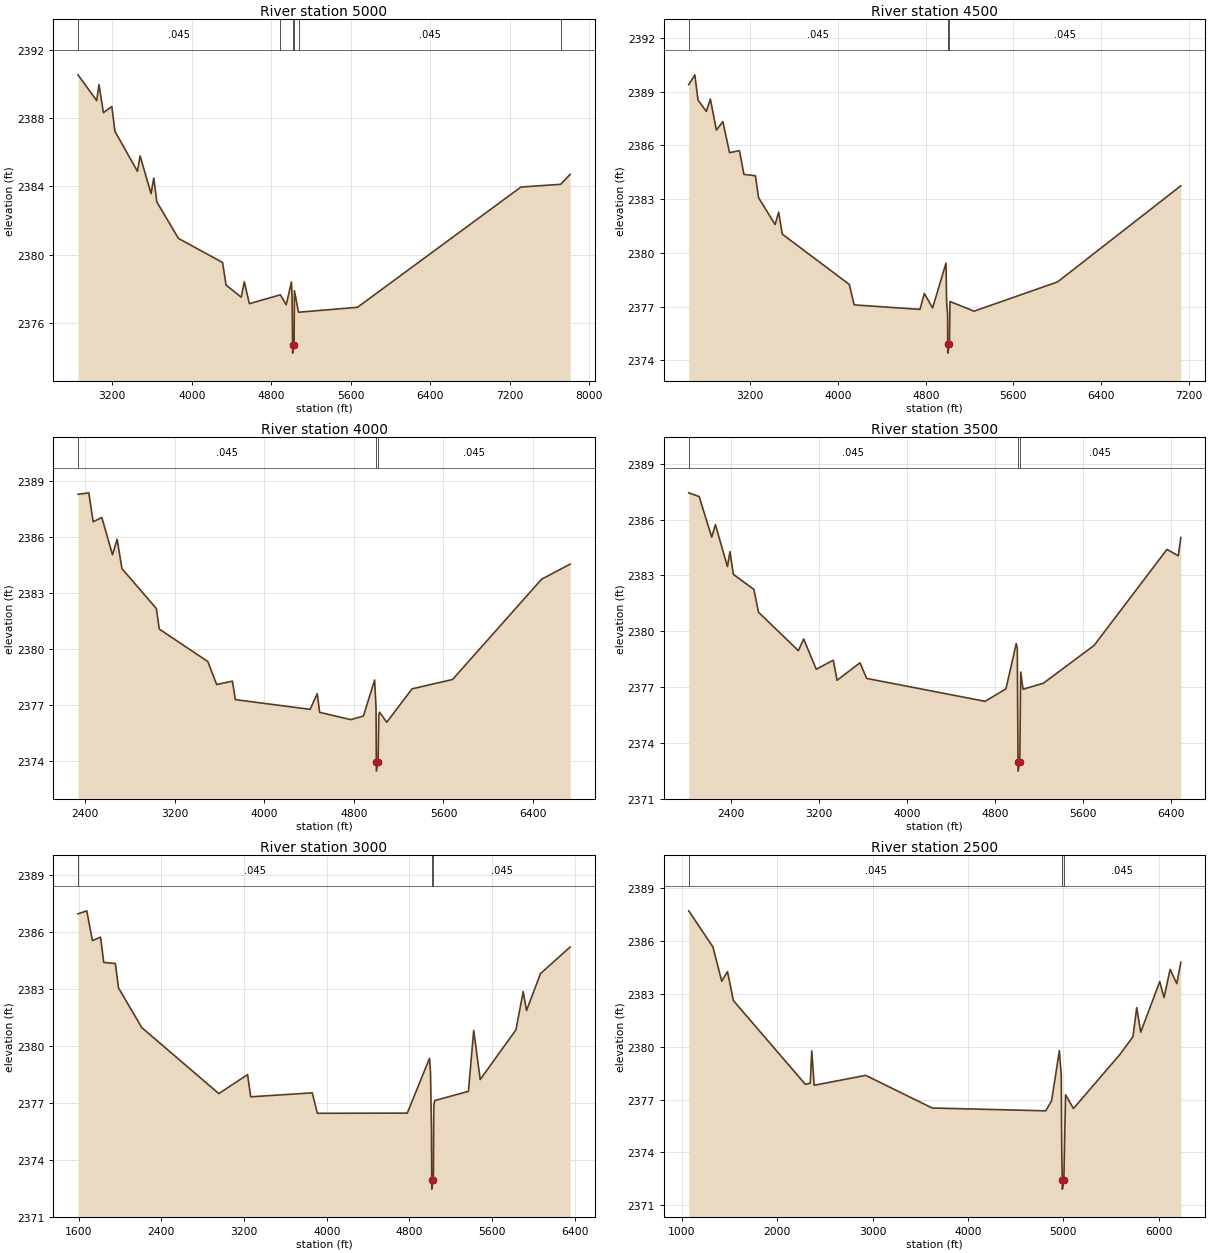
Type RM Length L Ch R = 1,5000,500,500,500
BEGIN DESCRIPTION:
Cottonwood Creek Trib030 10.0
END DESCRIPTION:
XS GIS Cut Line= 3
      1322055.00      6852388.00      1323176.01      6854217.11
      1325708.09      6855425.18
#Sta/Elev= 30
  2854.7 2390.52  3042.4 2389.01  3065.8 2389.95  3110.0 2388.31  3195.1 2388.67
  3226.0 2387.22  3452.3 2384.88  3479.4 2385.78  3589.6 2383.57  3617.1 2384.49
  3647.6 2383.09  3864.3 2380.96  4309.1 2379.55  4344.2 2378.23  4496.7 2377.52
  4527.6 2378.42  4578.8 2377.14  4890.5 2377.66  4949.2 2377.08  5002.2 2378.41
  5009.0 2377.40  5013.4 2374.75  5013.9 2374.25  5028.7 2374.75  5031.7 2377.90
  5073.1 2376.64  5666.6 2376.93  7310.9 2383.96  7710.4 2384.12  7805.5 2384.70
#Mann=6,-1,0
  2854.7   0.045       0  4890.5    0.07       0  5013.4    0.07       0
  5028.7    0.07       0  5073.1   0.045       0  7710.4    0.07       0
Bank Sta=5013.4,5028.7
Exp/Cntr=0.3,0.1

Type RM Length L Ch R = 1,4500,500,500,500
BEGIN DESCRIPTION:
Cottonwood Creek Trib030 9.0
END DESCRIPTION:
XS GIS Cut Line= 3
      1322105.00      6852517.11      1323054.95      6854678.90
      1325049.70      6855416.05
#Sta/Elev= 30
  2638.7 2389.38  2694.3 2389.93  2723.6 2388.52  2799.2 2387.89  2836.3 2388.58
  2890.9 2386.85  2950.2 2387.32  3011.1 2385.59  3101.2 2385.70  3142.1 2384.38
  3246.8 2384.30  3275.6 2383.08  3426.6 2381.58  3458.9 2382.27  3491.2 2381.05
  4103.3 2378.24  4147.5 2377.10  4747.8 2376.85  4787.4 2377.74  4862.9 2376.93
  4985.2 2379.43  4990.6 2377.29  5000.0 2376.54  5000.9 2374.91  5001.4 2374.41
  5016.4 2374.91  5021.4 2377.29  5241.3 2376.75  6002.2 2378.38  7126.6 2383.74
#Mann=3,-1,0
  2638.7   0.045       0  5000.9   0.045       0  5016.4   0.045       0
Bank Sta=5000.9,5016.4
Exp/Cntr=0.3,0.1

Type RM Length L Ch R = 1,4000,500,500,500
BEGIN DESCRIPTION:
Cottonwood Creek Trib030 8.0
END DESCRIPTION:
XS GIS Cut Line= 3
      1322095.86      6852626.86      1322954.66      6855146.63
      1324254.99      6856287.99
#Sta/Elev= 30
  2337.9 2388.31  2434.2 2388.39  2472.9 2386.84  2550.4 2387.07  2645.5 2385.07
  2687.1 2385.90  2730.0 2384.33  3037.2 2382.19  3063.2 2381.09  3496.8 2379.35
  3575.2 2378.12  3716.2 2378.30  3742.3 2377.31  4409.8 2376.79  4473.2 2377.63
  4494.6 2376.63  4771.4 2376.24  4885.2 2376.43  4985.6 2378.36  4998.1 2376.87
  5000.6 2373.98  5001.1 2373.48  5016.2 2373.98  5022.6 2376.46  5029.3 2376.64
  5093.6 2376.10  5319.8 2377.89  5681.2 2378.39  6475.4 2383.76  6730.2 2384.57
#Mann=3,-1,0
  2337.9   0.045       0  5000.6   0.045       0  5016.2   0.045       0
Bank Sta=5000.6,5016.2
Exp/Cntr=0.3,0.1

Type RM Length L Ch R = 1,3500,500,500,500
BEGIN DESCRIPTION:
Cottonwood Creek Trib030 7.0
END DESCRIPTION:
XS GIS Cut Line= 3
      1322077.56      6852736.57      1322854.77      6855614.36
      1324154.97      6856337.98
#Sta/Elev= 30
  2019.1 2387.44  2113.8 2387.24  2227.8 2385.06  2261.3 2385.73  2370.6 2383.48
  2393.5 2384.28  2424.6 2383.06  2611.0 2382.25  2652.4 2381.03  3015.0 2378.96
  3062.8 2379.59  3177.3 2377.96  3331.7 2378.45  3366.4 2377.37  3574.3 2378.31
  3635.3 2377.47  4710.9 2376.24  4900.0 2376.91  4993.4 2379.34  5003.0 2379.10
  5009.6 2372.99  5010.1 2372.49  5025.6 2372.99  5033.6 2377.81  5055.3 2376.89
  5239.4 2377.21  5700.2 2379.24  6362.2 2384.40  6465.1 2384.06  6488.0 2385.04
#Mann=3,-1,0
  2019.1   0.045       0  5009.6   0.045       0  5025.6   0.045       0
Bank Sta=5009.6,5025.6
Exp/Cntr=0.3,0.1

Type RM Length L Ch R = 1,3000,500,500,500
BEGIN DESCRIPTION:
Cottonwood Creek Trib030 6.0
END DESCRIPTION:
XS GIS Cut Line= 3
      1322040.99      6852754.88      1322762.18      6856083.44
      1324054.96      6856487.99
#Sta/Elev= 30
  1594.2 2386.97  1679.1 2387.13  1733.4 2385.56  1812.3 2385.74  1843.0 2384.41
  1955.5 2384.35  1986.2 2383.06  2211.3 2380.97  2956.1 2377.49  3234.5 2378.49
  3265.2 2377.32  3860.1 2377.53  3909.8 2376.45  4779.6 2376.46  4994.6 2379.35
  5004.1 2378.65  5013.4 2375.63  5015.9 2372.95  5016.4 2372.45  5031.9 2372.95
  5035.8 2376.86  5044.9 2377.12  5370.9 2377.61  5422.1 2380.82  5485.0 2378.23
  5830.6 2380.85  5900.7 2382.87  5933.2 2381.87  6068.3 2383.82  6354.6 2385.22
#Mann=3,-1,0
  1594.2   0.045       0  5015.9   0.045       0  5031.9   0.045       0
Bank Sta=5015.9,5031.9
Exp/Cntr=0.3,0.1

Type RM Length L Ch R = 1,2500,500,500,500
BEGIN DESCRIPTION:
Cottonwood Creek Trib030 5.0
END DESCRIPTION:
XS GIS Cut Line= 3
      1321903.81      6852709.11      1322683.57      6856559.34
      1323854.99      6856938.00
#Sta/Elev= 30
  1071.6 2387.70  1325.5 2385.65  1417.4 2383.71  1478.6 2384.25  1539.8 2382.61
  2294.8 2377.86  2345.8 2377.93  2361.7 2379.76  2386.7 2377.81  2927.4 2378.37
  3624.1 2376.52  4815.0 2376.36  4876.2 2376.93  4957.8 2379.77  4977.6 2378.38
  4982.7 2374.02  4988.7 2372.42  4989.2 2371.92  5004.8 2372.42  5022.5 2377.27
  5105.4 2376.49  5590.0 2379.54  5729.5 2380.56  5768.7 2382.21  5810.7 2380.82
  6010.4 2383.69  6055.0 2382.78  6119.0 2384.38  6189.1 2383.57  6231.1 2384.78
#Mann=3,-1,0
  1071.6   0.045       0  4988.7   0.045       0  5004.8   0.045       0
Bank Sta=4988.7,5004.8
Exp/Cntr=0.3,0.1

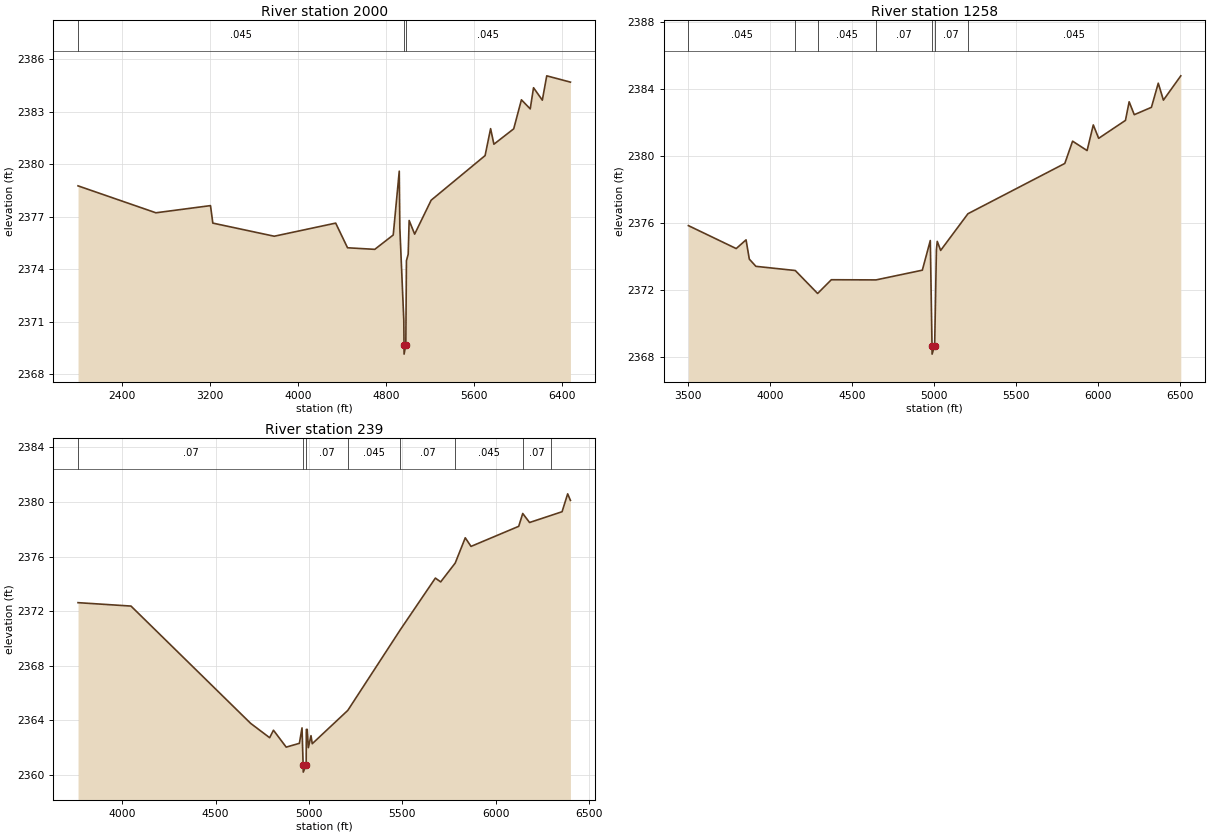
Type RM Length L Ch R = 1,2000,742,742,742
BEGIN DESCRIPTION:
Cottonwood Creek Trib030 4.0
END DESCRIPTION:
XS GIS Cut Line= 3
      1322095.86      6854080.92      1322602.27      6857033.40
      1324080.17      6857034.69
#Sta/Elev= 30
  2004.4 2378.76  2711.7 2377.22  3207.8 2377.63  3229.1 2376.63  3787.1 2375.88
  4345.2 2376.63  4452.9 2375.22  4700.3 2375.13  4868.0 2375.95  4922.9 2379.60
  4928.0 2376.36  4964.1 2371.08  4966.2 2369.64  4966.7 2369.14  4982.3 2369.64
  4988.0 2374.48  5003.9 2374.85  5012.7 2376.78  5062.7 2376.00  5212.7 2377.94
  5702.7 2380.49  5752.7 2382.03  5782.7 2381.14  5962.7 2382.02  6032.7 2383.68
  6112.7 2383.16  6142.7 2384.37  6222.7 2383.66  6262.7 2385.05  6477.9 2384.69
#Mann=3,-1,0
  2004.4   0.045       0  4966.2   0.045       0  4982.3   0.045       0
Bank Sta=4966.2,4982.3
Exp/Cntr=0.3,0.1

Type RM Length L Ch R = 1,1258,1019,1019,1019
BEGIN DESCRIPTION:
Cottonwood Creek Trib030 1.1
END DESCRIPTION:
XS GIS Cut Line= 4
      1322448.54      6856286.57      1322375.63      6857698.01
      1322454.70      6857727.85      1323896.43      6857284.82
#Sta/Elev= 30
  3501.8 2375.87  3793.6 2374.50  3853.7 2375.02  3873.7 2373.87  3913.8 2373.44
  4154.3 2373.19  4290.7 2371.82  4374.4 2372.64  4647.4 2372.63  4929.9 2373.21
  4978.6 2374.98  4989.1 2368.70  4989.6 2368.20  5005.2 2368.70  5015.9 2374.43
  5021.1 2374.93  5041.8 2374.39  5208.5 2376.58  5799.7 2379.58  5847.3 2380.91
  5935.8 2380.35  5973.7 2381.88  6006.5 2381.08  6170.0 2382.15  6192.6 2383.26
  6223.9 2382.49  6328.6 2382.93  6370.4 2384.37  6401.8 2383.36  6507.9 2384.81
#Mann=7,-1,0
  3501.8   0.045       0  4154.3    0.07       0  4290.7   0.045       0
  4647.4    0.07       0  4989.1    0.07       0  5005.2    0.07       0
  5208.5   0.045       0
Bank Sta=4989.1,5005.2
Exp/Cntr=0.3,0.1

Type RM Length L Ch R = 1,239,0,0,0
BEGIN DESCRIPTION:
Cottonwood Creek Trib030 1.2
END DESCRIPTION:
XS GIS Cut Line= 5
      1322373.03      6857519.18      1322169.03      6858617.28
      1322243.68      6858691.93      1322550.98      6858335.16
      1323363.48      6857855.99
#Sta/Elev= 30
  3763.4 2372.62  4047.0 2372.37  4687.8 2363.78  4789.5 2362.73  4809.8 2363.28
  4878.1 2362.04  4948.7 2362.32  4962.8 2363.45  4968.8 2360.71  4969.3 2360.21
  4985.0 2360.71  4985.9 2363.34  4990.7 2363.34  4996.6 2362.00  5010.9 2362.88
  5017.5 2362.29  5207.9 2364.73  5489.8 2370.65  5676.9 2374.42  5705.2 2374.14
  5783.1 2375.52  5836.9 2377.37  5867.7 2376.74  6123.1 2378.21  6144.7 2379.15
  6181.2 2378.49  6294.0 2379.00  6355.3 2379.28  6385.3 2380.59  6400.0 2380.11
#Mann=8,-1,0
  3763.4    0.07       0  4968.8    0.07       0  4985.0    0.07       0
  5207.9   0.045       0  5489.8    0.07       0  5783.1   0.045       0
  6144.7    0.07       0  6294.0   0.045       0
Bank Sta=4968.8,4985
Exp/Cntr=0.3,0.1

Chan Stop Cuts=-1