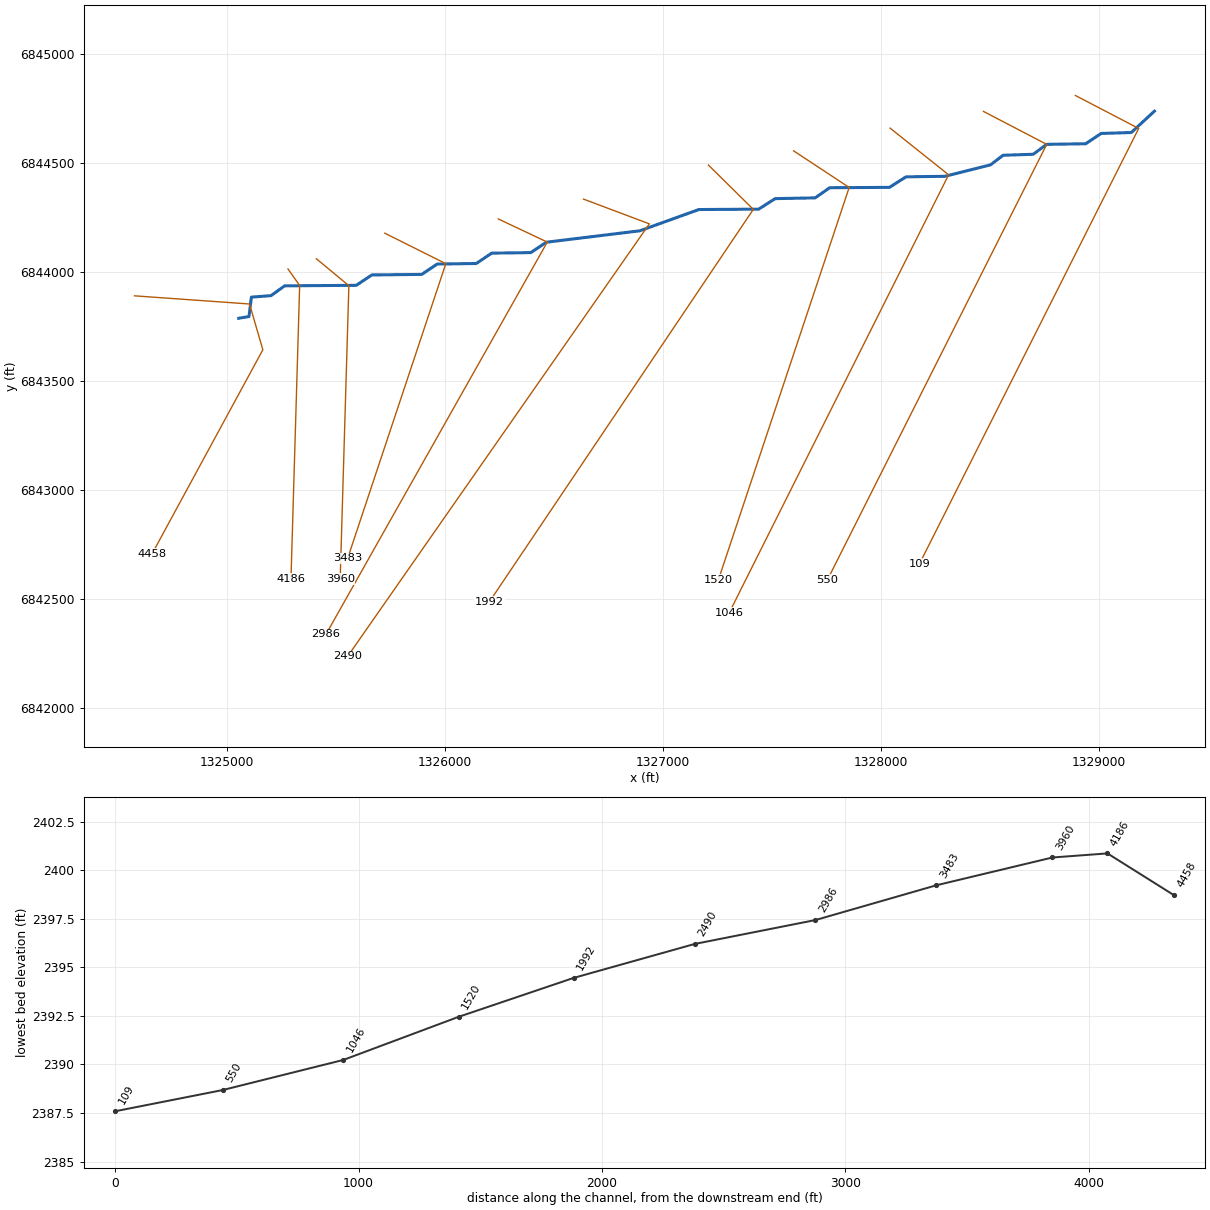
--- Cottonwood Creek Trib030_1.prj (project) ---

Proj Title=Cottonwood Creek Trib030_1 Base Level Engineering
Current Plan=p01
Default Exp/Contr=0.3,0.1
English Units
Geom File=g01
Flow File=f01
Plan File=p01
BEGIN DESCRIPTION:
Cottonwood Creek Trib030_1
END DESCRIPTION:

--- Cottonwood Creek Trib030_1.p01 (plan) ---

Plan Title=Multiple Run
Short Identifier=Multiple
Geom File=g01
Flow File=f01
Subcritical Flow
K Sum by GR= 0
Std Step Tol= 0.01
Critical Tol= 0.01
Num of Std Step Trials= 20
Max Error Tol= 0.3
Flow Tol Ratio= 0.001
Split Flow NTrial= 30
Split Flow Tol= 0.02
Split Flow Ratio= 0.02
Log Output Level= 0
Friction Slope Method= 1
Unsteady Friction Slope Method= 2
Unsteady Bridges Friction Slope Method= 1
Parabolic Critical Depth
Global Vel Dist=  1 , 1 , 1
Global Log Level= 0
CheckData=True
Encroach Param= -1, 0, 0, 0
BEGIN DESCRIPTION:
Multiple Run
END DESCRIPTION:

--- Cottonwood Creek Trib030_1.f01 (steady flow) ---

Flow Title=Multiple
Number of Profiles=7
Profile Names=10-year,25-year,50-year,1pct_min,100-year,1pct_plu,500-year
River Rch & RM= Cottonwood Creek,Reach-1,4458
     214     298     368     226     450     898     684
River Rch & RM= Cottonwood Creek,Reach-1,2986
     279     394     490     303     604    1206     932
Boundary for River Rch & Prof#=Cottonwood Creek,Reach-1,1
Up Type=0
Dn Type=3
Dn Slope=0.005
Boundary for River Rch & Prof#=Cottonwood Creek,Reach-1,2
Up Type=0
Dn Type=3
Dn Slope=0.005
Boundary for River Rch & Prof#=Cottonwood Creek,Reach-1,3
Up Type=0
Dn Type=3
Dn Slope=0.005
Boundary for River Rch & Prof#=Cottonwood Creek,Reach-1,4
Up Type=0
Dn Type=3
Dn Slope=0.005
Boundary for River Rch & Prof#=Cottonwood Creek,Reach-1,5
Up Type=0
Dn Type=3
Dn Slope=0.005
Boundary for River Rch & Prof#=Cottonwood Creek,Reach-1,6
Up Type=0
Dn Type=3
Dn Slope=0.005
Boundary for River Rch & Prof#=Cottonwood Creek,Reach-1,7
Up Type=0
Dn Type=3
Dn Slope=0.005

--- Cottonwood Creek Trib030_1.g01 (geometry) ---

Geom Title=Existing Conditions

River Reach=Cottonwood Creek,Reach-1
Reach XY= 30
      1325055.00      6843788.00      1325102.10      6843795.90
      1325112.97      6843884.98      1325203.32      6843891.89
      1325265.50      6843936.78      1325594.50      6843939.22
      1325665.50      6843986.78      1325894.50      6843989.22
      1325965.51      6844036.78      1326144.49      6844039.22
      1326215.51      6844086.78      1326394.49      6844089.22
      1326465.51      6844136.78      1326894.49      6844189.22
      1327165.50      6844286.78      1327439.78      6844288.52
      1327515.51      6844336.78      1327699.06      6844340.26
      1327765.50      6844386.78      1328039.78      6844388.52
      1328115.51      6844436.78      1328294.49      6844439.22
      1328503.43      6844491.79      1328560.94      6844535.73
      1328699.06      6844540.27      1328760.94      6844585.74
      1328939.78      6844588.52      1329010.94      6844635.73
      1329149.16      6844640.03      1329255.00      6844738.00

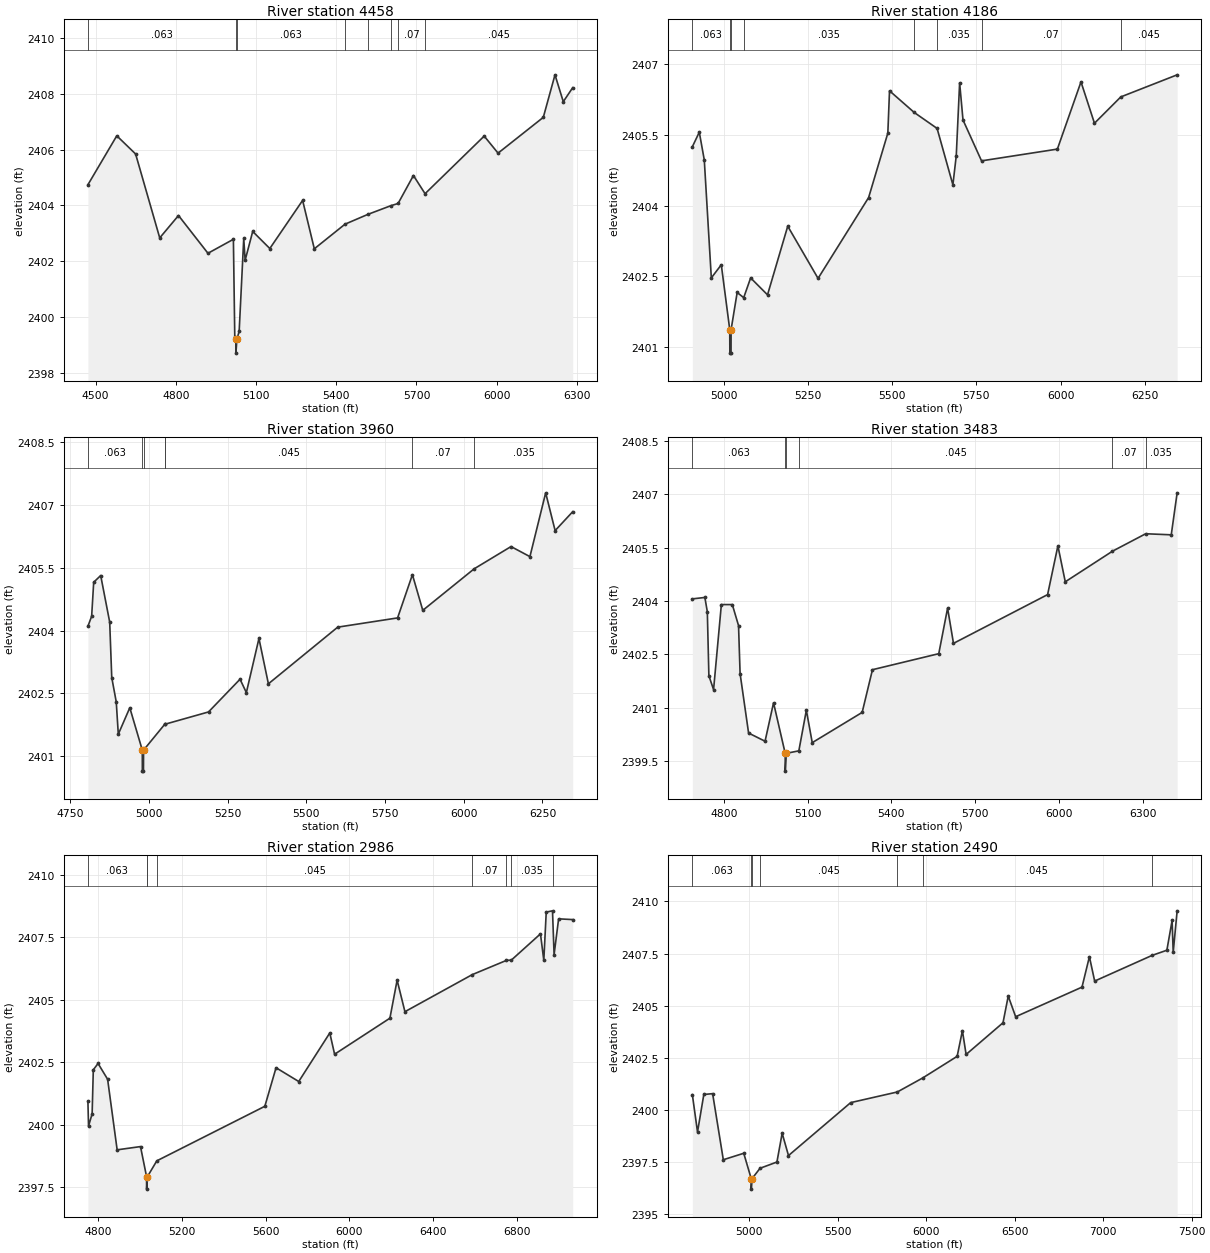
Type RM Length L Ch R = 1,4458,272,272,272
BEGIN DESCRIPTION:
Cottonwood Creek Trib030_1 9.0
END DESCRIPTION:
XS GIS Cut Line= 4
      1324577.10      6843890.99      1325104.47      6843853.52
      1325165.65      6843643.60      1324657.19      6842707.08
#Sta/Elev= 30
  4471.3 2404.74  4579.3 2406.49  4649.7 2405.84  4739.9 2402.84  4810.1 2403.64
  4920.3 2402.29  5015.4 2402.79  5020.6 2399.28  5024.6 2399.22  5024.8 2398.72
  5028.6 2399.22  5037.0 2399.50  5054.1 2402.82  5059.3 2402.04  5087.6 2403.07
  5151.6 2402.46  5274.3 2404.18  5318.0 2402.45  5432.8 2403.33  5518.2 2403.68
  5603.9 2403.99  5631.3 2404.07  5688.7 2405.07  5732.2 2404.42  5953.3 2406.48
  6005.2 2405.87  6174.4 2407.15  6218.1 2408.67  6249.1 2407.71  6284.3 2408.21
#Mann=8,-1,0
  4471.3   0.063       0  5024.6   0.063       0  5028.6   0.063       0
  5432.8   0.045       0  5518.2    0.07       0  5603.9   0.045       0
  5631.3    0.07       0  5732.2   0.045       0
Bank Sta=5024.6,5028.6
Exp/Cntr=0.3,0.1

Type RM Length L Ch R = 1,4186,226,226,226
BEGIN DESCRIPTION:
Cottonwood Creek Trib030_1 8.5
END DESCRIPTION:
XS GIS Cut Line= 3
      1325281.01      6844014.00      1325334.49      6843938.43
      1325294.65      6842592.69
#Sta/Elev= 30
  4907.2 2405.25  4927.8 2405.56  4942.6 2404.97  4963.5 2402.46  4993.1 2402.74
  5018.2 2401.36  5018.5 2400.86  5022.0 2400.86  5022.2 2401.36  5040.2 2402.15
  5059.6 2402.04  5080.2 2402.46  5130.3 2402.10  5190.3 2403.56  5280.3 2402.45
  5430.4 2404.17  5487.4 2405.54  5492.4 2406.44  5565.6 2405.98  5633.6 2405.64
  5680.5 2404.44  5690.5 2405.06  5700.5 2406.61  5710.5 2405.82  5765.5 2404.95
  5990.6 2405.20  6060.7 2406.63  6100.7 2405.75  6178.8 2406.31  6346.1 2406.78
#Mann=8,-1,0
  4907.2   0.063       0  5018.2   0.063       0  5022.2   0.063       0
  5059.6   0.035       0  5565.6   0.063       0  5633.6   0.035       0
  5765.5    0.07       0  6178.8   0.045       0
Bank Sta=5018.2,5022.2
Exp/Cntr=0.3,0.1

Type RM Length L Ch R = 1,3960,477,477,477
BEGIN DESCRIPTION:
Cottonwood Creek Trib030_1 8.0
END DESCRIPTION:
XS GIS Cut Line= 3
      1325411.21      6844060.90      1325560.18      6843937.56
      1325520.36      6842592.25
#Sta/Elev= 30
  4806.6 2404.10  4818.5 2404.34  4825.0 2405.15  4847.2 2405.31  4875.8 2404.20
  4882.3 2402.88  4896.6 2402.30  4903.1 2401.53  4939.6 2402.16  4979.3 2401.15
  4979.5 2400.65  4983.0 2400.65  4983.3 2401.15  5052.1 2401.78  5052.6 2401.77
  5189.6 2402.06  5289.7 2402.84  5309.7 2402.52  5349.7 2403.81  5379.7 2402.73
  5599.8 2404.08  5789.9 2404.30  5837.0 2405.33  5869.9 2404.48  6033.1 2405.47
  6150.1 2406.00  6210.1 2405.76  6260.1 2407.28  6290.1 2406.38  6345.9 2406.83
#Mann=7,-1,0
  4806.6   0.063       0  4979.3   0.063       0  4983.3   0.063       0
  5052.1   0.035       0  5052.6   0.045       0  5837.0    0.07       0
  6033.1   0.035       0
Bank Sta=4979.3,4983.3
Exp/Cntr=0.3,0.1

Type RM Length L Ch R = 1,3483,497,497,497
BEGIN DESCRIPTION:
Cottonwood Creek Trib030_1 7.0
END DESCRIPTION:
XS GIS Cut Line= 3
      1325724.90      6844178.42      1326004.83      6844038.40
      1325554.98      6842687.95
#Sta/Elev= 30
  4687.0 2404.06  4731.8 2404.10  4740.6 2403.70  4746.2 2401.90  4763.0 2401.51
  4790.9 2403.90  4830.1 2403.90  4852.4 2403.31  4858.0 2401.96  4888.4 2400.29
  4947.4 2400.06  4977.8 2401.14  5019.5 2399.72  5019.8 2399.22  5023.5 2399.72
  5068.4 2399.79  5095.3 2400.93  5116.4 2400.02  5295.2 2400.87  5332.1 2402.07
  5569.6 2402.52  5601.2 2403.80  5622.3 2402.81  5959.4 2404.18  5996.3 2405.55
  6022.7 2404.54  6191.8 2405.40  6310.8 2405.89  6402.3 2405.86  6423.4 2407.04
#Mann=6,-1,0
  4687.0   0.063       0  5019.5   0.063       0  5023.5   0.063       0
  5068.4   0.045       0  6191.8    0.07       0  6310.8   0.035       0
Bank Sta=5019.5,5023.5
Exp/Cntr=0.3,0.1

Type RM Length L Ch R = 1,2986,496,496,496
BEGIN DESCRIPTION:
Cottonwood Creek Trib030_1 6.0
END DESCRIPTION:
XS GIS Cut Line= 3
      1326245.71      6844243.54      1326470.22      6844137.48
      1325455.00      6842338.00
#Sta/Elev= 30
  4751.7 2400.95  4754.7 2399.95  4771.9 2400.44  4777.5 2402.20  4800.2 2402.45
  4845.8 2401.82  4891.3 2399.00  5002.8 2399.13  5031.7 2397.93  5032.0 2397.43
  5035.9 2397.93  5080.6 2398.56  5596.4 2400.74  5649.9 2402.28  5758.2 2401.73
  5906.5 2403.67  5929.4 2402.82  6193.5 2404.26  6227.9 2405.78  6265.2 2404.52
  6586.4 2406.00  6749.9 2406.57  6773.1 2406.58  6912.3 2407.63  6928.2 2406.57
  6939.8 2408.50  6969.7 2408.55  6977.3 2406.80  6998.9 2408.23  7066.1 2408.20
#Mann=8,-1,0
  4751.7   0.063       0  5031.7   0.063       0  5035.9   0.063       0
  5080.6   0.045       0  6586.4    0.07       0  6749.9   0.045       0
  6773.1   0.035       0  6969.7    0.07       0
Bank Sta=5031.7,5035.9
Exp/Cntr=0.3,0.1

Type RM Length L Ch R = 1,2490,498,498,498
BEGIN DESCRIPTION:
Cottonwood Creek Trib030_1 5.0
END DESCRIPTION:
XS GIS Cut Line= 3
      1326636.37      6844334.67      1326938.43      6844221.10
      1325554.98      6842237.98
#Sta/Elev= 30
  4677.3 2400.73  4706.5 2398.94  4742.1 2400.74  4791.9 2400.78  4852.3 2397.61
  4967.9 2397.92  5010.1 2396.70  5010.4 2396.20  5014.5 2396.70  5059.9 2397.20
  5155.4 2397.50  5185.0 2398.88  5220.8 2397.81  5572.4 2400.35  5836.0 2400.86
  5979.0 2401.53  6174.3 2402.57  6204.0 2403.80  6224.9 2402.66  6433.5 2404.18
  6463.1 2405.46  6505.0 2404.47  6880.1 2405.89  6922.0 2407.35  6951.7 2406.18
  7275.7 2407.41  7359.9 2407.66  7389.6 2409.09  7395.7 2407.56  7418.0 2409.55
#Mann=7,-1,0
  4677.3   0.063       0  5010.1   0.063       0  5014.5   0.063       0
  5059.9   0.045       0  5836.0    0.07       0  5979.0   0.045       0
  7275.7   0.035       0
Bank Sta=5010.1,5014.5
Exp/Cntr=0.3,0.1

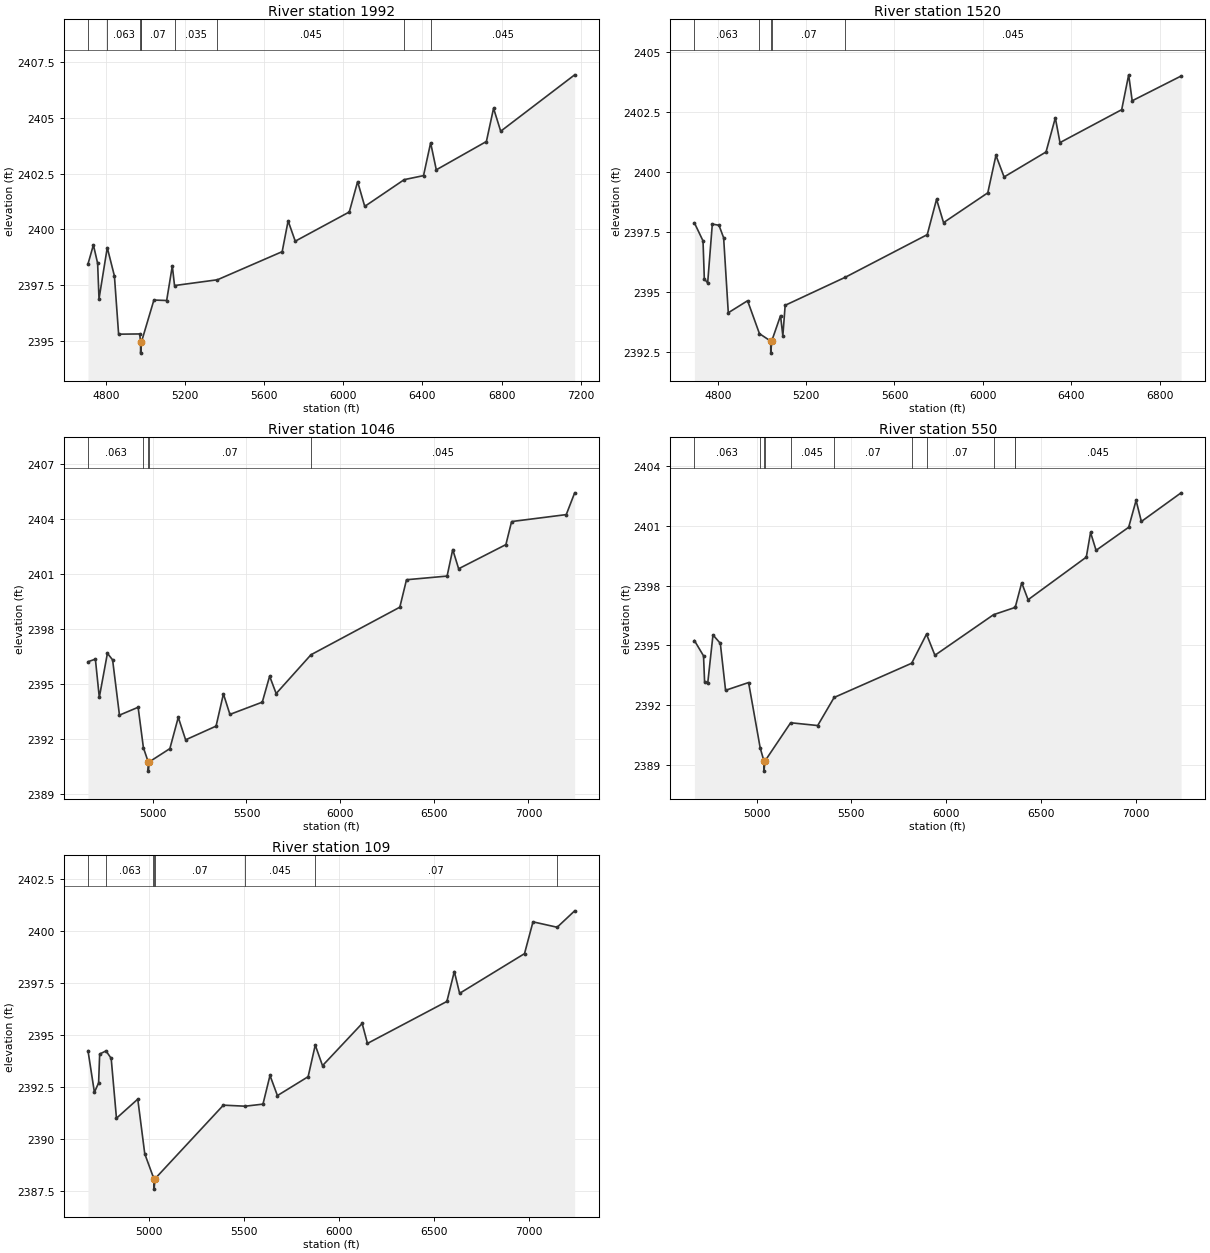
Type RM Length L Ch R = 1,1992,472,472,472
BEGIN DESCRIPTION:
Cottonwood Creek Trib030_1 4.0
END DESCRIPTION:
XS GIS Cut Line= 3
      1327209.28      6844490.91      1327415.19      6844287.55
      1326205.01      6842488.02
#Sta/Elev= 30
  4710.6 2398.45  4737.9 2399.30  4759.2 2398.48  4766.2 2396.88  4807.9 2399.18
  4844.0 2397.91  4865.2 2395.30  4971.7 2395.31  4976.1 2394.95  4976.4 2394.45
  4980.5 2394.95  5043.4 2396.83  5107.9 2396.81  5136.4 2398.36  5147.6 2397.48
  5364.4 2397.74  5691.3 2399.00  5721.3 2400.38  5757.3 2399.47  6030.3 2400.78
  6072.3 2402.14  6108.3 2401.03  6307.7 2402.23  6405.2 2402.41  6441.1 2403.88
  6469.7 2402.67  6722.7 2403.94  6758.9 2405.43  6795.0 2404.40  7168.6 2406.93
#Mann=9,-1,0
  4710.6   0.094       0  4807.9   0.063       0  4971.7    0.07       0
  4976.1    0.07       0  4980.5    0.07       0  5147.6   0.035       0
  5364.4   0.045       0  6307.7    0.07       0  6441.1   0.045       0
Bank Sta=4976.1,4980.5
Exp/Cntr=0.3,0.1

Type RM Length L Ch R = 1,1520,474,474,474
BEGIN DESCRIPTION:
Cottonwood Creek Trib030_1 3.0
END DESCRIPTION:
XS GIS Cut Line= 3
      1327599.90      6844556.03      1327854.97      6844388.08
      1327255.01      6842588.03
#Sta/Elev= 30
  4694.6 2397.87  4733.6 2397.12  4739.5 2395.54  4754.6 2395.37  4775.7 2397.82
  4805.8 2397.77  4826.9 2397.25  4848.0 2394.13  4935.3 2394.63  4989.0 2393.26
  5040.0 2392.95  5040.3 2392.45  5044.4 2392.95  5084.4 2394.01  5094.9 2393.17
  5105.4 2394.44  5378.2 2395.61  5748.5 2397.38  5790.6 2398.85  5822.3 2397.88
  6022.5 2399.12  6059.4 2400.68  6096.3 2399.78  6286.1 2400.82  6328.2 2402.24
  6349.3 2401.21  6628.6 2402.58  6660.2 2404.03  6676.1 2402.95  6897.4 2403.98
#Mann=5,-1,0
  4694.6   0.063       0  4989.0    0.07       0  5040.0    0.07       0
  5044.4    0.07       0  5378.2   0.045       0
Bank Sta=5040,5044.4
Exp/Cntr=0.3,0.1

Type RM Length L Ch R = 1,1046,496,496,496
BEGIN DESCRIPTION:
Cottonwood Creek Trib030_1 2.0
END DESCRIPTION:
XS GIS Cut Line= 3
      1328042.64      6844660.17      1328311.06      6844446.14
      1327304.98      6842437.96
#Sta/Elev= 30
  4656.7 2396.21  4696.0 2396.35  4716.8 2394.26  4760.0 2396.67  4787.6 2396.31
  4824.1 2393.29  4923.4 2393.72  4951.5 2391.51  4977.2 2390.73  4977.5 2390.23
  4981.8 2390.73  5092.3 2391.46  5137.0 2393.17  5176.1 2391.94  5338.1 2392.69
  5377.2 2394.45  5411.8 2393.33  5584.0 2394.00  5623.1 2395.42  5657.8 2394.47
  5843.0 2396.59  6315.8 2399.19  6351.3 2400.69  6567.3 2400.89  6597.3 2402.34
  6628.7 2401.29  6880.1 2402.61  6910.5 2403.87  7201.3 2404.25  7246.1 2405.44
#Mann=5,-1,0
  4656.7   0.063       0  4951.5    0.07       0  4977.2    0.07       0
  4981.8    0.07       0  5843.0   0.045       0
Bank Sta=4977.2,4981.8
Exp/Cntr=0.3,0.1

Type RM Length L Ch R = 1,550,441,441,441
BEGIN DESCRIPTION:
Cottonwood Creek Trib030_1 1.0
END DESCRIPTION:
XS GIS Cut Line= 3
      1328470.67      6844736.97      1328760.94      6844585.74
      1327755.00      6842588.01
#Sta/Elev= 30
  4672.7 2395.24  4720.8 2394.47  4726.4 2393.16  4742.9 2393.10  4770.6 2395.52
  4809.2 2395.10  4836.9 2392.74  4958.2 2393.13  5019.2 2389.85  5039.3 2389.18
  5039.6 2388.68  5043.9 2389.18  5179.8 2391.11  5322.2 2390.97  5408.8 2392.38
  5817.4 2394.10  5895.5 2395.56  5939.8 2394.50  6249.0 2396.54  6361.3 2396.90
  6363.0 2396.91  6397.0 2398.14  6430.7 2397.29  6737.4 2399.43  6759.8 2400.67
  6788.9 2399.77  6960.6 2400.93  6999.6 2402.28  7027.5 2401.22  7236.7 2402.66
#Mann=11,-1,0
  4672.7   0.063       0  5019.2    0.07       0  5039.3   0.063       0
  5043.9    0.07       0  5179.8   0.045       0  5408.8    0.07       0
  5817.4   0.045       0  5895.5    0.07       0  6249.0   0.045       0
  6361.3    0.07       0  6363.0   0.045       0
Bank Sta=5039.3,5043.9
Exp/Cntr=0.3,0.1

Type RM Length L Ch R = 1,109,0,0,0
BEGIN DESCRIPTION:
Cottonwood Creek Trib030_1 0.5
END DESCRIPTION:
XS GIS Cut Line= 3
      1328892.55      6844809.88      1329182.81      6844658.65
      1328177.42      6842661.99
#Sta/Elev= 30
  4677.4 2394.25  4711.1 2392.25  4733.2 2392.70  4738.9 2394.09  4772.3 2394.24
  4799.5 2393.88  4827.3 2391.00  4939.5 2391.92  4976.3 2389.29  5020.7 2388.18
  5025.1 2388.09  5025.5 2387.59  5030.3 2388.09  5390.3 2391.63  5505.2 2391.58
  5598.8 2391.68  5635.8 2393.06  5674.8 2392.09  5836.6 2393.00  5874.1 2394.52
  5912.3 2393.53  6121.1 2395.56  6149.0 2394.60  6567.3 2396.62  6606.4 2398.06
  6634.3 2397.01  6976.0 2398.92  7020.7 2400.45  7148.0 2400.19  7240.2 2400.98
#Mann=8,-1,0
  4677.4   0.094       0  4772.3   0.063       0  5020.7    0.07       0
  5025.1   0.063       0  5030.3    0.07       0  5505.2   0.045       0
  5874.1    0.07       0  7148.0   0.045       0
Bank Sta=5025.1,5030.3
Exp/Cntr=0.3,0.1

Chan Stop Cuts=-1