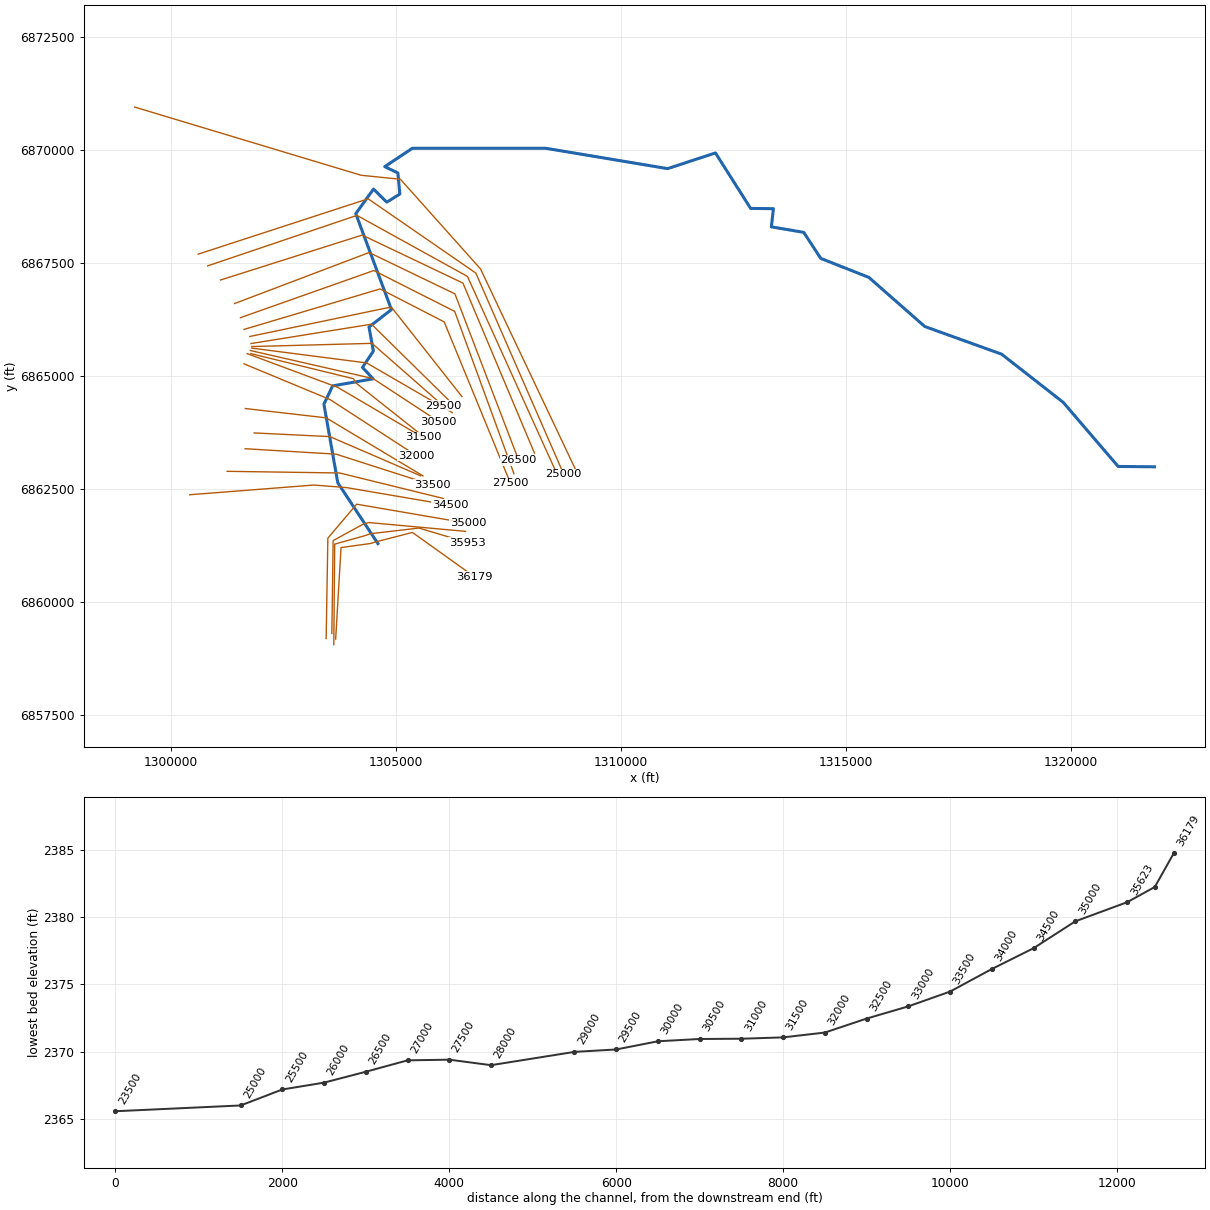
--- Cottonwood Creek Trib034.prj (project) ---

Proj Title=Cottonwood Creek Trib034 Base Level Engineering
Current Plan=p01
Default Exp/Contr=0.3,0.1
English Units
Geom File=g01
Flow File=f01
Plan File=p01
BEGIN DESCRIPTION:
Cottonwood Creek Trib034
END DESCRIPTION:

--- Cottonwood Creek Trib034.p01 (plan) ---

Plan Title=Multiple Run
Short Identifier=Multiple
Geom File=g01
Flow File=f01
Subcritical Flow
K Sum by GR= 0
Std Step Tol= 0.01
Critical Tol= 0.01
Num of Std Step Trials= 20
Max Error Tol= 0.3
Flow Tol Ratio= 0.001
Split Flow NTrial= 30
Split Flow Tol= 0.02
Split Flow Ratio= 0.02
Log Output Level= 0
Friction Slope Method= 1
Unsteady Friction Slope Method= 2
Unsteady Bridges Friction Slope Method= 1
Parabolic Critical Depth
Global Vel Dist=  1 , 1 , 1
Global Log Level= 0
CheckData=True
Encroach Param= -1, 0, 0, 0
BEGIN DESCRIPTION:
Multiple Run
END DESCRIPTION:

--- Cottonwood Creek Trib034.f01 (steady flow) ---

Flow Title=Multiple
Number of Profiles=7
Profile Names=10-year,25-year,50-year,1pct_min,100-year,1pct_plu,500-year
River Rch & RM= Cottonwood Creek,Reach-1,36179
     197     271     331     201     401     801     597
River Rch & RM= Cottonwood Creek,Reach-1,33500
     273     381     469     287     573    1143     864
River Rch & RM= Cottonwood Creek,Reach-1,27500
     310     435     538     330     658    1312     999
River Rch & RM= Cottonwood Creek,Reach-1,26000
     383     541     673     414     827    1650    1267
River Rch & RM= Cottonwood Creek,Reach-1,22500
     620     894    1126     701    1399    2791    2193
River Rch & RM= Cottonwood Creek,Reach-1,15500
     723    1045    1319     823    1642    3275    2582
River Rch & RM= Cottonwood Creek,Reach-1,11000
     741    1070    1349     840    1676    3345    2629
River Rch & RM= Cottonwood Creek,Reach-1,7500
     774    1120    1413     881    1758    3507    2762
River Rch & RM= Cottonwood Creek,Reach-1,6500
     805    1166    1472     918    1832    3655    2881
River Rch & RM= Cottonwood Creek,Reach-1,5500
     842    1221    1543     964    1923    3836    3028
River Rch & RM= Cottonwood Creek,Reach-1,5000
     897    1305    1653    1034    2063    4115    3262
River Rch & RM= Cottonwood Creek,Reach-1,2500
     940    1371    1740    1091    2177    4343    3456
Boundary for River Rch & Prof#=Cottonwood Creek,Reach-1,1
Up Type=0
Dn Type=3
Dn Slope=0.005
Boundary for River Rch & Prof#=Cottonwood Creek,Reach-1,2
Up Type=0
Dn Type=3
Dn Slope=0.005
Boundary for River Rch & Prof#=Cottonwood Creek,Reach-1,3
Up Type=0
Dn Type=3
Dn Slope=0.005
Boundary for River Rch & Prof#=Cottonwood Creek,Reach-1,4
Up Type=0
Dn Type=3
Dn Slope=0.005
Boundary for River Rch & Prof#=Cottonwood Creek,Reach-1,5
Up Type=0
Dn Type=3
Dn Slope=0.005
Boundary for River Rch & Prof#=Cottonwood Creek,Reach-1,6
Up Type=0
Dn Type=3
Dn Slope=0.005
Boundary for River Rch & Prof#=Cottonwood Creek,Reach-1,7
Up Type=0
Dn Type=3
Dn Slope=0.005

--- Cottonwood Creek Trib034.g01 (geometry) ---

Geom Title=Existing Conditions

River Reach=Cottonwood Creek,Reach-1
Reach XY= 30
      1304605.00      6861288.00      1303712.98      6862634.65
      1303405.33      6864372.97      1303597.98      6864778.97
      1304497.49      6864934.82      1304262.08      6865188.00
      1304503.80      6865548.51      1304406.63      6866081.96
      1304905.47      6866467.85      1304113.02      6868591.31
      1304506.17      6869134.88      1304801.31      6868845.65
      1305091.61      6869024.67      1305049.17      6869490.84
      1304756.73      6869631.84      1305370.09      6870037.81
      1308334.97      6870037.93      1311039.82      6869587.57
      1312102.99      6869935.05      1312884.61      6868707.05
      1313391.47      6868701.38      1313344.62      6868298.80
      1314065.00      6868177.05      1314441.32      6867601.50
      1315511.19      6867180.19      1316752.55      6866093.47
      1318461.06      6865480.52      1319828.47      6864414.99
      1321048.81      6862995.85      1321855.00      6862988.00

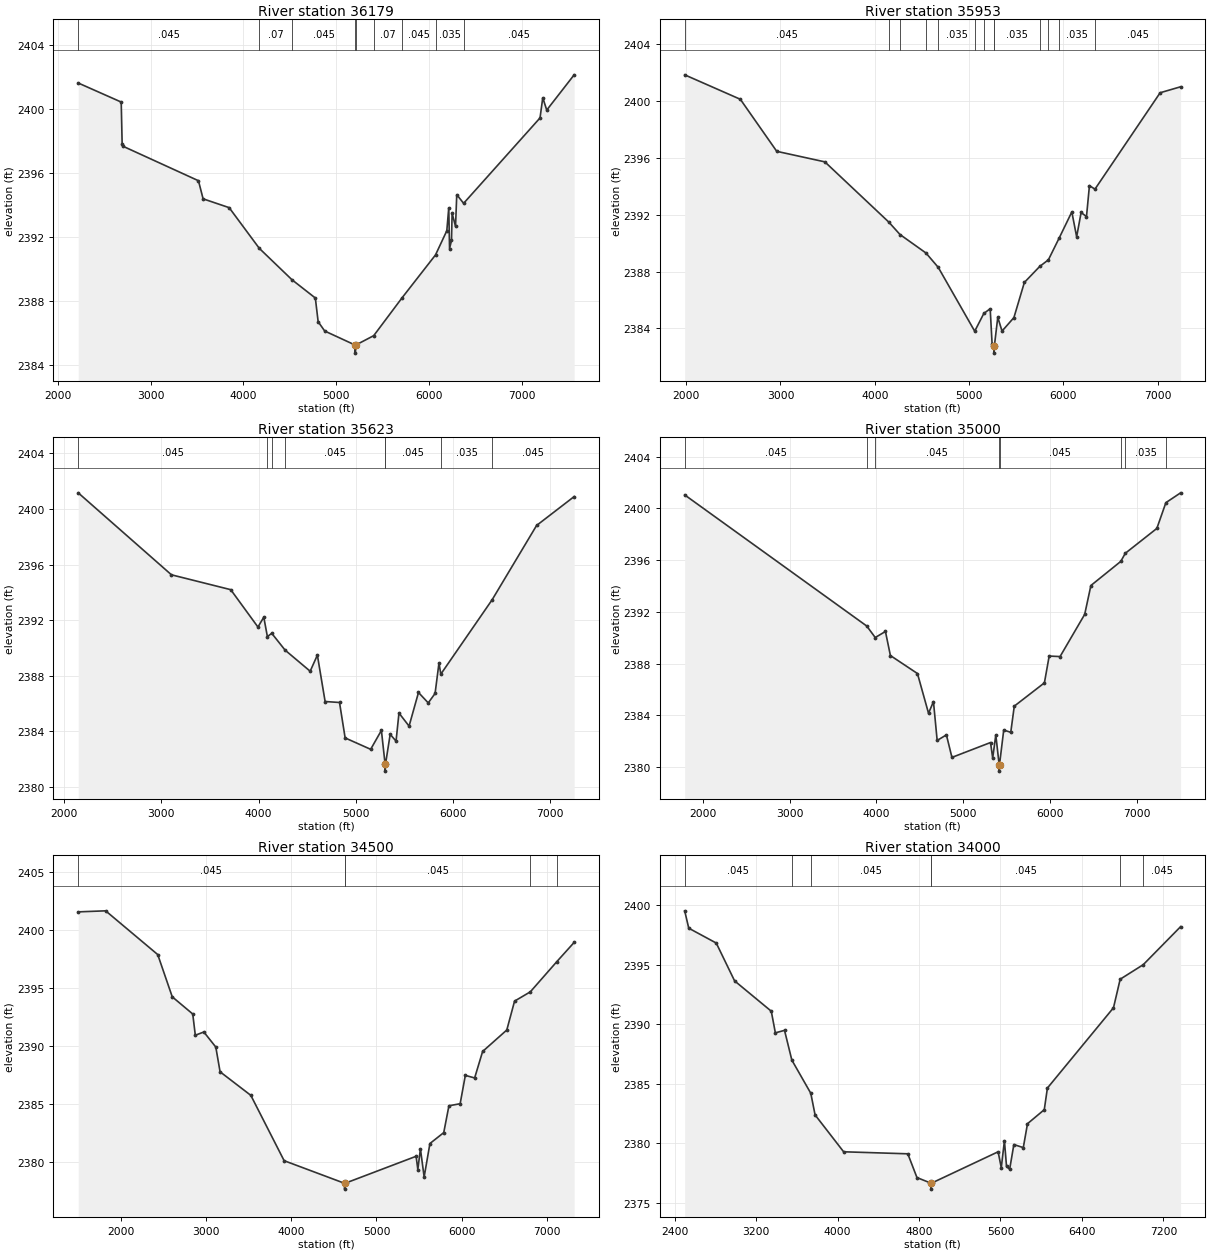
Type RM Length L Ch R = 1,36179,226,226,226
BEGIN DESCRIPTION:
Cottonwood Creek Trib034 71.0
END DESCRIPTION:
XS GIS Cut Line= 6
      1303666.24      6859175.94      1303785.60      6861200.68
      1304434.47      6861289.66      1304586.38      6861333.06
      1305370.52      6861535.61      1306745.43      6860557.33
#Sta/Elev= 30
  2221.0 2401.62  2683.9 2400.43  2693.9 2397.82  2703.9 2397.67  3515.3 2395.52
  3565.4 2394.39  3845.9 2393.84  4170.3 2391.30  4522.0 2389.34  4773.5 2388.20
  4803.8 2386.72  4874.5 2386.14  5203.4 2385.26  5203.6 2384.76  5207.4 2385.26
  5401.9 2385.85  5708.0 2388.22  6067.2 2390.89  6188.8 2392.40  6209.7 2393.83
  6218.3 2391.29  6239.2 2391.79  6245.8 2393.49  6282.6 2392.67  6295.8 2394.65
  6369.7 2394.11  7192.2 2399.44  7221.7 2400.70  7264.4 2399.93  7559.5 2402.13
#Mann=9,-1,0
  2221.0   0.045       0  4170.3    0.07       0  4522.0   0.045       0
  5203.4   0.045       0  5207.4   0.045       0  5401.9    0.07       0
  5708.0   0.045       0  6067.2   0.035       0  6369.7   0.045       0
Bank Sta=5203.4,5207.4
Exp/Cntr=0.3,0.1

Type RM Length L Ch R = 1,35953,330,330,330
BEGIN DESCRIPTION:
Cottonwood Creek Trib034 70.0
END DESCRIPTION:
XS GIS Cut Line= 6
      1303624.76      6859051.63      1303644.54      6861276.64
      1304296.67      6861458.29      1304443.26      6861507.15
      1305515.20      6861632.54      1306591.72      6861312.18
#Sta/Elev= 30
  1984.6 2401.83  2574.9 2400.11  2961.0 2396.45  3471.0 2395.71  4148.3 2391.48
  4267.9 2390.60  4543.4 2389.30  4673.5 2388.29  5060.2 2383.80  5156.8 2385.05
  5224.2 2385.38  5244.3 2382.93  5264.6 2382.76  5264.8 2382.26  5268.6 2382.76
  5304.7 2384.78  5349.9 2383.81  5475.9 2384.76  5586.6 2387.23  5750.2 2388.36
  5841.4 2388.82  5957.7 2390.38  6090.0 2392.19  6141.1 2390.44  6188.5 2392.15
  6245.4 2391.86  6276.7 2394.04  6335.2 2393.79  7026.5 2400.57  7243.6 2400.99
#Mann=13,-1,0
  1984.6   0.045       0  4148.3    0.07       0  4267.9   0.035       0
  4543.4    0.07       0  4673.5   0.035       0  5060.2   0.045       0
  5156.8   0.035       0  5264.6   0.035       0  5268.6   0.035       0
  5750.2    0.07       0  5841.4   0.045       0  5957.7   0.035       0
  6335.2   0.045       0
Bank Sta=5264.6,5268.6
Exp/Cntr=0.3,0.1

Type RM Length L Ch R = 1,35623,623,623,623
BEGIN DESCRIPTION:
Cottonwood Creek Trib034 69.5
END DESCRIPTION:
XS GIS Cut Line= 5
      1303581.36      6859299.03      1303609.82      6861354.76
      1304253.26      6861705.68      1304399.86      6861754.55
      1306549.92      6861559.09
#Sta/Elev= 30
  2144.4 2401.16  3103.5 2395.26  3713.5 2394.19  3993.6 2391.50  4053.6 2392.21
  4090.7 2390.81  4135.3 2391.05  4272.7 2389.84  4530.8 2388.32  4604.9 2389.48
  4684.6 2386.14  4832.7 2386.07  4890.6 2383.52  5153.2 2382.70  5263.6 2384.06
  5301.8 2381.63  5302.1 2381.13  5305.8 2381.63  5354.0 2383.78  5414.3 2383.29
  5444.4 2385.31  5548.3 2384.37  5645.2 2386.79  5745.6 2386.04  5815.9 2386.72
  5856.1 2388.92  5874.9 2388.11  6403.5 2393.47  6860.2 2398.81  7246.7 2400.89
#Mann=8,-1,0
  2144.4   0.045       0  4090.7    0.07       0  4135.3   0.035       0
  4272.7   0.045       0  5301.8   0.045       0  5305.8   0.045       0
  5874.9   0.035       0  6403.5   0.045       0
Bank Sta=5301.8,5305.8
Exp/Cntr=0.3,0.1

Type RM Length L Ch R = 1,35000,500,500,500
BEGIN DESCRIPTION:
Cottonwood Creek Trib034 69.0
END DESCRIPTION:
XS GIS Cut Line= 4
      1303455.00      6859187.98      1303492.63      6861409.02
      1304132.43      6862160.62      1306604.97      6861738.01
#Sta/Elev= 30
  1791.6 2401.04  3890.3 2390.91  3988.3 2390.02  4105.8 2390.49  4162.9 2388.63
  4474.8 2387.24  4602.6 2384.17  4659.3 2385.07  4702.1 2382.07  4808.6 2382.50
  4872.3 2380.76  5317.1 2381.91  5342.2 2380.71  5378.0 2382.50  5416.6 2380.20
  5416.8 2379.70  5420.6 2380.20  5469.3 2382.87  5550.4 2382.70  5591.0 2384.72
  5938.3 2386.52  5993.3 2388.59  6118.6 2388.55  6402.6 2391.81  6474.2 2394.04
  6818.2 2395.90  6870.8 2396.53  7234.5 2398.45  7338.4 2400.44  7508.4 2401.20
#Mann=8,-1,0
  1791.6   0.045       0  3890.3   0.035       0  3988.3   0.045       0
  5416.6   0.045       0  5420.6   0.045       0  6818.2    0.07       0
  6870.8   0.035       0  7338.4   0.045       0
Bank Sta=5416.6,5420.6
Exp/Cntr=0.3,0.1

Type RM Length L Ch R = 1,34500,500,500,500
BEGIN DESCRIPTION:
Cottonwood Creek Trib034 68.0
END DESCRIPTION:
XS GIS Cut Line= 4
      1300423.96      6862369.35      1303184.31      6862584.52
      1303916.27      6862526.29      1306204.97      6862138.01
#Sta/Elev= 30
  1497.0 2401.59  1819.0 2401.68  2430.9 2397.91  2601.4 2394.27  2842.1 2392.79
  2872.2 2390.96  2972.5 2391.24  3112.9 2389.94  3163.1 2387.81  3524.2 2385.78
  3915.4 2380.15  4625.6 2378.20  4625.8 2377.70  4629.6 2378.20  5465.3 2380.53
  5485.6 2379.39  5516.0 2381.17  5559.7 2378.75  5627.6 2381.63  5789.9 2382.57
  5850.7 2384.88  5982.6 2385.06  6043.4 2387.50  6152.8 2387.28  6246.3 2389.56
  6530.3 2391.41  6621.6 2393.90  6806.7 2394.70  7118.9 2397.31  7321.4 2398.96
#Mann=5,-1,0
  1497.0   0.045       0  4625.6   0.045       0  4629.6   0.045       0
  6806.7    0.07       0  7118.9   0.045       0
Bank Sta=4625.6,4629.6
Exp/Cntr=0.3,0.1

Type RM Length L Ch R = 1,34000,500,500,500
BEGIN DESCRIPTION:
Cottonwood Creek Trib034 67.0
END DESCRIPTION:
XS GIS Cut Line= 3
      1301255.02      6862888.00      1303754.85      6862851.41
      1306054.95      6862288.01
#Sta/Elev= 30
  2499.9 2399.55  2539.9 2398.09  2809.9 2396.84  2989.9 2393.66  3350.0 2391.11
  3390.0 2389.29  3480.0 2389.50  3551.8 2387.00  3737.8 2384.21  3780.0 2382.39
  4060.1 2379.29  4690.1 2379.12  4780.1 2377.12  4918.1 2376.65  4918.4 2376.15
  4922.1 2376.65  5576.7 2379.29  5607.6 2377.95  5638.5 2380.22  5659.1 2378.07
  5690.0 2377.82  5731.1 2379.90  5823.8 2379.64  5865.0 2381.65  6029.7 2382.83
  6060.6 2384.65  6709.2 2391.40  6774.8 2393.80  7000.9 2395.02  7368.1 2398.22
#Mann=7,-1,0
  2499.9   0.045       0  3551.8    0.07       0  3737.8   0.045       0
  4918.1   0.045       0  4922.1   0.045       0  6774.8    0.07       0
  7000.9   0.045       0
Bank Sta=4918.1,4922.1
Exp/Cntr=0.3,0.1

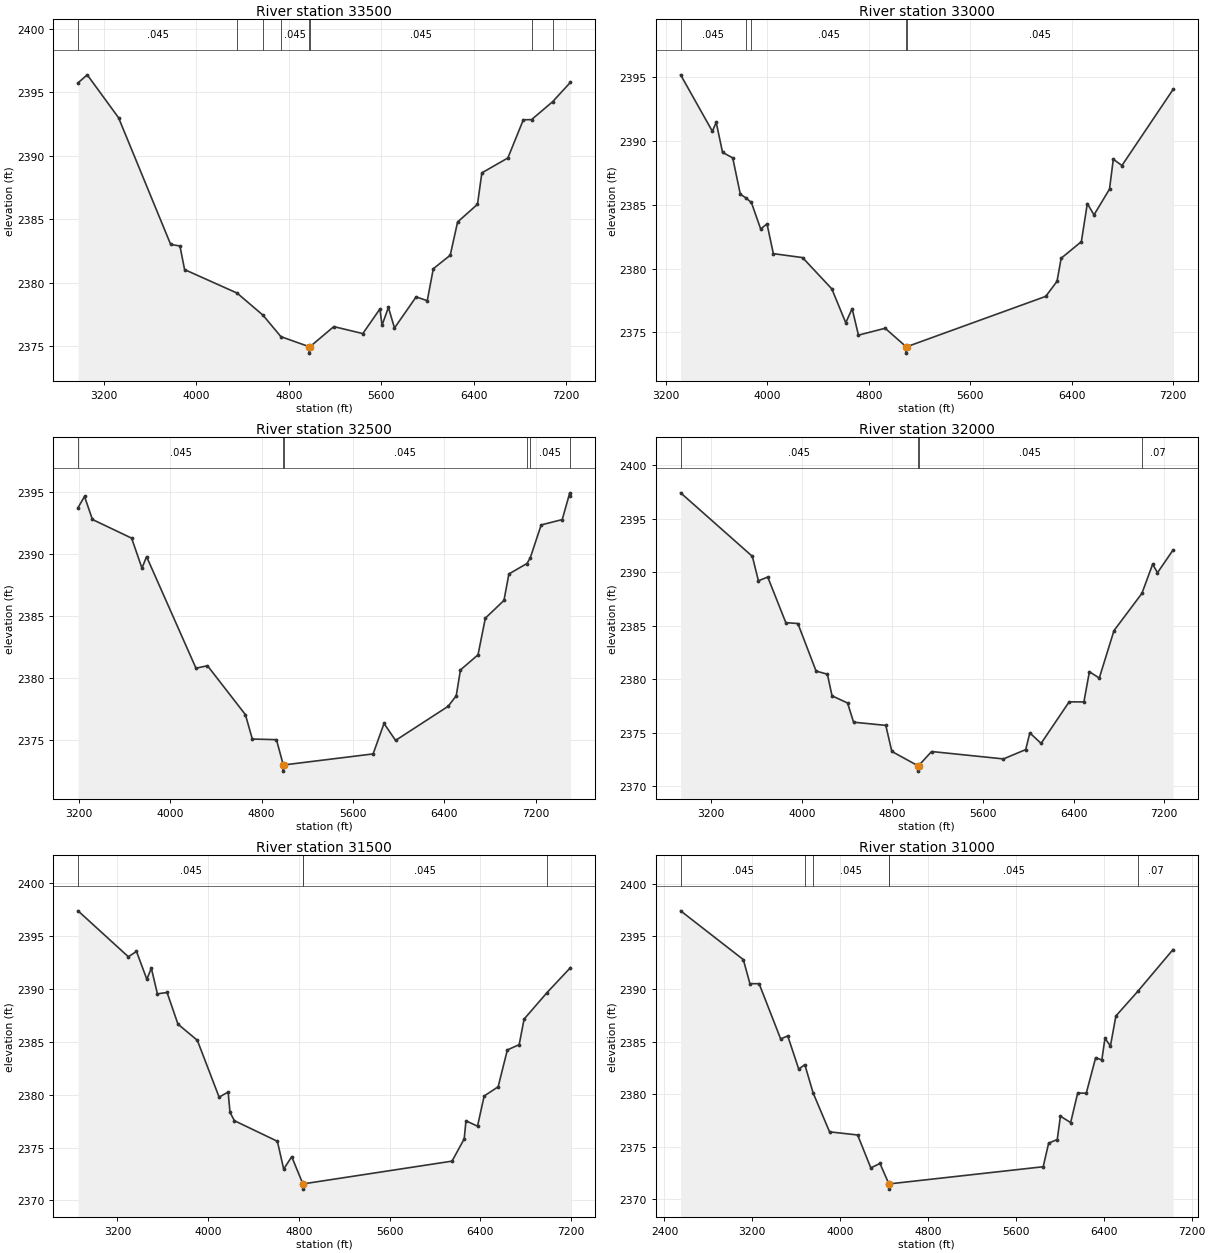
Type RM Length L Ch R = 1,33500,500,500,500
BEGIN DESCRIPTION:
Cottonwood Creek Trib034 66.0
END DESCRIPTION:
XS GIS Cut Line= 3
      1301654.98      6863388.00      1303675.33      6863268.05
      1305804.98      6862588.01
#Sta/Elev= 30
  2976.1 2395.76  3055.9 2396.39  3326.7 2393.01  3777.5 2383.03  3857.7 2382.91
  3897.7 2381.05  4351.9 2379.20  4575.9 2377.46  4730.9 2375.77  4977.4 2374.97
  4977.7 2374.47  4981.8 2374.97  5188.6 2376.56  5439.6 2376.01  5587.5 2377.95
  5605.8 2376.67  5661.0 2378.07  5713.5 2376.45  5900.7 2378.90  5996.9 2378.60
  6049.4 2381.12  6195.6 2382.18  6259.4 2384.80  6431.4 2386.19  6469.3 2388.67
  6694.1 2389.84  6828.1 2392.85  6898.9 2392.86  7081.1 2394.27  7235.6 2395.80
#Mann=8,-1,0
  2976.1   0.045       0  4351.9   0.035       0  4575.9   0.094       0
  4730.9   0.045       0  4977.4   0.045       0  4981.8   0.045       0
  6898.9    0.07       0  7081.1   0.045       0
Bank Sta=4977.4,4981.8
Exp/Cntr=0.3,0.1

Type RM Length L Ch R = 1,33000,500,500,500
BEGIN DESCRIPTION:
Cottonwood Creek Trib034 65.0
END DESCRIPTION:
XS GIS Cut Line= 3
      1301855.02      6863738.00      1303535.95      6863656.52
      1305554.97      6862788.01
#Sta/Elev= 30
  3317.1 2395.19  3567.4 2390.76  3597.4 2391.47  3647.5 2389.11  3727.6 2388.68
  3787.6 2385.83  3830.3 2385.55  3874.7 2385.18  3947.8 2383.11  3997.9 2383.50
  4047.9 2381.17  4278.2 2380.86  4508.5 2378.41  4618.6 2375.75  4668.7 2376.86
  4718.7 2374.78  4929.0 2375.32  5094.7 2373.87  5095.0 2373.37  5099.2 2373.87
  6194.6 2377.82  6283.5 2379.00  6316.2 2380.81  6475.4 2382.11  6522.4 2385.10
  6575.0 2384.21  6697.2 2386.23  6727.1 2388.57  6795.2 2388.08  7197.9 2394.04
#Mann=5,-1,0
  3317.1   0.045       0  3830.3   0.063       0  3874.7   0.045       0
  5094.7   0.045       0  5099.2   0.045       0
Bank Sta=5094.7,5099.2
Exp/Cntr=0.3,0.1

Type RM Length L Ch R = 1,32500,500,500,500
BEGIN DESCRIPTION:
Cottonwood Creek Trib034 64.0
END DESCRIPTION:
XS GIS Cut Line= 3
      1301658.80      6864277.79      1303455.11      6864071.66
      1305605.04      6862787.98
#Sta/Elev= 30
  3191.9 2393.73  3248.5 2394.64  3317.8 2392.78  3661.2 2391.27  3751.7 2388.85
  3792.0 2389.78  4224.8 2380.77  4325.5 2380.97  4657.7 2377.02  4718.0 2375.05
  4929.4 2375.00  4989.3 2372.96  4989.6 2372.46  4993.8 2372.96  5776.0 2373.85
  5871.4 2376.31  5972.5 2374.94  6432.4 2377.69  6503.8 2378.54  6540.7 2380.63
  6694.5 2381.85  6758.7 2384.81  6921.6 2386.24  6965.0 2388.38  7122.6 2389.22
  7151.3 2389.66  7247.7 2392.34  7432.0 2392.77  7498.0 2394.93  7504.0 2394.67
#Mann=6,-1,0
  3191.9   0.045       0  4989.3   0.045       0  4993.8   0.045       0
  7122.6    0.07       0  7151.3   0.045       0  7498.0    0.07       0
Bank Sta=4989.3,4993.8
Exp/Cntr=0.3,0.1

Type RM Length L Ch R = 1,32000,500,500,500
BEGIN DESCRIPTION:
Cottonwood Creek Trib034 63.0
END DESCRIPTION:
XS GIS Cut Line= 3
      1301629.65      6865267.39      1303542.50      6864475.72
      1305455.02      6863237.98
#Sta/Elev= 30
  2929.8 2397.40  3563.3 2391.47  3616.6 2389.19  3699.1 2389.54  3858.7 2385.28
  3965.1 2385.20  4126.1 2380.76  4225.8 2380.47  4266.8 2378.45  4403.9 2377.78
  4457.1 2375.99  4741.6 2375.69  4794.8 2373.26  5025.6 2371.92  5026.0 2371.42
  5030.5 2371.92  5145.9 2373.25  5780.6 2372.56  5977.1 2373.43  6013.4 2374.99
  6113.0 2374.01  6360.9 2377.89  6490.9 2377.88  6539.6 2380.70  6626.8 2380.11
  6756.7 2384.54  7003.0 2388.01  7098.3 2390.74  7140.6 2389.94  7278.1 2392.06
#Mann=4,-1,0
  2929.8   0.045       0  5025.6   0.045       0  5030.5   0.045       0
  7003.0    0.07       0
Bank Sta=5025.6,5030.5
Exp/Cntr=0.3,0.1

Type RM Length L Ch R = 1,31500,500,500,500
BEGIN DESCRIPTION:
Cottonwood Creek Trib034 62.0
END DESCRIPTION:
XS GIS Cut Line= 3
      1301699.13      6865493.07      1303711.92      6864746.18
      1305605.01      6863637.99
#Sta/Elev= 30
  2853.1 2397.41  3296.7 2393.06  3368.4 2393.57  3459.5 2390.93  3499.3 2391.98
  3552.7 2389.55  3638.0 2389.68  3734.0 2386.68  3904.7 2385.15  4096.7 2379.77
  4176.1 2380.25  4192.6 2378.33  4231.5 2377.54  4610.3 2375.59  4665.8 2372.96
  4736.6 2374.13  4834.9 2371.56  4835.2 2371.06  4839.8 2371.56  6149.7 2373.71
  6257.1 2375.82  6272.8 2377.53  6374.4 2377.02  6433.1 2379.88  6556.3 2380.75
  6637.4 2384.24  6741.7 2384.74  6785.0 2387.16  6986.4 2389.66  7193.6 2392.03
#Mann=4,-1,0
  2853.1   0.045       0  4834.9   0.045       0  4839.8   0.045       0
  6986.4    0.07       0
Bank Sta=4834.9,4839.8
Exp/Cntr=0.3,0.1

Type RM Length L Ch R = 1,31000,500,500,500
BEGIN DESCRIPTION:
Cottonwood Creek Trib034 61.0
END DESCRIPTION:
XS GIS Cut Line= 4
      1301780.33      6865493.07      1304063.27      6864937.52
      1304112.20      6864846.39      1305704.99      6863588.01
#Sta/Elev= 30
  2547.0 2397.43  3117.9 2392.79  3178.1 2390.50  3261.5 2390.50  3457.5 2385.25
  3522.2 2385.53  3622.2 2382.38  3677.8 2382.80  3753.3 2380.11  3902.9 2376.41
  4158.4 2376.11  4278.5 2372.98  4361.9 2373.40  4443.0 2371.46  4443.3 2370.96
  4447.9 2371.46  5847.7 2373.09  5897.4 2375.33  5975.9 2375.68  6004.8 2377.90
  6097.8 2377.29  6161.9 2380.10  6239.8 2380.08  6325.4 2383.46  6381.5 2383.25
  6410.3 2385.30  6460.0 2384.58  6509.7 2387.43  6708.0 2389.76  7029.9 2393.75
#Mann=6,-1,0
  2547.0   0.045       0  3677.8    0.07       0  3753.3   0.045       0
  4443.0   0.045       0  4447.9   0.045       0  6708.0    0.07       0
Bank Sta=4443,4447.9
Exp/Cntr=0.3,0.1

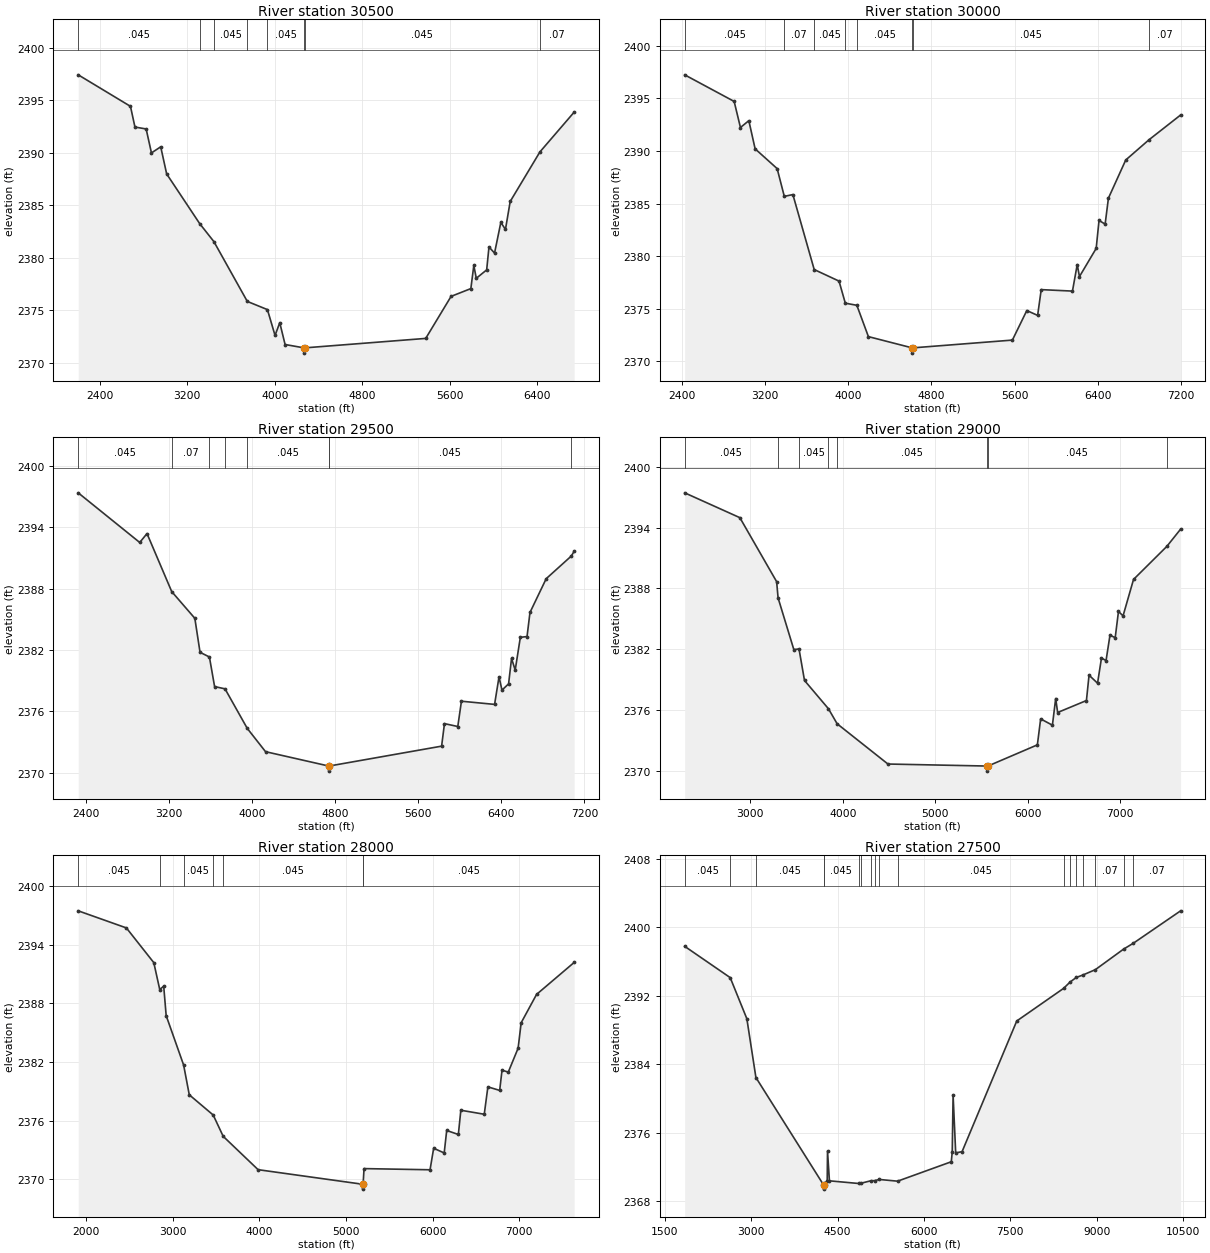
Type RM Length L Ch R = 1,30500,500,500,500
BEGIN DESCRIPTION:
Cottonwood Creek Trib034 60.0
END DESCRIPTION:
XS GIS Cut Line= 3
      1301768.61      6865562.51      1304497.69      6864940.35
      1305955.00      6863988.00
#Sta/Elev= 30
  2200.9 2397.42  2679.3 2394.42  2720.3 2392.45  2822.8 2392.27  2871.3 2389.99
  2956.2 2390.57  3010.6 2387.99  3313.1 2383.26  3443.0 2381.55  3748.8 2375.86
  3933.1 2375.08  4002.9 2372.62  4045.9 2373.84  4094.7 2371.76  4268.4 2371.44
  4268.9 2370.94  4274.0 2371.44  5382.0 2372.34  5614.3 2376.34  5795.3 2377.08
  5822.4 2379.28  5844.9 2378.06  5940.1 2378.86  5961.2 2381.04  6012.2 2380.46
  6069.8 2383.38  6112.0 2382.71  6155.5 2385.37  6427.2 2390.08  6740.9 2393.87
#Mann=8,-1,0
  2200.9   0.045       0  3313.1    0.07       0  3443.0   0.045       0
  3748.8    0.07       0  3933.1   0.045       0  4268.4   0.045       0
  4274.0   0.045       0  6427.2    0.07       0
Bank Sta=4268.4,4274
Exp/Cntr=0.3,0.1

Type RM Length L Ch R = 1,30000,500,500,500
BEGIN DESCRIPTION:
Cottonwood Creek Trib034 59.0
END DESCRIPTION:
XS GIS Cut Line= 3
      1301803.27      6865614.61      1304354.14      6865287.17
      1306255.02      6864187.99
#Sta/Elev= 30
  2428.2 2397.24  2903.8 2394.71  2964.3 2392.23  3045.0 2392.88  3105.4 2390.20
  3317.2 2388.32  3385.8 2385.68  3468.4 2385.85  3673.3 2378.72  3912.0 2377.62
  3972.4 2375.52  4083.3 2375.32  4194.3 2372.34  4615.0 2371.27  4615.4 2370.77
  4620.6 2371.27  5578.6 2372.01  5717.2 2374.82  5821.2 2374.36  5855.8 2376.81
  6156.1 2376.67  6201.8 2379.19  6223.3 2378.05  6384.1 2380.73  6411.4 2383.39
  6470.2 2383.04  6501.8 2385.51  6668.3 2389.14  6891.4 2391.06  7195.8 2393.42
#Mann=8,-1,0
  2428.2   0.045       0  3385.8    0.07       0  3673.3   0.045       0
  3972.4    0.07       0  4083.3   0.045       0  4615.0   0.045       0
  4620.6   0.045       0  6891.4    0.07       0
Bank Sta=4615,4620.6
Exp/Cntr=0.3,0.1

Type RM Length L Ch R = 1,29500,500,500,500
BEGIN DESCRIPTION:
Cottonwood Creek Trib034 58.0
END DESCRIPTION:
XS GIS Cut Line= 3
      1301803.31      6865649.33      1304472.96      6865720.60
      1306055.03      6864337.97
#Sta/Elev= 30
  2329.4 2397.35  2921.3 2392.50  2991.3 2393.37  3229.1 2387.70  3451.5 2385.09
  3501.5 2381.77  3591.8 2381.31  3641.6 2378.42  3741.9 2378.20  3955.6 2374.34
  4131.7 2372.06  4739.0 2370.66  4739.5 2370.16  4744.8 2370.66  5825.8 2372.60
  5853.3 2374.80  5981.5 2374.52  6016.6 2376.99  6335.5 2376.68  6378.2 2379.37
  6406.7 2378.07  6470.3 2378.69  6498.8 2381.17  6533.9 2380.03  6583.3 2383.23
  6647.8 2383.31  6676.1 2385.66  6832.0 2388.96  7073.4 2391.17  7101.1 2391.64
#Mann=8,-1,0
  2329.4   0.045       0  3229.1    0.07       0  3591.8   0.045       0
  3741.9    0.07       0  3955.6   0.045       0  4739.0   0.045       0
  4744.8   0.045       0  7073.4    0.07       0
Bank Sta=4739,4744.8
Exp/Cntr=0.3,0.1

Type RM Length L Ch R = 1,29000,1000,1000,1000
BEGIN DESCRIPTION:
Cottonwood Creek Trib034 57.0
END DESCRIPTION:
XS GIS Cut Line= 3
      1301785.94      6865716.17      1304461.84      6866144.72
      1306355.01      6864287.99
#Sta/Elev= 30
  2290.0 2397.42  2886.6 2394.97  3284.2 2388.66  3299.8 2387.06  3470.2 2381.96
  3526.0 2382.03  3585.4 2378.92  3844.3 2376.13  3938.1 2374.65  4487.5 2370.68
  5562.6 2370.48  5563.1 2369.98  5568.5 2370.48  6103.0 2372.57  6138.5 2375.13
  6265.6 2374.51  6301.1 2377.14  6322.2 2375.76  6633.4 2376.94  6661.7 2379.44
  6753.7 2378.65  6796.1 2381.13  6845.5 2380.88  6888.0 2383.38  6944.5 2383.14
  6979.8 2385.72  7029.4 2385.29  7142.6 2388.88  7502.8 2392.14  7651.7 2393.84
#Mann=8,-1,0
  2290.0   0.045       0  3299.8    0.07       0  3526.0   0.045       0
  3844.3    0.07       0  3938.1   0.045       0  5562.6   0.045       0
  5568.5   0.045       0  7502.8    0.07       0
Bank Sta=5562.6,5568.5
Exp/Cntr=0.3,0.1

Type RM Length L Ch R = 1,28000,500,500,500
BEGIN DESCRIPTION:
Cottonwood Creek Trib034 56.0
END DESCRIPTION:
XS GIS Cut Line= 4
      1301759.88      6865872.42      1304789.74      6866502.60
      1304908.63      6866516.69      1306470.28      6864543.40
#Sta/Elev= 30
  1905.3 2397.46  2462.1 2395.71  2778.7 2392.16  2847.4 2389.41  2893.2 2389.75
  2921.7 2386.74  3123.6 2381.68  3188.7 2378.64  3465.3 2376.57  3580.7 2374.39
  3984.0 2370.98  5191.5 2369.49  5192.0 2368.99  5197.6 2369.49  5208.1 2371.09
  5971.0 2370.97  6012.7 2373.17  6134.5 2372.69  6163.4 2374.99  6298.0 2374.58
  6326.8 2377.06  6597.4 2376.65  6639.3 2379.45  6775.6 2379.09  6802.8 2381.16
  6875.0 2380.96  6988.7 2383.41  7024.0 2386.01  7201.9 2388.91  7636.2 2392.18
#Mann=7,-1,0
  1905.3   0.045       0  2847.4    0.07       0  3123.6   0.045       0
  3465.3    0.07       0  3580.7   0.045       0  5191.5   0.045       0
  5197.6   0.045       0
Bank Sta=5191.5,5197.6
Exp/Cntr=0.3,0.1

Type RM Length L Ch R = 1,27500,500,500,500
BEGIN DESCRIPTION:
Cottonwood Creek Trib034 55.0
END DESCRIPTION:
XS GIS Cut Line= 4
      1301629.63      6866028.65      1304654.27      6866925.13
      1306076.96      6866194.86      1307548.33      6862627.12
#Sta/Elev= 30
  1845.3 2397.79  2636.0 2394.13  2925.2 2389.32  3082.4 2382.45  4256.5 2369.90
  4257.0 2369.40  4264.0 2369.90  4320.7 2370.39  4326.0 2373.85  4359.2 2370.37
  4865.4 2370.06  4913.7 2370.10  5080.8 2370.38  5142.7 2370.39  5226.2 2370.53
  5542.8 2370.33  6475.4 2372.60  6492.0 2373.73  6507.0 2380.39  6552.0 2373.64
  6662.8 2373.78  7612.6 2389.06  8425.4 2392.87  8537.9 2393.61  8646.8 2394.15
  8759.1 2394.43  8977.4 2395.06  9467.1 2397.46  9637.0 2398.15 10458.4 2401.94
#Mann=18,-1,0
  1845.3   0.045       0  2636.0    0.07       0  3082.4   0.045       0
  4256.5   0.045       0  4264.0   0.045       0  4865.4    0.07       0
  4913.7   0.045       0  5080.8    0.07       0  5142.7   0.045       0
  5226.2    0.07       0  5542.8   0.045       0  8425.4    0.07       0
  8537.9   0.045       0  8646.8    0.07       0  8759.1   0.045       0
  8977.4    0.07       0  9467.1   0.045       0  9637.0    0.07       0
Bank Sta=4256.5,4264
Exp/Cntr=0.3,0.1

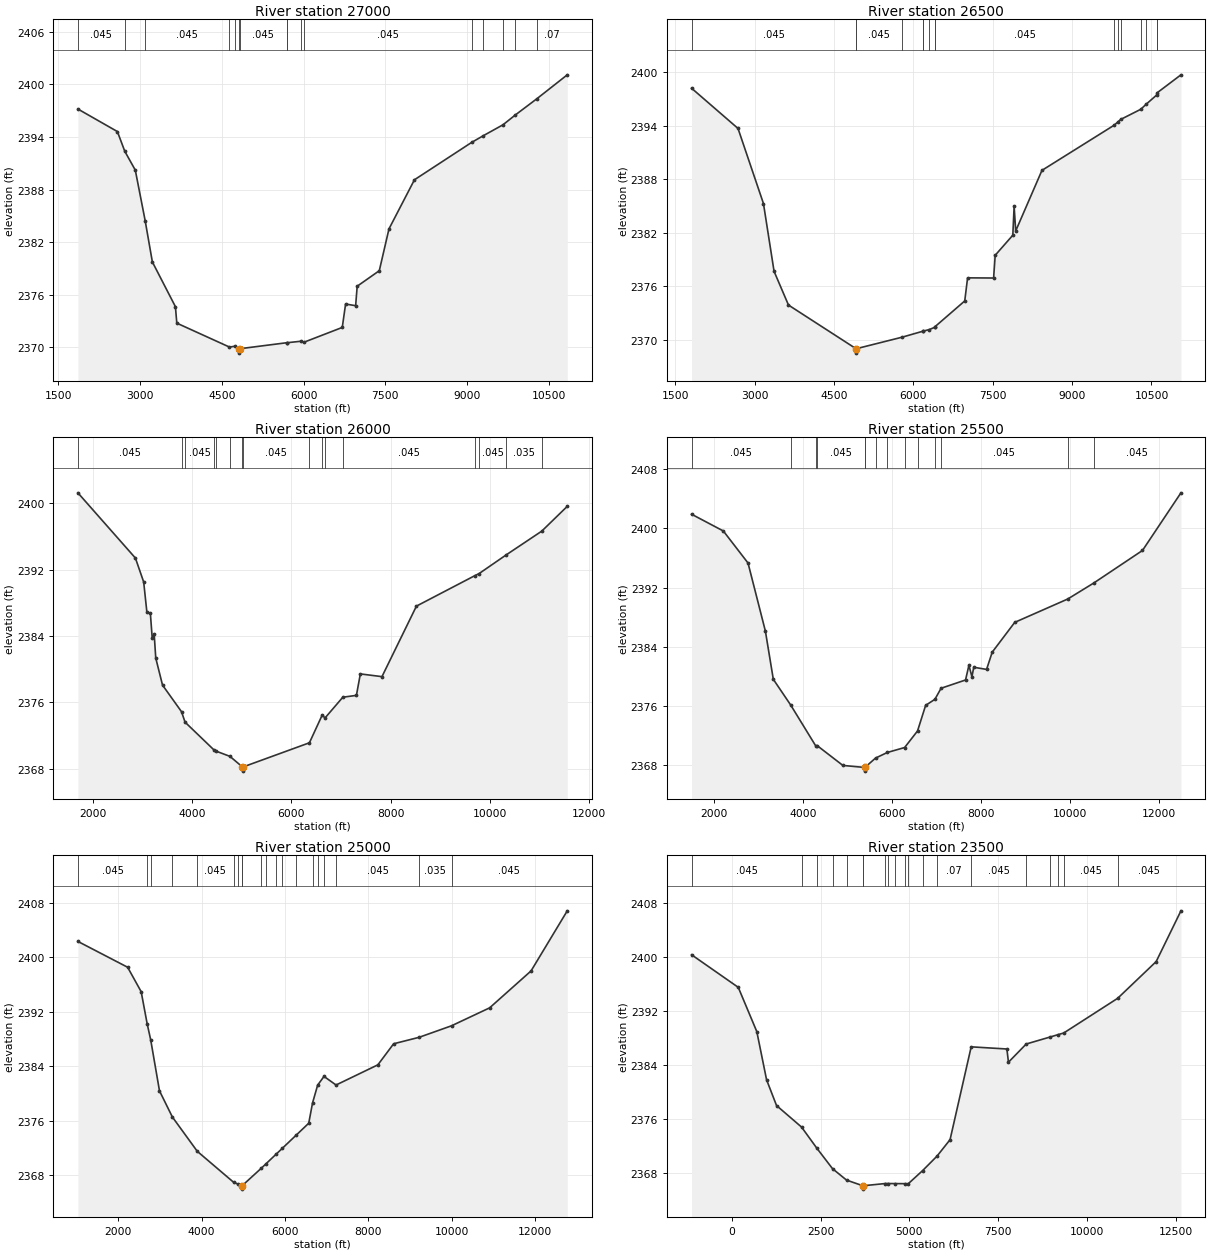
Type RM Length L Ch R = 1,27000,500,500,500
BEGIN DESCRIPTION:
Cottonwood Creek Trib034 54.0
END DESCRIPTION:
XS GIS Cut Line= 4
      1301551.52      6866289.07      1304513.62      6867332.18
      1306310.50      6866427.40      1307626.44      6862835.48
#Sta/Elev= 30
  1859.6 2397.19  2584.2 2394.62  2720.0 2392.37  2912.9 2390.22  3093.4 2384.47
  3225.9 2379.75  3648.7 2374.65  3674.4 2372.77  4640.7 2370.04  4744.0 2370.14
  4820.4 2369.85  4820.9 2369.35  4827.9 2369.85  5695.8 2370.54  5701.9 2370.54
  5944.2 2370.70  6001.8 2370.58  6709.6 2372.28  6770.5 2374.95  6955.1 2374.76
  6983.3 2376.98  7388.8 2378.75  7566.5 2383.52  8033.6 2389.12  9082.5 2393.38
  9289.2 2394.12  9657.6 2395.39  9886.1 2396.52 10279.0 2398.36 10837.2 2401.09
#Mann=16,-1,0
  1859.6   0.045       0  2720.0    0.07       0  3093.4   0.045       0
  4640.7    0.07       0  4744.0   0.045       0  4820.4   0.045       0
  4827.9   0.045       0  5695.8   0.035       0  5701.9   0.045       0
  5944.2    0.07       0  6001.8   0.045       0  9082.5    0.07       0
  9289.2   0.045       0  9657.6    0.07       0  9886.1   0.045       0
 10279.0    0.07       0
Bank Sta=4820.4,4827.9
Exp/Cntr=0.3,0.1

Type RM Length L Ch R = 1,26500,500,500,500
BEGIN DESCRIPTION:
Cottonwood Creek Trib034 53.0
END DESCRIPTION:
XS GIS Cut Line= 4
      1301421.32      6866601.58      1304409.47      6867730.80
      1306315.42      6866815.35      1307730.32      6863135.71
#Sta/Elev= 30
  1805.6 2398.20  2683.7 2393.69  3164.7 2385.27  3365.2 2377.67  3637.6 2373.89
  4913.6 2369.00  4914.1 2368.50  4922.8 2369.00  5787.0 2370.29  6186.7 2370.97
  6187.0 2370.97  6298.2 2371.14  6400.7 2371.39  6408.7 2371.47  6969.7 2374.35
  7023.5 2376.94  7515.3 2376.92  7545.3 2379.47  7878.5 2381.72  7903.2 2384.95
  7933.2 2382.20  8429.4 2388.99  9796.1 2394.06  9870.2 2394.45  9921.2 2394.71
 10298.4 2395.84 10400.4 2396.41 10596.8 2397.43 10608.0 2397.69 11056.7 2399.70
#Mann=16,-1,0
  1805.6   0.045       0  4913.6   0.045       0  4922.8   0.045       0
  5787.0   0.035       0  6186.7   0.045       0  6187.0    0.07       0
  6298.2   0.045       0  6400.7    0.07       0  6408.7   0.045       0
  9796.1    0.07       0  9870.2   0.045       0  9921.2    0.07       0
 10298.4   0.045       0 10400.4    0.07       0 10596.8   0.045       0
 10608.0    0.07       0
Bank Sta=4913.6,4922.8
Exp/Cntr=0.3,0.1

Type RM Length L Ch R = 1,26000,500,500,500
BEGIN DESCRIPTION:
Cottonwood Creek Trib034 52.0
END DESCRIPTION:
XS GIS Cut Line= 4
      1301108.82      6867122.41      1304255.26      6868117.01
      1306493.63      6867054.23      1308081.81      6863292.07
#Sta/Elev= 30
  1700.1 2401.27  2859.1 2393.40  3026.0 2390.51  3090.6 2386.86  3160.5 2386.74
  3198.1 2383.73  3237.8 2384.20  3269.3 2381.33  3405.6 2378.07  3788.3 2374.86
  3859.6 2373.60  4450.4 2370.20  4490.1 2370.09  4764.5 2369.47  5017.1 2368.19
  5017.6 2367.69  5026.6 2368.19  6365.7 2371.11  6626.1 2374.49  6677.9 2374.09
  7039.2 2376.61  7312.7 2376.83  7391.9 2379.42  7827.5 2379.09  8522.0 2387.60
  9700.4 2391.28  9783.1 2391.52 10335.4 2393.80 11048.0 2396.65 11561.5 2399.64
#Mann=16,-1,0
  1700.1   0.045       0  3788.3    0.07       0  3859.6   0.045       0
  4450.4   0.035       0  4490.1   0.063       0  4764.5   0.045       0
  5017.1   0.045       0  5026.6   0.045       0  6365.7    0.07       0
  6626.1   0.045       0  6677.9    0.07       0  7039.2   0.045       0
  9700.4   0.035       0  9783.1   0.045       0 10335.4   0.035       0
 11048.0   0.045       0
Bank Sta=5017.1,5026.6
Exp/Cntr=0.3,0.1

Type RM Length L Ch R = 1,25500,500,500,500
BEGIN DESCRIPTION:
Cottonwood Creek Trib034 51.0
END DESCRIPTION:
XS GIS Cut Line= 4
      1300822.42      6867434.93      1304139.07      6868552.87
      1306594.08      6867201.35      1308537.92      6862926.59
#Sta/Elev= 30
  1500.0 2401.91  2214.5 2399.64  2769.1 2395.31  3159.5 2386.10  3337.4 2379.59
  3724.2 2376.15  4290.8 2370.59  4322.6 2370.63  4900.7 2367.95  5386.7 2367.68
  5387.2 2367.18  5396.2 2367.68  5634.2 2368.94  5899.1 2369.70  6288.3 2370.37
  6578.5 2372.61  6760.6 2376.07  6969.1 2376.89  7107.3 2378.38  7657.3 2379.50
  7733.1 2381.48  7800.7 2379.94  7842.7 2381.22  8130.5 2380.93  8256.8 2383.26
  8763.1 2387.29  9952.3 2390.44 10536.9 2392.60 11634.1 2397.01 12498.4 2404.80
#Mann=14,-1,0
  1500.0   0.045       0  3724.2    0.07       0  4290.8   0.035       0
  4322.6   0.045       0  5386.7   0.045       0  5396.2   0.045       0
  5634.2   0.094       0  5899.1   0.045       0  6288.3    0.07       0
  6578.5   0.045       0  6969.1    0.07       0  7107.3   0.045       0
  9952.3   0.035       0 10536.9   0.045       0
Bank Sta=5386.7,5396.2
Exp/Cntr=0.3,0.1

Type RM Length L Ch R = 1,25000,1500,1500,1500
BEGIN DESCRIPTION:
Cottonwood Creek Trib034 50.0
END DESCRIPTION:
XS GIS Cut Line= 4
      1300614.02      6867695.32      1304387.28      6868920.24
      1306780.09      6867275.59      1308733.08      6862822.77
#Sta/Elev= 30
  1032.9 2402.34  2225.5 2398.55  2550.4 2394.96  2694.3 2390.24  2778.8 2387.89
  2989.5 2380.41  3297.7 2376.58  3895.2 2371.54  4765.5 2367.00  4877.8 2366.71
  4961.3 2366.49  4961.8 2365.99  4970.8 2366.49  5432.8 2369.07  5541.6 2369.70
  5789.5 2371.14  5938.0 2372.00  6260.9 2373.88  6567.5 2375.66  6658.5 2378.63
  6781.1 2381.25  6933.5 2382.53  7222.3 2381.27  8225.0 2384.23  8602.8 2387.32
  9214.7 2388.27  9990.9 2389.96 10903.8 2392.59 11897.4 2398.01 12765.8 2406.83
#Mann=20,-1,0
  1032.9   0.045       0  2694.3    0.07       0  2778.8   0.045       0
  3297.7    0.07       0  3895.2   0.045       0  4765.5   0.035       0
  4877.8    0.07       0  4961.3    0.07       0  4970.8    0.07       0
  5432.8   0.035       0  5541.6   0.045       0  5789.5   0.094       0
  5938.0   0.045       0  6260.9    0.07       0  6658.5   0.035       0
  6781.1    0.07       0  6933.5    0.07       0  7222.3   0.045       0
  9214.7   0.035       0  9990.9   0.045       0
Bank Sta=4961.3,4970.8
Exp/Cntr=0.3,0.1

Type RM Length L Ch R = 1,23500,1000,1000,1000
BEGIN DESCRIPTION:
Cottonwood Creek Trib034 47.0
END DESCRIPTION:
XS GIS Cut Line= 5
      1299200.63      6870950.34      1304233.84      6869440.13
      1305104.64      6869352.44      1306884.25      6867366.73
      1309019.68      6862874.53
#Sta/Elev= 30
 -1130.1 2400.30   183.8 2395.47   705.8 2388.91   980.7 2381.77  1260.8 2377.95
  1964.4 2374.76  2398.8 2371.60  2836.6 2368.59  3230.2 2366.90  3690.1 2366.06
  3690.6 2365.56  3699.9 2366.06  4325.0 2366.39  4405.1 2366.39  4592.7 2366.38
  4879.9 2366.37  4968.0 2366.36  5374.2 2368.32  5776.4 2370.45  6143.7 2372.89
  6738.1 2386.65  7742.6 2386.33  7786.9 2384.37  8286.8 2387.07  8954.4 2388.10
  9178.3 2388.45  9341.8 2388.70 10859.0 2393.84 11943.5 2399.29 12640.4 2406.81
#Mann=20,-1,0
 -1130.1   0.045       0  1964.4    0.07       0  2398.8   0.045       0
  2836.6   0.035       0  3230.2   0.035       0  3690.1   0.045       0
  3699.9   0.035       0  4325.0    0.07       0  4405.1   0.045       0
  4592.7   0.045       0  4879.9   0.035       0  4968.0   0.045       0
  5374.2   0.045       0  5776.4    0.07       0  6738.1   0.045       0
  8286.8   0.035       0  8954.4   0.045       0  9178.3    0.07       0
  9341.8   0.045       0 10859.0   0.045       0
Bank Sta=3690.1,3699.9
Exp/Cntr=0.3,0.1