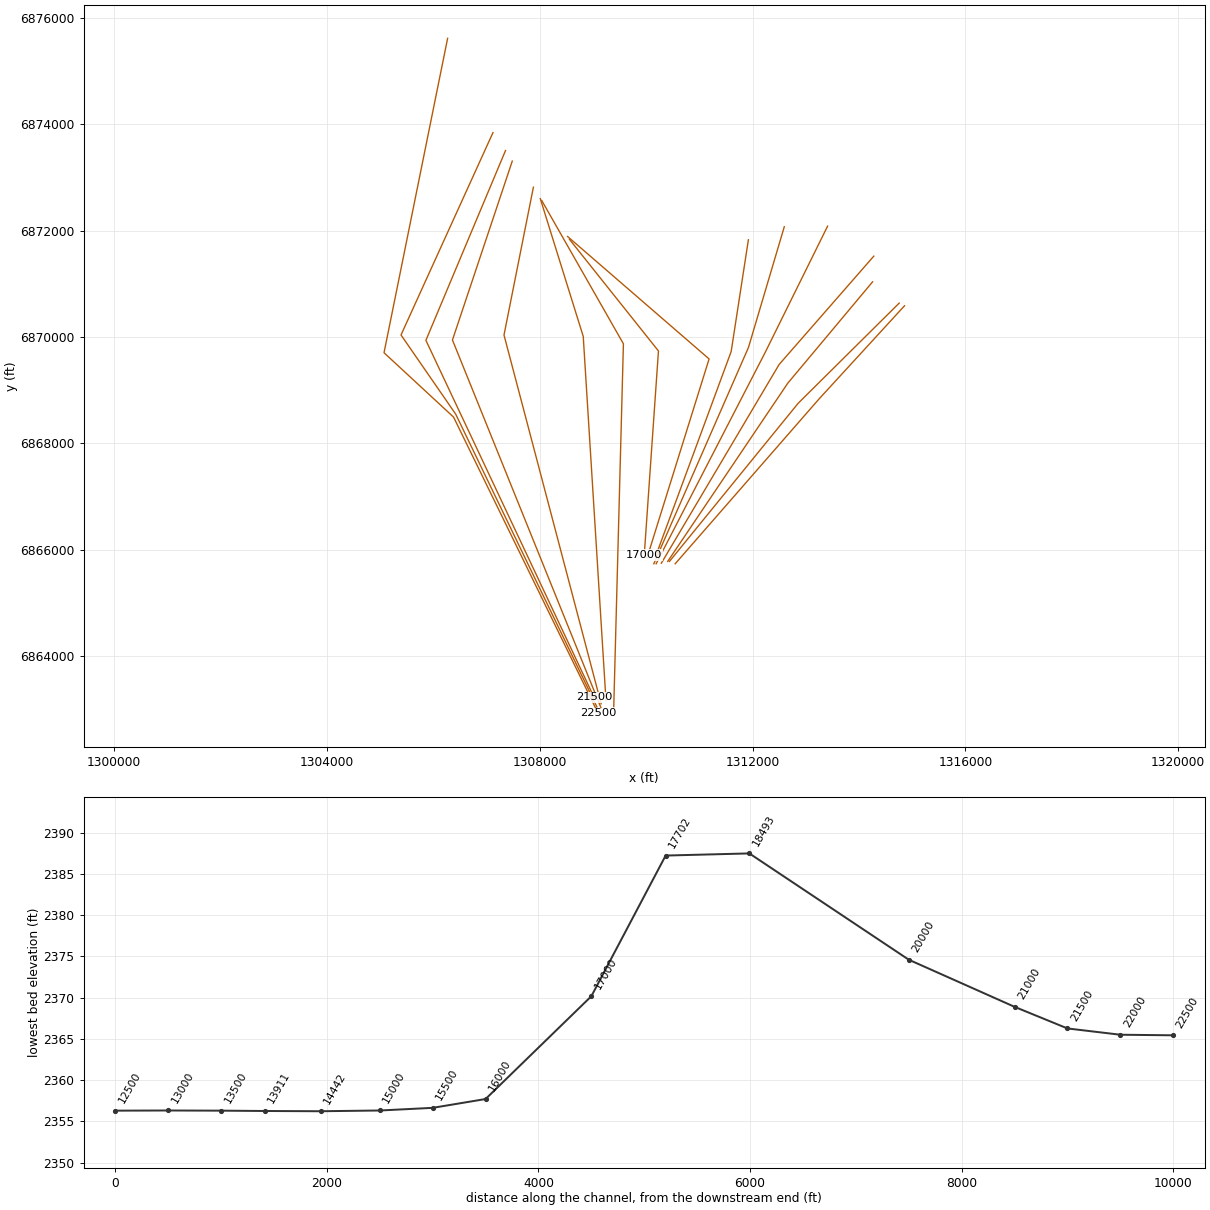
HEC-RAS study Cottonwood Creek Trib034.prj: Cottonwood Creek Trib034 Base Level Engineering

--- Cottonwood Creek Trib034.g01 (geometry) --- (continued)

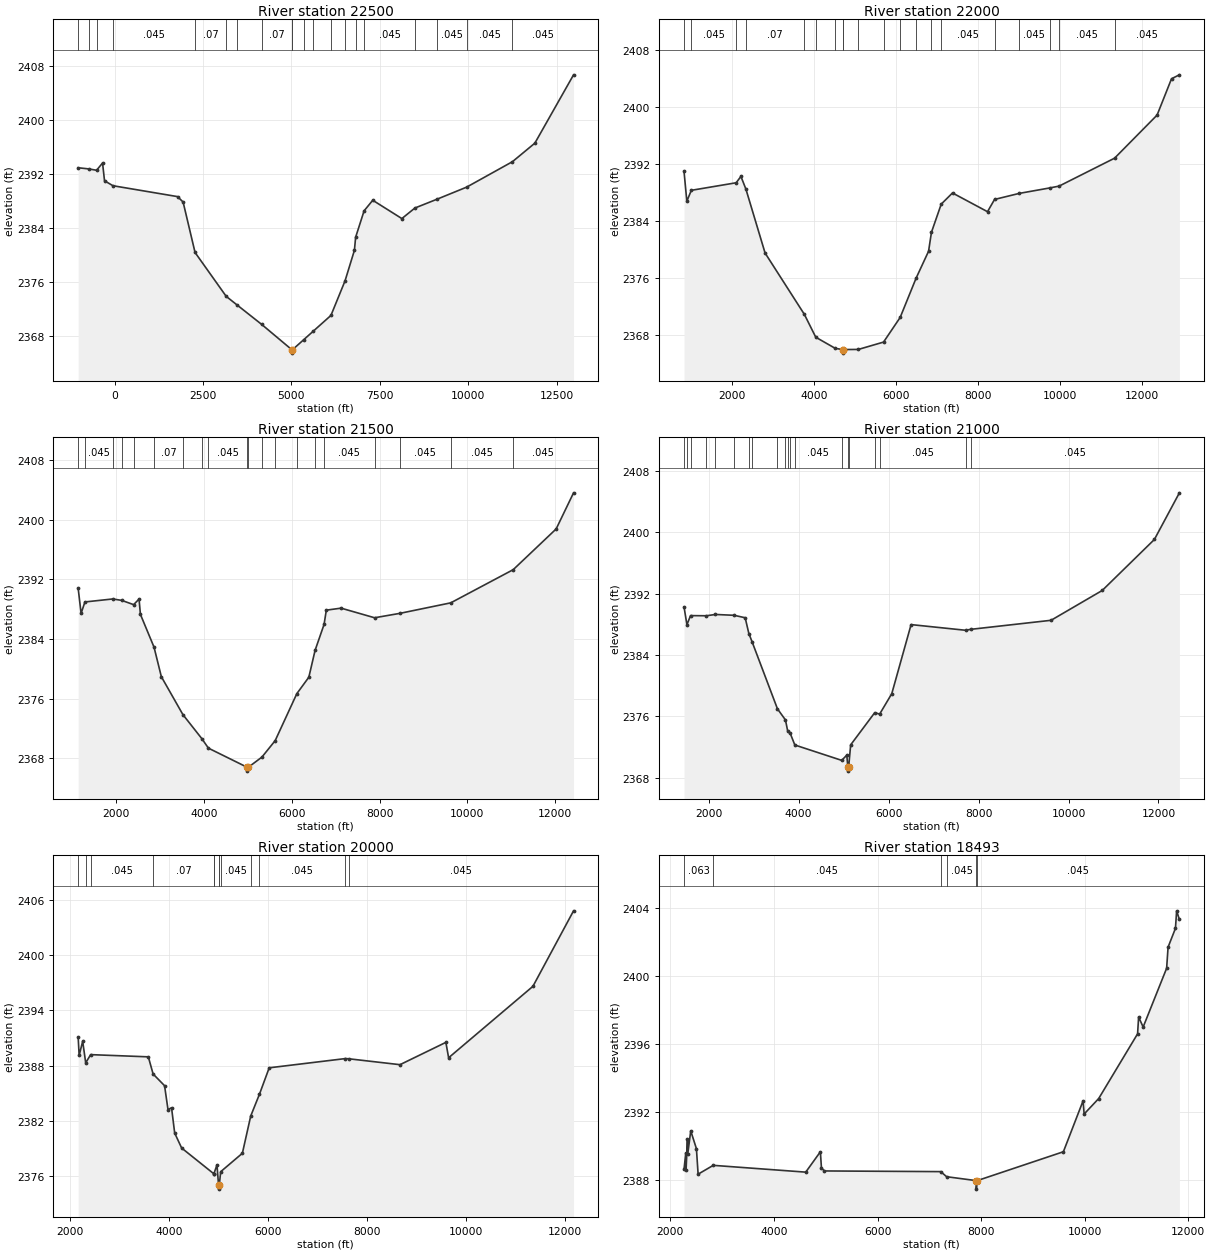
Type RM Length L Ch R = 1,22500,500,500,500
BEGIN DESCRIPTION:
Cottonwood Creek Trib034 45.0
END DESCRIPTION:
XS GIS Cut Line= 4
      1306267.27      6875615.42      1305071.99      6869704.56
      1306379.21      6868494.34      1309097.02      6862924.58
#Sta/Elev= 30
 -1030.5 2392.87  -736.6 2392.70  -510.7 2392.50  -341.2 2393.57  -285.4 2390.94
   -46.5 2390.21  1779.4 2388.60  1936.7 2387.80  2274.8 2380.33  3155.7 2373.84
  3473.8 2372.52  4158.7 2369.69  5012.9 2365.94  5013.4 2365.44  5028.7 2365.94
  5346.3 2367.42  5622.6 2368.71  6117.8 2371.02  6515.4 2376.12  6781.4 2380.65
  6816.0 2382.59  7055.5 2386.50  7300.3 2388.06  8123.4 2385.35  8491.8 2386.91
  9119.7 2388.22  9954.5 2390.00 11251.6 2393.77 11884.6 2396.51 12978.9 2406.62
#Mann=20,-1,0
 -1030.5    0.07       0  -736.6   0.035       0  -510.7   0.063       0
   -46.5   0.045       0  2274.8    0.07       0  3155.7   0.045       0
  3473.8   0.035       0  4158.7    0.07       0  5012.9   0.035       0
  5028.7   0.035       0  5346.3   0.045       0  5622.6   0.045       0
  6117.8    0.07       0  6515.4   0.045       0  6816.0    0.07       0
  7055.5   0.045       0  8491.8   0.035       0  9119.7   0.045       0
  9954.5   0.045       0 11251.6   0.045       0
Bank Sta=5012.9,5028.7
Exp/Cntr=0.3,0.1

Type RM Length L Ch R = 1,22000,500,500,500
BEGIN DESCRIPTION:
Cottonwood Creek Trib034 44.0
END DESCRIPTION:
XS GIS Cut Line= 4
      1307119.47      6873842.96      1305391.37      6870038.77
      1306419.33      6868549.83      1309072.44      6863047.49
#Sta/Elev= 30
   821.7 2391.02   890.3 2386.83  1000.2 2388.36  2094.5 2389.42  2211.1 2390.31
  2333.3 2388.52  2800.9 2379.56  3760.2 2370.95  4038.9 2367.74  4514.7 2366.18
  4696.1 2366.01  4696.6 2365.51  4712.4 2366.01  5079.2 2366.03  5693.8 2367.06
  6099.6 2370.52  6488.4 2376.03  6793.1 2379.81  6863.5 2382.47  7102.1 2386.42
  7377.5 2387.99  8232.4 2385.36  8404.2 2387.08  9008.0 2387.93  9747.4 2388.69
  9979.5 2388.95 11334.8 2392.87 12373.3 2398.92 12725.6 2404.02 12917.9 2404.57
#Mann=20,-1,0
   821.7   0.063       0  1000.2   0.045       0  2094.5   0.035       0
  2333.3    0.07       0  3760.2   0.035       0  4038.9   0.035       0
  4514.7    0.07       0  4696.1    0.07       0  4712.4    0.07       0
  5079.2   0.035       0  5693.8   0.045       0  6099.6    0.07       0
  6488.4   0.045       0  6863.5    0.07       0  7102.1   0.045       0
  8404.2   0.035       0  9008.0   0.045       0  9747.4   0.045       0
  9979.5   0.045       0 11334.8   0.045       0
Bank Sta=4696.1,4712.4
Exp/Cntr=0.3,0.1

Type RM Length L Ch R = 1,21500,500,500,500
BEGIN DESCRIPTION:
Cottonwood Creek Trib034 43.0
END DESCRIPTION:
XS GIS Cut Line= 3
      1307355.18      6873505.40      1305859.17      6869937.98
      1309019.69      6863226.07
#Sta/Elev= 30
  1131.6 2390.76  1198.0 2387.42  1285.3 2388.95  1918.8 2389.35  2124.4 2389.16
  2394.8 2388.59  2518.8 2389.34  2549.3 2387.29  2859.8 2382.89  3026.4 2378.93
  3518.4 2373.84  3949.5 2370.62  4099.1 2369.35  4987.9 2366.77  4988.4 2366.27
  5004.5 2366.77  5317.7 2368.15  5620.4 2370.36  6114.0 2376.66  6387.0 2378.86
  6529.8 2382.47  6734.3 2385.94  6785.5 2387.85  7122.2 2388.12  7885.2 2386.83
  8460.3 2387.42  9620.4 2388.83 11044.1 2393.28 12022.4 2398.74 12418.8 2403.58
#Mann=20,-1,0
  1131.6   0.063       0  1285.3   0.045       0  1918.8   0.035       0
  2124.4   0.045       0  2394.8    0.07       0  2859.8    0.07       0
  3518.4   0.035       0  3949.5   0.035       0  4099.1   0.045       0
  4987.9   0.045       0  5004.5   0.045       0  5317.7   0.045       0
  5620.4    0.07       0  6114.0   0.045       0  6529.8    0.07       0
  6734.3   0.045       0  7885.2   0.035       0  8460.3   0.045       0
  9620.4   0.045       0 11044.1   0.045       0
Bank Sta=4987.9,5004.5
Exp/Cntr=0.3,0.1

Type RM Length L Ch R = 1,21000,1000,1000,1000
BEGIN DESCRIPTION:
Cottonwood Creek Trib034 42.0
END DESCRIPTION:
XS GIS Cut Line= 3
      1307482.56      6873307.86      1306358.10      6869944.24
      1309152.66      6863022.49
#Sta/Elev= 30
  1453.4 2390.27  1518.0 2387.95  1598.4 2389.13  1950.3 2389.11  2152.1 2389.28
  2567.3 2389.17  2812.9 2388.85  2894.2 2386.80  2964.0 2385.76  3529.8 2377.00
  3708.2 2375.55  3757.7 2374.11  3812.4 2373.83  3916.6 2372.29  4958.7 2370.29
  5071.4 2370.97  5095.4 2369.39  5095.9 2368.89  5112.1 2369.39  5157.7 2372.31
  5692.7 2376.50  5801.5 2376.31  6071.3 2378.97  6500.6 2387.96  7715.3 2387.22
  7821.3 2387.34  9611.6 2388.52 10748.7 2392.40 11908.7 2399.04 12464.6 2405.11
#Mann=20,-1,0
  1453.4   0.063       0  1518.0   0.035       0  1598.4   0.045       0
  1950.3   0.035       0  2152.1   0.045       0  2567.3    0.07       0
  2894.2   0.035       0  2964.0    0.07       0  3529.8   0.035       0
  3708.2    0.07       0  3757.7   0.035       0  3812.4    0.07       0
  3916.6   0.045       0  4958.7    0.07       0  5095.4    0.07       0
  5112.1    0.07       0  5692.7    0.07       0  5801.5   0.045       0
  7715.3   0.035       0  7821.3   0.045       0
Bank Sta=5095.4,5112.1
Exp/Cntr=0.3,0.1

Type RM Length L Ch R = 1,20000,1507,1507,1507
BEGIN DESCRIPTION:
Cottonwood Creek Trib034 40.0
END DESCRIPTION:
XS GIS Cut Line= 3
      1307879.63      6872817.07      1307326.89      6870038.01
      1309152.84      6863104.51
#Sta/Elev= 30
  2166.5 2391.05  2185.9 2389.10  2257.3 2390.64  2318.2 2388.30  2418.6 2389.19
  3582.8 2388.95  3679.5 2387.09  3910.8 2385.82  3980.4 2383.22  4051.8 2383.43
  4115.3 2380.68  4255.7 2379.06  4899.6 2376.29  4907.9 2376.28  4969.4 2377.23
  5000.3 2375.10  5000.8 2374.60  5017.1 2375.10  5044.1 2376.49  5482.1 2378.49
  5650.6 2382.53  5827.4 2384.90  6023.8 2387.76  7559.1 2388.76  7629.3 2388.74
  8664.9 2388.10  9591.4 2390.52  9647.0 2388.85 11349.4 2396.60 12169.9 2404.79
#Mann=13,-1,0
  2166.5   0.063       0  2318.2   0.035       0  2418.6   0.045       0
  3679.5    0.07       0  4899.6   0.045       0  4907.9    0.07       0
  5000.3    0.07       0  5017.1    0.07       0  5044.1   0.045       0
  5650.6    0.07       0  5827.4   0.045       0  7559.1   0.035       0
  7629.3   0.045       0
Bank Sta=5000.3,5017.1
Exp/Cntr=0.3,0.1

Type RM Length L Ch R = 1,18493,791,791,791
BEGIN DESCRIPTION:
Cottonwood Creek Trib034 35.5
END DESCRIPTION:
XS GIS Cut Line= 3
      1308008.80      6872601.86      1308816.15      6870012.02
      1309243.48      6863172.12
#Sta/Elev= 30
  2263.2 2388.64  2297.1 2389.61  2302.4 2388.59  2329.6 2390.42  2334.9 2389.54
  2392.9 2390.91  2502.7 2389.86  2535.2 2388.36  2827.5 2388.88  4613.6 2388.48
  4896.4 2389.68  4916.9 2388.72  4975.5 2388.55  7220.2 2388.51  7334.6 2388.21
  7907.3 2387.98  7907.8 2387.48  7924.1 2387.98  9589.0 2389.68  9969.7 2392.68
  9989.7 2391.90 10270.3 2392.81 11021.8 2396.62 11041.8 2397.61 11129.4 2397.02
 11582.8 2400.48 11610.5 2401.72 11753.2 2402.83 11775.8 2403.86 11829.2 2403.35
#Mann=6,-1,0
  2263.2   0.063       0  2827.5   0.045       0  7220.2   0.035       0
  7334.6   0.045       0  7907.3   0.045       0  7924.1   0.045       0
Bank Sta=7907.3,7924.1
Exp/Cntr=0.3,0.1

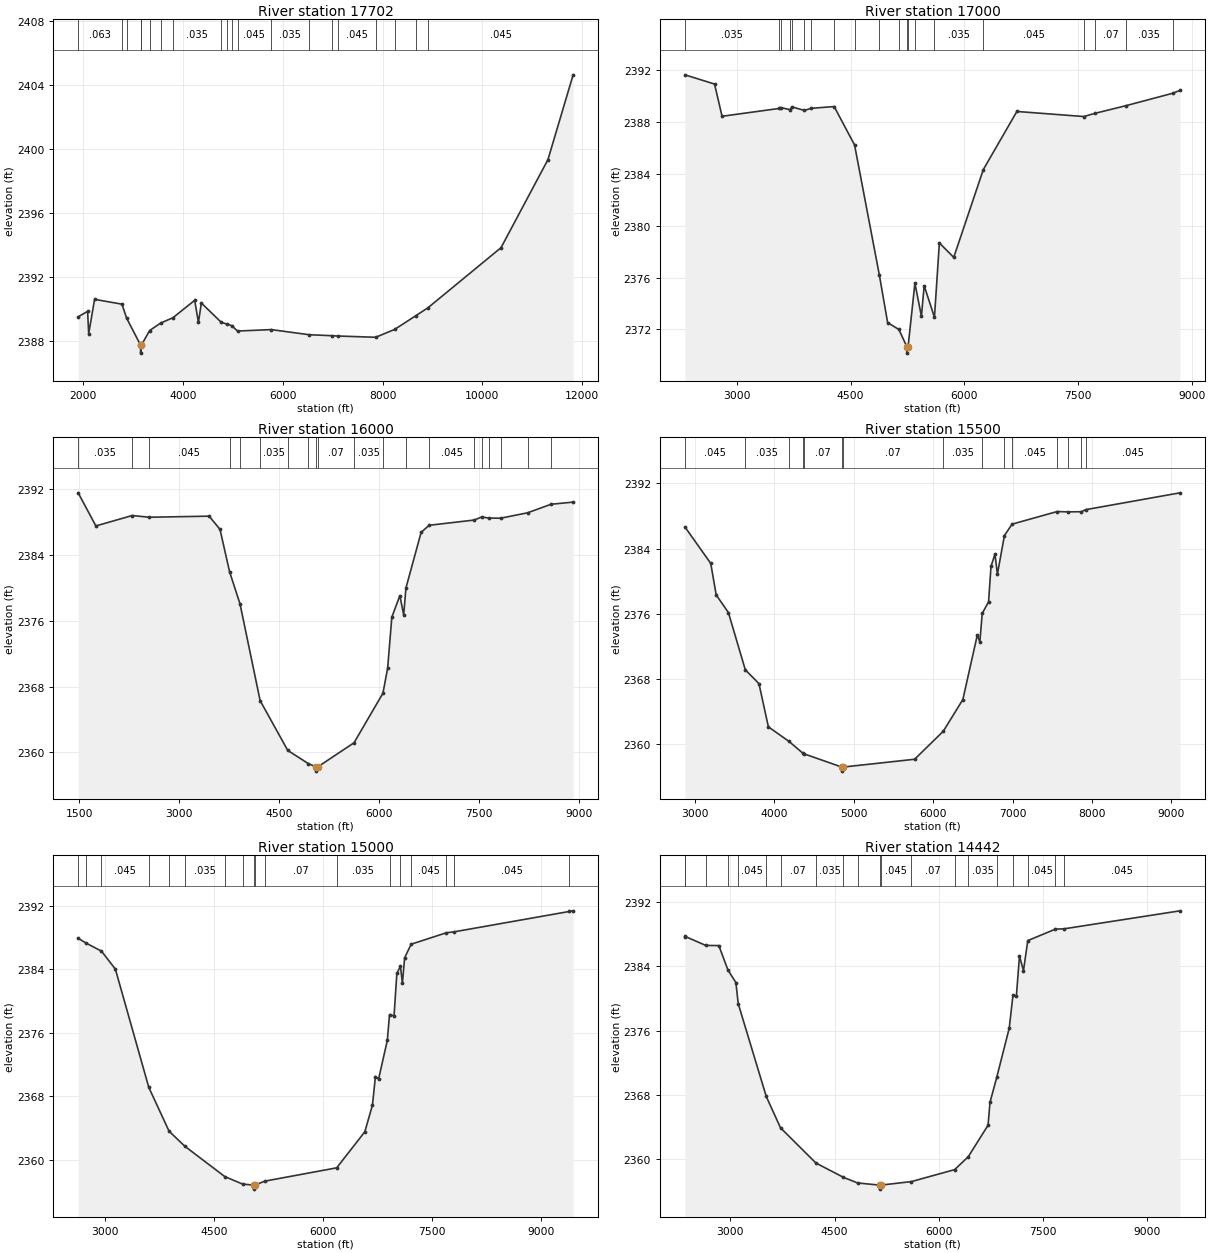
Type RM Length L Ch R = 1,17702,702,702,702
BEGIN DESCRIPTION:
Cottonwood Creek Trib034 35.0
END DESCRIPTION:
XS GIS Cut Line= 3
      1308035.90      6872566.99      1309571.31      6869872.65
      1309390.04      6863053.18
#Sta/Elev= 30
  1897.6 2389.49  2087.0 2389.83  2108.6 2388.44  2226.8 2390.58  2775.3 2390.28
  2868.5 2389.41  3149.0 2387.72  3149.5 2387.22  3165.8 2387.72  3329.9 2388.63
  3551.8 2389.10  3796.3 2389.43  4233.6 2390.52  4308.6 2389.14  4367.6 2390.35
  4764.7 2389.15  4883.0 2389.03  4975.4 2388.94  5092.5 2388.60  5767.9 2388.69
  6529.0 2388.37  6979.7 2388.31  7099.1 2388.29  7861.7 2388.21  8241.4 2388.70
  8672.6 2389.57  8908.5 2390.05 10375.3 2393.81 11315.6 2399.31 11820.6 2404.61
#Mann=20,-1,0
  1897.6   0.063       0  2775.3   0.035       0  2868.5   0.063       0
  3149.0   0.035       0  3165.8   0.063       0  3329.9   0.035       0
  3551.8   0.035       0  3796.3   0.035       0  4764.7   0.035       0
  4883.0   0.045       0  4975.4   0.035       0  5092.5   0.045       0
  5767.9   0.035       0  6529.0   0.045       0  6979.7   0.035       0
  7099.1   0.045       0  7861.7    0.07       0  8241.4   0.045       0
  8672.6    0.07       0  8908.5   0.045       0
Bank Sta=3149,3165.8
Exp/Cntr=0.3,0.1

Type RM Length L Ch R = 1,17000,1000,1000,1000
BEGIN DESCRIPTION:
Cottonwood Creek Trib034 34.0
END DESCRIPTION:
XS GIS Cut Line= 3
      1308556.72      6871837.85      1310230.06      6869737.79
      1309963.05      6865901.67
#Sta/Elev= 30
  2314.8 2391.60  2704.9 2390.89  2804.2 2388.41  3555.2 2389.01  3578.3 2389.08
  3700.7 2388.92  3726.4 2389.13  3891.2 2388.86  3978.4 2389.02  4283.2 2389.16
  4552.6 2386.20  4880.5 2376.16  4988.6 2372.53  5136.8 2372.00  5241.9 2370.68
  5242.4 2370.18  5258.8 2370.68  5348.6 2375.56  5434.4 2373.02  5470.9 2375.37
  5606.4 2372.94  5671.4 2378.66  5860.9 2377.55  6251.3 2384.31  6693.9 2388.78
  7577.6 2388.39  7727.1 2388.64  8129.7 2389.22  8749.1 2390.18  8845.4 2390.40
#Mann=20,-1,0
  2314.8   0.035       0  3555.2   0.045       0  3578.3   0.035       0
  3700.7   0.094       0  3726.4   0.035       0  3891.2   0.045       0
  3978.4   0.035       0  4283.2   0.045       0  4552.6   0.035       0
  4880.5   0.045       0  5136.8   0.035       0  5241.9   0.045       0
  5258.8   0.035       0  5348.6   0.063       0  5606.4   0.035       0
  6251.3   0.045       0  7577.6   0.035       0  7727.1    0.07       0
  8129.7   0.035       0  8749.1    0.07       0
Bank Sta=5241.9,5258.8
Exp/Cntr=0.3,0.1

Type RM Length L Ch R = 1,16000,500,500,500
BEGIN DESCRIPTION:
Cottonwood Creek Trib034 32.0
END DESCRIPTION:
XS GIS Cut Line= 3
      1308521.96      6871889.97      1311181.64      6869587.87
      1310015.05      6865848.31
#Sta/Elev= 30
  1482.4 2391.59  1748.6 2387.56  2294.7 2388.83  2547.2 2388.62  3449.7 2388.75
  3613.1 2387.14  3757.2 2381.97  3913.4 2378.08  4215.7 2366.30  4630.7 2360.24
  4940.7 2358.63  5061.8 2358.22  5062.3 2357.72  5078.8 2358.22  5626.0 2361.17
  6060.3 2367.20  6131.2 2370.26  6194.1 2376.46  6314.8 2379.08  6372.1 2376.73
  6406.0 2380.01  6634.0 2386.78  6754.2 2387.64  7434.3 2388.28  7544.2 2388.66
  7647.6 2388.52  7826.5 2388.50  8233.7 2389.16  8585.8 2390.20  8917.3 2390.46
#Mann=20,-1,0
  1482.4   0.035       0  2294.7    0.07       0  2547.2   0.045       0
  3757.2    0.07       0  3913.4   0.045       0  4215.7   0.035       0
  4630.7    0.07       0  4940.7    0.07       0  5061.8    0.07       0
  5078.8    0.07       0  5626.0   0.035       0  6060.3   0.063       0
  6406.0   0.035       0  6754.2   0.045       0  7434.3   0.035       0
  7544.2    0.07       0  7647.6   0.045       0  7826.5    0.07       0
  8233.7   0.045       0  8585.8   0.035       0
Bank Sta=5061.8,5078.8
Exp/Cntr=0.3,0.1

Type RM Length L Ch R = 1,15500,500,500,500
BEGIN DESCRIPTION:
Cottonwood Creek Trib034 31.0
END DESCRIPTION:
XS GIS Cut Line= 3
      1311920.34      6871828.67      1311596.58      6869727.47
      1310175.56      6865873.82
#Sta/Elev= 30
  2874.0 2386.65  3198.5 2382.18  3267.2 2378.31  3421.1 2376.13  3633.8 2369.10
  3805.5 2367.41  3924.4 2362.09  4182.9 2360.31  4362.7 2358.82  4375.2 2358.77
  4848.5 2357.15  4849.0 2356.65  4867.2 2357.15  5766.0 2358.11  6126.8 2361.55
  6373.3 2365.44  6555.9 2373.39  6587.5 2372.51  6617.4 2376.03  6697.4 2377.46
  6727.9 2381.81  6778.1 2383.32  6808.5 2380.86  6897.1 2385.60  6993.3 2387.00
  7560.4 2388.55  7695.2 2388.51  7865.8 2388.53  7920.2 2388.78  9107.3 2390.85
#Mann=15,-1,0
  2874.0   0.045       0  3633.8   0.035       0  4182.9    0.07       0
  4362.7   0.035       0  4375.2    0.07       0  4848.5    0.07       0
  4867.2    0.07       0  6126.8   0.035       0  6617.4   0.063       0
  6897.1   0.035       0  6993.3   0.045       0  7560.4   0.035       0
  7695.2   0.045       0  7865.8    0.07       0  7920.2   0.045       0
Bank Sta=4848.5,4867.2
Exp/Cntr=0.3,0.1

Type RM Length L Ch R = 1,15000,558,558,558
BEGIN DESCRIPTION:
Cottonwood Creek Trib034 30.0
END DESCRIPTION:
XS GIS Cut Line= 3
      1312595.25      6872073.88      1311922.35      6869805.69
      1310142.99      6865737.06
#Sta/Elev= 30
  2634.1 2387.90  2744.6 2387.28  2954.3 2386.28  3145.5 2384.02  3605.9 2369.12
  3884.3 2363.62  4100.7 2361.73  4650.1 2357.91  4894.3 2356.97  5047.1 2356.83
  5047.6 2356.33  5066.1 2356.83  5197.9 2357.33  6189.4 2359.01  6576.4 2363.55
  6680.9 2366.90  6722.0 2370.50  6765.6 2370.19  6885.7 2375.06  6915.6 2378.30
  6978.0 2378.13  7016.7 2383.47  7065.9 2384.38  7093.1 2382.24  7123.8 2385.45
  7213.5 2387.15  7697.7 2388.59  7805.5 2388.71  9388.1 2391.27  9440.7 2391.35
#Mann=18,-1,0
  2634.1   0.045       0  2744.6    0.07       0  2954.3   0.045       0
  3605.9   0.035       0  3884.3    0.07       0  4100.7   0.035       0
  4650.1    0.07       0  4894.3   0.045       0  5047.1   0.045       0
  5066.1   0.045       0  5197.9    0.07       0  6189.4   0.035       0
  6915.6   0.063       0  7065.9   0.035       0  7213.5   0.045       0
  7697.7   0.035       0  7805.5   0.045       0  9388.1   0.035       0
Bank Sta=5047.1,5066.1
Exp/Cntr=0.3,0.1

Type RM Length L Ch R = 1,14442,531,531,531
BEGIN DESCRIPTION:
Cottonwood Creek Trib034 29.0
END DESCRIPTION:
XS GIS Cut Line= 3
      1313409.04      6872084.71      1312235.22      6869709.15
      1310186.39      6865737.06
#Sta/Elev= 30
  2348.5 2387.72  2353.6 2387.71  2648.0 2386.60  2835.6 2386.58  2968.3 2383.50
  3081.0 2381.98  3114.2 2379.35  3517.8 2367.78  3722.5 2363.88  4232.3 2359.49
  4625.4 2357.72  4830.8 2357.01  5147.3 2356.74  5147.8 2356.24  5166.5 2356.74
  5605.5 2357.18  6227.4 2358.67  6423.4 2360.28  6707.7 2364.20  6735.5 2367.04
  6832.4 2370.16  7012.3 2376.29  7066.1 2380.41  7114.9 2380.28  7159.9 2385.28
  7217.3 2383.45  7279.0 2387.20  7676.5 2388.63  7802.2 2388.67  9467.6 2390.91
#Mann=20,-1,0
  2348.5   0.045       0  2353.6    0.07       0  2648.0   0.045       0
  2968.3   0.035       0  3114.2   0.045       0  3517.8   0.035       0
  3722.5    0.07       0  4232.3   0.035       0  4625.4    0.07       0
  4830.8   0.045       0  5147.3   0.045       0  5166.5   0.045       0
  5605.5    0.07       0  6227.4   0.035       0  6423.4   0.035       0
  6832.4   0.035       0  7066.1   0.063       0  7279.0   0.045       0
  7676.5   0.035       0  7802.2   0.045       0
Bank Sta=5147.3,5166.5
Exp/Cntr=0.3,0.1

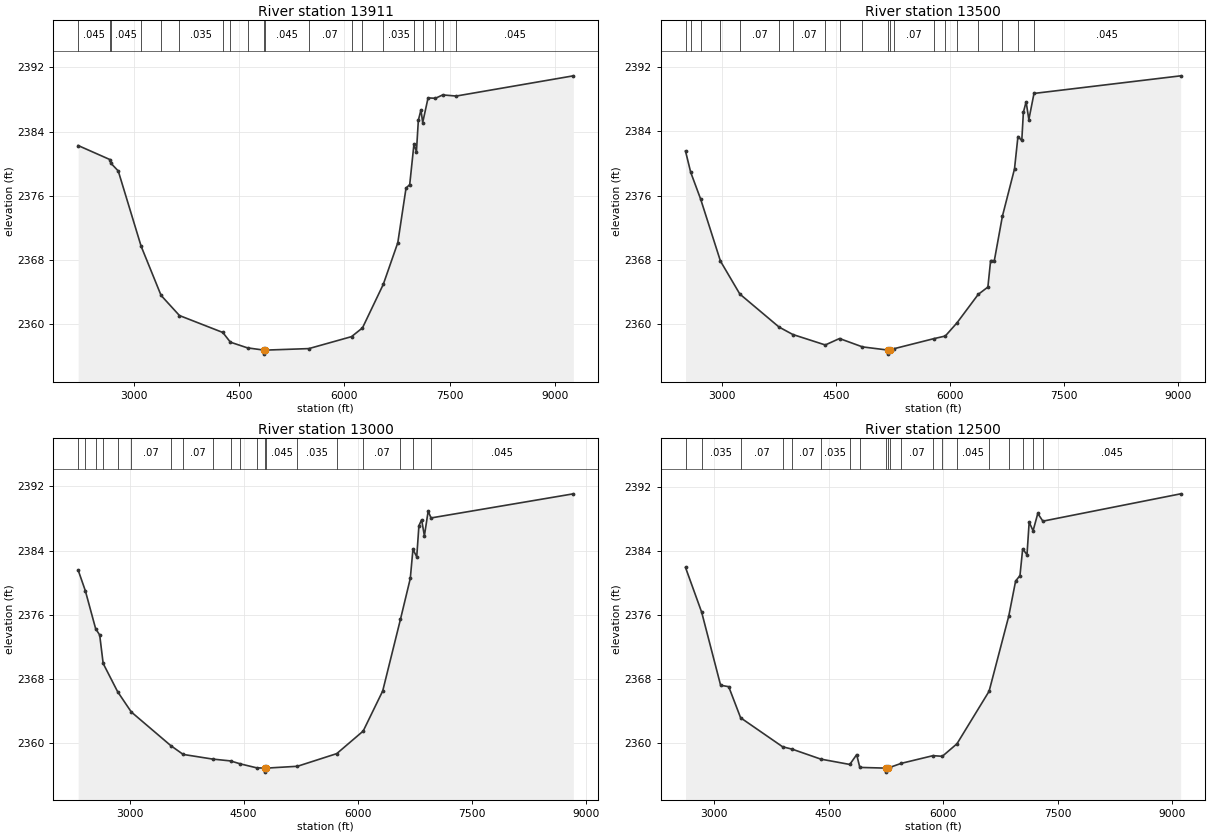
Type RM Length L Ch R = 1,13911,411,411,411
BEGIN DESCRIPTION:
Cottonwood Creek Trib034 28.0
END DESCRIPTION:
XS GIS Cut Line= 3
      1314277.09      6871520.47      1312498.33      6869484.22
      1310284.06      6865747.93
#Sta/Elev= 30
  2210.3 2382.27  2665.4 2380.51  2672.5 2380.10  2780.7 2379.10  3106.2 2369.72
  3390.2 2363.59  3651.7 2361.08  4268.6 2358.97  4376.7 2357.76  4620.1 2357.05
  4854.6 2356.77  4855.1 2356.27  4873.9 2356.77  5493.7 2356.96  6100.4 2358.45
  6256.3 2359.54  6552.2 2364.96  6759.1 2370.16  6876.1 2376.96  6928.8 2377.41
  6988.6 2382.41  7024.3 2381.52  7051.5 2385.42  7088.6 2386.71  7113.5 2385.14
  7189.9 2388.21  7294.5 2388.16  7397.8 2388.58  7590.5 2388.44  9257.2 2390.96
#Mann=20,-1,0
  2210.3   0.045       0  2665.4    0.07       0  2672.5   0.045       0
  3106.2   0.035       0  3390.2    0.07       0  3651.7   0.035       0
  4268.6   0.035       0  4376.7    0.07       0  4620.1   0.045       0
  4854.6   0.045       0  4873.9   0.045       0  5493.7    0.07       0
  6100.4   0.035       0  6256.3    0.07       0  6552.2   0.035       0
  6988.6   0.063       0  7113.5   0.035       0  7294.5   0.045       0
  7397.8   0.035       0  7590.5   0.045       0
Bank Sta=4854.6,4873.9
Exp/Cntr=0.3,0.1

Type RM Length L Ch R = 1,13500,500,500,500
BEGIN DESCRIPTION:
Cottonwood Creek Trib034 27.0
END DESCRIPTION:
XS GIS Cut Line= 3
      1314255.00      6871038.00      1312660.49      6869132.14
      1310404.25      6865781.72
#Sta/Elev= 30
  2515.1 2381.56  2583.5 2378.93  2714.2 2375.60  2975.6 2367.88  3231.2 2363.78
  3747.4 2359.68  3929.5 2358.75  4357.0 2357.45  4544.2 2358.25  4846.9 2357.21
  5185.1 2356.81  5185.6 2356.31  5204.5 2356.81  5261.0 2356.98  5785.5 2358.23
  5938.1 2358.56  6092.2 2360.20  6372.1 2363.74  6499.3 2364.65  6535.3 2367.94
  6584.3 2367.94  6690.3 2373.45  6850.2 2379.35  6895.3 2383.37  6946.0 2382.88
  6967.1 2386.39  7003.1 2387.69  7039.1 2385.48  7106.9 2388.73  9039.3 2390.92
#Mann=20,-1,0
  2515.1    0.07       0  2583.5   0.063       0  2714.2    0.07       0
  2975.6   0.035       0  3231.2    0.07       0  3747.4   0.035       0
  3929.5    0.07       0  4357.0    0.07       0  4544.2   0.094       0
  4846.9   0.045       0  5185.1   0.045       0  5204.5   0.045       0
  5261.0    0.07       0  5785.5   0.035       0  5938.1    0.07       0
  6092.2   0.045       0  6372.1    0.07       0  6690.3   0.035       0
  6895.3   0.063       0  7106.9   0.045       0
Bank Sta=5185.1,5204.5
Exp/Cntr=0.3,0.1

Type RM Length L Ch R = 1,13000,500,500,500
BEGIN DESCRIPTION:
Cottonwood Creek Trib034 26.0
END DESCRIPTION:
XS GIS Cut Line= 3
      1314755.01      6870638.01      1312855.68      6868754.35
      1310436.99      6865781.73
#Sta/Elev= 30
  2325.0 2381.55  2419.0 2378.98  2554.5 2374.24  2607.8 2373.45  2653.4 2369.90
  2843.7 2366.37  3023.2 2363.84  3543.4 2359.63  3705.3 2358.54  4091.6 2357.96
  4327.0 2357.73  4455.9 2357.36  4669.2 2356.87  4776.0 2356.83  4776.5 2356.33
  4795.5 2356.83  5206.5 2357.06  5723.1 2358.64  6070.7 2361.46  6326.9 2366.46
  6560.4 2375.41  6689.6 2380.51  6724.4 2384.14  6774.4 2383.22  6803.0 2387.10
  6838.8 2387.84  6874.9 2385.83  6924.4 2388.91  6962.6 2388.07  8832.3 2391.08
#Mann=20,-1,0
  2325.0    0.07       0  2419.0   0.063       0  2554.5   0.063       0
  2653.4   0.035       0  2843.7   0.035       0  3023.2    0.07       0
  3543.4   0.035       0  3705.3    0.07       0  4091.6   0.035       0
  4327.0    0.07       0  4455.9    0.07       0  4669.2   0.045       0
  4776.0   0.045       0  4795.5   0.045       0  5206.5   0.035       0
  5723.1   0.045       0  6070.7    0.07       0  6560.4   0.035       0
  6724.4   0.063       0  6962.6   0.045       0
Bank Sta=4776,4795.5
Exp/Cntr=0.3,0.1

Type RM Length L Ch R = 1,12500,500,500,500
BEGIN DESCRIPTION:
Cottonwood Creek Trib034 25.0
END DESCRIPTION:
XS GIS Cut Line= 3
      1314855.00      6870588.00      1313248.66      6868836.45
      1310544.44      6865737.03
#Sta/Elev= 30
  2623.4 2381.92  2834.9 2376.33  3083.7 2367.18  3189.8 2367.00  3345.8 2363.11
  3896.6 2359.48  4022.5 2359.18  4396.0 2357.94  4776.6 2357.27  4866.9 2358.50
  4908.0 2356.90  5253.6 2356.81  5254.1 2356.31  5273.2 2356.81  5309.7 2356.93
  5451.8 2357.41  5867.3 2358.37  5989.7 2358.29  6181.7 2359.86  6602.5 2366.43
  6859.7 2375.81  6950.2 2380.22  7007.2 2380.90  7042.8 2384.25  7099.2 2383.50
  7127.7 2387.59  7179.0 2386.51  7240.8 2388.67  7307.5 2387.71  9113.3 2391.13
#Mann=20,-1,0
  2623.4    0.07       0  2834.9   0.035       0  3345.8    0.07       0
  3896.6   0.035       0  4022.5    0.07       0  4396.0   0.035       0
  4776.6    0.07       0  4908.0   0.045       0  5253.6   0.045       0
  5273.2   0.045       0  5309.7   0.035       0  5451.8    0.07       0
  5867.3   0.045       0  5989.7   0.035       0  6181.7   0.045       0
  6602.5    0.07       0  6859.7   0.035       0  7042.8   0.063       0
  7179.0   0.035       0  7307.5   0.045       0
Bank Sta=5253.6,5273.2
Exp/Cntr=0.3,0.1