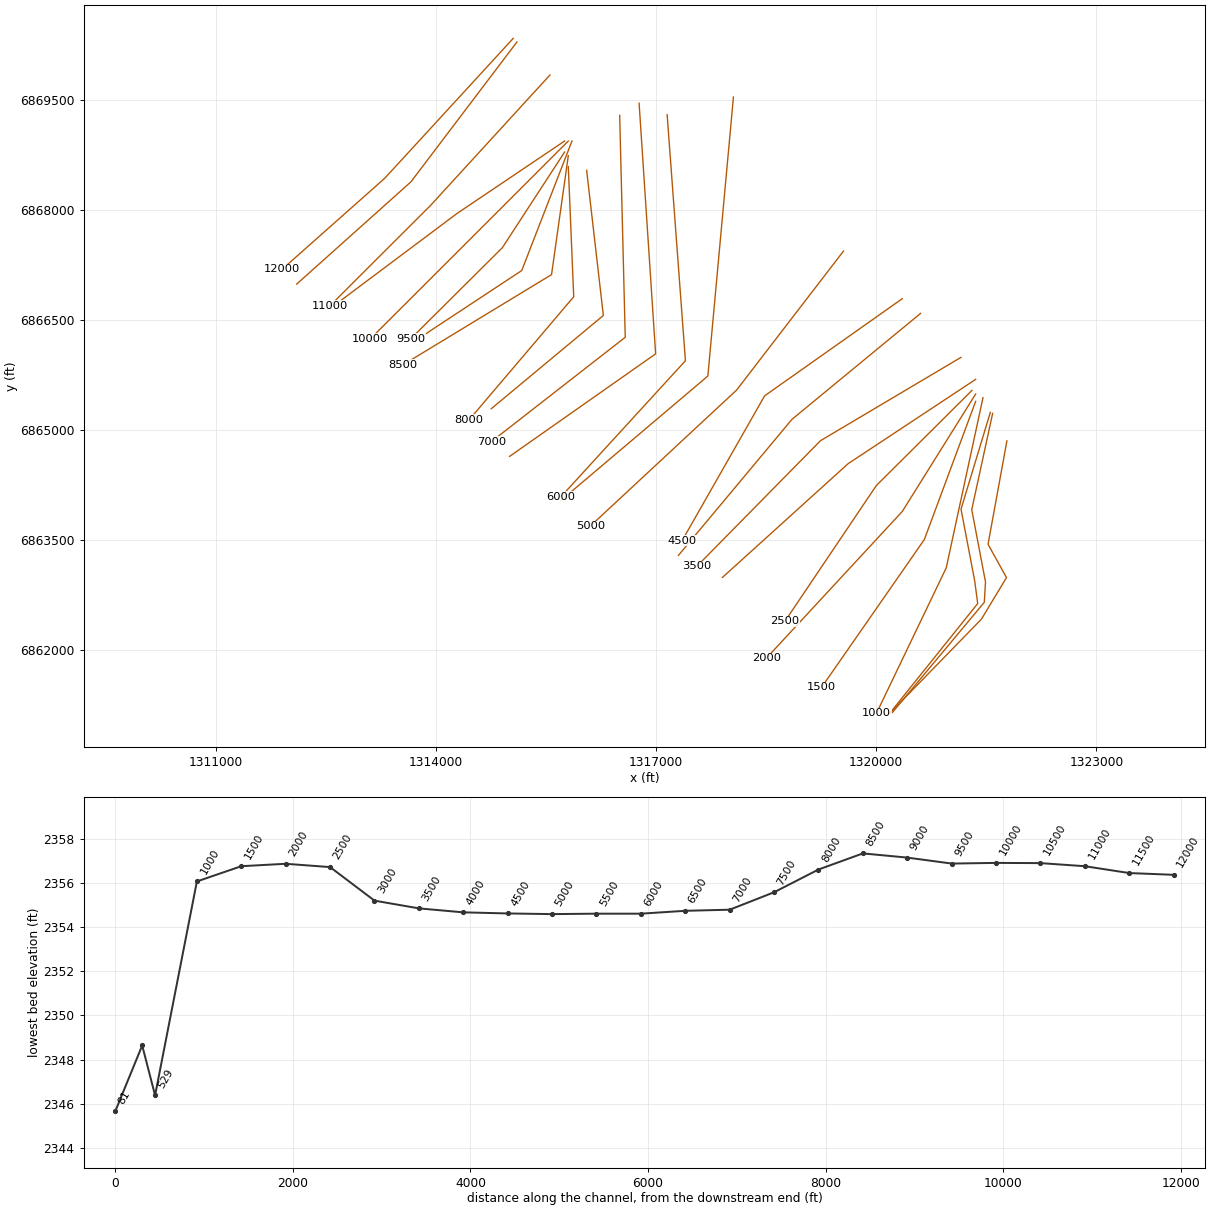
HEC-RAS study Cottonwood Creek Trib034.prj: Cottonwood Creek Trib034 Base Level Engineering

--- Cottonwood Creek Trib034.g01 (geometry) --- (continued)

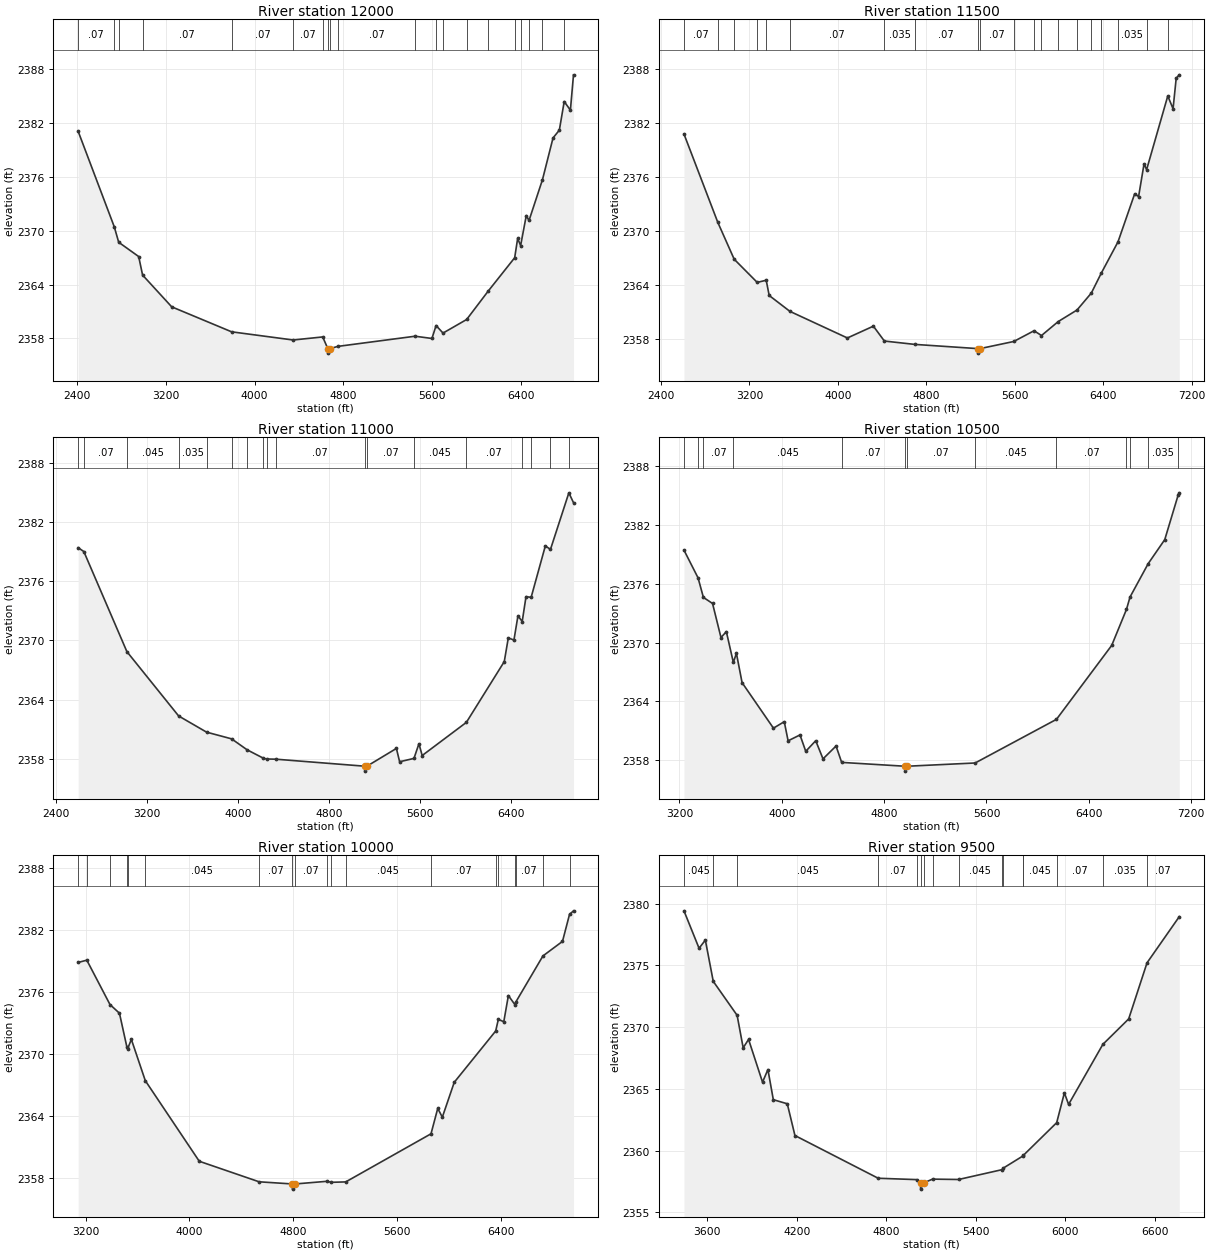
Type RM Length L Ch R = 1,12000,500,500,500
BEGIN DESCRIPTION:
Cottonwood Creek Trib034 24.0
END DESCRIPTION:
XS GIS Cut Line= 3
      1315055.03      6870338.03      1313304.56      6868430.61
      1311904.99      6867187.99
#Sta/Elev= 30
  2411.1 2381.03  2736.3 2370.41  2775.9 2368.70  2955.9 2367.11  2991.1 2365.05
  3253.1 2361.52  3792.8 2358.74  4346.6 2357.83  4613.2 2358.17  4659.0 2356.87
  4659.5 2356.37  4678.6 2356.87  4749.6 2357.12  5444.8 2358.25  5596.7 2358.00
  5634.1 2359.44  5696.6 2358.60  5909.3 2360.11  6101.0 2363.23  6341.9 2366.98
  6368.6 2369.12  6395.4 2368.33  6446.3 2371.67  6471.0 2371.12  6592.2 2375.66
  6687.2 2380.30  6744.1 2381.17  6787.9 2384.35  6843.6 2383.39  6871.6 2387.32
#Mann=20,-1,0
  2411.1    0.07       0  2736.3   0.045       0  2775.9   0.035       0
  2991.1    0.07       0  3792.8    0.07       0  4346.6    0.07       0
  4613.2   0.035       0  4659.0    0.07       0  4678.6   0.035       0
  4749.6    0.07       0  5444.8   0.035       0  5634.1    0.07       0
  5696.6   0.035       0  5909.3   0.045       0  6101.0   0.035       0
  6341.9    0.07       0  6395.4   0.035       0  6471.0    0.07       0
  6592.2   0.035       0  6787.9   0.063       0
Bank Sta=4659,4678.6
Exp/Cntr=0.3,0.1

Type RM Length L Ch R = 1,11500,500,500,500
BEGIN DESCRIPTION:
Cottonwood Creek Trib034 23.0
END DESCRIPTION:
XS GIS Cut Line= 3
      1315104.99      6870287.99      1313660.40      6868380.71
      1312105.00      6866988.00
#Sta/Elev= 30
  2607.4 2380.74  2913.6 2370.94  3061.6 2366.86  3269.9 2364.29  3351.3 2364.53
  3378.2 2362.84  3565.7 2361.08  4085.5 2358.13  4320.7 2359.44  4420.1 2357.79
  4693.0 2357.42  5265.3 2356.95  5265.8 2356.45  5285.0 2356.95  5590.2 2357.74
  5774.1 2358.93  5841.3 2358.40  5992.8 2359.95  6162.7 2361.23  6292.2 2363.11
  6382.3 2365.32  6533.5 2368.79  6684.5 2374.12  6719.6 2373.80  6768.9 2377.42
  6792.2 2376.79  6983.7 2384.96  7031.4 2383.54  7059.8 2386.92  7087.8 2387.30
#Mann=20,-1,0
  2607.4    0.07       0  2913.6   0.045       0  3061.6   0.035       0
  3269.9    0.07       0  3351.3   0.035       0  3565.7    0.07       0
  4420.1   0.035       0  4693.0    0.07       0  5265.3    0.07       0
  5285.0    0.07       0  5590.2   0.035       0  5774.1   0.035       0
  5841.3   0.045       0  5992.8   0.035       0  6162.7    0.07       0
  6292.2   0.035       0  6382.3    0.07       0  6533.5   0.035       0
  6792.2   0.035       0  6983.7   0.063       0
Bank Sta=5265.3,5285
Exp/Cntr=0.3,0.1

Type RM Length L Ch R = 1,11000,500,500,500
BEGIN DESCRIPTION:
Cottonwood Creek Trib034 22.0
END DESCRIPTION:
XS GIS Cut Line= 3
      1315555.00      6869838.00      1313932.77      6868064.80
      1312554.99      6866687.99
#Sta/Elev= 30
  2596.7 2379.40  2646.4 2379.01  3024.5 2368.87  3479.1 2362.35  3724.5 2360.71
  3944.5 2360.03  4080.6 2358.92  4223.4 2358.07  4251.3 2357.99  4332.4 2357.97
  5113.5 2357.26  5114.0 2356.76  5133.3 2357.26  5392.1 2359.06  5420.4 2357.71
  5546.5 2358.05  5590.1 2359.54  5618.4 2358.34  6006.7 2361.70  6339.7 2367.86
  6375.0 2370.26  6424.5 2370.04  6459.9 2372.50  6497.2 2371.92  6530.6 2374.44
  6575.7 2374.37  6700.3 2379.58  6745.5 2379.23  6907.0 2384.96  6947.8 2383.96
#Mann=18,-1,0
  2596.7   0.045       0  2646.4    0.07       0  3024.5   0.045       0
  3479.1   0.035       0  3724.5    0.07       0  3944.5   0.035       0
  4080.6   0.045       0  4223.4    0.07       0  4251.3   0.045       0
  4332.4    0.07       0  5113.5    0.07       0  5133.3    0.07       0
  5546.5   0.045       0  6006.7    0.07       0  6497.2   0.035       0
  6575.7    0.07       0  6745.5   0.035       0  6907.0   0.063       0
Bank Sta=5113.5,5133.3
Exp/Cntr=0.3,0.1

Type RM Length L Ch R = 1,10500,500,500,500
BEGIN DESCRIPTION:
Cottonwood Creek Trib034 21.0
END DESCRIPTION:
XS GIS Cut Line= 3
      1315755.00      6868938.00      1314291.38      6867951.75
      1312604.96      6866687.97
#Sta/Elev= 30
  3235.1 2379.43  3345.3 2376.60  3386.9 2374.61  3458.5 2373.99  3524.4 2370.52
  3566.4 2371.12  3621.1 2367.98  3645.1 2368.91  3689.4 2365.92  3934.5 2361.28
  4019.2 2361.94  4049.2 2359.99  4142.2 2360.59  4187.1 2358.92  4265.1 2360.00
  4322.1 2358.15  4424.0 2359.46  4467.9 2357.79  4961.6 2357.40  4962.1 2356.90
  4981.4 2357.40  5511.4 2357.73  6147.3 2362.18  6579.2 2369.72  6694.6 2373.39
  6722.3 2374.65  6864.2 2378.05  6993.8 2380.50  7098.7 2385.05  7107.4 2385.27
#Mann=13,-1,0
  3235.1   0.035       0  3345.3   0.045       0  3386.9    0.07       0
  3621.1   0.045       0  4467.9    0.07       0  4961.6    0.07       0
  4981.4    0.07       0  5511.4   0.045       0  6147.3    0.07       0
  6694.6   0.035       0  6722.3    0.07       0  6864.2   0.035       0
  7098.7   0.063       0
Bank Sta=4961.6,4981.4
Exp/Cntr=0.3,0.1

Type RM Length L Ch R = 1,10000,500,500,500
BEGIN DESCRIPTION:
Cottonwood Creek Trib034 20.0
END DESCRIPTION:
XS GIS Cut Line= 3
      1315804.99      6868937.99      1314492.52      6867624.41
      1313104.97      6866237.97
#Sta/Elev= 30
  3143.1 2378.87  3209.7 2379.09  3388.3 2374.79  3461.3 2373.95  3518.1 2370.70
  3524.4 2370.52  3553.2 2371.41  3660.4 2367.42  4076.5 2359.61  4537.9 2357.62
  4794.8 2357.41  4795.3 2356.91  4814.7 2357.41  5063.3 2357.67  5093.3 2357.57
  5205.7 2357.61  5863.0 2362.27  5914.9 2364.73  5950.3 2363.88  6042.2 2367.26
  6361.7 2372.23  6381.9 2373.35  6424.1 2373.13  6459.4 2375.66  6509.4 2374.79
  6515.6 2375.01  6725.8 2379.50  6876.6 2380.91  6930.7 2383.52  6961.5 2383.87
#Mann=19,-1,0
  3143.1   0.035       0  3209.7   0.045       0  3388.3    0.07       0
  3518.1   0.035       0  3524.4    0.07       0  3660.4   0.045       0
  4537.9    0.07       0  4794.8    0.07       0  4814.7    0.07       0
  5063.3   0.035       0  5093.3    0.07       0  5205.7   0.045       0
  5863.0    0.07       0  6361.7   0.035       0  6381.9    0.07       0
  6509.4   0.035       0  6515.6    0.07       0  6725.8   0.035       0
  6930.7   0.063       0
Bank Sta=4794.8,4814.7
Exp/Cntr=0.3,0.1

Type RM Length L Ch R = 1,9500,500,500,500
BEGIN DESCRIPTION:
Cottonwood Creek Trib034 19.0
END DESCRIPTION:
XS GIS Cut Line= 3
      1315755.01      6868788.02      1314906.15      6867483.24
      1313655.02      6866238.02
#Sta/Elev= 30
  3443.4 2379.41  3544.6 2376.38  3586.8 2377.04  3639.8 2373.70  3799.9 2370.95
  3840.4 2368.32  3876.6 2369.00  3970.2 2365.54  4006.4 2366.56  4042.6 2364.12
  4136.2 2363.79  4187.6 2361.22  4746.0 2357.76  5004.6 2357.65  5029.9 2357.38
  5030.4 2356.88  5049.8 2357.38  5110.5 2357.69  5284.9 2357.66  5578.0 2358.46
  5583.3 2358.57  5718.6 2359.58  5719.1 2359.61  5943.0 2362.26  5994.5 2364.67
  6022.8 2363.74  6252.6 2368.60  6425.8 2370.66  6548.8 2375.20  6765.2 2378.94
#Mann=16,-1,0
  3443.4   0.045       0  3639.8   0.035       0  3799.9   0.045       0
  4746.0    0.07       0  5004.6   0.045       0  5029.9    0.07       0
  5049.8   0.045       0  5110.5   0.035       0  5284.9   0.045       0
  5578.0   0.035       0  5583.3   0.045       0  5718.6   0.035       0
  5719.1   0.045       0  5943.0    0.07       0  6252.6   0.035       0
  6548.8    0.07       0
Bank Sta=5029.9,5049.8
Exp/Cntr=0.3,0.1

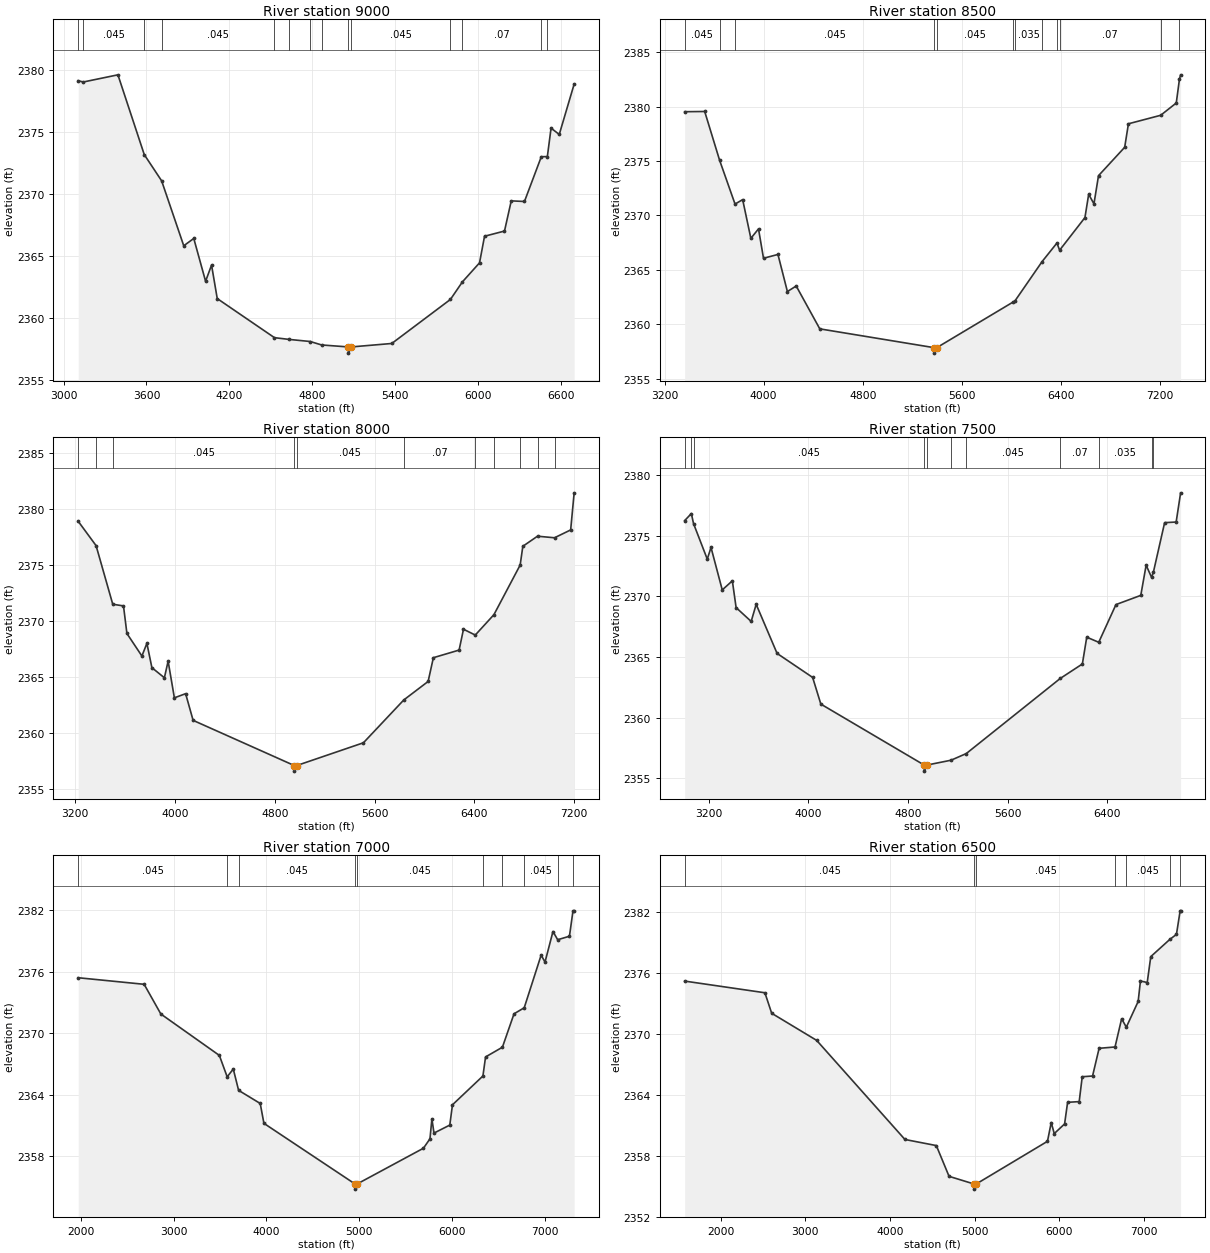
Type RM Length L Ch R = 1,9000,500,500,500
BEGIN DESCRIPTION:
Cottonwood Creek Trib034 18.0
END DESCRIPTION:
XS GIS Cut Line= 3
      1315855.01      6868938.01      1315170.64      6867172.19
      1313755.00      6866238.00
#Sta/Elev= 30
  3106.2 2379.17  3143.0 2379.07  3393.6 2379.65  3584.3 2373.20  3710.0 2371.08
  3870.1 2365.83  3942.7 2366.42  4028.2 2362.96  4071.4 2364.27  4112.6 2361.56
  4526.7 2358.40  4631.9 2358.26  4785.6 2358.09  4868.2 2357.81  5062.0 2357.65
  5062.5 2357.15  5081.9 2357.65  5376.0 2357.93  5800.4 2361.49  5887.3 2362.91
  6011.2 2364.45  6047.4 2366.60  6191.9 2367.02  6240.8 2369.46  6336.4 2369.41
  6458.4 2373.03  6502.1 2373.04  6529.0 2375.34  6588.3 2374.83  6696.1 2378.90
#Mann=14,-1,0
  3106.2   0.035       0  3143.0   0.045       0  3584.3   0.035       0
  3710.0   0.045       0  4526.7   0.035       0  4631.9   0.045       0
  4785.6   0.035       0  4868.2   0.045       0  5062.0   0.045       0
  5081.9   0.045       0  5800.4   0.035       0  5887.3    0.07       0
  6458.4   0.035       0  6502.1    0.07       0
Bank Sta=5062,5081.9
Exp/Cntr=0.3,0.1

Type RM Length L Ch R = 1,8500,500,500,500
BEGIN DESCRIPTION:
Cottonwood Creek Trib034 17.0
END DESCRIPTION:
XS GIS Cut Line= 3
      1315805.01      6868738.05      1315576.74      6867116.43
      1313554.99      6865888.00
#Sta/Elev= 30
  3362.4 2379.53  3524.0 2379.55  3644.2 2375.07  3768.9 2371.04  3830.4 2371.45
  3896.6 2367.89  3958.3 2368.76  3998.7 2366.06  4115.3 2366.41  4191.5 2363.00
  4262.7 2363.51  4453.1 2359.57  5377.0 2357.84  5377.5 2357.34  5397.0 2357.84
  6014.1 2362.04  6026.7 2362.11  6248.0 2365.76  6367.4 2367.46  6389.0 2366.80
  6593.4 2369.80  6623.5 2371.94  6666.1 2371.06  6702.9 2373.65  6914.2 2376.26
  6944.4 2378.42  7204.4 2379.20  7330.6 2380.33  7356.5 2382.54  7365.7 2382.92
#Mann=12,-1,0
  3362.4   0.045       0  3644.2   0.035       0  3768.9   0.045       0
  5377.0   0.045       0  5397.0   0.045       0  6014.1    0.07       0
  6026.7   0.035       0  6248.0    0.07       0  6367.4   0.035       0
  6389.0    0.07       0  7204.4   0.035       0  7356.5   0.063       0
Bank Sta=5377,5397
Exp/Cntr=0.3,0.1

Type RM Length L Ch R = 1,8000,500,500,500
BEGIN DESCRIPTION:
Cottonwood Creek Trib034 16.0
END DESCRIPTION:
XS GIS Cut Line= 3
      1315805.00      6868588.01      1315878.85      6866814.44
      1314455.00      6865138.00
#Sta/Elev= 30
  3224.9 2378.90  3368.0 2376.73  3501.7 2371.50  3587.8 2371.35  3615.2 2368.89
  3735.3 2366.88  3775.4 2368.01  3815.4 2365.84  3915.5 2364.94  3945.5 2366.42
  3995.6 2363.15  4085.7 2363.52  4145.7 2361.14  4956.1 2357.11  4956.6 2356.61
  4976.8 2357.11  5510.8 2359.14  5834.1 2362.96  6029.2 2364.61  6071.2 2366.73
  6277.5 2367.41  6312.6 2369.27  6407.0 2368.75  6556.6 2370.57  6766.9 2375.00
  6788.2 2376.67  6905.8 2377.57  7042.1 2377.43  7171.5 2378.13  7199.5 2381.44
#Mann=11,-1,0
  3224.9   0.045       0  3368.0   0.035       0  3501.7   0.045       0
  4956.1   0.045       0  4976.8   0.045       0  5834.1    0.07       0
  6407.0   0.035       0  6556.6    0.07       0  6766.9   0.063       0
  6905.8    0.07       0  7042.1   0.035       0
Bank Sta=4956.1,4976.8
Exp/Cntr=0.3,0.1

Type RM Length L Ch R = 1,7500,500,500,500
BEGIN DESCRIPTION:
Cottonwood Creek Trib034 15.0
END DESCRIPTION:
XS GIS Cut Line= 3
      1316055.00      6868537.97      1316282.78      6866559.64
      1314754.97      6865287.97
#Sta/Elev= 30
  3008.6 2376.25  3062.2 2376.83  3079.7 2376.00  3189.8 2373.07  3220.0 2374.03
  3310.0 2370.53  3391.1 2371.28  3421.3 2369.07  3542.1 2367.93  3582.3 2369.34
  3750.1 2365.29  4035.3 2363.31  4101.1 2361.11  4930.6 2356.08  4931.1 2355.58
  4952.0 2356.08  5145.6 2356.48  5268.1 2357.03  6022.6 2363.23  6199.5 2364.42
  6234.6 2366.63  6330.9 2366.21  6469.0 2369.32  6668.2 2370.08  6711.1 2372.57
  6754.5 2371.57  6769.5 2372.00  6859.5 2376.08  6952.0 2376.13  6987.8 2378.54
#Mann=11,-1,0
  3008.6   0.045       0  3062.2   0.035       0  3079.7   0.045       0
  4930.6   0.045       0  4952.0   0.045       0  5145.6    0.07       0
  5268.1   0.045       0  6022.6    0.07       0  6330.9   0.035       0
  6754.5    0.07       0  6769.5   0.063       0
Bank Sta=4930.6,4952
Exp/Cntr=0.3,0.1

Type RM Length L Ch R = 1,7000,500,500,500
BEGIN DESCRIPTION:
Cottonwood Creek Trib034 14.0
END DESCRIPTION:
XS GIS Cut Line= 3
      1316505.00      6869288.01      1316580.91      6866262.07
      1314754.99      6864837.99
#Sta/Elev= 30
  1973.1 2375.42  2683.3 2374.78  2863.4 2371.88  3493.6 2367.84  3577.7 2365.75
  3643.6 2366.51  3700.9 2364.43  3933.7 2363.15  3973.7 2361.21  4955.5 2355.29
  4956.0 2354.79  4977.0 2355.29  5691.8 2358.78  5762.4 2359.70  5783.2 2361.64
  5805.8 2360.26  5975.9 2361.04  6004.8 2363.02  6332.8 2365.83  6361.2 2367.69
  6542.8 2368.64  6667.9 2371.90  6777.8 2372.49  6960.1 2377.63  7001.7 2376.95
  7087.3 2379.93  7138.2 2379.13  7264.9 2379.47  7303.0 2381.94  7315.6 2381.95
#Mann=10,-1,0
  1973.1   0.045       0  3577.7    0.07       0  3700.9   0.045       0
  4955.5   0.045       0  4977.0   0.045       0  6332.8   0.035       0
  6542.8    0.07       0  6777.8   0.045       0  7138.2   0.035       0
  7303.0   0.063       0
Bank Sta=4955.5,4977
Exp/Cntr=0.3,0.1

Type RM Length L Ch R = 1,6500,500,500,500
BEGIN DESCRIPTION:
Cottonwood Creek Trib034 13.0
END DESCRIPTION:
XS GIS Cut Line= 3
      1316769.64      6869453.26      1316994.92      6866036.18
      1315005.01      6864638.00
#Sta/Elev= 30
  1575.5 2375.23  2522.8 2374.08  2603.0 2372.06  3134.1 2369.39  4176.4 2359.63
  4547.2 2359.03  4697.5 2356.00  4994.6 2355.24  4995.1 2354.74  5017.0 2355.24
  5859.7 2359.45  5904.1 2361.30  5939.8 2360.21  6061.8 2361.16  6097.5 2363.29
  6234.3 2363.36  6270.1 2365.81  6392.1 2365.88  6469.6 2368.61  6657.4 2368.74
  6735.4 2371.52  6790.8 2370.69  6930.5 2373.22  6957.6 2375.24  7037.7 2375.09
  7079.6 2377.64  7303.8 2379.33  7382.8 2379.83  7425.2 2382.09  7432.0 2382.15
#Mann=7,-1,0
  1575.5   0.045       0  4994.6   0.045       0  5017.0   0.045       0
  6657.4    0.07       0  6790.8   0.045       0  7303.8   0.035       0
  7425.2   0.063       0
Bank Sta=4994.6,5017
Exp/Cntr=0.3,0.1

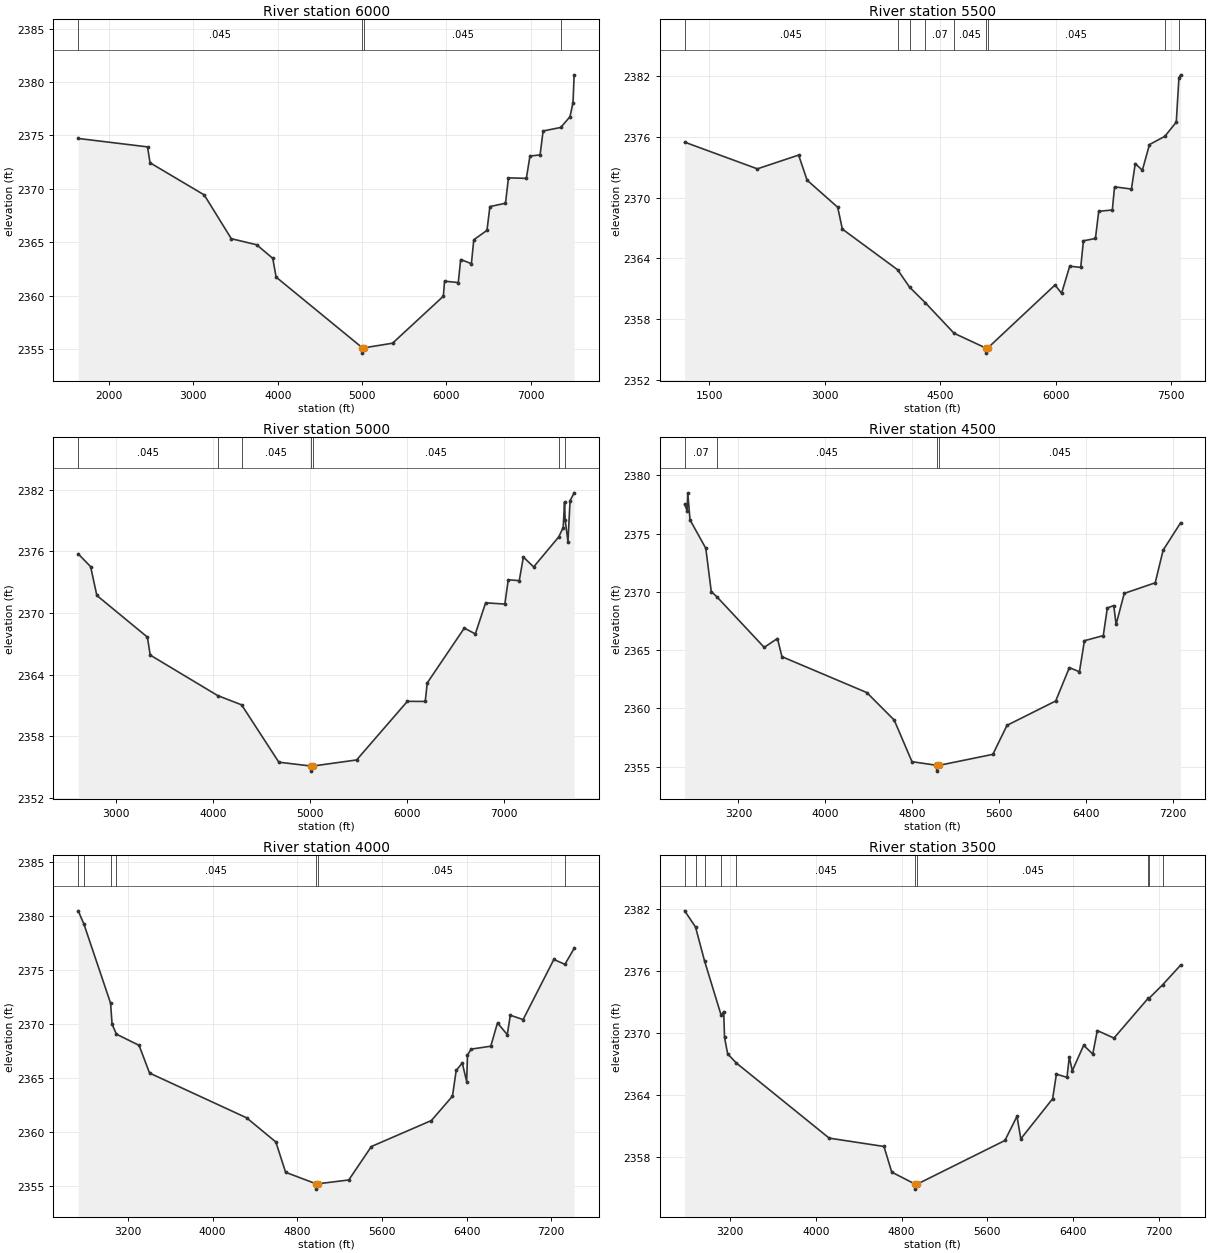
Type RM Length L Ch R = 1,6000,500,500,500
BEGIN DESCRIPTION:
Cottonwood Creek Trib034 12.0
END DESCRIPTION:
XS GIS Cut Line= 3
      1317151.59      6869296.98      1317400.70      6865942.32
      1315705.03      6864088.03
#Sta/Elev= 30
  1636.1 2374.72  2457.3 2373.93  2487.4 2372.44  3129.2 2369.43  3450.1 2365.33
  3750.9 2364.76  3941.4 2363.49  3981.5 2361.73  5003.0 2355.11  5003.5 2354.61
  5025.5 2355.11  5360.8 2355.54  5962.7 2359.94  5976.9 2361.35  6139.7 2361.22
  6168.1 2363.38  6295.1 2362.99  6323.5 2365.23  6479.5 2366.11  6514.6 2368.34
  6699.0 2368.65  6734.2 2371.03  6946.3 2370.98  6988.9 2373.07  7109.1 2373.18
  7144.9 2375.42  7353.0 2375.75  7463.1 2376.75  7498.9 2378.08  7512.7 2380.68
#Mann=4,-1,0
  1636.1   0.045       0  5003.0   0.045       0  5025.5   0.045       0
  7353.0   0.035       0
Bank Sta=5003,5025.5
Exp/Cntr=0.3,0.1

Type RM Length L Ch R = 1,5500,500,500,500
BEGIN DESCRIPTION:
Cottonwood Creek Trib034 11.0
END DESCRIPTION:
XS GIS Cut Line= 3
      1318055.00      6869537.96      1317706.43      6865733.49
      1315704.96      6864037.97
#Sta/Elev= 30
  1179.6 2375.48  2123.5 2372.84  2660.0 2374.20  2770.0 2371.72  3167.8 2369.04
  3228.1 2366.88  3945.9 2362.86  4102.1 2361.13  4307.9 2359.58  4678.9 2356.58
  5092.9 2355.11  5093.4 2354.61  5116.4 2355.11  5991.1 2361.35  6076.6 2360.53
  6182.2 2363.21  6325.1 2363.09  6360.3 2365.72  6516.2 2365.95  6559.1 2368.64
  6735.9 2368.77  6764.5 2371.06  6984.2 2370.84  7033.6 2373.36  7125.9 2372.70
  7218.2 2375.24  7418.6 2376.06  7566.5 2377.46  7601.4 2381.87  7623.1 2382.14
#Mann=9,-1,0
  1179.6   0.045       0  3945.9    0.07       0  4102.1   0.045       0
  4307.9    0.07       0  4678.9   0.045       0  5092.9   0.045       0
  5116.4   0.045       0  7418.6   0.035       0  7601.4   0.063       0
Bank Sta=5092.9,5116.4
Exp/Cntr=0.3,0.1

Type RM Length L Ch R = 1,5000,500,500,500
BEGIN DESCRIPTION:
Cottonwood Creek Trib034 10.0
END DESCRIPTION:
XS GIS Cut Line= 3
      1319554.98      6867437.98      1318097.97      6865542.20
      1316105.02      6863688.02
#Sta/Elev= 30
  2609.0 2375.76  2736.7 2374.52  2801.1 2371.71  3322.2 2367.65  3351.2 2365.90
  4047.4 2361.95  4293.5 2361.05  4677.4 2355.46  5006.9 2355.09  5007.4 2354.59
  5031.1 2355.09  5479.3 2355.68  6002.5 2361.39  6186.7 2361.38  6207.7 2363.19
  6589.8 2368.53  6703.2 2367.96  6809.2 2370.99  7007.6 2370.87  7042.7 2373.24
  7156.1 2373.15  7198.6 2375.45  7304.6 2374.49  7563.5 2377.42  7609.0 2378.33
  7623.2 2380.80  7629.3 2379.08  7658.4 2376.96  7679.9 2380.94  7722.1 2381.71
#Mann=7,-1,0
  2609.0   0.045       0  4047.4    0.07       0  4293.5   0.045       0
  5006.9   0.045       0  5031.1   0.045       0  7563.5   0.035       0
  7629.3   0.063       0
Bank Sta=5006.9,5031.1
Exp/Cntr=0.3,0.1

Type RM Length L Ch R = 1,4500,500,500,500
BEGIN DESCRIPTION:
Cottonwood Creek Trib034 9.0
END DESCRIPTION:
XS GIS Cut Line= 3
      1320355.01      6866788.01      1318479.99      6865463.77
      1317355.00      6863488.00
#Sta/Elev= 30
  2704.5 2377.50  2726.7 2376.98  2732.8 2378.50  2753.7 2376.18  2899.1 2373.74
  2949.4 2370.03  3002.0 2369.57  3437.1 2365.24  3559.0 2366.00  3600.8 2364.44
  4382.6 2361.36  4635.0 2359.00  4798.7 2355.43  5025.8 2355.12  5026.3 2354.62
  5050.1 2355.12  5543.7 2356.06  5674.1 2358.55  6122.9 2360.64  6248.3 2363.50
  6341.5 2363.15  6387.5 2365.81  6561.0 2366.25  6598.5 2368.62  6657.6 2368.83
  6679.2 2367.21  6754.1 2369.87  7039.4 2370.78  7112.5 2373.58  7273.6 2375.93
#Mann=4,-1,0
  2704.5    0.07       0  3002.0   0.045       0  5025.8   0.045       0
  5050.1   0.045       0
Bank Sta=5025.8,5050.1
Exp/Cntr=0.3,0.1

Type RM Length L Ch R = 1,4000,500,500,500
BEGIN DESCRIPTION:
Cottonwood Creek Trib034 8.0
END DESCRIPTION:
XS GIS Cut Line= 3
      1320604.98      6866587.98      1318852.86      6865143.78
      1317304.98      6863287.98
#Sta/Elev= 30
  2729.4 2380.47  2783.7 2379.23  3035.5 2371.90  3049.3 2369.97  3090.3 2369.04
  3304.6 2368.00  3403.6 2365.43  4321.0 2361.28  4597.2 2359.04  4689.7 2356.23
  4975.9 2355.17  4976.4 2354.67  5000.3 2355.17  5286.5 2355.52  5500.0 2358.62
  6067.5 2361.03  6266.6 2363.29  6301.7 2365.67  6359.0 2366.36  6400.9 2364.64
  6408.5 2367.11  6443.6 2367.65  6628.4 2367.92  6692.2 2370.08  6784.6 2368.99
  6813.3 2370.79  6934.3 2370.39  7224.6 2375.96  7329.4 2375.51  7416.6 2376.99
#Mann=7,-1,0
  2729.4   0.035       0  2783.7    0.07       0  3035.5   0.035       0
  3090.3   0.045       0  4975.9   0.045       0  5000.3   0.045       0
  7329.4    0.07       0
Bank Sta=4975.9,5000.3
Exp/Cntr=0.3,0.1

Type RM Length L Ch R = 1,3500,500,500,500
BEGIN DESCRIPTION:
Cottonwood Creek Trib034 7.0
END DESCRIPTION:
XS GIS Cut Line= 3
      1321155.03      6865988.02      1319240.86      6864852.19
      1317554.98      6863137.98
#Sta/Elev= 30
  2774.2 2381.86  2875.5 2380.29  2959.3 2377.01  3115.2 2371.71  3138.6 2372.08
  3146.3 2369.57  3175.7 2367.97  3256.6 2367.09  4123.1 2359.80  4634.7 2358.99
  4707.4 2356.50  4923.2 2355.35  4923.7 2354.85  4947.7 2355.35  5763.7 2359.57
  5876.8 2361.92  5912.2 2359.73  6209.3 2363.62  6244.6 2366.01  6343.6 2365.70
  6364.8 2367.67  6393.1 2366.34  6499.1 2368.81  6584.0 2367.96  6626.4 2370.24
  6782.0 2369.51  7102.0 2373.38  7107.7 2373.35  7237.0 2374.69  7404.3 2376.59
#Mann=10,-1,0
  2774.2    0.07       0  2875.5    0.16       0  2959.3    0.07       0
  3115.2   0.035       0  3256.6   0.045       0  4923.2   0.045       0
  4947.7   0.045       0  7102.0    0.07       0  7107.7   0.045       0
  7237.0    0.07       0
Bank Sta=4923.2,4947.7
Exp/Cntr=0.3,0.1

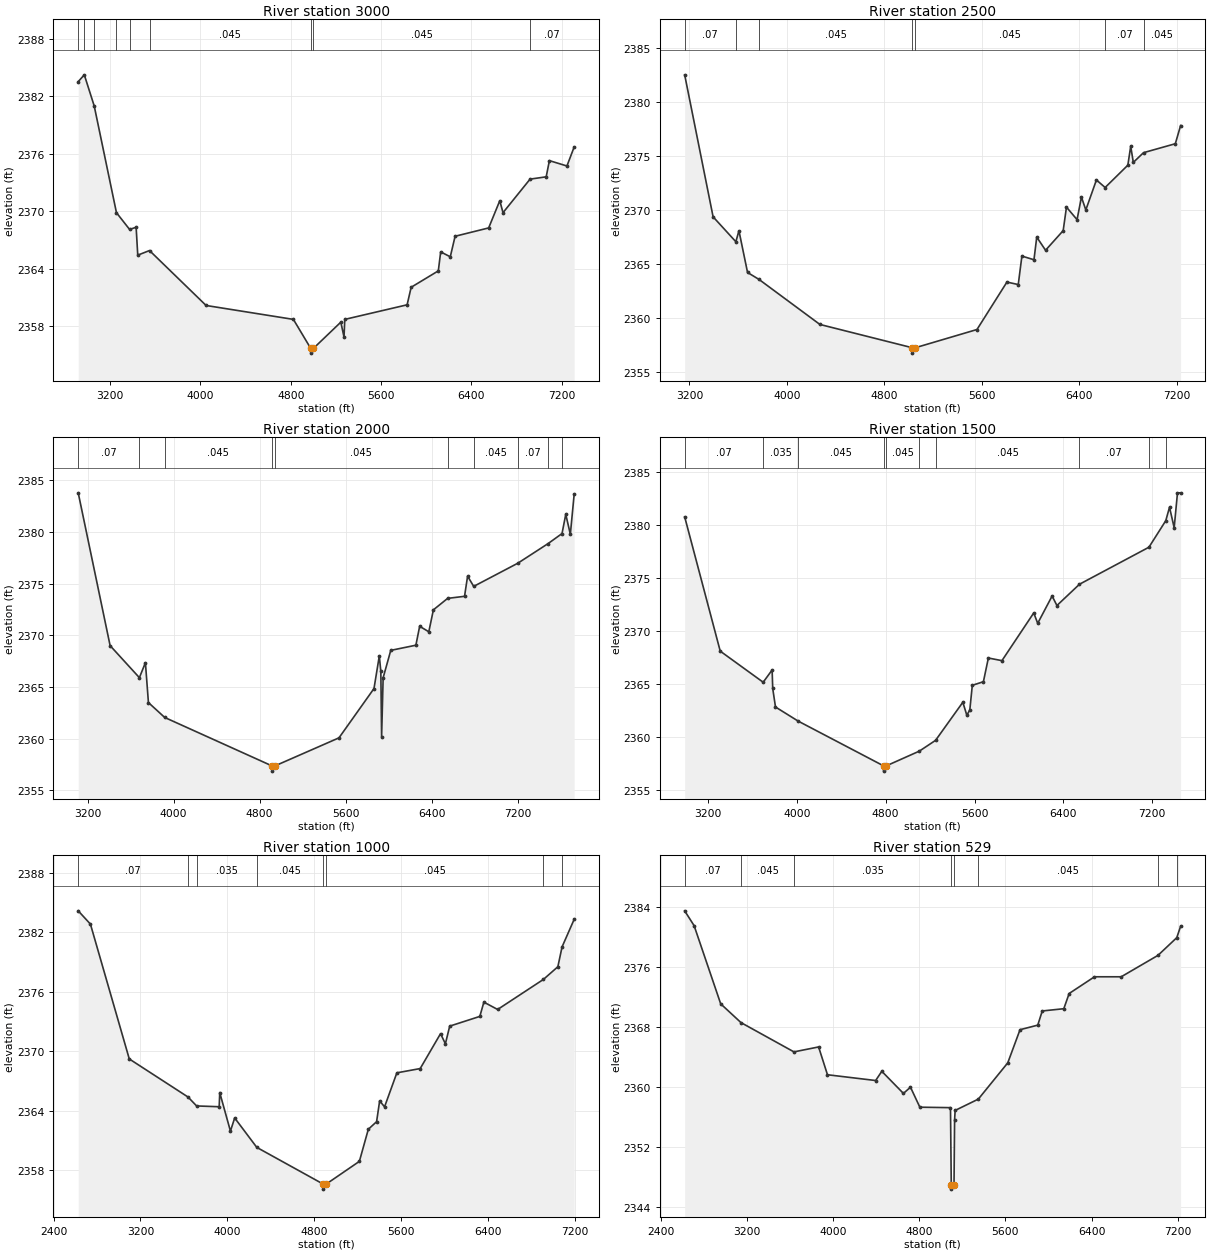
Type RM Length L Ch R = 1,3000,500,500,500
BEGIN DESCRIPTION:
Cottonwood Creek Trib034 6.0
END DESCRIPTION:
XS GIS Cut Line= 3
      1321354.98      6865687.99      1319617.99      6864539.22
      1317904.98      6862987.98
#Sta/Elev= 30
  2917.5 2383.52  2971.5 2384.23  3059.3 2380.98  3256.3 2369.85  3372.8 2368.10
  3430.6 2368.33  3445.0 2365.42  3549.1 2365.90  4050.5 2360.17  4823.7 2358.72
  4977.0 2355.70  4977.5 2355.20  5001.7 2355.70  5243.9 2358.43  5272.3 2356.88
  5279.0 2358.72  5831.2 2360.24  5867.0 2362.07  6107.6 2363.78  6128.6 2365.76
  6213.7 2365.25  6256.3 2367.39  6553.7 2368.26  6652.3 2371.10  6680.7 2369.85
  6920.5 2373.35  7063.3 2373.59  7091.7 2375.28  7247.1 2374.72  7311.0 2376.70
#Mann=9,-1,0
  2917.5    0.07       0  2971.5   0.045       0  3059.3    0.07       0
  3256.3    0.16       0  3372.8   0.035       0  3549.1   0.045       0
  4977.0   0.045       0  5001.7   0.045       0  6920.5    0.07       0
Bank Sta=4977,5001.7
Exp/Cntr=0.3,0.1

Type RM Length L Ch R = 1,2500,500,500,500
BEGIN DESCRIPTION:
Cottonwood Creek Trib034 5.0
END DESCRIPTION:
XS GIS Cut Line= 3
      1321305.02      6865538.02      1320002.09      6864240.92
      1318755.00      6862388.00
#Sta/Elev= 30
  3161.5 2382.53  3394.9 2369.36  3581.8 2367.05  3607.0 2368.07  3677.7 2364.20
  3772.5 2363.55  4271.7 2359.38  5030.2 2357.22  5030.7 2356.72  5055.1 2357.22
  5561.5 2358.91  5807.4 2363.31  5900.4 2363.08  5930.3 2365.72  6029.4 2365.38
  6052.2 2367.48  6124.5 2366.26  6269.2 2368.08  6296.3 2370.26  6383.2 2369.10
  6419.2 2371.19  6455.2 2370.00  6542.2 2372.78  6613.7 2372.08  6800.2 2374.15
  6823.7 2375.91  6845.1 2374.41  6928.9 2375.31  7190.0 2376.14  7233.5 2377.83
#Mann=7,-1,0
  3161.5    0.07       0  3581.8   0.035       0  3772.5   0.045       0
  5030.2   0.045       0  5055.1   0.045       0  6613.7    0.07       0
  6928.9   0.045       0
Bank Sta=5030.2,5055.1
Exp/Cntr=0.3,0.1

Type RM Length L Ch R = 1,2000,500,500,500
BEGIN DESCRIPTION:
Cottonwood Creek Trib034 4.0
END DESCRIPTION:
XS GIS Cut Line= 3
      1321355.00      6865488.00      1320355.64      6863887.36
      1318505.00      6861888.00
#Sta/Elev= 30
  3113.0 2383.79  3409.6 2369.01  3681.8 2365.91  3737.8 2367.36  3765.9 2363.50
  3917.5 2362.06  4916.1 2357.37  4916.6 2356.87  4941.0 2357.37  5537.8 2360.09
  5863.3 2364.86  5912.6 2368.01  5926.8 2366.52  5934.1 2360.20  5948.3 2365.90
  6019.2 2368.55  6252.7 2369.05  6287.9 2370.88  6373.0 2370.35  6415.5 2372.47
  6547.9 2373.58  6705.2 2373.78  6733.6 2375.73  6790.4 2374.74  7200.3 2376.98
  7482.1 2378.88  7611.6 2379.85  7646.4 2381.71  7689.0 2379.78  7724.4 2383.64
#Mann=10,-1,0
  3113.0    0.07       0  3681.8   0.035       0  3917.5   0.045       0
  4916.1   0.045       0  4941.0   0.045       0  6547.9    0.07       0
  6790.4   0.045       0  7200.3    0.07       0  7482.1   0.035       0
  7611.6   0.063       0
Bank Sta=4916.1,4941
Exp/Cntr=0.3,0.1

Type RM Length L Ch R = 1,1500,500,500,500
BEGIN DESCRIPTION:
Cottonwood Creek Trib034 3.0
END DESCRIPTION:
XS GIS Cut Line= 3
      1321355.00      6865388.00      1320655.80      6863504.17
      1319255.02      6861488.03
#Sta/Elev= 30
  2990.6 2380.79  3310.6 2368.10  3697.3 2365.16  3777.8 2366.32  3783.1 2364.57
  3808.1 2362.82  4011.7 2361.49  4780.7 2357.26  4781.2 2356.76  4805.8 2357.26
  5103.0 2358.65  5249.2 2359.67  5494.6 2363.27  5530.5 2362.04  5557.5 2362.55
  5579.8 2364.87  5679.7 2365.21  5724.3 2367.45  5846.5 2367.20  6132.8 2371.71
  6168.6 2370.73  6298.2 2373.31  6341.5 2372.41  6544.4 2374.42  7169.8 2377.92
  7321.5 2380.43  7355.1 2381.70  7397.0 2379.76  7426.7 2383.05  7455.0 2383.06
#Mann=10,-1,0
  2990.6    0.07       0  3697.3   0.035       0  4011.7   0.045       0
  4780.7   0.045       0  4805.8   0.045       0  5103.0    0.07       0
  5249.2   0.045       0  6544.4    0.07       0  7169.8   0.035       0
  7321.5   0.063       0
Bank Sta=4780.7,4805.8
Exp/Cntr=0.3,0.1

Type RM Length L Ch R = 1,1000,471,471,471
BEGIN DESCRIPTION:
Cottonwood Creek Trib034 2.0
END DESCRIPTION:
XS GIS Cut Line= 3
      1321454.99      6865437.96      1320954.48      6863118.75
      1320004.98      6861137.97
#Sta/Elev= 30
  2627.4 2384.14  2739.9 2382.80  3097.9 2369.20  3639.2 2365.36  3718.2 2364.46
  3926.2 2364.38  3931.3 2365.81  4029.9 2361.92  4068.9 2363.25  4272.7 2360.28
  4885.9 2356.57  4886.4 2356.07  4911.0 2356.57  5217.8 2358.87  5300.3 2362.11
  5376.4 2362.87  5404.6 2364.97  5449.9 2364.37  5563.2 2367.80  5778.2 2368.23
  5965.6 2371.75  6010.3 2370.73  6050.1 2372.51  6327.5 2373.49  6364.8 2374.93
  6491.7 2374.19  6913.2 2377.22  7046.5 2378.50  7085.2 2380.50  7196.6 2383.28
#Mann=8,-1,0
  2627.4    0.07       0  3639.2   0.045       0  3718.2   0.035       0
  4272.7   0.045       0  4885.9   0.045       0  4911.0   0.045       0
  6913.2   0.035       0  7085.2   0.063       0
Bank Sta=4885.9,4911
Exp/Cntr=0.3,0.1

Type RM Length L Ch R = 1,529,145,145,145
BEGIN DESCRIPTION:
Cottonwood Creek Trib034 1.0
END DESCRIPTION:
XS GIS Cut Line= 5
      1321555.01      6865238.04      1321155.95      6863919.14
      1321343.45      6862933.03      1321383.03      6862631.64
      1320183.75      6861134.45
#Sta/Elev= 30
  2623.3 2383.51  2710.9 2381.53  2957.7 2371.10  3145.7 2368.60  3637.7 2364.69
  3866.6 2365.35  3948.9 2361.64  4396.0 2360.87  4453.3 2362.10  4653.9 2359.15
  4719.5 2359.98  4806.6 2357.31  5090.8 2357.25  5098.3 2346.88  5098.8 2346.38
  5123.6 2346.88  5129.1 2355.65  5134.1 2356.88  5349.4 2358.39  5622.7 2363.23
  5736.5 2367.65  5901.2 2368.26  5942.8 2370.15  6142.9 2370.45  6192.5 2372.48
  6427.7 2374.71  6675.8 2374.71  7017.3 2377.57  7191.7 2379.93  7227.3 2381.45
#Mann=8,-1,0
  2623.3    0.07       0  3145.7   0.045       0  3637.7   0.035       0
  5098.3   0.035       0  5123.6   0.035       0  5349.4   0.045       0
  7017.3   0.035       0  7191.7   0.063       0
Bank Sta=5098.3,5123.6
Exp/Cntr=0.3,0.1

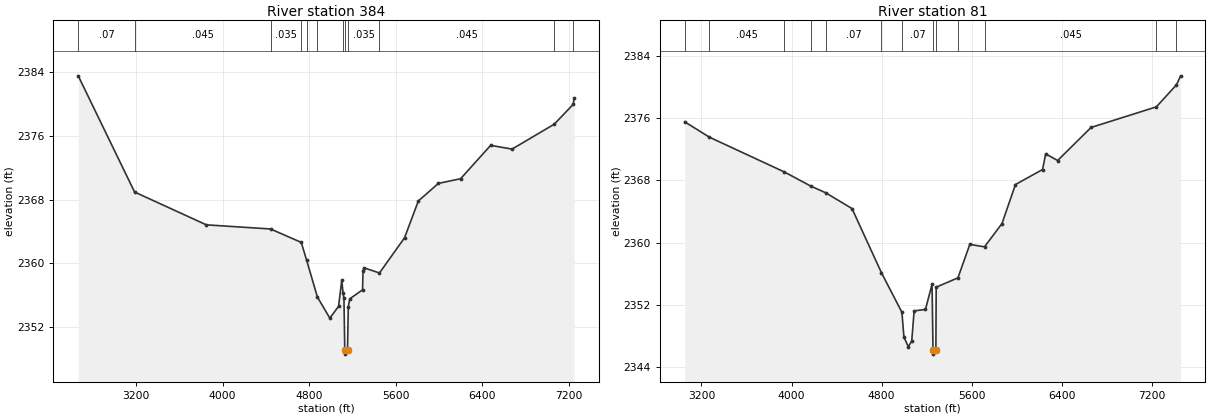
Type RM Length L Ch R = 1,384,303,303,303
BEGIN DESCRIPTION:
Cottonwood Creek Trib034 0.6
END DESCRIPTION:
XS GIS Cut Line= 5
      1321586.51      6865224.71      1321301.78      6863912.20
      1321489.28      6862926.09      1321473.31      6862649.01
      1320219.91      6861145.62
#Sta/Elev= 30
  2665.3 2383.51  3186.1 2368.95  3848.9 2364.84  4442.2 2364.32  4725.9 2362.64
  4775.6 2360.40  4874.8 2355.80  4989.8 2353.15  5070.3 2354.62  5100.4 2357.91
  5111.8 2356.32  5120.4 2355.64  5127.8 2349.14  5128.3 2348.64  5153.1 2349.14
  5160.5 2354.60  5174.5 2355.57  5292.2 2356.70  5296.2 2359.00  5304.0 2359.46
  5448.5 2358.81  5680.1 2363.22  5807.7 2367.83  5992.5 2370.03  6198.2 2370.62
  6475.5 2374.80  6673.3 2374.33  7063.1 2377.45  7238.0 2379.93  7247.0 2380.69
#Mann=12,-1,0
  2665.3    0.07       0  3186.1   0.045       0  4442.2   0.035       0
  4725.9    0.07       0  4775.6   0.035       0  4874.8    0.07       0
  5111.8   0.035       0  5127.8    0.07       0  5153.1   0.035       0
  5448.5   0.045       0  7063.1   0.035       0  7238.0   0.063       0
Bank Sta=5127.8,5153.1
Exp/Cntr=0.3,0.1

Type RM Length L Ch R = 1,81,0,0,0
BEGIN DESCRIPTION:
Cottonwood Creek Trib034 0.5
END DESCRIPTION:
XS GIS Cut Line= 5
      1321780.95      6864849.67      1321524.01      6863439.98
      1321775.39      6862985.81      1321433.73      6862419.14
      1320183.73      6861134.43
#Sta/Elev= 30
  3050.6 2375.54  3270.1 2373.56  3937.1 2369.08  4170.8 2367.27  4302.2 2366.42
  4537.2 2364.38  4798.0 2356.15  4980.6 2351.04  4998.5 2347.87  5036.7 2346.63
  5067.7 2347.31  5089.1 2351.22  5190.0 2351.41  5248.3 2354.65  5257.0 2346.16
  5257.5 2345.66  5282.3 2346.16  5285.2 2354.27  5478.4 2355.47  5583.9 2359.77
  5714.5 2359.46  5869.3 2362.44  5989.5 2367.47  6230.0 2369.40  6258.2 2371.41
  6364.2 2370.56  6661.3 2374.81  7241.4 2377.46  7420.2 2380.30  7456.8 2381.45
#Mann=13,-1,0
  3050.6    0.07       0  3270.1   0.045       0  3937.1   0.035       0
  4170.8   0.045       0  4302.2    0.07       0  4798.0   0.035       0
  4980.6    0.07       0  5257.0    0.07       0  5282.3    0.07       0
  5478.4   0.035       0  5714.5   0.045       0  7241.4   0.035       0
  7420.2   0.063       0
Bank Sta=5257,5282.3
Exp/Cntr=0.3,0.1

Chan Stop Cuts=-1