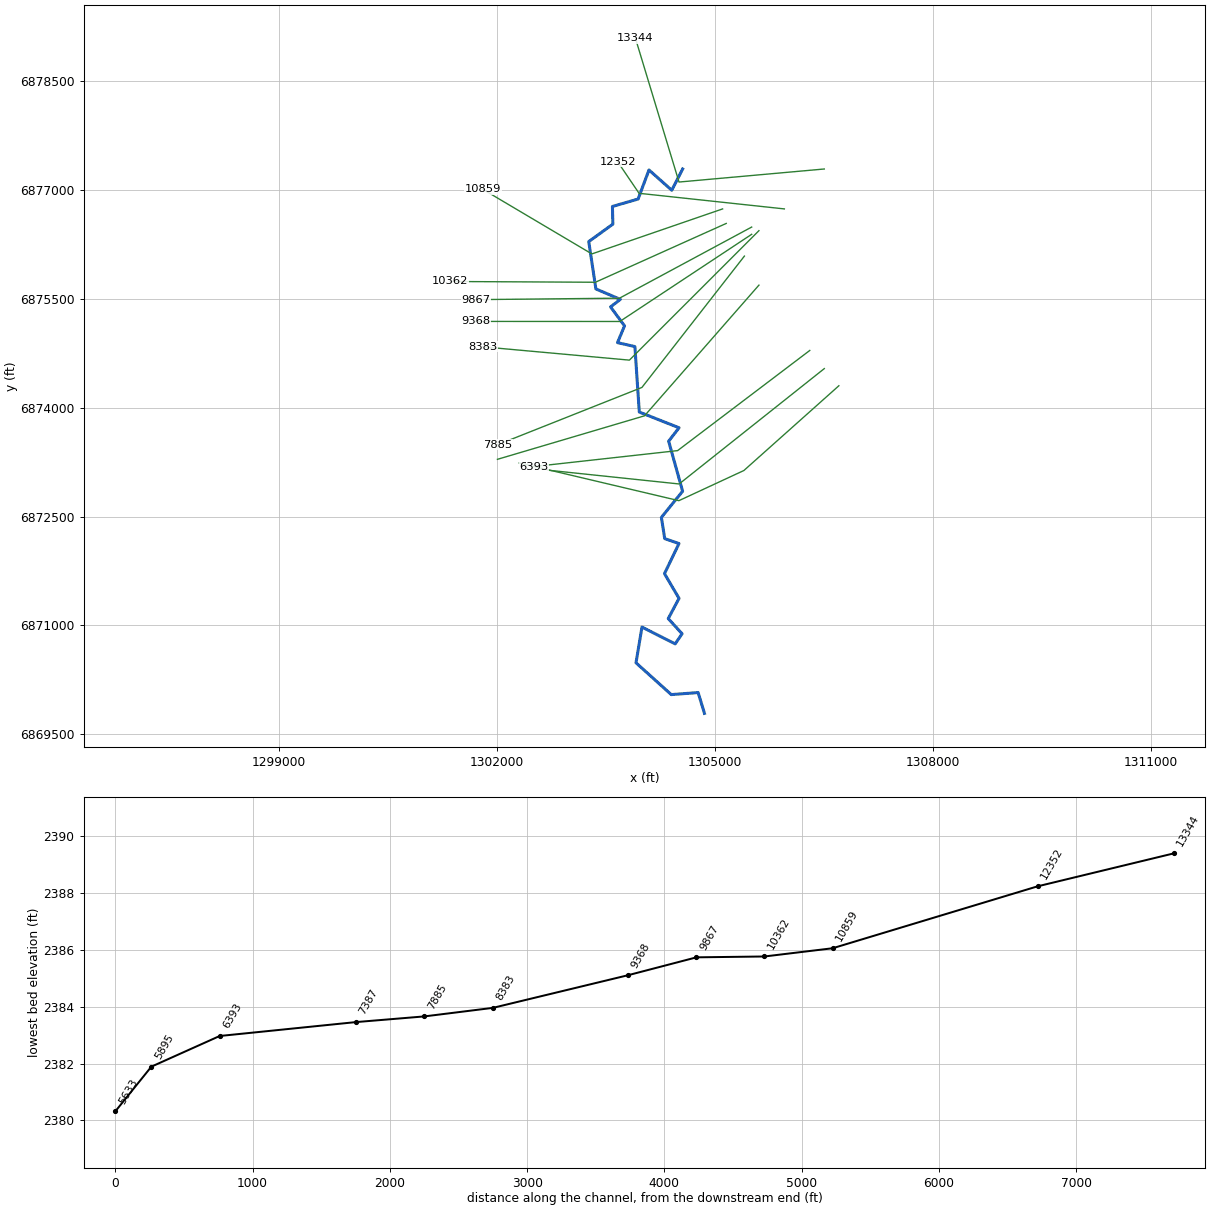
--- Cottonwood Creek Trib034_2.prj (project) ---

Proj Title=Cottonwood Creek Trib034_2 Base Level Engineering
Current Plan=p01
Default Exp/Contr=0.3,0.1
English Units
Geom File=g01
Flow File=f01
Plan File=p01
BEGIN DESCRIPTION:
Cottonwood Creek Trib034_2
END DESCRIPTION:

--- Cottonwood Creek Trib034_2.p01 (plan) ---

Plan Title=Multiple Run
Short Identifier=Multiple
Geom File=g01
Flow File=f01
Subcritical Flow
K Sum by GR= 0
Std Step Tol= 0.01
Critical Tol= 0.01
Num of Std Step Trials= 20
Max Error Tol= 0.3
Flow Tol Ratio= 0.001
Split Flow NTrial= 30
Split Flow Tol= 0.02
Split Flow Ratio= 0.02
Log Output Level= 0
Friction Slope Method= 1
Unsteady Friction Slope Method= 2
Unsteady Bridges Friction Slope Method= 1
Parabolic Critical Depth
Global Vel Dist=  1 , 1 , 1
Global Log Level= 0
CheckData=True
Encroach Param= -1, 0, 0, 0
BEGIN DESCRIPTION:
Multiple Run
END DESCRIPTION:

--- Cottonwood Creek Trib034_2.f01 (steady flow) ---

Flow Title=Multiple
Number of Profiles=7
Profile Names=10-year,25-year,50-year,1pct_min,100-year,1pct_plu,500-year
River Rch & RM= Cottonwood Creek,Reach-1,13344
     154     203     240     141     281     561     391
River Rch & RM= Cottonwood Creek,Reach-1,5895
     212     287     347     207     414     825     598
Boundary for River Rch & Prof#=Cottonwood Creek,Reach-1,1
Up Type=0
Dn Type=3
Dn Slope=0.005
Boundary for River Rch & Prof#=Cottonwood Creek,Reach-1,2
Up Type=0
Dn Type=3
Dn Slope=0.005
Boundary for River Rch & Prof#=Cottonwood Creek,Reach-1,3
Up Type=0
Dn Type=3
Dn Slope=0.005
Boundary for River Rch & Prof#=Cottonwood Creek,Reach-1,4
Up Type=0
Dn Type=3
Dn Slope=0.005
Boundary for River Rch & Prof#=Cottonwood Creek,Reach-1,5
Up Type=0
Dn Type=3
Dn Slope=0.005
Boundary for River Rch & Prof#=Cottonwood Creek,Reach-1,6
Up Type=0
Dn Type=3
Dn Slope=0.005
Boundary for River Rch & Prof#=Cottonwood Creek,Reach-1,7
Up Type=0
Dn Type=3
Dn Slope=0.005

--- Cottonwood Creek Trib034_2.g01 (geometry) ---

Geom Title=Existing Conditions

River Reach=Cottonwood Creek,Reach-1
Reach XY= 30
      1304555.00      6877288.00      1304405.01      6876995.07
      1304091.18      6877274.74      1303941.74      6876874.35
      1303588.25      6876771.72      1303594.04      6876527.95
      1303262.10      6876288.00      1303360.51      6875635.56
      1303697.59      6875491.40      1303562.01      6875388.21
      1303754.71      6875127.02      1303658.15      6874895.58
      1303897.40      6874841.35      1303958.03      6873939.39
      1304505.17      6873722.78      1304362.07      6873538.00
      1304554.23      6872848.69      1304262.26      6872488.30
      1304307.91      6872195.91      1304504.52      6872127.53
      1304304.80      6871712.92      1304505.05      6871372.66
      1304356.58      6871094.05      1304547.17      6870884.77
      1304451.86      6870745.53      1303994.94      6870976.89
      1303912.79      6870484.55      1304398.05      6870046.85
      1304768.33      6870074.58      1304855.00      6869788.00

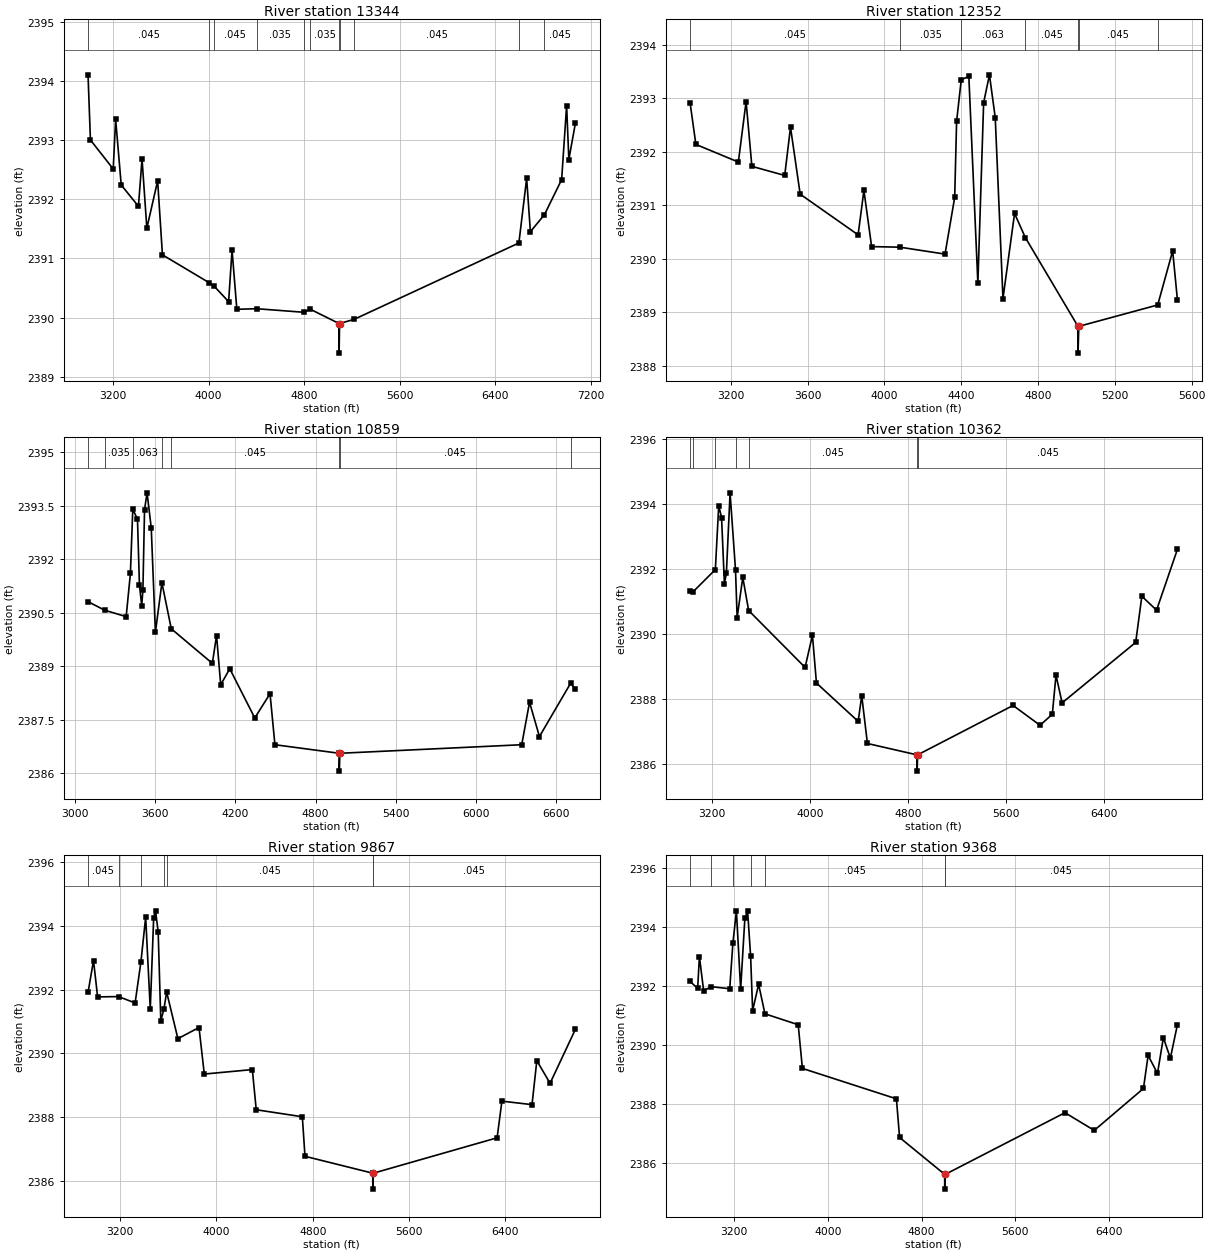
Type RM Length L Ch R = 1,13344,992,992,992
BEGIN DESCRIPTION:
Cottonwood Creek Trib034_2 15.0
END DESCRIPTION:
XS GIS Cut Line= 3
      1306504.99      6877288.00      1304504.76      6877108.15
      1303905.00      6879088.00
#Sta/Elev= 30
  2991.7 2394.10  3011.8 2393.00  3202.5 2392.51  3222.6 2393.35  3269.3 2392.24
  3413.4 2391.88  3443.5 2392.68  3483.7 2391.51  3574.0 2392.31  3614.2 2391.06
  4004.6 2390.59  4046.7 2390.53  4167.8 2390.27  4196.5 2391.14  4236.7 2390.14
  4402.2 2390.15  4796.4 2390.09  4852.5 2390.14  5091.8 2389.90  5092.1 2389.40
  5096.0 2389.90  5217.2 2389.97  6596.2 2391.26  6661.2 2392.35  6692.5 2391.45
  6810.5 2391.74  6953.8 2392.33  6995.6 2393.58  7014.1 2392.67  7068.7 2393.28
#Mann=11,-1,0
  2991.7   0.045       0  4004.6   0.035       0  4046.7   0.045       0
  4402.2   0.035       0  4796.4   0.045       0  4852.5   0.035       0
  5091.8   0.035       0  5096.0   0.035       0  5217.2   0.045       0
  6596.2    0.07       0  6810.5   0.045       0
Bank Sta=5091.8,5096
Exp/Cntr=0.3,0.1

Type RM Length L Ch R = 1,12352,1493,1493,1493
BEGIN DESCRIPTION:
Cottonwood Creek Trib034_2 14.0
END DESCRIPTION:
XS GIS Cut Line= 3
      1305954.98      6876738.00      1303954.81      6876953.07
      1303659.73      6877388.38
#Sta/Elev= 30
  2988.3 2392.92  3018.5 2392.14  3239.7 2391.81  3280.0 2392.94  3310.1 2391.73
  3481.1 2391.56  3511.3 2392.46  3561.6 2391.21  3863.3 2390.45  3893.5 2391.28
  3933.7 2390.23  4080.1 2390.22  4315.9 2390.09  4366.2 2391.15  4376.2 2392.57
  4400.4 2393.35  4439.9 2393.41  4486.9 2389.55  4517.0 2392.92  4547.2 2393.44
  4577.4 2392.64  4617.6 2389.26  4678.0 2390.85  4733.9 2390.40  5008.2 2388.74
  5008.5 2388.24  5012.4 2388.74  5423.4 2389.14  5501.3 2390.15  5525.9 2389.24
#Mann=7,-1,0
  2988.3   0.045       0  4080.1   0.035       0  4400.4   0.063       0
  4733.9   0.045       0  5008.2   0.045       0  5012.4   0.045       0
  5423.4   0.035       0
Bank Sta=5008.2,5012.4
Exp/Cntr=0.3,0.1

Type RM Length L Ch R = 1,10859,497,497,497
BEGIN DESCRIPTION:
Cottonwood Creek Trib034_2 13.0
END DESCRIPTION:
XS GIS Cut Line= 3
      1305104.97      6876737.99      1303304.90      6876117.84
      1301804.43      6877007.70
#Sta/Elev= 30
  3096.1 2390.81  3220.8 2390.57  3381.6 2390.39  3413.3 2391.60  3431.1 2393.40
  3466.3 2393.12  3481.0 2391.27  3498.0 2390.70  3506.9 2391.13  3519.1 2393.39
  3538.1 2393.86  3569.3 2392.88  3600.5 2389.95  3649.1 2391.34  3719.3 2390.05
  4026.8 2389.08  4058.2 2389.86  4089.4 2388.48  4157.1 2388.93  4344.4 2387.55
  4458.7 2388.23  4495.2 2386.80  4976.6 2386.56  4976.9 2386.06  4980.9 2386.56
  6343.0 2386.80  6401.4 2387.99  6475.5 2387.03  6708.6 2388.52  6744.5 2388.36
#Mann=8,-1,0
  3096.1   0.045       0  3220.8   0.035       0  3431.1   0.063       0
  3649.1    0.07       0  3719.3   0.045       0  4976.6   0.045       0
  4980.9   0.045       0  6708.6   0.035       0
Bank Sta=4976.6,4980.9
Exp/Cntr=0.3,0.1

Type RM Length L Ch R = 1,10362,495,495,495
BEGIN DESCRIPTION:
Cottonwood Creek Trib034_2 12.0
END DESCRIPTION:
XS GIS Cut Line= 3
      1305154.97      6876537.99      1303353.49      6875727.52
      1301355.02      6875738.00
#Sta/Elev= 30
  3024.6 2391.31  3047.6 2391.28  3230.7 2391.97  3258.2 2393.93  3281.4 2393.57
  3304.5 2391.54  3320.6 2391.85  3350.8 2394.33  3395.1 2391.96  3408.4 2390.49
  3454.4 2391.73  3502.2 2390.71  3962.5 2388.96  4022.4 2389.95  4055.1 2388.48
  4395.2 2387.30  4424.4 2388.09  4470.7 2386.62  4875.6 2386.27  4875.9 2385.77
  4879.9 2386.27  5658.5 2387.79  5878.5 2387.18  5978.5 2387.52  6008.5 2388.72
  6058.5 2387.87  6658.5 2389.73  6708.5 2391.15  6828.5 2390.72  6998.5 2392.59
#Mann=7,-1,0
  3024.6   0.045       0  3047.6   0.035       0  3230.7   0.063       0
  3395.1    0.07       0  3502.2   0.045       0  4875.6   0.045       0
  4879.9   0.045       0
Bank Sta=4875.6,4879.9
Exp/Cntr=0.3,0.1

Type RM Length L Ch R = 1,9867,499,499,499
BEGIN DESCRIPTION:
Cottonwood Creek Trib034_2 11.0
END DESCRIPTION:
XS GIS Cut Line= 3
      1305505.04      6876488.02      1303685.98      6875508.32
      1301704.99      6875488.00
#Sta/Elev= 30
  2933.9 2391.91  2979.4 2392.91  3013.4 2391.77  3187.0 2391.78  3324.9 2391.58
  3372.9 2392.86  3412.6 2394.27  3450.7 2391.39  3479.1 2394.26  3494.5 2394.47
  3516.4 2393.81  3538.3 2391.02  3564.2 2391.39  3586.8 2391.92  3680.2 2390.46
  3855.5 2390.81  3899.4 2389.35  4298.4 2389.49  4330.8 2388.23  4713.7 2388.01
  4735.6 2386.77  5298.7 2386.24  5299.0 2385.74  5303.3 2386.24  6331.1 2387.35
  6371.1 2388.50  6621.1 2388.39  6661.1 2389.77  6771.1 2389.06  6981.1 2390.75
#Mann=7,-1,0
  2933.9   0.045       0  3187.0   0.035       0  3372.9   0.063       0
  3564.2   0.035       0  3586.8   0.045       0  5298.7   0.045       0
  5303.3   0.045       0
Bank Sta=5298.7,5303.3
Exp/Cntr=0.3,0.1

Type RM Length L Ch R = 1,9368,985,985,985
BEGIN DESCRIPTION:
Cottonwood Creek Trib034_2 10.0
END DESCRIPTION:
XS GIS Cut Line= 3
      1305505.04      6876388.03      1303689.68      6875187.16
      1301704.98      6875188.00
#Sta/Elev= 30
  2823.4 2392.15  2888.1 2391.91  2903.2 2392.99  2939.3 2391.83  3003.1 2391.97
  3162.0 2391.90  3188.9 2393.44  3219.1 2394.54  3255.2 2391.88  3291.3 2394.29
  3315.0 2394.52  3340.5 2393.00  3357.6 2391.16  3408.7 2392.05  3462.7 2391.05
  3746.7 2390.68  3782.6 2389.20  4585.3 2388.17  4612.4 2386.86  4997.5 2385.61
  4997.8 2385.11  5002.1 2385.61  6024.7 2387.70  6274.7 2387.10  6694.7 2388.52
  6734.7 2389.64  6814.7 2389.03  6864.7 2390.24  6924.7 2389.55  6984.7 2390.68
#Mann=7,-1,0
  2823.4   0.045       0  3003.1   0.035       0  3188.9   0.063       0
  3340.5   0.035       0  3462.7   0.045       0  4997.5   0.045       0
  5002.1   0.045       0
Bank Sta=4997.5,5002.1
Exp/Cntr=0.3,0.1

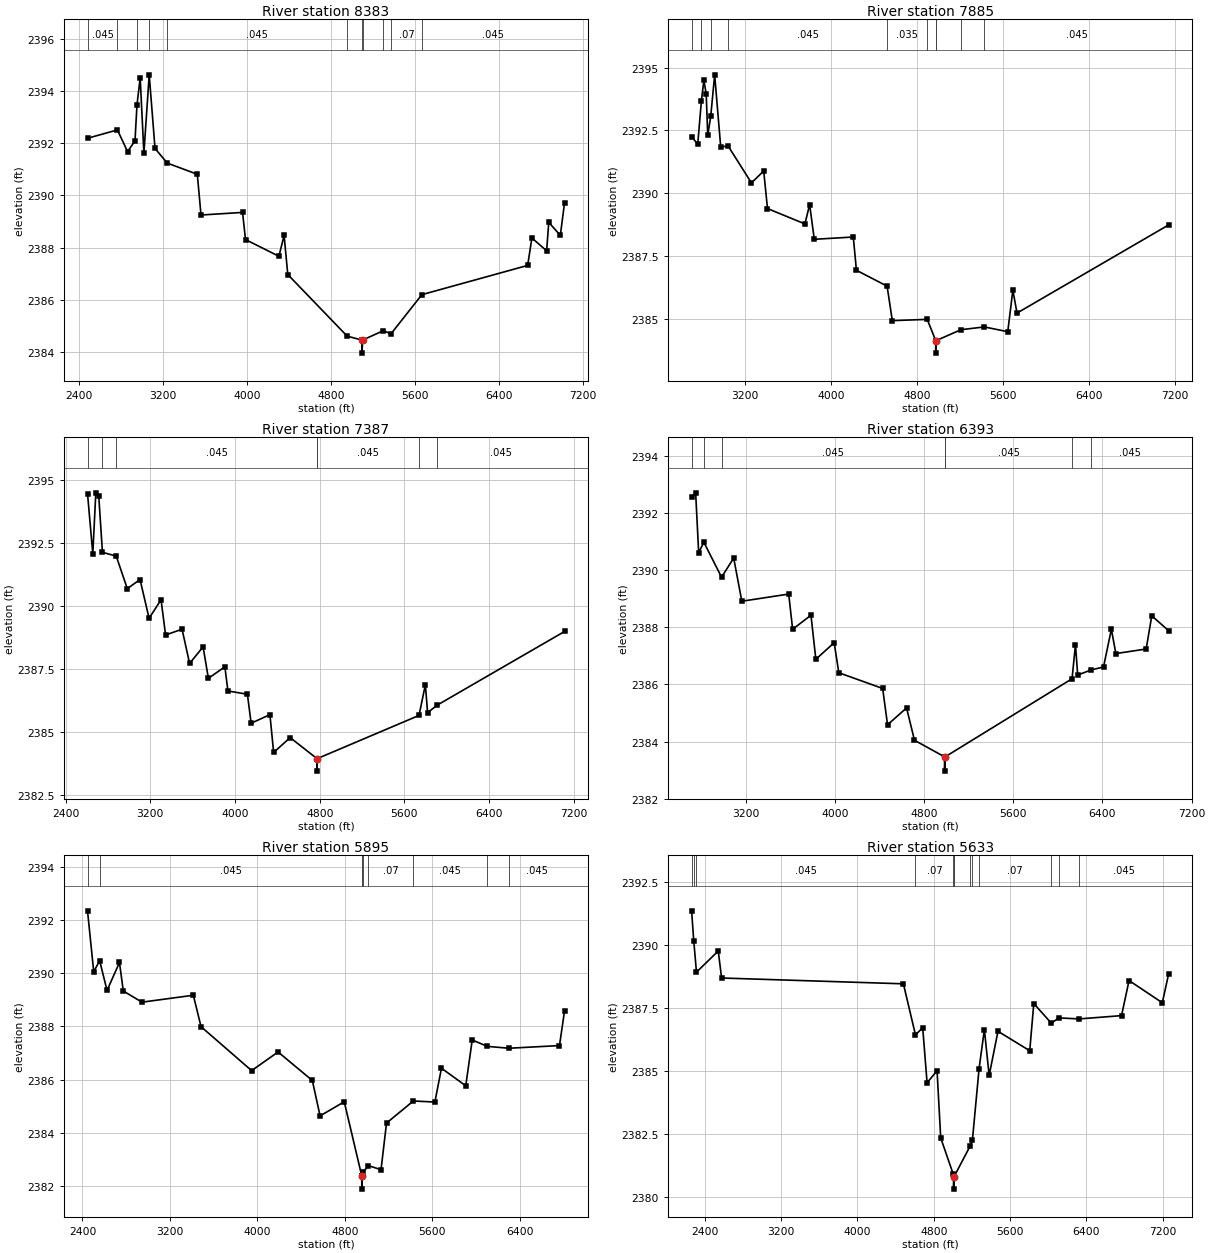
Type RM Length L Ch R = 1,8383,498,498,498
BEGIN DESCRIPTION:
Cottonwood Creek Trib034_2 9.0
END DESCRIPTION:
XS GIS Cut Line= 3
      1305604.97      6876437.97      1303822.05      6874654.67
      1301804.97      6874838.00
#Sta/Elev= 30
  2478.3 2392.19  2763.2 2392.51  2860.1 2391.68  2930.8 2392.09  2949.8 2393.47
  2980.3 2394.50  3015.7 2391.62  3066.4 2394.62  3121.7 2391.80  3238.4 2391.24
  3524.8 2390.81  3560.1 2389.25  3956.1 2389.35  3984.4 2388.31  4302.6 2387.67
  4352.1 2388.47  4387.4 2386.97  4953.5 2384.61  5094.6 2384.46  5095.1 2383.96
  5100.4 2384.46  5298.2 2384.82  5371.3 2384.70  5665.6 2386.20  6673.9 2387.32
  6714.1 2388.37  6854.7 2387.88  6874.8 2388.97  6985.2 2388.47  7025.4 2389.72
#Mann=11,-1,0
  2478.3   0.045       0  2763.2   0.035       0  2949.8   0.063       0
  3066.4   0.035       0  3238.4   0.045       0  4953.5    0.07       0
  5094.6    0.07       0  5100.4    0.07       0  5298.2   0.045       0
  5371.3    0.07       0  5665.6   0.045       0
Bank Sta=5094.6,5100.4
Exp/Cntr=0.3,0.1

Type RM Length L Ch R = 1,7885,498,498,498
BEGIN DESCRIPTION:
Cottonwood Creek Trib034_2 8.0
END DESCRIPTION:
XS GIS Cut Line= 3
      1305405.03      6876088.03      1303994.12      6874278.34
      1302004.99      6873487.99
#Sta/Elev= 30
  2705.3 2392.26  2762.3 2391.95  2796.6 2393.68  2819.5 2394.49  2841.0 2393.96
  2855.5 2392.31  2883.3 2393.06  2919.7 2394.71  2975.8 2391.86  3046.9 2391.87
  3261.7 2390.42  3375.7 2390.89  3411.0 2389.40  3759.2 2388.79  3802.7 2389.56
  3846.1 2388.18  4208.8 2388.27  4237.8 2386.95  4523.1 2386.32  4571.6 2384.95
  4896.1 2385.00  4974.8 2384.16  4975.3 2383.66  4980.7 2384.16  5209.4 2384.59
  5427.4 2384.70  5644.7 2384.51  5692.3 2386.16  5730.8 2385.25  7140.4 2388.75
#Mann=10,-1,0
  2705.3   0.035       0  2796.6   0.063       0  2883.3   0.035       0
  3046.9   0.045       0  4523.1   0.035       0  4896.1   0.045       0
  4974.8   0.045       0  4980.7   0.045       0  5209.4   0.035       0
  5427.4   0.045       0
Bank Sta=4974.8,4980.7
Exp/Cntr=0.3,0.1

Type RM Length L Ch R = 1,7387,994,994,994
BEGIN DESCRIPTION:
Cottonwood Creek Trib034_2 7.0
END DESCRIPTION:
XS GIS Cut Line= 3
      1305605.02      6875688.02      1304029.86      6873887.48
      1302005.04      6873288.01
#Sta/Elev= 30
  2607.7 2394.47  2657.6 2392.08  2686.0 2394.50  2714.0 2394.36  2748.6 2392.14
  2878.8 2391.99  2983.1 2390.70  3103.7 2391.06  3189.1 2389.52  3302.0 2390.26
  3344.7 2388.86  3500.4 2389.09  3571.6 2387.73  3698.8 2388.39  3749.1 2387.14
  3904.7 2387.60  3933.2 2386.64  4117.3 2386.51  4152.4 2385.36  4329.9 2385.70
  4365.1 2384.20  4521.0 2384.79  4773.1 2383.96  4773.6 2383.46  4779.0 2383.96
  5737.7 2385.67  5797.7 2386.89  5818.5 2385.78  5910.3 2386.08  7111.7 2389.00
#Mann=7,-1,0
  2607.7   0.094       0  2748.6   0.035       0  2878.8   0.045       0
  4773.1   0.045       0  4779.0   0.045       0  5737.7   0.035       0
  5910.3   0.045       0
Bank Sta=4773.1,4779
Exp/Cntr=0.3,0.1

Type RM Length L Ch R = 1,6393,498,498,498
BEGIN DESCRIPTION:
Cottonwood Creek Trib034_2 6.0
END DESCRIPTION:
XS GIS Cut Line= 3
      1306304.98      6874787.99      1304485.57      6873408.09
      1302504.96      6873188.00
#Sta/Elev= 30
  2716.5 2392.57  2752.9 2392.70  2780.0 2390.61  2826.7 2390.97  2985.1 2389.75
  3094.0 2390.42  3166.8 2388.91  3587.0 2389.16  3622.4 2387.93  3786.7 2388.42
  3830.4 2386.88  3994.7 2387.46  4036.3 2386.41  4429.4 2385.86  4473.1 2384.59
  4643.7 2385.18  4714.4 2384.05  4983.9 2383.47  4984.4 2382.97  4989.9 2383.47
  6127.2 2386.20  6157.7 2387.39  6177.8 2386.33  6299.8 2386.51  6409.2 2386.61
  6479.6 2387.93  6519.9 2387.08  6791.5 2387.24  6841.8 2388.40  6992.8 2387.88
#Mann=7,-1,0
  2716.5   0.063       0  2826.7    0.07       0  2985.1   0.045       0
  4983.9   0.045       0  4989.9   0.045       0  6127.2   0.035       0
  6299.8   0.045       0
Bank Sta=4983.9,4989.9
Exp/Cntr=0.3,0.1

Type RM Length L Ch R = 1,5895,262,262,262
BEGIN DESCRIPTION:
Cottonwood Creek Trib034_2 5.0
END DESCRIPTION:
XS GIS Cut Line= 3
      1306504.97      6874537.98      1304506.24      6872948.50
      1302704.98      6873138.00
#Sta/Elev= 30
  2446.3 2392.34  2503.1 2390.05  2557.3 2390.47  2624.9 2389.35  2738.6 2390.40
  2773.8 2389.33  2944.6 2388.91  3414.6 2389.17  3485.0 2387.99  3948.0 2386.34
  4189.9 2387.04  4503.3 2385.97  4574.3 2384.64  4795.4 2385.17  4955.4 2382.39
  4955.9 2381.89  4962.0 2382.39  4969.9 2382.54  5017.3 2382.77  5132.0 2382.62
  5182.2 2384.37  5427.7 2385.20  5624.7 2385.16  5685.0 2386.43  5907.2 2385.77
  5966.5 2387.49  6105.1 2387.25  6301.5 2387.18  6764.7 2387.28  6811.2 2388.58
#Mann=9,-1,0
  2446.3   0.063       0  2557.3   0.045       0  4955.4   0.063       0
  4962.0   0.045       0  4969.9   0.063       0  5017.3    0.07       0
  5427.7   0.045       0  6105.1   0.035       0  6301.5   0.045       0
Bank Sta=4955.4,4962
Exp/Cntr=0.3,0.1

Type RM Length L Ch R = 1,5633,0,0,0
BEGIN DESCRIPTION:
Cottonwood Creek Trib034_2 4.0
END DESCRIPTION:
XS GIS Cut Line= 4
      1306705.44      6874301.63      1305397.94      6873134.02
      1304503.14      6872718.39      1302305.00      6873238.00
#Sta/Elev= 30
  2262.9 2391.34  2285.7 2390.15  2314.0 2388.91  2542.2 2389.75  2577.3 2388.68
  4482.2 2388.45  4608.6 2386.43  4684.6 2386.71  4730.4 2384.53  4835.0 2385.01
  4873.2 2382.35  5004.6 2380.91  5007.5 2380.82  5008.0 2380.32  5014.1 2380.82
  5182.1 2382.03  5205.7 2382.27  5275.1 2385.09  5330.7 2386.64  5380.8 2384.82
  5473.2 2386.57  5806.1 2385.80  5848.4 2387.67  6032.4 2386.89  6110.3 2387.10
  6322.9 2387.06  6768.0 2387.19  6846.6 2388.58  7195.2 2387.70  7261.2 2388.84
#Mann=13,-1,0
  2262.9   0.094       0  2285.7   0.063       0  2314.0   0.045       0
  4608.6    0.07       0  5004.6   0.063       0  5007.5    0.07       0
  5014.1   0.063       0  5182.1   0.035       0  5205.7   0.063       0
  5275.1    0.07       0  6032.4   0.045       0  6110.3   0.035       0
  6322.9   0.045       0
Bank Sta=5007.5,5014.1
Exp/Cntr=0.3,0.1

Chan Stop Cuts=-1