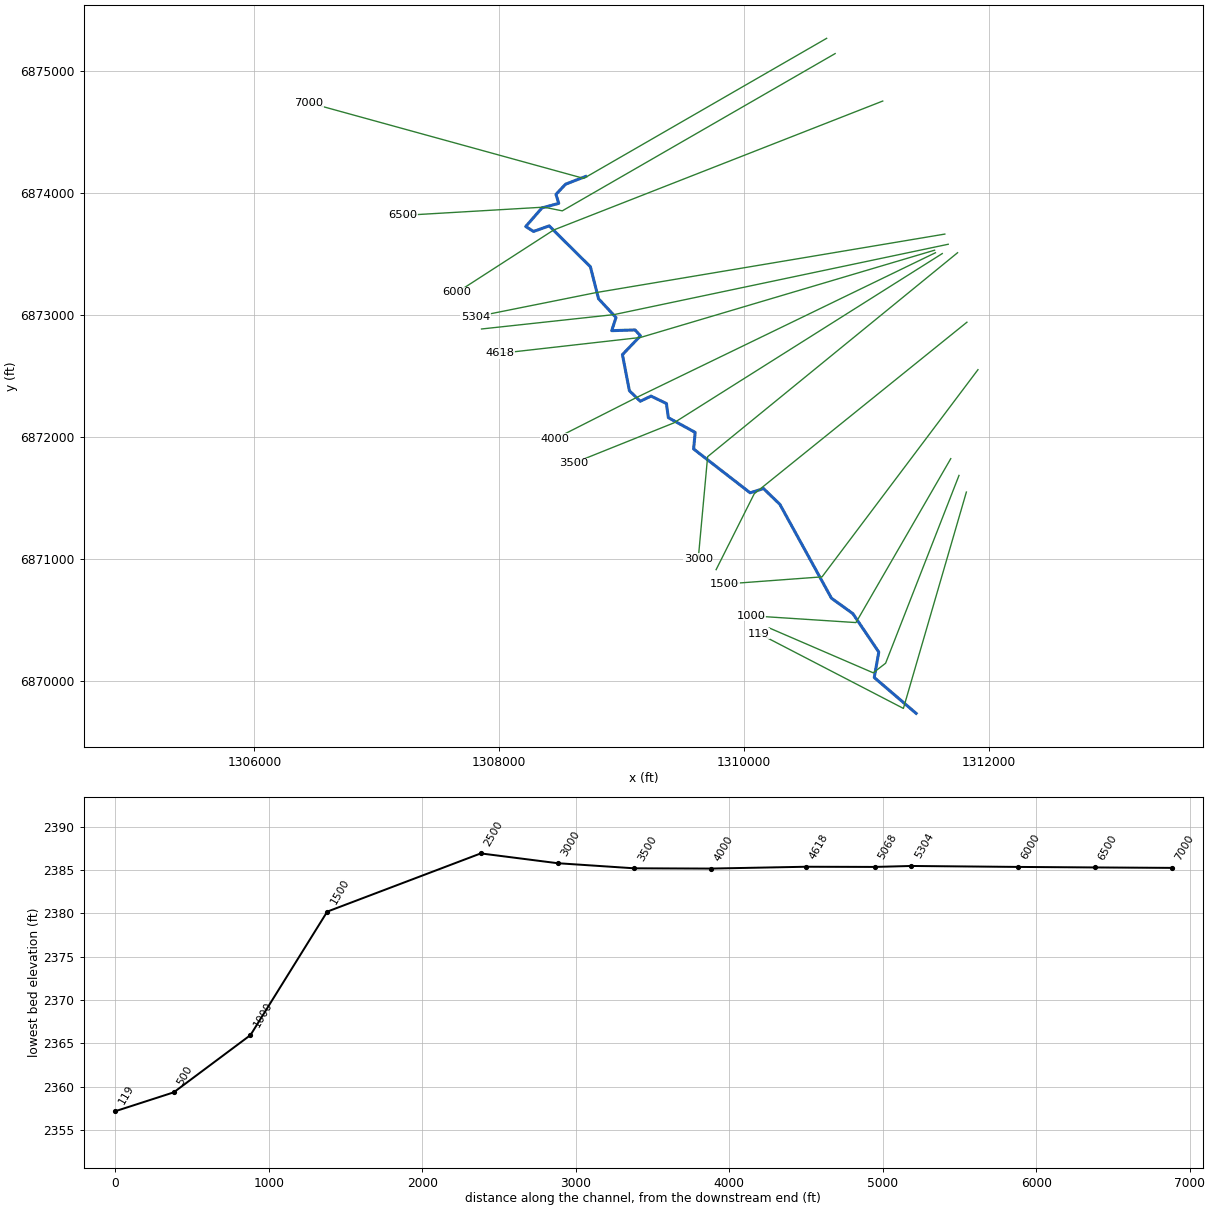
--- Cottonwood CreekTrib039.prj (project) ---

Proj Title=Cottonwood CreekTrib039 Base Level Engineering
Current Plan=p01
Default Exp/Contr=0.3,0.1
English Units
Geom File=g01
Flow File=f01
Plan File=p01
BEGIN DESCRIPTION:
Cottonwood CreekTrib039
END DESCRIPTION:

--- Cottonwood CreekTrib039.p01 (plan) ---

Plan Title=Multiple Run
Short Identifier=Multiple
Geom File=g01
Flow File=f01
Subcritical Flow
K Sum by GR= 0
Std Step Tol= 0.01
Critical Tol= 0.01
Num of Std Step Trials= 20
Max Error Tol= 0.3
Flow Tol Ratio= 0.001
Split Flow NTrial= 30
Split Flow Tol= 0.02
Split Flow Ratio= 0.02
Log Output Level= 0
Friction Slope Method= 1
Unsteady Friction Slope Method= 2
Unsteady Bridges Friction Slope Method= 1
Parabolic Critical Depth
Global Vel Dist=  1 , 1 , 1
Global Log Level= 0
CheckData=True
Encroach Param= -1, 0, 0, 0
BEGIN DESCRIPTION:
Multiple Run
END DESCRIPTION:

--- Cottonwood CreekTrib039.f01 (steady flow) ---

Flow Title=Multiple
Number of Profiles=7
Profile Names=10-year,25-year,50-year,1pct_min,100-year,1pct_plu,500-year
River Rch & RM= Cottonwood Creek,Reach-1,7000
      90     115     133      76     152     303     202
River Rch & RM= Cottonwood Creek,Reach-1,6000
     149     198     237     140     280     558     397
Boundary for River Rch & Prof#=Cottonwood Creek,Reach-1,1
Up Type=0
Dn Type=3
Dn Slope=0.005
Boundary for River Rch & Prof#=Cottonwood Creek,Reach-1,2
Up Type=0
Dn Type=3
Dn Slope=0.005
Boundary for River Rch & Prof#=Cottonwood Creek,Reach-1,3
Up Type=0
Dn Type=3
Dn Slope=0.005
Boundary for River Rch & Prof#=Cottonwood Creek,Reach-1,4
Up Type=0
Dn Type=3
Dn Slope=0.005
Boundary for River Rch & Prof#=Cottonwood Creek,Reach-1,5
Up Type=0
Dn Type=3
Dn Slope=0.005
Boundary for River Rch & Prof#=Cottonwood Creek,Reach-1,6
Up Type=0
Dn Type=3
Dn Slope=0.005
Boundary for River Rch & Prof#=Cottonwood Creek,Reach-1,7
Up Type=0
Dn Type=3
Dn Slope=0.005

--- Cottonwood CreekTrib039.g01 (geometry) ---

Geom Title=Existing Conditions

River Reach=Cottonwood Creek,Reach-1
Reach XY= 30
      1308705.00      6874138.00      1308541.64      6874074.60
      1308463.00      6873991.34      1308485.83      6873917.52
      1308348.83      6873880.14      1308215.82      6873727.57
      1308279.78      6873687.51      1308407.54      6873733.01
      1308744.25      6873397.68      1308810.81      6873135.71
      1308953.34      6872981.95      1308918.37      6872874.19
      1309108.74      6872880.30      1309153.44      6872832.32
      1309005.87      6872677.67      1309062.82      6872381.77
      1309151.58      6872295.81      1309239.59      6872337.86
      1309365.39      6872277.24      1309380.75      6872161.27
      1309600.00      6872040.57      1309587.44      6871904.64
      1310048.95      6871545.50      1310158.41      6871580.18
      1310291.60      6871451.31      1310713.13      6870681.93
      1310888.51      6870555.05      1311099.91      6870240.30
      1311062.76      6870031.83      1311405.00      6869738.00

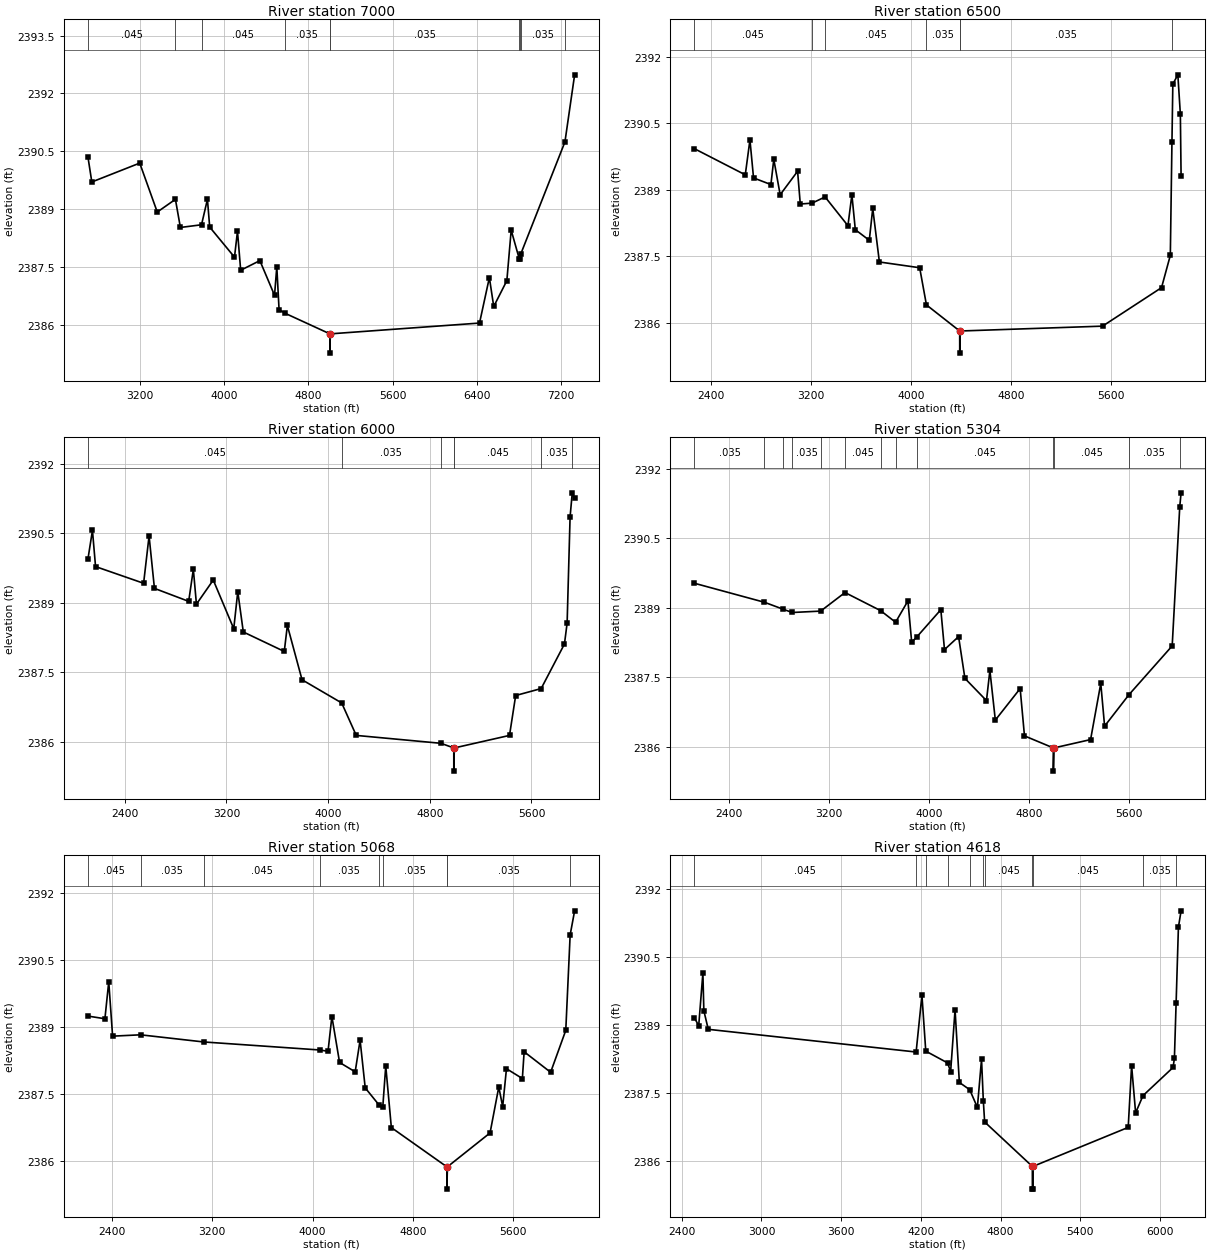
Type RM Length L Ch R = 1,7000,500,500,500
BEGIN DESCRIPTION:
Cottonwood CreekTrib039 14.0
END DESCRIPTION:
XS GIS Cut Line= 3
      1310673.79      6875269.84      1308689.80      6874122.01
      1306444.65      6874742.06
#Sta/Elev= 30
  2707.9 2390.34  2744.2 2389.70  3199.2 2390.19  3365.7 2388.92  3538.1 2389.25
  3585.3 2388.52  3786.0 2388.59  3842.1 2389.25  3863.7 2388.53  4099.0 2387.75
  4127.5 2388.42  4157.9 2387.41  4340.1 2387.66  4479.4 2386.76  4500.9 2387.50
  4522.4 2386.39  4574.7 2386.30  5004.9 2385.76  5005.2 2385.26  5008.9 2385.76
  6426.1 2386.04  6519.6 2387.22  6561.1 2386.47  6685.6 2387.14  6726.8 2388.45
  6805.2 2387.69  6807.0 2387.70  6816.1 2387.82  7237.3 2390.74  7329.2 2392.48
#Mann=10,-1,0
  2707.9   0.045       0  3538.1    0.07       0  3786.0   0.045       0
  4574.7   0.035       0  5004.9   0.035       0  5008.9   0.035       0
  6805.2    0.07       0  6807.0   0.045       0  6816.1   0.035       0
  7237.3   0.063       0
Bank Sta=5004.9,5008.9
Exp/Cntr=0.3,0.1

Type RM Length L Ch R = 1,6500,500,500,500
BEGIN DESCRIPTION:
Cottonwood CreekTrib039 13.0
END DESCRIPTION:
XS GIS Cut Line= 4
      1310743.23      6875144.83      1308514.68      6873856.15
      1308363.82      6873886.47      1307209.22      6873818.50
#Sta/Elev= 30
  2271.8 2389.93  2677.4 2389.34  2714.7 2390.13  2743.4 2389.27  2882.0 2389.12
  2905.1 2389.69  2955.9 2388.89  3095.1 2389.42  3116.6 2388.68  3210.4 2388.70
  3314.6 2388.84  3497.0 2388.19  3528.5 2388.89  3555.9 2388.10  3667.5 2387.86
  3695.1 2388.58  3748.1 2387.37  4069.7 2387.24  4123.7 2386.40  4389.2 2385.81
  4389.5 2385.31  4393.2 2385.81  5529.7 2385.92  6000.5 2386.79  6070.7 2387.52
  6083.7 2390.08  6090.7 2391.39  6130.8 2391.60  6150.8 2390.71  6156.6 2389.31
#Mann=7,-1,0
  2271.8   0.045       0  3210.4    0.07       0  3314.6   0.045       0
  4123.7   0.035       0  4389.2   0.035       0  4393.2   0.035       0
  6083.7   0.063       0
Bank Sta=4389.2,4393.2
Exp/Cntr=0.3,0.1

Type RM Length L Ch R = 1,6000,696,696,696
BEGIN DESCRIPTION:
Cottonwood CreekTrib039 12.0
END DESCRIPTION:
XS GIS Cut Line= 3
      1311132.14      6874755.96      1308443.66      6873698.97
      1307655.02      6873188.01
#Sta/Elev= 30
  2111.2 2389.95  2146.2 2390.56  2170.6 2389.78  2548.7 2389.42  2591.7 2390.44
  2633.9 2389.31  2903.3 2389.03  2940.0 2389.72  2964.4 2388.97  3096.7 2389.49
  3257.9 2388.44  3289.6 2389.24  3333.1 2388.37  3655.4 2387.95  3679.7 2388.51
  3795.1 2387.34  4107.1 2386.84  4221.6 2386.14  4887.7 2385.97  4989.0 2385.87
  4989.2 2385.37  4993.2 2385.87  5427.4 2386.14  5475.9 2387.00  5676.4 2387.15
  5859.6 2388.11  5880.7 2388.56  5904.0 2390.85  5921.1 2391.37  5939.7 2391.25
#Mann=7,-1,0
  2111.2   0.045       0  4107.1   0.035       0  4887.7   0.045       0
  4989.0   0.045       0  4993.2   0.045       0  5676.4   0.035       0
  5921.1   0.063       0
Bank Sta=4989,4993.2
Exp/Cntr=0.3,0.1

Type RM Length L Ch R = 1,5304,236,236,236
BEGIN DESCRIPTION:
Cottonwood CreekTrib039 11.0
END DESCRIPTION:
XS GIS Cut Line= 3
      1311639.09      6873665.68      1308791.86      6873186.51
      1307804.99      6872988.00
#Sta/Elev= 30
  2120.8 2389.53  2681.2 2389.12  2830.9 2388.97  2903.0 2388.90  3130.6 2388.93
  3325.4 2389.33  3610.3 2388.94  3730.1 2388.69  3828.9 2389.15  3859.0 2388.26
  3898.9 2388.37  4092.2 2388.96  4121.5 2388.10  4234.2 2388.38  4284.9 2387.48
  4457.3 2387.00  4484.8 2387.65  4528.3 2386.58  4727.0 2387.26  4761.5 2386.24
  4992.6 2385.98  4992.9 2385.48  4996.9 2385.98  5290.5 2386.16  5372.1 2387.37
  5402.7 2386.45  5598.3 2387.13  5943.5 2388.18  6004.0 2391.18  6014.7 2391.48
#Mann=13,-1,0
  2120.8   0.035       0  2681.2   0.045       0  2830.9    0.07       0
  2903.0   0.035       0  3130.6    0.07       0  3325.4   0.045       0
  3610.3   0.035       0  3730.1    0.07       0  3898.9   0.045       0
  4992.6   0.045       0  4996.9   0.045       0  5598.3   0.035       0
  6004.0   0.063       0
Bank Sta=4992.6,4996.9
Exp/Cntr=0.3,0.1

Type RM Length L Ch R = 1,5068,450,450,450
BEGIN DESCRIPTION:
Cottonwood CreekTrib039 10.0
END DESCRIPTION:
XS GIS Cut Line= 3
      1311666.86      6873582.34      1308937.69      6873005.96
      1307854.96      6872888.00
#Sta/Elev= 30
  2210.5 2389.25  2345.3 2389.19  2375.9 2390.02  2406.6 2388.80  2629.4 2388.83
  3132.0 2388.67  4057.4 2388.49  4123.6 2388.46  4154.3 2389.24  4215.6 2388.21
  4340.0 2388.00  4379.2 2388.71  4420.0 2387.64  4529.3 2387.26  4560.2 2387.22
  4583.7 2388.13  4628.3 2386.75  5070.8 2385.87  5071.1 2385.37  5075.1 2385.87
  5415.0 2386.63  5484.6 2387.66  5515.6 2387.22  5545.8 2388.07  5672.5 2387.85
  5686.6 2388.45  5897.8 2387.99  6018.5 2388.93  6053.4 2391.07  6089.0 2391.61
#Mann=9,-1,0
  2210.5   0.045       0  2629.4   0.035       0  3132.0   0.045       0
  4057.4   0.035       0  4529.3    0.07       0  4560.2   0.035       0
  5070.8   0.035       0  5075.1   0.035       0  6053.4   0.063       0
Bank Sta=5070.8,5075.1
Exp/Cntr=0.3,0.1

Type RM Length L Ch R = 1,4618,618,618,618
BEGIN DESCRIPTION:
Cottonwood CreekTrib039 9.0
END DESCRIPTION:
XS GIS Cut Line= 3
      1311555.72      6873533.72      1309152.97      6872818.46
      1308005.01      6872688.00
#Sta/Elev= 30
  2495.6 2389.16  2527.6 2388.99  2559.0 2390.15  2566.2 2389.32  2599.4 2388.91
  4163.8 2388.41  4207.5 2389.66  4236.4 2388.43  4400.5 2388.17  4423.6 2387.98
  4456.8 2389.34  4489.2 2387.74  4567.1 2387.58  4624.8 2387.19  4656.1 2388.25
  4669.5 2387.34  4679.4 2386.87  5038.6 2385.89  5038.9 2385.39  5042.6 2385.39
  5042.9 2385.89  5759.9 2386.75  5785.5 2388.11  5815.7 2387.07  5871.4 2387.45
  6097.5 2388.07  6107.6 2388.27  6120.4 2389.48  6137.8 2391.16  6157.9 2391.52
#Mann=11,-1,0
  2495.6   0.045       0  4163.8   0.035       0  4236.4   0.045       0
  4400.5   0.035       0  4567.1    0.07       0  4669.5   0.035       0
  4679.4   0.045       0  5038.6   0.045       0  5042.9   0.045       0
  5871.4   0.035       0  6120.4   0.063       0
Bank Sta=5038.6,5042.9
Exp/Cntr=0.3,0.1

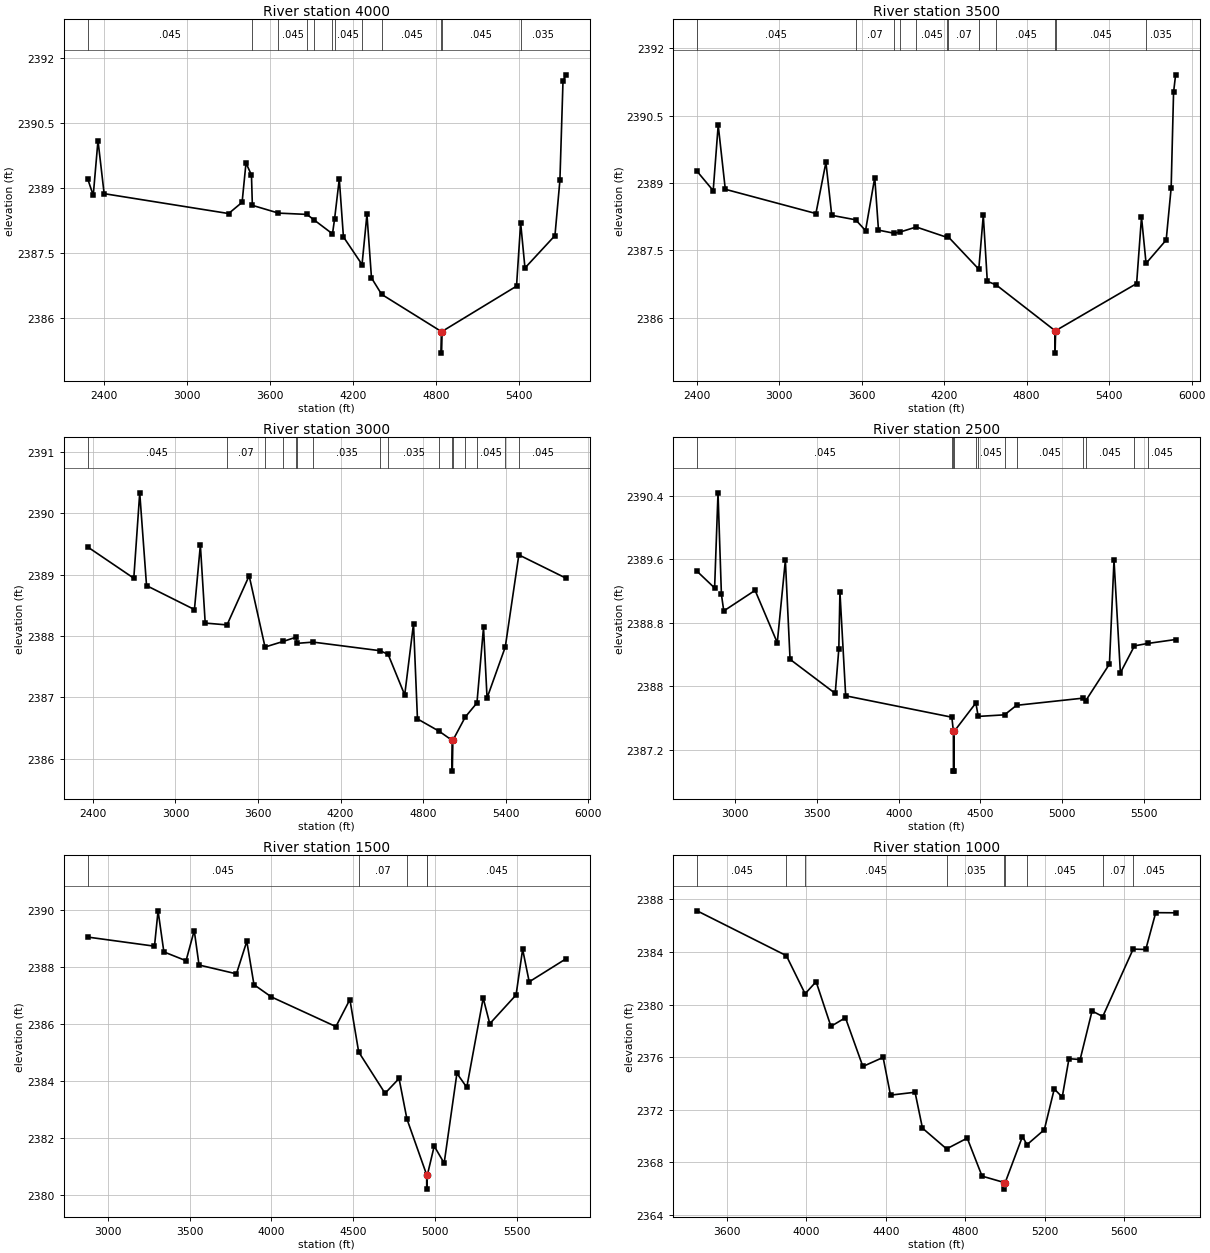
Type RM Length L Ch R = 1,4000,500,500,500
BEGIN DESCRIPTION:
Cottonwood CreekTrib039 8.0
END DESCRIPTION:
XS GIS Cut Line= 3
      1311562.67      6873512.89      1309117.39      6872324.63
      1308455.02      6871988.01
#Sta/Elev= 30
  2281.3 2389.22  2322.2 2388.83  2356.5 2390.10  2401.0 2388.87  3301.6 2388.41
  3399.1 2388.67  3427.2 2389.58  3466.8 2389.30  3473.3 2388.60  3662.3 2388.42
  3868.2 2388.39  3920.7 2388.26  4053.0 2387.94  4068.3 2388.29  4102.1 2389.21
  4132.1 2387.87  4266.7 2387.23  4302.2 2388.39  4335.1 2386.92  4408.5 2386.54
  4840.3 2385.68  4840.6 2385.18  4844.7 2385.68  5384.3 2386.73  5414.3 2388.19
  5445.4 2387.15  5662.3 2387.90  5698.2 2389.18  5720.6 2391.48  5743.0 2391.62
#Mann=12,-1,0
  2281.3   0.045       0  3473.3    0.07       0  3662.3   0.045       0
  3868.2    0.07       0  3920.7   0.045       0  4053.0    0.07       0
  4068.3   0.045       0  4266.7   0.035       0  4408.5   0.045       0
  4840.3   0.045       0  4844.7   0.045       0  5414.3   0.035       0
Bank Sta=4840.3,4844.7
Exp/Cntr=0.3,0.1

Type RM Length L Ch R = 1,3500,500,500,500
BEGIN DESCRIPTION:
Cottonwood CreekTrib039 7.0
END DESCRIPTION:
XS GIS Cut Line= 3
      1311618.29      6873505.98      1309424.40      6872117.79
      1308604.98      6871787.99
#Sta/Elev= 30
  2403.8 2389.26  2520.9 2388.83  2557.3 2390.29  2608.9 2388.86  3267.7 2388.32
  3340.6 2389.46  3382.9 2388.28  3556.9 2388.18  3628.7 2387.94  3695.7 2389.12
  3722.8 2387.95  3836.9 2387.88  3882.3 2387.91  3997.3 2388.02  4220.0 2387.79
  4227.4 2387.81  4452.1 2387.08  4484.9 2388.28  4514.1 2386.81  4578.5 2386.73
  5006.6 2385.71  5006.9 2385.21  5011.0 2385.71  5599.8 2386.76  5635.3 2388.24
  5668.5 2387.21  5814.8 2387.73  5850.9 2388.89  5868.5 2391.02  5883.3 2391.41
#Mann=12,-1,0
  2403.8   0.045       0  3556.9    0.07       0  3836.9   0.045       0
  3882.3    0.07       0  3997.3   0.045       0  4220.0   0.035       0
  4227.4    0.07       0  4452.1   0.035       0  4578.5   0.045       0
  5006.6   0.045       0  5011.0   0.045       0  5668.5   0.035       0
Bank Sta=5006.6,5011
Exp/Cntr=0.3,0.1

Type RM Length L Ch R = 1,3000,500,500,500
BEGIN DESCRIPTION:
Cottonwood CreekTrib039 6.0
END DESCRIPTION:
XS GIS Cut Line= 3
      1311743.29      6873512.93      1309701.73      6871841.64
      1309625.19      6871005.93
#Sta/Elev= 30
  2361.6 2389.45  2697.4 2388.94  2740.5 2390.33  2790.0 2388.82  3138.1 2388.43
  3181.2 2389.48  3216.4 2388.21  3374.9 2388.18  3535.8 2388.98  3651.2 2387.82
  3781.7 2387.91  3875.8 2387.98  3884.4 2387.88  4000.8 2387.90  4487.6 2387.76
  4545.9 2387.70  4666.3 2387.04  4730.2 2388.20  4758.9 2386.65  4916.0 2386.45
  5011.4 2386.30  5011.7 2385.80  5015.9 2386.30  5106.2 2386.68  5191.2 2386.91
  5239.0 2388.14  5264.7 2386.99  5397.1 2387.82  5495.7 2389.32  5839.2 2388.94
#Mann=16,-1,0
  2361.6   0.045       0  3374.9    0.07       0  3651.2   0.045       0
  3781.7    0.07       0  3875.8   0.045       0  3884.4    0.07       0
  4000.8   0.035       0  4487.6    0.07       0  4545.9   0.035       0
  4916.0   0.045       0  5011.4   0.045       0  5015.9   0.045       0
  5106.2   0.035       0  5191.2   0.045       0  5397.1   0.035       0
  5495.7   0.045       0
Bank Sta=5011.4,5015.9
Exp/Cntr=0.3,0.1

Type RM Length L Ch R = 1,2500,1000,1000,1000
BEGIN DESCRIPTION:
Cottonwood CreekTrib039 5.0
END DESCRIPTION:
XS GIS Cut Line= 3
      1311819.67      6872943.48      1310082.54      6871537.68
      1309771.05      6870915.72
#Sta/Elev= 30
  2765.3 2389.45  2872.6 2389.24  2893.4 2390.44  2914.2 2389.16  2928.6 2388.95
  3120.4 2389.21  3256.3 2388.55  3305.9 2389.59  3334.6 2388.34  3611.2 2387.91
  3633.2 2388.47  3640.0 2389.19  3675.2 2387.88  4325.5 2387.61  4334.8 2387.43
  4335.1 2386.93  4339.0 2386.93  4339.3 2387.43  4472.6 2387.79  4486.7 2387.62
  4647.9 2387.64  4721.5 2387.76  5126.7 2387.85  5145.8 2387.82  5290.4 2388.28
  5318.4 2389.59  5357.5 2388.17  5443.7 2388.51  5524.2 2388.54  5695.6 2388.59
#Mann=12,-1,0
  2765.3   0.045       0  4325.5    0.07       0  4334.8   0.045       0
  4339.3    0.07       0  4472.6   0.035       0  4486.7   0.045       0
  4647.9   0.035       0  4721.5   0.045       0  5126.7   0.035       0
  5145.8   0.045       0  5443.7   0.035       0  5524.2   0.045       0
Bank Sta=4334.8,4339.3
Exp/Cntr=0.3,0.1

Type RM Length L Ch R = 1,1500,500,500,500
BEGIN DESCRIPTION:
Cottonwood CreekTrib039 3.0
END DESCRIPTION:
XS GIS Cut Line= 3
      1311909.93      6872554.58      1310636.33      6870856.78
      1309840.42      6870797.62
#Sta/Elev= 30
  2877.6 2389.05  3285.9 2388.73  3307.7 2389.97  3343.1 2388.53  3478.5 2388.22
  3528.5 2389.28  3557.7 2388.07  3785.9 2387.76  3849.3 2388.90  3893.1 2387.38
  3999.3 2386.95  4393.1 2385.91  4478.5 2386.86  4532.1 2385.02  4693.1 2383.57
  4778.5 2384.09  4826.6 2382.67  4947.1 2380.71  4947.4 2380.21  4951.6 2380.71
  4993.1 2381.72  5053.8 2381.12  5131.7 2384.27  5191.9 2383.78  5292.1 2386.91
  5332.2 2386.01  5492.7 2387.02  5532.8 2388.62  5572.9 2387.48  5798.1 2388.29
#Mann=5,-1,0
  2877.6   0.045       0  4532.1    0.07       0  4826.6   0.045       0
  4947.1   0.045       0  4951.6   0.045       0
Bank Sta=4947.1,4951.6
Exp/Cntr=0.3,0.1

Type RM Length L Ch R = 1,1000,500,500,500
BEGIN DESCRIPTION:
Cottonwood CreekTrib039 2.0
END DESCRIPTION:
XS GIS Cut Line= 3
      1311687.71      6871825.42      1310913.47      6870482.07
      1310054.99      6870538.00
#Sta/Elev= 30
  3449.5 2387.13  3899.2 2383.72  3993.7 2380.82  4049.1 2381.74  4123.8 2378.34
  4196.8 2379.00  4284.7 2375.29  4386.7 2375.98  4424.0 2373.11  4547.6 2373.33
  4584.9 2370.60  4706.4 2369.02  4810.5 2369.84  4885.1 2366.95  4997.2 2366.46
  4997.5 2365.96  5001.8 2366.46  5088.7 2369.96  5111.6 2369.34  5198.9 2370.48
  5249.0 2373.58  5289.1 2372.96  5323.1 2375.88  5379.3 2375.82  5439.4 2379.51
  5493.3 2379.09  5646.5 2384.22  5710.0 2384.19  5760.1 2386.99  5860.3 2386.98
#Mann=9,-1,0
  3449.5   0.045       0  3899.2    0.07       0  3993.7   0.045       0
  4706.4   0.035       0  4997.2   0.035       0  5001.8   0.035       0
  5111.6   0.045       0  5493.3    0.07       0  5646.5   0.045       0
Bank Sta=4997.2,5001.8
Exp/Cntr=0.3,0.1

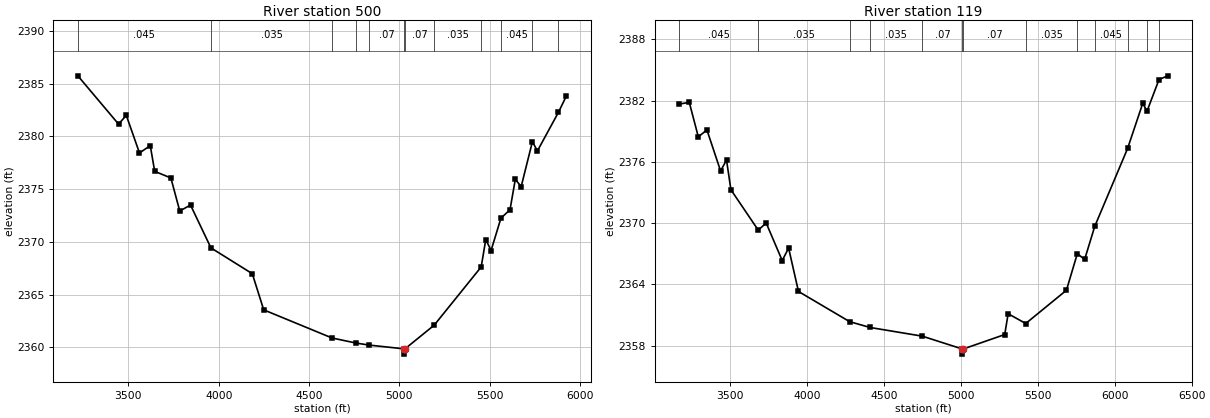
Type RM Length L Ch R = 1,500,381,381,381
BEGIN DESCRIPTION:
Cottonwood CreekTrib039 1.0
END DESCRIPTION:
XS GIS Cut Line= 4
      1311754.99      6871687.97      1311155.50      6870148.91
      1311054.30      6870070.36      1310204.96      6870438.02
#Sta/Elev= 30
  3220.2 2385.75  3445.5 2381.17  3488.5 2382.00  3561.4 2378.43  3621.1 2379.13
  3645.6 2376.69  3735.3 2376.06  3784.3 2372.93  3844.0 2373.49  3957.0 2369.43
  4186.0 2366.98  4249.2 2363.55  4627.6 2360.88  4757.8 2360.41  4831.0 2360.21
  5026.8 2359.85  5027.2 2359.35  5031.4 2359.85  5193.2 2362.10  5453.2 2367.62
  5478.7 2370.22  5508.0 2369.18  5562.4 2372.24  5612.8 2373.05  5642.1 2375.92
  5674.8 2375.25  5736.7 2379.50  5764.6 2378.63  5880.7 2382.28  5925.5 2383.86
#Mann=12,-1,0
  3220.2   0.045       0  3957.0   0.035       0  4627.6    0.07       0
  4757.8   0.035       0  4831.0    0.07       0  5026.8    0.07       0
  5031.4    0.07       0  5193.2   0.035       0  5453.2    0.07       0
  5562.4   0.045       0  5736.7    0.07       0  5880.7   0.045       0
Bank Sta=5026.8,5031.4
Exp/Cntr=0.3,0.1

Type RM Length L Ch R = 1,119,0,0,0
BEGIN DESCRIPTION:
Cottonwood CreekTrib039 0.5
END DESCRIPTION:
XS GIS Cut Line= 3
      1311815.23      6871551.70      1311300.83      6869778.69
      1310120.79      6870391.96
#Sta/Elev= 30
  3168.4 2381.67  3234.7 2381.84  3293.4 2378.46  3349.3 2379.14  3438.1 2375.12
  3476.8 2376.19  3505.2 2373.28  3682.9 2369.32  3734.5 2370.02  3838.6 2366.34
  3880.3 2367.56  3944.4 2363.31  4277.2 2360.35  4410.0 2359.78  4749.3 2358.93
  5010.0 2357.67  5010.3 2357.17  5014.6 2357.67  5285.0 2359.09  5307.1 2361.13
  5421.5 2360.17  5686.0 2363.43  5756.8 2367.01  5804.4 2366.45  5870.1 2369.69
  6083.5 2377.32  6181.9 2381.74  6209.9 2380.98  6287.9 2384.08  6344.4 2384.44
#Mann=13,-1,0
  3168.4   0.045       0  3682.9   0.035       0  4277.2    0.07       0
  4410.0   0.035       0  4749.3    0.07       0  5010.0    0.07       0
  5014.6    0.07       0  5421.5   0.035       0  5756.8    0.07       0
  5870.1   0.045       0  6083.5    0.07       0  6209.9   0.035       0
  6287.9   0.045       0
Bank Sta=5010,5014.6
Exp/Cntr=0.3,0.1

Chan Stop Cuts=-1