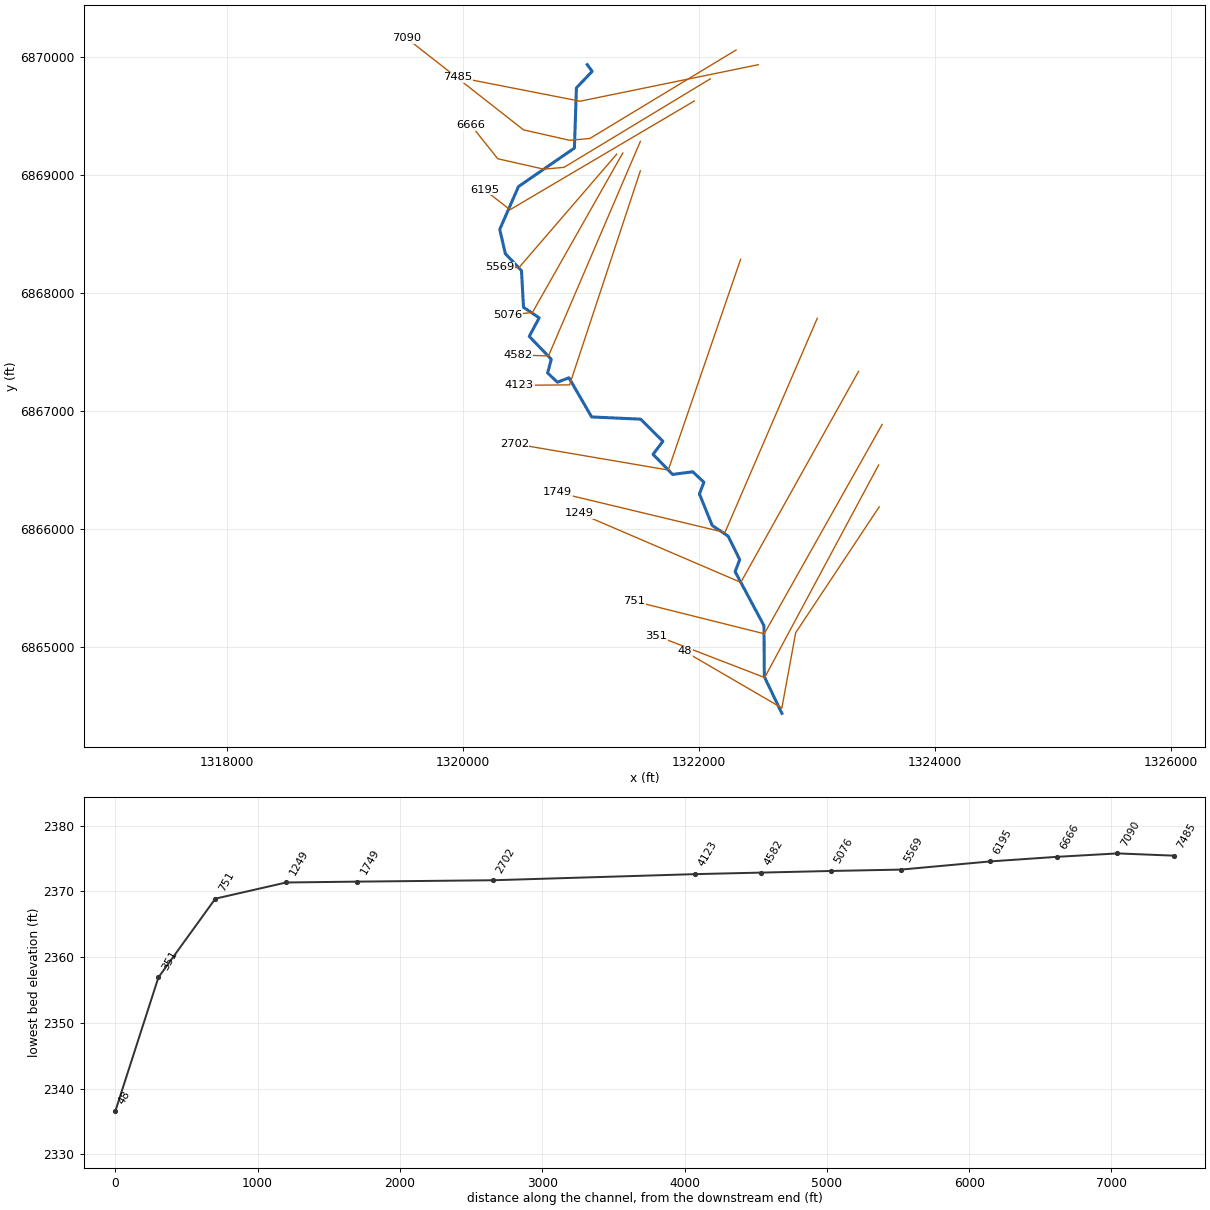
--- Cottonwood Creek Trib040.prj (project) ---

Proj Title=Cottonwood Creek Trib040 Base Level Engineering
Current Plan=p01
Default Exp/Contr=0.3,0.1
English Units
Geom File=g01
Flow File=f01
Plan File=p01
BEGIN DESCRIPTION:
Cottonwood Creek Trib040
END DESCRIPTION:

--- Cottonwood Creek Trib040.p01 (plan) ---

Plan Title=Multiple Run
Short Identifier=Multiple
Geom File=g01
Flow File=f01
Subcritical Flow
K Sum by GR= 0
Std Step Tol= 0.01
Critical Tol= 0.01
Num of Std Step Trials= 20
Max Error Tol= 0.3
Flow Tol Ratio= 0.001
Split Flow NTrial= 30
Split Flow Tol= 0.02
Split Flow Ratio= 0.02
Log Output Level= 0
Friction Slope Method= 1
Unsteady Friction Slope Method= 2
Unsteady Bridges Friction Slope Method= 1
Parabolic Critical Depth
Global Vel Dist=  1 , 1 , 1
Global Log Level= 0
CheckData=True
Encroach Param= -1, 0, 0, 0
BEGIN DESCRIPTION:
Multiple Run
END DESCRIPTION:

--- Cottonwood Creek Trib040.f01 (steady flow) ---

Flow Title=Multiple
Number of Profiles=7
Profile Names=10-year,25-year,50-year,1pct_min,100-year,1pct_plu,500-year
River Rch & RM= Cottonwood Creek,Reach-1,7485
      87     111     128      74     147     293     195
River Rch & RM= Cottonwood Creek,Reach-1,5076
     168     226     273     163     326     651     472
Boundary for River Rch & Prof#=Cottonwood Creek,Reach-1,1
Up Type=0
Dn Type=3
Dn Slope=0.005
Boundary for River Rch & Prof#=Cottonwood Creek,Reach-1,2
Up Type=0
Dn Type=3
Dn Slope=0.005
Boundary for River Rch & Prof#=Cottonwood Creek,Reach-1,3
Up Type=0
Dn Type=3
Dn Slope=0.005
Boundary for River Rch & Prof#=Cottonwood Creek,Reach-1,4
Up Type=0
Dn Type=3
Dn Slope=0.005
Boundary for River Rch & Prof#=Cottonwood Creek,Reach-1,5
Up Type=0
Dn Type=3
Dn Slope=0.005
Boundary for River Rch & Prof#=Cottonwood Creek,Reach-1,6
Up Type=0
Dn Type=3
Dn Slope=0.005
Boundary for River Rch & Prof#=Cottonwood Creek,Reach-1,7
Up Type=0
Dn Type=3
Dn Slope=0.005

--- Cottonwood Creek Trib040.g01 (geometry) ---

Geom Title=Existing Conditions

River Reach=Cottonwood Creek,Reach-1
Reach XY= 30
      1321055.00      6869938.00      1321096.23      6869881.33
      1320962.82      6869741.41      1320945.86      6869231.25
      1320471.64      6868904.68      1320312.62      6868541.33
      1320360.12      6868335.71      1320497.18      6868191.41
      1320514.18      6867881.05      1320647.33      6867791.66
      1320562.77      6867634.59      1320749.88      6867440.29
      1320718.54      6867324.56      1320801.59      6867245.83
      1320899.74      6867283.34      1321091.67      6866951.33
      1321507.43      6866932.60      1321696.03      6866744.67
      1321612.61      6866634.67      1321778.18      6866464.04
      1321948.98      6866486.38      1322043.89      6866398.08
      1322005.65      6866298.64      1322114.18      6866031.05
      1322249.58      6865940.67      1322347.17      6865741.40
      1322308.37      6865639.74      1322552.85      6865182.03
      1322556.20      6864748.50      1322705.00      6864438.00

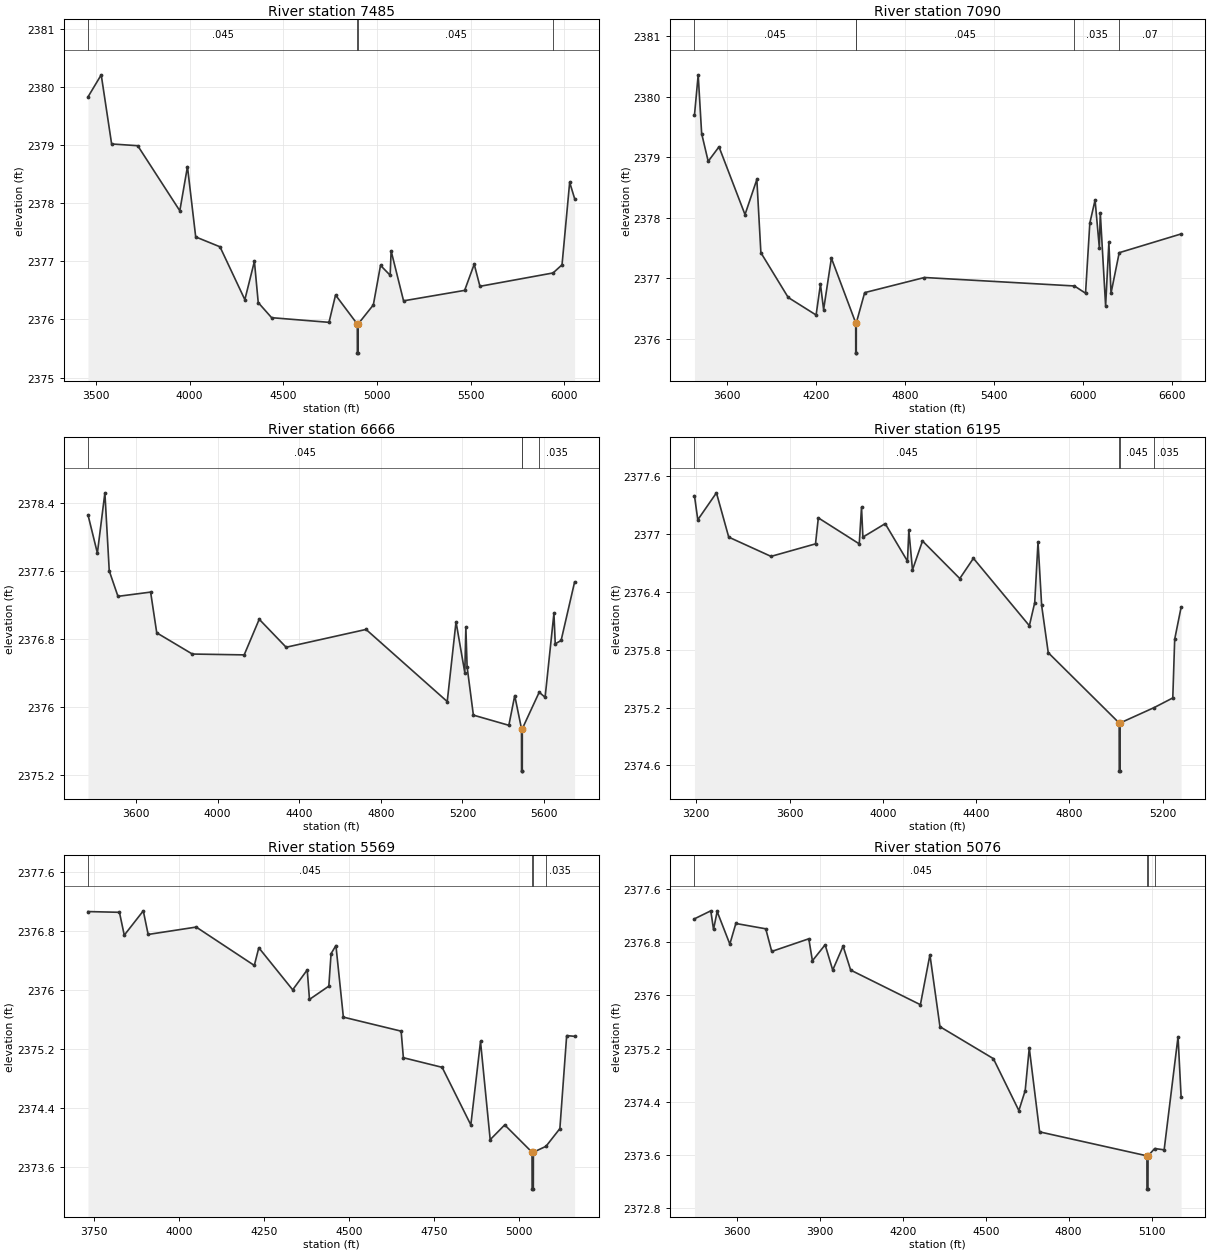
Type RM Length L Ch R = 1,7485,395,395,395
BEGIN DESCRIPTION:
Cottonwood Creek Trib040 9.0
END DESCRIPTION:
XS GIS Cut Line= 3
      1322505.03      6869938.01      1320994.41      6869628.48
      1319959.06      6869831.15
#Sta/Elev= 30
  3458.0 2379.83  3528.6 2380.21  3584.1 2379.02  3723.4 2378.99  3948.0 2377.87
  3988.8 2378.63  4032.8 2377.42  4162.4 2377.25  4295.1 2376.34  4346.1 2377.00
  4366.5 2376.29  4438.0 2376.03  4744.2 2375.95  4779.1 2376.42  4895.3 2375.92
  4895.6 2375.42  4899.1 2375.42  4899.3 2375.92  4980.8 2376.25  5019.1 2376.93
  5070.6 2376.76  5075.7 2377.18  5142.1 2376.32  5468.1 2376.50  5519.1 2376.95
  5549.7 2376.57  5939.9 2376.80  5987.8 2376.94  6028.6 2378.36  6055.0 2378.08
#Mann=4,-1,0
  3458.0   0.045       0  4895.3   0.045       0  4899.3   0.045       0
  5939.9   0.035       0
Bank Sta=4895.3,4899.3
Exp/Cntr=0.3,0.1

Type RM Length L Ch R = 1,7090,424,424,424
BEGIN DESCRIPTION:
Cottonwood Creek Trib040 8.7
END DESCRIPTION:
XS GIS Cut Line= 5
      1322316.44      6870062.57      1321076.84      6869312.56
      1320904.97      6869296.93      1320514.34      6869385.48
      1319524.78      6870161.50
#Sta/Elev= 30
  3379.9 2379.69  3405.0 2380.36  3428.3 2379.39  3472.4 2378.93  3545.2 2379.17
  3720.5 2378.05  3800.3 2378.63  3827.5 2377.42  4011.7 2376.68  4199.7 2376.39
  4229.0 2376.90  4250.3 2376.48  4302.7 2377.33  4466.6 2376.26  4466.8 2375.76
  4470.3 2375.76  4470.6 2376.26  4527.0 2376.76  4930.1 2377.01  5940.6 2376.87
  6015.5 2376.75  6044.4 2377.91  6079.7 2378.29  6108.6 2377.50  6114.9 2378.08
  6150.8 2376.54  6172.8 2377.59  6187.2 2376.75  6242.4 2377.42  6659.4 2377.73
#Mann=5,-1,0
  3379.9   0.045       0  4466.6   0.045       0  4470.6   0.045       0
  5940.6   0.035       0  6242.4    0.07       0
Bank Sta=4466.6,4470.6
Exp/Cntr=0.3,0.1

Type RM Length L Ch R = 1,6666,471,471,471
BEGIN DESCRIPTION:
Cottonwood Creek Trib040 8.6
END DESCRIPTION:
XS GIS Cut Line= 5
      1322097.71      6869817.79      1320858.09      6869067.77
      1320686.22      6869052.14      1320295.59      6869140.68
      1320069.01      6869425.09
#Sta/Elev= 30
  3364.3 2378.26  3410.3 2377.81  3447.1 2378.52  3468.5 2377.60  3511.2 2377.30
  3671.3 2377.35  3701.3 2376.87  3875.8 2376.62  4130.0 2376.61  4203.7 2377.03
  4335.6 2376.70  4727.4 2376.91  5125.4 2376.06  5168.5 2377.00  5211.6 2376.40
  5216.7 2376.94  5222.8 2376.47  5253.6 2375.90  5427.5 2375.78  5456.3 2376.13
  5489.5 2375.74  5489.8 2375.24  5493.3 2375.24  5493.5 2375.74  5576.3 2376.17
  5605.2 2376.11  5648.5 2377.10  5654.9 2376.74  5683.7 2376.78  5749.9 2377.47
#Mann=4,-1,0
  3364.3   0.045       0  5489.5   0.045       0  5493.5   0.045       0
  5576.3   0.035       0
Bank Sta=5489.5,5493.5
Exp/Cntr=0.3,0.1

Type RM Length L Ch R = 1,6195,626,626,626
BEGIN DESCRIPTION:
Cottonwood Creek Trib040 8.5
END DESCRIPTION:
XS GIS Cut Line= 3
      1321962.27      6869630.28      1320399.76      6868708.39
      1320183.98      6868876.45
#Sta/Elev= 30
  3191.9 2377.40  3206.2 2377.15  3286.2 2377.43  3338.9 2376.97  3520.4 2376.77
  3711.2 2376.90  3723.3 2377.17  3898.9 2376.90  3908.6 2377.28  3914.5 2376.97
  4010.2 2377.11  4105.8 2376.72  4111.6 2377.04  4127.3 2376.63  4170.2 2376.93
  4330.2 2376.54  4388.7 2376.75  4628.7 2376.05  4651.7 2376.29  4665.8 2376.92
  4681.4 2376.26  4709.7 2375.77  5014.0 2375.04  5014.3 2374.54  5017.8 2374.54
  5018.0 2375.04  5164.1 2375.20  5244.0 2375.30  5252.2 2375.91  5279.6 2376.24
#Mann=4,-1,0
  3191.9   0.045       0  5014.0   0.045       0  5018.0   0.045       0
  5164.1   0.035       0
Bank Sta=5014,5018
Exp/Cntr=0.3,0.1

Type RM Length L Ch R = 1,5569,493,493,493
BEGIN DESCRIPTION:
Cottonwood Creek Trib040 8.0
END DESCRIPTION:
XS GIS Cut Line= 3
      1321304.01      6869178.95      1320475.93      6868218.02
      1320311.64      6868219.31
#Sta/Elev= 30
  3731.5 2377.06  3824.1 2377.05  3838.3 2376.74  3894.3 2377.07  3908.6 2376.75
  4050.1 2376.85  4221.2 2376.33  4234.4 2376.57  4334.2 2376.00  4377.0 2376.27
  4383.6 2375.87  4440.6 2376.05  4447.2 2376.49  4461.5 2376.60  4483.4 2375.63
  4653.5 2375.44  4660.1 2375.08  4774.2 2374.95  4858.7 2374.17  4887.2 2375.30
  4915.7 2373.97  4958.5 2374.17  5038.9 2373.80  5039.2 2373.30  5042.7 2373.30
  5042.9 2373.80  5080.0 2373.88  5120.9 2374.12  5140.9 2375.38  5164.3 2375.37
#Mann=4,-1,0
  3731.5   0.045       0  5038.9   0.045       0  5042.9   0.045       0
  5080.0   0.035       0
Bank Sta=5038.9,5042.9
Exp/Cntr=0.3,0.1

Type RM Length L Ch R = 1,5076,494,494,494
BEGIN DESCRIPTION:
Cottonwood Creek Trib040 7.0
END DESCRIPTION:
XS GIS Cut Line= 3
      1321356.11      6869189.39      1320589.80      6867837.13
      1320384.10      6867814.81
#Sta/Elev= 30
  3445.7 2377.15  3504.8 2377.27  3514.7 2376.99  3527.8 2377.26  3573.7 2376.77
  3595.5 2377.08  3703.7 2377.00  3725.3 2376.66  3859.5 2376.85  3872.6 2376.52
  3918.6 2376.76  3946.1 2376.38  3983.6 2376.74  4011.0 2376.38  4263.4 2375.86
  4297.9 2376.61  4334.2 2375.53  4527.5 2375.05  4619.8 2374.27  4642.7 2374.57
  4657.4 2375.21  4694.9 2373.95  5083.3 2373.59  5083.5 2373.09  5087.0 2373.09
  5087.3 2373.59  5111.5 2373.70  5145.6 2373.68  5195.9 2375.38  5206.9 2374.48
#Mann=4,-1,0
  3445.7   0.045       0  5083.3   0.045       0  5087.3   0.045       0
  5111.5   0.035       0
Bank Sta=5083.3,5087.3
Exp/Cntr=0.3,0.1

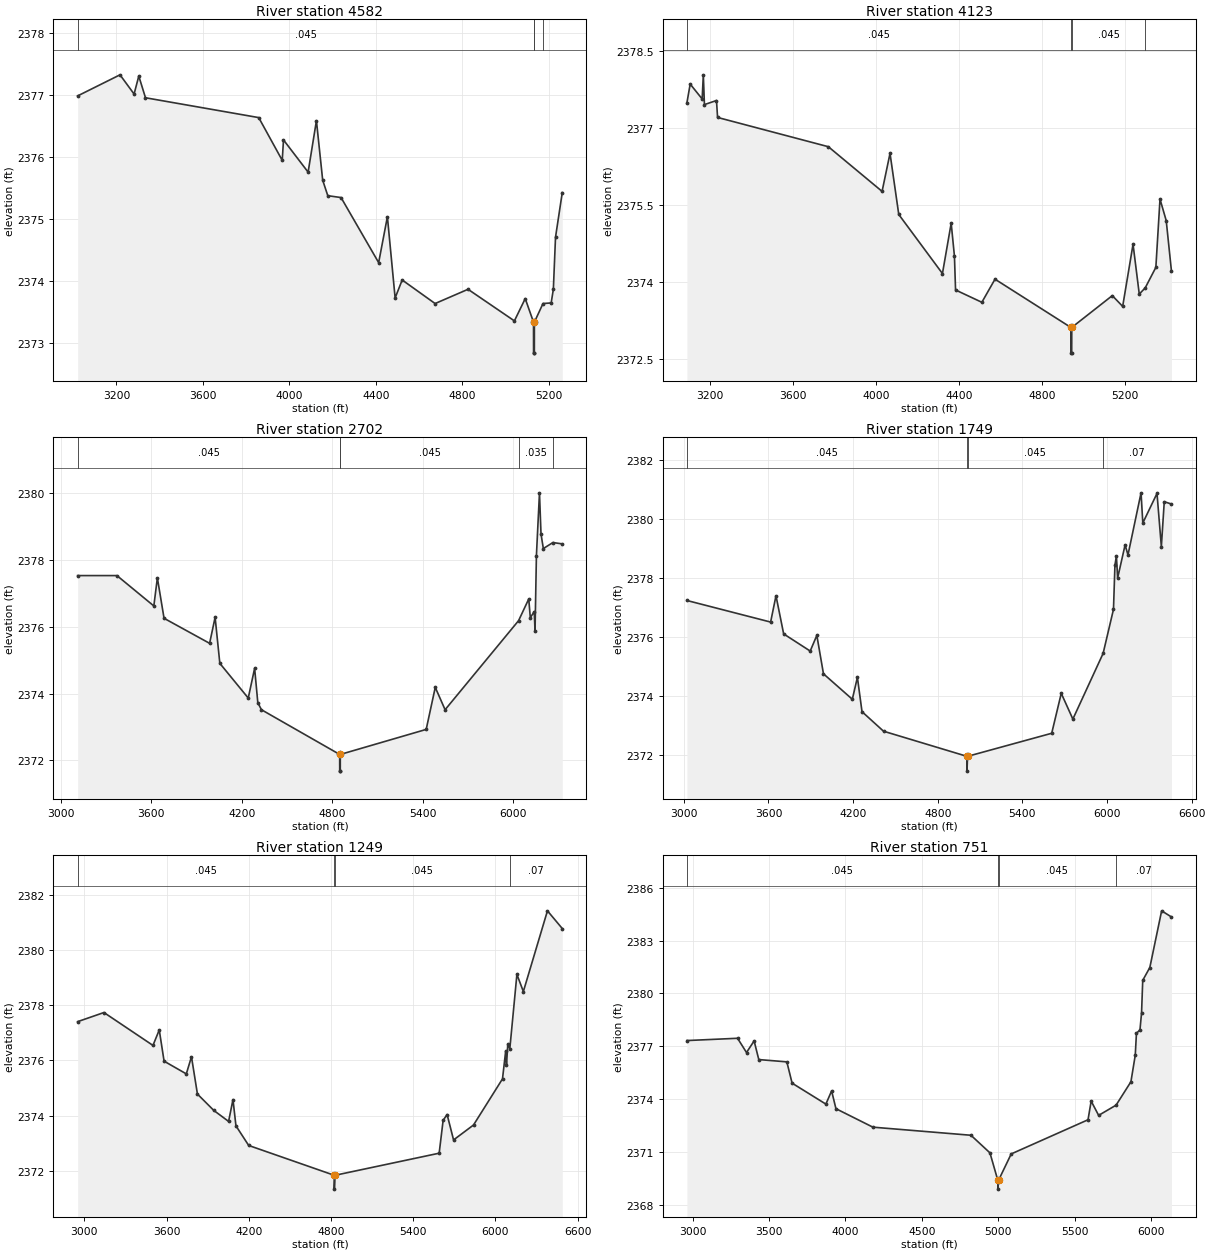
Type RM Length L Ch R = 1,4582,459,459,459
BEGIN DESCRIPTION:
Cottonwood Creek Trib040 6.0
END DESCRIPTION:
XS GIS Cut Line= 3
      1321504.99      6869287.98      1320725.59      6867468.16
      1320463.78      6867478.19
#Sta/Elev= 30
  3020.3 2376.99  3216.2 2377.33  3281.4 2377.02  3303.1 2377.31  3334.1 2376.96
  3857.9 2376.64  3966.7 2375.95  3972.5 2376.28  4086.4 2375.76  4124.8 2376.59
  4153.8 2375.63  4177.4 2375.38  4238.7 2375.35  4412.7 2374.30  4453.1 2375.04
  4488.9 2373.73  4521.5 2374.02  4673.8 2373.64  4826.1 2373.87  5040.6 2373.36
  5090.7 2373.72  5129.0 2373.34  5129.3 2372.84  5132.9 2372.84  5133.1 2373.34
  5172.9 2373.64  5210.7 2373.65  5220.8 2373.87  5230.8 2374.71  5262.0 2375.43
#Mann=4,-1,0
  3020.3   0.045       0  5129.0   0.045       0  5133.1   0.045       0
  5172.9   0.035       0
Bank Sta=5129,5133.1
Exp/Cntr=0.3,0.1

Type RM Length L Ch R = 1,4123,1421,1421,1421
BEGIN DESCRIPTION:
Cottonwood Creek Trib040 5.0
END DESCRIPTION:
XS GIS Cut Line= 3
      1321505.00      6869038.01      1320904.91      6867223.25
      1320479.63      6867219.76
#Sta/Elev= 30
  3088.6 2377.48  3104.5 2377.85  3162.3 2377.56  3167.9 2378.03  3173.2 2377.45
  3231.4 2377.53  3236.6 2377.20  3770.7 2376.63  4029.8 2375.76  4068.1 2376.50
  4110.3 2375.31  4320.9 2374.16  4363.0 2375.14  4378.7 2374.50  4384.1 2373.84
  4510.9 2373.60  4574.3 2374.05  4940.3 2373.11  4940.5 2372.61  4944.1 2372.61
  4944.4 2373.11  5139.9 2373.73  5189.9 2373.52  5239.9 2374.73  5269.9 2373.76
  5298.5 2373.88  5349.9 2374.28  5369.9 2375.61  5399.9 2375.19  5425.3 2374.20
#Mann=4,-1,0
  3088.6   0.045       0  4940.3   0.045       0  4944.4   0.045       0
  5298.5   0.035       0
Bank Sta=4940.3,4944.4
Exp/Cntr=0.3,0.1

Type RM Length L Ch R = 1,2702,953,953,953
BEGIN DESCRIPTION:
Cottonwood Creek Trib040 4.0
END DESCRIPTION:
XS GIS Cut Line= 3
      1322355.02      6868288.05      1321741.62      6866501.20
      1320436.01      6866724.08
#Sta/Elev= 30
  3110.8 2377.54  3371.3 2377.54  3616.0 2376.63  3639.5 2377.47  3683.8 2376.26
  3985.9 2375.51  4022.4 2376.29  4053.7 2374.91  4242.1 2373.87  4284.4 2374.76
  4305.6 2373.73  4329.7 2373.52  4848.4 2372.18  4848.7 2371.68  4852.4 2371.68
  4852.6 2372.18  5422.1 2372.93  5482.3 2374.19  5547.5 2373.52  6034.9 2376.19
  6102.3 2376.84  6112.5 2376.28  6138.8 2376.46  6143.9 2375.87  6153.1 2378.14
  6173.4 2380.02  6183.5 2378.79  6199.0 2378.35  6262.4 2378.53  6324.5 2378.49
#Mann=5,-1,0
  3110.8   0.045       0  4848.4   0.045       0  4852.6   0.045       0
  6034.9   0.035       0  6262.4    0.07       0
Bank Sta=4848.4,4852.6
Exp/Cntr=0.3,0.1

Type RM Length L Ch R = 1,1749,500,500,500
BEGIN DESCRIPTION:
Cottonwood Creek Trib040 3.0
END DESCRIPTION:
XS GIS Cut Line= 3
      1323005.00      6867788.01      1322222.11      6865971.54
      1320805.12      6866311.06
#Sta/Elev= 30
  3022.0 2377.24  3615.6 2376.51  3653.6 2377.40  3708.0 2376.11  3896.1 2375.53
  3943.2 2376.06  3990.2 2374.76  4194.7 2373.90  4230.7 2374.64  4263.4 2373.48
  4415.8 2372.82  5007.2 2371.97  5007.5 2371.47  5011.6 2371.97  5608.0 2372.75
  5675.7 2374.10  5758.0 2373.23  5972.4 2375.45  6045.9 2376.94  6056.2 2378.43
  6066.5 2378.75  6075.4 2378.00  6128.2 2379.12  6148.7 2378.78  6241.3 2380.88
  6253.8 2379.86  6354.4 2380.86  6385.2 2379.06  6405.8 2380.58  6457.1 2380.50
#Mann=4,-1,0
  3022.0   0.045       0  5007.2   0.045       0  5011.6   0.045       0
  5972.4    0.07       0
Bank Sta=5007.2,5011.6
Exp/Cntr=0.3,0.1

Type RM Length L Ch R = 1,1249,498,498,498
BEGIN DESCRIPTION:
Cottonwood Creek Trib040 2.0
END DESCRIPTION:
XS GIS Cut Line= 3
      1323355.01      6867338.01      1322356.65      6865548.69
      1320989.79      6866135.25
#Sta/Elev= 30
  2951.0 2377.40  3143.0 2377.73  3500.7 2376.54  3546.5 2377.10  3581.8 2375.97
  3744.0 2375.51  3781.7 2376.13  3825.1 2374.78  3944.0 2374.19  4052.5 2373.79
  4084.5 2374.58  4106.2 2373.63  4199.2 2372.92  4823.9 2371.84  4824.2 2371.34
  4828.3 2371.84  5589.1 2372.64  5618.1 2373.83  5647.1 2374.04  5694.2 2373.12
  5839.7 2373.66  6051.3 2375.33  6074.8 2376.35  6080.3 2375.82  6090.0 2376.59
  6104.7 2376.42  6156.4 2379.11  6203.5 2378.49  6379.3 2381.41  6487.4 2380.77
#Mann=4,-1,0
  2951.0   0.045       0  4823.9   0.045       0  4828.3   0.045       0
  6104.7    0.07       0
Bank Sta=4823.9,4828.3
Exp/Cntr=0.3,0.1

Type RM Length L Ch R = 1,751,400,400,400
BEGIN DESCRIPTION:
Cottonwood Creek Trib040 1.0
END DESCRIPTION:
XS GIS Cut Line= 3
      1323555.01      6866888.01      1322555.31      6865112.96
      1321454.97      6865388.01
#Sta/Elev= 30
  2962.8 2377.32  3294.5 2377.45  3353.0 2376.64  3402.8 2377.30  3433.4 2376.24
  3617.0 2376.11  3651.4 2374.90  3872.4 2373.71  3910.0 2374.46  3938.3 2373.45
  4180.2 2372.40  4821.9 2371.94  4946.1 2370.94  4997.7 2369.38  4998.0 2368.88
  5002.2 2369.38  5085.3 2370.88  5587.9 2372.82  5608.5 2373.88  5657.4 2373.07
  5771.5 2373.65  5868.7 2374.98  5897.1 2376.49  5904.8 2377.73  5928.0 2377.93
  5938.3 2378.90  5946.0 2380.74  5992.4 2381.47  6069.7 2384.69  6134.2 2384.34
#Mann=4,-1,0
  2962.8   0.045       0  4997.7   0.045       0  5002.2   0.045       0
  5771.5    0.07       0
Bank Sta=4997.7,5002.2
Exp/Cntr=0.3,0.1

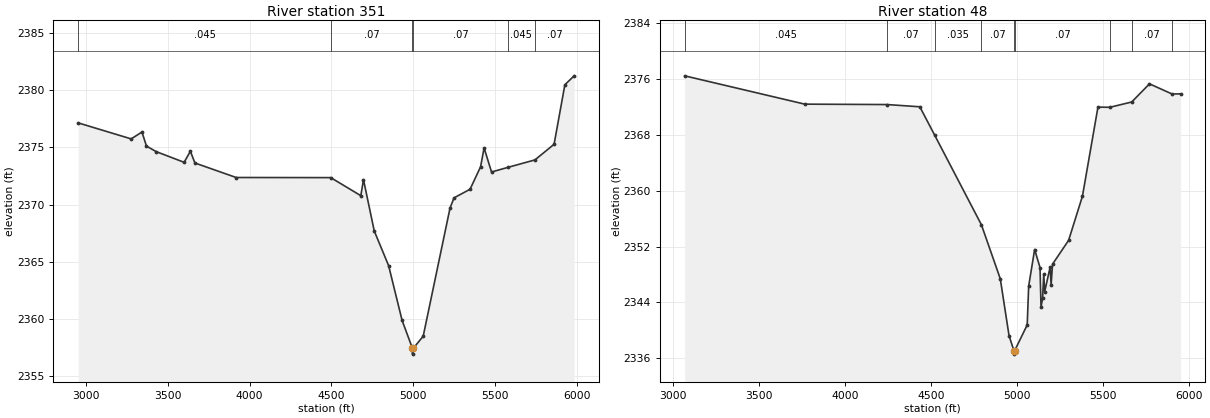
Type RM Length L Ch R = 1,351,303,303,303
BEGIN DESCRIPTION:
Cottonwood Creek Trib040 0.6
END DESCRIPTION:
XS GIS Cut Line= 3
      1323525.03      6866543.73      1322558.86      6864741.60
      1321642.19      6865095.78
#Sta/Elev= 30
  2954.2 2377.15  3277.5 2375.75  3343.3 2376.35  3370.9 2375.12  3431.0 2374.63
  3600.8 2373.70  3639.0 2374.67  3666.6 2373.64  3918.4 2372.37  4495.8 2372.36
  4679.4 2370.78  4695.7 2372.18  4761.4 2367.69  4849.2 2364.65  4931.2 2359.87
  4994.7 2357.41  4995.0 2356.91  4999.3 2357.41  5060.2 2358.48  5223.9 2369.69
  5248.5 2370.59  5346.2 2371.34  5410.5 2373.31  5431.9 2374.96  5477.4 2372.85
  5575.4 2373.25  5742.4 2373.91  5859.2 2375.28  5925.1 2380.49  5981.7 2381.27
#Mann=6,-1,0
  2954.2   0.045       0  4495.8    0.07       0  4994.7    0.07       0
  4999.3    0.07       0  5575.4   0.045       0  5742.4    0.07       0
Bank Sta=4994.7,4999.3
Exp/Cntr=0.3,0.1

Type RM Length L Ch R = 1,48,0,0,0
BEGIN DESCRIPTION:
Cottonwood Creek Trib040 0.5
END DESCRIPTION:
XS GIS Cut Line= 4
      1323530.21      6866189.51      1322821.88      6865121.81
      1322704.70      6864483.79      1321881.82      6864962.94
#Sta/Elev= 30
  3066.6 2376.47  3764.4 2372.41  4243.7 2372.35  4433.1 2372.03  4520.2 2367.93
  4791.0 2355.12  4900.8 2347.37  4951.6 2339.23  4979.8 2337.07  4980.2 2336.57
  4984.4 2337.07  5057.3 2340.76  5065.7 2346.31  5100.4 2351.57  5131.7 2348.98
  5137.5 2343.30  5146.7 2344.60  5153.2 2348.04  5159.0 2345.54  5190.5 2349.05
  5196.2 2346.49  5204.5 2349.47  5298.0 2352.89  5378.2 2359.21  5468.4 2371.98
  5538.1 2371.96  5664.7 2372.72  5767.9 2375.32  5899.5 2373.86  5948.8 2373.89
#Mann=9,-1,0
  3066.6   0.045       0  4243.7    0.07       0  4520.2   0.035       0
  4791.0    0.07       0  4979.8    0.07       0  4984.4    0.07       0
  5538.1   0.045       0  5664.7    0.07       0  5899.5   0.045       0
Bank Sta=4979.8,4984.4
Exp/Cntr=0.3,0.1

Chan Stop Cuts=-1