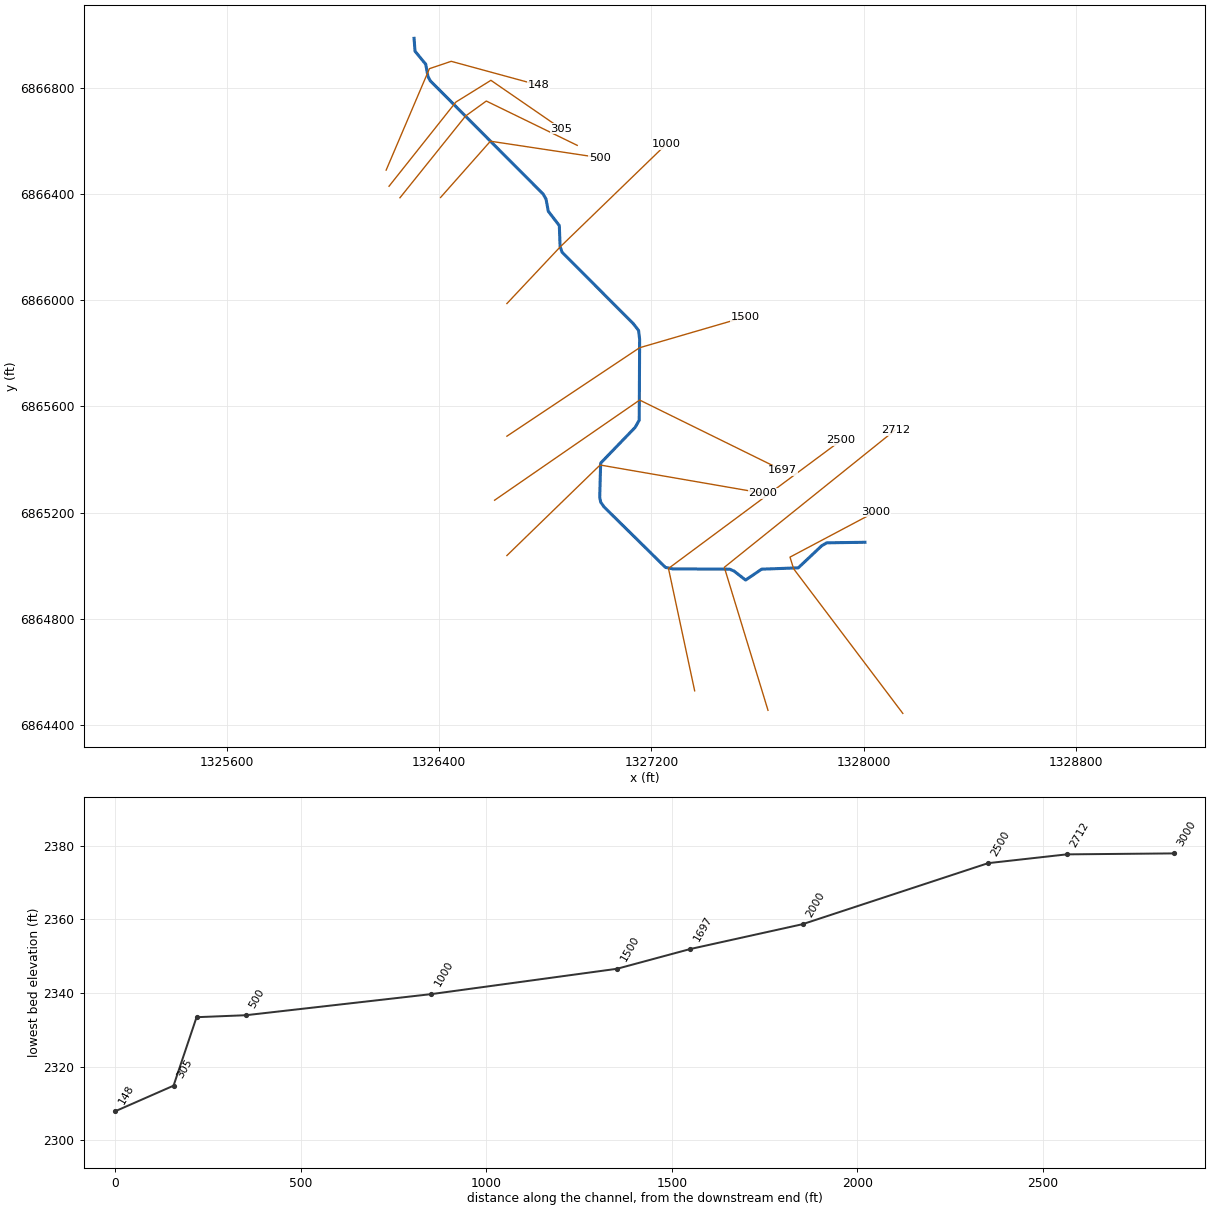
--- Cottonwood Creek Trib041.prj (project) ---

Proj Title=Cottonwood Creek Trib041 Base Level Engineering
Current Plan=p01
Default Exp/Contr=0.3,0.1
English Units
Geom File=g01
Flow File=f01
Plan File=p01
BEGIN DESCRIPTION:
Cottonwood Creek Trib041
END DESCRIPTION:

--- Cottonwood Creek Trib041.p01 (plan) ---

Plan Title=Multiple Run
Short Identifier=Multiple
Geom File=g01
Flow File=f01
Subcritical Flow
K Sum by GR= 0
Std Step Tol= 0.01
Critical Tol= 0.01
Num of Std Step Trials= 20
Max Error Tol= 0.3
Flow Tol Ratio= 0.001
Split Flow NTrial= 30
Split Flow Tol= 0.02
Split Flow Ratio= 0.02
Log Output Level= 0
Friction Slope Method= 1
Unsteady Friction Slope Method= 2
Unsteady Bridges Friction Slope Method= 1
Parabolic Critical Depth
Global Vel Dist=  1 , 1 , 1
Global Log Level= 0
CheckData=True
Encroach Param= -1, 0, 0, 0
BEGIN DESCRIPTION:
Multiple Run
END DESCRIPTION:

--- Cottonwood Creek Trib041.f01 (steady flow) ---

Flow Title=Multiple
Number of Profiles=7
Profile Names=10-year,25-year,50-year,1pct_min,100-year,1pct_plu,500-year
River Rch & RM= Cottonwood Creek,Reach-1,3000
     230     320     393     240     479     956     721
Boundary for River Rch & Prof#=Cottonwood Creek,Reach-1,1
Up Type=0
Dn Type=3
Dn Slope=0.005
Boundary for River Rch & Prof#=Cottonwood Creek,Reach-1,2
Up Type=0
Dn Type=3
Dn Slope=0.005
Boundary for River Rch & Prof#=Cottonwood Creek,Reach-1,3
Up Type=0
Dn Type=3
Dn Slope=0.005
Boundary for River Rch & Prof#=Cottonwood Creek,Reach-1,4
Up Type=0
Dn Type=3
Dn Slope=0.005
Boundary for River Rch & Prof#=Cottonwood Creek,Reach-1,5
Up Type=0
Dn Type=3
Dn Slope=0.005
Boundary for River Rch & Prof#=Cottonwood Creek,Reach-1,6
Up Type=0
Dn Type=3
Dn Slope=0.005
Boundary for River Rch & Prof#=Cottonwood Creek,Reach-1,7
Up Type=0
Dn Type=3
Dn Slope=0.005

--- Cottonwood Creek Trib041.g01 (geometry) ---

Geom Title=Existing Conditions

River Reach=Cottonwood Creek,Reach-1
Reach XY= 30
      1328005.00      6865088.00      1327860.84      6865085.98
      1327841.69      6865074.61      1327753.53      6864991.56
      1327615.44      6864986.60      1327555.00      6864945.56
      1327511.19      6864979.55      1327494.56      6864986.62
      1327279.88      6864987.70      1327252.55      6864993.46
      1327021.43      6865221.24      1327008.53      6865239.47
      1327004.94      6865257.99      1327008.53      6865386.53
      1327138.57      6865521.24      1327153.95      6865548.43
      1327155.49      6865853.20      1327151.46      6865886.54
      1327132.14      6865911.53      1326862.86      6866181.83
      1326855.52      6866203.22      1326852.67      6866282.03
      1326811.14      6866335.83      1326802.50      6866381.97
      1326791.38      6866401.22      1326365.75      6866828.31
      1326357.47      6866844.02      1326349.03      6866890.24
      1326308.60      6866939.49      1326305.00      6866988.00

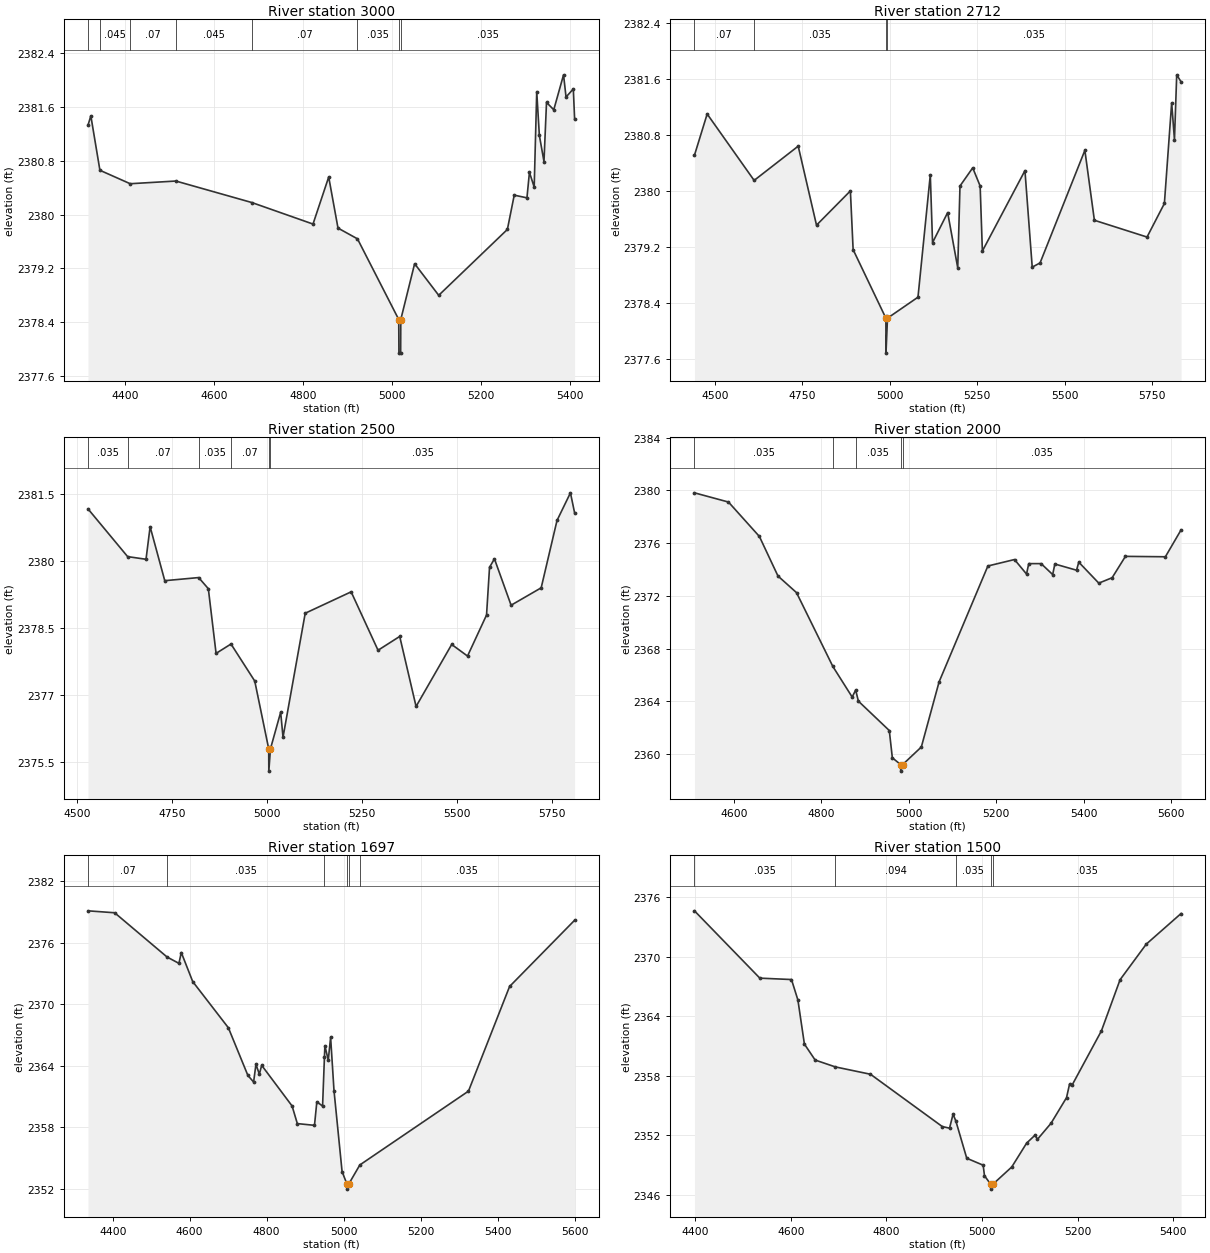
Type RM Length L Ch R = 1,3000,288,288,288
BEGIN DESCRIPTION:
Cottonwood Creek Trib041 6.0
END DESCRIPTION:
XS GIS Cut Line= 4
      1328147.66      6864442.91      1327736.05      6864988.07
      1327722.39      6865032.03      1328045.02      6865203.09
#Sta/Elev= 30
  4316.9 2381.33  4323.3 2381.47  4343.7 2380.66  4411.8 2380.46  4514.5 2380.50
  4685.4 2380.18  4822.9 2379.86  4858.2 2380.56  4879.1 2379.80  4922.9 2379.64
  5015.7 2378.44  5016.1 2377.94  5020.0 2377.94  5020.3 2378.44  5051.4 2379.27
  5105.6 2378.80  5260.0 2379.78  5275.4 2380.29  5304.0 2380.25  5309.6 2380.63
  5320.3 2380.41  5326.0 2381.83  5331.9 2381.18  5342.3 2380.79  5348.0 2381.67
  5364.3 2381.56  5386.3 2382.08  5391.9 2381.75  5408.3 2381.87  5411.2 2381.42
#Mann=8,-1,0
  4316.9    0.07       0  4343.7   0.045       0  4411.8    0.07       0
  4514.5   0.045       0  4685.4    0.07       0  4922.9   0.035       0
  5015.7   0.035       0  5020.3   0.035       0
Bank Sta=5015.7,5020.3
Exp/Cntr=0.3,0.1

Type RM Length L Ch R = 1,2712,212,212,212
BEGIN DESCRIPTION:
Cottonwood Creek Trib041 5.5
END DESCRIPTION:
XS GIS Cut Line= 3
      1327639.43      6864454.49      1327474.73      6864993.65
      1328119.04      6865511.37
#Sta/Elev= 30
  4441.9 2380.51  4478.2 2381.10  4612.4 2380.15  4738.3 2380.64  4790.6 2379.51
  4887.4 2380.00  4895.2 2379.16  4988.8 2378.18  4989.1 2377.68  4993.4 2378.18
  5080.5 2378.48  5115.7 2380.23  5122.1 2379.26  5165.3 2379.69  5194.1 2378.90
  5200.5 2380.07  5236.9 2380.33  5258.1 2380.07  5264.5 2379.14  5386.1 2380.29
  5406.9 2378.91  5429.3 2378.97  5557.3 2380.58  5584.5 2379.58  5734.9 2379.34
  5784.5 2379.82  5805.3 2381.26  5813.3 2380.73  5819.7 2381.66  5832.2 2381.56
#Mann=4,-1,0
  4441.9    0.07       0  4612.4   0.035       0  4988.8   0.035       0
  4993.4   0.035       0
Bank Sta=4988.8,4993.4
Exp/Cntr=0.3,0.1

Type RM Length L Ch R = 1,2500,500,500,500
BEGIN DESCRIPTION:
Cottonwood Creek Trib041 5.0
END DESCRIPTION:
XS GIS Cut Line= 3
      1327362.94      6864527.96      1327264.23      6864989.31
      1327915.07      6865472.33
#Sta/Elev= 30
  4528.2 2381.17  4632.6 2380.10  4681.1 2380.04  4691.9 2380.77  4730.5 2379.56
  4819.8 2379.63  4845.3 2379.38  4865.7 2377.93  4905.0 2378.14  4967.6 2377.31
  5004.4 2375.79  5004.7 2375.29  5009.0 2375.79  5035.9 2376.61  5042.1 2376.05
  5100.6 2378.83  5221.6 2379.31  5292.5 2378.00  5349.6 2378.31  5392.7 2376.74
  5486.6 2378.13  5528.3 2377.87  5578.4 2378.79  5586.3 2379.86  5599.2 2380.05
  5643.1 2379.01  5722.4 2379.40  5764.1 2380.91  5799.5 2381.53  5810.5 2381.08
#Mann=6,-1,0
  4528.2   0.035       0  4632.6    0.07       0  4819.8   0.035       0
  4905.0    0.07       0  5004.4    0.07       0  5009.0   0.035       0
Bank Sta=5004.4,5009
Exp/Cntr=0.3,0.1

Type RM Length L Ch R = 1,2000,303,303,303
BEGIN DESCRIPTION:
Cottonwood Creek Trib041 4.0
END DESCRIPTION:
XS GIS Cut Line= 3
      1326655.01      6865038.01      1327006.43      6865379.35
      1327620.40      6865273.06
#Sta/Elev= 30
  4510.1 2379.81  4587.9 2379.11  4658.6 2376.50  4701.1 2373.50  4743.5 2372.24
  4826.6 2366.64  4870.8 2364.32  4878.8 2364.85  4885.0 2364.01  4955.7 2361.78
  4962.7 2359.71  4981.6 2359.20  4981.9 2358.70  4986.4 2359.20  5029.0 2360.53
  5069.6 2365.47  5181.2 2374.26  5242.1 2374.75  5269.6 2373.65  5274.7 2374.44
  5303.0 2374.44  5329.4 2373.61  5334.4 2374.41  5384.0 2373.94  5389.1 2374.55
  5434.9 2372.96  5465.4 2373.37  5495.8 2374.99  5587.2 2374.96  5623.1 2377.00
#Mann=5,-1,0
  4510.1   0.035       0  4826.6    0.07       0  4878.8   0.035       0
  4981.6   0.035       0  4986.4   0.035       0
Bank Sta=4981.6,4986.4
Exp/Cntr=0.3,0.1

Type RM Length L Ch R = 1,1697,197,197,197
BEGIN DESCRIPTION:
Cottonwood Creek Trib041 3.5
END DESCRIPTION:
XS GIS Cut Line= 3
      1326608.61      6865246.61      1327155.49      6865624.21
      1327693.71      6865359.44
#Sta/Elev= 30
  4335.8 2379.12  4405.1 2378.93  4541.2 2374.61  4572.1 2373.99  4578.2 2375.05
  4607.9 2372.21  4700.5 2367.70  4751.3 2363.04  4766.1 2362.40  4772.2 2364.13
  4781.0 2363.17  4787.1 2364.03  4866.1 2360.06  4879.7 2358.34  4924.3 2358.17
  4930.4 2360.47  4945.3 2360.05  4950.2 2364.87  4951.3 2365.95  4960.1 2364.54
  4966.2 2366.77  4975.0 2361.56  4996.0 2353.65  5008.6 2352.44  5008.9 2351.94
  5013.4 2352.44  5042.1 2354.30  5324.4 2361.51  5431.2 2371.73  5600.2 2378.20
#Mann=6,-1,0
  4335.8    0.07       0  4541.2   0.035       0  4950.2   0.094       0
  5008.6    0.07       0  5013.4   0.094       0  5042.1   0.035       0
Bank Sta=5008.6,5013.4
Exp/Cntr=0.3,0.1

Type RM Length L Ch R = 1,1500,500,500,500
BEGIN DESCRIPTION:
Cottonwood Creek Trib041 3.0
END DESCRIPTION:
XS GIS Cut Line= 3
      1326654.97      6865487.98      1327155.32      6865821.47
      1327554.98      6865937.99
#Sta/Elev= 30
  4398.7 2374.61  4535.4 2367.83  4601.6 2367.69  4615.0 2365.63  4628.6 2361.19
  4651.1 2359.58  4693.3 2358.89  4766.8 2358.15  4917.0 2352.88  4932.1 2352.72
  4939.5 2354.13  4945.3 2353.44  4968.1 2349.69  5002.4 2348.99  5005.2 2347.93
  5018.0 2347.08  5018.4 2346.58  5022.9 2347.08  5062.2 2348.81  5093.4 2351.22
  5110.8 2352.01  5116.0 2351.60  5144.3 2353.21  5176.7 2355.79  5183.0 2357.14
  5188.2 2357.04  5249.7 2362.52  5288.7 2367.67  5343.4 2371.25  5416.3 2374.34
#Mann=5,-1,0
  4398.7   0.035       0  4693.3   0.094       0  4945.3   0.035       0
  5018.0   0.035       0  5022.9   0.035       0
Bank Sta=5018,5022.9
Exp/Cntr=0.3,0.1

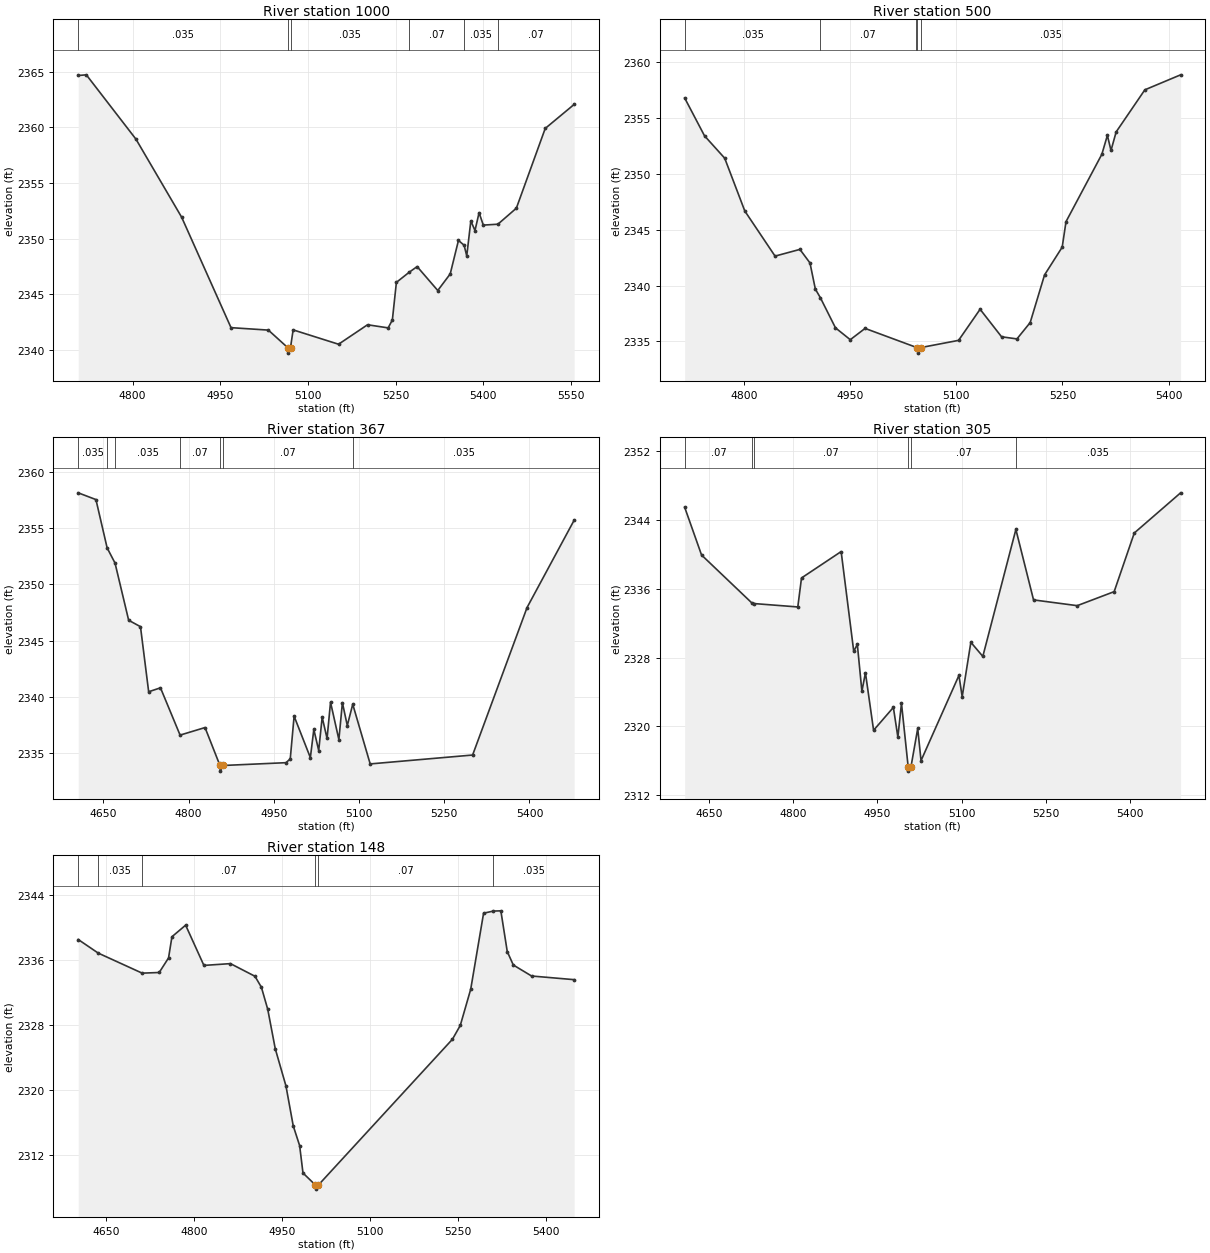
Type RM Length L Ch R = 1,1000,500,500,500
BEGIN DESCRIPTION:
Cottonwood Creek Trib041 2.0
END DESCRIPTION:
XS GIS Cut Line= 3
      1326655.03      6865988.03      1326855.76      6866201.47
      1327255.00      6866588.00
#Sta/Elev= 30
  4707.0 2364.66  4720.9 2364.72  4805.9 2358.93  4884.0 2351.92  4968.5 2341.99
  5032.4 2341.77  5065.4 2340.20  5065.7 2339.70  5070.3 2340.20  5074.8 2341.79
  5152.5 2340.50  5202.1 2342.25  5237.4 2341.97  5244.6 2342.68  5251.5 2346.06
  5273.6 2346.98  5287.0 2347.48  5322.3 2345.33  5343.6 2346.82  5357.7 2349.83
  5367.4 2349.40  5371.9 2348.44  5378.9 2351.59  5386.0 2350.72  5393.0 2352.33
  5400.2 2351.21  5425.2 2351.29  5456.8 2352.73  5506.2 2359.90  5555.7 2362.06
#Mann=6,-1,0
  4707.0   0.035       0  5065.4   0.035       0  5070.3   0.035       0
  5273.6    0.07       0  5367.4   0.035       0  5425.2    0.07       0
Bank Sta=5065.4,5070.3
Exp/Cntr=0.3,0.1

Type RM Length L Ch R = 1,500,133,133,133
BEGIN DESCRIPTION:
Cottonwood Creek Trib041 1.0
END DESCRIPTION:
XS GIS Cut Line= 3
      1326404.97      6866387.97      1326592.84      6866600.15
      1327004.98      6866538.00
#Sta/Elev= 30
  4716.6 2356.76  4744.6 2353.38  4773.1 2351.38  4801.5 2346.66  4844.2 2342.63
  4879.3 2343.23  4893.5 2342.02  4901.1 2339.68  4908.2 2338.91  4929.5 2336.22
  4950.4 2335.16  4971.3 2336.17  5043.0 2334.49  5045.3 2334.46  5045.7 2333.96
  5050.3 2334.46  5103.3 2335.10  5133.7 2337.88  5164.0 2335.42  5185.7 2335.23
  5204.4 2336.69  5224.7 2340.95  5249.6 2343.43  5255.0 2345.71  5305.6 2351.73
  5313.4 2353.42  5318.5 2352.07  5325.8 2353.73  5366.3 2357.49  5416.8 2358.83
#Mann=5,-1,0
  4716.6   0.035       0  4908.2    0.07       0  5043.0   0.035       0
  5045.3    0.07       0  5050.3   0.035       0
Bank Sta=5045.3,5050.3
Exp/Cntr=0.3,0.1

Type RM Length L Ch R = 1,367,62,62,62
BEGIN DESCRIPTION:
Cottonwood Creek Trib041 0.7
END DESCRIPTION:
XS GIS Cut Line= 4
      1326251.84      6866386.95      1326499.26      6866695.14
      1326577.39      6866751.57      1326920.16      6866584.52
#Sta/Elev= 30
  4605.8 2358.14  4637.0 2357.54  4656.7 2353.25  4670.6 2351.90  4694.6 2346.82
  4715.4 2346.25  4729.8 2340.47  4750.6 2340.82  4785.1 2336.62  4829.0 2337.29
  4855.3 2333.92  4855.7 2333.42  4860.3 2333.92  4971.4 2334.17  4979.0 2334.50
  4985.8 2338.30  5014.4 2334.62  5020.5 2337.12  5029.1 2335.25  5035.2 2338.21
  5043.8 2336.32  5049.9 2339.54  5064.6 2336.22  5070.8 2339.50  5079.4 2337.47
  5089.0 2339.36  5119.7 2334.06  5300.0 2334.85  5395.8 2347.95  5478.7 2355.71
#Mann=7,-1,0
  4605.8   0.035       0  4656.7    0.07       0  4670.6   0.035       0
  4785.1    0.07       0  4855.3    0.07       0  4860.3    0.07       0
  5089.0   0.035       0
Bank Sta=4855.3,4860.3
Exp/Cntr=0.3,0.1

Type RM Length L Ch R = 1,305,157,157,157
BEGIN DESCRIPTION:
Cottonwood Creek Trib041 0.6
END DESCRIPTION:
XS GIS Cut Line= 4
      1326210.66      6866430.42      1326462.64      6866747.72
      1326594.75      6866829.69      1326859.50      6866647.40
#Sta/Elev= 30
  4607.2 2345.49  4637.2 2339.94  4727.4 2334.32  4731.3 2334.29  4808.4 2333.90
  4815.0 2337.27  4885.5 2340.34  4907.9 2328.74  4914.3 2329.55  4922.4 2324.09
  4928.7 2326.25  4943.2 2319.56  4978.4 2322.22  4986.4 2318.76  4992.8 2322.70
  5004.7 2315.31  5005.1 2314.81  5009.7 2315.31  5021.7 2319.77  5027.6 2316.03
  5095.0 2325.94  5100.8 2323.46  5116.2 2329.79  5137.5 2328.15  5196.3 2342.91
  5227.7 2334.72  5305.4 2334.05  5371.1 2335.68  5406.9 2342.50  5489.3 2347.17
#Mann=6,-1,0
  4607.2    0.07       0  4727.4   0.035       0  4731.3    0.07       0
  5004.7    0.07       0  5009.7    0.07       0  5196.3   0.035       0
Bank Sta=5004.7,5009.7
Exp/Cntr=0.3,0.1

Type RM Length L Ch R = 1,148,0,0,0
BEGIN DESCRIPTION:
Cottonwood Creek Trib041 0.5
END DESCRIPTION:
XS GIS Cut Line= 4
      1326199.79      6866491.18      1326362.81      6866873.59
      1326445.01      6866901.31      1326774.94      6866811.44
#Sta/Elev= 30
  4603.0 2338.50  4637.1 2336.83  4711.9 2334.37  4740.9 2334.45  4756.8 2336.24
  4762.6 2338.84  4785.9 2340.26  4817.0 2335.32  4862.2 2335.54  4903.9 2333.99
  4914.9 2332.64  4925.7 2329.93  4938.5 2325.09  4956.7 2320.53  4969.1 2315.63
  4980.0 2313.20  4985.7 2309.84  5006.9 2308.36  5007.3 2307.86  5011.9 2308.36
  5240.2 2326.26  5253.5 2327.95  5271.3 2332.40  5293.2 2341.73  5309.9 2341.99
  5322.6 2342.02  5333.5 2337.02  5343.8 2335.37  5374.9 2334.02  5447.4 2333.57
#Mann=6,-1,0
  4603.0    0.07       0  4637.1   0.035       0  4711.9    0.07       0
  5006.9    0.07       0  5011.9    0.07       0  5309.9   0.035       0
Bank Sta=5006.9,5011.9
Exp/Cntr=0.3,0.1

Chan Stop Cuts=-1