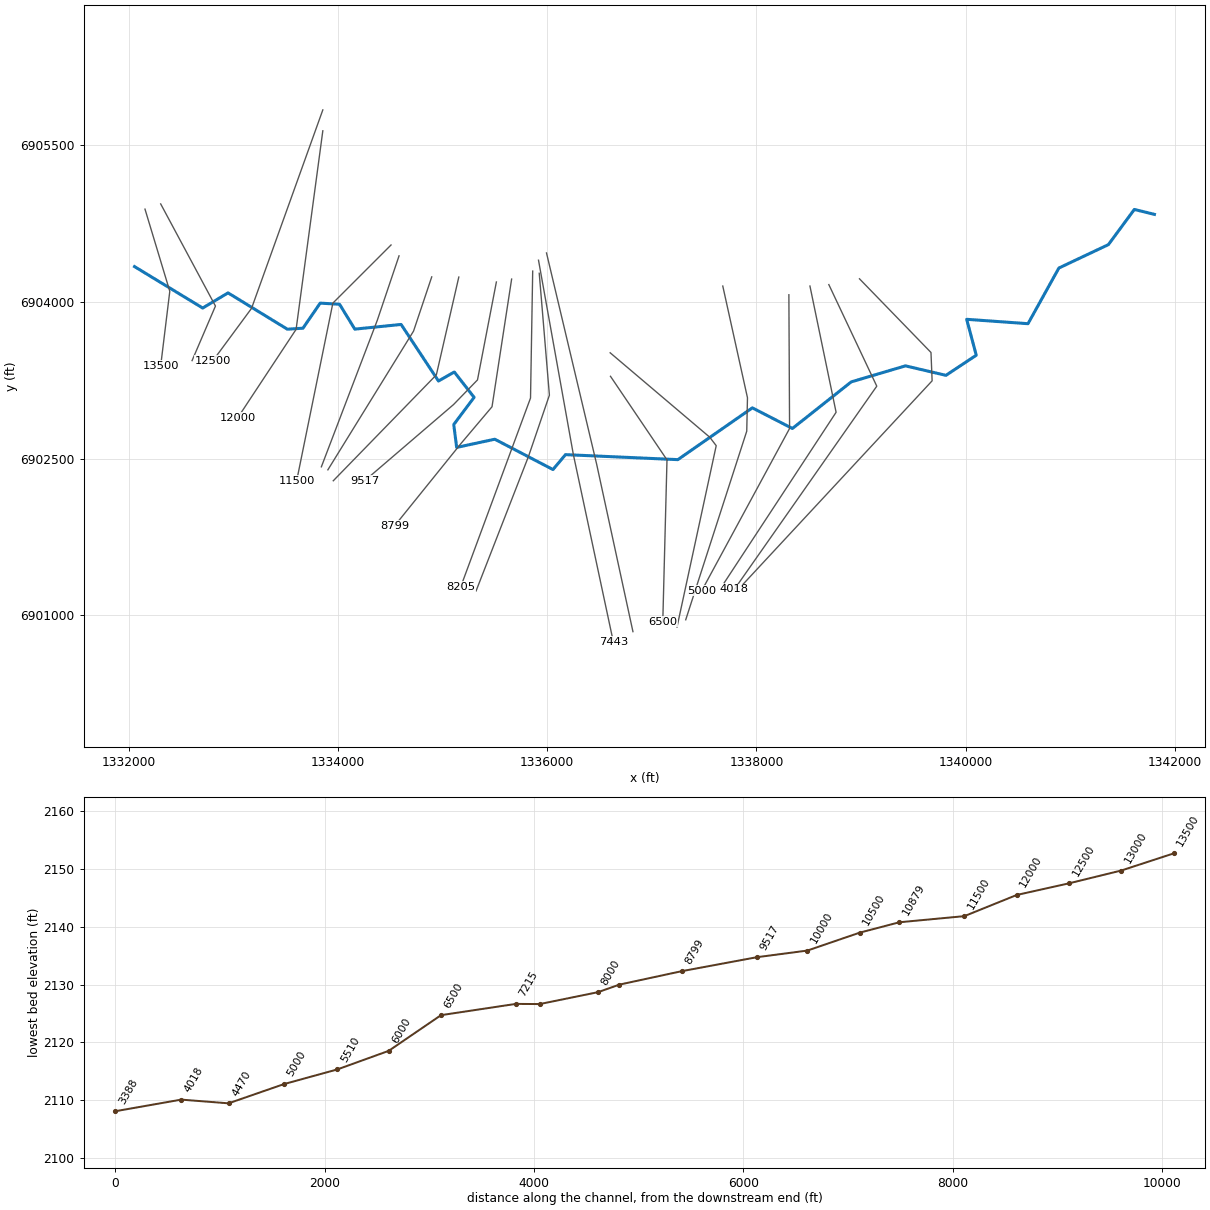
--- Cottonwood Creek Trib079.prj (project) ---

Proj Title=Cottonwood Creek Trib079 Base Level Engineering
Current Plan=p01
Default Exp/Contr=0.3,0.1
English Units
Geom File=g01
Flow File=f01
Plan File=p01
BEGIN DESCRIPTION:
Cottonwood Creek Trib079
END DESCRIPTION:

--- Cottonwood Creek Trib079.p01 (plan) ---

Plan Title=Multiple Run
Short Identifier=Multiple
Geom File=g01
Flow File=f01
Subcritical Flow
K Sum by GR= 0
Std Step Tol= 0.01
Critical Tol= 0.01
Num of Std Step Trials= 20
Max Error Tol= 0.3
Flow Tol Ratio= 0.001
Split Flow NTrial= 30
Split Flow Tol= 0.02
Split Flow Ratio= 0.02
Log Output Level= 0
Friction Slope Method= 1
Unsteady Friction Slope Method= 2
Unsteady Bridges Friction Slope Method= 1
Parabolic Critical Depth
Global Vel Dist=  1 , 1 , 1
Global Log Level= 0
CheckData=True
Encroach Param= -1, 0, 0, 0
BEGIN DESCRIPTION:
Multiple Run
END DESCRIPTION:

--- Cottonwood Creek Trib079.f01 (steady flow) ---

Flow Title=Multiple
Number of Profiles=7
Profile Names=10-year,25-year,50-year,1pct_min,100-year,1pct_plu,500-year
River Rch & RM= Cottonwood Creek,Reach-1,13500
     380     554     703     444     886    1768    1426
River Rch & RM= Cottonwood Creek,Reach-1,11500
     426     619     786     495     988    1970    1582
Boundary for River Rch & Prof#=Cottonwood Creek,Reach-1,1
Up Type=0
Dn Type=3
Dn Slope=0.005
Boundary for River Rch & Prof#=Cottonwood Creek,Reach-1,2
Up Type=0
Dn Type=3
Dn Slope=0.005
Boundary for River Rch & Prof#=Cottonwood Creek,Reach-1,3
Up Type=0
Dn Type=3
Dn Slope=0.005
Boundary for River Rch & Prof#=Cottonwood Creek,Reach-1,4
Up Type=0
Dn Type=3
Dn Slope=0.005
Boundary for River Rch & Prof#=Cottonwood Creek,Reach-1,5
Up Type=0
Dn Type=3
Dn Slope=0.005
Boundary for River Rch & Prof#=Cottonwood Creek,Reach-1,6
Up Type=0
Dn Type=3
Dn Slope=0.005
Boundary for River Rch & Prof#=Cottonwood Creek,Reach-1,7
Up Type=0
Dn Type=3
Dn Slope=0.005

--- Cottonwood Creek Trib079.g01 (geometry) ---

Geom Title=Existing Conditions

River Reach=Cottonwood Creek,Reach-1
Reach XY= 30
      1332055.00      6904338.00      1332706.50      6903941.47
      1332948.92      6904086.44      1333515.44      6903739.03
      1333665.12      6903748.34      1333829.79      6903988.33
      1334014.83      6903977.53      1334160.85      6903739.49
      1334603.44      6903784.24      1334960.62      6903242.74
      1335111.93      6903329.11      1335301.26      6903086.44
      1335106.62      6902826.17      1335134.42      6902607.21
      1335499.06      6902685.74      1336055.31      6902395.23
      1336174.89      6902538.10      1337249.06      6902490.26
      1337961.06      6902985.86      1338344.36      6902788.55
      1338906.46      6903234.46      1339425.01      6903387.94
      1339811.73      6903297.15      1340101.88      6903489.62
      1340010.16      6903833.41      1340596.52      6903791.51
      1340891.78      6904324.38      1341365.10      6904548.40
      1341612.97      6904885.08      1341805.00      6904838.00

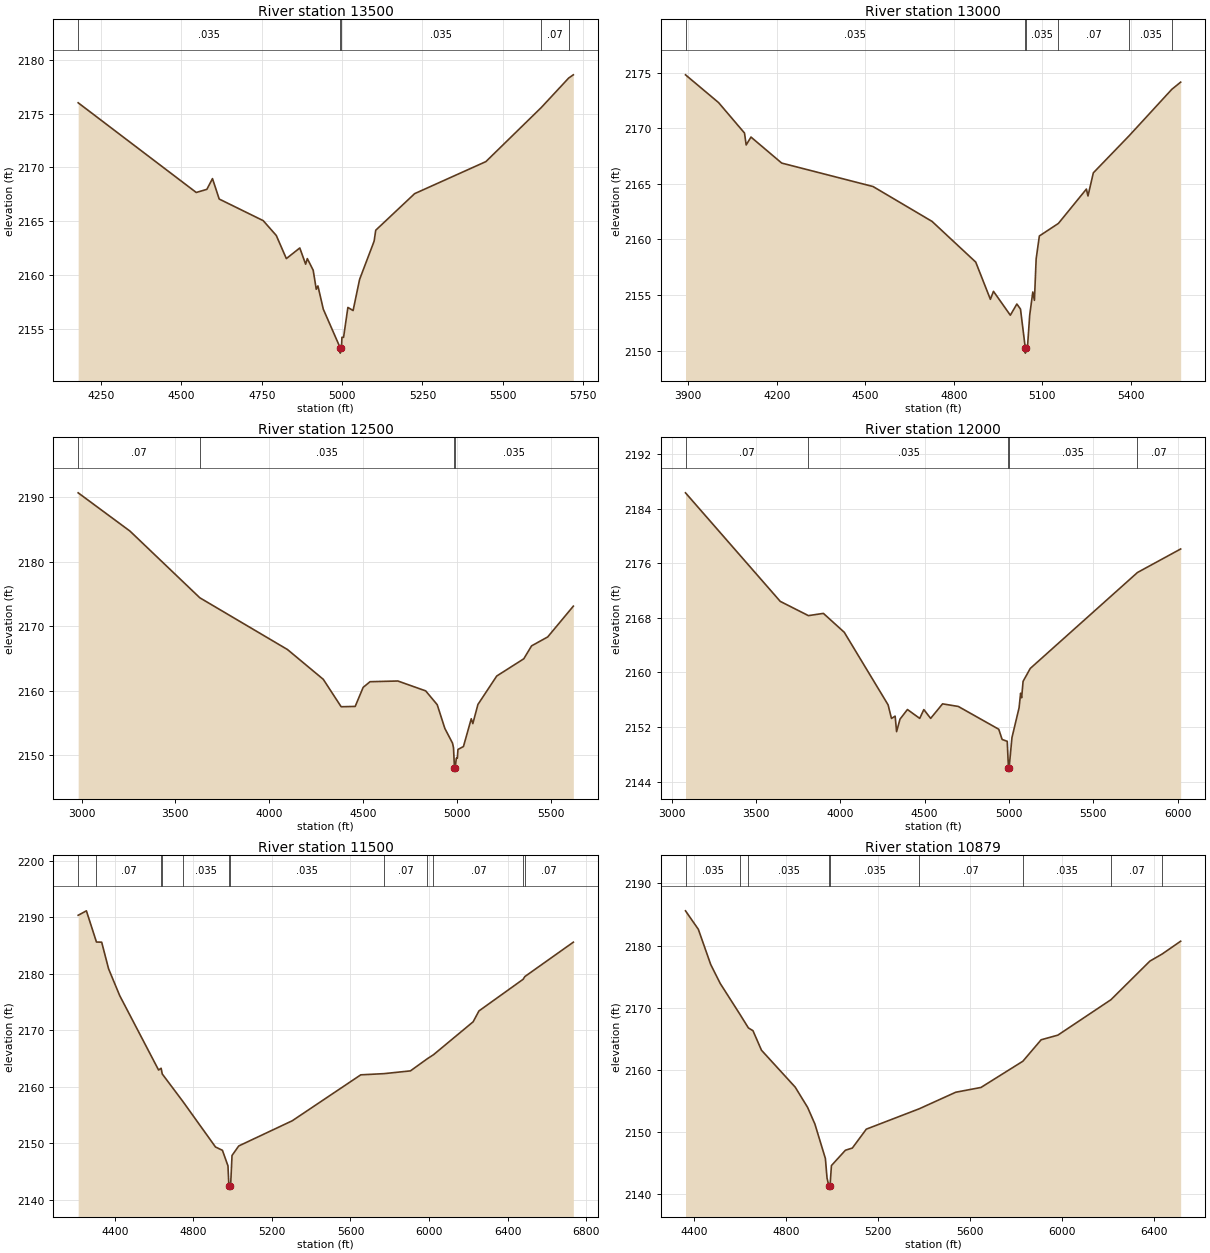
Type RM Length L Ch R = 1,13500,500,500,500
BEGIN DESCRIPTION:
Cottonwood Creek Trib079 27.0
END DESCRIPTION:
XS GIS Cut Line= 3
      1332154.99      6904888.02      1332392.04      6904101.88
      1332305.00      6903387.97
#Sta/Elev= 30
  4178.9 2176.01  4546.2 2167.67  4579.2 2167.96  4596.7 2168.96  4617.6 2167.06
  4754.5 2165.05  4795.2 2163.67  4826.5 2161.52  4868.3 2162.51  4886.5 2161.00
  4891.7 2161.52  4910.0 2160.44  4919.5 2158.67  4924.7 2158.98  4941.4 2156.82
  4993.9 2153.23  4994.1 2152.73  4997.9 2153.23  4999.4 2154.20  5004.5 2154.20
  5017.9 2156.98  5034.1 2156.69  5054.3 2159.58  5099.5 2163.14  5104.6 2164.16
  5225.5 2167.56  5447.2 2170.54  5619.2 2175.56  5704.7 2178.31  5719.2 2178.61
#Mann=5,-1,0
  4178.9   0.035       0  4993.9   0.035       0  4997.9   0.035       0
  5619.2    0.07       0  5704.7   0.035       0
Bank Sta=4993.9,4997.9
Exp/Cntr=0.3,0.1

Type RM Length L Ch R = 1,13000,500,500,500
BEGIN DESCRIPTION:
Cottonwood Creek Trib079 26.0
END DESCRIPTION:
XS GIS Cut Line= 3
      1332305.01      6904937.99      1332828.52      6903960.34
      1332604.98      6903437.96
#Sta/Elev= 30
  3891.0 2174.81  4003.1 2172.31  4090.9 2169.57  4096.5 2168.50  4112.8 2169.21
  4216.8 2166.87  4526.2 2164.76  4726.2 2161.62  4874.1 2157.96  4923.7 2154.61
  4934.2 2155.33  4991.3 2153.18  5013.4 2154.19  5025.7 2153.73  5041.8 2150.27
  5042.1 2149.77  5045.8 2150.27  5049.3 2150.29  5056.9 2153.19  5067.4 2155.27
  5072.9 2154.52  5078.7 2158.24  5089.6 2160.31  5154.1 2161.44  5248.9 2164.53
  5254.3 2163.91  5272.4 2165.99  5394.1 2169.34  5538.4 2173.51  5568.2 2174.15
#Mann=6,-1,0
  3891.0   0.035       0  5041.8   0.035       0  5045.8   0.035       0
  5154.1    0.07       0  5394.1   0.035       0  5538.4    0.07       0
Bank Sta=5041.8,5045.8
Exp/Cntr=0.3,0.1

Type RM Length L Ch R = 1,12500,500,500,500
BEGIN DESCRIPTION:
Cottonwood Creek Trib079 25.0
END DESCRIPTION:
XS GIS Cut Line= 3
      1333855.00      6905837.99      1333173.58      6903938.30
      1332805.01      6903438.01
#Sta/Elev= 30
  2981.8 2190.69  3257.9 2184.76  3630.3 2174.42  4097.5 2166.40  4288.5 2161.78
  4383.7 2157.53  4458.5 2157.58  4501.0 2160.53  4537.5 2161.41  4685.9 2161.52
  4834.3 2159.99  4895.8 2157.85  4936.6 2154.16  4977.4 2151.89  4982.7 2151.17
  4987.7 2148.05  4987.9 2147.55  4991.7 2148.05  4997.5 2149.55  5003.0 2149.55
  5006.3 2150.91  5035.6 2151.36  5077.3 2155.67  5085.7 2154.92  5112.8 2157.88
  5213.0 2162.29  5357.2 2164.96  5398.9 2166.97  5484.8 2168.35  5621.4 2173.12
#Mann=4,-1,0
  2981.8    0.07       0  3630.3   0.035       0  4987.7   0.035       0
  4991.7   0.035       0
Bank Sta=4987.7,4991.7
Exp/Cntr=0.3,0.1

Type RM Length L Ch R = 1,12000,500,500,500
BEGIN DESCRIPTION:
Cottonwood Creek Trib079 24.0
END DESCRIPTION:
XS GIS Cut Line= 3
      1333855.00      6905638.03      1333599.61      6903737.51
      1333039.81      6902888.20
#Sta/Elev= 30
  3082.4 2186.32  3644.0 2170.41  3811.0 2168.32  3899.7 2168.65  4023.4 2165.88
  4283.1 2155.25  4303.3 2153.25  4324.9 2153.59  4333.6 2151.32  4353.8 2153.15
  4397.8 2154.56  4470.6 2153.26  4495.0 2154.55  4535.4 2153.26  4606.0 2155.39
  4699.3 2155.01  4939.0 2151.67  4959.1 2150.17  4989.4 2149.90  4996.5 2146.03
  4996.8 2145.53  5000.5 2146.03  5017.4 2150.45  5059.5 2154.81  5068.6 2156.95
  5074.6 2156.28  5083.3 2158.69  5125.8 2160.58  5761.1 2174.64  6017.2 2178.09
#Mann=5,-1,0
  3082.4    0.07       0  3811.0   0.035       0  4996.5   0.035       0
  5000.5   0.035       0  5761.1    0.07       0
Bank Sta=4996.5,5000.5
Exp/Cntr=0.3,0.1

Type RM Length L Ch R = 1,11500,621,621,621
BEGIN DESCRIPTION:
Cottonwood Creek Trib079 23.0
END DESCRIPTION:
XS GIS Cut Line= 3
      1334507.20      6904545.01      1333950.95      6903988.42
      1333604.99      6902287.95
#Sta/Elev= 30
  4213.1 2190.34  4255.0 2191.13  4306.2 2185.61  4332.8 2185.58  4368.1 2180.86
  4424.7 2176.12  4622.7 2162.95  4635.6 2163.27  4641.5 2162.25  4746.6 2157.38
  4912.6 2149.33  4947.9 2148.74  4976.2 2145.98  4980.8 2142.37  4981.2 2141.87
  4985.7 2142.37  4990.4 2143.08  4996.8 2147.83  5031.0 2149.51  5303.6 2153.97
  5652.6 2162.10  5770.6 2162.31  5905.6 2162.80  5990.8 2164.93  6023.0 2165.66
  6225.0 2171.49  6254.6 2173.41  6479.9 2179.02  6488.2 2179.49  6735.3 2185.58
#Mann=12,-1,0
  4213.1   0.035       0  4306.2    0.07       0  4635.6   0.035       0
  4641.5    0.07       0  4746.6   0.035       0  4980.8   0.035       0
  4985.7   0.035       0  5770.6    0.07       0  5990.8   0.035       0
  6023.0    0.07       0  6479.9   0.035       0  6488.2    0.07       0
Bank Sta=4980.8,4985.7
Exp/Cntr=0.3,0.1

Type RM Length L Ch R = 1,10879,379,379,379
BEGIN DESCRIPTION:
Cottonwood Creek Trib079 22.0
END DESCRIPTION:
XS GIS Cut Line= 3
      1334583.61      6904440.87      1334375.27      6903822.81
      1333841.11      6902421.50
#Sta/Elev= 30
  4364.2 2185.59  4420.0 2182.62  4473.7 2176.96  4515.0 2173.91  4599.2 2169.03
  4637.7 2166.74  4657.3 2166.31  4694.4 2163.16  4841.0 2157.22  4894.9 2153.96
  4926.5 2151.29  4972.2 2145.73  4979.3 2142.59  4987.4 2141.31  4987.7 2140.81
  4992.3 2141.31  4998.4 2144.60  5059.2 2147.07  5089.3 2147.42  5150.0 2150.46
  5379.5 2153.73  5538.6 2156.40  5648.3 2157.17  5830.4 2161.39  5909.8 2164.84
  5982.6 2165.59  6213.2 2171.29  6382.4 2177.50  6435.2 2178.63  6516.1 2180.70
#Mann=9,-1,0
  4364.2   0.035       0  4599.2    0.07       0  4637.7   0.035       0
  4987.4   0.035       0  4992.3   0.035       0  5379.5    0.07       0
  5830.4   0.035       0  6213.2    0.07       0  6435.2   0.035       0
Bank Sta=4987.4,4992.3
Exp/Cntr=0.3,0.1

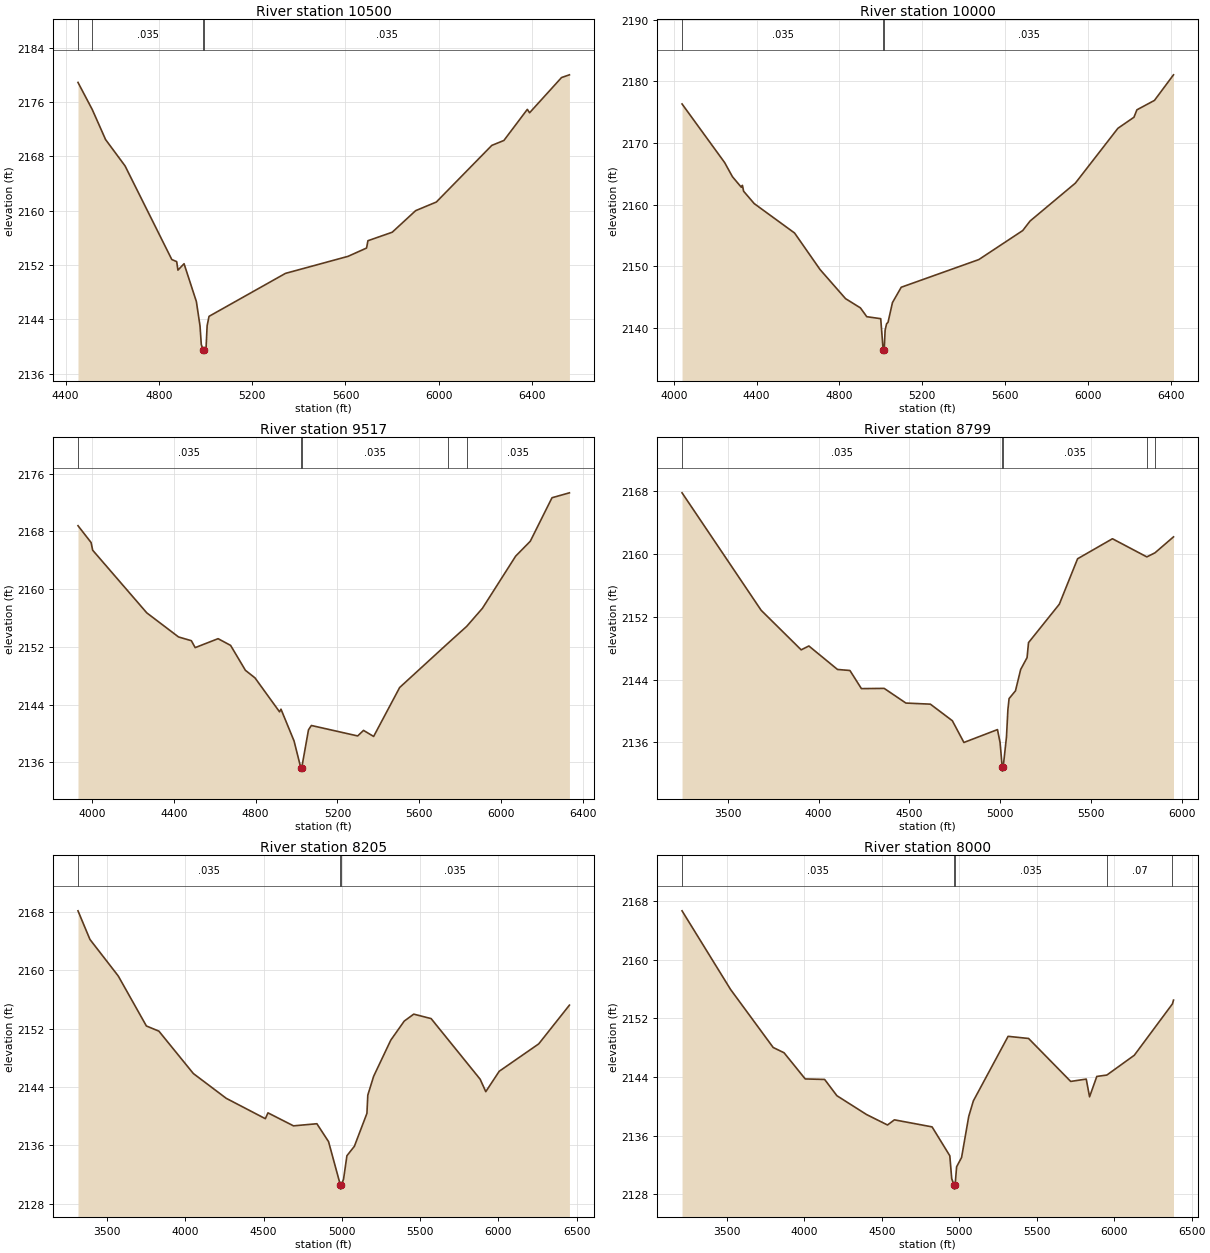
Type RM Length L Ch R = 1,10500,500,500,500
BEGIN DESCRIPTION:
Cottonwood Creek Trib079 21.0
END DESCRIPTION:
XS GIS Cut Line= 3
      1334896.09      6904239.45      1334722.36      6903720.77
      1333903.28      6902392.63
#Sta/Elev= 30
  4453.0 2178.89  4514.3 2174.89  4571.2 2170.48  4654.9 2166.59  4855.3 2152.80
  4876.3 2152.49  4881.6 2151.24  4907.9 2152.18  4960.7 2146.60  4976.3 2143.02
  4981.8 2140.27  4989.9 2139.51  4990.3 2139.01  4994.8 2139.51  5002.2 2139.75
  5006.8 2143.05  5015.0 2144.43  5342.8 2150.76  5611.2 2153.27  5690.4 2154.49
  5696.4 2155.57  5800.5 2156.82  5901.0 2160.00  5989.7 2161.27  6227.4 2169.61
  6279.4 2170.34  6379.9 2174.92  6389.5 2174.42  6526.6 2179.61  6560.4 2180.01
#Mann=4,-1,0
  4453.0    0.07       0  4514.3   0.035       0  4989.9   0.035       0
  4994.8   0.035       0
Bank Sta=4989.9,4994.8
Exp/Cntr=0.3,0.1

Type RM Length L Ch R = 1,10000,483,483,483
BEGIN DESCRIPTION:
Cottonwood Creek Trib079 20.0
END DESCRIPTION:
XS GIS Cut Line= 3
      1335155.00      6904237.98      1334940.43      6903301.86
      1333955.03      6902288.03
#Sta/Elev= 30
  4039.6 2176.34  4245.4 2166.83  4283.2 2164.53  4326.1 2162.82  4331.2 2163.14
  4337.1 2162.18  4388.4 2160.17  4583.3 2155.40  4706.4 2149.47  4829.5 2144.75
  4901.4 2143.25  4932.1 2141.82  4999.4 2141.50  5011.2 2136.41  5011.6 2135.91
  5016.2 2136.41  5020.6 2139.63  5027.8 2140.67  5034.8 2140.92  5056.1 2144.11
  5098.5 2146.60  5473.3 2151.09  5685.5 2155.80  5720.8 2157.34  5939.9 2163.50
  6145.2 2172.39  6222.9 2174.19  6237.0 2175.39  6321.9 2176.92  6413.8 2181.07
#Mann=3,-1,0
  4039.6   0.035       0  5011.2   0.035       0  5016.2   0.035       0
Bank Sta=5011.2,5016.2
Exp/Cntr=0.3,0.1

Type RM Length L Ch R = 1,9517,718,718,718
BEGIN DESCRIPTION:
Cottonwood Creek Trib079 19.0
END DESCRIPTION:
XS GIS Cut Line= 4
      1335514.15      6904190.83      1335333.60      6903253.36
      1335104.44      6903017.25      1334254.97      6902287.97
#Sta/Elev= 30
  3931.5 2168.80  3995.5 2166.47  4003.4 2165.40  4268.0 2156.71  4423.2 2153.37
  4485.8 2152.85  4504.7 2151.89  4616.7 2153.13  4677.8 2152.20  4750.4 2148.74
  4797.2 2147.69  4917.3 2142.98  4924.3 2143.35  4988.1 2138.95  5020.8 2135.26
  5021.2 2134.76  5025.9 2135.26  5058.8 2140.49  5072.9 2141.09  5299.3 2139.64
  5327.9 2140.41  5377.3 2139.57  5504.6 2146.36  5743.0 2152.55  5832.5 2154.84
  5909.5 2157.35  6071.9 2164.58  6143.3 2166.64  6249.7 2172.68  6334.8 2173.36
#Mann=5,-1,0
  3931.5   0.035       0  5020.8   0.035       0  5025.9   0.035       0
  5743.0    0.07       0  5832.5   0.035       0
Bank Sta=5020.8,5025.9
Exp/Cntr=0.3,0.1

Type RM Length L Ch R = 1,8799,594,594,594
BEGIN DESCRIPTION:
Cottonwood Creek Trib079 18.0
END DESCRIPTION:
XS GIS Cut Line= 4
      1335659.99      6904218.62      1335472.49      6902996.42
      1335173.88      6902642.25      1334541.93      6901857.53
#Sta/Elev= 30
  3247.7 2167.79  3683.4 2152.83  3904.0 2147.79  3946.4 2148.28  4104.1 2145.29
  4172.5 2145.16  4235.8 2142.85  4361.2 2142.88  4480.9 2141.01  4615.8 2140.87
  4736.7 2138.76  4800.5 2135.99  4985.3 2137.63  4999.7 2135.99  5011.5 2132.84
  5011.9 2132.34  5016.7 2132.84  5034.9 2136.67  5042.8 2140.17  5049.3 2141.58
  5084.5 2142.57  5113.2 2145.29  5148.4 2146.80  5156.4 2148.71  5326.0 2153.60
  5426.7 2159.39  5618.7 2161.94  5808.1 2159.63  5853.2 2160.15  5955.0 2162.18
#Mann=5,-1,0
  3247.7   0.035       0  5011.5   0.035       0  5016.7   0.035       0
  5808.1    0.07       0  5853.2   0.035       0
Bank Sta=5011.5,5016.7
Exp/Cntr=0.3,0.1

Type RM Length L Ch R = 1,8205,205,205,205
BEGIN DESCRIPTION:
Cottonwood Creek Trib079 17.0
END DESCRIPTION:
XS GIS Cut Line= 3
      1335861.38      6904295.05      1335840.55      6903079.75
      1335173.87      6901274.18
#Sta/Elev= 30
  3313.9 2168.11  3390.2 2164.20  3571.0 2159.20  3751.0 2152.35  3831.0 2151.64
  4051.1 2145.84  4261.1 2142.45  4511.1 2139.66  4527.8 2140.46  4691.1 2138.68
  4840.4 2138.97  4915.0 2136.52  4991.3 2130.52  4991.7 2130.02  4996.5 2130.52
  5010.9 2131.40  5032.3 2134.59  5079.9 2135.88  5160.2 2140.39  5165.8 2142.88
  5202.8 2145.45  5312.6 2150.41  5398.6 2153.02  5459.4 2153.97  5570.4 2153.36
  5883.8 2145.06  5919.6 2143.36  6005.5 2146.15  6258.0 2149.90  6454.1 2155.20
#Mann=3,-1,0
  3313.9   0.035       0  4991.3   0.035       0  4996.5   0.035       0
Bank Sta=4991.3,4996.5
Exp/Cntr=0.3,0.1

Type RM Length L Ch R = 1,8000,557,557,557
BEGIN DESCRIPTION:
Cottonwood Creek Trib079 16.0
END DESCRIPTION:
XS GIS Cut Line= 4
      1335923.88      6904274.24      1336021.10      6903107.53
      1335821.48      6902521.76      1335319.94      6901233.12
#Sta/Elev= 30
  3210.4 2166.67  3523.8 2155.94  3798.7 2148.03  3868.9 2147.31  4005.5 2143.74
  4130.9 2143.67  4210.1 2141.45  4401.8 2138.88  4536.7 2137.46  4581.4 2138.16
  4824.4 2137.20  4938.9 2133.26  4951.2 2130.13  4967.7 2129.21  4968.1 2128.71
  4972.9 2129.21  4982.8 2131.76  5014.8 2133.02  5061.1 2138.63  5091.0 2140.75
  5315.2 2149.55  5447.3 2149.26  5719.3 2143.40  5819.6 2143.72  5841.0 2141.30
  5887.8 2144.08  5952.6 2144.27  6129.9 2146.97  6376.1 2153.98  6382.8 2154.49
#Mann=5,-1,0
  3210.4   0.035       0  4967.7   0.035       0  4972.9   0.035       0
  5952.6    0.07       0  6376.1   0.035       0
Bank Sta=4967.7,4972.9
Exp/Cntr=0.3,0.1

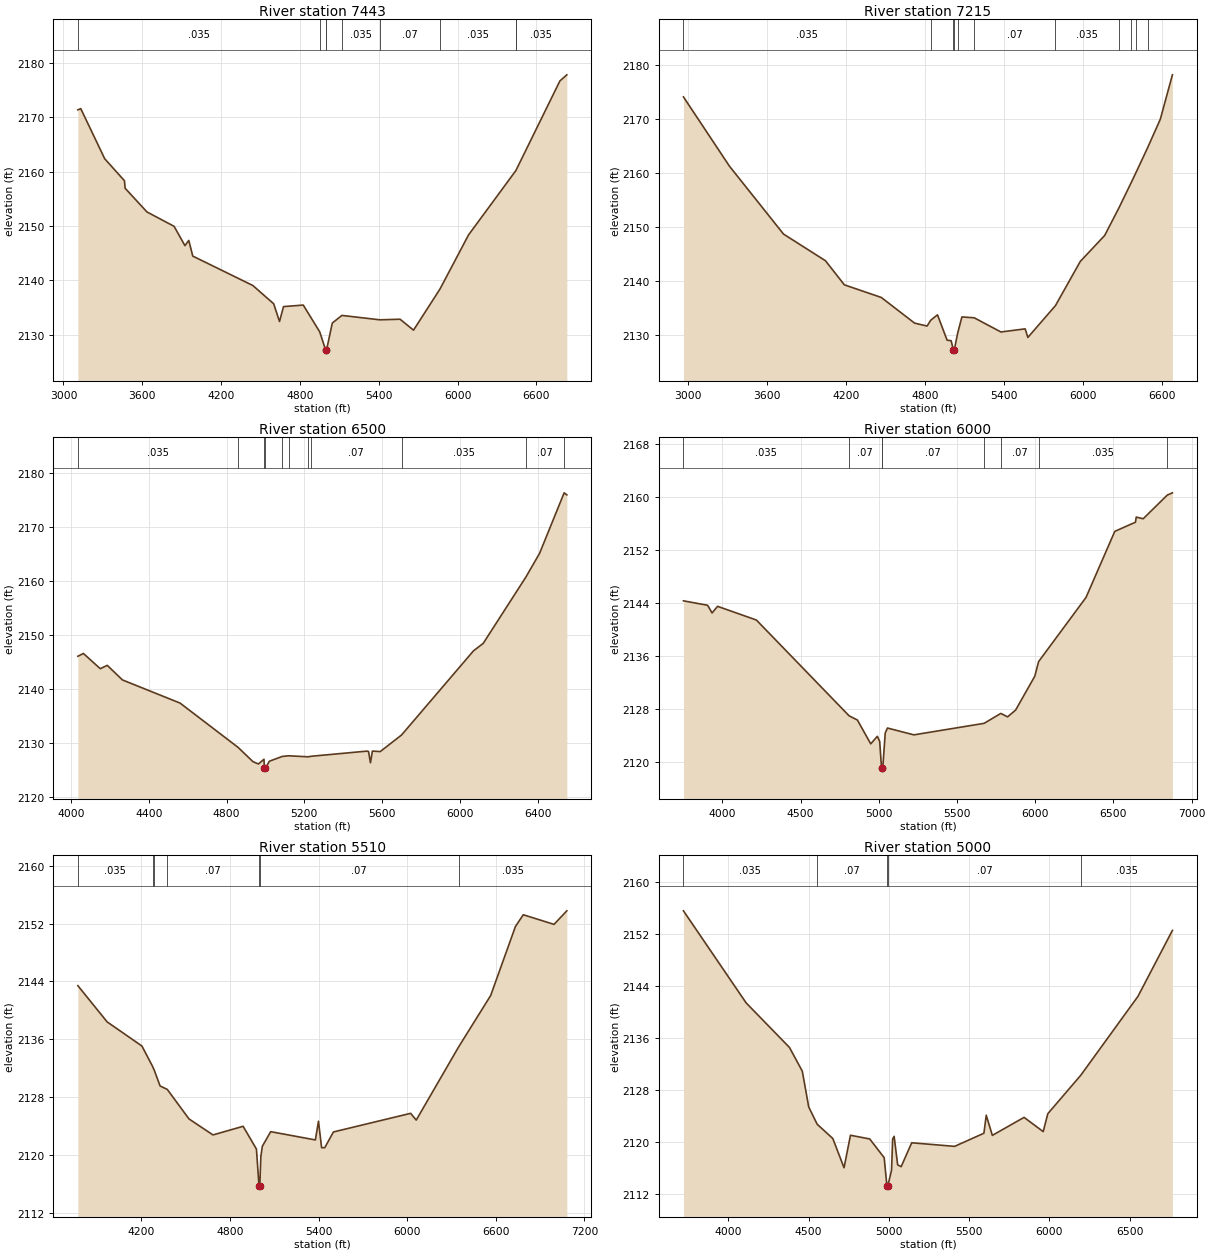
Type RM Length L Ch R = 1,7443,228,228,228
BEGIN DESCRIPTION:
Cottonwood Creek Trib079 15.0
END DESCRIPTION:
XS GIS Cut Line= 3
      1335916.94      6904399.16      1336250.27      6902538.08
      1336632.21      6900746.43
#Sta/Elev= 30
  3109.7 2171.35  3131.7 2171.58  3314.1 2162.37  3464.4 2158.33  3469.5 2156.95
  3635.8 2152.59  3842.3 2149.95  3924.9 2146.40  3954.1 2147.36  3984.6 2144.48
  4441.7 2139.08  4600.5 2135.72  4644.9 2132.46  4675.4 2135.20  4825.7 2135.48
  4951.1 2130.56  4997.0 2127.15  4997.4 2126.65  5002.3 2127.15  5046.8 2132.18
  5119.9 2133.58  5409.1 2132.77  5562.8 2132.88  5665.1 2130.87  5866.9 2138.44
  6084.3 2148.38  6442.3 2160.13  6444.8 2160.22  6779.6 2176.67  6832.3 2177.79
#Mann=9,-1,0
  3109.7   0.035       0  4951.1    0.07       0  4997.0    0.07       0
  5002.3    0.07       0  5119.9   0.035       0  5409.1    0.07       0
  5866.9   0.035       0  6442.3    0.07       0  6444.8   0.035       0
Bank Sta=4997,5002.3
Exp/Cntr=0.3,0.1

Type RM Length L Ch R = 1,7215,715,715,715
BEGIN DESCRIPTION:
Cottonwood Creek Trib079 14.0
END DESCRIPTION:
XS GIS Cut Line= 3
      1335993.31      6904468.68      1336472.49      6902447.81
      1336819.71      6900843.66
#Sta/Elev= 30
  2964.8 2174.18  3314.9 2161.33  3725.7 2148.75  4044.6 2143.81  4188.5 2139.34
  4469.3 2137.00  4722.6 2132.24  4817.4 2131.70  4845.0 2132.77  4896.7 2133.78
  4969.6 2129.08  5000.4 2128.98  5018.3 2127.18  5018.7 2126.68  5023.7 2127.18
  5050.4 2130.42  5082.4 2133.39  5175.6 2133.23  5379.1 2130.60  5563.3 2131.18
  5583.8 2129.59  5793.4 2135.48  5982.8 2143.69  6168.3 2148.50  6277.0 2153.64
  6368.8 2158.25  6403.7 2160.03  6494.8 2164.78  6590.7 2170.02  6683.0 2178.27
#Mann=11,-1,0
  2964.8   0.035       0  4845.0    0.07       0  5018.3    0.07       0
  5023.7    0.07       0  5050.4   0.035       0  5175.6    0.07       0
  5793.4   0.035       0  6277.0    0.07       0  6368.8   0.035       0
  6403.7    0.07       0  6494.8   0.035       0
Bank Sta=5018.3,5023.7
Exp/Cntr=0.3,0.1

Type RM Length L Ch R = 1,6500,500,500,500
BEGIN DESCRIPTION:
Cottonwood Creek Trib079 13.0
END DESCRIPTION:
XS GIS Cut Line= 3
      1336605.02      6903287.97      1337145.17      6902487.94
      1337105.00      6900937.96
#Sta/Elev= 30
  4034.7 2146.00  4063.1 2146.52  4150.1 2143.70  4186.0 2144.32  4264.0 2141.62
  4560.7 2137.33  4859.3 2129.12  4935.4 2126.49  4963.7 2126.05  4992.3 2126.93
  4994.2 2125.23  4994.6 2124.73  4999.7 2125.23  5019.9 2126.56  5086.1 2127.45
  5118.8 2127.57  5220.6 2127.38  5232.1 2127.47  5520.1 2128.43  5530.1 2128.38
  5540.1 2126.28  5550.1 2128.44  5590.3 2128.35  5700.1 2131.42  6070.3 2147.01
  6120.3 2148.39  6339.8 2160.67  6410.4 2165.07  6536.7 2176.27  6550.5 2175.89
#Mann=11,-1,0
  4034.7   0.035       0  4859.3    0.07       0  4994.2    0.07       0
  4999.7    0.07       0  5086.1   0.035       0  5118.8    0.07       0
  5220.6   0.035       0  5232.1    0.07       0  5700.1   0.035       0
  6339.8    0.07       0  6536.7   0.035       0
Bank Sta=4994.2,4999.7
Exp/Cntr=0.3,0.1

Type RM Length L Ch R = 1,6000,490,490,490
BEGIN DESCRIPTION:
Cottonwood Creek Trib079 12.0
END DESCRIPTION:
XS GIS Cut Line= 4
      1336602.12      6903512.91      1337554.56      6902704.28
      1337615.78      6902623.84      1337241.01      6900887.92
#Sta/Elev= 30
  3750.6 2144.28  3905.1 2143.61  3933.7 2142.45  3968.8 2143.45  4217.0 2141.38
  4809.7 2126.91  4862.9 2126.27  4948.1 2122.67  4990.3 2123.81  5005.3 2123.04
  5017.1 2119.05  5017.5 2118.55  5022.6 2119.05  5026.1 2119.37  5040.7 2124.30
  5055.2 2125.06  5224.0 2124.03  5673.0 2125.77  5779.8 2127.27  5823.2 2126.75
  5874.3 2127.77  5997.1 2132.89  6021.5 2135.10  6324.5 2144.79  6508.6 2154.78
  6640.7 2156.16  6645.8 2156.94  6690.0 2156.68  6843.8 2160.25  6877.0 2160.60
#Mann=8,-1,0
  3750.6   0.035       0  4809.7    0.07       0  5017.1    0.07       0
  5022.6    0.07       0  5673.0   0.035       0  5779.8    0.07       0
  6021.5   0.035       0  6843.8    0.07       0
Bank Sta=5017.1,5022.6
Exp/Cntr=0.3,0.1

Type RM Length L Ch R = 1,5510,510,510,510
BEGIN DESCRIPTION:
Cottonwood Creek Trib079 11.0
END DESCRIPTION:
XS GIS Cut Line= 4
      1337678.51      6904151.79      1337914.62      6903082.35
      1337907.68      6902762.91      1337324.33      6900957.31
#Sta/Elev= 30
  3769.1 2143.42  3967.6 2138.42  4203.1 2135.09  4274.9 2132.29  4287.0 2131.73
  4326.0 2129.58  4374.9 2129.10  4521.9 2125.03  4684.4 2122.82  4888.6 2124.01
  4978.7 2120.87  4995.9 2115.84  4996.3 2115.34  5001.5 2115.84  5008.7 2119.84
  5018.7 2121.25  5075.3 2123.27  5378.1 2122.13  5398.9 2124.71  5420.2 2121.06
  5441.5 2121.06  5500.3 2123.23  6023.2 2125.80  6061.2 2124.87  6348.1 2134.96
  6565.6 2142.07  6733.0 2151.58  6786.3 2153.21  6994.5 2151.88  7081.3 2153.75
#Mann=7,-1,0
  3769.1   0.035       0  4274.9    0.07       0  4287.0   0.035       0
  4374.9    0.07       0  4995.9    0.07       0  5001.5    0.07       0
  6348.1   0.035       0
Bank Sta=4995.9,5001.5
Exp/Cntr=0.3,0.1

Type RM Length L Ch R = 1,5000,530,530,530
BEGIN DESCRIPTION:
Cottonwood Creek Trib079 10.0
END DESCRIPTION:
XS GIS Cut Line= 3
      1338310.45      6904068.43      1338317.10      6902788.35
      1337477.12      6901235.13
#Sta/Elev= 30
  3719.9 2155.62  4110.3 2141.46  4380.3 2134.60  4460.3 2130.95  4500.3 2125.44
  4552.7 2122.79  4650.3 2120.59  4720.3 2116.09  4760.3 2121.09  4880.3 2120.52
  4970.3 2117.64  4987.5 2113.30  4988.0 2112.80  4993.1 2113.30  5016.2 2115.72
  5023.1 2120.51  5032.4 2120.92  5054.3 2116.53  5076.1 2116.26  5141.8 2119.93
  5409.2 2119.38  5591.6 2121.40  5606.1 2124.17  5644.1 2121.07  5841.7 2123.84
  5961.0 2121.65  5989.5 2124.40  6195.3 2130.33  6550.9 2142.45  6765.8 2152.61
#Mann=5,-1,0
  3719.9   0.035       0  4552.7    0.07       0  4987.5    0.07       0
  4993.1    0.07       0  6195.3   0.035       0
Bank Sta=4987.5,4993.1
Exp/Cntr=0.3,0.1

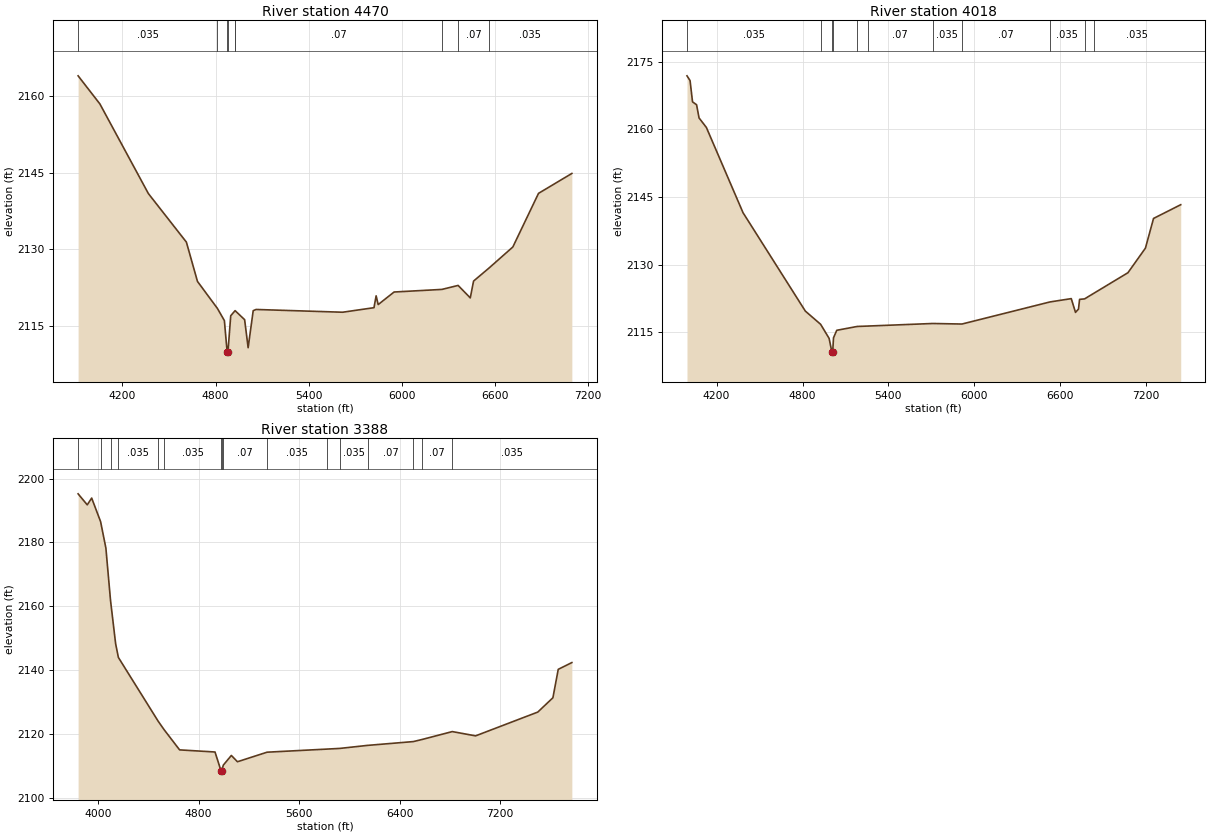
Type RM Length L Ch R = 1,4470,452,452,452
BEGIN DESCRIPTION:
Cottonwood Creek Trib079 9.0
END DESCRIPTION:
XS GIS Cut Line= 3
      1338511.83      6904151.85      1338761.84      6902943.47
      1337692.90      6901312.29
#Sta/Elev= 30
  3913.8 2164.00  4054.2 2158.50  4367.0 2140.93  4612.1 2131.42  4683.6 2123.72
  4812.4 2118.42  4857.2 2116.04  4874.8 2109.97  4875.3 2109.47  4880.4 2109.97
  4898.1 2116.99  4926.2 2117.99  4926.3 2117.99  4987.7 2116.22  5010.4 2110.73
  5043.0 2117.98  5061.4 2118.22  5620.0 2117.68  5822.0 2118.57  5835.8 2120.89
  5849.1 2119.18  5951.6 2121.64  6260.0 2122.15  6364.6 2122.93  6443.0 2120.49
  6464.1 2123.78  6561.6 2126.28  6717.4 2130.46  6883.1 2140.97  7098.0 2144.87
#Mann=9,-1,0
  3913.8   0.035       0  4812.4    0.07       0  4874.8    0.07       0
  4880.4    0.07       0  4926.2   0.035       0  4926.3    0.07       0
  6260.0   0.035       0  6364.6    0.07       0  6561.6   0.035       0
Bank Sta=4874.8,4880.4
Exp/Cntr=0.3,0.1

Type RM Length L Ch R = 1,4018,630,630,630
BEGIN DESCRIPTION:
Cottonwood Creek Trib079 8.0
END DESCRIPTION:
XS GIS Cut Line= 3
      1338692.39      6904165.70      1339150.73      6903193.47
      1337789.82      6901249.31
#Sta/Elev= 30
  3993.2 2171.89  4014.7 2170.84  4031.9 2166.11  4060.2 2165.47  4077.5 2162.54
  4128.6 2160.43  4384.7 2141.50  4819.8 2119.66  4926.5 2116.73  4985.7 2113.61
  5004.8 2110.61  5005.3 2110.11  5010.8 2110.61  5016.4 2113.72  5039.1 2115.40
  5181.3 2116.25  5255.8 2116.34  5709.4 2116.91  5913.6 2116.79  6527.5 2121.69
  6676.8 2122.43  6706.4 2119.38  6727.3 2120.11  6734.8 2122.27  6769.6 2122.37
  6834.1 2123.61  7072.6 2128.18  7194.7 2133.64  7251.3 2140.23  7441.2 2143.28
#Mann=11,-1,0
  3993.2   0.035       0  4926.5    0.07       0  5004.8    0.07       0
  5010.8    0.07       0  5181.3   0.035       0  5255.8    0.07       0
  5709.4   0.035       0  5913.6    0.07       0  6527.5   0.035       0
  6769.6    0.07       0  6834.1   0.035       0
Bank Sta=5004.8,5010.8
Exp/Cntr=0.3,0.1

Type RM Length L Ch R = 1,3388,0,0,0
BEGIN DESCRIPTION:
Cottonwood Creek Trib079 7.0
END DESCRIPTION:
XS GIS Cut Line= 4
      1338985.38      6904221.23      1339668.96      6903515.95
      1339679.81      6903244.68      1337857.96      6901281.86
#Sta/Elev= 30
  3839.9 2195.21  3912.7 2191.76  3948.0 2193.88  4019.0 2186.52  4061.2 2178.22
  4098.1 2161.84  4138.9 2148.25  4160.8 2143.99  4477.4 2124.04  4525.1 2121.37
  4648.2 2115.06  4930.1 2114.40  4977.2 2108.60  4977.7 2108.10  4983.2 2108.60
  4996.7 2110.31  5060.2 2113.32  5108.8 2111.35  5344.9 2114.34  5821.4 2115.31
  5923.5 2115.52  6145.0 2116.47  6509.4 2117.66  6578.3 2118.31  6819.5 2120.79
  7005.1 2119.45  7500.6 2126.90  7620.8 2131.38  7663.3 2140.27  7771.6 2142.39
#Mann=16,-1,0
  3839.9    0.07       0  4019.0   0.035       0  4098.1    0.07       0
  4160.8   0.035       0  4477.4    0.07       0  4525.1   0.035       0
  4977.2    0.07       0  4983.2   0.035       0  4996.7    0.07       0
  5344.9   0.035       0  5821.4    0.07       0  5923.5   0.035       0
  6145.0    0.07       0  6509.4   0.035       0  6578.3    0.07       0
  6819.5   0.035       0
Bank Sta=4977.2,4983.2
Exp/Cntr=0.3,0.1

Chan Stop Cuts=-1