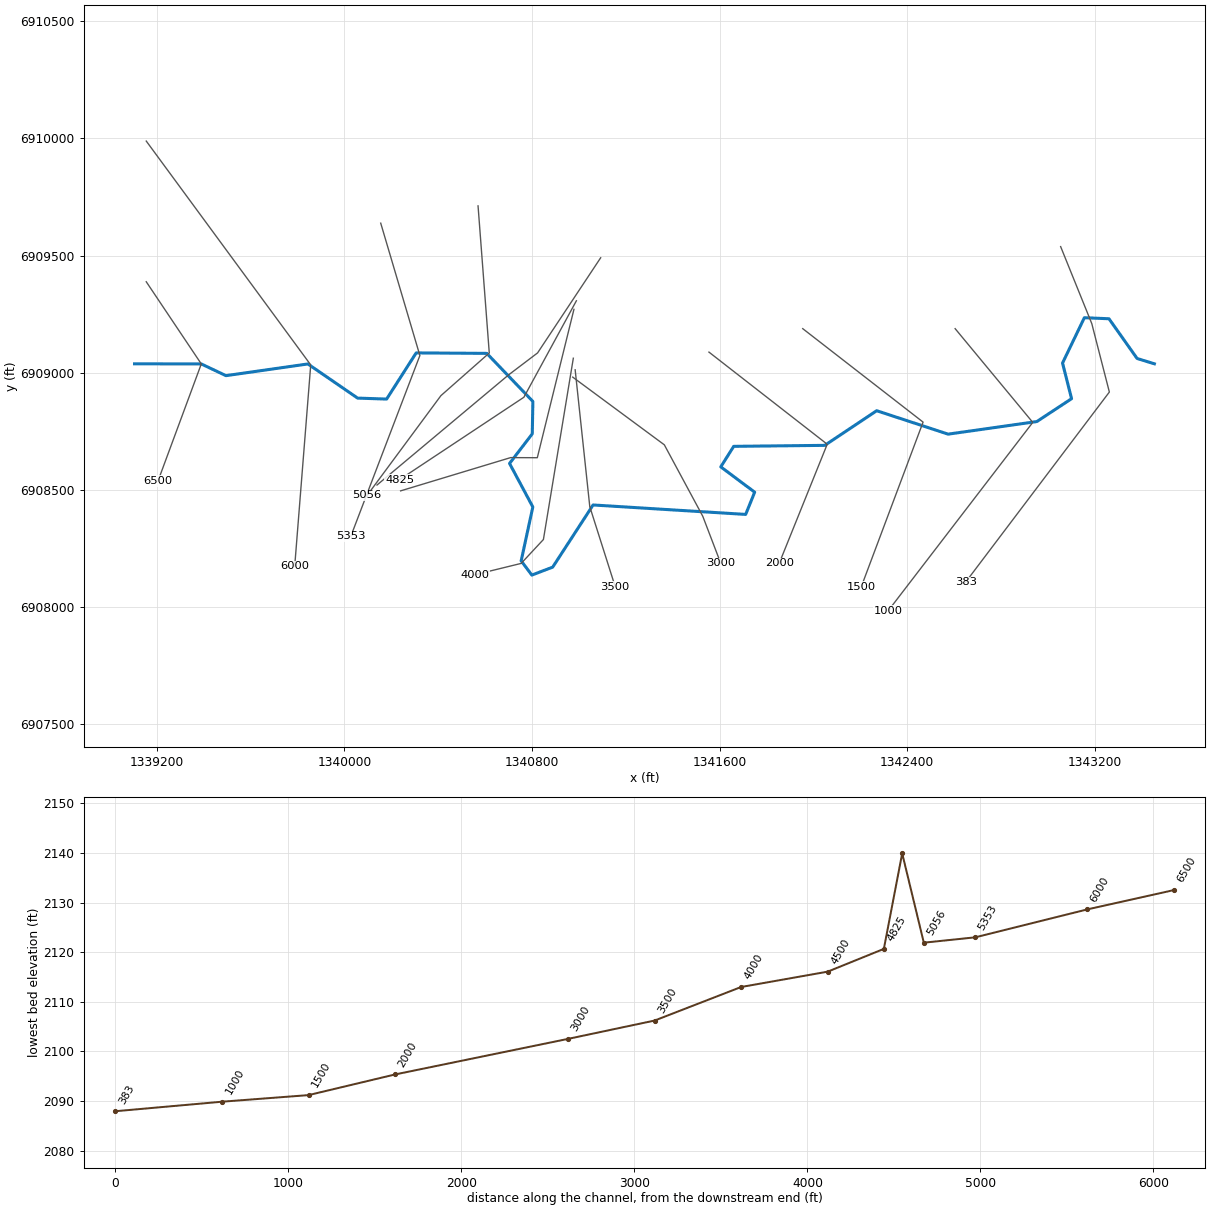
--- Cottonwood Creek Trib080.prj (project) ---

Proj Title=Cottonwood Creek Trib080 Base Level Engineering
Current Plan=p01
Default Exp/Contr=0.3,0.1
English Units
Geom File=g01
Flow File=f01
Plan File=p01
BEGIN DESCRIPTION:
Cottonwood Creek Trib080
END DESCRIPTION:

--- Cottonwood Creek Trib080.p01 (plan) ---

Plan Title=Multiple Run
Short Identifier=Multiple
Geom File=g01
Flow File=f01
Subcritical Flow
K Sum by GR= 0
Std Step Tol= 0.01
Critical Tol= 0.01
Num of Std Step Trials= 20
Max Error Tol= 0.3
Flow Tol Ratio= 0.001
Split Flow NTrial= 30
Split Flow Tol= 0.02
Split Flow Ratio= 0.02
Log Output Level= 0
Friction Slope Method= 1
Unsteady Friction Slope Method= 2
Unsteady Bridges Friction Slope Method= 1
Parabolic Critical Depth
Global Vel Dist=  1 , 1 , 1
Global Log Level= 0
CheckData=True
Encroach Param= -1, 0, 0, 0
BEGIN DESCRIPTION:
Multiple Run
END DESCRIPTION:

--- Cottonwood Creek Trib080.f01 (steady flow) ---

Flow Title=Multiple
Number of Profiles=7
Profile Names=10-year,25-year,50-year,1pct_min,100-year,1pct_plu,500-year
River Rch & RM= Cottonwood Creek,Reach-1,6500
     304     438     552     347     692    1381    1100
River Rch & RM= Cottonwood Creek,Reach-1,4500
     327     471     593     372     742    1481    1178
Boundary for River Rch & Prof#=Cottonwood Creek,Reach-1,1
Up Type=0
Dn Type=3
Dn Slope=0.005
Boundary for River Rch & Prof#=Cottonwood Creek,Reach-1,2
Up Type=0
Dn Type=3
Dn Slope=0.005
Boundary for River Rch & Prof#=Cottonwood Creek,Reach-1,3
Up Type=0
Dn Type=3
Dn Slope=0.005
Boundary for River Rch & Prof#=Cottonwood Creek,Reach-1,4
Up Type=0
Dn Type=3
Dn Slope=0.005
Boundary for River Rch & Prof#=Cottonwood Creek,Reach-1,5
Up Type=0
Dn Type=3
Dn Slope=0.005
Boundary for River Rch & Prof#=Cottonwood Creek,Reach-1,6
Up Type=0
Dn Type=3
Dn Slope=0.005
Boundary for River Rch & Prof#=Cottonwood Creek,Reach-1,7
Up Type=0
Dn Type=3
Dn Slope=0.005

--- Cottonwood Creek Trib080.g01 (geometry) ---

Geom Title=Existing Conditions

River Reach=Cottonwood Creek,Reach-1
Reach XY= 30
      1339105.00      6909038.00      1339389.78      6909037.48
      1339494.81      6908987.55      1339844.38      6909037.40
      1340056.56      6908891.74      1340180.21      6908887.64
      1340306.22      6909084.56      1340607.45      6909082.54
      1340803.97      6908877.56      1340801.46      6908739.47
      1340704.50      6908613.03      1340803.81      6908427.50
      1340754.07      6908197.70      1340799.50      6908136.92
      1340888.54      6908170.85      1341060.84      6908435.95
      1341711.57      6908395.69      1341750.05      6908490.51
      1341605.46      6908598.54      1341660.62      6908686.02
      1342049.07      6908690.24      1342270.36      6908837.99
      1342575.03      6908738.04      1342953.45      6908791.75
      1343101.63      6908889.28      1343063.08      6909041.30
      1343156.25      6909234.64      1343261.19      6909230.25
      1343381.02      6909060.82      1343455.00      6909038.00

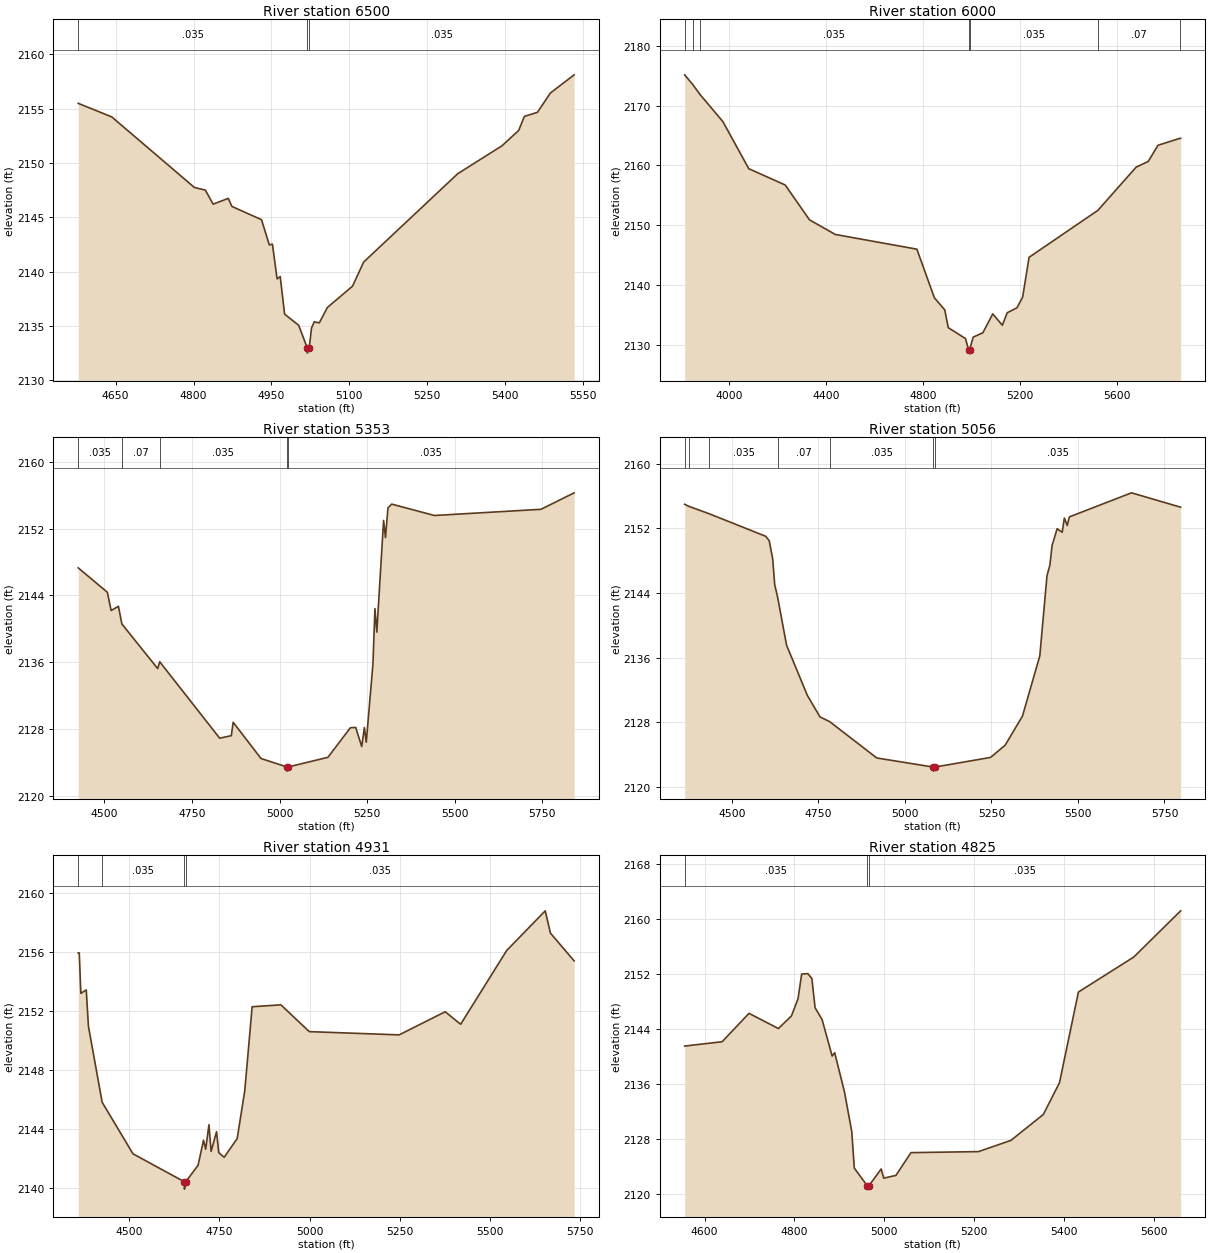
Type RM Length L Ch R = 1,6500,500,500,500
BEGIN DESCRIPTION:
Cottonwood Creek Trib080 12.0
END DESCRIPTION:
XS GIS Cut Line= 3
      1339154.98      6909388.03      1339389.75      6909037.48
      1339204.98      6908537.96
#Sta/Elev= 30
  4578.1 2155.48  4642.7 2154.23  4801.8 2147.74  4822.8 2147.50  4837.8 2146.21
  4867.0 2146.74  4873.8 2146.00  4930.9 2144.78  4945.9 2142.46  4951.9 2142.53
  4960.9 2139.34  4966.9 2139.55  4975.3 2136.10  5002.4 2135.07  5018.8 2133.01
  5019.0 2132.51  5022.8 2133.01  5027.1 2134.81  5032.4 2135.39  5042.1 2135.29
  5057.5 2136.70  5106.1 2138.67  5127.4 2140.88  5308.6 2149.01  5393.9 2151.58
  5425.9 2152.99  5436.8 2154.28  5461.9 2154.65  5486.9 2156.43  5532.6 2158.10
#Mann=3,-1,0
  4578.1   0.035       0  5018.8   0.035       0  5022.8   0.035       0
Bank Sta=5018.8,5022.8
Exp/Cntr=0.3,0.1

Type RM Length L Ch R = 1,6000,647,647,647
BEGIN DESCRIPTION:
Cottonwood Creek Trib080 11.0
END DESCRIPTION:
XS GIS Cut Line= 3
      1339155.01      6909987.99      1339856.49      6909033.30
      1339788.17      6908174.91
#Sta/Elev= 30
  3815.3 2175.15  3848.2 2173.55  3878.7 2171.86  3973.1 2167.32  4079.6 2159.46
  4230.0 2156.73  4330.3 2150.90  4436.8 2148.46  4773.2 2146.00  4845.3 2137.88
  4888.2 2135.85  4902.8 2132.87  4973.9 2131.05  4986.5 2129.12  4986.7 2128.62
  4990.5 2129.12  5005.3 2131.29  5045.4 2132.03  5086.2 2135.18  5125.7 2133.29
  5145.8 2135.37  5185.9 2136.20  5209.4 2137.98  5236.0 2144.64  5520.1 2152.50
  5677.4 2159.71  5727.6 2160.67  5767.7 2163.37  5857.7 2164.53  5861.1 2164.53
#Mann=7,-1,0
  3815.3   0.035       0  3848.2    0.07       0  3878.7   0.035       0
  4986.5   0.035       0  4990.5   0.035       0  5520.1    0.07       0
  5857.7   0.035       0
Bank Sta=4986.5,4990.5
Exp/Cntr=0.3,0.1

Type RM Length L Ch R = 1,5353,297,297,297
BEGIN DESCRIPTION:
Cottonwood Creek Trib080 10.0
END DESCRIPTION:
XS GIS Cut Line= 3
      1340155.00      6909638.00      1340322.02      6909073.33
      1340027.30      6908301.86
#Sta/Elev= 30
  4425.8 2147.30  4509.0 2144.38  4519.7 2142.20  4540.5 2142.71  4550.4 2140.59
  4652.5 2135.26  4658.4 2136.07  4829.3 2126.94  4862.5 2127.24  4867.8 2128.84
  4947.2 2124.51  5021.0 2123.50  5021.3 2123.00  5025.0 2123.50  5138.1 2124.65
  5202.3 2128.19  5217.4 2128.22  5234.5 2125.94  5242.1 2128.21  5247.5 2126.46
  5266.6 2135.85  5272.2 2142.43  5277.6 2139.62  5296.9 2152.97  5302.3 2150.92
  5309.4 2154.46  5320.1 2154.92  5441.9 2153.56  5745.9 2154.30  5840.5 2156.27
#Mann=5,-1,0
  4425.8   0.035       0  4550.4    0.07       0  4658.4   0.035       0
  5021.0   0.035       0  5025.0   0.035       0
Bank Sta=5021,5025
Exp/Cntr=0.3,0.1

Type RM Length L Ch R = 1,5056,125,125,125
BEGIN DESCRIPTION:
Cottonwood Creek Trib080 9.6
END DESCRIPTION:
XS GIS Cut Line= 4
      1340570.15      6909711.72      1340618.02      6909084.18
      1340411.73      6908902.25      1340097.07      6908476.91
#Sta/Elev= 30
  4363.2 2154.99  4374.5 2154.75  4434.4 2153.81  4597.6 2151.02  4607.6 2150.47
  4617.7 2148.20  4623.4 2145.03  4631.7 2143.51  4657.8 2137.51  4717.9 2131.30
  4754.3 2128.64  4782.1 2128.06  4918.5 2123.55  5082.2 2122.42  5082.4 2121.92
  5086.2 2122.42  5247.3 2123.62  5289.5 2125.13  5339.6 2128.74  5389.7 2136.21
  5410.5 2146.15  5418.9 2147.46  5425.1 2149.87  5439.8 2151.96  5454.4 2151.52
  5460.6 2153.28  5469.0 2152.37  5475.2 2153.43  5654.8 2156.41  5796.7 2154.63
#Mann=7,-1,0
  4363.2   0.035       0  4374.5    0.07       0  4434.4   0.035       0
  4631.7    0.07       0  4782.1   0.035       0  5082.2   0.035       0
  5086.2   0.035       0
Bank Sta=5082.2,5086.2
Exp/Cntr=0.3,0.1

Type RM Length L Ch R = 1,4931,106,106,106
BEGIN DESCRIPTION:
Cottonwood Creek Trib080 9.5
END DESCRIPTION:
XS GIS Cut Line= 4
      1341093.16      6909490.37      1340824.06      6909084.54
      1340700.49      6908990.86      1340139.17      6908521.04
#Sta/Elev= 30
  4359.2 2155.94  4362.1 2155.94  4366.5 2153.20  4381.5 2153.43  4387.5 2150.97
  4425.5 2145.81  4510.8 2142.31  4653.2 2140.41  4653.5 2139.91  4657.2 2140.41
  4691.3 2141.53  4706.4 2143.23  4712.4 2142.62  4721.4 2144.28  4727.4 2142.47
  4742.5 2143.81  4748.5 2142.39  4763.5 2142.07  4799.6 2143.34  4820.6 2146.58
  4841.1 2152.29  4920.7 2152.42  4999.4 2150.60  5248.4 2150.38  5375.9 2151.95
  5418.8 2151.10  5546.4 2156.11  5653.1 2158.80  5667.4 2157.29  5733.2 2155.40
#Mann=4,-1,0
  4359.2    0.07       0  4425.5   0.035       0  4653.2   0.035       0
  4657.2   0.035       0
Bank Sta=4653.2,4657.2
Exp/Cntr=0.3,0.1

Type RM Length L Ch R = 1,4825,325,325,325
BEGIN DESCRIPTION:
Cottonwood Creek Trib080 9.0
END DESCRIPTION:
XS GIS Cut Line= 3
      1340989.58      6909306.88      1340765.59      6908895.38
      1340235.24      6908543.83
#Sta/Elev= 30
  4555.6 2141.49  4639.0 2142.12  4698.9 2146.25  4764.4 2144.04  4793.4 2145.87
  4808.1 2148.37  4816.2 2151.97  4830.0 2152.03  4839.0 2151.31  4846.1 2147.07
  4861.7 2145.35  4884.1 2140.04  4889.8 2140.52  4911.6 2134.81  4927.8 2129.05
  4933.5 2123.73  4962.2 2121.17  4962.4 2120.67  4966.2 2121.17  4993.3 2123.60
  4999.0 2122.27  5026.3 2122.67  5059.7 2125.98  5210.1 2126.13  5282.3 2127.76
  5354.5 2131.53  5390.6 2136.16  5432.7 2149.35  5556.0 2154.44  5660.4 2161.17
#Mann=3,-1,0
  4555.6   0.035       0  4962.2   0.035       0  4966.2   0.035       0
Bank Sta=4962.2,4966.2
Exp/Cntr=0.3,0.1

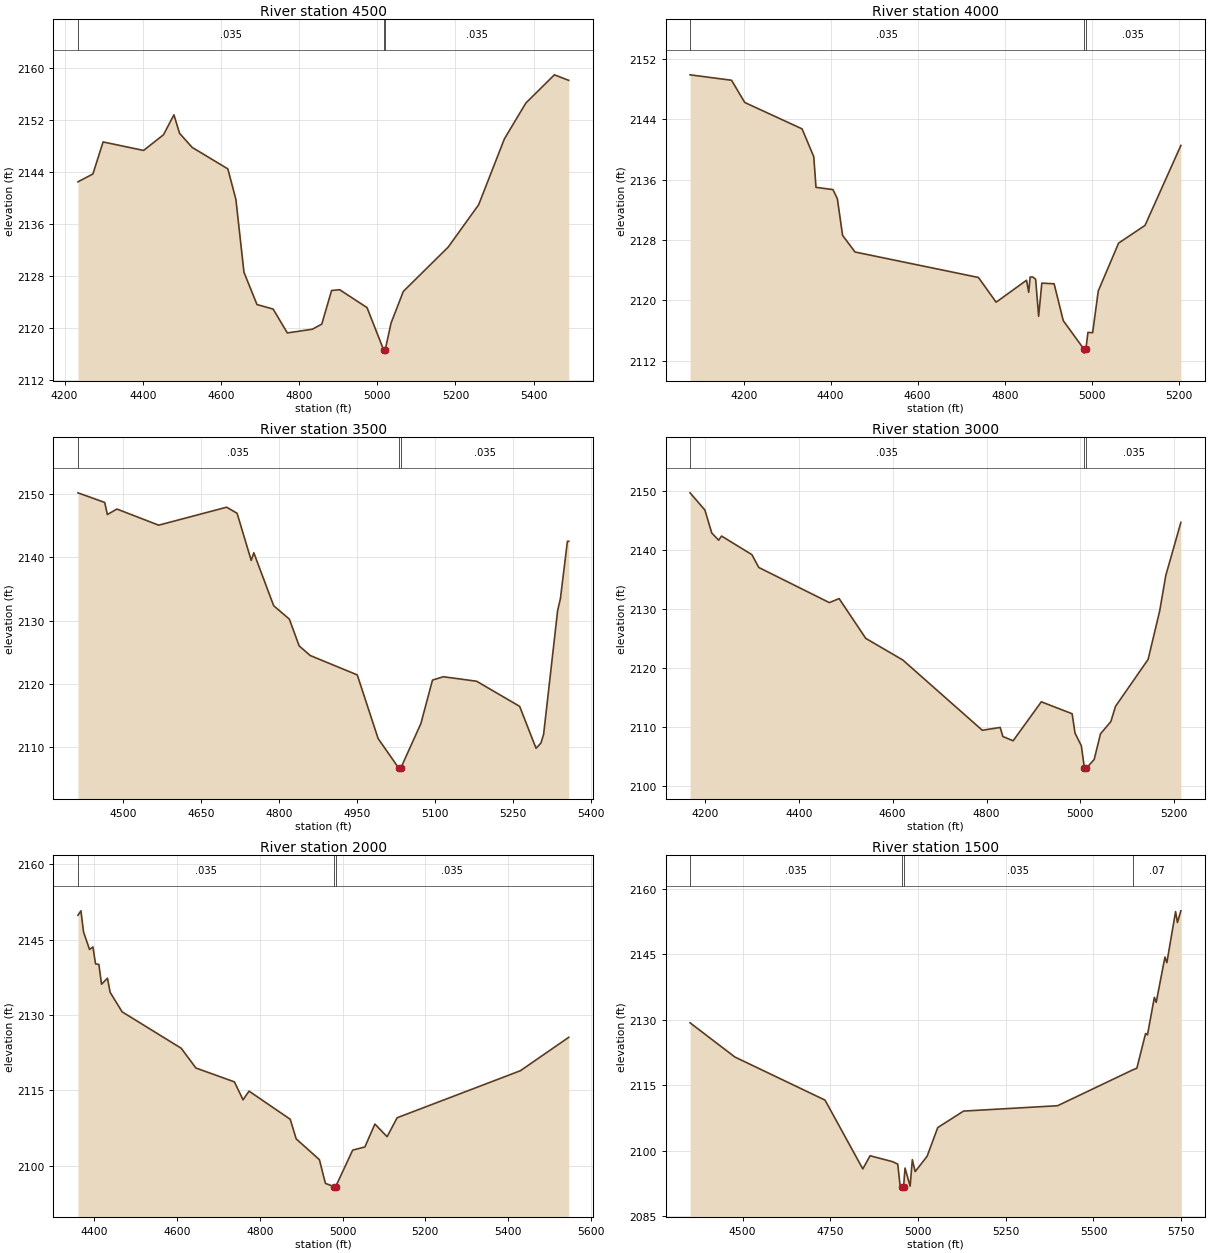
Type RM Length L Ch R = 1,4500,500,500,500
BEGIN DESCRIPTION:
Cottonwood Creek Trib080 8.0
END DESCRIPTION:
XS GIS Cut Line= 4
      1340979.14      6909270.40      1340822.89      6908637.57
      1340708.93      6908637.95      1340239.79      6908496.14
#Sta/Elev= 30
  4234.2 2142.45  4272.5 2143.66  4298.5 2148.59  4402.1 2147.28  4453.0 2149.69
  4479.8 2152.76  4494.2 2149.92  4526.4 2147.75  4617.8 2144.44  4638.4 2139.73
  4659.0 2128.53  4692.3 2123.56  4733.7 2122.86  4770.0 2119.19  4834.1 2119.76
  4858.1 2120.55  4883.2 2125.72  4903.9 2125.84  4973.9 2123.09  5016.4 2116.58
  5016.7 2116.08  5020.4 2116.58  5035.4 2120.71  5066.8 2125.58  5181.7 2132.41
  5259.5 2138.92  5325.4 2149.06  5380.2 2154.57  5453.3 2158.92  5490.1 2158.07
#Mann=3,-1,0
  4234.2   0.035       0  5016.4   0.035       0  5020.4   0.035       0
Bank Sta=5016.4,5020.4
Exp/Cntr=0.3,0.1

Type RM Length L Ch R = 1,4000,500,500,500
BEGIN DESCRIPTION:
Cottonwood Creek Trib080 7.0
END DESCRIPTION:
XS GIS Cut Line= 4
      1340976.53      6909062.00      1340848.93      6908288.61
      1340753.99      6908186.74      1340554.97      6908137.99
#Sta/Elev= 30
  4076.9 2149.92  4172.2 2149.20  4202.6 2146.25  4334.3 2142.75  4361.2 2139.06
  4366.3 2134.99  4405.3 2134.69  4415.4 2133.49  4427.4 2128.62  4456.0 2126.41
  4739.7 2123.03  4780.3 2119.75  4850.2 2122.66  4855.2 2121.06  4858.5 2123.09
  4864.6 2123.09  4871.1 2122.79  4878.0 2117.88  4885.3 2122.28  4913.6 2122.19
  4934.6 2117.30  4982.5 2113.49  4982.7 2112.99  4986.5 2113.49  4991.3 2115.74
  5002.1 2115.70  5015.1 2121.25  5061.8 2127.59  5122.5 2129.94  5204.9 2140.55
#Mann=3,-1,0
  4076.9   0.035       0  4982.5   0.035       0  4986.5   0.035       0
Bank Sta=4982.5,4986.5
Exp/Cntr=0.3,0.1

Type RM Length L Ch R = 1,3500,500,500,500
BEGIN DESCRIPTION:
Cottonwood Creek Trib080 6.0
END DESCRIPTION:
XS GIS Cut Line= 3
      1340984.34      6909012.57      1341046.75      6908428.69
      1341155.01      6908087.98
#Sta/Elev= 30
  4412.8 2150.19  4464.3 2148.67  4469.4 2146.76  4487.8 2147.63  4568.2 2145.08
  4699.0 2147.92  4719.1 2146.96  4746.3 2139.52  4751.3 2140.72  4789.5 2132.36
  4819.7 2130.24  4838.6 2126.01  4859.9 2124.49  4950.4 2121.43  4990.6 2111.37
  5030.1 2106.73  5030.4 2106.23  5034.3 2106.73  5072.9 2113.75  5095.2 2120.61
  5116.1 2121.14  5180.1 2120.43  5263.0 2116.46  5294.5 2109.84  5303.9 2110.66
  5309.1 2112.04  5336.1 2131.61  5341.4 2133.46  5354.9 2142.53  5357.5 2142.53
#Mann=3,-1,0
  4412.8   0.035       0  5030.1   0.035       0  5034.3   0.035       0
Bank Sta=5030.1,5034.3
Exp/Cntr=0.3,0.1

Type RM Length L Ch R = 1,3000,1000,1000,1000
BEGIN DESCRIPTION:
Cottonwood Creek Trib080 5.0
END DESCRIPTION:
XS GIS Cut Line= 4
      1340973.95      6908981.30      1341364.68      6908692.52
      1341528.57      6908387.99      1341605.00      6908188.00
#Sta/Elev= 30
  4168.3 2149.67  4199.9 2146.76  4214.5 2142.87  4229.2 2141.65  4235.4 2142.35
  4300.1 2139.20  4314.7 2137.03  4465.1 2131.08  4485.9 2131.76  4542.7 2125.02
  4621.6 2121.36  4791.0 2109.46  4829.1 2109.94  4834.8 2108.40  4856.7 2107.68
  4916.7 2114.28  4982.4 2112.26  4988.6 2108.97  5002.0 2106.84  5008.6 2103.04
  5008.8 2102.54  5012.8 2103.04  5029.4 2104.52  5042.8 2108.85  5064.8 2110.92
  5074.9 2113.52  5144.3 2121.46  5169.0 2129.69  5182.0 2135.69  5214.1 2144.66
#Mann=3,-1,0
  4168.3   0.035       0  5008.6   0.035       0  5012.8   0.035       0
Bank Sta=5008.6,5012.8
Exp/Cntr=0.3,0.1

Type RM Length L Ch R = 1,2000,500,500,500
BEGIN DESCRIPTION:
Cottonwood Creek Trib080 4.0
END DESCRIPTION:
XS GIS Cut Line= 3
      1341555.02      6909087.98      1342059.44      6908695.04
      1341855.00      6908188.01
#Sta/Elev= 30
  4360.6 2149.86  4367.8 2150.74  4374.1 2146.53  4388.6 2143.05  4396.8 2143.55
  4403.1 2140.19  4411.2 2140.07  4417.6 2136.14  4432.0 2137.33  4438.4 2134.52
  4467.3 2130.65  4610.3 2123.39  4645.6 2119.47  4738.7 2116.71  4759.6 2113.14
  4774.0 2114.87  4873.6 2109.27  4888.0 2105.37  4944.1 2101.23  4958.6 2096.52
  4979.1 2095.87  4979.4 2095.37  4983.4 2095.87  5024.5 2103.13  5054.0 2103.76
  5078.2 2108.32  5107.7 2105.80  5131.9 2109.57  5429.9 2118.93  5546.7 2125.58
#Mann=3,-1,0
  4360.6   0.035       0  4979.1   0.035       0  4983.4   0.035       0
Bank Sta=4979.1,4983.4
Exp/Cntr=0.3,0.1

Type RM Length L Ch R = 1,1500,500,500,500
BEGIN DESCRIPTION:
Cottonwood Creek Trib080 3.0
END DESCRIPTION:
XS GIS Cut Line= 3
      1341954.96      6909188.03      1342468.26      6908789.41
      1342205.00      6908087.99
#Sta/Elev= 30
  4350.1 2129.34  4477.8 2121.50  4734.8 2111.62  4842.5 2095.85  4863.3 2098.86
  4927.6 2097.50  4942.1 2096.95  4948.4 2092.33  4954.3 2091.71  4954.6 2091.21
  4958.7 2091.71  4962.9 2096.04  4977.4 2091.90  4983.7 2097.95  4991.8 2095.22
  5025.9 2098.76  5056.1 2105.32  5129.7 2109.10  5397.8 2110.33  5612.0 2118.55
  5623.7 2118.92  5648.6 2126.89  5654.0 2126.58  5673.6 2135.17  5678.9 2134.03
  5703.8 2144.42  5709.2 2143.12  5734.1 2154.83  5739.4 2152.34  5749.2 2155.01
#Mann=4,-1,0
  4350.1   0.035       0  4954.3   0.035       0  4958.7   0.035       0
  5612.0    0.07       0
Bank Sta=4954.3,4958.7
Exp/Cntr=0.3,0.1

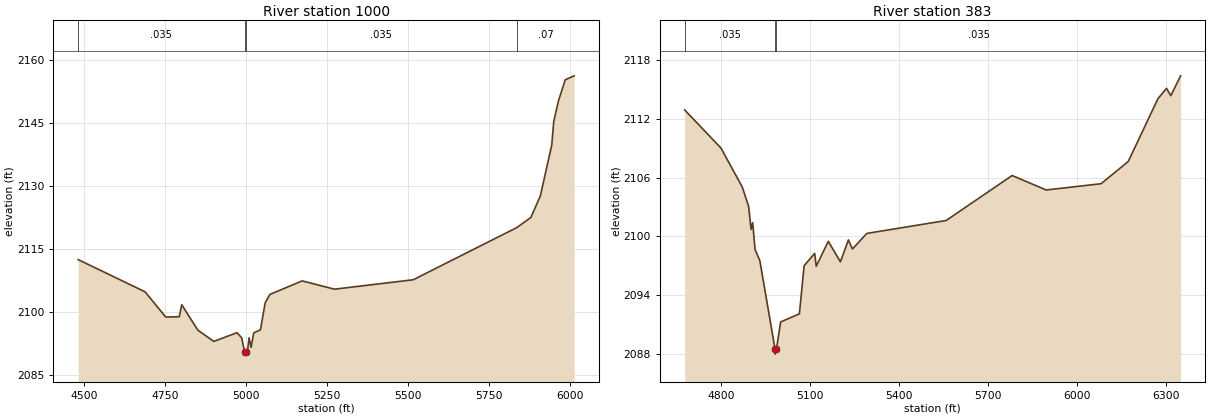
Type RM Length L Ch R = 1,1000,617,617,617
BEGIN DESCRIPTION:
Cottonwood Creek Trib080 2.0
END DESCRIPTION:
XS GIS Cut Line= 3
      1342605.03      6909187.97      1342936.12      6908788.17
      1342319.97      6907985.36
#Sta/Elev= 30
  4480.9 2112.42  4687.3 2104.74  4751.1 2098.73  4792.8 2098.79  4800.6 2101.65
  4850.1 2095.61  4899.6 2092.91  4971.2 2095.00  4985.6 2093.76  4994.7 2090.38
  4995.0 2089.88  4999.1 2090.38  5003.3 2090.38  5008.3 2093.78  5014.6 2091.49
  5022.8 2094.96  5043.6 2095.68  5058.1 2102.13  5072.6 2104.11  5172.3 2107.35
  5272.0 2105.37  5515.0 2107.61  5834.1 2120.02  5878.4 2122.47  5907.5 2127.58
  5942.8 2139.71  5949.1 2145.41  5963.6 2150.28  5984.4 2155.30  6012.0 2156.25
#Mann=4,-1,0
  4480.9   0.035       0  4994.7   0.035       0  4999.1   0.035       0
  5834.1    0.07       0
Bank Sta=4994.7,4999.1
Exp/Cntr=0.3,0.1

Type RM Length L Ch R = 1,383,0,0,0
BEGIN DESCRIPTION:
Cottonwood Creek Trib080 1.0
END DESCRIPTION:
XS GIS Cut Line= 4
      1343055.01      6909537.97      1343187.95      6909209.22
      1343262.80      6908917.62      1342649.85      6908106.92
#Sta/Elev= 30
  4676.8 2112.92  4798.8 2109.04  4870.9 2105.05  4892.5 2103.05  4900.7 2100.71
  4906.1 2101.40  4914.1 2098.66  4930.2 2097.51  4981.6 2088.46  4981.9 2087.96
  4986.1 2088.46  5000.4 2091.25  5063.6 2092.08  5079.5 2097.00  5115.1 2098.26
  5120.3 2096.94  5161.0 2099.49  5201.8 2097.40  5228.8 2099.63  5242.5 2098.71
  5290.8 2100.30  5558.3 2101.62  5780.9 2106.22  5895.4 2104.74  6080.6 2105.38
  6172.2 2107.65  6272.2 2114.06  6301.2 2115.13  6315.7 2114.38  6348.8 2116.41
#Mann=3,-1,0
  4676.8   0.035       0  4981.6   0.035       0  4986.1   0.035       0
Bank Sta=4981.6,4986.1
Exp/Cntr=0.3,0.1

Chan Stop Cuts=-1