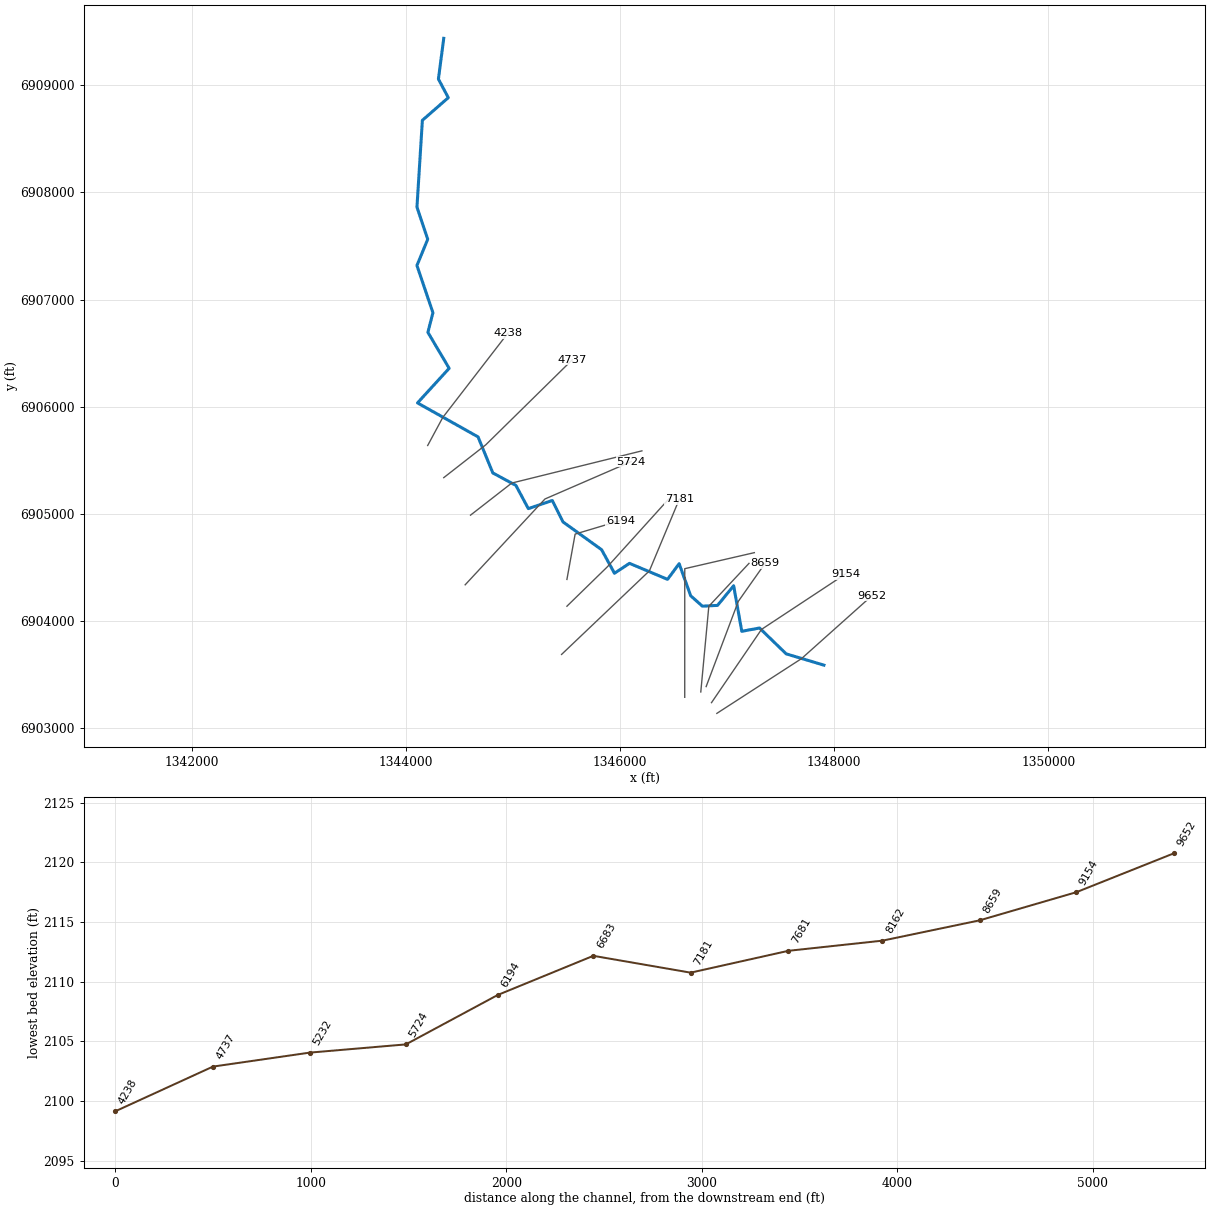
--- Cottonwood Creek Trib081.prj (project) ---

Proj Title=Cottonwood Creek Trib081 Base Level Engineering
Current Plan=p01
Default Exp/Contr=0.3,0.1
English Units
Geom File=g01
Flow File=f01
Plan File=p01
BEGIN DESCRIPTION:
Cottonwood Creek Trib081
END DESCRIPTION:

--- Cottonwood Creek Trib081.p01 (plan) ---

Plan Title=Multiple Run
Short Identifier=Multiple
Geom File=g01
Flow File=f01
Subcritical Flow
K Sum by GR= 0
Std Step Tol= 0.01
Critical Tol= 0.01
Num of Std Step Trials= 20
Max Error Tol= 0.3
Flow Tol Ratio= 0.001
Split Flow NTrial= 30
Split Flow Tol= 0.02
Split Flow Ratio= 0.02
Log Output Level= 0
Friction Slope Method= 1
Unsteady Friction Slope Method= 2
Unsteady Bridges Friction Slope Method= 1
Parabolic Critical Depth
Global Vel Dist=  1 , 1 , 1
Global Log Level= 0
CheckData=True
Encroach Param= -1, 0, 0, 0
BEGIN DESCRIPTION:
Multiple Run
END DESCRIPTION:

--- Cottonwood Creek Trib081.f01 (steady flow) ---

Flow Title=Multiple
Number of Profiles=7
Profile Names=10-year,25-year,50-year,1pct_min,100-year,1pct_plu,500-year
River Rch & RM= Cottonwood Creek,Reach-1,9652
     431     627     795     501     999    1994    1601
Boundary for River Rch & Prof#=Cottonwood Creek,Reach-1,1
Up Type=0
Dn Type=3
Dn Slope=0.005
Boundary for River Rch & Prof#=Cottonwood Creek,Reach-1,2
Up Type=0
Dn Type=3
Dn Slope=0.005
Boundary for River Rch & Prof#=Cottonwood Creek,Reach-1,3
Up Type=0
Dn Type=3
Dn Slope=0.005
Boundary for River Rch & Prof#=Cottonwood Creek,Reach-1,4
Up Type=0
Dn Type=3
Dn Slope=0.005
Boundary for River Rch & Prof#=Cottonwood Creek,Reach-1,5
Up Type=0
Dn Type=3
Dn Slope=0.005
Boundary for River Rch & Prof#=Cottonwood Creek,Reach-1,6
Up Type=0
Dn Type=3
Dn Slope=0.005
Boundary for River Rch & Prof#=Cottonwood Creek,Reach-1,7
Up Type=0
Dn Type=3
Dn Slope=0.005

--- Cottonwood Creek Trib081.g01 (geometry) ---

Geom Title=Existing Conditions

River Reach=Cottonwood Creek,Reach-1
Reach XY= 30
      1347905.00      6903588.00      1347552.34      6903693.46
      1347303.50      6903934.54      1347137.83      6903904.10
      1347061.84      6904329.25      1346911.21      6904145.80
      1346770.16      6904138.36      1346660.45      6904235.53
      1346552.93      6904535.09      1346444.58      6904388.83
      1346089.24      6904538.11      1345948.95      6904445.45
      1345828.99      6904665.32      1345468.40      6904924.70
      1345368.33      6905124.68      1345144.68      6905048.82
      1345028.90      6905265.28      1344813.13      6905381.92
      1344675.20      6905718.39      1344109.96      6906035.46
      1344405.39      6906358.37      1344206.82      6906694.12
      1344253.90      6906877.45      1344104.60      6907317.86
      1344205.32      6907562.89      1344104.79      6907862.91
      1344155.38      6908672.84      1344397.33      6908884.34
      1344305.06      6909058.03      1344355.00      6909438.00

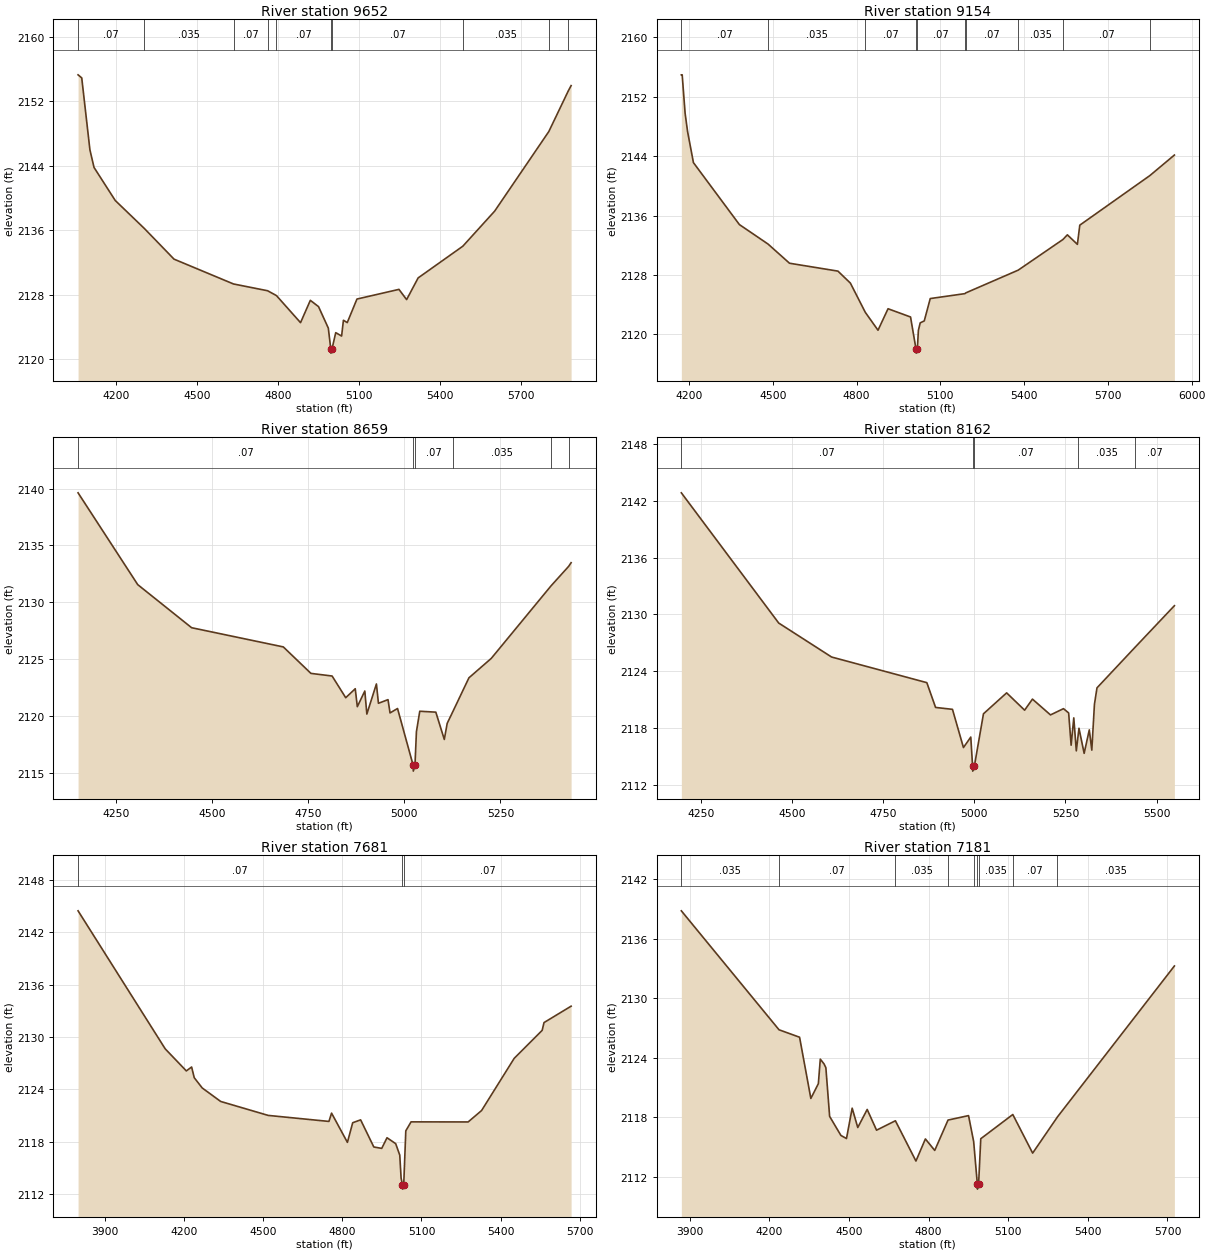
Type RM Length L Ch R = 1,9652,498,498,498
BEGIN DESCRIPTION:
Cottonwood Creek Trib081 12.0
END DESCRIPTION:
XS GIS Cut Line= 3
      1346904.98      6903137.99      1347695.35      6903648.85
      1348354.97      6904237.97
#Sta/Elev= 30
  4058.9 2155.27  4072.5 2154.89  4102.8 2145.96  4118.0 2143.78  4196.5 2139.68
  4304.8 2136.19  4414.2 2132.40  4634.4 2129.32  4760.7 2128.48  4793.4 2127.88
  4882.6 2124.52  4918.9 2127.29  4949.2 2126.51  4985.5 2123.84  4994.6 2121.24
  4994.9 2120.74  4999.0 2121.24  5012.9 2123.28  5034.7 2122.86  5041.4 2124.82
  5055.6 2124.53  5091.5 2127.45  5247.0 2128.65  5275.4 2127.38  5318.0 2130.07
  5483.6 2134.01  5601.4 2138.36  5802.0 2148.24  5873.9 2153.27  5884.4 2153.93
#Mann=10,-1,0
  4058.9    0.07       0  4304.8   0.035       0  4634.4    0.07       0
  4760.7   0.035       0  4793.4    0.07       0  4994.6    0.07       0
  4999.0    0.07       0  5483.6   0.035       0  5802.0    0.07       0
  5873.9   0.035       0
Bank Sta=4994.6,4999
Exp/Cntr=0.3,0.1

Type RM Length L Ch R = 1,9154,495,495,495
BEGIN DESCRIPTION:
Cottonwood Creek Trib081 11.0
END DESCRIPTION:
XS GIS Cut Line= 3
      1346855.03      6903238.04      1347321.75      6903921.60
      1348105.03      6904438.02
#Sta/Elev= 30
  4172.3 2154.92  4175.3 2154.92  4185.8 2149.74  4194.6 2147.29  4215.6 2143.11
  4380.2 2134.78  4482.8 2132.16  4559.7 2129.58  4733.1 2128.52  4777.7 2126.91
  4831.1 2122.98  4876.7 2120.57  4912.6 2123.46  4993.2 2122.35  5013.0 2117.99
  5013.4 2117.49  5017.5 2117.99  5021.3 2120.55  5027.8 2121.56  5042.3 2121.82
  5063.8 2124.83  5187.9 2125.49  5191.6 2125.60  5378.8 2128.65  5538.9 2132.77
  5554.9 2133.40  5590.8 2132.12  5599.4 2134.70  5850.4 2141.37  5938.2 2144.13
#Mann=10,-1,0
  4172.3    0.07       0  4482.8   0.035       0  4831.1    0.07       0
  5013.0    0.07       0  5017.5    0.07       0  5187.9   0.035       0
  5191.6    0.07       0  5378.8   0.035       0  5538.9    0.07       0
  5850.4   0.035       0
Bank Sta=5013,5017.5
Exp/Cntr=0.3,0.1

Type RM Length L Ch R = 1,8659,497,497,497
BEGIN DESCRIPTION:
Cottonwood Creek Trib081 10.0
END DESCRIPTION:
XS GIS Cut Line= 3
      1346804.99      6903387.97      1347105.06      6904183.03
      1347354.98      6904537.97
#Sta/Elev= 30
  4150.2 2139.62  4305.6 2131.54  4445.9 2127.75  4684.7 2126.06  4756.6 2123.73
  4811.7 2123.50  4847.2 2121.59  4872.0 2122.38  4877.4 2120.80  4896.9 2122.18
  4902.2 2120.15  4927.1 2122.80  4932.4 2121.10  4957.3 2121.42  4962.6 2120.25
  4982.1 2120.64  5022.9 2115.63  5023.2 2115.13  5027.5 2115.63  5031.3 2118.60
  5040.0 2120.40  5081.8 2120.32  5103.9 2117.92  5111.4 2119.33  5127.0 2120.43
  5168.0 2123.34  5226.2 2125.05  5381.5 2131.42  5427.7 2133.15  5434.1 2133.47
#Mann=6,-1,0
  4150.2    0.07       0  5022.9    0.07       0  5027.5    0.07       0
  5127.0   0.035       0  5381.5    0.07       0  5427.7   0.035       0
Bank Sta=5022.9,5027.5
Exp/Cntr=0.3,0.1

Type RM Length L Ch R = 1,8162,481,481,481
BEGIN DESCRIPTION:
Cottonwood Creek Trib081 9.0
END DESCRIPTION:
XS GIS Cut Line= 3
      1346755.00      6903337.99      1346830.00      6904137.58
      1347205.00      6904538.00
#Sta/Elev= 30
  4196.9 2142.84  4463.8 2129.08  4608.7 2125.49  4869.9 2122.78  4893.9 2120.16
  4940.2 2119.96  4970.3 2115.92  4990.4 2117.03  4995.4 2113.93  4995.7 2113.43
  5000.1 2113.93  5025.2 2119.49  5088.7 2121.70  5138.0 2119.87  5159.5 2121.04
  5208.9 2119.37  5244.5 2120.03  5258.7 2119.58  5265.5 2116.17  5272.8 2119.06
  5279.7 2115.57  5283.7 2116.88  5287.0 2117.96  5301.2 2115.31  5315.3 2117.79
  5322.2 2115.65  5329.4 2120.49  5336.4 2122.23  5441.6 2126.55  5548.6 2130.91
#Mann=5,-1,0
  4196.9    0.07       0  4995.4    0.07       0  5000.1    0.07       0
  5283.7   0.035       0  5441.6    0.07       0
Bank Sta=4995.4,5000.1
Exp/Cntr=0.3,0.1

Type RM Length L Ch R = 1,7681,500,500,500
BEGIN DESCRIPTION:
Cottonwood Creek Trib081 8.0
END DESCRIPTION:
XS GIS Cut Line= 3
      1346605.00      6903287.99      1346605.30      6904488.39
      1347255.00      6904638.00
#Sta/Elev= 30
  3799.6 2144.48  4129.6 2128.66  4209.6 2126.13  4229.6 2126.58  4239.6 2125.35
  4269.6 2124.18  4339.6 2122.63  4519.6 2121.03  4749.6 2120.34  4759.6 2121.29
  4819.6 2117.94  4839.6 2120.19  4869.6 2120.52  4919.6 2117.41  4949.6 2117.25
  4969.6 2118.47  5002.4 2117.79  5017.8 2116.48  5022.9 2113.85  5028.1 2113.08
  5028.5 2112.58  5032.8 2113.08  5040.7 2119.26  5060.6 2120.29  5276.8 2120.28
  5327.7 2121.59  5451.2 2127.57  5557.1 2130.78  5564.1 2131.67  5666.7 2133.55
#Mann=3,-1,0
  3799.6    0.07       0  5028.1    0.07       0  5032.8    0.07       0
Bank Sta=5028.1,5032.8
Exp/Cntr=0.3,0.1

Type RM Length L Ch R = 1,7181,498,498,498
BEGIN DESCRIPTION:
Cottonwood Creek Trib081 7.0
END DESCRIPTION:
XS GIS Cut Line= 3
      1345455.00      6903688.00      1346275.09      6904468.02
      1346555.00      6905138.00
#Sta/Elev= 30
  3868.2 2138.80  4236.3 2126.81  4313.7 2126.06  4356.2 2119.89  4384.5 2121.38
  4391.8 2123.85  4405.9 2123.37  4412.8 2122.99  4427.0 2118.08  4469.5 2116.16
  4490.5 2115.85  4511.9 2118.91  4533.0 2116.96  4568.5 2118.78  4603.8 2116.69
  4674.8 2117.64  4752.2 2113.58  4787.8 2115.81  4823.0 2114.65  4873.1 2117.71
  4950.4 2118.16  4969.7 2115.55  4983.6 2111.25  4983.9 2110.75  4988.3 2111.25
  4996.5 2115.83  5117.2 2118.27  5192.0 2114.38  5285.5 2118.03  5726.1 2133.24
#Mann=9,-1,0
  3868.2   0.035       0  4236.3    0.07       0  4674.8   0.035       0
  4873.1    0.07       0  4969.7   0.035       0  4983.6   0.035       0
  4988.3   0.035       0  5117.2    0.07       0  5285.5   0.035       0
Bank Sta=4983.6,4988.3
Exp/Cntr=0.3,0.1

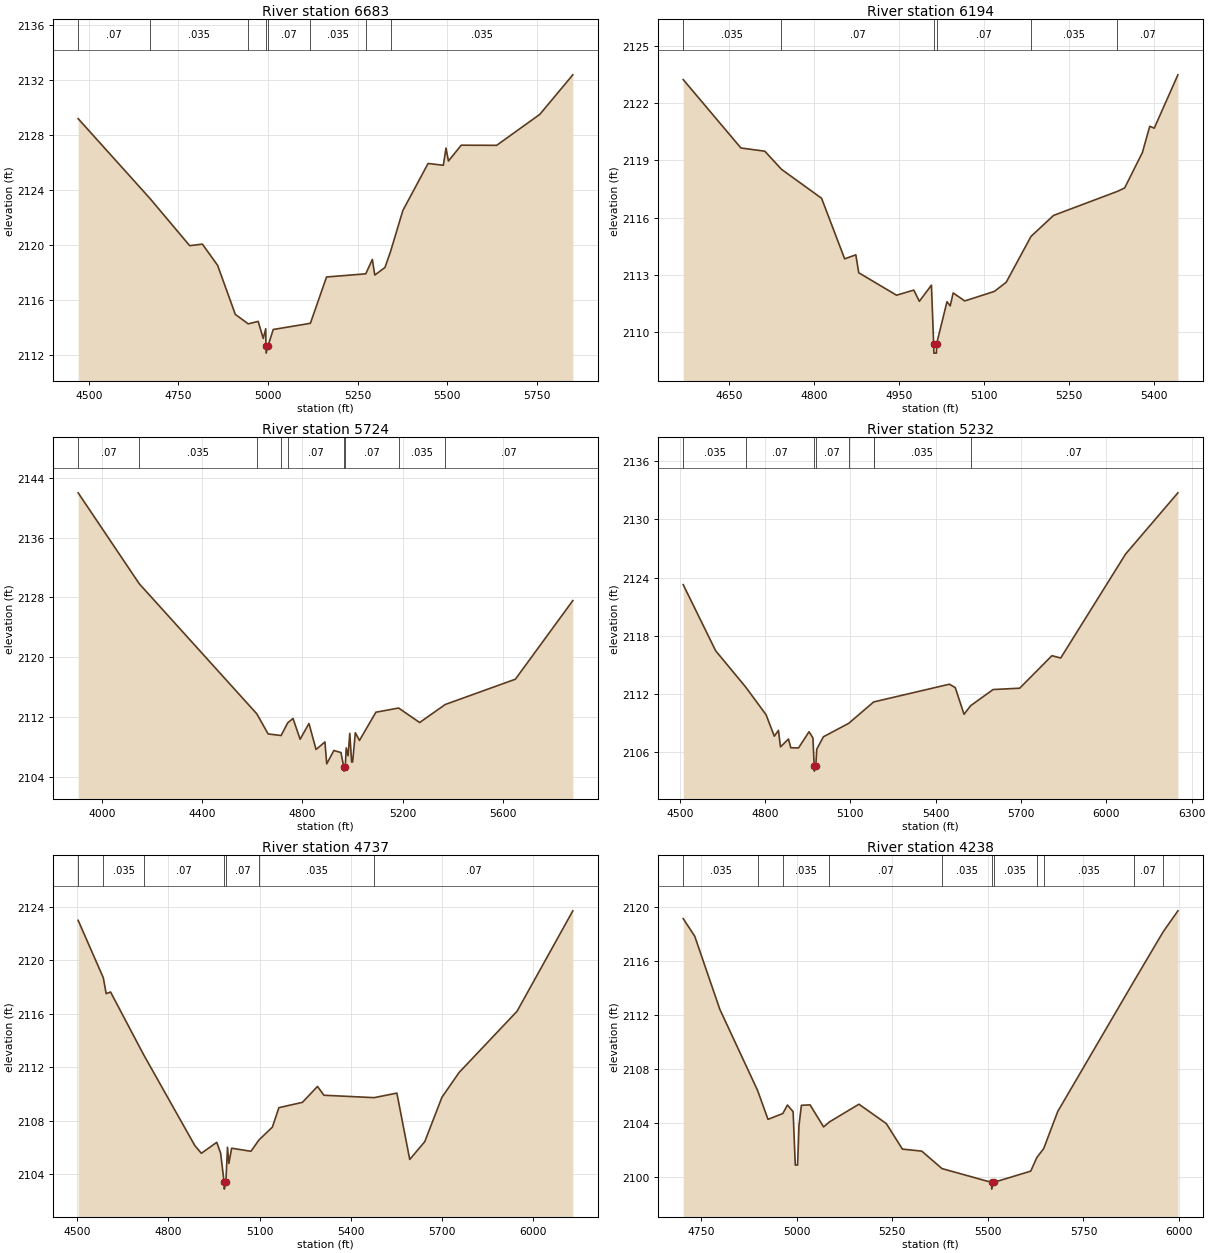
Type RM Length L Ch R = 1,6683,489,489,489
BEGIN DESCRIPTION:
Cottonwood Creek Trib081 6.0
END DESCRIPTION:
XS GIS Cut Line= 3
      1345505.01      6904138.01      1345884.49      6904507.71
      1346454.97      6905137.97
#Sta/Elev= 30
  4470.2 2129.22  4670.0 2123.43  4781.3 2119.98  4816.8 2120.09  4859.2 2118.55
  4908.6 2114.98  4944.6 2114.29  4972.4 2114.47  4986.5 2113.23  4993.5 2113.94
  4994.2 2112.66  4994.6 2112.16  4999.5 2112.66  5014.4 2113.88  5118.0 2114.33
  5163.1 2117.70  5272.5 2117.93  5290.9 2118.98  5297.6 2117.84  5326.0 2118.39
  5341.5 2119.54  5376.0 2122.54  5446.3 2125.96  5488.9 2125.83  5496.3 2127.08
  5503.1 2126.14  5538.9 2127.29  5637.6 2127.28  5757.9 2129.53  5850.1 2132.41
#Mann=8,-1,0
  4470.2    0.07       0  4670.0   0.035       0  4944.6    0.07       0
  4994.2    0.07       0  4999.5    0.07       0  5118.0   0.035       0
  5272.5    0.07       0  5341.5   0.035       0
Bank Sta=4994.2,4999.5
Exp/Cntr=0.3,0.1

Type RM Length L Ch R = 1,6194,470,470,470
BEGIN DESCRIPTION:
Cottonwood Creek Trib081 5.0
END DESCRIPTION:
XS GIS Cut Line= 3
      1345504.99      6904387.96      1345581.65      6904811.27
      1346004.99      6904938.00
#Sta/Elev= 30
  4569.8 2123.24  4671.5 2119.65  4713.7 2119.48  4743.0 2118.53  4813.7 2117.01
  4854.4 2113.83  4874.1 2114.04  4879.2 2113.10  4945.9 2111.92  4976.3 2112.19
  4986.1 2111.60  5007.4 2112.45  5011.3 2109.38  5011.7 2108.88  5016.2 2108.88
  5016.6 2109.38  5034.8 2111.58  5040.5 2111.36  5045.7 2112.04  5066.1 2111.62
  5118.3 2112.12  5139.2 2112.60  5183.0 2115.01  5222.7 2116.11  5335.1 2117.37
  5348.0 2117.55  5379.3 2119.41  5392.3 2120.79  5400.2 2120.69  5441.9 2123.49
#Mann=6,-1,0
  4569.8   0.035       0  4743.0    0.07       0  5011.3    0.07       0
  5016.6    0.07       0  5183.0   0.035       0  5335.1    0.07       0
Bank Sta=5011.3,5016.6
Exp/Cntr=0.3,0.1

Type RM Length L Ch R = 1,5724,492,492,492
BEGIN DESCRIPTION:
Cottonwood Creek Trib081 4.0
END DESCRIPTION:
XS GIS Cut Line= 3
      1344554.99      6904337.99      1345299.97      6905138.87
      1346105.02      6905488.01
#Sta/Elev= 30
  3906.2 2142.01  4149.6 2129.84  4618.3 2112.41  4663.3 2109.72  4714.9 2109.51
  4741.6 2111.22  4762.5 2111.79  4790.8 2109.01  4826.0 2111.12  4854.3 2107.64
  4889.6 2108.65  4896.8 2105.72  4925.2 2107.50  4953.5 2107.23  4965.0 2105.24
  4965.4 2104.74  4970.4 2105.24  4974.5 2107.85  4981.8 2106.79  4988.7 2109.80
  4996.0 2105.96  5000.0 2105.96  5010.7 2109.88  5027.3 2108.85  5092.7 2112.63
  5183.3 2113.19  5267.1 2111.25  5368.8 2113.66  5648.6 2117.05  5877.5 2127.58
#Mann=9,-1,0
  3906.2    0.07       0  4149.6   0.035       0  4618.3    0.07       0
  4714.9   0.035       0  4741.6    0.07       0  4965.0    0.07       0
  4970.4    0.07       0  5183.3   0.035       0  5368.8    0.07       0
Bank Sta=4965,4970.4
Exp/Cntr=0.3,0.1

Type RM Length L Ch R = 1,5232,495,495,495
BEGIN DESCRIPTION:
Cottonwood Creek Trib081 3.0
END DESCRIPTION:
XS GIS Cut Line= 3
      1344605.01      6904988.01      1344989.91      6905287.53
      1346205.01      6905588.00
#Sta/Elev= 30
  4512.3 2123.27  4626.3 2116.46  4732.1 2112.71  4803.7 2109.86  4832.6 2107.65
  4847.1 2108.25  4854.4 2106.55  4882.4 2107.36  4890.5 2106.46  4917.8 2106.44
  4954.7 2108.11  4968.4 2107.47  4972.8 2104.55  4973.3 2104.05  4978.3 2104.55
  4981.9 2106.32  5005.2 2107.59  5094.3 2108.98  5182.3 2111.19  5183.1 2111.19
  5448.2 2113.01  5468.8 2112.66  5499.7 2109.91  5522.7 2110.79  5601.8 2112.46
  5695.4 2112.60  5808.7 2115.95  5839.6 2115.71  6067.8 2126.43  6251.7 2132.74
#Mann=8,-1,0
  4512.3   0.035       0  4732.1    0.07       0  4972.8    0.07       0
  4978.3    0.07       0  5094.3   0.035       0  5182.3    0.07       0
  5183.1   0.035       0  5522.7    0.07       0
Bank Sta=4972.8,4978.3
Exp/Cntr=0.3,0.1

Type RM Length L Ch R = 1,4737,499,499,499
BEGIN DESCRIPTION:
Cottonwood Creek Trib081 2.0
END DESCRIPTION:
XS GIS Cut Line= 3
      1344354.98      6905337.98      1344747.19      6905644.21
      1345554.97      6906437.97
#Sta/Elev= 30
  4502.4 2122.98  4585.4 2118.68  4594.7 2117.50  4609.2 2117.62  4718.0 2112.94
  4886.8 2106.14  4908.4 2105.56  4959.2 2106.38  4971.9 2105.57  4983.5 2103.38
  4984.0 2102.88  4989.1 2103.38  4994.5 2106.01  4999.0 2104.80  5008.2 2105.94
  5071.8 2105.71  5098.4 2106.56  5142.5 2107.52  5163.8 2108.97  5241.5 2109.37
  5291.1 2110.56  5312.3 2109.90  5477.6 2109.72  5552.7 2110.06  5595.1 2105.10
  5644.6 2106.43  5701.2 2109.75  5757.7 2111.60  5948.7 2116.18  6132.5 2123.69
#Mann=7,-1,0
  4502.4    0.07       0  4585.4   0.035       0  4718.0    0.07       0
  4983.5    0.07       0  4989.1    0.07       0  5098.4   0.035       0
  5477.6    0.07       0
Bank Sta=4983.5,4989.1
Exp/Cntr=0.3,0.1

Type RM Length L Ch R = 1,4238,0,0,0
BEGIN DESCRIPTION:
Cottonwood Creek Trib081 1.0
END DESCRIPTION:
XS GIS Cut Line= 3
      1344204.99      6905637.98      1344345.46      6905899.10
      1344954.97      6906687.96
#Sta/Elev= 30
  4703.5 2119.14  4733.5 2117.85  4799.3 2112.43  4898.2 2106.42  4925.1 2104.30
  4963.9 2104.73  4976.0 2105.36  4990.8 2104.87  4996.5 2100.92  5002.5 2100.92
  5006.2 2103.85  5012.5 2105.34  5035.2 2105.37  5070.5 2103.74  5085.8 2104.11
  5162.9 2105.42  5234.4 2103.99  5276.6 2102.10  5327.2 2101.95  5380.0 2100.66
  5509.6 2099.64  5510.1 2099.14  5515.2 2099.64  5612.1 2100.47  5627.9 2101.47
  5646.0 2102.14  5682.7 2104.88  5880.8 2114.46  5958.2 2118.16  5996.9 2119.72
#Mann=11,-1,0
  4703.5   0.035       0  4898.2    0.07       0  4963.9   0.035       0
  5085.8    0.07       0  5380.0   0.035       0  5509.6   0.035       0
  5515.2   0.035       0  5627.9    0.07       0  5646.0   0.035       0
  5880.8    0.07       0  5958.2   0.035       0
Bank Sta=5509.6,5515.2
Exp/Cntr=0.3,0.1

Chan Stop Cuts=-1