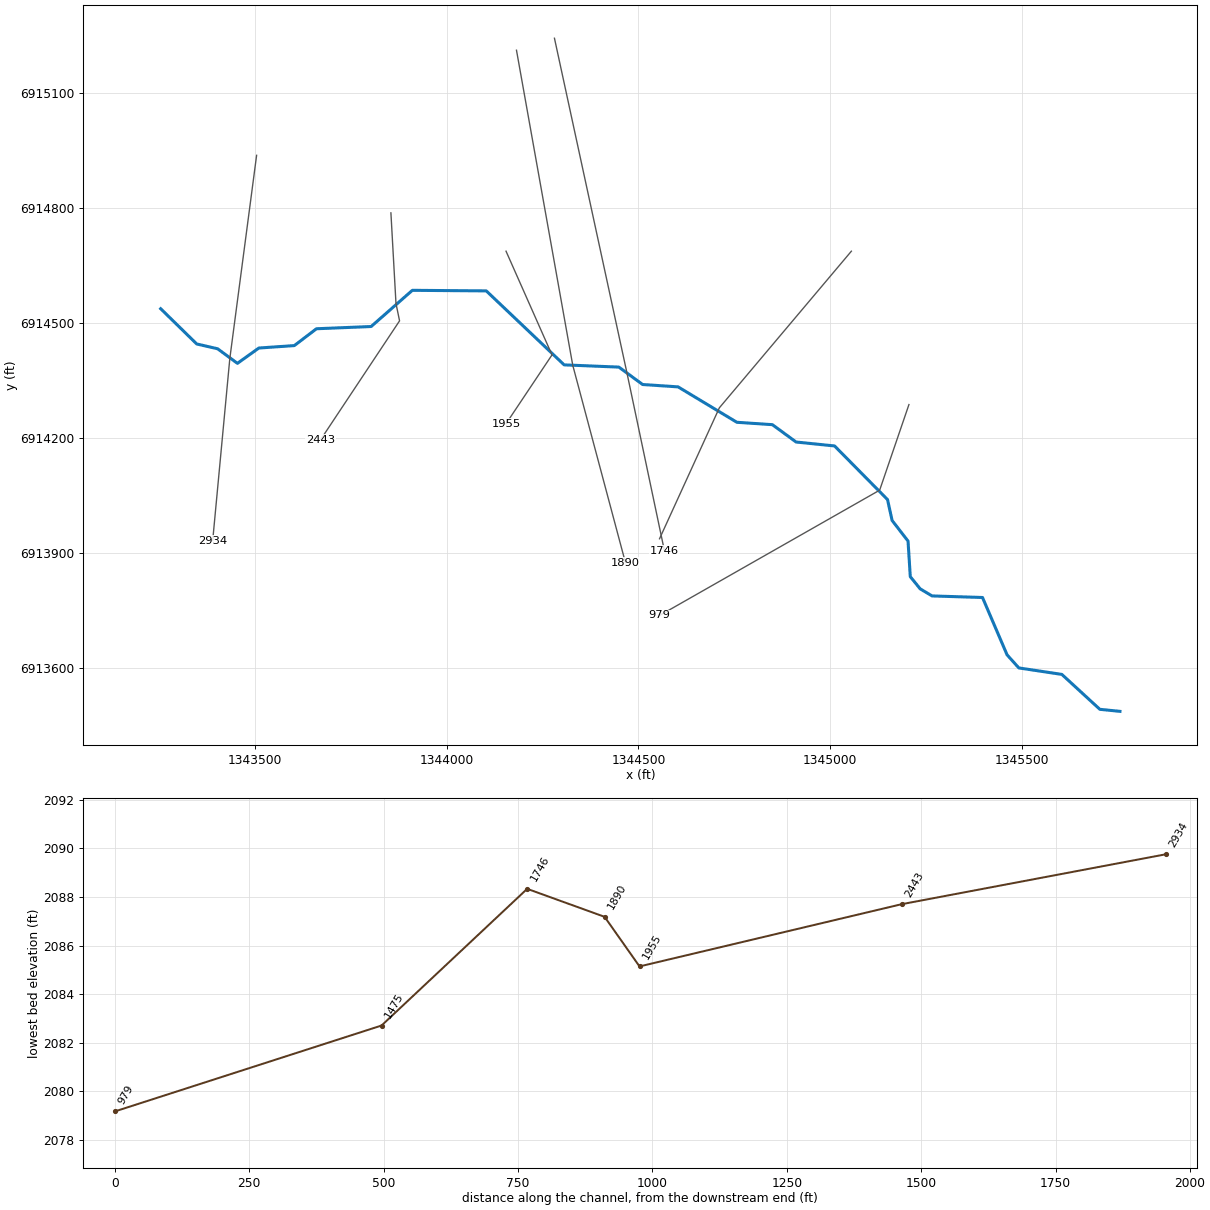
--- Cottonwood Creek Trib083.prj (project) ---

Proj Title=Cottonwood Creek Trib083 Base Level Engineering
Current Plan=p01
Default Exp/Contr=0.3,0.1
English Units
Geom File=g01
Flow File=f01
Plan File=p01
BEGIN DESCRIPTION:
Cottonwood Creek Trib083
END DESCRIPTION:

--- Cottonwood Creek Trib083.p01 (plan) ---

Plan Title=Multiple Run
Short Identifier=Multiple
Geom File=g01
Flow File=f01
Subcritical Flow
K Sum by GR= 0
Std Step Tol= 0.01
Critical Tol= 0.01
Num of Std Step Trials= 20
Max Error Tol= 0.3
Flow Tol Ratio= 0.001
Split Flow NTrial= 30
Split Flow Tol= 0.02
Split Flow Ratio= 0.02
Log Output Level= 0
Friction Slope Method= 1
Unsteady Friction Slope Method= 2
Unsteady Bridges Friction Slope Method= 1
Parabolic Critical Depth
Global Vel Dist=  1 , 1 , 1
Global Log Level= 0
CheckData=True
Encroach Param= -1, 0, 0, 0
BEGIN DESCRIPTION:
Multiple Run
END DESCRIPTION:

--- Cottonwood Creek Trib083.f01 (steady flow) ---

Flow Title=Multiple
Number of Profiles=7
Profile Names=10-year,25-year,50-year,1pct_min,100-year,1pct_plu,500-year
River Rch & RM= Cottonwood Creek,Reach-1,2934
     309     445     562     353     704    1405    1122
River Rch & RM= Cottonwood Creek,Reach-1,1746
     334     483     610     384     766    1529    1224
Boundary for River Rch & Prof#=Cottonwood Creek,Reach-1,1
Up Type=0
Dn Type=3
Dn Slope=0.005
Boundary for River Rch & Prof#=Cottonwood Creek,Reach-1,2
Up Type=0
Dn Type=3
Dn Slope=0.005
Boundary for River Rch & Prof#=Cottonwood Creek,Reach-1,3
Up Type=0
Dn Type=3
Dn Slope=0.005
Boundary for River Rch & Prof#=Cottonwood Creek,Reach-1,4
Up Type=0
Dn Type=3
Dn Slope=0.005
Boundary for River Rch & Prof#=Cottonwood Creek,Reach-1,5
Up Type=0
Dn Type=3
Dn Slope=0.005
Boundary for River Rch & Prof#=Cottonwood Creek,Reach-1,6
Up Type=0
Dn Type=3
Dn Slope=0.005
Boundary for River Rch & Prof#=Cottonwood Creek,Reach-1,7
Up Type=0
Dn Type=3
Dn Slope=0.005

--- Cottonwood Creek Trib083.g01 (geometry) ---

Geom Title=Existing Conditions

River Reach=Cottonwood Creek,Reach-1
Reach XY= 30
      1343255.00      6914538.00      1343348.93      6914446.06
      1343403.35      6914433.55      1343454.99      6914395.53
      1343510.89      6914435.45      1343603.40      6914441.85
      1343660.94      6914485.73      1343803.53      6914491.56
      1343910.86      6914585.94      1344103.54      6914584.47
      1344306.47      6914391.54      1344449.06      6914385.73
      1344510.98      6914340.36      1344603.42      6914334.17
      1344756.58      6914241.83      1344849.03      6914235.65
      1344910.98      6914190.36      1345011.17      6914180.14
      1345149.17      6914040.30      1345161.14      6913985.83
      1345202.66      6913932.03      1345208.51      6913839.25
      1345234.36      6913807.41      1345265.28      6913789.00
      1345396.72      6913784.93      1345460.72      6913635.42
      1345491.34      6913601.26      1345603.50      6913584.38
      1345702.49      6913493.33      1345755.00      6913488.00

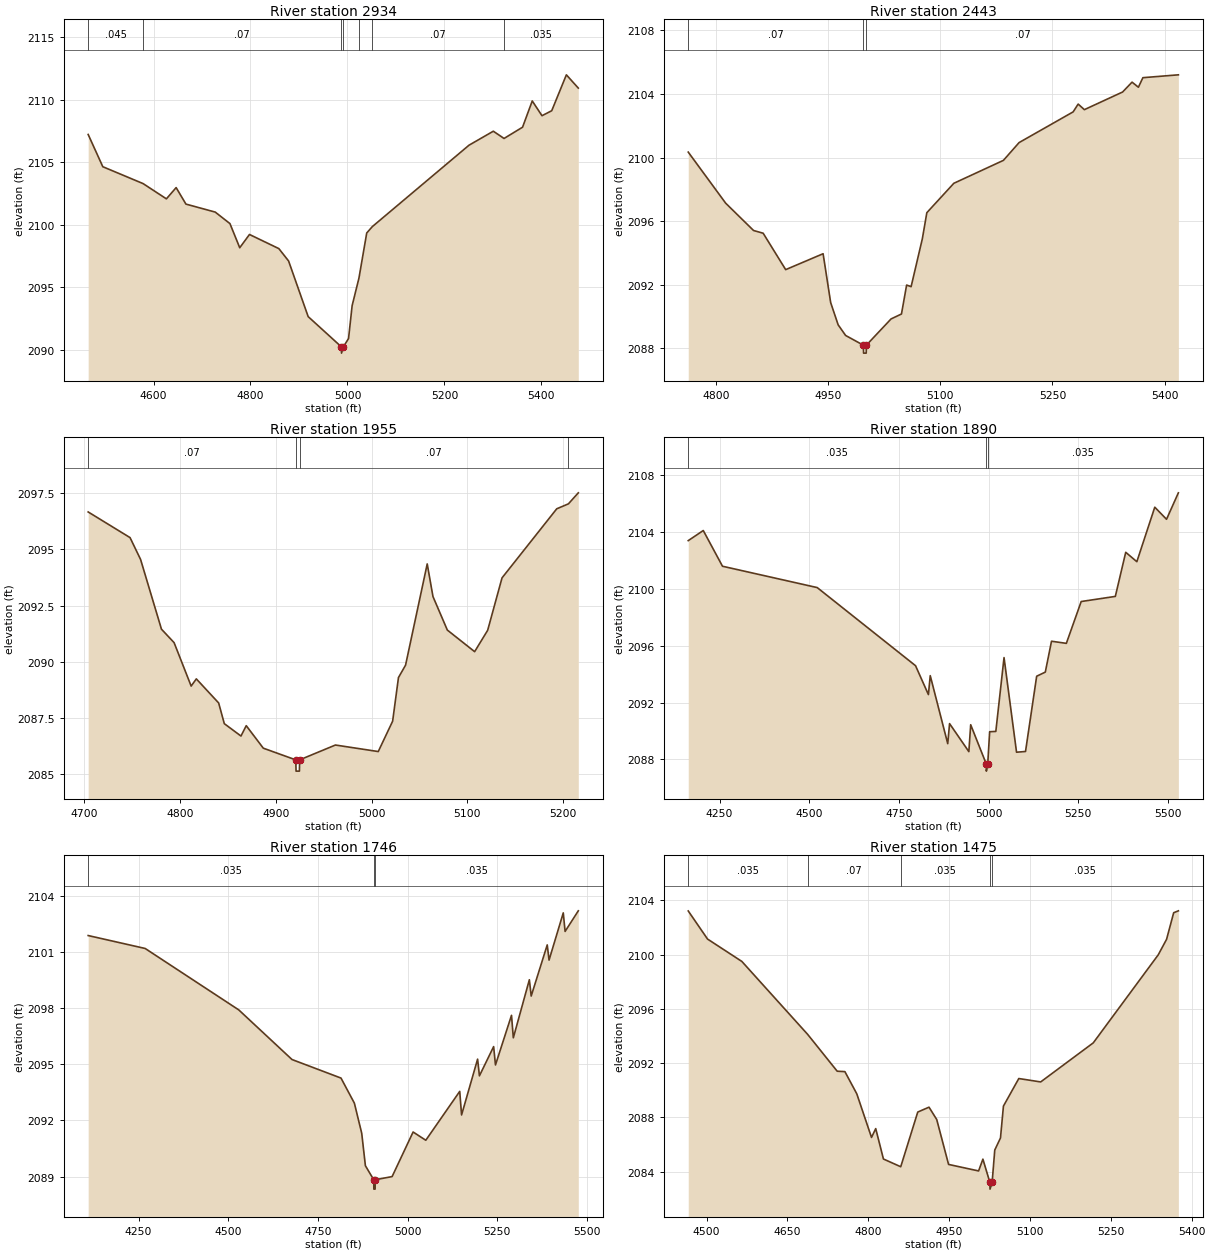
Type RM Length L Ch R = 1,2934,491,491,491
BEGIN DESCRIPTION:
Cottonwood Creek Trib083 5.0
END DESCRIPTION:
XS GIS Cut Line= 3
      1343505.00      6914937.99      1343435.13      6914407.67
      1343390.57      6913933.46
#Sta/Elev= 30
  4465.1 2107.24  4495.3 2104.66  4578.4 2103.31  4626.5 2102.09  4646.6 2102.99
  4666.8 2101.67  4727.3 2101.03  4757.6 2100.11  4777.8 2098.18  4797.9 2099.24
  4858.5 2098.11  4878.6 2097.12  4919.0 2092.67  4987.6 2090.25  4987.8 2089.75
  4991.6 2090.25  5002.3 2090.92  5009.7 2093.55  5023.8 2095.76  5039.8 2099.36
  5051.4 2099.87  5250.8 2106.38  5301.0 2107.50  5323.1 2106.92  5361.3 2107.82
  5381.3 2109.92  5401.4 2108.74  5421.5 2109.14  5451.7 2112.01  5476.3 2110.95
#Mann=7,-1,0
  4465.1   0.045       0  4578.4    0.07       0  4987.6    0.07       0
  4991.6    0.07       0  5023.8    0.16       0  5051.4    0.07       0
  5323.1   0.035       0
Bank Sta=4987.6,4991.6
Exp/Cntr=0.3,0.1

Type RM Length L Ch R = 1,2443,488,488,488
BEGIN DESCRIPTION:
Cottonwood Creek Trib083 4.0
END DESCRIPTION:
XS GIS Cut Line= 4
      1343855.00      6914787.97      1343868.21      6914551.64
      1343877.55      6914506.37      1343671.81      6914196.46
#Sta/Elev= 30
  4763.3 2100.34  4813.3 2097.13  4850.6 2095.41  4863.4 2095.24  4893.5 2092.95
  4943.5 2093.95  4953.6 2090.88  4963.6 2089.48  4973.6 2088.81  4997.3 2088.20
  4997.6 2087.70  5001.1 2087.70  5001.3 2088.20  5034.3 2089.85  5048.2 2090.16
  5055.1 2091.98  5061.1 2091.88  5076.1 2094.89  5082.1 2096.53  5118.2 2098.38
  5184.4 2099.82  5205.4 2100.94  5277.6 2102.87  5284.3 2103.36  5292.6 2103.01
  5343.7 2104.12  5356.3 2104.74  5364.8 2104.42  5370.8 2105.02  5418.2 2105.20
#Mann=3,-1,0
  4763.3    0.07       0  4997.3    0.07       0  5001.3    0.07       0
Bank Sta=4997.3,5001.3
Exp/Cntr=0.3,0.1

Type RM Length L Ch R = 1,1955,65,65,65
BEGIN DESCRIPTION:
Cottonwood Creek Trib083 3.0
END DESCRIPTION:
XS GIS Cut Line= 3
      1344155.01      6914687.97      1344274.80      6914417.51
      1344155.01      6914238.01
#Sta/Elev= 30
  4704.2 2096.66  4747.9 2095.52  4758.9 2094.55  4780.7 2091.45  4793.9 2090.85
  4811.7 2088.92  4817.1 2089.24  4840.4 2088.17  4846.3 2087.25  4863.7 2086.70
  4869.2 2087.16  4887.0 2086.16  4920.9 2085.64  4921.2 2085.14  4924.7 2085.14
  4924.9 2085.64  4962.3 2086.30  5007.0 2086.01  5022.0 2087.36  5028.1 2089.30
  5035.5 2089.85  5058.1 2094.35  5064.1 2092.90  5079.1 2091.41  5107.6 2090.45
  5121.2 2091.40  5136.2 2093.73  5193.3 2096.80  5205.5 2097.02  5215.8 2097.51
#Mann=4,-1,0
  4704.2    0.07       0  4920.9    0.07       0  4924.9    0.07       0
  5205.5   0.035       0
Bank Sta=4920.9,4924.9
Exp/Cntr=0.3,0.1

Type RM Length L Ch R = 1,1890,144,144,144
BEGIN DESCRIPTION:
Cottonwood Creek Trib083 2.6
END DESCRIPTION:
XS GIS Cut Line= 3
      1344182.24      6915212.06      1344328.85      6914390.66
      1344466.10      6913876.13
#Sta/Elev= 30
  4162.6 2103.38  4204.5 2104.09  4258.1 2101.58  4522.3 2100.08  4796.5 2094.59
  4832.4 2092.56  4837.5 2093.89  4886.3 2089.11  4891.4 2090.52  4945.2 2088.55
  4950.3 2090.44  4993.8 2087.68  4994.0 2087.18  4997.8 2087.68  5003.2 2089.95
  5020.4 2089.97  5043.3 2095.16  5078.2 2088.51  5103.2 2088.56  5134.3 2093.85
  5158.4 2094.14  5175.7 2096.31  5217.1 2096.16  5258.5 2099.10  5353.7 2099.46
  5382.7 2102.56  5413.7 2101.90  5463.7 2105.73  5496.5 2104.88  5529.5 2106.74
#Mann=3,-1,0
  4162.6   0.035       0  4993.8   0.035       0  4997.8   0.035       0
Bank Sta=4993.8,4997.8
Exp/Cntr=0.3,0.1

Type RM Length L Ch R = 1,1746,271,271,271
BEGIN DESCRIPTION:
Cottonwood Creek Trib083 2.5
END DESCRIPTION:
XS GIS Cut Line= 3
      1344281.20      6915243.32      1344470.11      6914370.63
      1344567.66      6913907.39
#Sta/Elev= 30
  4109.4 2101.87  4268.3 2101.18  4529.2 2097.90  4677.6 2095.25  4814.2 2094.26
  4851.5 2092.92  4872.0 2091.31  4882.2 2089.58  4905.5 2088.83  4905.8 2088.33
  4909.3 2088.33  4909.5 2088.83  4956.7 2089.00  5015.2 2091.38  5050.6 2090.94
  5145.2 2093.55  5150.3 2092.29  5195.0 2095.27  5200.1 2094.38  5239.7 2095.94
  5244.8 2094.96  5289.5 2097.61  5294.6 2096.41  5339.3 2099.51  5344.4 2098.64
  5389.1 2101.37  5394.2 2100.56  5433.8 2103.08  5438.9 2102.09  5475.7 2103.19
#Mann=3,-1,0
  4109.4   0.035       0  4905.5   0.035       0  4909.5   0.035       0
Bank Sta=4905.5,4909.5
Exp/Cntr=0.3,0.1

Type RM Length L Ch R = 1,1475,496,496,496
BEGIN DESCRIPTION:
Cottonwood Creek Trib083 2.0
END DESCRIPTION:
XS GIS Cut Line= 3
      1345055.02      6914688.02      1344710.92      6914279.53
      1344555.02      6913938.04
#Sta/Elev= 30
  4465.9 2103.21  4501.7 2101.14  4565.4 2099.49  4687.6 2094.11  4742.3 2091.40
  4756.6 2091.37  4778.7 2089.73  4806.0 2086.52  4813.8 2087.17  4828.1 2084.93
  4860.2 2084.36  4891.8 2088.39  4912.7 2088.75  4927.0 2087.84  4949.0 2084.53
  5004.7 2084.05  5012.7 2084.92  5025.6 2083.21  5025.9 2082.71  5029.8 2083.21
  5034.7 2085.59  5045.3 2086.48  5050.8 2088.83  5079.3 2090.86  5119.9 2090.61
  5217.5 2093.49  5338.1 2099.98  5353.5 2101.12  5366.7 2103.08  5375.4 2103.22
#Mann=5,-1,0
  4465.9   0.035       0  4687.6    0.07       0  4860.2   0.035       0
  5025.6   0.035       0  5029.8   0.035       0
Bank Sta=5025.6,5029.8
Exp/Cntr=0.3,0.1

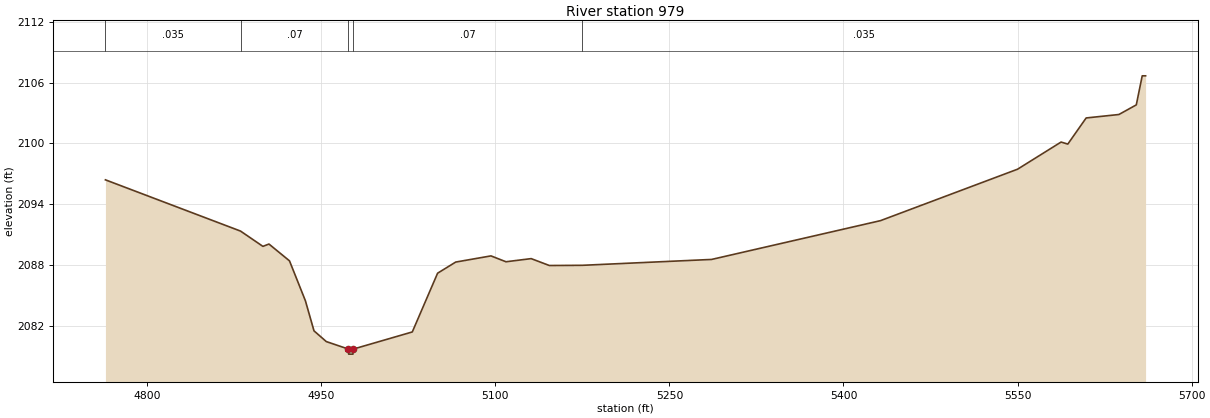
Type RM Length L Ch R = 1,979,0,0,0
BEGIN DESCRIPTION:
Cottonwood Creek Trib083 1.0
END DESCRIPTION:
XS GIS Cut Line= 3
      1345205.01      6914288.04      1345128.71      6914064.82
      1344554.97      6913737.99
#Sta/Elev= 30
  4764.1 2096.39  4880.5 2091.33  4899.8 2089.82  4905.0 2090.05  4922.7 2088.39
  4936.4 2084.45  4943.8 2081.48  4954.4 2080.42  4973.4 2079.68  4973.7 2079.18
  4977.4 2079.18  4977.7 2079.68  5028.5 2081.37  5050.3 2087.17  5065.9 2088.27
  5096.3 2088.88  5109.2 2088.30  5130.9 2088.61  5146.6 2087.93  5175.1 2087.95
  5286.4 2088.53  5431.9 2092.36  5550.0 2097.44  5587.5 2100.12  5593.3 2099.92
  5609.1 2102.50  5637.3 2102.84  5652.3 2103.79  5657.4 2106.66  5660.3 2106.66
#Mann=5,-1,0
  4764.1   0.035       0  4880.5    0.07       0  4973.4    0.07       0
  4977.7    0.07       0  5175.1   0.035       0
Bank Sta=4973.4,4977.7
Exp/Cntr=0.3,0.1

Chan Stop Cuts=-1