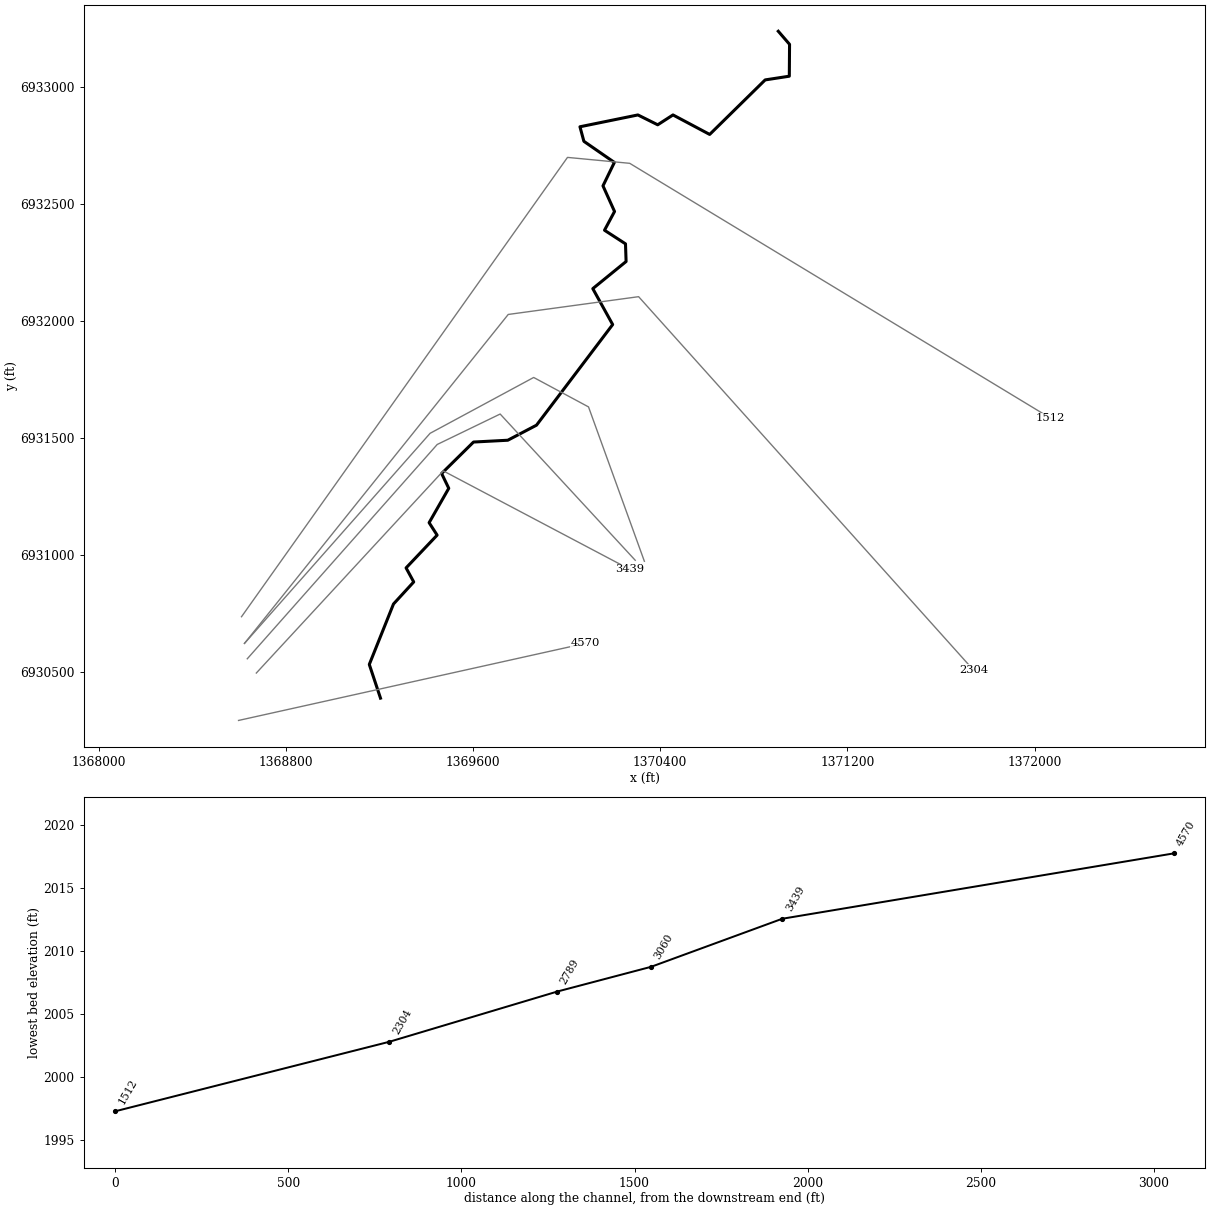
--- Cottonwood Creek Trib117.prj (project) ---

Proj Title=Cottonwood Creek Trib117 Base Level Engineering
Current Plan=p01
Default Exp/Contr=0.3,0.1
English Units
Geom File=g01
Flow File=f01
Plan File=p01
BEGIN DESCRIPTION:
Cottonwood Creek Trib117
END DESCRIPTION:

--- Cottonwood Creek Trib117.p01 (plan) ---

Plan Title=Multiple Run
Short Identifier=Multiple
Geom File=g01
Flow File=f01
Subcritical Flow
K Sum by GR= 0
Std Step Tol= 0.01
Critical Tol= 0.01
Num of Std Step Trials= 20
Max Error Tol= 0.3
Flow Tol Ratio= 0.001
Split Flow NTrial= 30
Split Flow Tol= 0.02
Split Flow Ratio= 0.02
Log Output Level= 0
Friction Slope Method= 1
Unsteady Friction Slope Method= 2
Unsteady Bridges Friction Slope Method= 1
Parabolic Critical Depth
Global Vel Dist=  1 , 1 , 1
Global Log Level= 0
CheckData=True
Encroach Param= -1, 0, 0, 0
BEGIN DESCRIPTION:
Multiple Run
END DESCRIPTION:

--- Cottonwood Creek Trib117.f01 (steady flow) ---

Flow Title=Multiple
Number of Profiles=7
Profile Names=10-year,25-year,50-year,1pct_min,100-year,1pct_plu,500-year
River Rch & RM= Cottonwood Creek,Reach-1,4570
     254     358     445     275     549    1096     847
Boundary for River Rch & Prof#=Cottonwood Creek,Reach-1,1
Up Type=0
Dn Type=3
Dn Slope=0.005
Boundary for River Rch & Prof#=Cottonwood Creek,Reach-1,2
Up Type=0
Dn Type=3
Dn Slope=0.005
Boundary for River Rch & Prof#=Cottonwood Creek,Reach-1,3
Up Type=0
Dn Type=3
Dn Slope=0.005
Boundary for River Rch & Prof#=Cottonwood Creek,Reach-1,4
Up Type=0
Dn Type=3
Dn Slope=0.005
Boundary for River Rch & Prof#=Cottonwood Creek,Reach-1,5
Up Type=0
Dn Type=3
Dn Slope=0.005
Boundary for River Rch & Prof#=Cottonwood Creek,Reach-1,6
Up Type=0
Dn Type=3
Dn Slope=0.005
Boundary for River Rch & Prof#=Cottonwood Creek,Reach-1,7
Up Type=0
Dn Type=3
Dn Slope=0.005

--- Cottonwood Creek Trib117.g01 (geometry) ---

Geom Title=Existing Conditions

River Reach=Cottonwood Creek,Reach-1
Reach XY= 30
      1369205.00      6930388.00      1369157.13      6930532.05
      1369260.55      6930790.43      1369346.98      6930884.67
      1369314.30      6930944.67      1369447.01      6931084.66
      1369412.78      6931137.91      1369496.75      6931284.77
      1369466.24      6931348.00      1369602.55      6931482.53
      1369749.07      6931490.25      1369871.71      6931554.63
      1370197.22      6931984.60      1370112.28      6932138.10
      1370254.54      6932254.02      1370252.01      6932329.57
      1370162.29      6932387.71      1370205.19      6932467.79
      1370155.79      6932577.32      1370204.46      6932677.53
      1370074.18      6932767.72      1370057.41      6932829.86
      1370305.01      6932880.41      1370389.64      6932838.29
      1370455.00      6932880.44      1370611.73      6932797.11
      1370848.88      6933030.12      1370952.08      6933045.97
      1370953.13      6933182.20      1370905.00      6933238.00

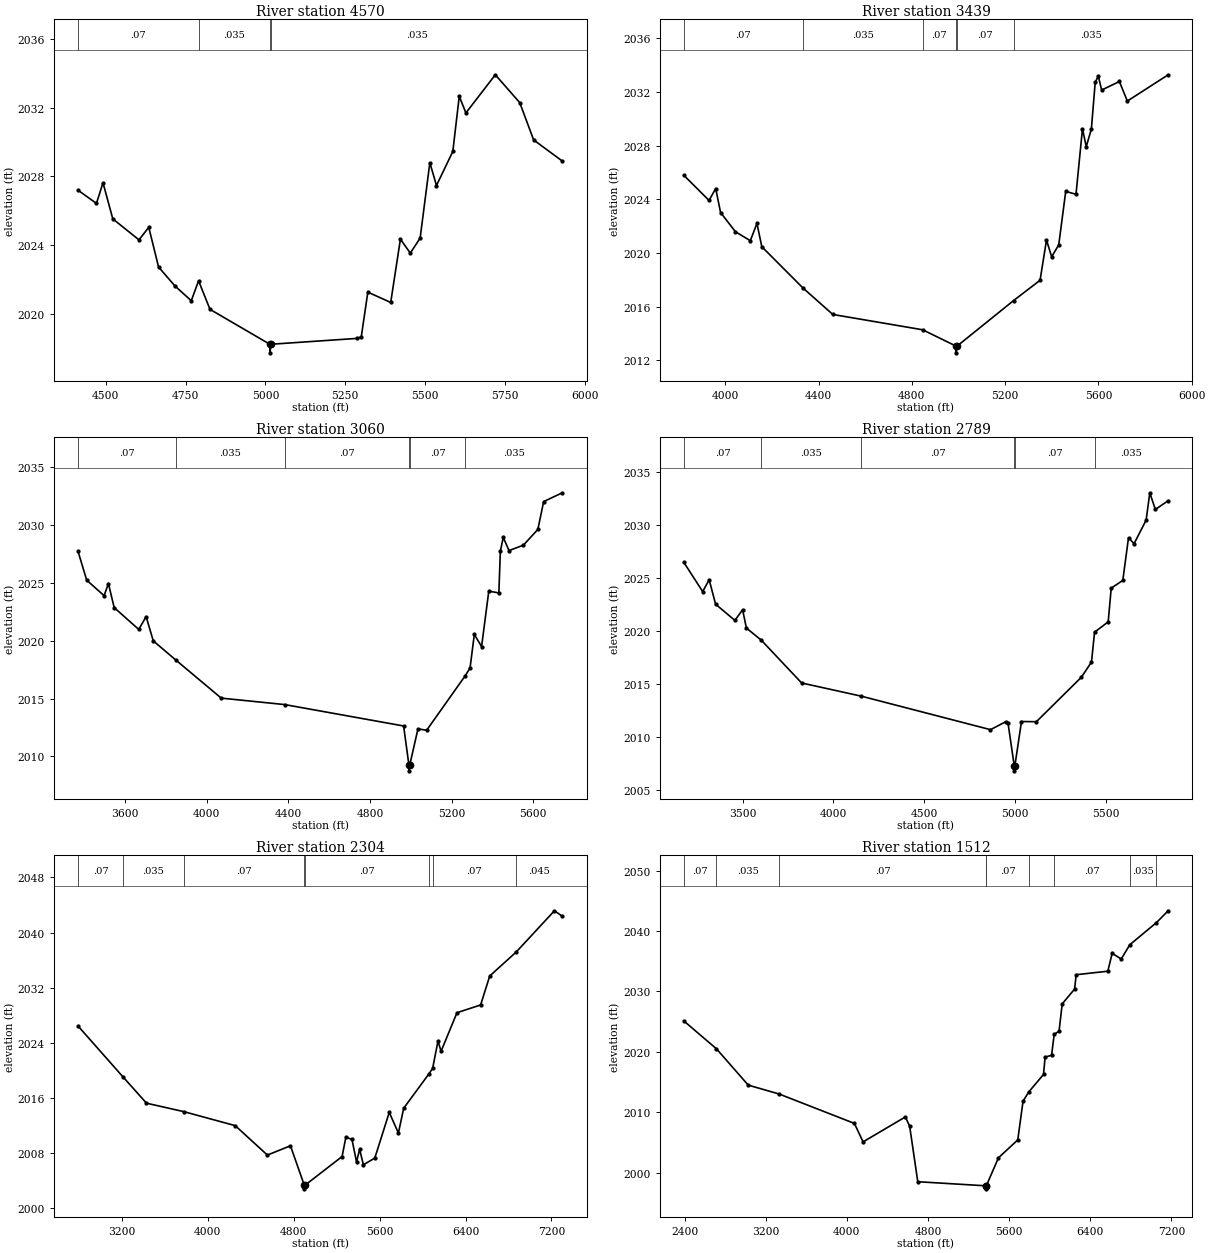
Type RM Length L Ch R = 1,4570,1131,1131,1131
BEGIN DESCRIPTION:
Cottonwood Creek Trib117 4.0
END DESCRIPTION:
XS GIS Cut Line= 2
      1368598.37      6930292.75      1370080.03      6930622.01
#Sta/Elev= 30
  4412.6 2027.20  4470.6 2026.43  4491.1 2027.63  4521.8 2025.53  4603.8 2024.31
  4634.5 2025.04  4665.2 2022.73  4716.5 2021.63  4767.7 2020.77  4790.6 2021.93
  4826.3 2020.27  5013.8 2018.24  5014.1 2017.74  5017.8 2018.24  5287.3 2018.58
  5300.4 2018.67  5320.9 2021.27  5392.6 2020.67  5423.0 2024.35  5454.0 2023.54
  5484.8 2024.41  5515.2 2028.80  5536.0 2027.47  5587.2 2029.45  5607.4 2032.66
  5628.2 2031.69  5720.4 2033.91  5796.9 2032.29  5840.5 2030.12  5930.4 2028.89
#Mann=4,-1,0
  4412.6    0.07       0  4790.6   0.035       0  5013.8   0.035       0
  5017.8   0.035       0
Bank Sta=5013.8,5017.8
Exp/Cntr=0.3,0.1

Type RM Length L Ch R = 1,3439,379,379,379
BEGIN DESCRIPTION:
Cottonwood Creek Trib117 3.0
END DESCRIPTION:
XS GIS Cut Line= 3
      1368674.38      6930495.39      1369473.33      6931359.21
      1370270.00      6930938.68
#Sta/Elev= 30
  3821.7 2025.80  3930.2 2023.92  3958.6 2024.81  3979.6 2023.02  4043.2 2021.59
  4107.1 2020.92  4135.5 2022.21  4156.5 2020.47  4333.2 2017.39  4461.0 2015.42
  4846.0 2014.28  4989.7 2013.06  4989.9 2012.56  4993.7 2013.06  5236.4 2016.46
  5349.8 2017.97  5377.4 2020.97  5399.5 2019.72  5429.9 2020.61  5459.9 2024.60
  5503.9 2024.38  5531.7 2029.27  5547.9 2027.93  5569.9 2029.25  5586.3 2032.72
  5599.5 2033.19  5614.0 2032.15  5690.0 2032.79  5724.1 2031.33  5899.2 2033.29
#Mann=6,-1,0
  3821.7    0.07       0  4333.2   0.035       0  4846.0    0.07       0
  4989.7    0.07       0  4993.7    0.07       0  5236.4   0.035       0
Bank Sta=4989.7,4993.7
Exp/Cntr=0.3,0.1

Type RM Length L Ch R = 1,3060,271,271,271
BEGIN DESCRIPTION:
Cottonwood Creek Trib117 2.6
END DESCRIPTION:
XS GIS Cut Line= 4
      1368635.66      6930556.26      1369447.29      6931472.06
      1369716.38      6931602.26      1370293.62      6930977.28
#Sta/Elev= 30
  3368.6 2027.76  3411.5 2025.24  3496.8 2023.90  3517.9 2024.95  3546.1 2022.87
  3666.6 2020.98  3702.6 2022.09  3737.7 2019.99  3849.7 2018.31  4070.6 2015.04
  4382.0 2014.48  4964.3 2012.63  4990.3 2009.25  4990.6 2008.75  4994.3 2009.25
  5034.6 2012.38  5077.1 2012.26  5266.9 2016.99  5289.8 2017.65  5310.7 2020.55
  5346.3 2019.50  5381.6 2024.29  5430.9 2024.14  5438.3 2027.74  5452.5 2028.94
  5480.8 2027.80  5551.2 2028.27  5622.0 2029.63  5650.4 2032.04  5742.0 2032.80
#Mann=6,-1,0
  3368.6    0.07       0  3849.7   0.035       0  4382.0    0.07       0
  4990.3    0.07       0  4994.3    0.07       0  5266.9   0.035       0
Bank Sta=4990.3,4994.3
Exp/Cntr=0.3,0.1

Type RM Length L Ch R = 1,2789,485,485,485
BEGIN DESCRIPTION:
Cottonwood Creek Trib117 2.5
END DESCRIPTION:
XS GIS Cut Line= 5
      1368623.71      6930622.02      1369416.91      6931519.80
      1369859.61      6931758.51      1370093.99      6931632.65
      1370332.68      6930972.99
#Sta/Elev= 30
  3176.1 2026.45  3280.2 2023.69  3316.2 2024.80  3351.3 2022.50  3457.5 2020.97
  3500.2 2021.97  3521.1 2020.25  3602.9 2019.11  3825.6 2015.07  4153.7 2013.83
  4865.8 2010.67  4948.9 2011.41  4962.6 2011.27  4996.4 2007.29  4996.6 2006.79
  5000.4 2007.29  5036.5 2011.44  5118.5 2011.42  5366.3 2015.61  5422.2 2017.04
  5439.1 2019.86  5514.2 2020.83  5530.9 2024.01  5594.7 2024.74  5626.1 2028.76
  5656.8 2028.20  5723.4 2030.43  5743.4 2033.00  5774.0 2031.43  5844.6 2032.25
#Mann=6,-1,0
  3176.1    0.07       0  3602.9   0.035       0  4153.7    0.07       0
  4996.4    0.07       0  5000.4    0.07       0  5439.1   0.035       0
Bank Sta=4996.4,5000.4
Exp/Cntr=0.3,0.1

Type RM Length L Ch R = 1,2304,792,792,792
BEGIN DESCRIPTION:
Cottonwood Creek Trib117 2.0
END DESCRIPTION:
XS GIS Cut Line= 4
      1368623.74      6930622.06      1369750.84      6932027.77
      1370308.08      6932103.76      1371739.15      6930508.04
#Sta/Elev= 30
  2793.4 2026.45  3215.7 2019.00  3431.2 2015.24  3776.8 2014.02  4257.0 2011.98
  4556.2 2007.71  4770.9 2009.06  4900.2 2003.31  4900.4 2002.81  4904.2 2003.31
  5251.5 2007.50  5286.6 2010.30  5343.4 2009.98  5386.0 2006.70  5414.4 2008.56
  5449.6 2006.30  5555.7 2007.27  5690.3 2013.90  5775.5 2010.91  5824.8 2014.51
  6059.3 2019.49  6093.8 2020.28  6144.1 2024.26  6172.5 2022.77  6320.5 2028.37
  6540.3 2029.49  6625.5 2033.70  6872.0 2037.18  7227.3 2043.16  7301.0 2042.37
#Mann=8,-1,0
  2793.4    0.07       0  3215.7   0.035       0  3776.8    0.07       0
  4900.2    0.07       0  4904.2    0.07       0  6059.3   0.035       0
  6093.8    0.07       0  6872.0   0.045       0
Bank Sta=4900.2,4904.2
Exp/Cntr=0.3,0.1

Type RM Length L Ch R = 1,1512,0,0,0
BEGIN DESCRIPTION:
Cottonwood Creek Trib117 1.0
END DESCRIPTION:
XS GIS Cut Line= 4
      1368611.03      6930735.98      1370004.13      6932698.98
      1370270.08      6932673.66      1372068.43      6931584.51
#Sta/Elev= 30
  2392.2 2025.12  2714.8 2020.49  3028.0 2014.48  3332.3 2013.01  4074.6 2008.14
  4160.5 2005.08  4577.4 2009.21  4619.8 2007.67  4699.8 1998.48  5371.4 1997.80
  5371.7 1997.30  5375.4 1997.80  5495.7 2002.45  5685.7 2005.40  5738.0 2011.83
  5794.3 2013.35  5939.8 2016.25  5955.3 2019.12  6019.3 2019.43  6045.1 2022.90
  6093.0 2023.41  6124.0 2027.94  6246.2 2030.39  6261.7 2032.77  6574.0 2033.35
  6616.6 2036.32  6705.8 2035.37  6790.3 2037.73  7053.3 2041.40  7168.9 2043.36
#Mann=9,-1,0
  2392.2    0.07       0  2714.8   0.035       0  3332.3    0.07       0
  5371.4    0.07       0  5375.4    0.07       0  5794.3   0.035       0
  6045.1    0.07       0  6790.3   0.035       0  7053.3    0.07       0
Bank Sta=5371.4,5375.4
Exp/Cntr=0.3,0.1

Chan Stop Cuts=-1