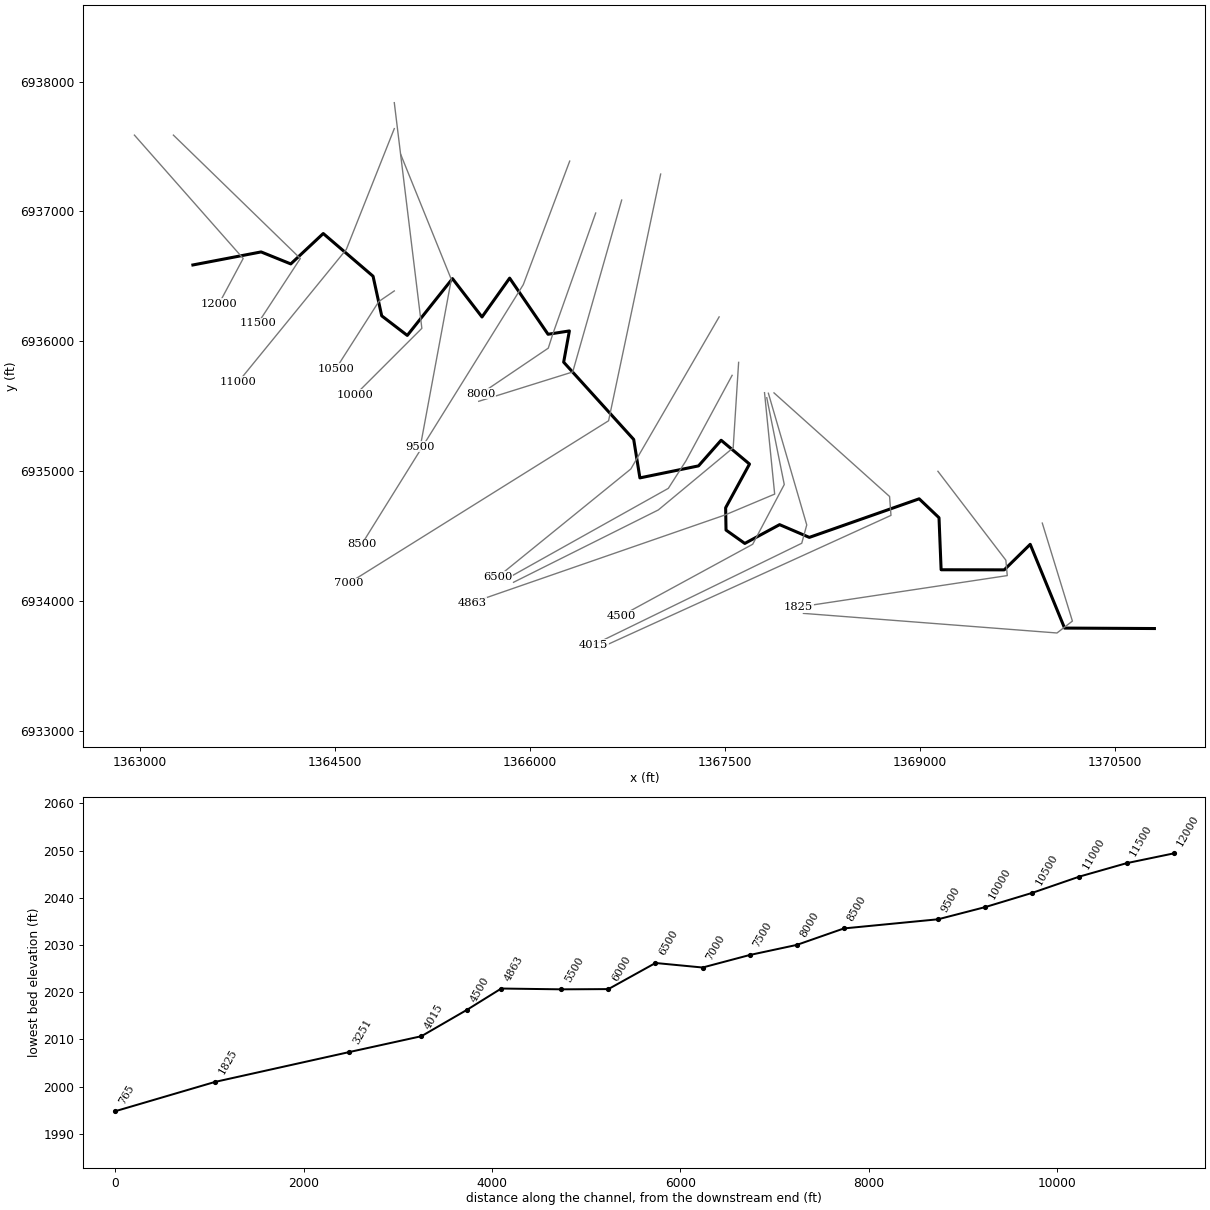
--- Cottonwood Creek Trib118.prj (project) ---

Proj Title=Cottonwood Creek Trib118 Base Level Engineering
Current Plan=p01
Default Exp/Contr=0.3,0.1
English Units
Geom File=g01
Flow File=f01
Plan File=p01
BEGIN DESCRIPTION:
Cottonwood Creek Trib118
END DESCRIPTION:

--- Cottonwood Creek Trib118.p01 (plan) ---

Plan Title=Multiple Run
Short Identifier=Multiple
Geom File=g01
Flow File=f01
Subcritical Flow
K Sum by GR= 0
Std Step Tol= 0.01
Critical Tol= 0.01
Num of Std Step Trials= 20
Max Error Tol= 0.3
Flow Tol Ratio= 0.001
Split Flow NTrial= 30
Split Flow Tol= 0.02
Split Flow Ratio= 0.02
Log Output Level= 0
Friction Slope Method= 1
Unsteady Friction Slope Method= 2
Unsteady Bridges Friction Slope Method= 1
Parabolic Critical Depth
Global Vel Dist=  1 , 1 , 1
Global Log Level= 0
CheckData=True
Encroach Param= -1, 0, 0, 0
BEGIN DESCRIPTION:
Multiple Run
END DESCRIPTION:

--- Cottonwood Creek Trib118.f01 (steady flow) ---

Flow Title=Multiple
Number of Profiles=7
Profile Names=10-year,25-year,50-year,1pct_min,100-year,1pct_plu,500-year
River Rch & RM= Cottonwood Creek,Reach-1,12000
     268     381     476     296     590    1177     919
River Rch & RM= Cottonwood Creek,Reach-1,11000
     382     549     691     432     863    1722    1363
Boundary for River Rch & Prof#=Cottonwood Creek,Reach-1,1
Up Type=0
Dn Type=3
Dn Slope=0.005
Boundary for River Rch & Prof#=Cottonwood Creek,Reach-1,2
Up Type=0
Dn Type=3
Dn Slope=0.005
Boundary for River Rch & Prof#=Cottonwood Creek,Reach-1,3
Up Type=0
Dn Type=3
Dn Slope=0.005
Boundary for River Rch & Prof#=Cottonwood Creek,Reach-1,4
Up Type=0
Dn Type=3
Dn Slope=0.005
Boundary for River Rch & Prof#=Cottonwood Creek,Reach-1,5
Up Type=0
Dn Type=3
Dn Slope=0.005
Boundary for River Rch & Prof#=Cottonwood Creek,Reach-1,6
Up Type=0
Dn Type=3
Dn Slope=0.005
Boundary for River Rch & Prof#=Cottonwood Creek,Reach-1,7
Up Type=0
Dn Type=3
Dn Slope=0.005

--- Cottonwood Creek Trib118.g01 (geometry) ---

Geom Title=Existing Conditions

River Reach=Cottonwood Creek,Reach-1
Reach XY= 30
      1363405.00      6936588.00      1363930.00      6936688.40
      1364158.32      6936596.04      1364408.22      6936830.17
      1364791.63      6936501.32      1364858.16      6936196.34
      1365054.91      6936045.28      1365402.74      6936482.95
      1365630.00      6936187.35      1365842.78      6936486.56
      1366138.26      6936054.28      1366302.50      6936079.97
      1366258.52      6935839.46      1366797.53      6935244.07
      1366845.29      6934948.18      1367296.50      6935040.67
      1367470.36      6935238.11      1367688.72      6935054.70
      1367505.06      6934717.97      1367508.07      6934546.30
      1367652.58      6934443.41      1367920.36      6934588.11
      1368149.11      6934489.96      1368994.52      6934787.07
      1369147.21      6934641.42      1369163.46      6934240.62
      1369649.29      6934239.89      1369849.15      6934436.51
      1370113.48      6933791.51      1370805.00      6933788.00

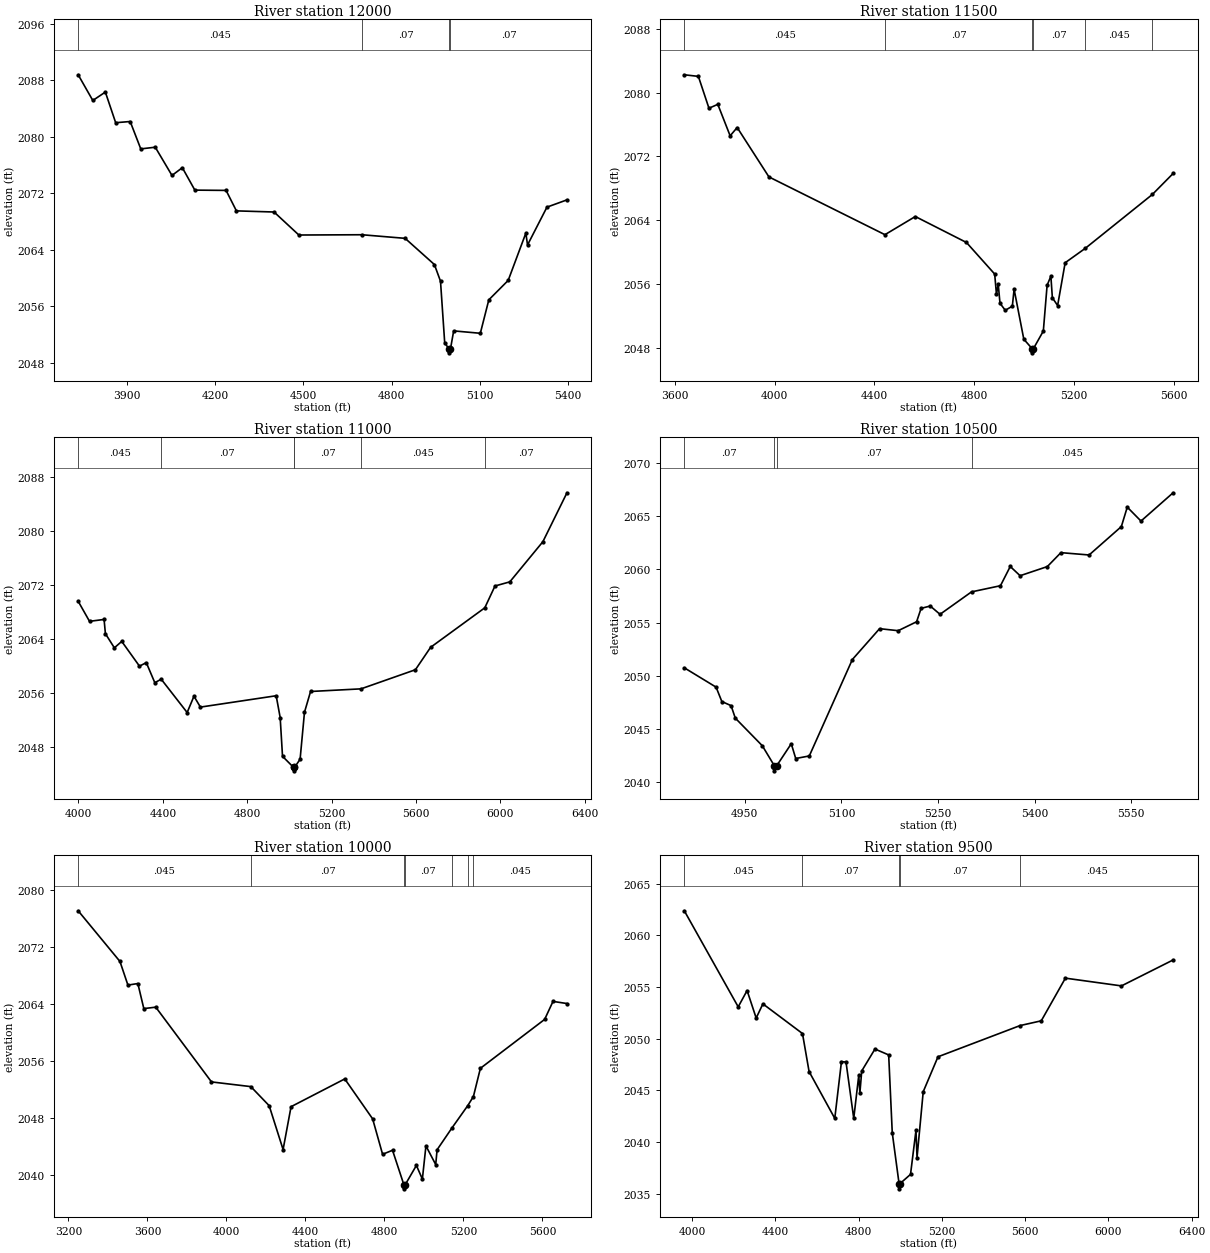
Type RM Length L Ch R = 1,12000,500,500,500
BEGIN DESCRIPTION:
Cottonwood Creek Trib118 23.0
END DESCRIPTION:
XS GIS Cut Line= 3
      1362954.97      6937588.03      1363792.05      6936638.13
      1363604.98      6936287.97
#Sta/Elev= 30
  3733.9 2088.80  3783.7 2085.16  3826.4 2086.35  3861.5 2082.01  3910.9 2082.18
  3946.9 2078.30  3996.2 2078.54  4053.1 2074.54  4088.3 2075.64  4130.9 2072.46
  4237.2 2072.42  4272.3 2069.52  4400.4 2069.36  4484.8 2066.10  4699.2 2066.14
  4846.3 2065.63  4945.9 2061.92  4966.7 2059.56  4981.0 2050.83  4996.4 2049.91
  4996.7 2049.41  5000.4 2049.91  5011.5 2052.52  5102.2 2052.18  5131.1 2056.92
  5197.0 2059.67  5257.1 2066.37  5262.8 2064.69  5328.9 2070.05  5397.0 2071.08
#Mann=4,-1,0
  3733.9   0.045       0  4699.2    0.07       0  4996.4    0.07       0
  5000.4    0.07       0
Bank Sta=4996.4,5000.4
Exp/Cntr=0.3,0.1

Type RM Length L Ch R = 1,11500,500,500,500
BEGIN DESCRIPTION:
Cottonwood Creek Trib118 22.0
END DESCRIPTION:
XS GIS Cut Line= 3
      1363255.03      6937587.97      1364231.81      6936637.93
      1363904.98      6936137.98
#Sta/Elev= 30
  3637.4 2082.24  3693.8 2082.04  3736.3 2078.04  3771.7 2078.53  3821.2 2074.58
  3849.4 2075.62  3976.8 2069.42  4441.9 2062.17  4563.7 2064.45  4768.8 2061.19
  4881.9 2057.23  4889.1 2054.67  4896.1 2055.97  4903.2 2053.56  4924.4 2052.68
  4952.7 2053.20  4959.8 2055.32  4998.7 2049.05  5032.8 2047.84  5033.1 2047.34
  5036.8 2047.84  5077.0 2050.08  5092.1 2055.81  5107.2 2056.97  5113.2 2054.25
  5134.3 2053.28  5164.5 2058.65  5244.9 2060.45  5514.2 2067.22  5597.3 2069.85
#Mann=6,-1,0
  3637.4   0.045       0  4441.9    0.07       0  5032.8    0.07       0
  5036.8    0.07       0  5244.9   0.045       0  5514.2    0.07       0
Bank Sta=5032.8,5036.8
Exp/Cntr=0.3,0.1

Type RM Length L Ch R = 1,11000,500,500,500
BEGIN DESCRIPTION:
Cottonwood Creek Trib118 21.0
END DESCRIPTION:
XS GIS Cut Line= 3
      1364955.00      6937637.99      1364585.65      6936707.40
      1363754.99      6935687.98
#Sta/Elev= 30
  3998.8 2069.59  4052.6 2066.62  4121.6 2066.90  4127.9 2064.79  4170.3 2062.70
  4205.3 2063.65  4289.3 2059.99  4321.6 2060.51  4362.0 2057.54  4392.3 2058.06
  4515.2 2053.13  4547.5 2055.54  4578.0 2053.93  4937.1 2055.61  4956.0 2052.39
  4967.1 2046.65  5019.7 2045.00  5019.9 2044.50  5023.7 2045.00  5050.4 2046.21
  5071.2 2053.17  5100.0 2056.24  5339.0 2056.63  5596.9 2059.46  5668.7 2062.77
  5925.6 2068.62  5973.9 2071.85  6044.2 2072.46  6200.8 2078.40  6315.0 2085.64
#Mann=6,-1,0
  3998.8   0.045       0  4392.3    0.07       0  5019.7    0.07       0
  5023.7    0.07       0  5339.0   0.045       0  5925.6    0.07       0
Bank Sta=5019.7,5023.7
Exp/Cntr=0.3,0.1

Type RM Length L Ch R = 1,10500,500,500,500
BEGIN DESCRIPTION:
Cottonwood Creek Trib118 20.0
END DESCRIPTION:
XS GIS Cut Line= 3
      1364955.01      6936388.01      1364836.06      6936306.67
      1364505.01      6935788.02
#Sta/Elev= 30
  4855.9 2050.75  4905.3 2048.93  4914.2 2047.58  4928.6 2047.19  4935.1 2046.02
  4977.1 2043.42  4995.6 2041.56  4995.8 2041.06  4999.7 2041.56  5022.1 2043.61
  5029.0 2042.22  5050.1 2042.46  5117.0 2051.53  5159.3 2054.43  5188.2 2054.24
  5216.8 2055.08  5223.8 2056.34  5238.0 2056.56  5253.2 2055.78  5302.1 2057.89
  5347.1 2058.47  5362.3 2060.28  5377.6 2059.41  5419.9 2060.27  5441.0 2061.58
  5484.8 2061.36  5534.9 2064.03  5544.1 2065.86  5565.4 2064.55  5615.3 2067.21
#Mann=4,-1,0
  4855.9    0.07       0  4995.6    0.07       0  4999.7    0.07       0
  5302.1   0.045       0
Bank Sta=4995.6,4999.7
Exp/Cntr=0.3,0.1

Type RM Length L Ch R = 1,10000,500,500,500
BEGIN DESCRIPTION:
Cottonwood Creek Trib118 19.0
END DESCRIPTION:
XS GIS Cut Line= 3
      1364955.00      6937838.00      1365167.13      6936100.10
      1364655.03      6935588.03
#Sta/Elev= 30
  3249.2 2077.10  3460.8 2069.98  3501.1 2066.66  3551.4 2066.88  3581.6 2063.36
  3642.1 2063.56  3924.2 2053.06  4123.4 2052.40  4216.3 2049.72  4286.8 2043.56
  4327.1 2049.58  4599.1 2053.48  4740.2 2047.87  4790.6 2042.89  4840.9 2043.46
  4899.3 2038.54  4899.6 2038.04  4903.4 2038.54  4961.8 2041.33  4992.0 2039.41
  5010.1 2044.07  5059.6 2041.45  5066.6 2043.53  5140.7 2046.55  5222.1 2049.74
  5250.5 2051.01  5285.8 2054.97  5611.1 2061.84  5653.5 2064.37  5724.2 2064.07
#Mann=7,-1,0
  3249.2   0.045       0  4123.4    0.07       0  4899.3    0.07       0
  4903.4    0.07       0  5140.7   0.045       0  5222.1    0.07       0
  5250.5   0.045       0
Bank Sta=4899.3,4903.4
Exp/Cntr=0.3,0.1

Type RM Length L Ch R = 1,9500,1000,1000,1000
BEGIN DESCRIPTION:
Cottonwood Creek Trib118 18.0
END DESCRIPTION:
XS GIS Cut Line= 3
      1365005.01      6937437.98      1365393.94      6936476.68
      1365155.01      6935188.04
#Sta/Elev= 30
  3963.0 2062.37  4221.9 2053.07  4264.6 2054.65  4308.2 2051.99  4340.5 2053.36
  4530.6 2050.49  4562.3 2046.81  4685.7 2042.28  4717.8 2047.77  4739.7 2047.73
  4776.8 2042.28  4800.9 2046.44  4806.3 2044.74  4815.2 2046.87  4878.7 2048.99
  4944.6 2048.42  4961.8 2040.88  4994.5 2035.96  4994.8 2035.46  4998.7 2035.96
  5049.5 2036.86  5075.7 2041.12  5080.8 2038.49  5110.5 2044.86  5181.4 2048.24
  5575.6 2051.26  5677.4 2051.72  5793.3 2055.85  6062.6 2055.10  6310.6 2057.61
#Mann=5,-1,0
  3963.0   0.045       0  4530.6    0.07       0  4994.5    0.07       0
  4998.7    0.07       0  5575.6   0.045       0
Bank Sta=4994.5,4998.7
Exp/Cntr=0.3,0.1

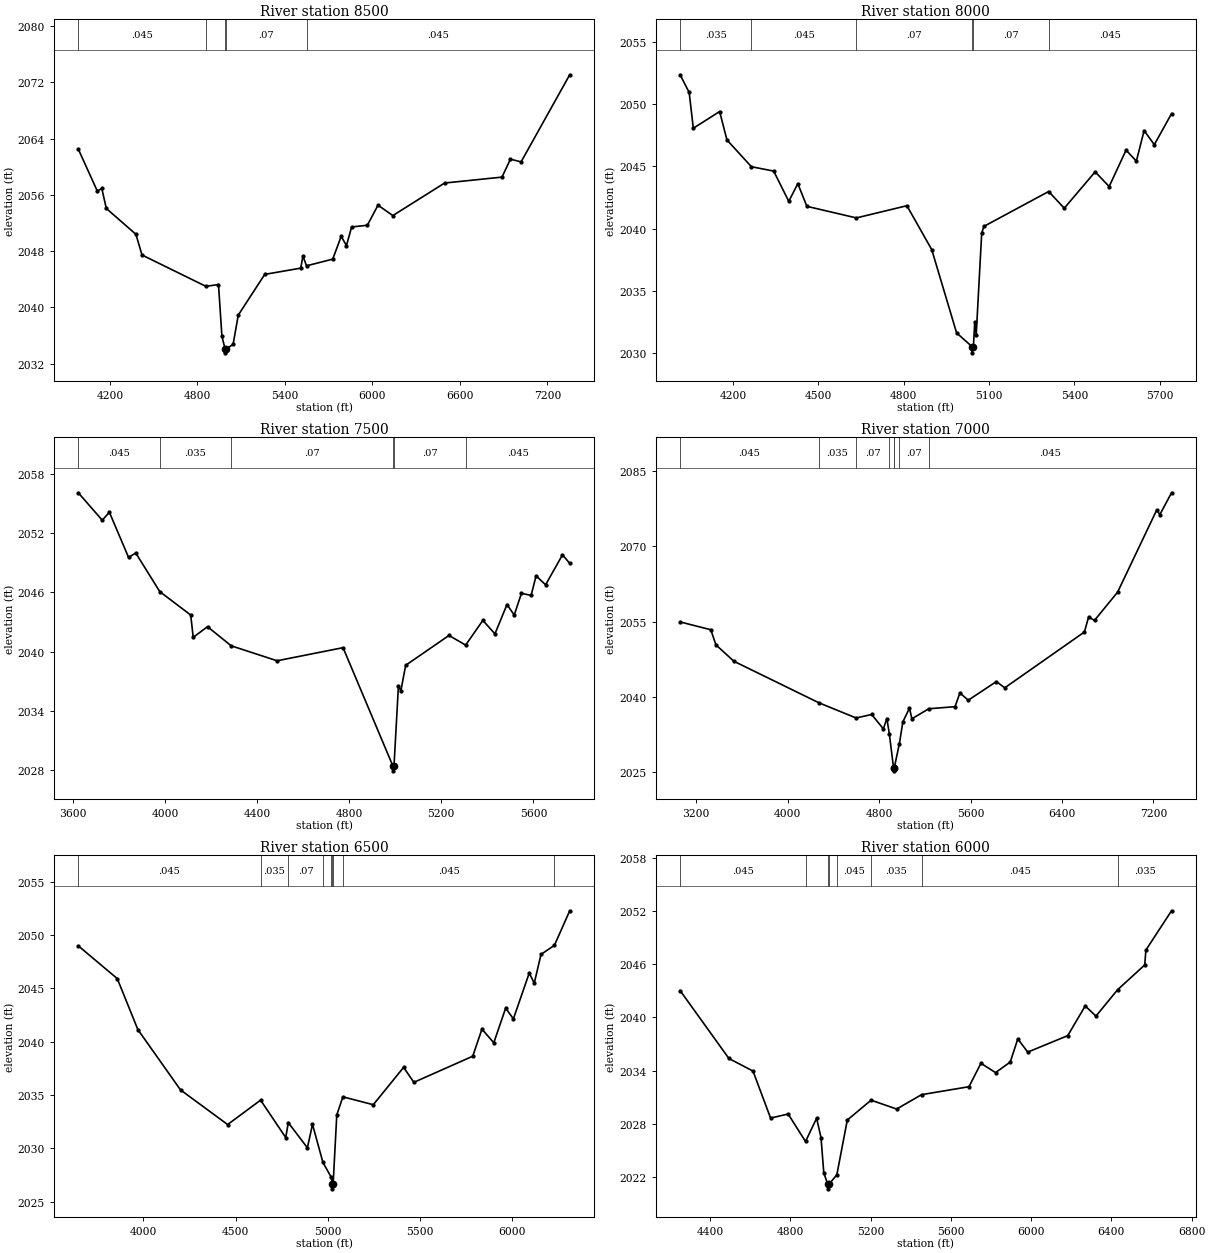
Type RM Length L Ch R = 1,8500,500,500,500
BEGIN DESCRIPTION:
Cottonwood Creek Trib118 17.0
END DESCRIPTION:
XS GIS Cut Line= 3
      1366304.99      6937387.97      1365947.67      6936436.23
      1364705.01      6934438.01
#Sta/Elev= 30
  3983.4 2062.50  4114.1 2056.52  4144.4 2056.91  4175.6 2054.06  4378.6 2050.38
  4420.2 2047.44  4858.4 2042.98  4944.7 2043.24  4968.2 2035.87  4990.6 2034.02
  4991.0 2033.52  4995.5 2034.02  5045.0 2034.74  5080.4 2038.89  5261.8 2044.68
  5508.5 2045.57  5523.9 2047.29  5548.3 2045.90  5728.0 2046.85  5786.0 2050.09
  5822.2 2048.78  5857.6 2051.43  5965.4 2051.67  6038.6 2054.53  6140.2 2053.05
  6495.4 2057.68  6888.6 2058.52  6946.4 2061.07  7019.6 2060.69  7353.1 2073.08
#Mann=5,-1,0
  3983.4   0.045       0  4858.4    0.07       0  4990.6    0.07       0
  4995.5    0.07       0  5548.3   0.045       0
Bank Sta=4990.6,4995.5
Exp/Cntr=0.3,0.1

Type RM Length L Ch R = 1,8000,500,500,500
BEGIN DESCRIPTION:
Cottonwood Creek Trib118 16.0
END DESCRIPTION:
XS GIS Cut Line= 4
      1366505.01      6936988.03      1366175.75      6936058.63
      1366140.06      6935947.32      1365622.63      6935597.28
#Sta/Elev= 30
  4014.0 2052.35  4045.9 2050.93  4060.4 2048.06  4153.0 2049.40  4178.6 2047.12
  4264.6 2044.97  4342.9 2044.62  4396.0 2042.19  4427.8 2043.61  4459.6 2041.79
  4633.7 2040.86  4811.3 2041.84  4898.7 2038.31  4986.0 2031.63  5040.2 2030.53
  5040.6 2030.03  5045.1 2030.53  5049.8 2032.50  5055.0 2031.49  5074.2 2039.63
  5081.9 2040.18  5309.6 2042.98  5364.5 2041.64  5473.1 2044.56  5522.3 2043.38
  5581.8 2046.30  5618.0 2045.42  5645.2 2047.87  5681.1 2046.74  5741.6 2049.23
#Mann=6,-1,0
  4014.0   0.035       0  4264.6   0.045       0  4633.7    0.07       0
  5040.2    0.07       0  5045.1    0.07       0  5309.6   0.045       0
Bank Sta=5040.2,5045.1
Exp/Cntr=0.3,0.1

Type RM Length L Ch R = 1,7500,500,500,500
BEGIN DESCRIPTION:
Cottonwood Creek Trib118 15.0
END DESCRIPTION:
XS GIS Cut Line= 3
      1366704.99      6937087.97      1366328.26      6935764.13
      1365604.99      6935538.00
#Sta/Elev= 30
  3623.6 2056.11  3727.5 2053.33  3758.7 2054.13  3841.9 2049.55  3873.1 2050.00
  3977.4 2046.08  4111.9 2043.70  4122.6 2041.44  4184.8 2042.52  4287.6 2040.58
  4486.9 2039.06  4773.4 2040.39  4989.7 2028.39  4990.1 2027.89  4994.7 2028.39
  5013.9 2036.52  5024.4 2036.00  5045.3 2038.60  5233.5 2041.63  5305.8 2040.65
  5380.6 2043.16  5433.0 2041.79  5485.4 2044.77  5516.8 2043.70  5548.2 2045.91
  5590.1 2045.69  5611.7 2047.68  5653.0 2046.77  5726.4 2049.81  5757.8 2048.95
#Mann=6,-1,0
  3623.6   0.045       0  3977.4   0.035       0  4287.6    0.07       0
  4989.7    0.07       0  4994.7    0.07       0  5305.8   0.045       0
Bank Sta=4989.7,4994.7
Exp/Cntr=0.3,0.1

Type RM Length L Ch R = 1,7000,500,500,500
BEGIN DESCRIPTION:
Cottonwood Creek Trib118 14.0
END DESCRIPTION:
XS GIS Cut Line= 3
      1367005.01      6937288.03      1366604.20      6935388.15
      1364605.00      6934138.00
#Sta/Elev= 30
  3058.3 2054.93  3327.0 2053.37  3371.6 2050.36  3528.5 2047.09  4271.5 2038.82
  4598.0 2035.78  4734.6 2036.48  4836.6 2033.60  4867.3 2035.67  4889.2 2032.56
  4926.1 2025.74  4926.5 2025.24  4931.1 2025.74  4976.6 2030.64  5007.3 2035.01
  5065.1 2037.74  5086.3 2035.62  5234.4 2037.62  5463.7 2038.03  5506.2 2040.78
  5579.2 2039.32  5825.6 2043.04  5898.7 2041.79  6595.6 2052.92  6632.2 2055.90
  6684.0 2055.24  6886.1 2060.87  7228.2 2077.24  7255.9 2076.33  7357.9 2080.68
#Mann=8,-1,0
  3058.3   0.045       0  4271.5   0.035       0  4598.0    0.07       0
  4889.2    0.16       0  4926.1    0.07       0  4931.1    0.16       0
  4976.6    0.07       0  5234.4   0.045       0
Bank Sta=4926.1,4931.1
Exp/Cntr=0.3,0.1

Type RM Length L Ch R = 1,6500,500,500,500
BEGIN DESCRIPTION:
Cottonwood Creek Trib118 13.0
END DESCRIPTION:
XS GIS Cut Line= 3
      1367455.00      6936188.00      1366775.47      6935016.87
      1365754.98      6934187.99
#Sta/Elev= 30
  3646.0 2048.99  3857.6 2045.92  3969.4 2041.14  4201.0 2035.48  4457.0 2032.23
  4635.9 2034.52  4772.5 2031.01  4786.4 2032.41  4890.1 2030.05  4917.8 2032.25
  4974.4 2028.68  5019.8 2027.28  5024.8 2026.70  5025.2 2026.20  5030.0 2026.70
  5049.7 2033.13  5082.9 2034.83  5247.9 2034.09  5412.5 2037.59  5468.5 2036.19
  5788.1 2038.64  5838.0 2041.18  5902.4 2039.90  5966.8 2043.15  6008.7 2042.14
  6094.9 2046.44  6122.1 2045.49  6158.8 2048.19  6231.7 2049.04  6314.7 2052.28
#Mann=9,-1,0
  3646.0   0.045       0  4635.9   0.035       0  4786.4    0.07       0
  4974.4    0.16       0  5019.8    0.07       0  5024.8    0.07       0
  5030.0    0.07       0  5082.9   0.045       0  6231.7   0.035       0
Bank Sta=5024.8,5030
Exp/Cntr=0.3,0.1

Type RM Length L Ch R = 1,6000,500,500,500
BEGIN DESCRIPTION:
Cottonwood Creek Trib118 12.0
END DESCRIPTION:
XS GIS Cut Line= 4
      1367555.00      6935737.99      1367199.26      6935078.86
      1367063.97      6934867.51      1365799.81      6934159.84
#Sta/Elev= 30
  4251.0 2043.03  4494.2 2035.37  4614.2 2033.95  4701.8 2028.65  4789.3 2029.11
  4875.9 2026.01  4931.2 2028.63  4953.1 2026.45  4966.9 2022.48  4987.0 2021.17
  4987.4 2020.67  4992.2 2021.17  5032.0 2022.26  5084.1 2028.43  5202.6 2030.67
  5330.0 2029.67  5454.1 2031.29  5690.5 2032.19  5749.9 2034.83  5822.8 2033.78
  5896.0 2034.97  5933.7 2037.58  5983.2 2036.09  6182.6 2037.95  6269.7 2041.30
  6323.0 2040.15  6431.2 2043.13  6566.2 2045.92  6571.9 2047.60  6699.7 2052.03
#Mann=8,-1,0
  4251.0   0.045       0  4875.9    0.07       0  4987.0    0.07       0
  4992.2    0.07       0  5032.0   0.045       0  5202.6   0.035       0
  5454.1   0.045       0  6431.2   0.035       0
Bank Sta=4987,4992.2
Exp/Cntr=0.3,0.1

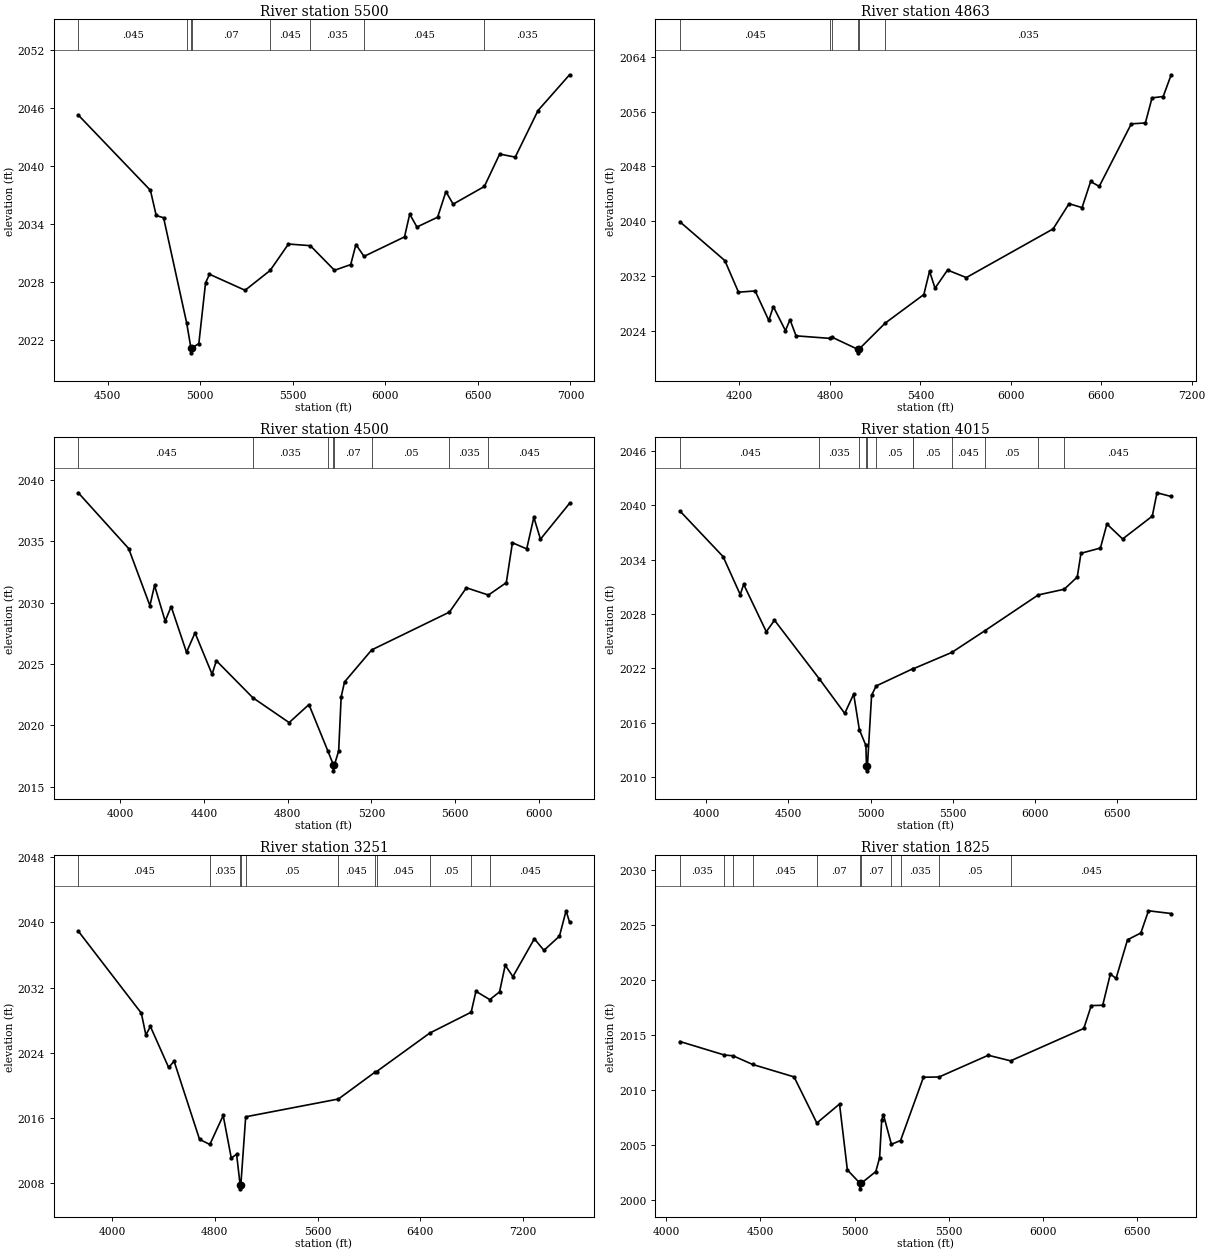
Type RM Length L Ch R = 1,5500,637,637,637
BEGIN DESCRIPTION:
Cottonwood Creek Trib118 11.0
END DESCRIPTION:
XS GIS Cut Line= 4
      1367605.00      6935837.96      1367563.16      6935180.09
      1366987.20      6934701.44      1365872.65      6934144.16
#Sta/Elev= 30
  4340.8 2045.25  4730.6 2037.45  4761.6 2034.85  4801.7 2034.61  4926.6 2023.69
  4949.3 2021.12  4949.8 2020.62  4954.6 2021.12  4992.1 2021.58  5028.4 2027.87
  5049.6 2028.76  5242.0 2027.10  5377.2 2029.15  5476.3 2031.89  5594.5 2031.72
  5725.0 2029.17  5812.7 2029.76  5840.8 2031.84  5884.6 2030.61  6103.4 2032.63
  6131.5 2034.99  6170.4 2033.65  6282.2 2034.67  6327.0 2037.32  6366.1 2036.02
  6534.6 2037.85  6617.6 2041.21  6701.5 2040.89  6824.7 2045.72  6995.0 2049.42
#Mann=8,-1,0
  4340.8   0.045       0  4926.6    0.07       0  4949.3    0.07       0
  4954.6    0.07       0  5377.2   0.045       0  5594.5   0.035       0
  5884.6   0.045       0  6534.6   0.035       0
Bank Sta=4949.3,4954.6
Exp/Cntr=0.3,0.1

Type RM Length L Ch R = 1,4863,363,363,363
BEGIN DESCRIPTION:
Cottonwood Creek Trib118 10.0
END DESCRIPTION:
XS GIS Cut Line= 4
      1367804.34      6935604.54      1367882.46      6934823.31
      1367500.52      6934662.72      1365555.04      6933988.02
#Sta/Elev= 30
  3805.1 2039.91  4103.1 2034.25  4193.6 2029.64  4304.1 2029.82  4394.6 2025.52
  4424.7 2027.54  4505.1 2024.03  4535.3 2025.62  4575.5 2023.27  4799.6 2022.90
  4815.3 2023.06  4986.2 2021.29  4986.6 2020.79  4991.5 2021.29  5166.9 2025.13
  5423.2 2029.30  5460.9 2032.70  5497.3 2030.22  5580.1 2032.87  5704.7 2031.77
  6280.4 2038.87  6386.3 2042.55  6472.5 2041.98  6529.5 2045.79  6586.4 2045.07
  6799.1 2054.20  6892.5 2054.33  6936.7 2057.99  7010.8 2058.19  7063.7 2061.36
#Mann=6,-1,0
  3805.1   0.045       0  4799.6    0.07       0  4815.3   0.045       0
  4986.2   0.045       0  4991.5   0.045       0  5166.9   0.035       0
Bank Sta=4986.2,4991.5
Exp/Cntr=0.3,0.1

Type RM Length L Ch R = 1,4500,485,485,485
BEGIN DESCRIPTION:
Cottonwood Creek Trib118 9.0
END DESCRIPTION:
XS GIS Cut Line= 4
      1367821.70      6935565.48      1367956.25      6934897.10
      1367713.43      6934437.15      1366704.96      6933887.98
#Sta/Elev= 30
  3798.1 2038.94  4039.0 2034.40  4140.7 2029.75  4162.8 2031.39  4213.8 2028.49
  4242.4 2029.67  4315.8 2025.95  4356.6 2027.53  4438.2 2024.16  4458.6 2025.26
  4632.9 2022.25  4806.8 2020.22  4901.6 2021.69  4992.7 2017.88  5018.2 2016.79
  5018.6 2016.29  5023.8 2016.79  5043.8 2017.92  5055.7 2022.32  5071.8 2023.53
  5201.7 2026.14  5573.6 2029.22  5654.9 2031.20  5760.2 2030.61  5845.8 2031.62
  5875.0 2034.87  5943.3 2034.37  5977.5 2036.94  6009.1 2035.16  6148.3 2038.08
#Mann=8,-1,0
  3798.1   0.045       0  4632.9   0.035       0  4992.7    0.07       0
  5018.2    0.07       0  5023.8    0.07       0  5201.7    0.05       0
  5573.6   0.035       0  5760.2   0.045       0
Bank Sta=5018.2,5023.8
Exp/Cntr=0.3,0.1

Type RM Length L Ch R = 1,4015,764,764,764
BEGIN DESCRIPTION:
Cottonwood Creek Trib118 8.0
END DESCRIPTION:
XS GIS Cut Line= 4
      1367834.03      6935600.12      1368129.29      6934585.97
      1368090.77      6934444.76      1366487.43      6933662.32
#Sta/Elev= 30
  3841.3 2039.38  4103.9 2034.34  4208.0 2030.15  4228.9 2031.28  4366.5 2026.05
  4416.3 2027.32  4689.4 2020.83  4843.4 2017.03  4897.6 2019.16  4932.1 2015.24
  4972.0 2013.49  4975.5 2011.19  4976.0 2010.69  4981.2 2011.19  5006.6 2019.03
  5034.3 2020.06  5258.2 2021.97  5259.0 2021.95  5494.9 2023.77  5693.7 2026.14
  6019.6 2030.11  6177.8 2030.74  6257.0 2032.09  6279.6 2034.71  6397.8 2035.29
  6437.3 2037.94  6532.9 2036.29  6713.2 2038.81  6741.7 2041.39  6828.0 2040.98
#Mann=12,-1,0
  3841.3   0.045       0  4689.4   0.035       0  4932.1    0.07       0
  4975.5    0.07       0  4981.2    0.07       0  5034.3    0.05       0
  5258.2   0.045       0  5259.0    0.05       0  5494.9   0.045       0
  5693.7    0.05       0  6019.6   0.035       0  6177.8   0.045       0
Bank Sta=4975.5,4981.2
Exp/Cntr=0.3,0.1

Type RM Length L Ch R = 1,3251,1426,1426,1426
BEGIN DESCRIPTION:
Cottonwood Creek Trib118 7.0
END DESCRIPTION:
XS GIS Cut Line= 4
      1367877.30      6935602.79      1368766.79      6934804.95
      1368777.57      6934659.39      1366519.37      6933630.00
#Sta/Elev= 30
  3737.8 2038.93  4228.4 2028.87  4263.5 2026.20  4298.9 2027.24  4440.7 2022.22
  4483.3 2022.98  4681.4 2013.40  4761.6 2012.78  4865.3 2016.33  4928.1 2011.12
  4969.7 2011.57  4997.0 2007.84  4997.4 2007.34  5002.7 2007.84  5040.4 2016.17
  5761.9 2018.35  6043.0 2021.60  6059.6 2021.72  6472.7 2026.43  6794.9 2028.99
  6832.1 2031.55  6939.7 2030.53  7015.7 2031.48  7059.7 2034.74  7119.7 2033.35
  7286.5 2037.99  7361.1 2036.57  7481.8 2038.31  7533.4 2041.42  7560.4 2040.03
#Mann=11,-1,0
  3737.8   0.045       0  4761.6   0.035       0  4997.0   0.035       0
  5002.7   0.035       0  5040.4    0.05       0  5761.9   0.045       0
  6043.0    0.05       0  6059.6   0.045       0  6472.7    0.05       0
  6794.9   0.035       0  6939.7   0.045       0
Bank Sta=4997,5002.7
Exp/Cntr=0.3,0.1

Type RM Length L Ch R = 1,1825,1060,1060,1060
BEGIN DESCRIPTION:
Cottonwood Creek Trib118 6.0
END DESCRIPTION:
XS GIS Cut Line= 4
      1369138.75      6934999.04      1369661.68      6934314.37
      1369672.46      6934195.77      1368065.99      6933953.19
#Sta/Elev= 30
  4074.1 2014.42  4310.3 2013.19  4356.1 2013.12  4460.1 2012.33  4679.4 2011.20
  4800.3 2007.00  4920.6 2008.73  4962.1 2002.73  5029.6 2001.51  5030.1 2001.01
  5035.4 2001.51  5112.8 2002.58  5133.1 2003.83  5144.2 2007.28  5153.3 2007.77
  5195.6 2005.06  5244.3 2005.41  5365.7 2011.17  5448.3 2011.19  5709.5 2013.17
  5827.7 2012.66  6216.0 2015.61  6255.6 2017.69  6316.3 2017.72  6356.8 2020.56
  6387.1 2020.16  6447.8 2023.68  6518.6 2024.30  6559.0 2026.32  6679.4 2026.07
#Mann=11,-1,0
  4074.1   0.035       0  4310.3    0.05       0  4356.1   0.035       0
  4460.1   0.045       0  4800.3    0.07       0  5029.6    0.07       0
  5035.4    0.07       0  5195.6    0.05       0  5244.3   0.035       0
  5448.3    0.05       0  5827.7   0.045       0
Bank Sta=5029.6,5035.4
Exp/Cntr=0.3,0.1

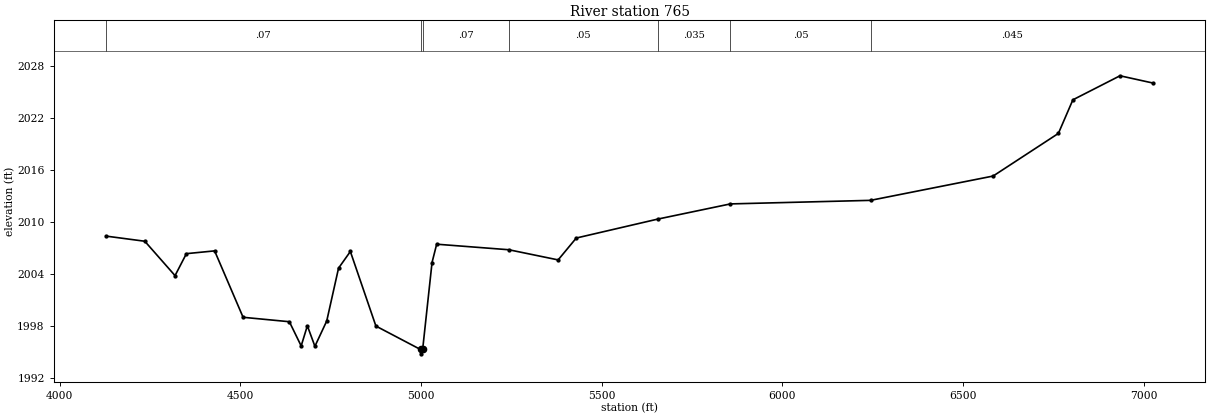
Type RM Length L Ch R = 1,765,0,0,0
BEGIN DESCRIPTION:
Cottonwood Creek Trib118 5.0
END DESCRIPTION:
XS GIS Cut Line= 4
      1369942.01      6934600.08      1370173.82      6933845.37
      1370055.22      6933753.72      1368103.74      6933904.66
#Sta/Elev= 30
  4128.9 2008.36  4235.7 2007.77  4319.4 2003.81  4350.8 2006.34  4428.9 2006.66
  4507.7 1999.01  4635.7 1998.50  4668.4 1995.71  4685.5 1998.03  4706.4 1995.67
  4739.1 1998.58  4771.8 2004.67  4804.5 2006.59  4875.2 1998.00  4998.7 1995.30
  4999.1 1994.80  5004.5 1995.30  5030.5 2005.32  5043.3 2007.43  5243.1 2006.79
  5379.4 2005.62  5429.6 2008.14  5654.9 2010.32  5856.0 2012.07  6243.9 2012.48
  6583.0 2015.28  6763.6 2020.19  6803.7 2024.06  6934.1 2026.83  7025.6 2025.99
#Mann=7,-1,0
  4128.9    0.07       0  4998.7    0.07       0  5004.5    0.07       0
  5243.1    0.05       0  5654.9   0.035       0  5856.0    0.05       0
  6243.9   0.045       0
Bank Sta=4998.7,5004.5
Exp/Cntr=0.3,0.1

Chan Stop Cuts=-1