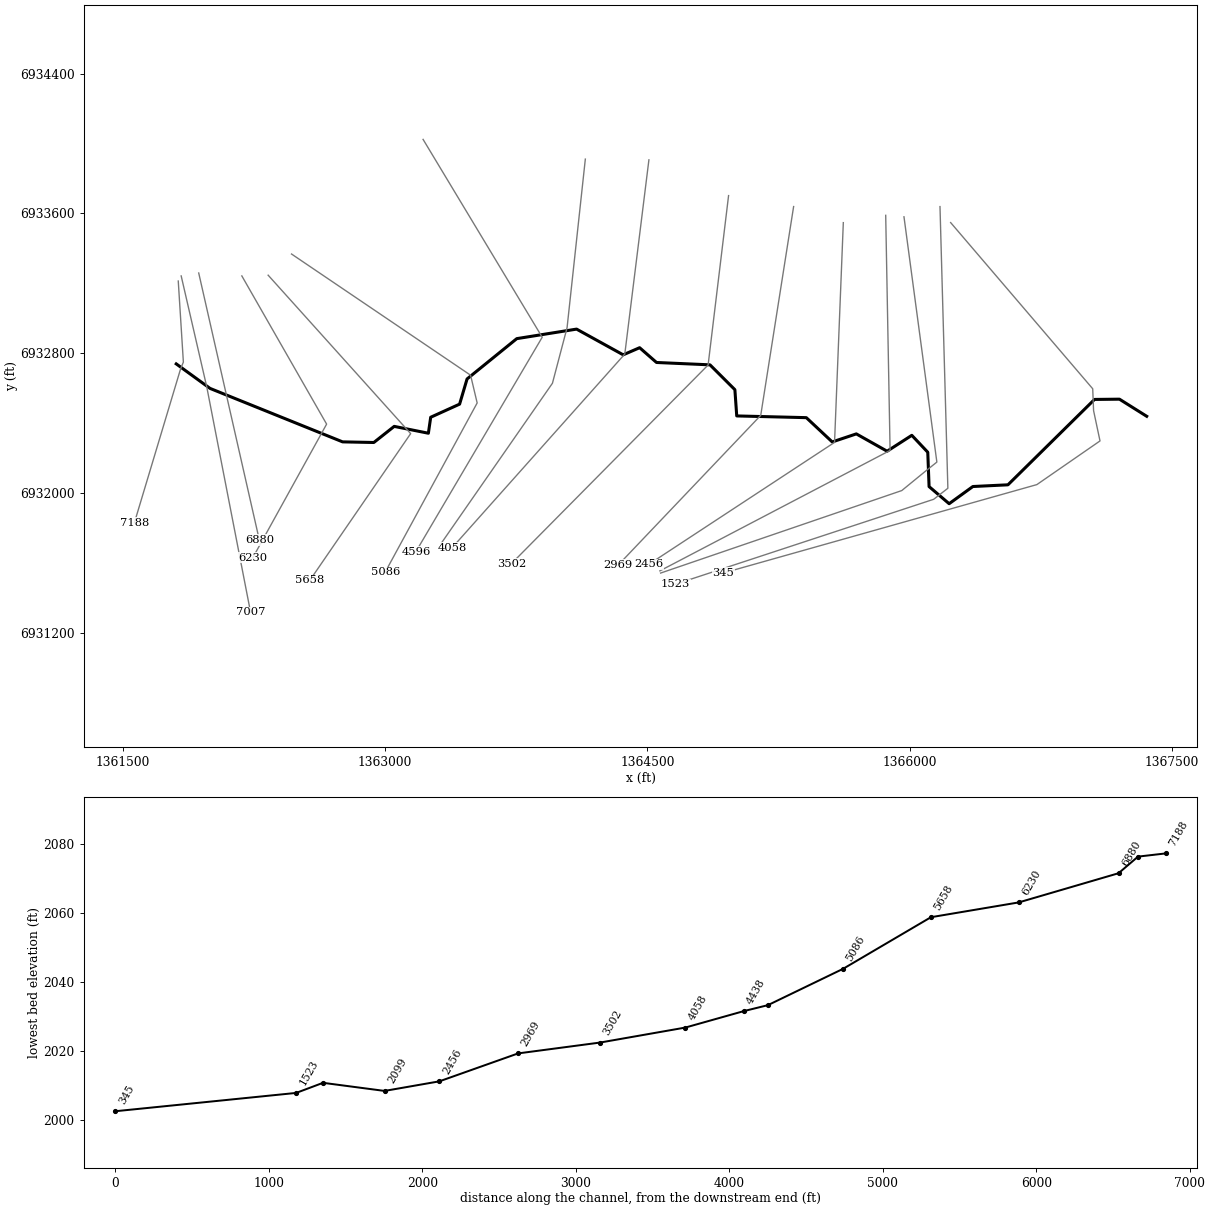
--- Cottonwood Creek Trib118a.prj (project) ---

Proj Title=Cottonwood Creek Trib118a Base Level Engineering
Current Plan=p01
Default Exp/Contr=0.3,0.1
English Units
Geom File=g01
Flow File=f01
Plan File=p01
BEGIN DESCRIPTION:
Cottonwood Creek Trib118a
END DESCRIPTION:

--- Cottonwood Creek Trib118a.p01 (plan) ---

Plan Title=Multiple Run
Short Identifier=Multiple
Geom File=g01
Flow File=f01
Subcritical Flow
K Sum by GR= 0
Std Step Tol= 0.01
Critical Tol= 0.01
Num of Std Step Trials= 20
Max Error Tol= 0.3
Flow Tol Ratio= 0.001
Split Flow NTrial= 30
Split Flow Tol= 0.02
Split Flow Ratio= 0.02
Log Output Level= 0
Friction Slope Method= 1
Unsteady Friction Slope Method= 2
Unsteady Bridges Friction Slope Method= 1
Parabolic Critical Depth
Global Vel Dist=  1 , 1 , 1
Global Log Level= 0
CheckData=True
Encroach Param= -1, 0, 0, 0
BEGIN DESCRIPTION:
Multiple Run
END DESCRIPTION:

--- Cottonwood Creek Trib118a.f01 (steady flow) ---

Flow Title=Multiple
Number of Profiles=7
Profile Names=10-year,25-year,50-year,1pct_min,100-year,1pct_plu,500-year
River Rch & RM= Cottonwood Creek,Reach-1,7188
     234     331     412     255     510    1017     790
Boundary for River Rch & Prof#=Cottonwood Creek,Reach-1,1
Up Type=0
Dn Type=3
Dn Slope=0.005
Boundary for River Rch & Prof#=Cottonwood Creek,Reach-1,2
Up Type=0
Dn Type=3
Dn Slope=0.005
Boundary for River Rch & Prof#=Cottonwood Creek,Reach-1,3
Up Type=0
Dn Type=3
Dn Slope=0.005
Boundary for River Rch & Prof#=Cottonwood Creek,Reach-1,4
Up Type=0
Dn Type=3
Dn Slope=0.005
Boundary for River Rch & Prof#=Cottonwood Creek,Reach-1,5
Up Type=0
Dn Type=3
Dn Slope=0.005
Boundary for River Rch & Prof#=Cottonwood Creek,Reach-1,6
Up Type=0
Dn Type=3
Dn Slope=0.005
Boundary for River Rch & Prof#=Cottonwood Creek,Reach-1,7
Up Type=0
Dn Type=3
Dn Slope=0.005

--- Cottonwood Creek Trib118a.g01 (geometry) ---

Geom Title=Existing Conditions

River Reach=Cottonwood Creek,Reach-1
Reach XY= 30
      1361805.00      6932738.00      1361998.45      6932597.58
      1362756.47      6932291.55      1362935.02      6932287.96
      1363051.59      6932380.19      1363247.00      6932340.98
      1363260.28      6932432.48      1363425.57      6932507.58
      1363468.26      6932651.65      1363752.55      6932882.54
      1364094.52      6932937.06      1364361.13      6932789.86
      1364455.09      6932830.63      1364551.66      6932746.02
      1364857.45      6932732.54      1364999.88      6932590.29
      1365010.45      6932440.05      1365408.41      6932430.18
      1365556.63      6932291.13      1365694.31      6932337.25
      1365870.41      6932238.02      1366011.69      6932329.05
      1366102.94      6932232.17      1366110.45      6932035.53
      1366225.16      6931937.53      1366360.86      6932035.93
      1366561.48      6932045.69      1367056.47      6932534.47
      1367199.14      6932535.95      1367355.00      6932438.00

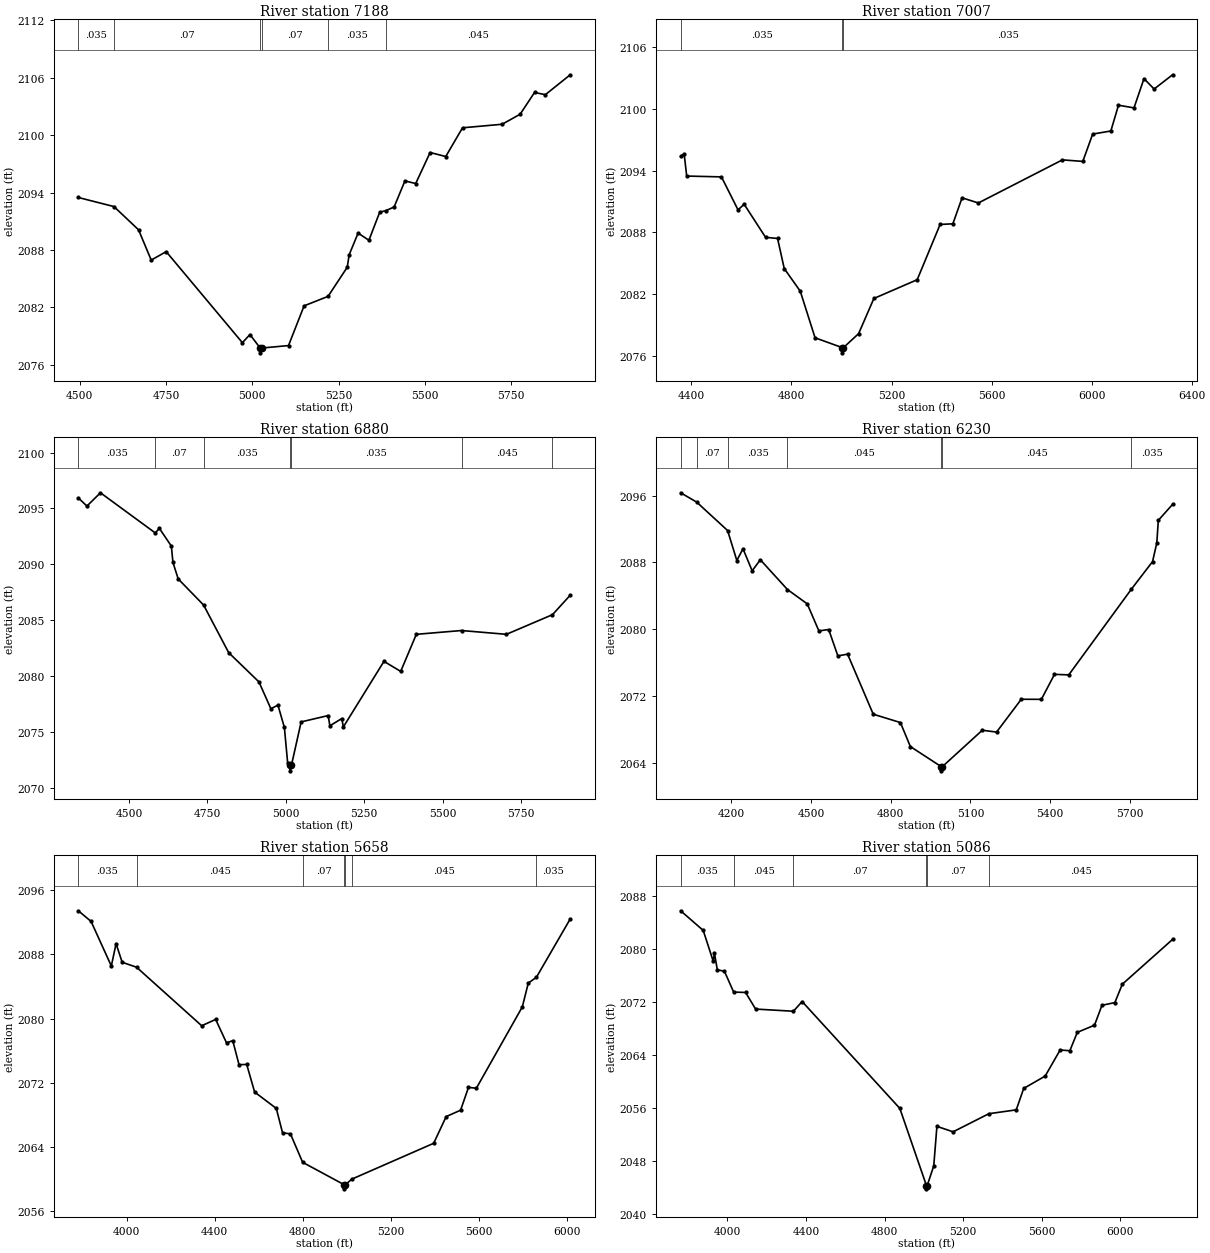
Type RM Length L Ch R = 1,7188,181,181,181
BEGIN DESCRIPTION:
Cottonwood Creek Trib118a 15.0
END DESCRIPTION:
XS GIS Cut Line= 4
      1361816.61      6933212.32      1361845.86      6932748.38
      1361829.14      6932706.59      1361565.84      6931828.91
#Sta/Elev= 30
  4495.6 2093.49  4599.0 2092.54  4670.3 2090.11  4706.9 2086.95  4750.4 2087.83
  4971.3 2078.32  4993.2 2079.17  5022.9 2077.76  5023.1 2077.26  5026.9 2077.76
  5105.0 2078.02  5150.2 2082.17  5219.7 2083.16  5275.4 2086.21  5280.8 2087.50
  5306.8 2089.77  5338.1 2089.02  5369.4 2091.95  5388.2 2092.13  5411.2 2092.50
  5442.5 2095.22  5473.8 2094.95  5515.6 2098.19  5560.9 2097.77  5609.5 2100.77
  5724.4 2101.14  5776.6 2102.19  5818.3 2104.46  5849.7 2104.23  5921.8 2106.31
#Mann=6,-1,0
  4495.6   0.035       0  4599.0    0.07       0  5022.9    0.07       0
  5026.9    0.07       0  5219.7   0.035       0  5388.2   0.045       0
Bank Sta=5022.9,5026.9
Exp/Cntr=0.3,0.1

Type RM Length L Ch R = 1,7007,127,127,127
BEGIN DESCRIPTION:
Cottonwood Creek Trib118a 14.0
END DESCRIPTION:
XS GIS Cut Line= 3
      1361833.32      6933241.57      1361979.61      6932606.28
      1362230.19      6931315.79
#Sta/Elev= 30
  4356.9 2095.37  4370.8 2095.63  4381.1 2093.47  4520.0 2093.39  4586.3 2090.19
  4610.7 2090.74  4696.3 2087.53  4744.3 2087.42  4771.0 2084.50  4835.0 2082.31
  4894.2 2077.79  5003.4 2076.83  5003.6 2076.33  5007.4 2076.83  5068.3 2078.19
  5129.3 2081.60  5302.5 2083.42  5394.2 2088.78  5445.1 2088.84  5481.9 2091.36
  5547.0 2090.86  5883.1 2095.04  5964.6 2094.89  6004.0 2097.54  6076.7 2097.84
  6107.2 2100.34  6169.2 2100.08  6209.1 2102.91  6249.8 2101.91  6323.4 2103.29
#Mann=3,-1,0
  4356.9   0.035       0  5003.4   0.035       0  5007.4   0.035       0
Bank Sta=5003.4,5007.4
Exp/Cntr=0.3,0.1

Type RM Length L Ch R = 1,6880,650,650,650
BEGIN DESCRIPTION:
Cottonwood Creek Trib118a 13.0
END DESCRIPTION:
XS GIS Cut Line= 2
      1361933.62      6933258.33      1362280.27      6931729.74
#Sta/Elev= 30
  4338.8 2095.94  4366.2 2095.21  4409.3 2096.40  4583.8 2092.81  4597.2 2093.21
  4635.2 2091.63  4640.3 2090.17  4657.0 2088.69  4738.0 2086.35  4817.9 2082.09
  4914.4 2079.47  4952.3 2077.07  4974.9 2077.39  4995.4 2075.39  5005.7 2072.25
  5013.9 2072.01  5014.1 2071.51  5017.9 2072.01  5048.8 2075.89  5135.1 2076.46
  5140.2 2075.54  5178.2 2076.19  5183.3 2075.44  5312.7 2081.31  5366.0 2080.41
  5415.8 2083.73  5559.8 2084.07  5702.9 2083.73  5849.7 2085.49  5906.2 2087.23
#Mann=7,-1,0
  4338.8   0.035       0  4583.8    0.07       0  4738.0   0.035       0
  5013.9   0.035       0  5017.9   0.035       0  5559.8   0.045       0
  5849.7   0.035       0
Bank Sta=5013.9,5017.9
Exp/Cntr=0.3,0.1

Type RM Length L Ch R = 1,6230,572,572,572
BEGIN DESCRIPTION:
Cottonwood Creek Trib118a 12.0
END DESCRIPTION:
XS GIS Cut Line= 3
      1362180.22      6933241.57      1362665.05      6932393.13
      1362242.92      6931628.28
#Sta/Elev= 30
  4009.7 2096.34  4070.1 2095.22  4186.3 2091.82  4221.1 2088.23  4244.2 2089.64
  4278.7 2087.00  4309.5 2088.32  4411.4 2084.76  4486.0 2083.04  4529.8 2079.80
  4566.7 2079.97  4601.2 2076.81  4637.8 2077.02  4734.3 2069.83  4836.5 2068.83
  4873.9 2065.96  4990.2 2063.55  4990.4 2063.05  4994.2 2063.55  5144.6 2067.91
  5198.3 2067.69  5291.3 2071.62  5366.9 2071.61  5416.2 2074.60  5470.0 2074.54
  5705.1 2084.78  5785.2 2088.10  5801.2 2090.33  5806.9 2093.04  5860.5 2094.95
#Mann=7,-1,0
  4009.7   0.035       0  4070.1    0.07       0  4186.3   0.035       0
  4411.4   0.045       0  4990.2   0.045       0  4994.2   0.045       0
  5705.1   0.035       0
Bank Sta=4990.2,4994.2
Exp/Cntr=0.3,0.1

Type RM Length L Ch R = 1,5658,572,572,572
BEGIN DESCRIPTION:
Cottonwood Creek Trib118a 11.0
END DESCRIPTION:
XS GIS Cut Line= 3
      1362330.71      6933245.72      1363145.69      6932338.79
      1362569.45      6931499.48
#Sta/Elev= 30
  3779.2 2093.44  3837.3 2092.11  3929.3 2086.55  3950.9 2089.34  3978.6 2087.02
  4044.1 2086.40  4340.4 2079.10  4403.9 2079.89  4453.2 2076.97  4481.6 2077.24
  4510.1 2074.25  4545.2 2074.27  4581.1 2070.83  4679.7 2068.79  4708.1 2065.75
  4744.0 2065.62  4799.4 2062.07  4989.4 2059.26  4989.7 2058.76  4993.4 2059.26
  5023.1 2059.97  5395.5 2064.44  5452.3 2067.77  5518.0 2068.57  5553.8 2071.41
  5589.7 2071.31  5798.8 2081.46  5825.8 2084.42  5862.9 2085.15  6016.6 2092.42
#Mann=7,-1,0
  3779.2   0.035       0  4044.1   0.045       0  4799.4    0.07       0
  4989.4    0.07       0  4993.4    0.07       0  5023.1   0.045       0
  5862.9   0.035       0
Bank Sta=4989.4,4993.4
Exp/Cntr=0.3,0.1

Type RM Length L Ch R = 1,5086,490,490,490
BEGIN DESCRIPTION:
Cottonwood Creek Trib118a 10.0
END DESCRIPTION:
XS GIS Cut Line= 4
      1362464.41      6933366.97      1363488.41      6932673.15
      1363526.03      6932514.33      1362999.72      6931545.26
#Sta/Elev= 30
  3762.1 2085.84  3876.9 2082.87  3927.8 2078.21  3933.8 2079.45  3948.7 2076.91
  3984.7 2076.70  4031.7 2073.55  4092.5 2073.49  4143.4 2070.98  4335.8 2070.65
  4380.1 2072.12  4877.3 2055.96  5012.6 2044.30  5012.8 2043.80  5016.6 2044.30
  5049.9 2047.27  5066.0 2053.25  5148.2 2052.42  5330.5 2055.16  5469.6 2055.74
  5507.6 2058.98  5616.9 2060.85  5692.9 2064.79  5742.3 2064.68  5780.4 2067.46
  5867.8 2068.54  5905.8 2071.55  5971.4 2071.96  6009.4 2074.74  6265.0 2081.51
#Mann=6,-1,0
  3762.1   0.035       0  4031.7   0.045       0  4335.8    0.07       0
  5012.6    0.07       0  5016.6    0.07       0  5330.5   0.045       0
Bank Sta=5012.6,5016.6
Exp/Cntr=0.3,0.1

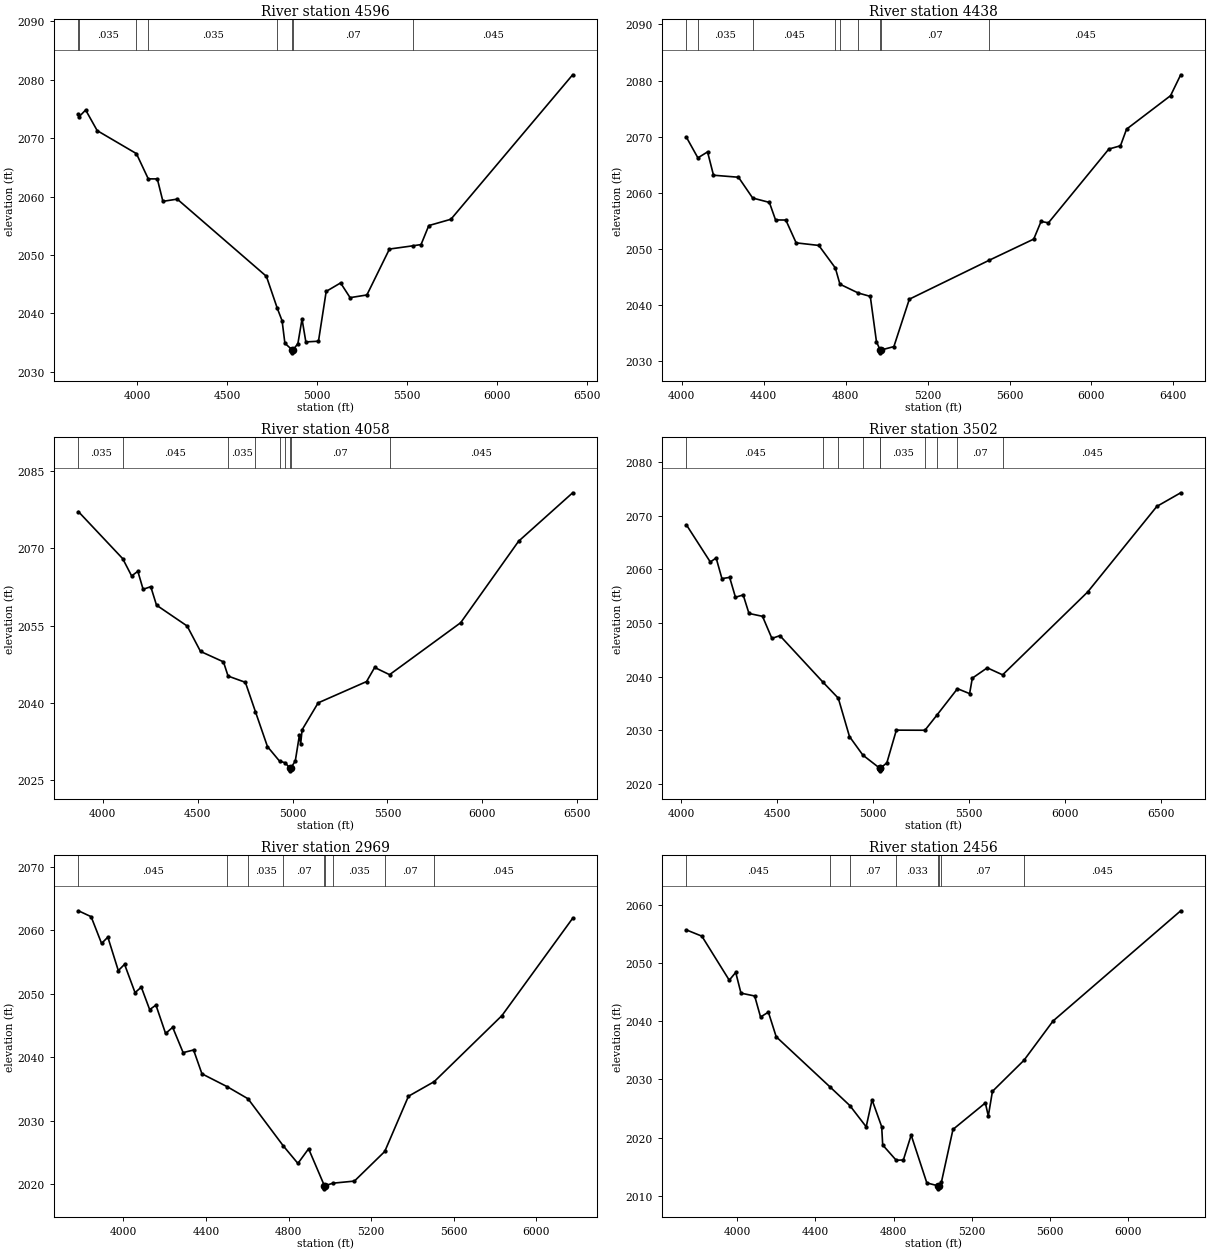
Type RM Length L Ch R = 1,4596,158,158,158
BEGIN DESCRIPTION:
Cottonwood Creek Trib118a 9.0
END DESCRIPTION:
XS GIS Cut Line= 3
      1363216.75      6934023.13      1363898.00      6932890.49
      1363175.33      6931662.37
#Sta/Elev= 30
  3675.0 2074.10  3678.4 2073.68  3715.1 2074.84  3779.2 2071.31  3997.2 2067.37
  4063.1 2063.05  4113.4 2063.04  4144.4 2059.20  4224.1 2059.58  4719.6 2046.36
  4780.1 2040.89  4806.8 2038.75  4822.4 2034.90  4863.1 2033.76  4863.4 2033.26
  4867.1 2033.76  4894.6 2034.83  4917.6 2039.05  4938.9 2035.13  5009.0 2035.25
  5051.9 2043.78  5131.9 2045.23  5184.7 2042.71  5278.1 2043.17  5403.4 2051.03
  5534.6 2051.59  5579.1 2051.80  5622.1 2055.05  5745.0 2056.13  6421.7 2080.87
#Mann=8,-1,0
  3675.0    0.07       0  3678.4   0.035       0  3997.2    0.07       0
  4063.1   0.035       0  4780.1    0.07       0  4863.1    0.07       0
  4867.1    0.07       0  5534.6   0.045       0
Bank Sta=4863.1,4867.1
Exp/Cntr=0.3,0.1

Type RM Length L Ch R = 1,4438,380,380,380
BEGIN DESCRIPTION:
Cottonwood Creek Trib118a 8.0
END DESCRIPTION:
XS GIS Cut Line= 4
      1364144.60      6933910.33      1364040.11      6932944.82
      1363956.52      6932627.18      1363321.62      6931712.43
#Sta/Elev= 30
  4022.5 2069.88  4078.2 2066.23  4125.4 2067.29  4154.4 2063.14  4276.3 2062.78
  4345.7 2059.08  4427.2 2058.30  4457.4 2055.18  4507.6 2055.16  4557.9 2051.10
  4668.6 2050.64  4749.3 2046.63  4771.7 2043.74  4861.3 2042.17  4920.0 2041.57
  4950.2 2033.48  4968.3 2032.02  4968.6 2031.52  4972.3 2032.02  5035.1 2032.63
  5110.6 2041.07  5499.9 2047.99  5718.0 2051.77  5753.8 2054.91  5789.6 2054.66
  6084.8 2067.80  6141.5 2068.38  6171.2 2071.34  6386.0 2077.30  6435.6 2081.02
#Mann=9,-1,0
  4022.5    0.07       0  4078.2   0.035       0  4345.7   0.045       0
  4749.3    0.07       0  4771.7   0.045       0  4861.3    0.07       0
  4968.3    0.07       0  4972.3    0.07       0  5499.9   0.045       0
Bank Sta=4968.3,4972.3
Exp/Cntr=0.3,0.1

Type RM Length L Ch R = 1,4058,556,556,556
BEGIN DESCRIPTION:
Cottonwood Creek Trib118a 7.0
END DESCRIPTION:
XS GIS Cut Line= 3
      1364508.21      6933906.11      1364370.29      6932794.36
      1363383.91      6931686.78
#Sta/Elev= 30
  3872.4 2077.13  4105.5 2068.00  4152.6 2064.64  4185.3 2065.54  4213.1 2062.04
  4253.4 2062.55  4283.6 2058.96  4444.9 2054.91  4515.4 2049.97  4636.3 2047.94
  4660.6 2045.18  4751.8 2043.96  4804.6 2038.27  4868.1 2031.47  4931.9 2028.64
  4961.5 2028.33  4986.3 2027.26  4986.6 2026.76  4990.3 2027.26  5014.7 2028.68
  5036.4 2033.69  5043.1 2032.01  5050.6 2034.74  5135.1 2039.97  5390.1 2044.11
  5432.8 2046.85  5511.3 2045.45  5885.9 2055.55  6191.1 2071.39  6475.8 2080.80
#Mann=9,-1,0
  3872.4   0.035       0  4105.5   0.045       0  4660.6   0.035       0
  4804.6    0.07       0  4931.9   0.035       0  4961.5    0.07       0
  4986.3    0.07       0  4990.3    0.07       0  5511.3   0.045       0
Bank Sta=4986.3,4990.3
Exp/Cntr=0.3,0.1

Type RM Length L Ch R = 1,3502,533,533,533
BEGIN DESCRIPTION:
Cottonwood Creek Trib118a 6.0
END DESCRIPTION:
XS GIS Cut Line= 3
      1364963.78      6933701.34      1364846.75      6932731.67
      1363722.45      6931594.83
#Sta/Elev= 30
  4028.0 2068.26  4152.2 2061.35  4182.5 2062.11  4212.7 2058.26  4253.0 2058.48
  4283.2 2054.78  4323.5 2055.21  4353.7 2051.76  4424.2 2051.22  4473.2 2047.10
  4514.9 2047.62  4740.0 2038.92  4819.1 2035.96  4877.5 2028.80  4947.3 2025.34
  5034.9 2022.91  5035.1 2022.41  5038.9 2022.91  5072.2 2023.90  5121.7 2030.00
  5270.7 2029.98  5333.7 2032.83  5440.2 2037.73  5503.5 2036.81  5517.6 2039.69
  5595.5 2041.62  5675.5 2040.31  6118.7 2055.76  6479.3 2071.72  6603.6 2074.26
#Mann=10,-1,0
  4028.0   0.045       0  4740.0   0.035       0  4819.1    0.07       0
  4947.3   0.035       0  5034.9   0.035       0  5038.9   0.035       0
  5270.7    0.07       0  5333.7   0.035       0  5440.2    0.07       0
  5675.5   0.045       0
Bank Sta=5034.9,5038.9
Exp/Cntr=0.3,0.1

Type RM Length L Ch R = 1,2969,513,513,513
BEGIN DESCRIPTION:
Cottonwood Creek Trib118a 5.0
END DESCRIPTION:
XS GIS Cut Line= 3
      1365335.76      6933638.63      1365147.68      6932443.28
      1364332.65      6931586.46
#Sta/Elev= 30
  3782.7 2063.05  3844.1 2062.12  3894.7 2057.91  3925.1 2058.90  3975.7 2053.63
  4006.0 2054.62  4056.7 2050.16  4087.0 2051.03  4127.5 2047.49  4157.9 2048.20
  4204.6 2043.73  4238.9 2044.70  4289.5 2040.72  4340.1 2041.13  4380.6 2037.38
  4503.6 2035.34  4603.7 2033.45  4774.5 2026.03  4845.2 2023.27  4896.9 2025.58
  4973.3 2019.77  4973.6 2019.27  4977.3 2019.77  5014.6 2020.16  5118.7 2020.49
  5265.5 2025.15  5380.4 2033.85  5505.0 2036.15  5833.0 2046.55  6175.3 2061.87
#Mann=9,-1,0
  3782.7   0.045       0  4503.6    0.07       0  4603.7   0.035       0
  4774.5    0.07       0  4973.3    0.07       0  4977.3    0.07       0
  5014.6   0.035       0  5265.5    0.07       0  5505.0   0.045       0
Bank Sta=4973.3,4977.3
Exp/Cntr=0.3,0.1

Type RM Length L Ch R = 1,2456,357,357,357
BEGIN DESCRIPTION:
Cottonwood Creek Trib118a 4.0
END DESCRIPTION:
XS GIS Cut Line= 3
      1365619.96      6933546.62      1365569.81      6932288.64
      1364509.11      6931591.25
#Sta/Elev= 30
  3740.1 2055.74  3818.8 2054.67  3958.9 2047.09  3992.0 2048.43  4018.9 2044.86
  4089.0 2044.37  4119.0 2040.75  4159.1 2041.59  4199.1 2037.35  4473.9 2028.73
  4576.0 2025.50  4659.5 2021.85  4689.5 2026.49  4738.8 2021.86  4743.9 2018.72
  4813.1 2016.09  4849.6 2016.14  4889.6 2020.42  4969.7 2012.19  5029.2 2011.67
  5029.4 2011.17  5033.2 2011.67  5044.3 2012.32  5103.5 2021.40  5269.1 2025.96
  5284.2 2023.71  5305.3 2027.95  5466.6 2033.30  5615.6 2040.07  6268.5 2059.04
#Mann=8,-1,0
  3740.1   0.045       0  4473.9   0.035       0  4576.0    0.07       0
  4813.1   0.033       0  5029.2   0.033       0  5033.2   0.033       0
  5044.3    0.07       0  5466.6   0.045       0
Bank Sta=5029.2,5033.2
Exp/Cntr=0.3,0.1

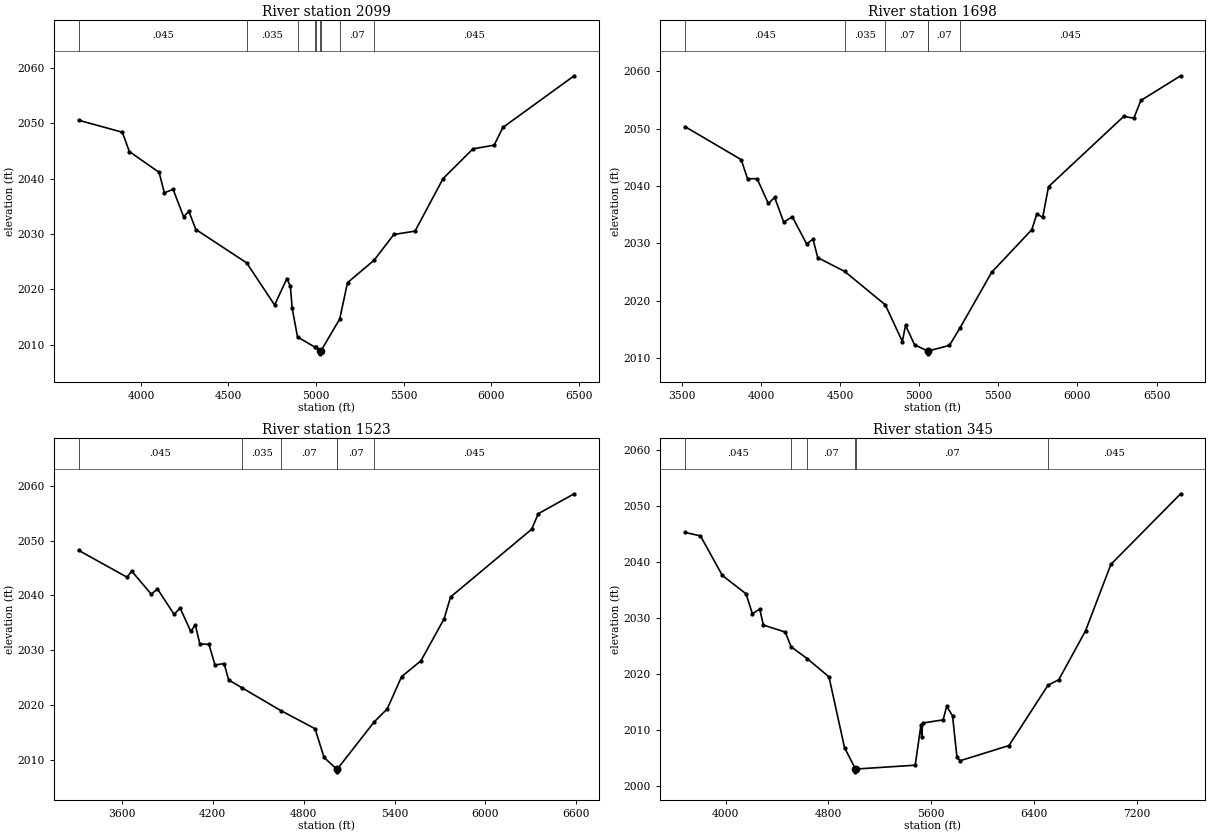
Type RM Length L Ch R = 1,2099,401,401,401
BEGIN DESCRIPTION:
Cottonwood Creek Trib118a 3.0
END DESCRIPTION:
XS GIS Cut Line= 3
      1365862.37      6933588.44      1365887.45      6932242.66
      1364570.94      6931553.06
#Sta/Elev= 30
  3643.0 2050.52  3893.5 2048.35  3933.5 2044.87  4103.5 2041.11  4133.5 2037.43
  4183.5 2038.05  4243.5 2033.12  4273.6 2034.07  4313.6 2030.81  4604.0 2024.79
  4763.6 2017.19  4833.6 2021.97  4853.7 2020.55  4863.7 2016.66  4894.4 2011.43
  4996.4 2009.56  4998.8 2009.64  5023.6 2008.89  5023.9 2008.39  5027.6 2008.89
  5135.4 2014.66  5180.1 2021.23  5331.4 2025.25  5444.9 2029.91  5566.0 2030.52
  5726.1 2039.99  5897.0 2045.35  6018.1 2046.02  6067.9 2049.21  6475.2 2058.53
#Mann=9,-1,0
  3643.0   0.045       0  4604.0   0.035       0  4894.4   0.033       0
  4996.4   0.035       0  4998.8   0.033       0  5023.6   0.033       0
  5027.6   0.033       0  5135.4    0.07       0  5331.4   0.045       0
Bank Sta=5023.6,5027.6
Exp/Cntr=0.3,0.1

Type RM Length L Ch R = 1,1698,175,175,175
BEGIN DESCRIPTION:
Cottonwood Creek Trib118a 2.0
END DESCRIPTION:
XS GIS Cut Line= 5
      1365966.86      6933580.08      1366154.94      6932175.79
      1366092.24      6932125.64      1365954.32      6932012.79
      1364575.06      6931540.50
#Sta/Elev= 30
  3519.2 2050.36  3874.4 2044.60  3914.6 2041.28  3975.3 2041.27  4045.9 2036.96
  4086.3 2038.00  4143.6 2033.67  4197.3 2034.65  4288.1 2029.92  4328.4 2030.72
  4358.7 2027.51  4528.7 2025.11  4785.3 2019.29  4893.4 2012.89  4913.6 2015.72
  4970.2 2012.33  5053.0 2011.24  5053.3 2010.74  5057.0 2011.24  5190.7 2012.21
  5258.1 2015.27  5458.0 2024.96  5711.7 2032.39  5743.4 2035.14  5780.4 2034.53
  5817.4 2039.89  6293.1 2052.15  6356.5 2051.82  6400.9 2054.91  6652.4 2059.22
#Mann=6,-1,0
  3519.2   0.045       0  4528.7   0.035       0  4785.3    0.07       0
  5053.0    0.07       0  5057.0    0.07       0  5258.1   0.045       0
Bank Sta=5053,5057
Exp/Cntr=0.3,0.1

Type RM Length L Ch R = 1,1523,1178,1178,1178
BEGIN DESCRIPTION:
Cottonwood Creek Trib118a 1.0
END DESCRIPTION:
XS GIS Cut Line= 4
      1366172.83      6933638.42      1366217.87      6932025.90
      1366136.80      6931962.84      1364659.77      6931476.50
#Sta/Elev= 30
  3314.5 2048.24  3635.0 2043.32  3665.1 2044.46  3795.1 2040.21  3835.1 2041.21
  3945.2 2036.55  3985.2 2037.69  4055.2 2033.43  4085.2 2034.62  4115.2 2031.16
  4175.3 2031.06  4215.3 2027.31  4275.3 2027.57  4305.3 2024.58  4396.0 2023.10
  4648.7 2019.00  4875.5 2015.68  4935.0 2010.43  5018.1 2008.31  5018.3 2007.81
  5022.1 2008.31  5265.4 2016.91  5351.5 2019.29  5446.8 2025.19  5573.9 2028.06
  5727.1 2035.73  5769.9 2039.72  6304.9 2052.08  6348.3 2054.91  6585.4 2058.55
#Mann=6,-1,0
  3314.5   0.045       0  4396.0   0.035       0  4648.7    0.07       0
  5018.1    0.07       0  5022.1    0.07       0  5265.4   0.045       0
Bank Sta=5018.1,5022.1
Exp/Cntr=0.3,0.1

Type RM Length L Ch R = 1,345,0,0,0
BEGIN DESCRIPTION:
Cottonwood Creek Trib118a 0.5
END DESCRIPTION:
XS GIS Cut Line= 6
      1366233.74      6933546.93      1367046.25      6932595.53
      1367051.21      6932470.34      1367087.92      6932296.91
      1366726.81      6932046.91      1364932.58      6931540.56
#Sta/Elev= 30
  3683.5 2045.33  3804.0 2044.72  3974.1 2037.64  4158.6 2034.35  4208.1 2030.78
  4265.1 2031.62  4293.6 2028.76  4463.8 2027.51  4509.1 2024.88  4635.8 2022.74
  4804.1 2019.49  4924.9 2006.85  5010.2 2003.00  5010.5 2002.50  5014.2 2003.00
  5475.2 2003.69  5519.8 2010.87  5525.9 2008.75  5532.6 2011.23  5692.3 2011.80
  5719.8 2014.20  5765.5 2012.55  5799.5 2005.20  5823.7 2004.48  6204.6 2007.20
  6508.0 2017.98  6592.6 2018.99  6800.5 2027.72  6997.9 2039.62  7540.7 2052.25
#Mann=6,-1,0
  3683.5   0.045       0  4509.1   0.035       0  4635.8    0.07       0
  5010.2    0.07       0  5014.2    0.07       0  6508.0   0.045       0
Bank Sta=5010.2,5014.2
Exp/Cntr=0.3,0.1

Chan Stop Cuts=-1