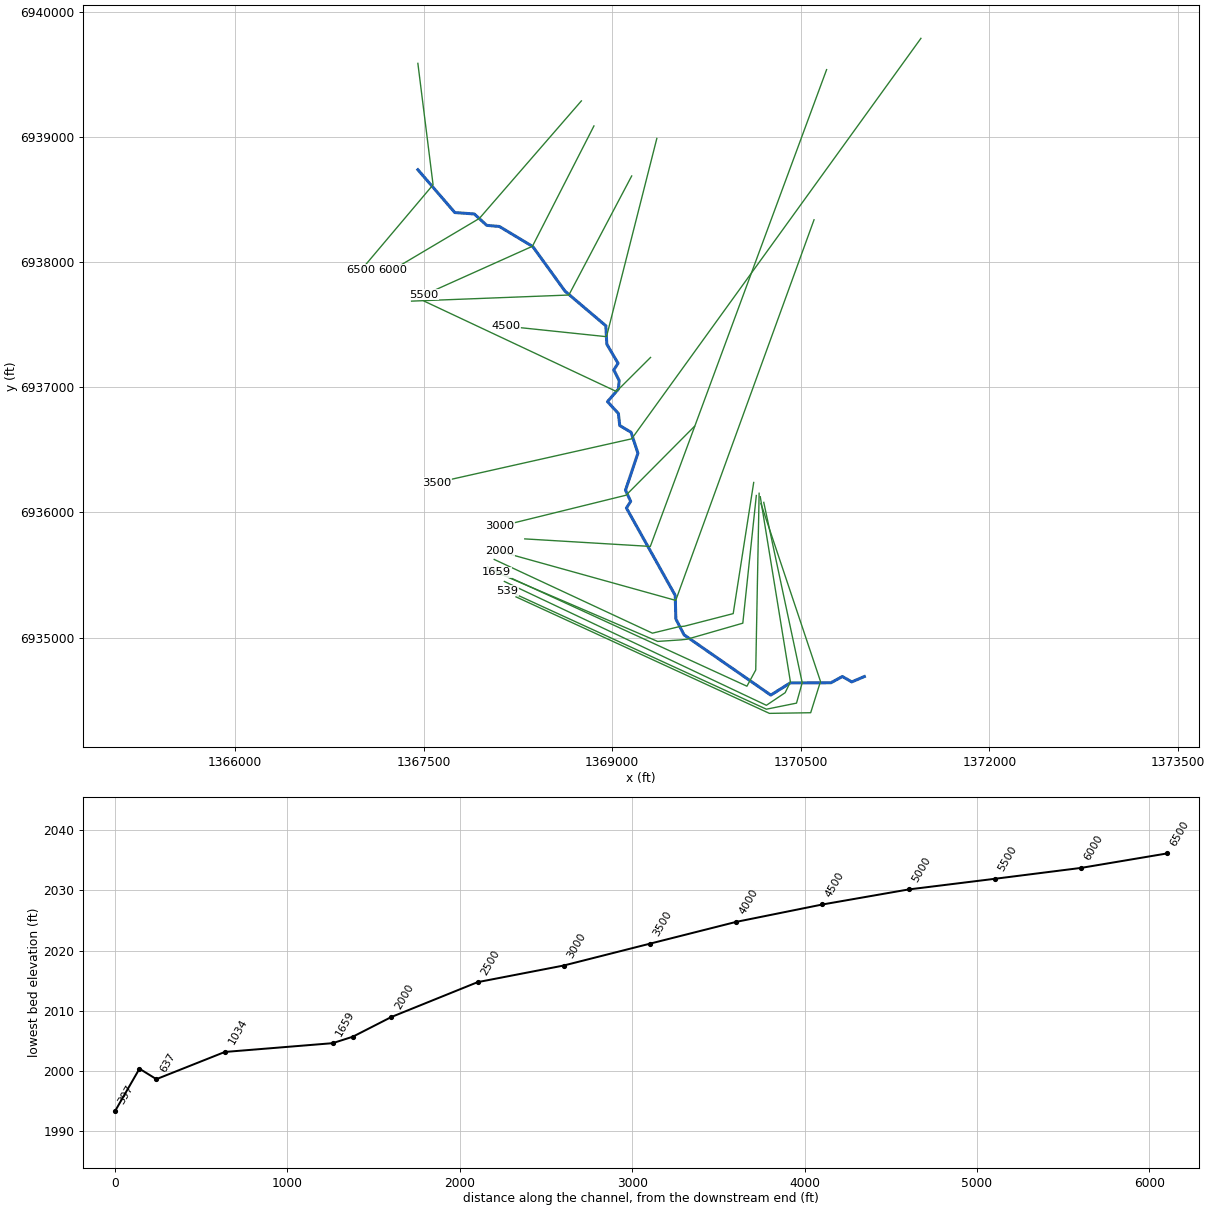
--- Cottonwood Creek Trib119.prj (project) ---

Proj Title=Cottonwood Creek Trib119 Base Level Engineering
Current Plan=p01
Default Exp/Contr=0.3,0.1
English Units
Geom File=g01
Flow File=f01
Plan File=p01
BEGIN DESCRIPTION:
Cottonwood Creek Trib119
END DESCRIPTION:

--- Cottonwood Creek Trib119.p01 (plan) ---

Plan Title=Multiple Run
Short Identifier=Multiple
Geom File=g01
Flow File=f01
Subcritical Flow
K Sum by GR= 0
Std Step Tol= 0.01
Critical Tol= 0.01
Num of Std Step Trials= 20
Max Error Tol= 0.3
Flow Tol Ratio= 0.001
Split Flow NTrial= 30
Split Flow Tol= 0.02
Split Flow Ratio= 0.02
Log Output Level= 0
Friction Slope Method= 1
Unsteady Friction Slope Method= 2
Unsteady Bridges Friction Slope Method= 1
Parabolic Critical Depth
Global Vel Dist=  1 , 1 , 1
Global Log Level= 0
CheckData=True
Encroach Param= -1, 0, 0, 0
BEGIN DESCRIPTION:
Multiple Run
END DESCRIPTION:

--- Cottonwood Creek Trib119.f01 (steady flow) ---

Flow Title=Multiple
Number of Profiles=7
Profile Names=10-year,25-year,50-year,1pct_min,100-year,1pct_plu,500-year
River Rch & RM= Cottonwood Creek,Reach-1,6500
     229     320     395     243     484     966     737
River Rch & RM= Cottonwood Creek,Reach-1,2500
     262     370     460     285     568    1133     876
Boundary for River Rch & Prof#=Cottonwood Creek,Reach-1,1
Up Type=0
Dn Type=3
Dn Slope=0.005
Boundary for River Rch & Prof#=Cottonwood Creek,Reach-1,2
Up Type=0
Dn Type=3
Dn Slope=0.005
Boundary for River Rch & Prof#=Cottonwood Creek,Reach-1,3
Up Type=0
Dn Type=3
Dn Slope=0.005
Boundary for River Rch & Prof#=Cottonwood Creek,Reach-1,4
Up Type=0
Dn Type=3
Dn Slope=0.005
Boundary for River Rch & Prof#=Cottonwood Creek,Reach-1,5
Up Type=0
Dn Type=3
Dn Slope=0.005
Boundary for River Rch & Prof#=Cottonwood Creek,Reach-1,6
Up Type=0
Dn Type=3
Dn Slope=0.005
Boundary for River Rch & Prof#=Cottonwood Creek,Reach-1,7
Up Type=0
Dn Type=3
Dn Slope=0.005

--- Cottonwood Creek Trib119.g01 (geometry) ---

Geom Title=Existing Conditions

River Reach=Cottonwood Creek,Reach-1
Reach XY= 30
      1367455.00      6938738.00      1367748.81      6938395.82
      1367903.53      6938384.44      1368002.58      6938293.54
      1368103.50      6938284.37      1368368.24      6938124.39
      1368624.77      6937767.87      1368949.64      6937490.70
      1368957.25      6937343.93      1369046.76      6937191.23
      1369012.80      6937138.10      1369055.67      6937053.08
      1369049.57      6936985.57      1368962.61      6936884.67
      1369049.42      6936790.37      1369060.29      6936693.49
      1369149.54      6936640.66      1369204.62      6936472.73
      1369105.81      6936177.29      1369147.17      6936087.92
      1369113.24      6936034.77      1369501.25      6935336.45
      1369506.20      6935148.50      1369571.63      6935021.29
      1370261.12      6934539.76      1370415.44      6934636.94
      1370739.79      6934638.54      1370830.04      6934688.32
      1370905.03      6934645.35      1371005.00      6934688.00

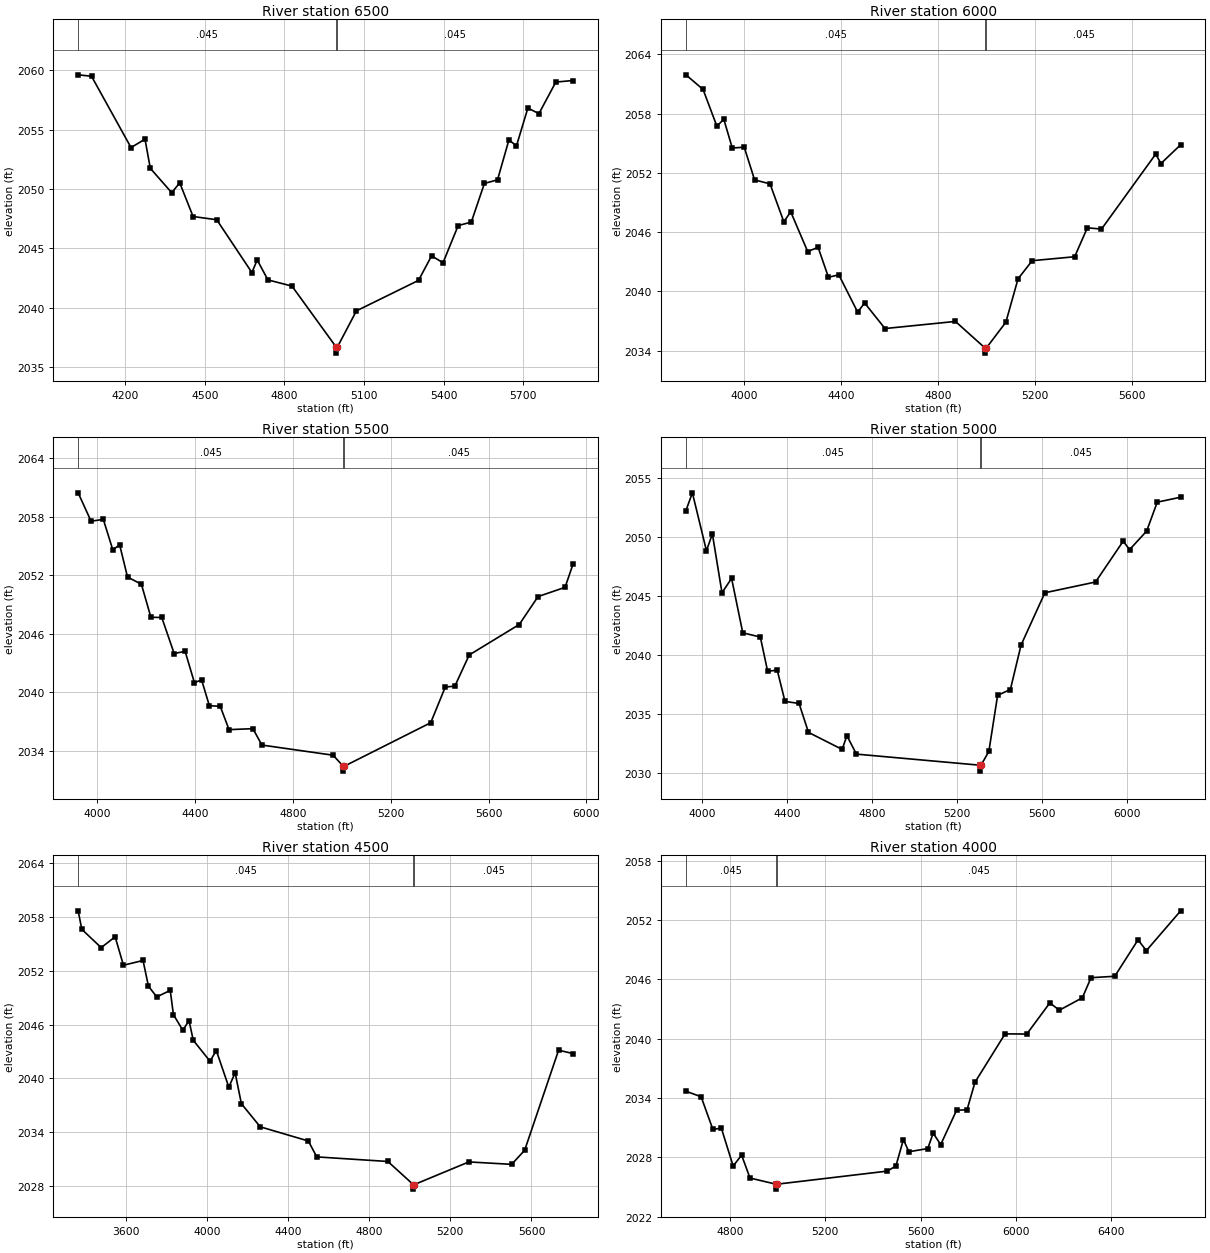
Type RM Length L Ch R = 1,6500,500,500,500
BEGIN DESCRIPTION:
Cottonwood Creek Trib119 13.0
END DESCRIPTION:
XS GIS Cut Line= 3
      1367454.99      6939588.05      1367575.86      6938617.65
      1367004.99      6937937.99
#Sta/Elev= 30
  4022.1 2059.61  4072.5 2059.49  4221.5 2053.48  4274.1 2054.19  4294.2 2051.73
  4374.9 2049.68  4405.1 2050.51  4455.5 2047.67  4544.6 2047.40  4677.2 2042.95
  4697.3 2044.01  4737.6 2042.33  4828.3 2041.81  4995.3 2036.66  4995.6 2036.16
  4999.3 2036.66  5071.3 2039.72  5305.5 2042.29  5354.9 2044.36  5397.8 2043.77
  5455.1 2046.91  5504.5 2047.20  5553.9 2050.46  5603.4 2050.76  5646.3 2054.12
  5674.9 2053.63  5717.8 2056.81  5759.5 2056.34  5823.2 2059.00  5887.6 2059.13
#Mann=3,-1,0
  4022.1   0.045       0  4995.3   0.045       0  4999.3   0.045       0
Bank Sta=4995.3,4999.3
Exp/Cntr=0.3,0.1

Type RM Length L Ch R = 1,6000,500,500,500
BEGIN DESCRIPTION:
Cottonwood Creek Trib119 12.0
END DESCRIPTION:
XS GIS Cut Line= 3
      1368754.98      6939287.98      1367944.24      6938349.07
      1367255.01      6937938.01
#Sta/Elev= 30
  3759.5 2061.93  3830.2 2060.45  3887.3 2056.73  3915.8 2057.43  3950.9 2054.52
  4000.3 2054.60  4043.0 2051.29  4106.7 2050.89  4163.7 2047.05  4192.2 2048.06
  4262.4 2044.03  4305.2 2044.47  4348.0 2041.43  4390.8 2041.68  4468.6 2037.90
  4497.2 2038.83  4581.6 2036.24  4872.3 2036.96  4995.4 2034.25  4995.7 2033.75
  4999.4 2034.25  5080.6 2036.88  5131.0 2041.28  5189.4 2043.11  5364.6 2043.51
  5417.1 2046.44  5475.5 2046.31  5699.3 2053.90  5721.0 2052.95  5802.5 2054.85
#Mann=3,-1,0
  3759.5   0.045       0  4995.4   0.045       0  4999.4   0.045       0
Bank Sta=4995.4,4999.4
Exp/Cntr=0.3,0.1

Type RM Length L Ch R = 1,5500,500,500,500
BEGIN DESCRIPTION:
Cottonwood Creek Trib119 11.0
END DESCRIPTION:
XS GIS Cut Line= 3
      1368854.98      6939087.96      1368365.89      6938126.29
      1367505.00      6937738.00
#Sta/Elev= 30
  3921.1 2060.45  3973.9 2057.54  4024.0 2057.73  4062.9 2054.60  4090.7 2055.13
  4123.0 2051.82  4179.7 2051.09  4218.6 2047.70  4263.1 2047.68  4313.7 2043.99
  4358.6 2044.21  4396.6 2041.00  4425.9 2041.29  4457.7 2038.64  4502.2 2038.58
  4538.1 2036.19  4635.7 2036.29  4672.7 2034.61  4963.8 2033.57  5005.2 2032.44
  5005.5 2031.94  5009.2 2032.44  5363.0 2036.90  5422.4 2040.55  5461.7 2040.65
  5520.4 2043.84  5725.0 2046.96  5801.8 2049.82  5912.4 2050.77  5944.4 2053.11
#Mann=3,-1,0
  3921.1   0.045       0  5005.2   0.045       0  5009.2   0.045       0
Bank Sta=5005.2,5009.2
Exp/Cntr=0.3,0.1

Type RM Length L Ch R = 1,5000,500,500,500
BEGIN DESCRIPTION:
Cottonwood Creek Trib119 10.0
END DESCRIPTION:
XS GIS Cut Line= 3
      1369155.02      6938688.04      1368655.58      6937736.78
      1367405.03      6937688.00
#Sta/Elev= 30
  3925.6 2052.23  3955.9 2053.73  4022.0 2048.83  4049.9 2050.25  4095.1 2045.27
  4140.2 2046.49  4192.8 2041.88  4275.4 2041.52  4309.7 2038.62  4354.8 2038.72
  4391.3 2036.07  4457.4 2035.90  4501.7 2033.45  4659.8 2032.01  4682.4 2033.16
  4727.1 2031.61  5308.8 2030.67  5309.1 2030.17  5312.8 2030.67  5349.7 2031.84
  5390.9 2036.59  5450.9 2037.08  5501.0 2040.84  5613.1 2045.27  5851.2 2046.18
  5981.3 2049.64  6011.3 2048.92  6091.4 2050.49  6141.4 2052.94  6251.5 2053.36
#Mann=3,-1,0
  3925.6   0.045       0  5308.8   0.045       0  5312.8   0.045       0
Bank Sta=5308.8,5312.8
Exp/Cntr=0.3,0.1

Type RM Length L Ch R = 1,4500,500,500,500
BEGIN DESCRIPTION:
Cottonwood Creek Trib119 9.0
END DESCRIPTION:
XS GIS Cut Line= 3
      1369355.01      6938988.03      1368954.88      6937403.88
      1368154.99      6937488.00
#Sta/Elev= 30
  3366.1 2058.67  3384.1 2056.61  3479.6 2054.57  3548.3 2055.78  3589.3 2052.61
  3685.9 2053.14  3712.4 2050.28  3753.5 2049.08  3819.9 2049.81  3835.6 2047.11
  3881.8 2045.37  3912.5 2046.44  3933.4 2044.25  4015.9 2041.92  4046.9 2043.11
  4108.7 2039.03  4139.7 2040.63  4170.6 2037.18  4263.5 2034.61  4500.7 2033.03
  4541.9 2031.26  4892.4 2030.75  5018.0 2028.17  5018.2 2027.67  5022.0 2028.17
  5291.5 2030.70  5502.6 2030.43  5566.6 2032.00  5733.9 2043.15  5804.3 2042.77
#Mann=3,-1,0
  3366.1   0.045       0  5018.0   0.045       0  5022.0   0.045       0
Bank Sta=5018,5022
Exp/Cntr=0.3,0.1

Type RM Length L Ch R = 1,4000,500,500,500
BEGIN DESCRIPTION:
Cottonwood Creek Trib119 8.0
END DESCRIPTION:
XS GIS Cut Line= 3
      1369305.01      6937238.01      1369033.45      6936965.94
      1367505.02      6937687.99
#Sta/Elev= 30
  4615.6 2034.68  4679.3 2034.12  4728.7 2030.81  4764.1 2030.95  4813.6 2027.11
  4849.0 2028.22  4884.3 2025.90  4993.4 2025.28  4993.6 2024.78  4997.4 2025.28
  5459.3 2026.60  5496.0 2027.11  5527.6 2029.79  5550.4 2028.56  5629.7 2028.88
  5652.5 2030.44  5684.0 2029.28  5750.4 2032.75  5794.6 2032.81  5827.8 2035.59
  5954.0 2040.48  6045.0 2040.46  6141.6 2043.61  6181.6 2042.87  6278.2 2044.13
  6314.4 2046.16  6413.9 2046.30  6511.4 2049.98  6546.6 2048.90  6690.4 2052.92
#Mann=3,-1,0
  4615.6   0.045       0  4993.4   0.045       0  4997.4   0.045       0
Bank Sta=4993.4,4997.4
Exp/Cntr=0.3,0.1

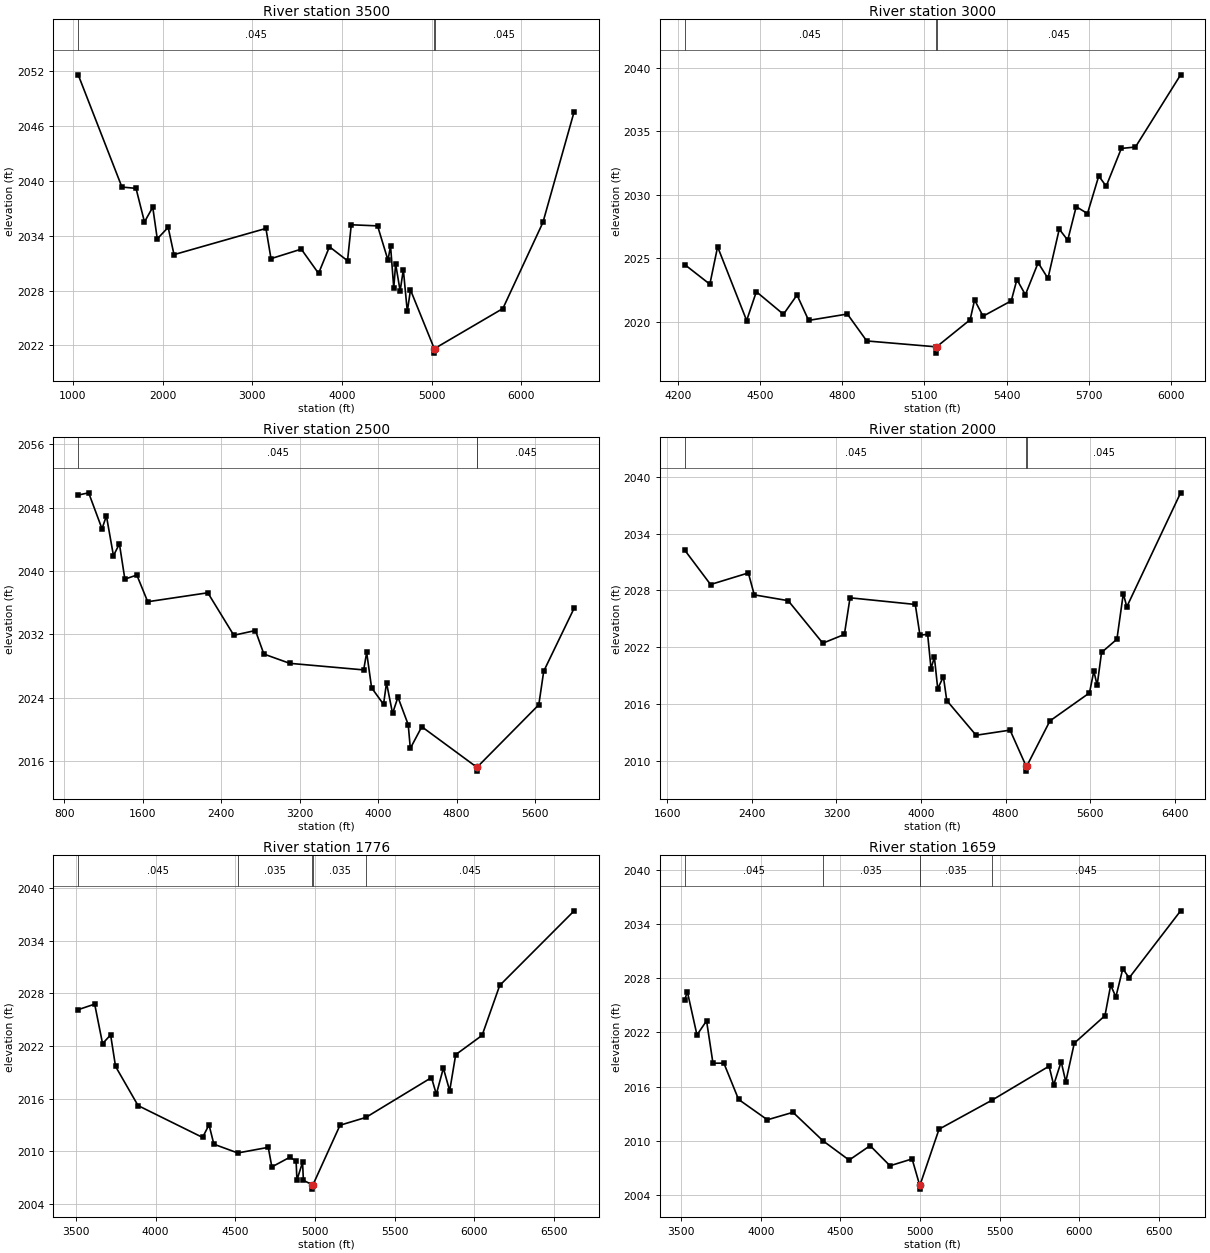
Type RM Length L Ch R = 1,3500,500,500,500
BEGIN DESCRIPTION:
Cottonwood Creek Trib119 7.0
END DESCRIPTION:
XS GIS Cut Line= 3
      1371454.99      6939787.98      1369155.06      6936587.70
      1367605.01      6936238.00
#Sta/Elev= 30
  1059.0 2051.56  1546.4 2039.30  1703.5 2039.16  1797.8 2035.49  1890.1 2037.10
  1940.5 2033.64  2062.0 2034.90  2127.1 2031.92  3152.2 2034.78  3208.7 2031.48
  3546.3 2032.52  3739.0 2029.87  3860.6 2032.78  4061.9 2031.25  4103.7 2035.18
  4397.1 2035.06  4512.5 2031.33  4541.9 2032.84  4577.5 2028.27  4598.4 2030.91
  4648.7 2027.95  4684.3 2030.28  4728.5 2025.71  4764.1 2028.06  5028.8 2021.66
  5029.1 2021.16  5032.8 2021.66  5794.2 2026.03  6240.5 2035.43  6589.0 2047.54
#Mann=3,-1,0
  1059.0   0.045       0  5028.8   0.045       0  5032.8   0.045       0
Bank Sta=5028.8,5032.8
Exp/Cntr=0.3,0.1

Type RM Length L Ch R = 1,3000,500,500,500
BEGIN DESCRIPTION:
Cottonwood Creek Trib119 6.0
END DESCRIPTION:
XS GIS Cut Line= 3
      1369654.98      6936687.98      1369109.97      6936136.99
      1368104.95      6935887.99
#Sta/Elev= 30
  4225.0 2024.51  4316.9 2022.96  4345.2 2025.91  4451.2 2020.10  4486.6 2022.37
  4585.6 2020.59  4635.1 2022.11  4677.5 2020.11  4818.9 2020.61  4889.6 2018.49
  5140.8 2018.03  5141.0 2017.53  5144.8 2018.03  5267.0 2020.16  5283.3 2021.72
  5314.2 2020.44  5417.2 2021.65  5437.8 2023.33  5468.7 2022.13  5515.3 2024.65
  5551.1 2023.42  5592.4 2027.30  5623.3 2026.43  5654.2 2029.07  5695.4 2028.53
  5736.6 2031.49  5763.7 2030.68  5819.0 2033.66  5870.5 2033.77  6035.4 2039.46
#Mann=3,-1,0
  4225.0   0.045       0  5140.8   0.045       0  5144.8   0.045       0
Bank Sta=5140.8,5144.8
Exp/Cntr=0.3,0.1

Type RM Length L Ch R = 1,2500,500,500,500
BEGIN DESCRIPTION:
Cottonwood Creek Trib119 5.0
END DESCRIPTION:
XS GIS Cut Line= 3
      1370704.99      6939537.96      1369303.38      6935727.88
      1368304.99      6935788.00
#Sta/Elev= 30
   940.3 2049.59  1046.9 2049.87  1183.2 2045.33  1227.9 2046.97  1299.8 2041.94
  1360.7 2043.43  1416.3 2038.98  1538.2 2039.50  1649.4 2036.13  2262.5 2037.26
  2527.9 2031.90  2748.4 2032.50  2834.5 2029.53  3098.0 2028.36  3852.8 2027.53
  3883.3 2029.73  3933.6 2025.27  4055.4 2023.19  4085.9 2025.90  4147.5 2022.04
  4202.4 2024.09  4307.3 2020.62  4328.6 2017.63  4445.8 2020.36  5006.4 2015.26
  5006.6 2014.76  5010.4 2015.26  5639.5 2023.13  5689.6 2027.36  6000.2 2035.32
#Mann=3,-1,0
   940.3   0.045       0  5006.4   0.045       0  5010.4   0.045       0
Bank Sta=5006.4,5010.4
Exp/Cntr=0.3,0.1

Type RM Length L Ch R = 1,2000,224,224,224
BEGIN DESCRIPTION:
Cottonwood Creek Trib119 4.0
END DESCRIPTION:
XS GIS Cut Line= 3
      1370605.01      6938338.02      1369505.42      6935296.48
      1368105.02      6935687.99
#Sta/Elev= 30
  1765.8 2032.26  2010.4 2028.63  2367.7 2029.85  2423.7 2027.54  2744.1 2026.93
  3071.6 2022.45  3275.5 2023.37  3328.9 2027.23  3945.7 2026.53  3990.0 2023.29
  4062.6 2023.39  4094.5 2019.77  4126.4 2020.97  4158.0 2017.65  4211.5 2018.92
  4243.4 2016.41  4520.6 2012.75  4841.8 2013.29  4994.5 2009.47  4994.7 2008.97
  4998.6 2009.47  5218.5 2014.26  5592.3 2017.21  5633.8 2019.51  5665.0 2018.01
  5706.5 2021.47  5851.9 2022.87  5912.3 2027.67  5945.3 2026.28  6454.1 2038.29
#Mann=3,-1,0
  1765.8   0.045       0  4994.5   0.045       0  4998.6   0.045       0
Bank Sta=4994.5,4998.6
Exp/Cntr=0.3,0.1

Type RM Length L Ch R = 1,1776,117,117,117
BEGIN DESCRIPTION:
Cottonwood Creek Trib119 3.0
END DESCRIPTION:
XS GIS Cut Line= 6
      1370125.29      6936238.89      1369962.27      6935190.89
      1369575.43      6935090.66      1369526.91      6935085.27
      1369319.91      6935034.64      1368062.03      6935623.68
#Sta/Elev= 30
  3514.2 2026.14  3617.5 2026.77  3666.9 2022.27  3717.5 2023.26  3748.4 2019.67
  3889.6 2015.21  4294.4 2011.58  4334.8 2013.02  4365.2 2010.81  4515.0 2009.81
  4706.3 2010.45  4729.0 2008.22  4840.4 2009.31  4881.0 2008.92  4886.2 2006.73
  4921.6 2008.74  4926.8 2006.69  4982.9 2006.19  4983.1 2005.69  4987.0 2006.19
  5156.5 2012.97  5318.8 2013.86  5730.4 2018.40  5760.7 2016.50  5804.9 2019.48
  5844.5 2016.89  5882.2 2021.01  6047.8 2023.21  6158.3 2028.90  6625.3 2037.40
#Mann=5,-1,0
  3514.2   0.045       0  4515.0   0.035       0  4982.9   0.035       0
  4987.0   0.035       0  5318.8   0.045       0
Bank Sta=4982.9,4987
Exp/Cntr=0.3,0.1

Type RM Length L Ch R = 1,1659,625,625,625
BEGIN DESCRIPTION:
Cottonwood Creek Trib119 2.5
END DESCRIPTION:
XS GIS Cut Line= 6
      1370146.13      6936134.73      1370038.66      6935114.50
      1369596.26      6934986.50      1369547.74      6934981.11
      1369361.57      6934968.67      1368081.44      6935520.19
#Sta/Elev= 30
  3521.4 2025.60  3538.2 2026.52  3598.6 2021.72  3658.9 2023.29  3699.1 2018.59
  3767.6 2018.59  3860.0 2014.57  4041.0 2012.31  4201.9 2013.14  4390.2 2009.98
  4554.5 2007.84  4686.4 2009.44  4811.3 2007.21  4950.2 2007.97  4996.7 2005.12
  4996.9 2004.62  5000.8 2005.12  5119.5 2011.27  5451.4 2014.48  5810.7 2018.26
  5839.6 2016.17  5886.7 2018.76  5915.6 2016.52  5969.0 2020.81  6161.8 2023.86
  6197.7 2027.24  6230.3 2025.94  6273.9 2029.07  6313.8 2028.05  6637.1 2035.49
#Mann=5,-1,0
  3521.4   0.045       0  4390.2   0.035       0  4996.7   0.035       0
  5000.8   0.035       0  5451.4   0.045       0
Bank Sta=4996.7,5000.8
Exp/Cntr=0.3,0.1

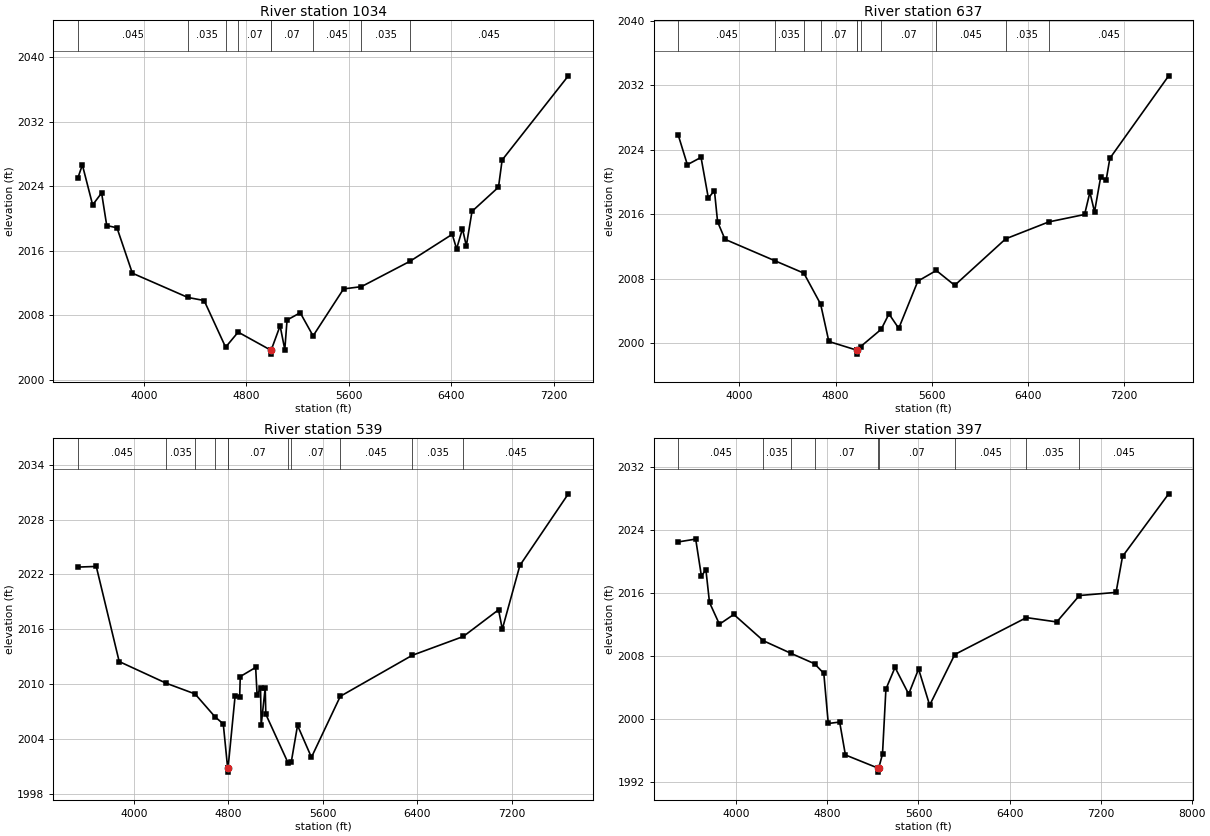
Type RM Length L Ch R = 1,1034,397,397,397
BEGIN DESCRIPTION:
Cottonwood Creek Trib119 2.0
END DESCRIPTION:
XS GIS Cut Line= 4
      1370168.43      6936152.63      1370141.47      6934740.26
      1370071.39      6934610.87      1368012.03      6935559.69
#Sta/Elev= 30
  3484.9 2025.04  3519.5 2026.63  3599.6 2021.67  3669.6 2023.15  3709.6 2019.11
  3789.6 2018.83  3909.6 2013.20  4342.9 2010.19  4469.7 2009.81  4637.4 2004.02
  4735.3 2005.89  4989.0 2003.66  4989.3 2003.16  4993.2 2003.66  5062.7 2006.67
  5099.4 2003.72  5116.9 2007.39  5219.7 2008.29  5320.2 2005.42  5558.2 2011.25
  5697.3 2011.53  6075.6 2014.67  6406.0 2018.02  6440.2 2016.22  6486.1 2018.71
  6516.1 2016.58  6560.5 2020.87  6767.1 2023.87  6795.6 2027.24  7312.1 2037.68
#Mann=9,-1,0
  3484.9   0.045       0  4342.9   0.035       0  4637.4   0.045       0
  4735.3    0.07       0  4989.0    0.07       0  4993.2    0.07       0
  5320.2   0.045       0  5697.3   0.035       0  6075.6   0.045       0
Bank Sta=4989,4993.2
Exp/Cntr=0.3,0.1

Type RM Length L Ch R = 1,637,98,98,98
BEGIN DESCRIPTION:
Cottonwood Creek Trib119 1.1
END DESCRIPTION:
XS GIS Cut Line= 5
      1370177.55      6936124.91      1370417.13      6934645.75
      1370375.46      6934558.95      1370226.16      6934458.25
      1368142.84      6935447.83
#Sta/Elev= 30
  3491.1 2025.81  3566.5 2022.15  3680.4 2023.06  3741.2 2018.01  3791.9 2018.93
  3818.2 2015.06  3879.8 2012.89  4293.3 2010.24  4536.1 2008.69  4675.6 2004.85
  4744.1 2000.21  4975.0 1999.14  4975.3 1998.64  4979.2 1999.14  5009.0 1999.58
  5179.7 2001.72  5244.4 2003.63  5325.8 2001.84  5484.9 2007.70  5638.4 2009.02
  5791.4 2007.18  6215.9 2012.95  6574.5 2015.05  6872.5 2015.97  6916.7 2018.73
  6955.3 2016.30  7006.3 2020.61  7051.7 2020.21  7082.8 2022.94  7572.3 2033.18
#Mann=11,-1,0
  3491.1   0.045       0  4293.3   0.035       0  4536.1   0.045       0
  4675.6    0.07       0  4975.0    0.07       0  4979.2    0.07       0
  5009.0   0.035       0  5179.7    0.07       0  5638.4   0.045       0
  6215.9   0.035       0  6574.5   0.045       0
Bank Sta=4975,4979.2
Exp/Cntr=0.3,0.1

Type RM Length L Ch R = 1,539,142,142,142
BEGIN DESCRIPTION:
Cottonwood Creek Trib119 1.0
END DESCRIPTION:
XS GIS Cut Line= 5
      1370205.32      6936079.81      1370510.88      6934638.81
      1370465.74      6934475.62      1370226.16      6934427.00
      1368168.38      6935375.09
#Sta/Elev= 30
  3526.2 2022.80  3681.4 2022.87  3875.6 2012.47  4275.7 2010.09  4518.0 2008.93
  4686.0 2006.44  4756.9 2005.65  4793.5 2000.88  4793.8 2000.38  4797.7 2000.88
  4857.0 2008.70  4895.7 2008.61  4900.8 2010.83  5031.2 2011.83  5043.4 2008.78
  5072.5 2009.59  5077.7 2005.49  5112.0 2009.60  5117.2 2006.71  5305.6 2001.39
  5332.2 2001.45  5385.8 2005.49  5503.5 2002.00  5747.9 2008.67  6356.5 2013.15
  6789.2 2015.21  7087.9 2018.13  7119.7 2016.01  7268.5 2022.98  7678.7 2030.81
#Mann=11,-1,0
  3526.2   0.045       0  4275.7   0.035       0  4518.0   0.045       0
  4686.0    0.07       0  4793.5    0.07       0  4797.7    0.07       0
  5305.6   0.035       0  5332.2    0.07       0  5747.9   0.045       0
  6356.5   0.035       0  6789.2   0.045       0
Bank Sta=4793.5,4797.7
Exp/Cntr=0.3,0.1

Type RM Length L Ch R = 1,397,0,0,0
BEGIN DESCRIPTION:
Cottonwood Creek Trib119 0.5
END DESCRIPTION:
XS GIS Cut Line= 5
      1370182.54      6936070.78      1370656.49      6934648.91
      1370578.37      6934398.91      1370250.24      6934393.70
      1368235.52      6935324.68
#Sta/Elev= 30
  3489.7 2022.51  3642.6 2022.87  3692.9 2018.17  3732.2 2018.99  3763.9 2014.83
  3851.0 2012.07  3977.5 2013.31  4237.7 2009.97  4480.9 2008.37  4686.4 2007.06
  4768.1 2005.84  4807.4 1999.48  4907.5 1999.66  4957.8 1995.49  5246.2 1993.81
  5246.4 1993.31  5250.4 1993.81  5283.8 1995.60  5313.8 2003.84  5393.8 2006.59
  5513.8 2003.21  5600.8 2006.39  5698.1 2001.80  5918.7 2008.23  6548.4 2012.91
  6814.6 2012.36  7013.7 2015.71  7335.7 2016.11  7392.6 2020.67  7798.0 2028.61
#Mann=9,-1,0
  3489.7   0.045       0  4237.7   0.035       0  4480.9   0.045       0
  4686.4    0.07       0  5246.2    0.07       0  5250.4    0.07       0
  5918.7   0.045       0  6548.4   0.035       0  7013.7   0.045       0
Bank Sta=5246.2,5250.4
Exp/Cntr=0.3,0.1

Chan Stop Cuts=-1