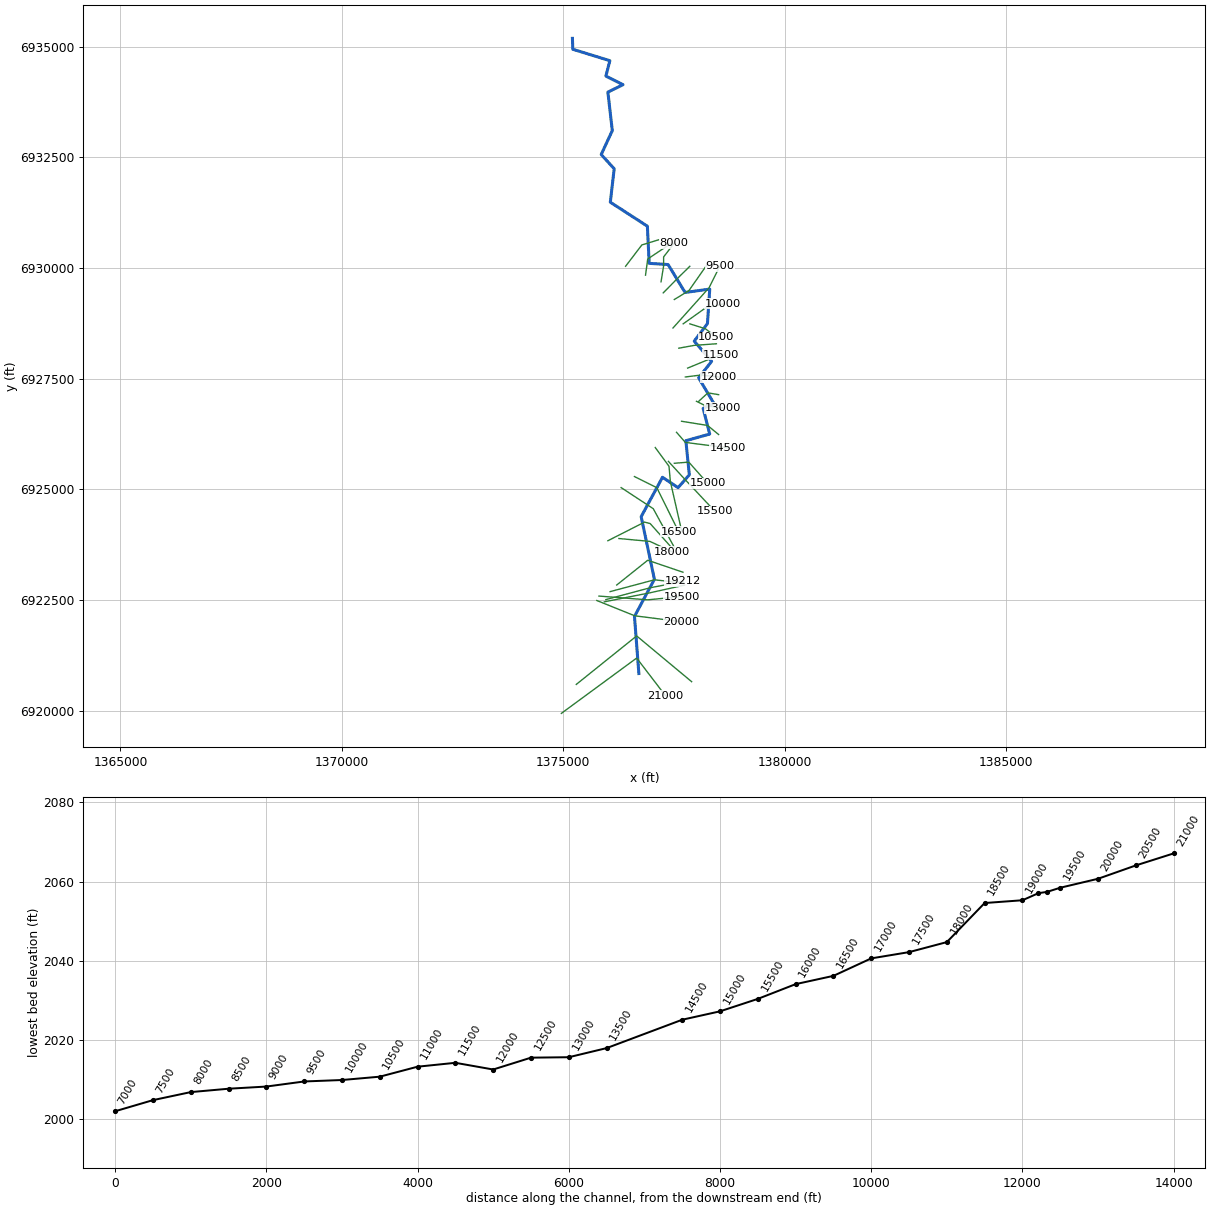
--- Cottonwood Creek Trib120.prj (project) ---

Proj Title=Cottonwood Creek Trib120 Base Level Engineering
Current Plan=p01
Default Exp/Contr=0.3,0.1
English Units
Geom File=g01
Flow File=f01
Plan File=p01
BEGIN DESCRIPTION:
Cottonwood Creek Trib120
END DESCRIPTION:

--- Cottonwood Creek Trib120.p01 (plan) ---

Plan Title=Multiple Run
Short Identifier=Multiple
Geom File=g01
Flow File=f01
Subcritical Flow
K Sum by GR= 0
Std Step Tol= 0.01
Critical Tol= 0.01
Num of Std Step Trials= 20
Max Error Tol= 0.3
Flow Tol Ratio= 0.001
Split Flow NTrial= 30
Split Flow Tol= 0.02
Split Flow Ratio= 0.02
Log Output Level= 0
Friction Slope Method= 1
Unsteady Friction Slope Method= 2
Unsteady Bridges Friction Slope Method= 1
Parabolic Critical Depth
Global Vel Dist=  1 , 1 , 1
Global Log Level= 0
CheckData=True
Encroach Param= -1, 0, 0, 0
BEGIN DESCRIPTION:
Multiple Run
END DESCRIPTION:

--- Cottonwood Creek Trib120.f01 (steady flow) ---

Flow Title=Multiple
Number of Profiles=7
Profile Names=10-year,25-year,50-year,1pct_min,100-year,1pct_plu,500-year
River Rch & RM= Cottonwood Creek,Reach-1,21000
     293     417     523     326     650    1296    1017
River Rch & RM= Cottonwood Creek,Reach-1,19500
     344     494     622     389     775    1547    1222
River Rch & RM= Cottonwood Creek,Reach-1,15500
     448     653     829     523    1043    2081    1673
River Rch & RM= Cottonwood Creek,Reach-1,14500
     557     817    1043     661    1318    2630    2135
River Rch & RM= Cottonwood Creek,Reach-1,11000
     565     826    1052     664    1325    2644    2134
River Rch & RM= Cottonwood Creek,Reach-1,5500
     718    1061    1359     863    1721    3434    2801
Boundary for River Rch & Prof#=Cottonwood Creek,Reach-1,1
Up Type=0
Dn Type=3
Dn Slope=0.005
Boundary for River Rch & Prof#=Cottonwood Creek,Reach-1,2
Up Type=0
Dn Type=3
Dn Slope=0.005
Boundary for River Rch & Prof#=Cottonwood Creek,Reach-1,3
Up Type=0
Dn Type=3
Dn Slope=0.005
Boundary for River Rch & Prof#=Cottonwood Creek,Reach-1,4
Up Type=0
Dn Type=3
Dn Slope=0.005
Boundary for River Rch & Prof#=Cottonwood Creek,Reach-1,5
Up Type=0
Dn Type=3
Dn Slope=0.005
Boundary for River Rch & Prof#=Cottonwood Creek,Reach-1,6
Up Type=0
Dn Type=3
Dn Slope=0.005
Boundary for River Rch & Prof#=Cottonwood Creek,Reach-1,7
Up Type=0
Dn Type=3
Dn Slope=0.005

--- Cottonwood Creek Trib120.g01 (geometry) ---

Geom Title=Existing Conditions

River Reach=Cottonwood Creek,Reach-1
Reach XY= 30
      1376705.00      6920838.00      1376605.59      6922127.39
      1377055.36      6922967.85      1376756.57      6924381.96
      1377238.30      6925271.82      1377589.78      6925037.83
      1377844.05      6925327.63      1377765.19      6926097.68
      1378304.13      6926248.29      1378155.52      6926827.55
      1378397.22      6926941.01      1378054.56      6927517.97
      1378347.41      6927891.35      1377954.48      6928348.25
      1378252.74      6928743.94      1378304.68      6929522.98
      1377748.24      6929447.12      1377364.70      6930077.84
      1376937.86      6930104.46      1376896.86      6930944.06
      1376060.52      6931485.57      1376147.41      6932241.35
      1375854.58      6932563.00      1376104.92      6933103.39
      1376005.33      6933972.97      1376347.49      6934141.12
      1375960.29      6934335.25      1376050.01      6934683.00
      1375213.01      6934941.03      1375205.00      6935188.00

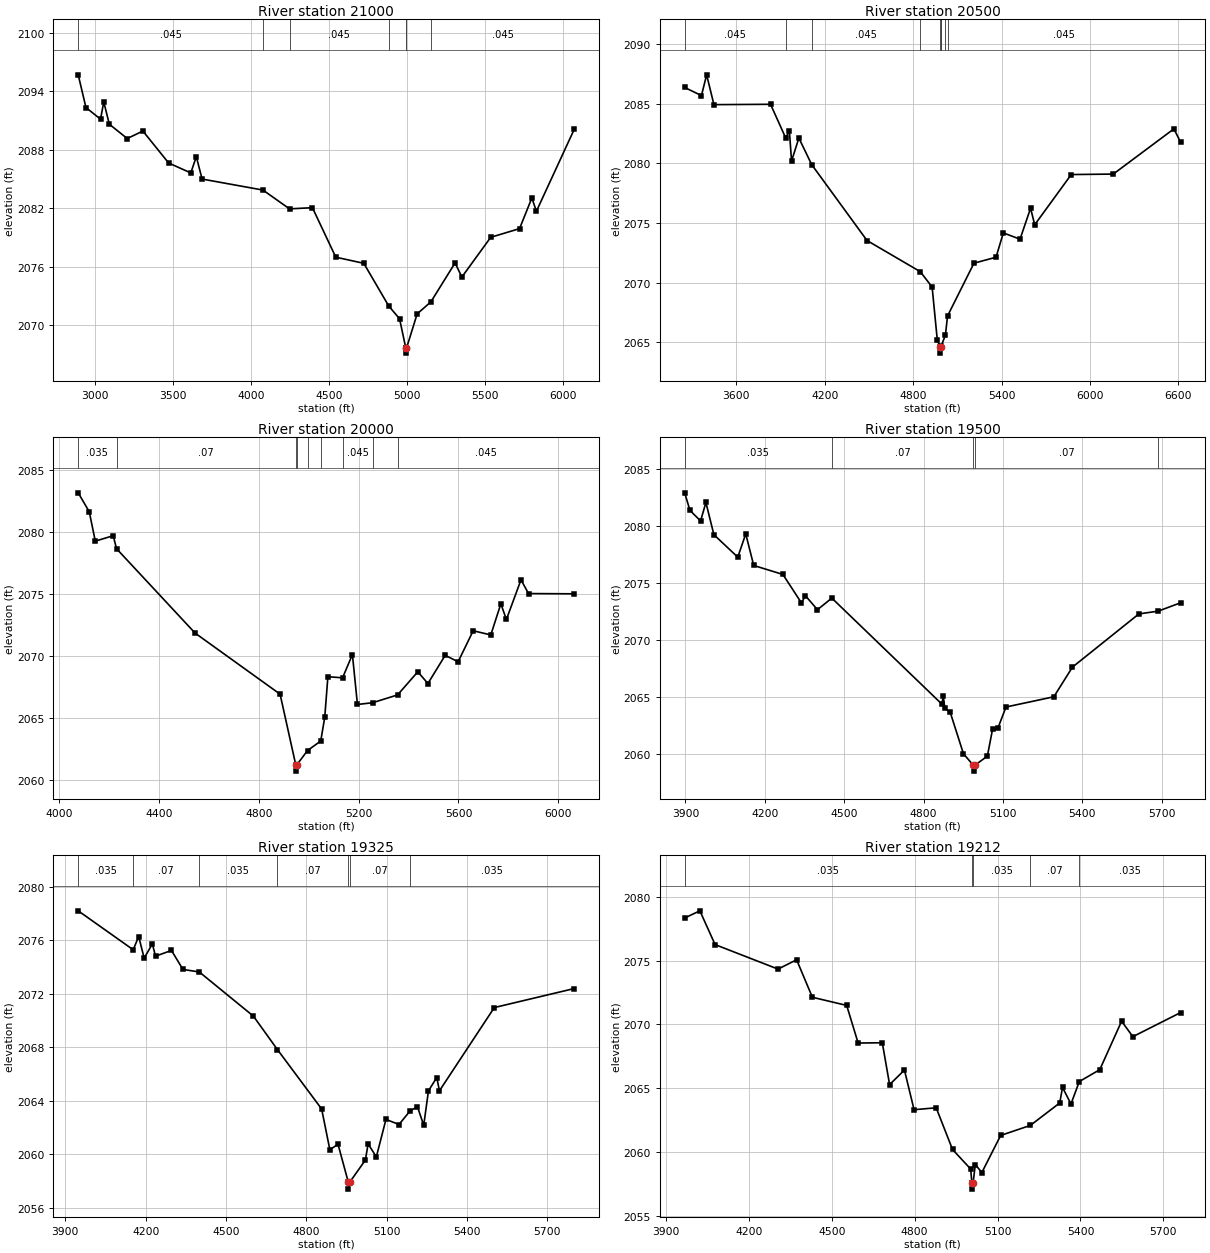
Type RM Length L Ch R = 1,21000,500,500,500
BEGIN DESCRIPTION:
Cottonwood Creek Trib120 41.0
END DESCRIPTION:
XS GIS Cut Line= 3
      1374955.02      6919938.01      1376654.99      6921187.89
      1377305.02      6920337.97
#Sta/Elev= 30
  2890.0 2095.68  2939.6 2092.32  3033.1 2091.13  3053.9 2092.90  3089.4 2090.61
  3204.4 2089.14  3304.7 2089.91  3469.8 2086.63  3611.8 2085.61  3647.3 2087.28
  3684.3 2084.98  4074.6 2083.85  4244.9 2081.92  4391.8 2082.04  4541.5 2076.96
  4721.2 2076.33  4881.0 2071.95  4950.4 2070.64  4990.8 2067.61  4991.0 2067.11
  4994.8 2067.61  5063.4 2071.14  5151.2 2072.37  5306.4 2076.37  5350.0 2074.92
  5535.0 2079.00  5719.9 2079.89  5798.8 2083.04  5827.9 2081.67  6070.0 2090.07
#Mann=7,-1,0
  2890.0   0.045       0  4074.6   0.035       0  4244.9   0.045       0
  4881.0    0.07       0  4990.8    0.07       0  4994.8    0.07       0
  5151.2   0.045       0
Bank Sta=4990.8,4994.8
Exp/Cntr=0.3,0.1

Type RM Length L Ch R = 1,20500,500,500,500
BEGIN DESCRIPTION:
Cottonwood Creek Trib120 40.0
END DESCRIPTION:
XS GIS Cut Line= 3
      1375291.28      6920591.81      1376654.99      6921687.89
      1377895.42      6920654.32
#Sta/Elev= 30
  3250.4 2086.35  3364.1 2085.67  3399.3 2087.41  3448.9 2084.91  3832.9 2084.94
  3934.8 2082.14  3960.9 2082.67  3975.3 2080.18  4025.0 2082.11  4112.2 2079.88
  4487.3 2073.52  4848.5 2070.91  4928.9 2069.62  4964.1 2065.17  4984.5 2064.58
  4984.7 2064.08  4988.5 2064.58  4989.5 2064.65  5019.2 2065.59  5033.3 2067.19
  5212.8 2071.62  5362.5 2072.12  5411.9 2074.16  5525.2 2073.63  5596.8 2076.23
  5624.8 2074.84  5872.7 2079.05  6157.8 2079.09  6569.1 2082.88  6614.6 2081.76
#Mann=9,-1,0
  3250.4   0.045       0  3934.8   0.035       0  4112.2   0.045       0
  4848.5    0.07       0  4984.5   0.045       0  4988.5    0.07       0
  4989.5   0.045       0  5019.2    0.07       0  5033.3   0.045       0
Bank Sta=4984.5,4988.5
Exp/Cntr=0.3,0.1

Type RM Length L Ch R = 1,20000,500,500,500
BEGIN DESCRIPTION:
Cottonwood Creek Trib120 39.0
END DESCRIPTION:
XS GIS Cut Line= 3
      1375755.00      6922488.00      1376611.38      6922142.35
      1377666.32      6922008.47
#Sta/Elev= 30
  4076.5 2083.17  4120.8 2081.64  4144.9 2079.27  4216.7 2079.71  4230.0 2078.66
  4544.8 2071.85  4885.3 2066.92  4948.1 2061.21  4948.4 2060.71  4952.1 2061.21
  4995.2 2062.37  5048.1 2063.14  5064.1 2065.04  5076.8 2068.33  5135.6 2068.24
  5175.0 2070.12  5195.2 2066.09  5255.8 2066.23  5356.0 2066.86  5437.1 2068.73
  5477.4 2067.78  5546.9 2070.06  5598.4 2069.53  5658.9 2072.04  5729.4 2071.70
  5769.7 2074.21  5792.0 2072.95  5850.4 2076.15  5880.6 2075.04  6063.4 2075.02
#Mann=9,-1,0
  4076.5   0.035       0  4230.0    0.07       0  4948.1   0.045       0
  4952.1    0.07       0  4995.2   0.045       0  5048.1    0.07       0
  5135.6   0.045       0  5255.8    0.07       0  5356.0   0.045       0
Bank Sta=4948.1,4952.1
Exp/Cntr=0.3,0.1

Type RM Length L Ch R = 1,19500,175,175,175
BEGIN DESCRIPTION:
Cottonwood Creek Trib120 38.0
END DESCRIPTION:
XS GIS Cut Line= 3
      1375805.02      6922588.00      1376904.36      6922503.24
      1377671.65      6922577.76
#Sta/Elev= 30
  3897.4 2082.93  3917.4 2081.38  3957.5 2080.46  3977.6 2082.08  4007.7 2079.25
  4098.0 2077.27  4128.1 2079.32  4158.2 2076.54  4268.5 2075.75  4338.7 2073.24
  4353.2 2073.89  4398.9 2072.65  4453.3 2073.67  4869.2 2064.34  4874.2 2065.04
  4880.3 2063.96  4900.3 2063.64  4950.5 2059.98  4988.4 2058.95  4988.7 2058.45
  4992.8 2058.95  5040.8 2059.77  5060.9 2062.19  5081.0 2062.25  5111.2 2064.09
  5292.0 2064.99  5362.3 2067.60  5613.3 2072.28  5685.9 2072.52  5770.9 2073.26
#Mann=5,-1,0
  3897.4   0.035       0  4453.3    0.07       0  4988.4    0.07       0
  4992.8    0.07       0  5685.9   0.035       0
Bank Sta=4988.4,4992.8
Exp/Cntr=0.3,0.1

Type RM Length L Ch R = 1,19325,113,113,113
BEGIN DESCRIPTION:
Cottonwood Creek Trib120 37.6
END DESCRIPTION:
XS GIS Cut Line= 3
      1375923.52      6922457.52      1376963.55      6922663.78
      1377735.99      6922835.12
#Sta/Elev= 30
  3948.3 2078.20  4153.6 2075.29  4174.1 2076.28  4194.5 2074.66  4225.1 2075.73
  4236.9 2074.81  4296.4 2075.24  4339.3 2073.82  4400.4 2073.63  4602.3 2070.33
  4692.0 2067.83  4857.1 2063.39  4887.7 2060.35  4918.3 2060.75  4956.9 2057.90
  4957.2 2057.40  4961.3 2057.90  5020.3 2059.57  5030.6 2060.78  5061.3 2059.81
  5097.2 2062.61  5145.9 2062.23  5187.4 2063.25  5214.9 2063.55  5238.2 2062.17
  5255.9 2064.75  5286.9 2065.74  5296.9 2064.75  5501.7 2070.97  5799.8 2072.39
#Mann=7,-1,0
  3948.3   0.035       0  4153.6    0.07       0  4400.4   0.035       0
  4692.0    0.07       0  4956.9    0.07       0  4961.3    0.07       0
  5187.4   0.035       0
Bank Sta=4956.9,4961.3
Exp/Cntr=0.3,0.1

Type RM Length L Ch R = 1,19212,212,212,212
BEGIN DESCRIPTION:
Cottonwood Creek Trib120 37.5
END DESCRIPTION:
XS GIS Cut Line= 3
      1375958.63      6922508.31      1376958.35      6922775.76
      1377704.75      6922918.46
#Sta/Elev= 30
  3967.7 2078.35  4022.7 2078.91  4077.8 2076.26  4305.5 2074.34  4372.8 2075.07
  4429.8 2072.13  4554.0 2071.49  4595.4 2068.54  4682.9 2068.56  4709.3 2065.28
  4763.0 2066.42  4797.8 2063.31  4877.9 2063.46  4937.0 2060.19  5002.6 2058.66
  5007.1 2057.58  5007.4 2057.08  5011.5 2057.58  5019.5 2059.01  5043.1 2058.38
  5111.2 2061.29  5218.8 2062.08  5325.0 2063.84  5335.1 2065.06  5365.7 2063.76
  5395.9 2065.52  5469.9 2066.45  5548.9 2070.25  5589.7 2069.04  5762.5 2070.93
#Mann=5,-1,0
  3967.7   0.035       0  5007.1   0.035       0  5011.5   0.035       0
  5218.8    0.07       0  5395.9   0.035       0
Bank Sta=5007.1,5011.5
Exp/Cntr=0.3,0.1

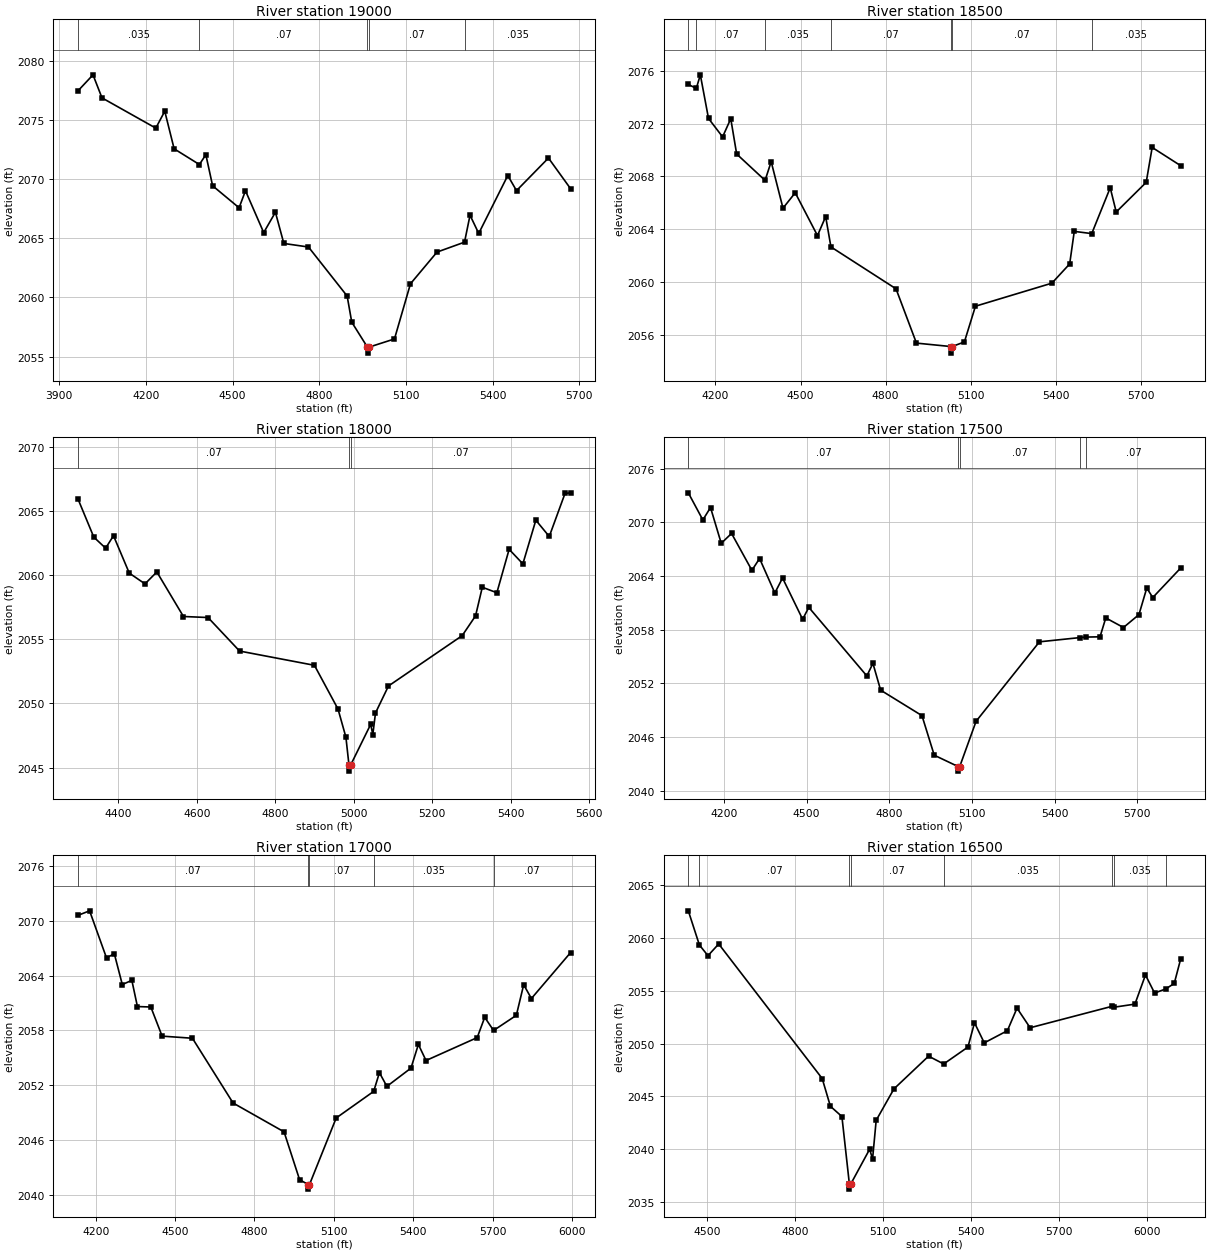
Type RM Length L Ch R = 1,19000,500,500,500
BEGIN DESCRIPTION:
Cottonwood Creek Trib120 37.0
END DESCRIPTION:
XS GIS Cut Line= 3
      1376054.96      6922687.99      1377054.70      6922955.44
      1377720.93      6922883.57
#Sta/Elev= 30
  3965.1 2077.49  4016.9 2078.84  4048.0 2076.89  4234.3 2074.33  4265.3 2075.76
  4297.8 2072.58  4385.2 2071.25  4407.6 2072.08  4431.0 2069.45  4522.6 2067.59
  4544.8 2069.03  4607.9 2065.49  4648.4 2067.21  4677.6 2064.57  4762.9 2064.27
  4896.8 2060.12  4912.7 2057.91  4967.1 2055.79  4967.4 2055.29  4971.5 2055.79
  5060.6 2056.49  5116.0 2061.16  5207.9 2063.84  5303.1 2064.68  5322.2 2066.96
  5352.3 2065.42  5452.9 2070.32  5483.1 2069.04  5593.7 2071.80  5670.1 2069.21
#Mann=5,-1,0
  3965.1   0.035       0  4385.2    0.07       0  4967.1    0.07       0
  4971.5    0.07       0  5303.1   0.035       0
Bank Sta=4967.1,4971.5
Exp/Cntr=0.3,0.1

Type RM Length L Ch R = 1,18500,500,500,500
BEGIN DESCRIPTION:
Cottonwood Creek Trib120 36.0
END DESCRIPTION:
XS GIS Cut Line= 3
      1376205.00      6922838.00      1376904.64      6923397.44
      1377700.54      6923126.68
#Sta/Elev= 30
  4104.2 2074.98  4132.4 2074.68  4146.6 2075.71  4175.4 2072.40  4225.1 2071.00
  4253.9 2072.38  4274.7 2069.70  4374.9 2067.70  4396.4 2069.12  4438.0 2065.59
  4481.2 2066.76  4559.6 2063.51  4588.5 2064.95  4607.1 2062.65  4836.6 2059.47
  4908.6 2055.35  5029.9 2055.09  5030.2 2054.59  5034.3 2055.09  5077.7 2055.44
  5116.6 2058.15  5386.2 2059.90  5448.9 2061.36  5465.1 2063.83  5526.7 2063.66
  5591.9 2067.14  5613.0 2065.30  5718.7 2067.55  5739.8 2070.20  5840.7 2068.81
#Mann=7,-1,0
  4104.2   0.035       0  4132.4    0.07       0  4374.9   0.035       0
  4607.1    0.07       0  5029.9    0.07       0  5034.3    0.07       0
  5526.7   0.035       0
Bank Sta=5029.9,5034.3
Exp/Cntr=0.3,0.1

Type RM Length L Ch R = 1,18000,500,500,500
BEGIN DESCRIPTION:
Cottonwood Creek Trib120 35.0
END DESCRIPTION:
XS GIS Cut Line= 3
      1376254.98      6923888.00      1376954.59      6923823.26
      1377454.96      6923588.02
#Sta/Elev= 30
  4297.4 2065.91  4337.6 2062.95  4367.7 2062.09  4387.8 2063.06  4428.0 2060.15
  4468.1 2059.31  4498.3 2060.24  4566.1 2056.77  4628.8 2056.69  4709.2 2054.08
  4900.0 2052.97  4960.2 2049.56  4980.3 2047.37  4988.0 2045.23  4988.3 2044.73
  4992.8 2045.23  5043.4 2048.37  5048.9 2047.58  5055.7 2049.26  5088.8 2051.36
  5276.7 2055.28  5310.8 2056.82  5328.0 2059.05  5365.1 2058.62  5396.4 2062.00
  5431.4 2060.87  5464.5 2064.27  5498.7 2063.00  5538.8 2066.35  5552.9 2066.40
#Mann=3,-1,0
  4297.4    0.07       0  4988.0    0.07       0  4992.8    0.07       0
Bank Sta=4988,4992.8
Exp/Cntr=0.3,0.1

Type RM Length L Ch R = 1,17500,500,500,500
BEGIN DESCRIPTION:
Cottonwood Creek Trib120 34.0
END DESCRIPTION:
XS GIS Cut Line= 4
      1376005.04      6923838.02      1376833.63      6924259.22
      1376960.02      6924226.05      1377443.65      6923682.54
#Sta/Elev= 30
  4070.5 2073.30  4123.3 2070.27  4151.1 2071.66  4190.0 2067.66  4227.5 2068.76
  4301.3 2064.64  4329.2 2065.96  4384.6 2062.11  4412.6 2063.78  4485.5 2059.17
  4507.9 2060.50  4718.5 2052.84  4740.7 2054.24  4768.6 2051.25  4918.7 2048.40
  4963.2 2043.98  5050.7 2042.70  5051.0 2042.20  5055.6 2042.70  5115.1 2047.77
  5345.1 2056.65  5494.1 2057.13  5514.3 2057.18  5565.0 2057.21  5585.9 2059.32
  5650.1 2058.25  5706.3 2059.69  5734.7 2062.66  5756.5 2061.60  5858.2 2064.91
#Mann=5,-1,0
  4070.5    0.07       0  5050.7    0.07       0  5055.6    0.07       0
  5494.1   0.035       0  5514.3    0.07       0
Bank Sta=5050.7,5055.6
Exp/Cntr=0.3,0.1

Type RM Length L Ch R = 1,17000,500,500,500
BEGIN DESCRIPTION:
Cottonwood Creek Trib120 33.0
END DESCRIPTION:
XS GIS Cut Line= 3
      1376305.01      6925038.00      1377029.77      6924562.00
      1377504.98      6923688.04
#Sta/Elev= 30
  4132.9 2070.60  4176.6 2071.09  4240.6 2065.93  4270.0 2066.40  4300.2 2063.02
  4336.3 2063.48  4357.4 2060.61  4408.1 2060.56  4450.8 2057.37  4565.3 2057.14
  4719.0 2050.05  4911.8 2046.89  4970.4 2041.66  5002.9 2041.12  5003.2 2040.62
  5007.9 2041.12  5108.9 2048.41  5250.6 2051.32  5272.3 2053.37  5300.5 2051.87
  5391.6 2053.87  5419.6 2056.46  5448.5 2054.70  5642.0 2057.21  5670.4 2059.43
  5703.9 2057.99  5790.0 2059.65  5817.7 2063.00  5846.9 2061.49  5994.8 2066.51
#Mann=5,-1,0
  4132.9    0.07       0  5002.9    0.07       0  5007.9    0.07       0
  5250.6   0.035       0  5703.9    0.07       0
Bank Sta=5002.9,5007.9
Exp/Cntr=0.3,0.1

Type RM Length L Ch R = 1,16500,500,500,500
BEGIN DESCRIPTION:
Cottonwood Creek Trib120 32.0
END DESCRIPTION:
XS GIS Cut Line= 3
      1376605.00      6925288.00      1377109.14      6925037.16
      1377604.99      6924038.03
#Sta/Elev= 30
  4436.9 2062.58  4474.7 2059.34  4503.9 2058.33  4540.5 2059.44  4893.2 2046.69
  4921.2 2044.06  4960.4 2043.09  4985.8 2036.71  4986.2 2036.21  4990.9 2036.71
  5054.9 2039.99  5064.9 2039.07  5077.2 2042.73  5137.8 2045.71  5255.8 2048.81
  5307.3 2048.07  5389.9 2049.67  5412.3 2051.97  5445.6 2050.07  5524.3 2051.22
  5557.2 2053.36  5601.9 2051.50  5879.4 2053.52  5888.7 2053.45  5959.1 2053.74
  5995.0 2056.50  6026.1 2054.79  6064.2 2055.18  6093.1 2055.70  6115.4 2058.06
#Mann=8,-1,0
  4436.9    0.05       0  4474.7    0.07       0  4985.8    0.07       0
  4990.9    0.07       0  5307.3   0.035       0  5879.4    0.07       0
  5888.7   0.035       0  6064.2    0.07       0
Bank Sta=4985.8,4990.9
Exp/Cntr=0.3,0.1

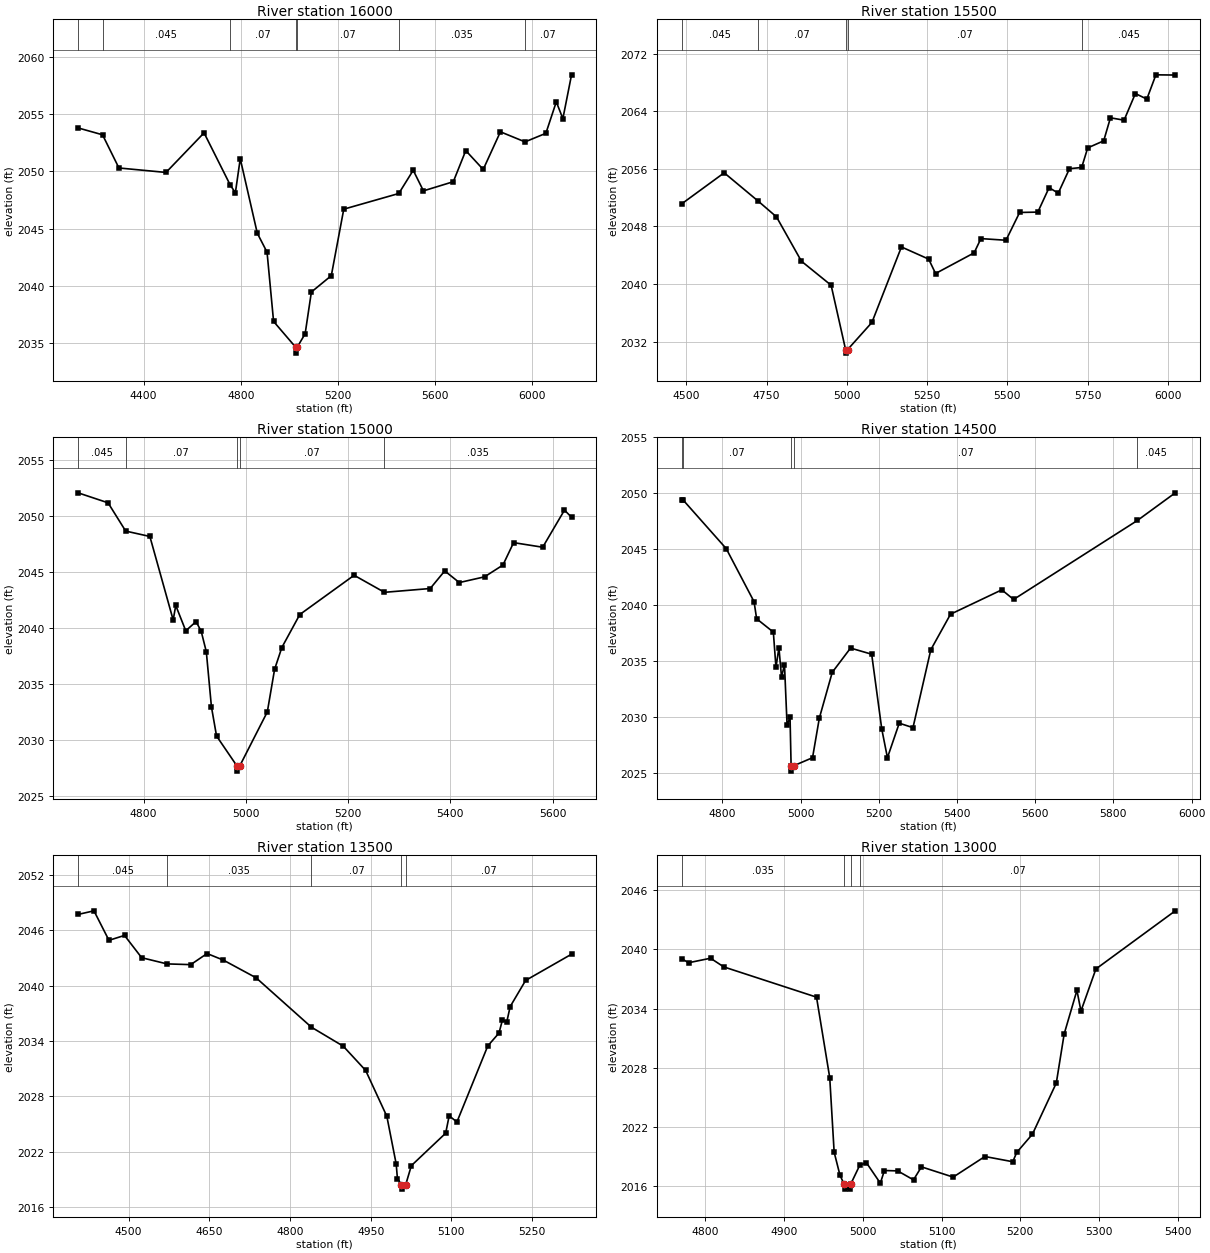
Type RM Length L Ch R = 1,16000,500,500,500
BEGIN DESCRIPTION:
Cottonwood Creek Trib120 31.0
END DESCRIPTION:
XS GIS Cut Line= 4
      1377074.54      6925943.55      1377385.32      6925520.39
      1377415.53      6925176.54      1377674.28      6924043.20
#Sta/Elev= 30
  4129.8 2053.80  4230.5 2053.20  4298.0 2050.30  4492.0 2049.91  4648.7 2053.37
  4756.1 2048.83  4777.7 2048.13  4797.8 2051.11  4868.0 2044.60  4908.2 2042.94
  4935.1 2036.89  5026.7 2034.62  5027.1 2034.12  5031.8 2034.62  5065.1 2035.81
  5090.8 2039.46  5172.9 2040.89  5224.2 2046.70  5450.9 2048.07  5510.3 2050.10
  5552.4 2048.30  5675.5 2049.10  5726.8 2051.82  5798.6 2050.17  5869.5 2053.46
  5970.9 2052.58  6056.8 2053.33  6099.7 2056.08  6126.8 2054.61  6162.5 2058.44
#Mann=7,-1,0
  4129.8    0.05       0  4230.5   0.045       0  4756.1    0.07       0
  5026.7    0.07       0  5031.8    0.07       0  5450.9   0.035       0
  5970.9    0.07       0
Bank Sta=5026.7,5031.8
Exp/Cntr=0.3,0.1

Type RM Length L Ch R = 1,15500,500,500,500
BEGIN DESCRIPTION:
Cottonwood Creek Trib120 30.0
END DESCRIPTION:
XS GIS Cut Line= 3
      1377371.44      6925631.01      1377718.52      6925252.17
      1378418.34      6924505.99
#Sta/Elev= 30
  4486.2 2051.15  4618.2 2055.45  4725.0 2051.48  4781.0 2049.33  4858.7 2043.17
  4951.2 2039.83  4996.2 2030.90  4996.7 2030.40  5002.7 2030.90  5078.2 2034.66
  5170.2 2045.15  5255.0 2043.46  5276.5 2041.46  5396.6 2044.33  5417.7 2046.31
  5495.8 2046.08  5538.3 2049.94  5594.9 2049.99  5630.1 2053.39  5658.5 2052.62
  5693.6 2056.02  5731.5 2056.19  5750.3 2058.91  5800.1 2059.89  5821.1 2063.09
  5863.6 2062.76  5898.8 2066.46  5934.4 2065.69  5962.7 2069.06  6023.0 2069.03
#Mann=5,-1,0
  4486.2   0.045       0  4725.0    0.07       0  4996.2    0.07       0
  5002.7    0.07       0  5731.5   0.045       0
Bank Sta=4996.2,5002.7
Exp/Cntr=0.3,0.1

Type RM Length L Ch R = 1,15000,500,500,500
BEGIN DESCRIPTION:
Cottonwood Creek Trib120 29.0
END DESCRIPTION:
XS GIS Cut Line= 3
      1377505.04      6925588.00      1377831.98      6925614.39
      1378255.00      6925138.00
#Sta/Elev= 30
  4672.0 2052.07  4730.6 2051.18  4765.1 2048.66  4812.4 2048.18  4858.0 2040.73
  4863.0 2042.03  4882.6 2039.77  4902.7 2040.59  4912.7 2039.74  4922.8 2037.90
  4932.8 2032.99  4942.8 2030.39  4982.1 2027.76  4982.6 2027.26  4988.6 2027.76
  5042.1 2032.54  5056.3 2036.33  5070.5 2038.28  5105.6 2041.22  5211.9 2044.72
  5271.2 2043.20  5360.7 2043.54  5389.1 2045.11  5417.6 2044.07  5466.9 2044.58
  5502.9 2045.63  5523.8 2047.63  5580.7 2047.22  5623.3 2050.53  5637.1 2049.89
#Mann=5,-1,0
  4672.0   0.045       0  4765.1    0.07       0  4982.1    0.07       0
  4988.6    0.07       0  5271.2   0.035       0
Bank Sta=4982.1,4988.6
Exp/Cntr=0.3,0.1

Type RM Length L Ch R = 1,14500,1000,1000,1000
BEGIN DESCRIPTION:
Cottonwood Creek Trib120 28.0
END DESCRIPTION:
XS GIS Cut Line= 3
      1377554.99      6926288.01      1377754.59      6926059.39
      1378704.97      6925938.00
#Sta/Elev= 30
  4696.5 2049.41  4699.5 2049.41  4810.0 2045.05  4881.2 2040.30  4887.8 2038.77
  4930.5 2037.58  4937.2 2034.42  4944.8 2036.19  4951.4 2033.55  4959.0 2034.67
  4965.6 2029.27  4973.2 2029.94  4975.9 2025.64  4976.4 2025.14  4983.8 2025.64
  5030.7 2026.34  5048.1 2029.88  5081.1 2033.98  5127.9 2036.15  5181.9 2035.60
  5207.7 2028.91  5222.2 2026.34  5252.4 2029.43  5287.5 2029.03  5333.1 2036.00
  5383.5 2039.18  5514.6 2041.36  5544.8 2040.50  5861.4 2047.57  5958.1 2050.04
#Mann=5,-1,0
  4696.5   0.045       0  4699.5    0.07       0  4975.9    0.07       0
  4983.8    0.07       0  5861.4   0.045       0
Bank Sta=4975.9,4983.8
Exp/Cntr=0.3,0.1

Type RM Length L Ch R = 1,13500,500,500,500
BEGIN DESCRIPTION:
Cottonwood Creek Trib120 27.0
END DESCRIPTION:
XS GIS Cut Line= 3
      1377668.29      6926537.27      1378254.65      6926442.95
      1378504.97      6926238.02
#Sta/Elev= 30
  4406.1 2047.69  4435.6 2048.08  4463.5 2044.89  4492.4 2045.42  4524.3 2043.01
  4571.4 2042.34  4615.5 2042.26  4645.9 2043.46  4676.2 2042.75  4737.0 2040.84
  4840.0 2035.49  4899.1 2033.44  4940.7 2030.82  4980.1 2025.86  4997.5 2020.70
  4999.8 2019.12  5007.3 2018.48  5007.8 2017.98  5015.3 2018.48  5025.7 2020.52
  5089.5 2024.03  5096.0 2025.91  5110.4 2025.24  5167.8 2033.47  5188.6 2034.86
  5195.1 2036.29  5203.0 2036.04  5209.4 2037.72  5238.1 2040.55  5323.5 2043.39
#Mann=5,-1,0
  4406.1   0.045       0  4571.4   0.035       0  4840.0    0.07       0
  5007.3    0.07       0  5015.3    0.07       0
Bank Sta=5007.3,5015.3
Exp/Cntr=0.3,0.1

Type RM Length L Ch R = 1,13000,500,500,500
BEGIN DESCRIPTION:
Cottonwood Creek Trib120 26.0
END DESCRIPTION:
XS GIS Cut Line= 3
      1378004.97      6926988.02      1378211.04      6926886.10
      1378605.01      6926838.00
#Sta/Elev= 30
  4770.1 2039.06  4778.6 2038.65  4806.6 2039.11  4823.4 2038.23  4941.2 2035.16
  4958.0 2026.99  4963.6 2019.43  4971.0 2017.09  4976.3 2016.18  4976.8 2015.68
  4984.1 2015.68  4984.6 2016.18  4996.1 2018.10  5004.5 2018.37  5022.3 2016.28
  5027.4 2017.57  5044.3 2017.53  5064.4 2016.62  5074.5 2017.94  5114.8 2016.90
  5155.1 2018.99  5190.5 2018.46  5195.5 2019.40  5215.5 2021.26  5245.8 2026.45
  5255.8 2031.43  5272.0 2035.85  5277.1 2033.75  5296.1 2038.02  5396.9 2043.92
#Mann=4,-1,0
  4770.1   0.035       0  4976.3    0.07       0  4984.6   0.035       0
  4996.1    0.07       0
Bank Sta=4976.3,4984.6
Exp/Cntr=0.3,0.1

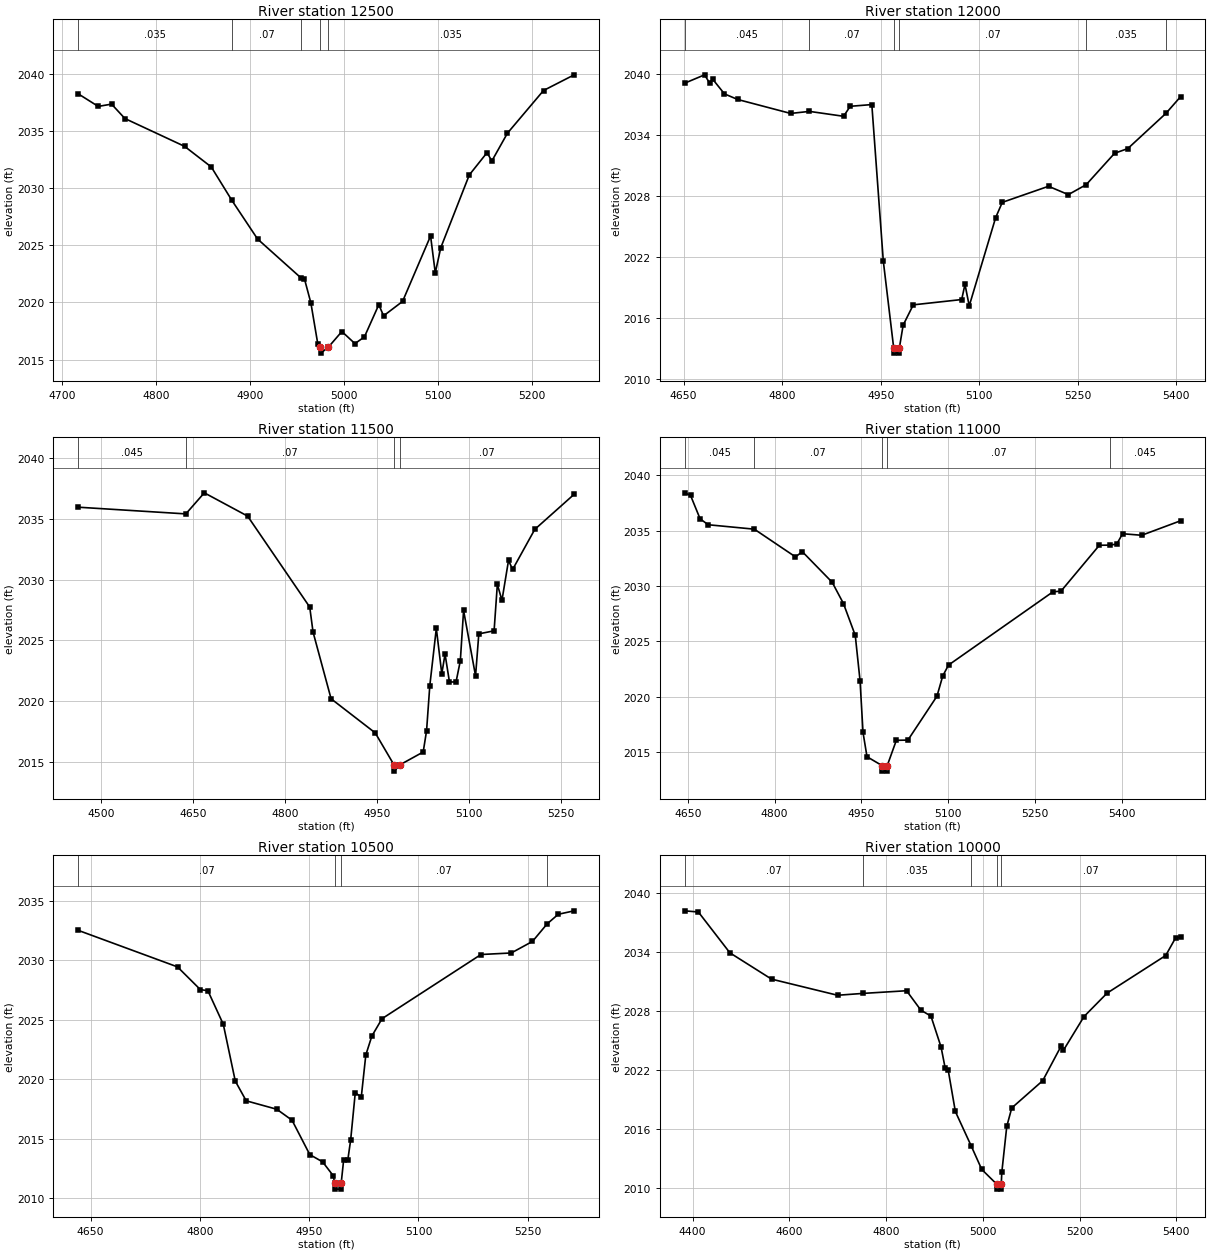
Type RM Length L Ch R = 1,12500,500,500,500
BEGIN DESCRIPTION:
Cottonwood Creek Trib120 25.0
END DESCRIPTION:
XS GIS Cut Line= 3
      1378054.98      6926987.98      1378263.88      6927179.19
      1378504.99      6927138.00
#Sta/Elev= 30
  4716.8 2038.23  4738.1 2037.13  4752.3 2037.33  4766.5 2036.07  4830.0 2033.64
  4858.4 2031.84  4880.4 2028.91  4907.7 2025.54  4953.8 2022.15  4957.6 2022.05
  4964.4 2019.96  4971.8 2016.36  4974.4 2016.07  4974.9 2015.57  4982.8 2016.07
  4997.4 2017.46  5011.3 2016.40  5021.4 2016.99  5036.7 2019.80  5041.8 2018.83
  5062.0 2020.09  5091.8 2025.81  5096.8 2022.58  5102.6 2024.77  5133.0 2031.14
  5151.9 2033.09  5157.0 2032.36  5173.6 2034.79  5212.0 2038.52  5244.6 2039.89
#Mann=5,-1,0
  4716.8   0.035       0  4880.4    0.07       0  4953.8   0.035       0
  4974.4   0.035       0  4982.8   0.035       0
Bank Sta=4974.4,4982.8
Exp/Cntr=0.3,0.1

Type RM Length L Ch R = 1,12000,500,500,500
BEGIN DESCRIPTION:
Cottonwood Creek Trib120 24.0
END DESCRIPTION:
XS GIS Cut Line= 3
      1377754.96      6927538.00      1378100.58      6927581.16
      1378504.98      6927538.00
#Sta/Elev= 30
  4651.7 2039.08  4682.0 2039.90  4689.5 2039.11  4694.6 2039.45  4712.2 2038.03
  4732.4 2037.48  4813.0 2036.11  4841.7 2036.31  4893.6 2035.83  4903.7 2036.81
  4936.6 2036.98  4954.1 2021.60  4969.9 2013.08  4970.4 2012.58  4978.0 2012.58
  4978.5 2013.08  4984.3 2015.33  4999.7 2017.32  5073.4 2017.84  5078.4 2019.33
  5084.9 2017.22  5125.1 2025.88  5135.2 2027.38  5205.6 2028.96  5235.8 2028.14
  5263.0 2029.12  5306.2 2032.20  5326.3 2032.66  5384.4 2036.12  5406.7 2037.76
#Mann=6,-1,0
  4651.7   0.045       0  4841.7    0.07       0  4969.9    0.07       0
  4978.5    0.07       0  5263.0   0.035       0  5384.4    0.07       0
Bank Sta=4969.9,4978.5
Exp/Cntr=0.3,0.1

Type RM Length L Ch R = 1,11500,500,500,500
BEGIN DESCRIPTION:
Cottonwood Creek Trib120 23.0
END DESCRIPTION:
XS GIS Cut Line= 3
      1377805.03      6927738.01      1378301.58      6927942.19
      1378554.98      6928037.99
#Sta/Elev= 30
  4463.1 2035.94  4638.4 2035.39  4668.5 2037.12  4739.0 2035.21  4840.2 2027.74
  4845.6 2025.69  4875.0 2020.21  4946.9 2017.41  4977.6 2014.77  4978.1 2014.27
  4986.5 2014.77  5025.0 2015.84  5030.5 2017.58  5035.8 2021.30  5046.4 2025.99
  5055.3 2022.26  5060.6 2023.88  5067.8 2021.59  5078.5 2021.59  5085.5 2023.33
  5090.8 2027.46  5110.3 2022.09  5115.6 2025.54  5140.5 2025.79  5145.8 2029.61
  5153.3 2028.29  5164.0 2031.57  5170.7 2030.83  5206.8 2034.12  5270.9 2037.00
#Mann=4,-1,0
  4463.1   0.045       0  4638.4    0.07       0  4977.6    0.07       0
  4986.5    0.07       0
Bank Sta=4977.6,4986.5
Exp/Cntr=0.3,0.1

Type RM Length L Ch R = 1,11000,500,500,500
BEGIN DESCRIPTION:
Cottonwood Creek Trib120 22.0
END DESCRIPTION:
XS GIS Cut Line= 3
      1377605.02      6928188.00      1377954.64      6928251.80
      1378455.04      6928288.00
#Sta/Elev= 30
  4644.6 2038.40  4654.7 2038.17  4671.2 2036.06  4685.2 2035.52  4765.0 2035.12
  4836.1 2032.62  4847.9 2033.09  4899.5 2030.33  4919.0 2028.41  4939.4 2025.54
  4947.7 2021.44  4952.8 2016.78  4959.7 2014.59  4985.7 2013.79  4986.2 2013.29
  4994.2 2013.29  4994.7 2013.79  5010.4 2016.07  5030.4 2016.09  5080.6 2020.05
  5090.6 2021.88  5100.6 2022.86  5281.1 2029.47  5295.0 2029.53  5361.3 2033.67
  5379.5 2033.68  5391.4 2033.78  5401.4 2034.71  5434.4 2034.57  5501.7 2035.88
#Mann=5,-1,0
  4644.6   0.045       0  4765.0    0.07       0  4985.7    0.07       0
  4994.7    0.07       0  5379.5   0.045       0
Bank Sta=4985.7,4994.7
Exp/Cntr=0.3,0.1

Type RM Length L Ch R = 1,10500,500,500,500
BEGIN DESCRIPTION:
Cottonwood Creek Trib120 21.0
END DESCRIPTION:
XS GIS Cut Line= 3
      1377855.02      6928737.99      1378205.16      6928627.69
      1378455.01      6928438.00
#Sta/Elev= 30
  4632.9 2032.51  4769.2 2029.44  4800.6 2027.53  4810.9 2027.44  4832.1 2024.61
  4848.5 2019.85  4863.5 2018.19  4905.5 2017.48  4926.4 2016.56  4950.8 2013.67
  4968.4 2013.06  4983.2 2011.88  4984.8 2011.27  4985.3 2010.77  4993.4 2010.77
  4993.9 2011.27  4997.3 2013.23  5003.0 2013.23  5006.9 2014.90  5013.2 2018.86
  5021.5 2018.52  5027.7 2022.04  5036.0 2023.63  5050.0 2025.09  5185.8 2030.48
  5227.4 2030.61  5256.5 2031.58  5276.7 2033.06  5291.9 2033.86  5313.7 2034.15
#Mann=4,-1,0
  4632.9    0.07       0  4984.8    0.07       0  4993.9    0.07       0
  5276.7   0.045       0
Bank Sta=4984.8,4993.9
Exp/Cntr=0.3,0.1

Type RM Length L Ch R = 1,10000,500,500,500
BEGIN DESCRIPTION:
Cottonwood Creek Trib120 20.0
END DESCRIPTION:
XS GIS Cut Line= 3
      1377704.96      6928737.97      1378206.86      6929095.64
      1378604.99      6929188.00
#Sta/Elev= 30
  4383.7 2038.21  4412.0 2038.09  4477.2 2033.94  4563.2 2031.27  4699.7 2029.63
  4752.7 2029.82  4842.3 2030.09  4871.8 2028.12  4892.7 2027.51  4913.6 2024.37
  4922.2 2022.20  4928.4 2022.01  4943.1 2017.82  4975.7 2014.34  4997.7 2011.93
  5028.7 2010.43  5029.2 2009.93  5037.5 2009.93  5038.0 2010.43  5039.1 2011.62
  5049.4 2016.31  5059.7 2018.18  5123.7 2020.95  5161.3 2024.43  5166.4 2024.03
  5209.1 2027.47  5256.8 2029.85  5377.9 2033.67  5398.4 2035.47  5408.7 2035.51
#Mann=5,-1,0
  4383.7    0.07       0  4752.7   0.035       0  4975.7    0.07       0
  5028.7    0.07       0  5038.0    0.07       0
Bank Sta=5028.7,5038
Exp/Cntr=0.3,0.1

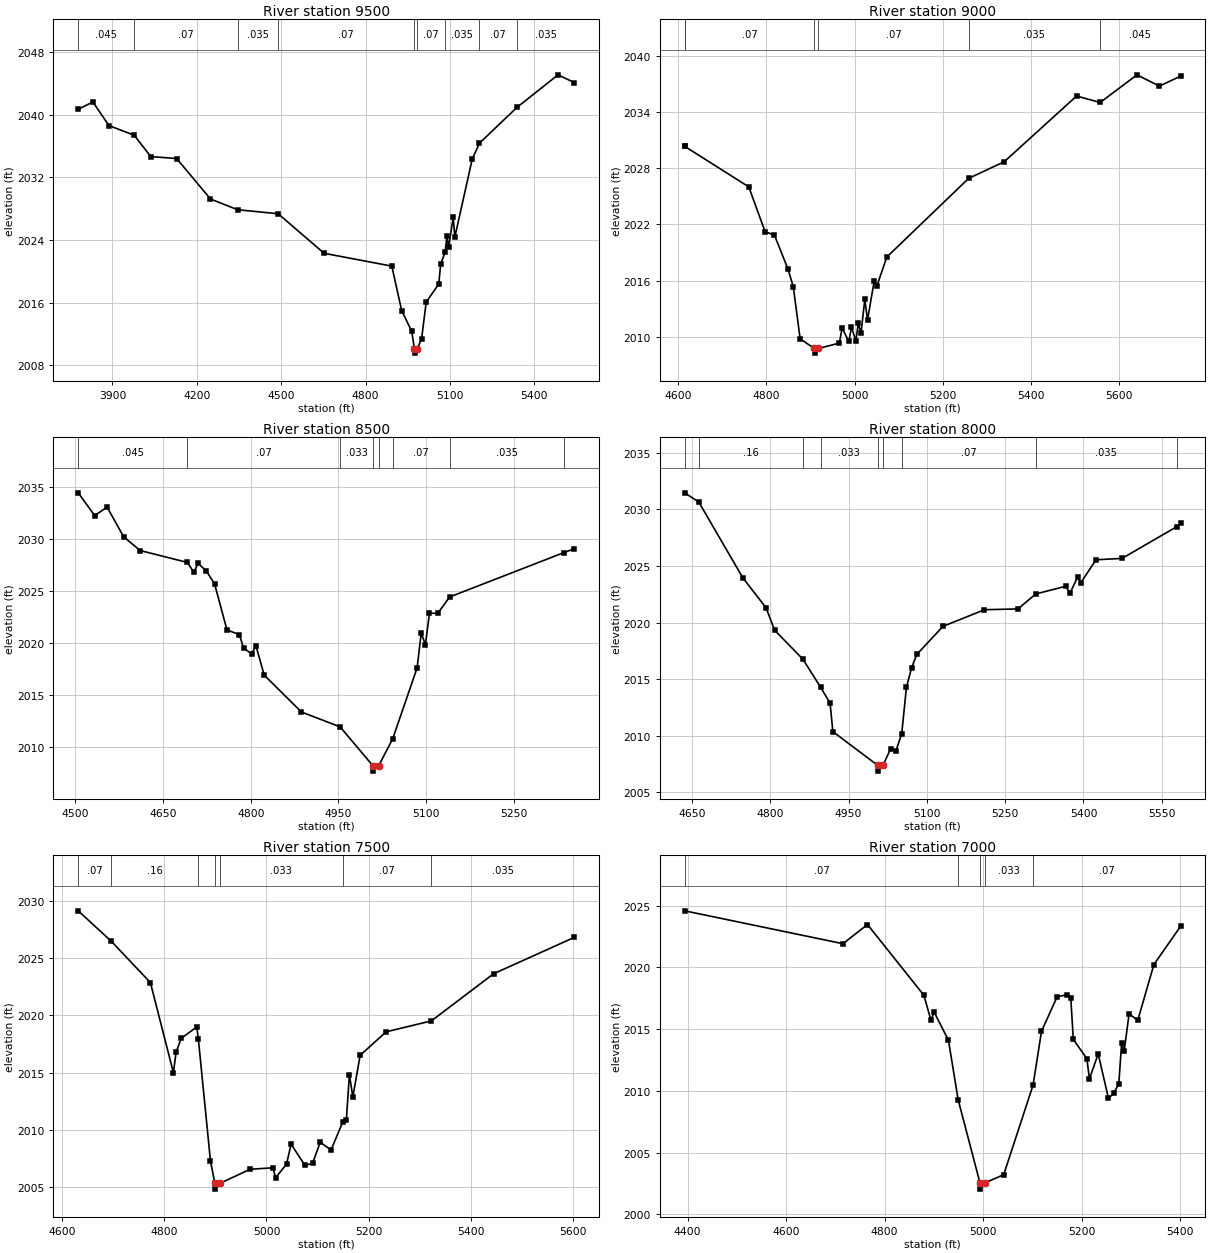
Type RM Length L Ch R = 1,9500,500,500,500
BEGIN DESCRIPTION:
Cottonwood Creek Trib120 19.0
END DESCRIPTION:
XS GIS Cut Line= 3
      1377475.11      6928644.05      1378289.77      6929554.07
      1378530.33      6930039.20
#Sta/Elev= 30
  3778.6 2040.71  3830.9 2041.63  3887.7 2038.62  3977.5 2037.39  4036.5 2034.66
  4128.5 2034.41  4248.8 2029.24  4345.5 2027.87  4489.4 2027.36  4652.6 2022.31
  4893.3 2020.67  4928.4 2014.99  4964.3 2012.33  4973.8 2010.06  4974.3 2009.56
  4983.1 2010.06  4999.3 2011.40  5015.5 2016.07  5060.2 2018.38  5066.9 2020.89
  5082.7 2022.44  5089.3 2024.52  5094.9 2023.05  5111.7 2026.89  5117.3 2024.37
  5179.0 2034.31  5204.8 2036.37  5338.2 2040.94  5484.3 2045.10  5541.5 2044.12
#Mann=9,-1,0
  3778.6   0.045       0  3977.5    0.07       0  4345.5   0.035       0
  4489.4    0.07       0  4973.8    0.07       0  4983.1    0.07       0
  5082.7   0.035       0  5204.8    0.07       0  5338.2   0.035       0
Bank Sta=4973.8,4983.1
Exp/Cntr=0.3,0.1

Type RM Length L Ch R = 1,9000,500,500,500
BEGIN DESCRIPTION:
Cottonwood Creek Trib120 18.0
END DESCRIPTION:
XS GIS Cut Line= 3
      1377505.00      6929288.00      1377833.76      6929487.98
      1378257.01      6930093.39
#Sta/Elev= 30
  4615.2 2030.31  4615.8 2030.31  4760.5 2026.00  4797.3 2021.23  4818.6 2020.86
  4849.3 2017.23  4861.3 2015.34  4876.8 2009.80  4908.9 2008.78  4909.4 2008.28
  4918.3 2008.78  4965.8 2009.35  4971.7 2010.95  4987.2 2009.52  4993.0 2011.05
  5003.1 2009.58  5008.5 2011.47  5014.6 2010.42  5023.3 2014.00  5029.4 2011.81
  5044.3 2015.92  5050.4 2015.41  5073.2 2018.53  5258.5 2026.91  5339.0 2028.68
  5503.0 2035.69  5556.4 2035.00  5639.9 2037.95  5690.5 2036.75  5738.7 2037.81
#Mann=6,-1,0
  4615.2   0.045       0  4615.8    0.07       0  4908.9    0.07       0
  4918.3    0.07       0  5258.5   0.035       0  5556.4   0.045       0
Bank Sta=4908.9,4918.3
Exp/Cntr=0.3,0.1

Type RM Length L Ch R = 1,8500,500,500,500
BEGIN DESCRIPTION:
Cottonwood Creek Trib120 17.0
END DESCRIPTION:
XS GIS Cut Line= 3
      1377255.03      6929438.03      1377602.94      6929790.41
      1377854.99      6930037.99
#Sta/Elev= 30
  4504.8 2034.40  4533.0 2032.22  4554.3 2033.03  4582.5 2030.19  4610.8 2028.87
  4691.5 2027.73  4702.7 2026.78  4709.8 2027.65  4724.0 2026.91  4738.1 2025.67
  4759.3 2021.26  4780.6 2020.81  4787.6 2019.53  4801.7 2018.96  4808.8 2019.76
  4823.0 2016.93  4886.6 2013.40  4952.9 2011.97  5009.2 2008.23  5009.7 2007.73
  5018.7 2008.23  5042.8 2010.82  5084.6 2017.62  5091.7 2020.98  5098.8 2019.83
  5105.8 2022.87  5119.9 2022.85  5140.3 2024.42  5336.1 2028.68  5353.3 2029.03
#Mann=8,-1,0
  4504.8   0.045       0  4691.5    0.07       0  4952.9   0.033       0
  5009.2   0.033       0  5018.7   0.033       0  5042.8    0.07       0
  5140.3   0.035       0  5336.1   0.045       0
Bank Sta=5009.2,5018.7
Exp/Cntr=0.3,0.1

Type RM Length L Ch R = 1,8000,500,500,500
BEGIN DESCRIPTION:
Cottonwood Creek Trib120 16.0
END DESCRIPTION:
XS GIS Cut Line= 4
      1377204.99      6929687.96      1377263.79      6930047.08
      1377263.31      6930249.96      1377497.39      6930553.39
#Sta/Elev= 30
  4636.1 2031.45  4663.1 2030.64  4747.6 2023.94  4792.0 2021.30  4808.4 2019.32
  4862.4 2016.77  4896.6 2014.28  4914.7 2012.87  4919.9 2010.37  5006.1 2007.38
  5006.6 2006.88  5015.8 2007.38  5030.9 2008.87  5040.9 2008.68  5051.9 2010.20
  5060.9 2014.29  5070.9 2016.02  5080.9 2017.19  5130.9 2019.66  5210.3 2021.13
  5274.6 2021.20  5308.5 2022.52  5366.0 2023.20  5374.2 2022.59  5388.7 2024.01
  5395.0 2023.52  5424.0 2025.54  5473.9 2025.66  5578.3 2028.45  5586.1 2028.77
#Mann=9,-1,0
  4636.1    0.07       0  4663.1    0.16       0  4862.4    0.07       0
  4896.6   0.033       0  5006.1   0.033       0  5015.8   0.033       0
  5051.9    0.07       0  5308.5   0.035       0  5578.3   0.045       0
Bank Sta=5006.1,5015.8
Exp/Cntr=0.3,0.1

Type RM Length L Ch R = 1,7500,500,500,500
BEGIN DESCRIPTION:
Cottonwood Creek Trib120 15.0
END DESCRIPTION:
XS GIS Cut Line= 3
      1376855.00      6929838.00      1376904.53      6930203.15
      1377405.04      6930538.03
#Sta/Elev= 30
  4631.5 2029.12  4696.4 2026.46  4772.8 2022.86  4817.8 2015.01  4823.2 2016.82
  4833.3 2018.01  4863.6 2018.99  4866.6 2017.97  4890.4 2007.28  4899.1 2005.35
  4899.6 2004.85  4908.8 2005.35  4967.9 2006.58  5012.1 2006.71  5018.2 2005.86
  5039.2 2007.03  5048.2 2008.77  5075.2 2006.92  5090.2 2007.10  5105.2 2008.94
  5126.3 2008.26  5149.4 2010.71  5156.3 2010.86  5162.3 2014.84  5169.0 2012.88
  5183.3 2016.52  5234.3 2018.57  5322.7 2019.52  5444.5 2023.63  5602.2 2026.80
#Mann=7,-1,0
  4631.5    0.07       0  4696.4    0.16       0  4866.6   0.033       0
  4899.1   0.033       0  4908.8   0.033       0  5149.4    0.07       0
  5322.7   0.035       0
Bank Sta=4899.1,4908.8
Exp/Cntr=0.3,0.1

Type RM Length L Ch R = 1,7000,500,500,500
BEGIN DESCRIPTION:
Cottonwood Creek Trib120 14.0
END DESCRIPTION:
XS GIS Cut Line= 3
      1376405.02      6930038.03      1376771.76      6930520.20
      1377154.96      6930637.99
#Sta/Elev= 30
  4394.2 2024.57  4715.4 2021.91  4765.3 2023.46  4879.7 2017.74  4894.2 2015.71
  4900.5 2016.38  4929.6 2014.10  4949.4 2009.27  4993.6 2002.55  4994.1 2002.05
  5003.4 2002.55  5041.8 2003.22  5101.4 2010.47  5118.5 2014.82  5150.4 2017.63
  5170.8 2017.77  5177.9 2017.54  5183.1 2014.16  5210.6 2012.61  5215.8 2010.98
  5233.6 2012.99  5254.5 2009.39  5264.9 2009.80  5275.4 2010.56  5281.2 2013.91
  5286.4 2013.23  5296.3 2016.24  5313.9 2015.70  5346.6 2020.22  5400.9 2023.32
#Mann=5,-1,0
  4394.2    0.07       0  4949.4   0.033       0  4993.6   0.033       0
  5003.4   0.033       0  5101.4    0.07       0
Bank Sta=4993.6,5003.4
Exp/Cntr=0.3,0.1