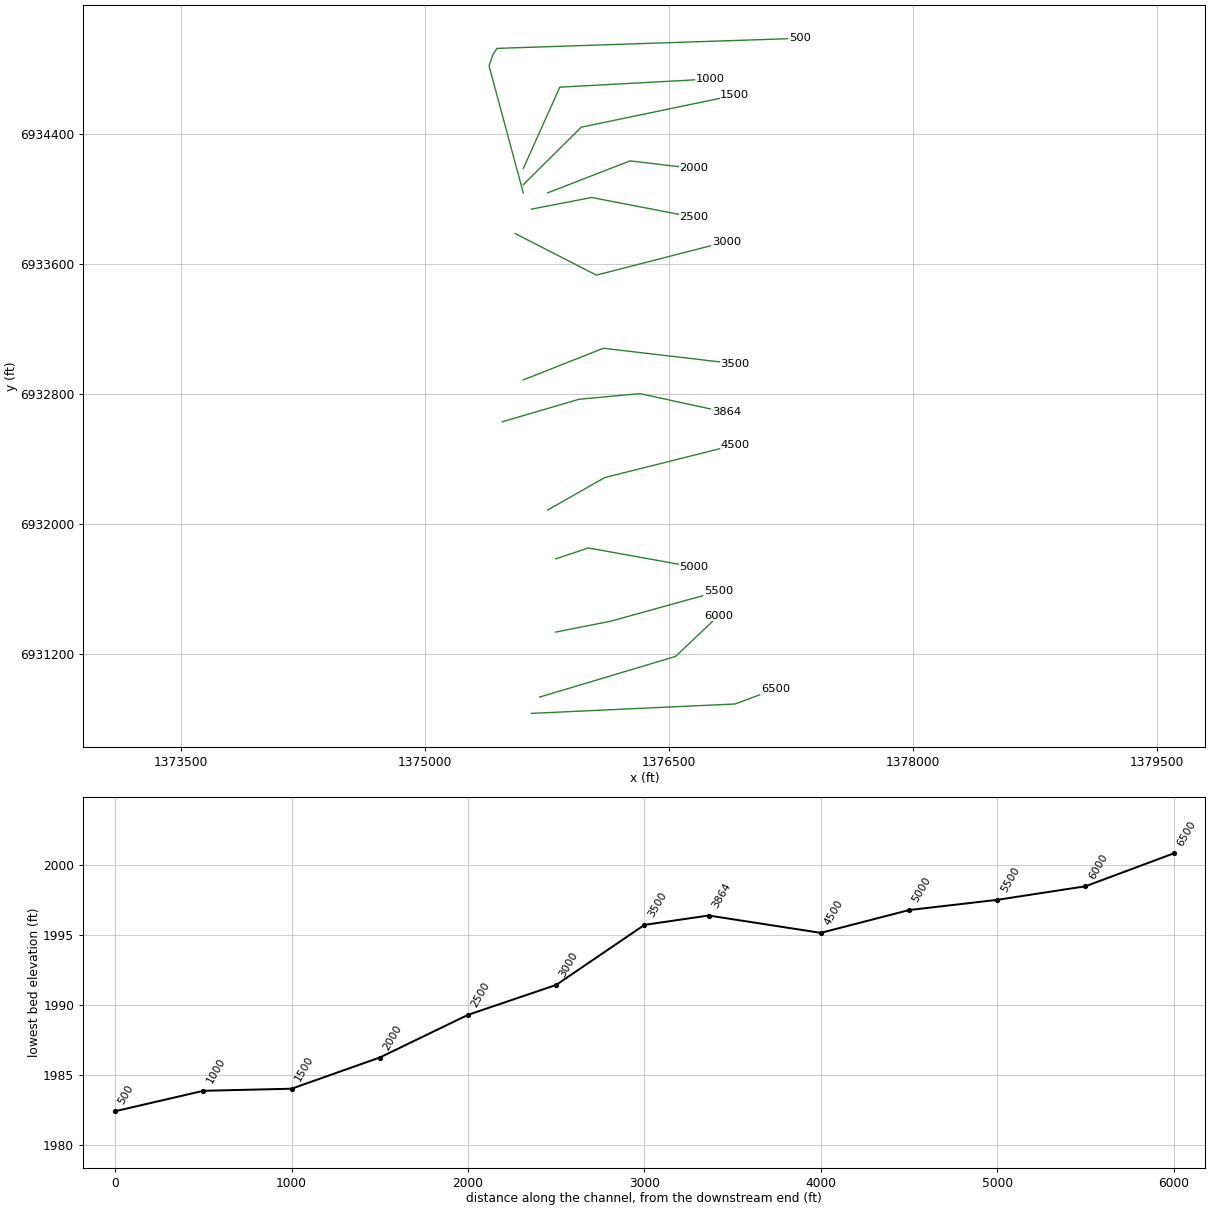
HEC-RAS study Cottonwood Creek Trib120.prj: Cottonwood Creek Trib120 Base Level Engineering

--- Cottonwood Creek Trib120.g01 (geometry) --- (continued)

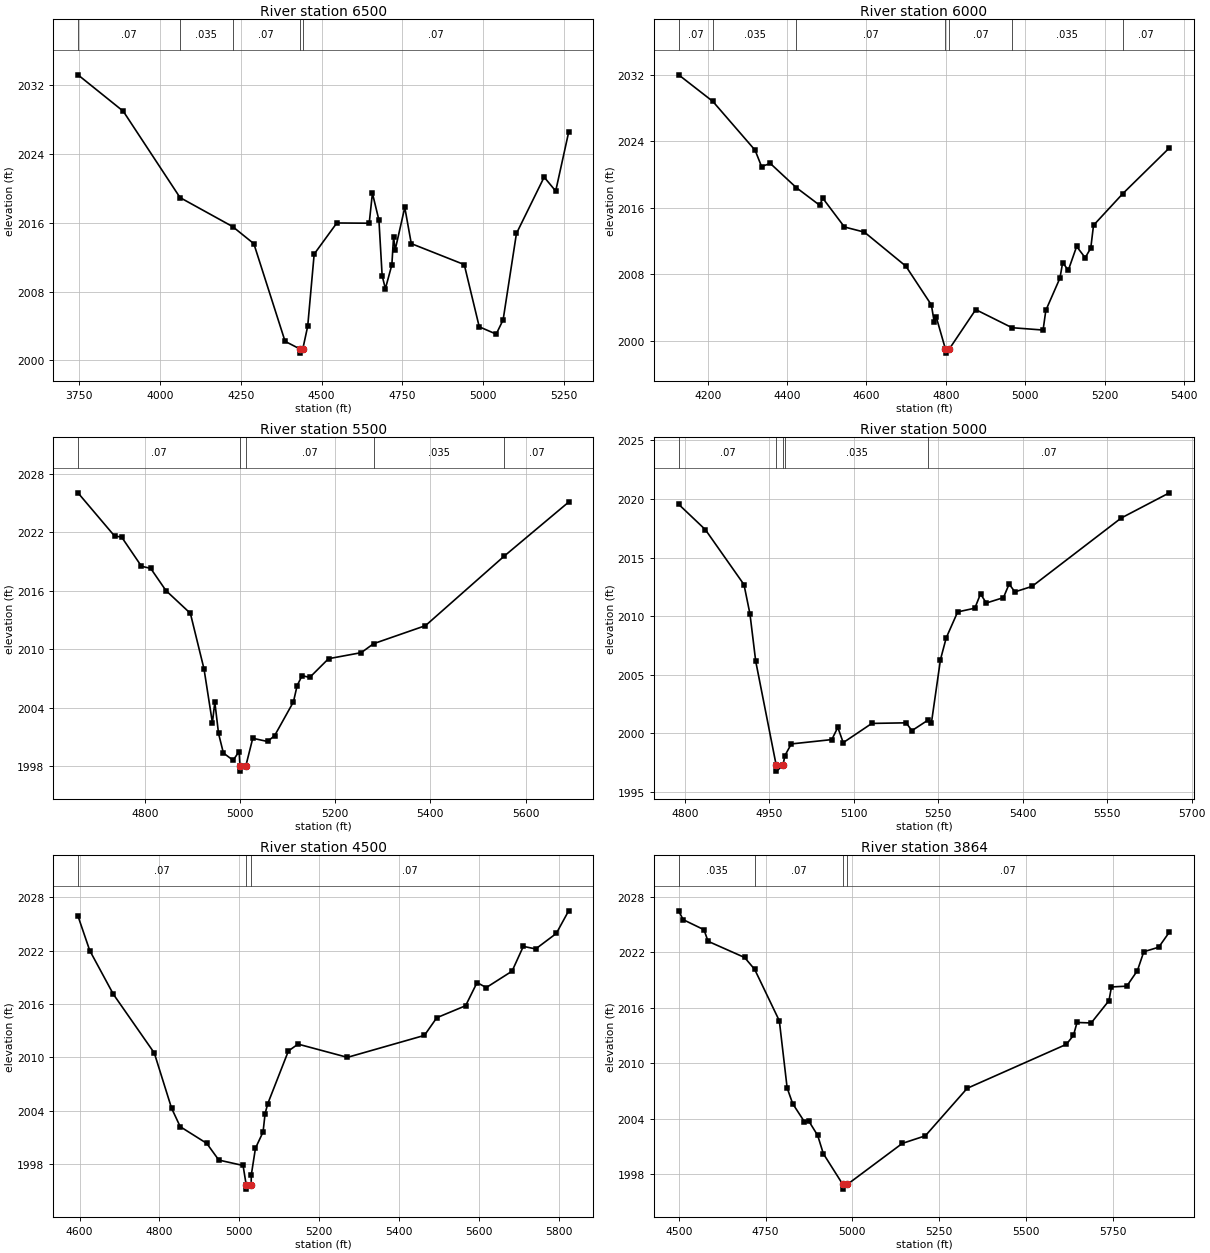
Type RM Length L Ch R = 1,6500,500,500,500
BEGIN DESCRIPTION:
Cottonwood Creek Trib120 13.0
END DESCRIPTION:
XS GIS Cut Line= 3
      1375655.03      6930838.00      1376907.40      6930895.76
      1377154.98      6930987.99
#Sta/Elev= 30
  3746.3 2033.19  3886.4 2028.96  4062.1 2018.92  4224.7 2015.55  4290.4 2013.56
  4387.0 2002.21  4432.1 2001.34  4432.6 2000.84  4441.9 2001.34  4457.0 2003.97
  4477.0 2012.35  4547.1 2015.97  4647.2 2015.94  4657.2 2019.43  4677.3 2016.30
  4687.3 2009.83  4697.3 2008.33  4717.3 2011.11  4722.6 2014.35  4727.6 2012.85
  4757.3 2017.78  4777.4 2013.57  4941.3 2011.13  4987.6 2003.90  5040.1 2003.05
  5061.5 2004.71  5102.7 2014.75  5188.4 2021.30  5224.1 2019.68  5264.2 2026.52
#Mann=5,-1,0
  3746.3    0.07       0  4062.1   0.035       0  4224.7    0.07       0
  4432.1    0.07       0  4441.9    0.07       0
Bank Sta=4432.1,4441.9
Exp/Cntr=0.3,0.1

Type RM Length L Ch R = 1,6000,500,500,500
BEGIN DESCRIPTION:
Cottonwood Creek Trib120 12.0
END DESCRIPTION:
XS GIS Cut Line= 3
      1375704.95      6930937.99      1376541.35      6931188.14
      1376804.97      6931437.97
#Sta/Elev= 30
  4127.0 2032.00  4213.1 2028.80  4319.6 2022.92  4335.8 2020.96  4357.9 2021.33
  4423.1 2018.43  4481.9 2016.31  4490.3 2017.13  4544.6 2013.68  4594.9 2013.06
  4699.4 2008.96  4763.7 2004.29  4770.8 2002.23  4776.0 2002.82  4799.0 1998.99
  4799.5 1998.49  4808.8 1998.99  4875.4 2003.73  4966.9 2001.55  5045.1 2001.27
  5052.0 2003.64  5087.5 2007.52  5094.4 2009.39  5108.6 2008.47  5129.6 2011.33
  5151.1 2009.98  5165.2 2011.13  5172.1 2013.88  5245.6 2017.68  5363.2 2023.20
#Mann=7,-1,0
  4127.0    0.07       0  4213.1   0.035       0  4423.1    0.07       0
  4799.0   0.035       0  4808.8    0.07       0  4966.9   0.035       0
  5245.6    0.07       0
Bank Sta=4799,4808.8
Exp/Cntr=0.3,0.1

Type RM Length L Ch R = 1,5500,500,500,500
BEGIN DESCRIPTION:
Cottonwood Creek Trib120 11.0
END DESCRIPTION:
XS GIS Cut Line= 3
      1375805.01      6931338.00      1376139.30      6931403.76
      1376804.98      6931587.99
#Sta/Elev= 30
  4659.3 2026.06  4736.4 2021.62  4751.0 2021.53  4792.8 2018.53  4812.2 2018.31
  4844.2 2016.04  4895.6 2013.70  4924.3 2007.99  4941.9 2002.48  4947.0 2004.60
  4954.8 2001.38  4965.0 1999.38  4985.4 1998.63  4998.0 1999.53  4999.9 1998.02
  5000.4 1997.52  5012.0 1998.02  5026.7 2000.89  5057.8 2000.56  5072.7 2001.16
  5112.2 2004.62  5120.0 2006.29  5130.4 2007.31  5146.5 2007.13  5186.0 2009.05
  5254.7 2009.67  5280.7 2010.59  5389.8 2012.44  5554.8 2019.55  5690.7 2025.11
#Mann=5,-1,0
  4659.3    0.07       0  4999.9    0.07       0  5012.0    0.07       0
  5280.7   0.035       0  5554.8    0.07       0
Bank Sta=4999.9,5012
Exp/Cntr=0.3,0.1

Type RM Length L Ch R = 1,5000,500,500,500
BEGIN DESCRIPTION:
Cottonwood Creek Trib120 10.0
END DESCRIPTION:
XS GIS Cut Line= 3
      1375804.98      6931787.99      1376004.99      6931854.90
      1376654.96      6931738.01
#Sta/Elev= 30
  4789.1 2019.55  4836.5 2017.39  4905.1 2012.70  4915.7 2010.20  4925.9 2006.17
  4962.3 1997.29  4962.8 1996.79  4974.4 1997.29  4977.6 1998.10  4989.1 1999.11
  5061.0 1999.48  5071.7 2000.52  5081.3 1999.22  5132.1 2000.86  5193.1 2000.91
  5203.2 2000.24  5232.1 2001.15  5237.8 2000.87  5254.0 2006.31  5264.2 2008.16
  5284.5 2010.37  5315.0 2010.69  5325.1 2011.91  5335.3 2011.13  5365.8 2011.59
  5375.9 2012.75  5386.1 2012.08  5416.6 2012.55  5574.9 2018.38  5660.4 2020.53
#Mann=5,-1,0
  4789.1    0.07       0  4962.3   0.035       0  4974.4    0.07       0
  4977.6   0.035       0  5232.1    0.07       0
Bank Sta=4962.3,4974.4
Exp/Cntr=0.3,0.1

Type RM Length L Ch R = 1,4500,636,636,636
BEGIN DESCRIPTION:
Cottonwood Creek Trib120 9.0
END DESCRIPTION:
XS GIS Cut Line= 3
      1375755.00      6932088.00      1376106.05      6932287.75
      1376905.03      6932488.01
#Sta/Elev= 30
  4596.1 2025.90  4625.6 2022.01  4684.7 2017.09  4787.1 2010.48  4830.3 2004.27
  4851.9 2002.19  4918.3 2000.31  4948.5 1998.43  5009.2 1997.82  5016.9 1995.66
  5017.4 1995.16  5029.4 1995.66  5029.8 1996.77  5040.2 1999.77  5059.2 2001.59
  5064.3 2003.67  5071.1 2004.79  5122.6 2010.71  5146.7 2011.48  5270.2 2009.99
  5462.8 2012.46  5493.8 2014.45  5565.9 2015.80  5594.6 2018.41  5617.5 2017.84
  5682.1 2019.69  5710.3 2022.48  5741.2 2022.19  5792.7 2023.93  5823.7 2026.48
#Mann=3,-1,0
  4596.1    0.07       0  5016.9    0.07       0  5029.4    0.07       0
Bank Sta=5016.9,5029.4
Exp/Cntr=0.3,0.1

Type RM Length L Ch R = 1,3864,364,364,364
BEGIN DESCRIPTION:
Cottonwood Creek Trib120 8.0
END DESCRIPTION:
XS GIS Cut Line= 4
      1375475.08      6932630.16      1375947.34      6932769.06
      1376322.34      6932803.78      1376855.04      6932687.99
#Sta/Elev= 30
  4499.7 2026.46  4512.5 2025.51  4572.6 2024.42  4584.4 2023.17  4689.7 2021.42
  4718.7 2020.14  4789.8 2014.58  4812.3 2007.33  4828.3 2005.63  4861.7 2003.70
  4874.9 2003.74  4900.3 2002.20  4916.6 2000.23  4972.8 1996.90  4973.3 1996.40
  4985.4 1996.90  5144.2 2001.34  5210.6 2002.16  5331.1 2007.29  5616.9 2012.04
  5637.4 2013.01  5647.6 2014.40  5688.5 2014.35  5739.7 2016.76  5746.8 2018.24
  5790.9 2018.32  5821.6 2020.00  5840.0 2022.04  5883.0 2022.53  5913.7 2024.16
#Mann=4,-1,0
  4499.7   0.035       0  4718.7    0.07       0  4972.8    0.07       0
  4985.4    0.07       0
Bank Sta=4972.8,4985.4
Exp/Cntr=0.3,0.1

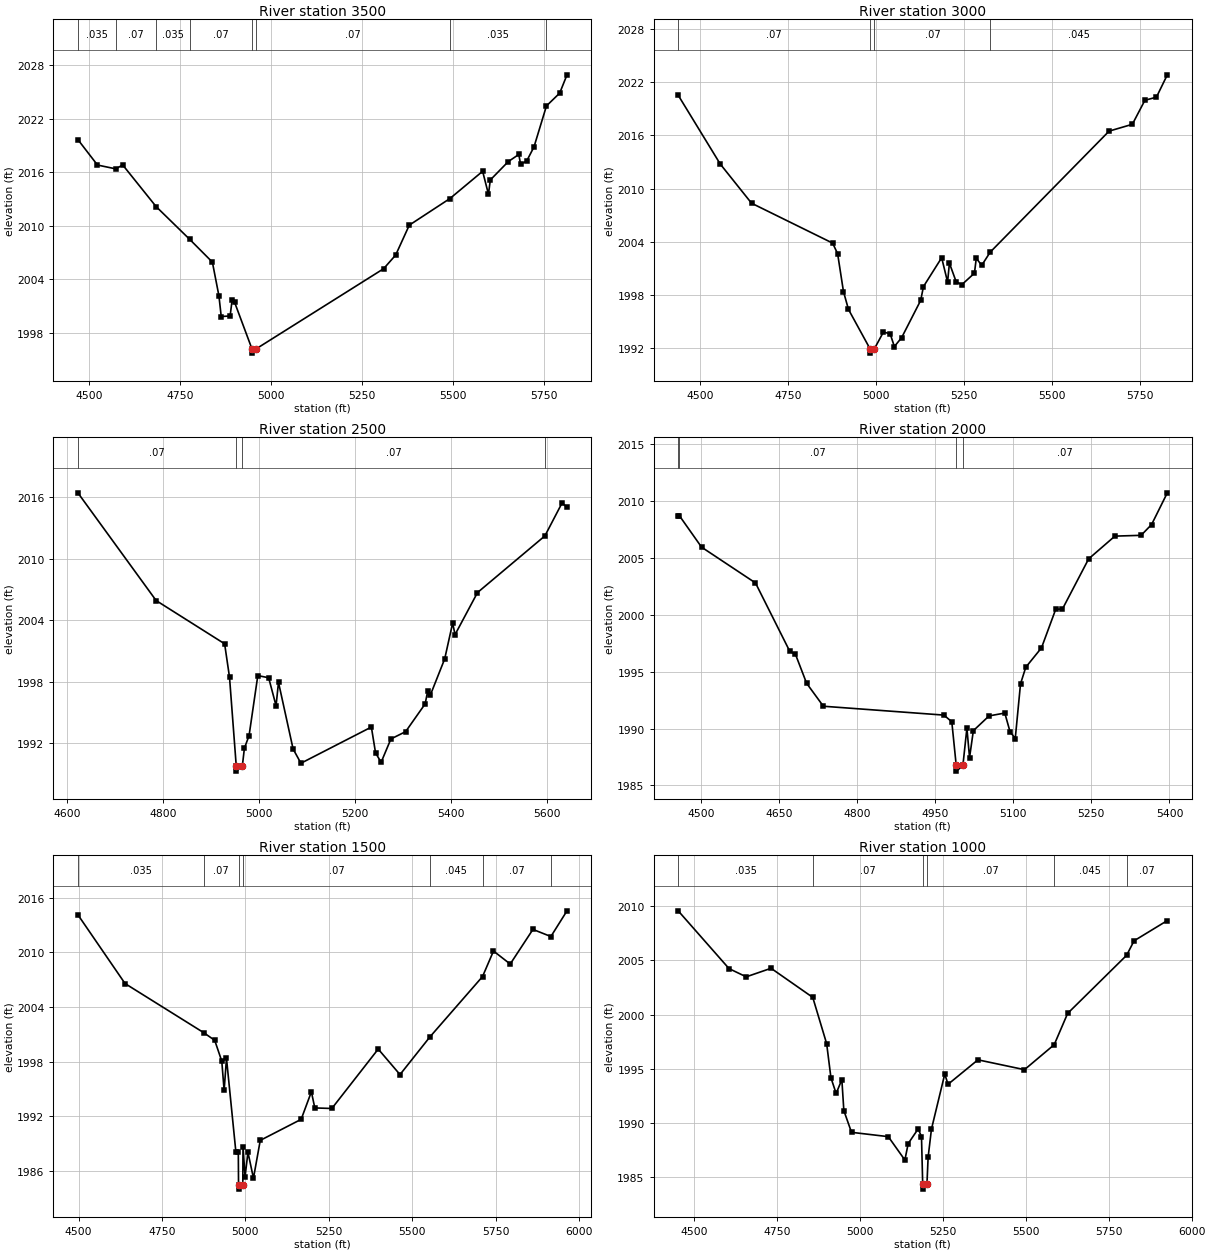
Type RM Length L Ch R = 1,3500,500,500,500
BEGIN DESCRIPTION:
Cottonwood Creek Trib120 7.0
END DESCRIPTION:
XS GIS Cut Line= 3
      1375604.98      6932887.99      1376097.62      6933082.66
      1376904.99      6932988.00
#Sta/Elev= 30
  4470.3 2019.64  4524.1 2016.79  4574.4 2016.36  4593.4 2016.80  4685.0 2012.14
  4777.2 2008.47  4839.5 2005.92  4857.4 2002.16  4863.8 1999.83  4888.2 1999.89
  4893.6 2001.64  4900.4 2001.43  4947.9 1996.23  4948.4 1995.73  4960.5 1996.23
  5309.5 2005.18  5342.6 2006.71  5380.0 2010.06  5491.6 2013.04  5581.3 2016.09
  5597.3 2013.52  5602.4 2015.12  5651.8 2017.18  5680.5 2017.97  5685.6 2016.88
  5702.2 2017.24  5722.3 2018.82  5756.5 2023.41  5792.8 2024.84  5812.9 2026.89
#Mann=8,-1,0
  4470.3   0.035       0  4574.4    0.07       0  4685.0   0.035       0
  4777.2    0.07       0  4947.9    0.07       0  4960.5    0.07       0
  5491.6   0.035       0  5756.5    0.07       0
Bank Sta=4947.9,4960.5
Exp/Cntr=0.3,0.1

Type RM Length L Ch R = 1,3000,500,500,500
BEGIN DESCRIPTION:
Cottonwood Creek Trib120 6.0
END DESCRIPTION:
XS GIS Cut Line= 3
      1375555.04      6933787.98      1376054.63      6933532.12
      1376854.97      6933737.99
#Sta/Elev= 30
  4438.7 2020.53  4558.0 2012.77  4646.8 2008.35  4876.8 2003.85  4891.0 2002.66
  4907.6 1998.39  4921.8 1996.37  4982.8 1991.94  4983.3 1991.44  4995.5 1991.94
  5021.0 1993.82  5040.1 1993.62  5052.0 1992.18  5072.7 1993.19  5126.7 1997.39
  5134.6 1998.95  5186.2 2002.20  5203.0 1999.46  5208.2 2001.59  5227.5 1999.47
  5243.7 1999.17  5279.2 2000.46  5284.4 2002.14  5299.8 2001.34  5323.9 2002.83
  5661.2 2016.48  5727.2 2017.25  5762.8 2019.96  5795.5 2020.31  5826.4 2022.83
#Mann=4,-1,0
  4438.7    0.07       0  4982.8    0.07       0  4995.5    0.07       0
  5323.9   0.045       0
Bank Sta=4982.8,4995.5
Exp/Cntr=0.3,0.1

Type RM Length L Ch R = 1,2500,500,500,500
BEGIN DESCRIPTION:
Cottonwood Creek Trib120 5.0
END DESCRIPTION:
XS GIS Cut Line= 3
      1375654.97      6933937.99      1376025.59      6934009.71
      1376655.03      6933887.99
#Sta/Elev= 30
  4622.5 2016.45  4785.5 2005.94  4928.1 2001.72  4938.3 1998.46  4952.3 1989.80
  4952.8 1989.30  4965.0 1989.80  4969.3 1991.54  4979.0 1992.76  4997.2 1998.62
  5019.8 1998.41  5035.2 1995.68  5040.3 1997.96  5070.7 1991.46  5087.0 1990.07
  5233.7 1993.60  5242.4 1991.08  5254.0 1990.16  5274.4 1992.44  5305.0 1993.15
  5345.7 1995.86  5351.1 1997.13  5356.2 1996.68  5386.4 2000.25  5402.9 2003.74
  5408.0 2002.62  5454.7 2006.72  5595.1 2012.25  5630.9 2015.47  5641.1 2015.03
#Mann=4,-1,0
  4622.5    0.07       0  4952.3    0.07       0  4965.0    0.07       0
  5595.1   0.045       0
Bank Sta=4952.3,4965
Exp/Cntr=0.3,0.1

Type RM Length L Ch R = 1,2000,500,500,500
BEGIN DESCRIPTION:
Cottonwood Creek Trib120 4.0
END DESCRIPTION:
XS GIS Cut Line= 3
      1375754.99      6934038.00      1376261.89      6934234.61
      1376655.04      6934188.00
#Sta/Elev= 30
  4456.3 2008.72  4458.7 2008.72  4501.2 2005.96  4604.8 2002.81  4670.8 1996.78
  4681.6 1996.53  4703.0 1993.98  4735.2 1991.96  4966.8 1991.18  4981.9 1990.59
  4990.4 1986.75  4990.9 1986.25  5003.2 1986.75  5010.9 1990.03  5016.0 1987.44
  5023.3 1989.81  5053.5 1991.11  5083.7 1991.36  5093.7 1989.73  5103.8 1989.12
  5113.9 1993.93  5124.0 1995.39  5154.2 1997.10  5181.5 2000.49  5194.5 2000.52
  5244.8 2004.93  5295.2 2006.93  5345.5 2007.00  5365.7 2007.95  5395.9 2010.74
#Mann=4,-1,0
  4456.3   0.035       0  4458.7    0.07       0  4990.4    0.07       0
  5003.2    0.07       0
Bank Sta=4990.4,5003.2
Exp/Cntr=0.3,0.1

Type RM Length L Ch R = 1,1500,500,500,500
BEGIN DESCRIPTION:
Cottonwood Creek Trib120 3.0
END DESCRIPTION:
XS GIS Cut Line= 3
      1375605.03      6934088.03      1375961.20      6934441.66
      1376904.99      6934638.00
#Sta/Elev= 30
  4498.1 2014.13  4639.5 2006.58  4875.2 2001.19  4908.2 2000.35  4929.4 1998.06
  4936.4 1994.85  4943.5 1998.37  4971.8 1988.04  4978.9 1988.12  4979.6 1984.52
  4980.1 1984.02  4992.4 1984.52  4993.0 1988.68  4999.2 1985.38  5007.8 1988.07
  5024.3 1985.22  5044.7 1989.37  5167.3 1991.68  5197.9 1994.70  5208.2 1992.93
  5259.2 1992.87  5398.2 1999.39  5463.5 1996.59  5553.3 2000.73  5710.9 2007.35
  5743.7 2010.15  5793.8 2008.72  5861.9 2012.52  5915.7 2011.74  5964.0 2014.56
#Mann=7,-1,0
  4498.1   0.035       0  4875.2    0.07       0  4979.6    0.07       0
  4992.4    0.07       0  5553.3   0.045       0  5710.9    0.07       0
  5915.7   0.045       0
Bank Sta=4979.6,4992.4
Exp/Cntr=0.3,0.1

Type RM Length L Ch R = 1,1000,500,500,500
BEGIN DESCRIPTION:
Cottonwood Creek Trib120 2.0
END DESCRIPTION:
XS GIS Cut Line= 3
      1375604.99      6934187.98      1375829.77      6934687.76
      1376755.01      6934738.00
#Sta/Elev= 30
  4452.0 2009.59  4605.3 2004.25  4657.1 2003.49  4732.0 2004.28  4857.7 2001.59
  4899.6 1997.31  4912.5 1994.16  4928.2 1992.71  4945.4 1993.99  4951.4 1991.13
  4974.5 1989.12  5085.4 1988.72  5135.4 1986.56  5145.4 1988.08  5175.5 1989.44
  5185.5 1988.72  5189.1 1984.37  5189.6 1983.87  5202.0 1984.37  5205.5 1986.82
  5215.5 1989.41  5255.6 1994.50  5265.6 1993.56  5355.7 1995.82  5496.0 1994.91
  5585.6 1997.22  5626.1 2000.11  5803.9 2005.48  5826.4 2006.82  5926.6 2008.69
#Mann=6,-1,0
  4452.0   0.035       0  4857.7    0.07       0  5189.1    0.07       0
  5202.0    0.07       0  5585.6   0.045       0  5803.9    0.07       0
Bank Sta=5189.1,5202
Exp/Cntr=0.3,0.1

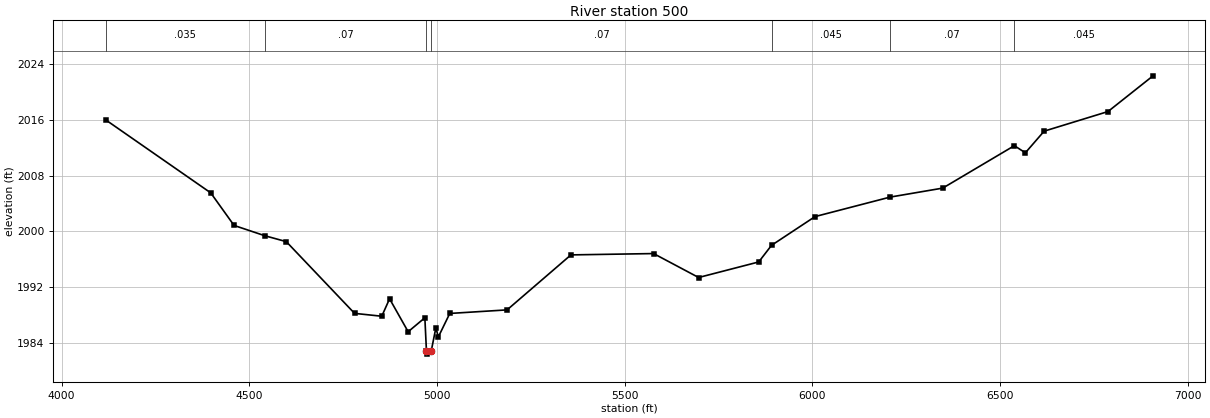
Type RM Length L Ch R = 1,500,0,0,0
BEGIN DESCRIPTION:
Cottonwood Creek Trib120 1.0
END DESCRIPTION:
XS GIS Cut Line= 5
      1375605.00      6934038.00      1375394.56      6934818.60
      1375418.79      6934888.14      1375443.17      6934926.24
      1377305.01      6934988.00
#Sta/Elev= 30
  4117.9 2015.97  4397.5 2005.52  4459.7 2000.85  4542.0 1999.37  4598.8 1998.53
  4780.7 1988.25  4853.2 1987.84  4874.0 1990.34  4923.5 1985.62  4968.0 1987.62
  4972.2 1982.91  4972.7 1982.41  4985.2 1982.91  4997.3 1986.17  5004.0 1984.88
  5034.4 1988.24  5187.1 1988.75  5357.2 1996.63  5577.4 1996.82  5697.4 1993.39
  5857.5 1995.62  5891.6 1998.00  6007.6 2002.12  6207.4 2004.91  6347.8 2006.20
  6538.6 2012.28  6567.9 2011.26  6617.9 2014.36  6788.0 2017.17  6908.1 2022.29
#Mann=7,-1,0
  4117.9   0.035       0  4542.0    0.07       0  4972.2    0.07       0
  4985.2    0.07       0  5891.6   0.045       0  6207.4    0.07       0
  6538.6   0.045       0
Bank Sta=4972.2,4985.2
Exp/Cntr=0.3,0.1

Chan Stop Cuts=-1