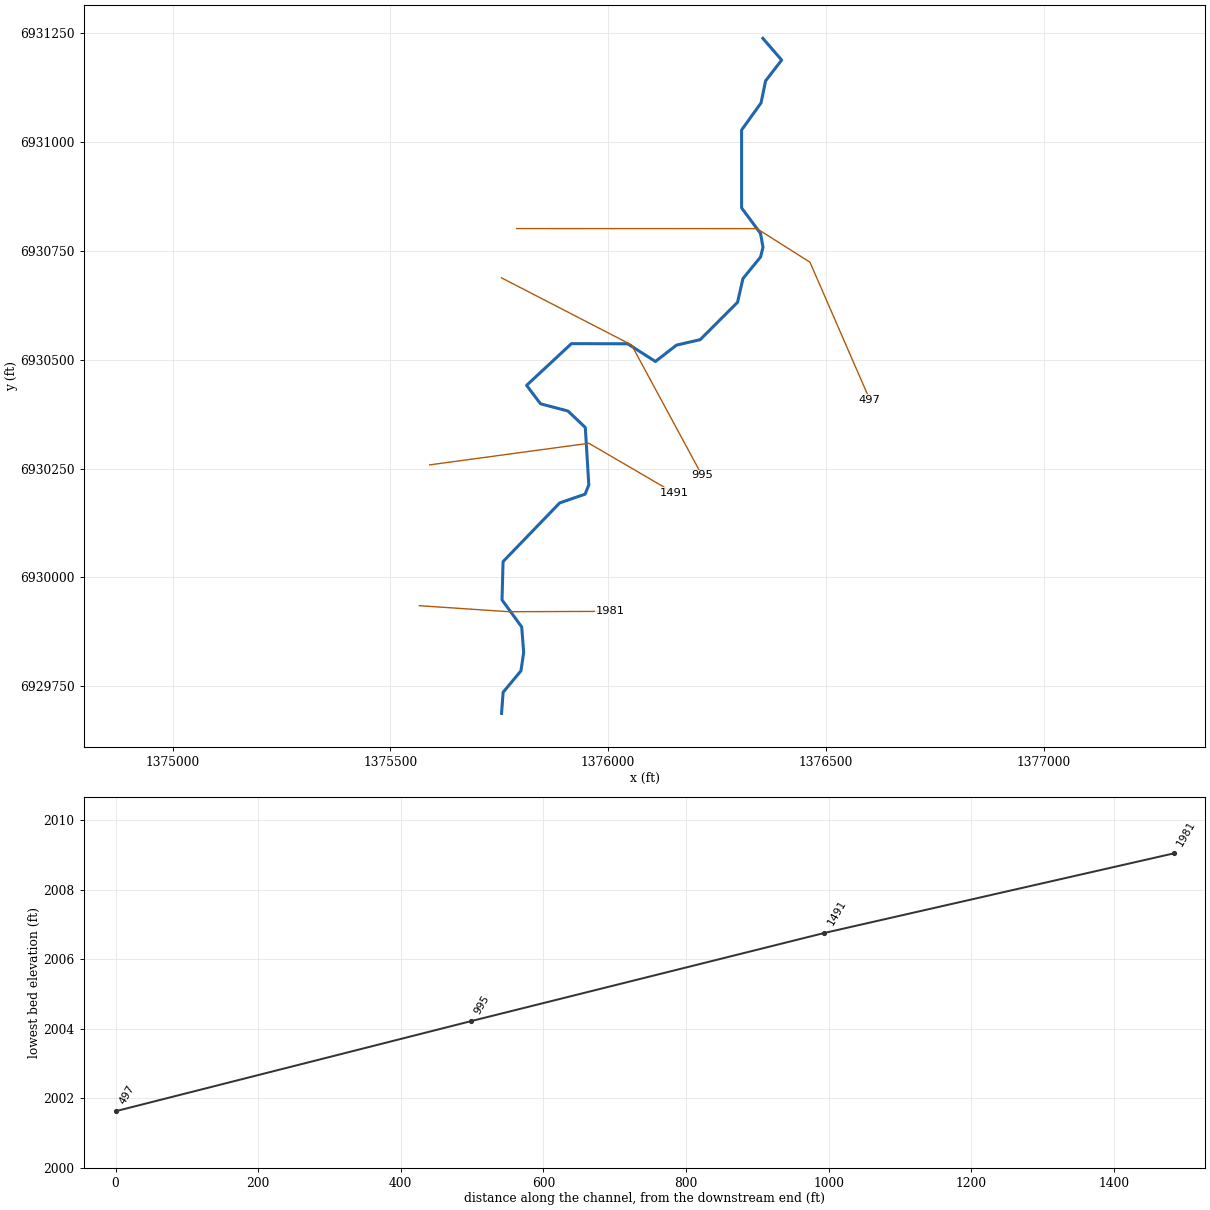
--- Cottonwood Creek Trib120_3.prj (project) ---

Proj Title=Cottonwood Creek Trib120_3 Base Level Engineering
Current Plan=p01
Default Exp/Contr=0.3,0.1
English Units
Geom File=g01
Flow File=f01
Plan File=p01
BEGIN DESCRIPTION:
Cottonwood Creek Trib120_3
END DESCRIPTION:

--- Cottonwood Creek Trib120_3.p01 (plan) ---

Plan Title=Multiple Run
Short Identifier=Multiple
Geom File=g01
Flow File=f01
Subcritical Flow
K Sum by GR= 0
Std Step Tol= 0.01
Critical Tol= 0.01
Num of Std Step Trials= 20
Max Error Tol= 0.3
Flow Tol Ratio= 0.001
Split Flow NTrial= 30
Split Flow Tol= 0.02
Split Flow Ratio= 0.02
Log Output Level= 0
Friction Slope Method= 1
Unsteady Friction Slope Method= 2
Unsteady Bridges Friction Slope Method= 1
Parabolic Critical Depth
Global Vel Dist=  1 , 1 , 1
Global Log Level= 0
CheckData=True
Encroach Param= -1, 0, 0, 0
BEGIN DESCRIPTION:
Multiple Run
END DESCRIPTION:

--- Cottonwood Creek Trib120_3.f01 (steady flow) ---

Flow Title=Multiple
Number of Profiles=7
Profile Names=10-year,25-year,50-year,1pct_min,100-year,1pct_plu,500-year
River Rch & RM= Cottonwood Creek,Reach-1,1981
     271     384     479     297     593    1184     923
Boundary for River Rch & Prof#=Cottonwood Creek,Reach-1,1
Up Type=0
Dn Type=3
Dn Slope=0.005
Boundary for River Rch & Prof#=Cottonwood Creek,Reach-1,2
Up Type=0
Dn Type=3
Dn Slope=0.005
Boundary for River Rch & Prof#=Cottonwood Creek,Reach-1,3
Up Type=0
Dn Type=3
Dn Slope=0.005
Boundary for River Rch & Prof#=Cottonwood Creek,Reach-1,4
Up Type=0
Dn Type=3
Dn Slope=0.005
Boundary for River Rch & Prof#=Cottonwood Creek,Reach-1,5
Up Type=0
Dn Type=3
Dn Slope=0.005
Boundary for River Rch & Prof#=Cottonwood Creek,Reach-1,6
Up Type=0
Dn Type=3
Dn Slope=0.005
Boundary for River Rch & Prof#=Cottonwood Creek,Reach-1,7
Up Type=0
Dn Type=3
Dn Slope=0.005

--- Cottonwood Creek Trib120_3.g01 (geometry) ---

Geom Title=Existing Conditions

River Reach=Cottonwood Creek,Reach-1
Reach XY= 30
      1375755.00      6929688.00      1375758.65      6929736.49
      1375799.54      6929785.61      1375805.79      6929827.95
      1375801.29      6929886.40      1375756.10      6929948.55
      1375758.46      6930036.50      1375888.55      6930171.26
      1375946.90      6930191.39      1375955.36      6930212.80
      1375947.31      6930344.47      1375907.52      6930382.26
      1375844.58      6930398.79      1375812.51      6930441.17
      1375915.42      6930536.96      1376044.56      6930536.63
      1376108.32      6930496.04      1376156.65      6930533.55
      1376211.07      6930546.11      1376296.87      6930631.93
      1376309.25      6930686.26      1376349.66      6930735.80
      1376355.30      6930758.17      1376349.63      6930790.18
      1376306.24      6930848.50      1376306.20      6931027.50
      1376350.84      6931089.74      1376361.27      6931140.32
      1376398.13      6931188.12      1376355.00      6931238.00

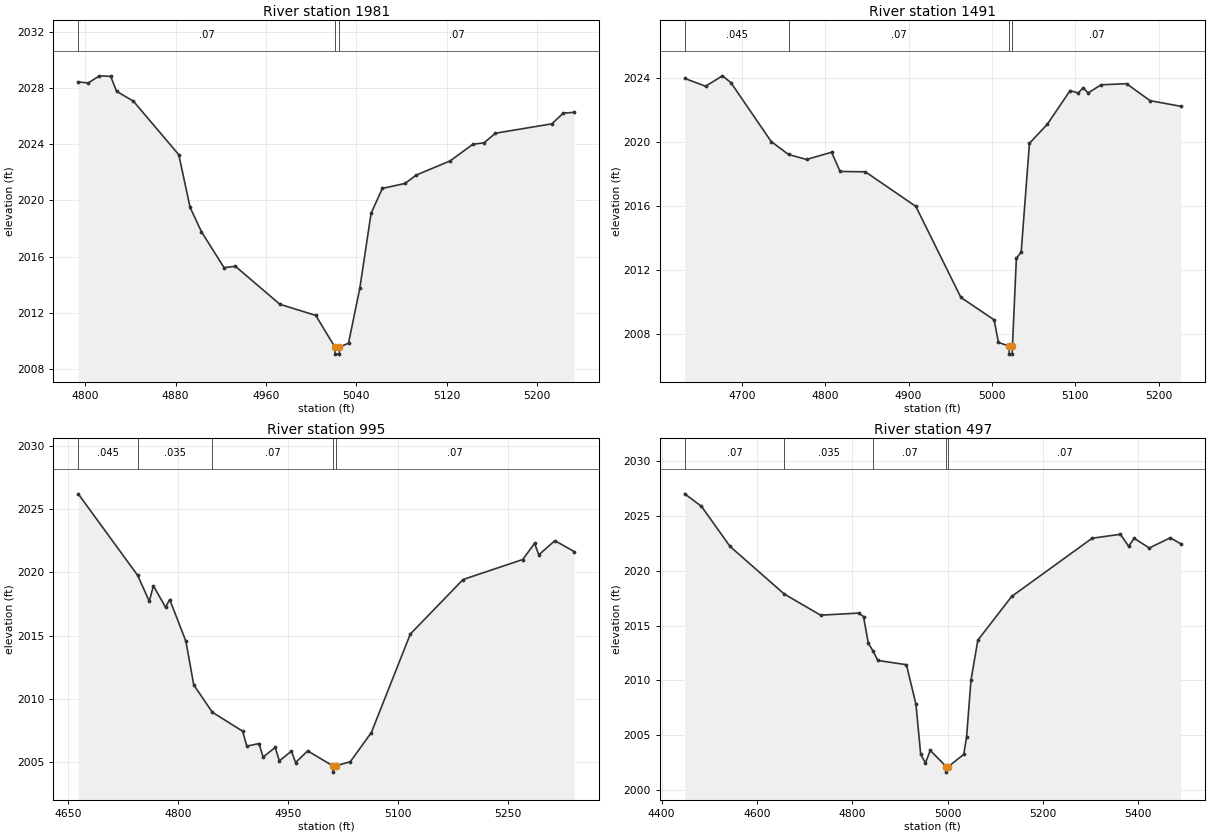
Type RM Length L Ch R = 1,1981,490,490,490
BEGIN DESCRIPTION:
Cottonwood Creek Trib120_3 4.0
END DESCRIPTION:
XS GIS Cut Line= 3
      1375566.24      6929935.29      1375771.87      6929921.43
      1376004.67      6929922.27
#Sta/Elev= 30
  4793.9 2028.45  4802.7 2028.37  4812.7 2028.88  4822.7 2028.84  4827.8 2027.78
  4842.8 2027.07  4882.9 2023.26  4892.9 2019.51  4902.9 2017.78  4923.0 2015.21
  4933.0 2015.31  4972.4 2012.60  5004.1 2011.81  5021.1 2009.55  5021.4 2009.05
  5024.9 2009.05  5025.1 2009.55  5033.1 2009.83  5043.1 2013.74  5053.1 2019.09
  5063.1 2020.86  5083.1 2021.21  5093.1 2021.81  5123.1 2022.82  5143.1 2024.00
  5153.1 2024.11  5163.1 2024.79  5213.1 2025.46  5223.1 2026.22  5232.8 2026.28
#Mann=3,-1,0
  4793.9    0.07       0  5021.1    0.07       0  5025.1    0.07       0
Bank Sta=5021.1,5025.1
Exp/Cntr=0.3,0.1

Type RM Length L Ch R = 1,1491,496,496,496
BEGIN DESCRIPTION:
Cottonwood Creek Trib120_3 3.0
END DESCRIPTION:
XS GIS Cut Line= 3
      1375590.15      6930258.64      1375955.51      6930308.20
      1376151.09      6930194.18
#Sta/Elev= 30
  4631.3 2023.97  4656.4 2023.48  4676.6 2024.13  4686.7 2023.71  4735.1 2020.03
  4755.9 2019.22  4777.5 2018.91  4807.6 2019.36  4817.8 2018.16  4848.1 2018.14
  4908.7 2015.98  4962.7 2010.30  5002.6 2008.90  5007.8 2007.49  5020.6 2007.26
  5020.8 2006.76  5024.3 2006.76  5024.6 2007.26  5029.3 2012.73  5035.1 2013.14
  5045.0 2019.92  5066.5 2021.11  5093.8 2023.21  5103.6 2023.06  5109.5 2023.39
  5115.3 2023.06  5131.0 2023.57  5161.5 2023.64  5189.7 2022.58  5226.4 2022.23
#Mann=4,-1,0
  4631.3   0.045       0  4755.9    0.07       0  5020.6    0.07       0
  5024.6    0.07       0
Bank Sta=5020.6,5024.6
Exp/Cntr=0.3,0.1

Type RM Length L Ch R = 1,995,498,498,498
BEGIN DESCRIPTION:
Cottonwood Creek Trib120_3 2.0
END DESCRIPTION:
XS GIS Cut Line= 3
      1375755.01      6930687.99      1376053.53      6930533.99
      1376215.14      6930234.75
#Sta/Elev= 30
  4664.1 2026.21  4745.2 2019.76  4761.0 2017.72  4766.6 2018.94  4783.1 2017.25
  4788.8 2017.86  4810.9 2014.56  4821.6 2011.11  4846.8 2008.96  4888.3 2007.45
  4893.9 2006.27  4910.5 2006.48  4916.1 2005.41  4932.6 2006.17  4938.3 2005.11
  4954.8 2005.88  4960.4 2004.98  4976.9 2005.90  5011.0 2004.72  5011.3 2004.22
  5015.1 2004.72  5034.9 2005.04  5063.6 2007.34  5116.8 2015.13  5188.7 2019.44
  5270.0 2021.02  5286.2 2022.30  5291.9 2021.39  5313.8 2022.51  5340.1 2021.65
#Mann=5,-1,0
  4664.1   0.045       0  4745.2   0.035       0  4846.8    0.07       0
  5011.0    0.07       0  5015.1    0.07       0
Bank Sta=5011,5015.1
Exp/Cntr=0.3,0.1

Type RM Length L Ch R = 1,497,0,0,0
BEGIN DESCRIPTION:
Cottonwood Creek Trib120_3 1.0
END DESCRIPTION:
XS GIS Cut Line= 4
      1375789.76      6930801.17      1376341.46      6930801.04
      1376463.12      6930723.98      1376600.71      6930407.84
#Sta/Elev= 30
  4448.3 2027.02  4483.5 2025.88  4543.5 2022.22  4657.2 2017.88  4733.5 2015.95
  4813.5 2016.14  4823.5 2015.82  4833.5 2013.40  4843.7 2012.66  4853.5 2011.82
  4913.5 2011.43  4933.5 2007.83  4943.5 2003.24  4953.5 2002.47  4963.5 2003.61
  4997.2 2002.13  4997.5 2001.63  5001.3 2002.13  5033.8 2003.25  5039.7 2004.82
  5049.0 2010.03  5063.4 2013.67  5134.4 2017.66  5303.2 2022.97  5362.5 2023.33
  5379.6 2022.24  5391.4 2022.96  5423.2 2022.08  5467.1 2023.01  5488.8 2022.47
#Mann=5,-1,0
  4448.3    0.07       0  4657.2   0.035       0  4843.7    0.07       0
  4997.2    0.07       0  5001.3    0.07       0
Bank Sta=4997.2,5001.3
Exp/Cntr=0.3,0.1

Chan Stop Cuts=-1