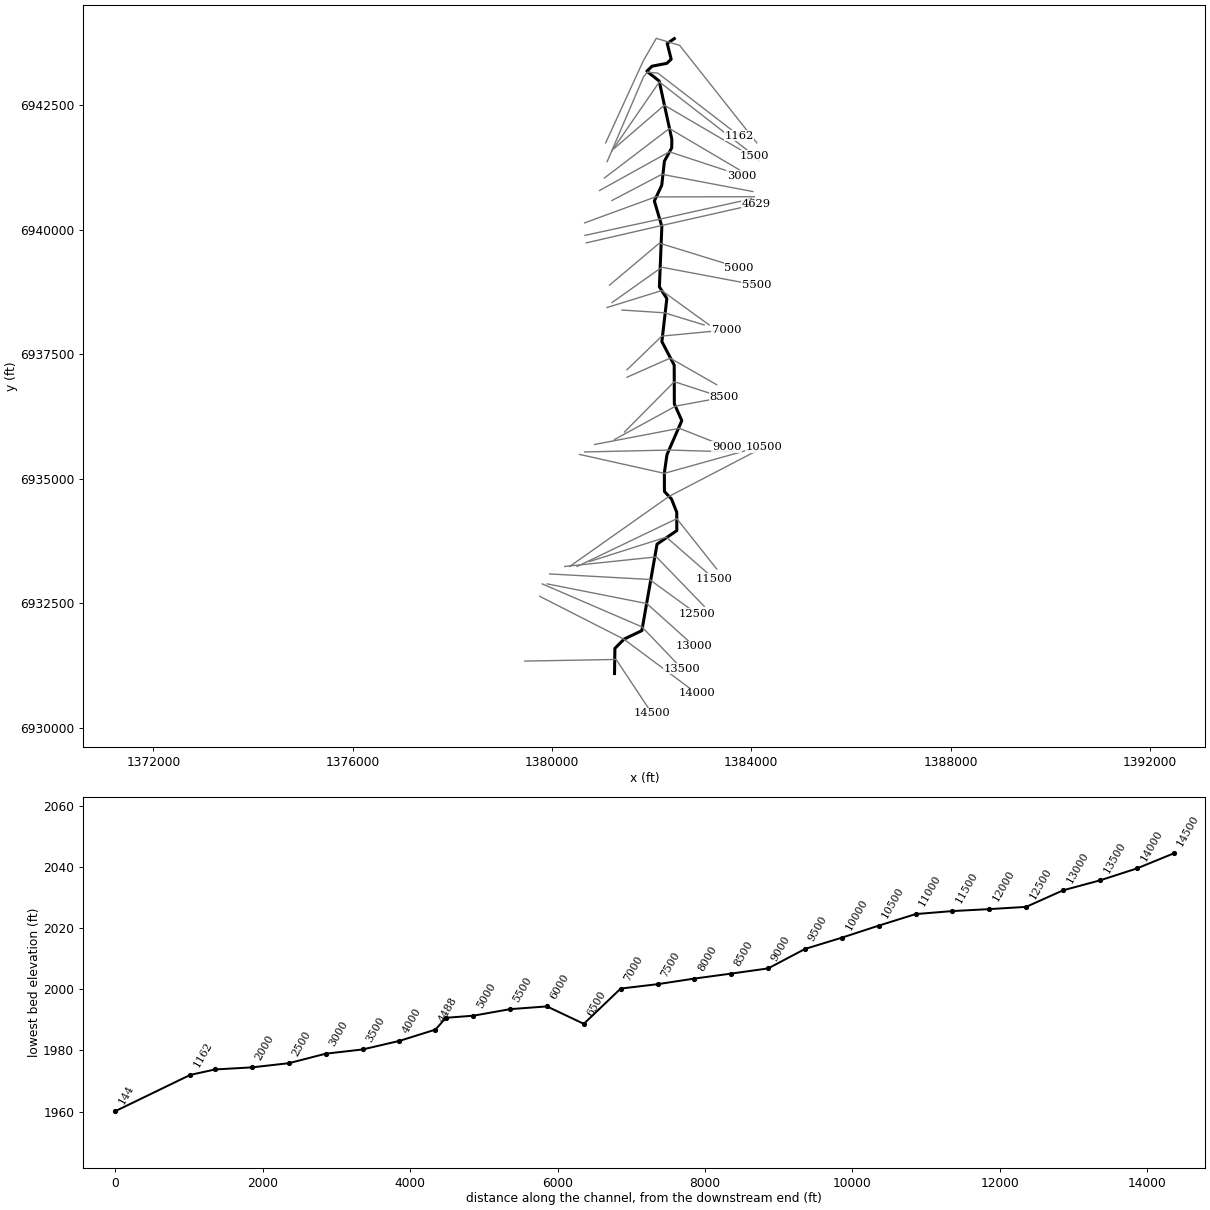
--- Cottonwood Creek Trib126.prj (project) ---

Proj Title=Cottonwood Creek Trib126 Base Level Engineering
Current Plan=p01
Default Exp/Contr=0.3,0.1
English Units
Geom File=g01
Flow File=f01
Plan File=p01
BEGIN DESCRIPTION:
Cottonwood Creek Trib126
END DESCRIPTION:

--- Cottonwood Creek Trib126.p01 (plan) ---

Plan Title=Multiple Run
Short Identifier=Multiple
Geom File=g01
Flow File=f01
Subcritical Flow
K Sum by GR= 0
Std Step Tol= 0.01
Critical Tol= 0.01
Num of Std Step Trials= 20
Max Error Tol= 0.3
Flow Tol Ratio= 0.001
Split Flow NTrial= 30
Split Flow Tol= 0.02
Split Flow Ratio= 0.02
Log Output Level= 0
Friction Slope Method= 1
Unsteady Friction Slope Method= 2
Unsteady Bridges Friction Slope Method= 1
Parabolic Critical Depth
Global Vel Dist=  1 , 1 , 1
Global Log Level= 0
CheckData=True
Encroach Param= -1, 0, 0, 0
BEGIN DESCRIPTION:
Multiple Run
END DESCRIPTION:

--- Cottonwood Creek Trib126.f01 (steady flow) ---

Flow Title=Multiple
Number of Profiles=7
Profile Names=10-year,25-year,50-year,1pct_min,100-year,1pct_plu,500-year
River Rch & RM= Cottonwood Creek,Reach-1,14500
     213     295     361     221     440     879     662
River Rch & RM= Cottonwood Creek,Reach-1,13500
     367     526     660     411     821    1638    1287
River Rch & RM= Cottonwood Creek,Reach-1,9000
     473     684     865     542    1082    2159    1718
River Rch & RM= Cottonwood Creek,Reach-1,2500
     546     796    1011     637    1271    2536    2038
Boundary for River Rch & Prof#=Cottonwood Creek,Reach-1,1
Up Type=0
Dn Type=3
Dn Slope=0.005
Boundary for River Rch & Prof#=Cottonwood Creek,Reach-1,2
Up Type=0
Dn Type=3
Dn Slope=0.005
Boundary for River Rch & Prof#=Cottonwood Creek,Reach-1,3
Up Type=0
Dn Type=3
Dn Slope=0.005
Boundary for River Rch & Prof#=Cottonwood Creek,Reach-1,4
Up Type=0
Dn Type=3
Dn Slope=0.005
Boundary for River Rch & Prof#=Cottonwood Creek,Reach-1,5
Up Type=0
Dn Type=3
Dn Slope=0.005
Boundary for River Rch & Prof#=Cottonwood Creek,Reach-1,6
Up Type=0
Dn Type=3
Dn Slope=0.005
Boundary for River Rch & Prof#=Cottonwood Creek,Reach-1,7
Up Type=0
Dn Type=3
Dn Slope=0.005

--- Cottonwood Creek Trib126.g01 (geometry) ---

Geom Title=Existing Conditions

River Reach=Cottonwood Creek,Reach-1
Reach XY= 30
      1381255.00      6931088.00      1381262.81      6931594.19
      1381448.83      6931780.14      1381803.50      6931949.53
      1382108.45      6933686.75      1382504.96      6933958.18
      1382503.80      6934327.50      1382399.48      6934590.43
      1382257.06      6934743.85      1382254.80      6935113.08
      1382307.26      6935482.06      1382605.28      6936167.82
      1382455.51      6936503.21      1382452.76      6937282.07
      1382205.52      6937753.22      1382305.04      6938618.02
      1382155.50      6938853.21      1382204.95      6940067.96
      1382054.23      6940577.95      1382202.93      6940893.86
      1382256.20      6941377.50      1382402.76      6941643.93
      1382404.93      6941817.97      1382151.46      6942986.54
      1381903.97      6943183.26      1382006.52      6943284.26
      1382303.52      6943341.61      1382391.89      6943424.76
      1382312.77      6943741.43      1382455.00      6943838.00

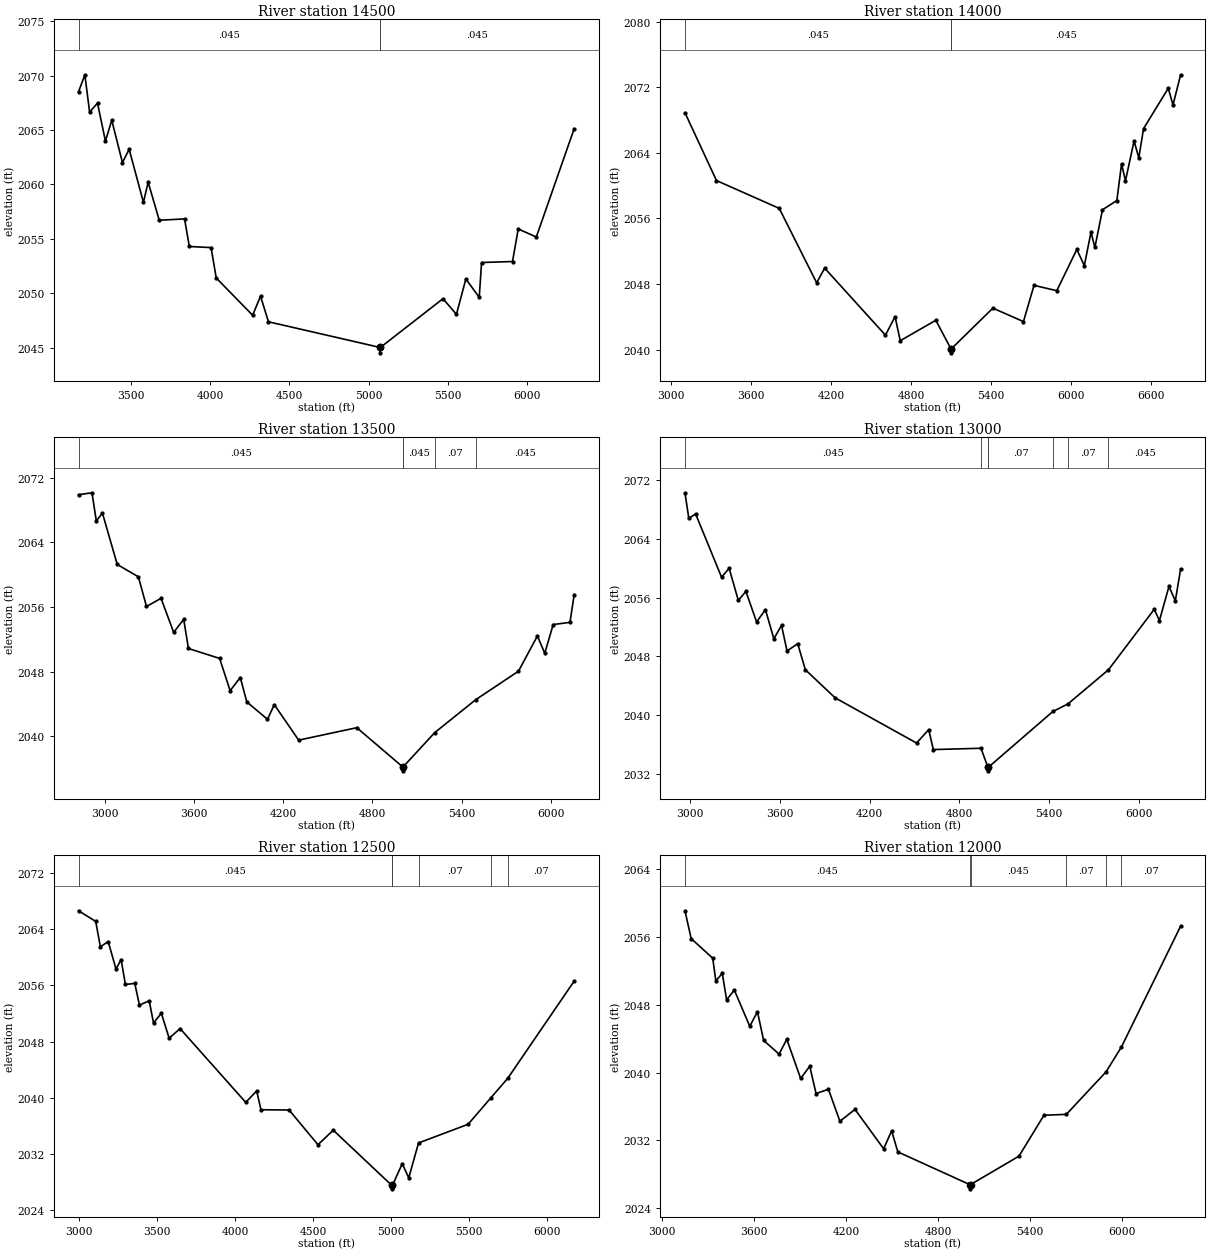
Type RM Length L Ch R = 1,14500,500,500,500
BEGIN DESCRIPTION:
Cottonwood Creek Trib126 29.0
END DESCRIPTION:
XS GIS Cut Line= 3
      1379454.95      6931338.00      1381287.56      6931370.73
      1382005.02      6930287.97
#Sta/Elev= 30
  3167.1 2068.50  3207.2 2070.07  3237.2 2066.65  3287.2 2067.47  3337.2 2063.98
  3377.2 2065.90  3444.7 2062.01  3487.2 2063.23  3577.2 2058.36  3607.2 2060.21
  3677.2 2056.72  3837.3 2056.84  3867.3 2054.31  4004.7 2054.21  4037.3 2051.42
  4267.3 2048.00  4317.3 2049.75  4367.3 2047.40  5071.0 2045.05  5071.3 2044.55
  5075.0 2045.05  5470.1 2049.52  5555.1 2048.08  5614.5 2051.33  5699.1 2049.64
  5713.8 2052.84  5909.3 2052.93  5945.4 2055.92  6059.7 2055.18  6298.9 2065.12
#Mann=3,-1,0
  3167.1   0.045       0  5071.0   0.045       0  5075.0   0.045       0
Bank Sta=5071,5075
Exp/Cntr=0.3,0.1

Type RM Length L Ch R = 1,14000,500,500,500
BEGIN DESCRIPTION:
Cottonwood Creek Trib126 28.0
END DESCRIPTION:
XS GIS Cut Line= 3
      1379754.96      6932638.02      1381444.63      6931777.00
      1382905.00      6930688.00
#Sta/Elev= 30
  3103.6 2068.89  3339.9 2060.62  3810.7 2057.23  4091.3 2048.15  4151.4 2049.94
  4607.2 2041.77  4679.5 2044.02  4718.4 2041.09  4985.2 2043.58  5098.3 2040.11
  5098.5 2039.61  5102.3 2040.11  5413.3 2045.06  5642.6 2043.42  5721.9 2047.84
  5892.8 2047.19  6043.0 2052.22  6099.2 2050.25  6149.3 2054.32  6178.5 2052.46
  6235.4 2057.06  6343.2 2058.18  6378.6 2062.66  6407.8 2060.58  6472.4 2065.46
  6507.9 2063.39  6543.4 2066.95  6728.9 2071.88  6764.4 2069.84  6821.7 2073.52
#Mann=3,-1,0
  3103.6   0.045       0  5098.3   0.045       0  5102.3   0.045       0
Bank Sta=5098.3,5102.3
Exp/Cntr=0.3,0.1

Type RM Length L Ch R = 1,13500,500,500,500
BEGIN DESCRIPTION:
Cottonwood Creek Trib126 27.0
END DESCRIPTION:
XS GIS Cut Line= 3
      1379804.96      6932888.02      1381805.19      6932025.18
      1382604.98      6931188.02
#Sta/Elev= 30
  2821.6 2069.88  2912.1 2070.12  2941.4 2066.64  2982.7 2067.60  3082.2 2061.25
  3224.6 2059.72  3279.1 2056.05  3377.1 2057.06  3462.1 2052.84  3529.5 2054.46
  3561.6 2050.85  3771.5 2049.62  3842.0 2045.63  3910.7 2047.26  3954.3 2044.24
  4093.5 2042.09  4139.4 2043.90  4303.4 2039.51  4694.8 2041.05  5002.9 2036.21
  5003.2 2035.71  5007.0 2036.21  5218.7 2040.43  5494.1 2044.50  5783.1 2048.04
  5910.1 2052.40  5959.8 2050.26  6016.5 2053.81  6129.7 2054.09  6157.8 2057.51
#Mann=5,-1,0
  2821.6   0.045       0  5002.9   0.045       0  5007.0   0.045       0
  5218.7    0.07       0  5494.1   0.045       0
Bank Sta=5002.9,5007
Exp/Cntr=0.3,0.1

Type RM Length L Ch R = 1,13000,500,500,500
BEGIN DESCRIPTION:
Cottonwood Creek Trib126 26.0
END DESCRIPTION:
XS GIS Cut Line= 3
      1379905.02      6932888.00      1381902.38      6932493.20
      1382855.02      6931637.98
#Sta/Elev= 30
  2964.0 2070.25  2989.6 2066.78  3035.3 2067.37  3208.6 2058.78  3259.6 2059.98
  3320.7 2055.63  3371.7 2056.85  3443.1 2052.69  3502.3 2054.37  3558.7 2050.40
  3609.9 2052.23  3646.9 2048.75  3718.3 2049.74  3769.3 2046.20  3968.8 2042.38
  4513.4 2036.24  4594.9 2038.06  4625.5 2035.35  4944.5 2035.53  4990.3 2032.96
  4990.6 2032.46  4994.7 2032.96  5425.5 2040.53  5525.2 2041.54  5797.2 2046.19
  6103.4 2054.41  6138.5 2052.89  6202.1 2057.52  6244.7 2055.56  6280.2 2059.89
#Mann=7,-1,0
  2964.0   0.045       0  4944.5    0.07       0  4990.3    0.07       0
  4994.7    0.07       0  5425.5   0.045       0  5525.2    0.07       0
  5797.2   0.045       0
Bank Sta=4990.3,4994.7
Exp/Cntr=0.3,0.1

Type RM Length L Ch R = 1,12500,500,500,500
BEGIN DESCRIPTION:
Cottonwood Creek Trib126 25.0
END DESCRIPTION:
XS GIS Cut Line= 3
      1379955.01      6933088.00      1381956.12      6932976.82
      1382904.97      6932288.02
#Sta/Elev= 30
  2995.8 2066.62  3106.0 2065.11  3136.0 2061.49  3186.1 2062.24  3236.2 2058.32
  3268.7 2059.68  3296.3 2056.13  3356.3 2056.28  3386.4 2053.20  3449.0 2053.81
  3476.5 2050.64  3526.6 2052.04  3576.7 2048.48  3646.8 2049.85  4067.4 2039.35
  4137.6 2040.97  4165.1 2038.30  4345.4 2038.26  4530.6 2033.32  4628.3 2035.39
  5003.4 2027.54  5003.7 2027.04  5008.0 2027.54  5070.6 2030.62  5112.3 2028.60
  5175.0 2033.57  5492.9 2036.23  5639.8 2040.03  5746.8 2042.77  6172.5 2056.61
#Mann=6,-1,0
  2995.8   0.045       0  5003.4   0.045       0  5008.0   0.045       0
  5175.0    0.07       0  5639.8   0.045       0  5746.8    0.07       0
Bank Sta=5003.4,5008
Exp/Cntr=0.3,0.1

Type RM Length L Ch R = 1,12000,500,500,500
BEGIN DESCRIPTION:
Cottonwood Creek Trib126 24.0
END DESCRIPTION:
XS GIS Cut Line= 3
      1380255.01      6933238.00      1382095.77      6933430.51
      1383055.01      6932437.99
#Sta/Elev= 30
  3149.2 2059.05  3189.4 2055.78  3330.2 2053.46  3350.3 2050.80  3392.5 2051.67
  3420.7 2048.56  3470.9 2049.71  3571.5 2045.45  3621.8 2047.16  3662.0 2043.78
  3762.5 2042.17  3812.8 2043.91  3903.3 2039.30  3962.5 2040.74  4003.8 2037.52
  4084.3 2038.03  4159.2 2034.26  4257.5 2035.66  4444.2 2031.02  4496.5 2033.13
  4536.7 2030.65  5006.0 2026.80  5006.3 2026.30  5010.6 2026.80  5326.5 2030.15
  5489.3 2034.97  5635.1 2035.07  5893.8 2040.07  5994.7 2043.02  6380.3 2057.24
#Mann=6,-1,0
  3149.2   0.045       0  5006.0   0.045       0  5010.6   0.045       0
  5635.1    0.07       0  5893.8   0.045       0  5994.7    0.07       0
Bank Sta=5006,5010.6
Exp/Cntr=0.3,0.1

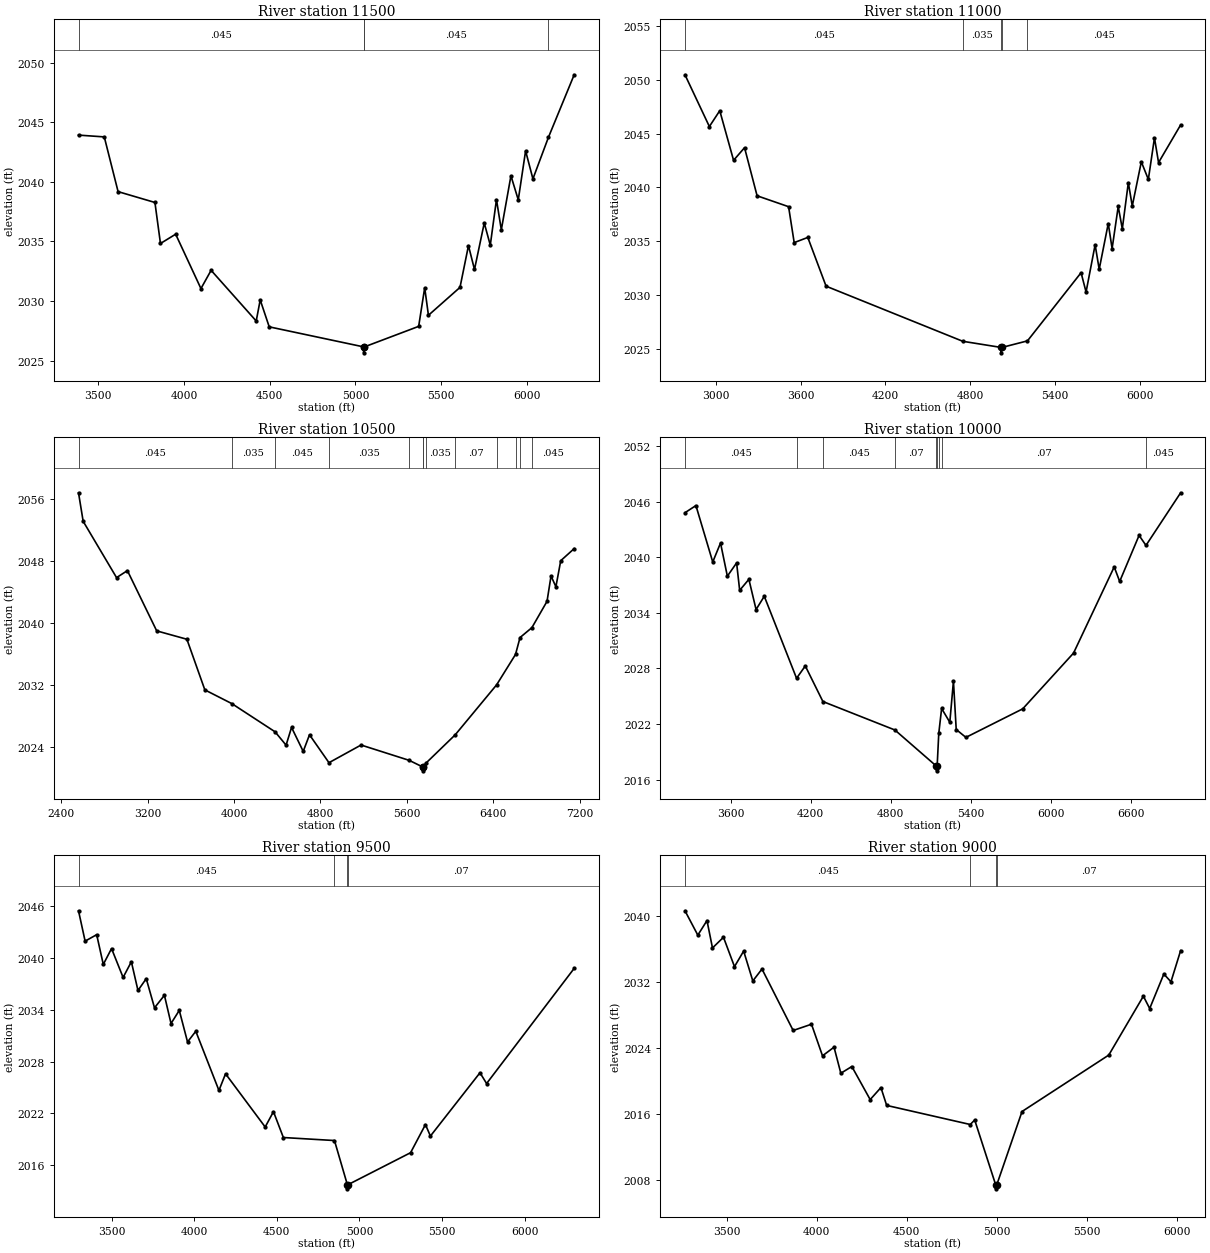
Type RM Length L Ch R = 1,11500,500,500,500
BEGIN DESCRIPTION:
Cottonwood Creek Trib126 23.0
END DESCRIPTION:
XS GIS Cut Line= 3
      1380755.02      6933338.01      1382294.27      6933827.47
      1383254.99      6932988.01
#Sta/Elev= 30
  3384.8 2043.92  3535.1 2043.77  3615.6 2039.18  3830.5 2038.27  3862.8 2034.83
  3951.4 2035.61  4098.9 2031.05  4158.2 2032.58  4421.3 2028.33  4444.6 2030.10
  4497.1 2027.84  5047.6 2026.16  5047.9 2025.66  5052.3 2026.16  5368.8 2027.88
  5404.0 2031.12  5425.8 2028.81  5609.9 2031.15  5659.3 2034.65  5694.4 2032.65
  5751.4 2036.55  5786.5 2034.69  5822.6 2038.51  5850.9 2035.98  5907.0 2040.51
  5949.8 2038.49  5992.5 2042.60  6035.2 2040.25  6125.6 2043.73  6275.8 2048.98
#Mann=4,-1,0
  3384.8   0.045       0  5047.6   0.045       0  5052.3   0.045       0
  6125.6    0.07       0
Bank Sta=5047.6,5052.3
Exp/Cntr=0.3,0.1

Type RM Length L Ch R = 1,11000,500,500,500
BEGIN DESCRIPTION:
Cottonwood Creek Trib126 22.0
END DESCRIPTION:
XS GIS Cut Line= 3
      1380505.02      6933238.01      1382505.04      6934197.59
      1383305.00      6933188.00
#Sta/Elev= 30
  2781.7 2050.45  2954.3 2045.65  3027.8 2047.12  3125.5 2042.52  3203.1 2043.69
  3291.9 2039.23  3514.6 2038.22  3554.3 2034.89  3650.5 2035.37  3779.9 2030.85
  4747.0 2025.74  5018.9 2025.17  5019.3 2024.67  5023.7 2025.17  5204.6 2025.78
  5583.8 2032.10  5619.1 2030.31  5683.2 2034.69  5712.0 2032.42  5776.1 2036.66
  5803.3 2034.34  5846.6 2038.24  5875.5 2036.17  5918.1 2040.45  5945.9 2038.28
  6010.0 2042.38  6059.7 2040.75  6103.0 2044.60  6131.9 2042.31  6288.1 2045.80
#Mann=5,-1,0
  2781.7   0.045       0  4747.0   0.035       0  5018.9   0.035       0
  5023.7   0.035       0  5204.6   0.045       0
Bank Sta=5018.9,5023.7
Exp/Cntr=0.3,0.1

Type RM Length L Ch R = 1,10500,500,500,500
BEGIN DESCRIPTION:
Cottonwood Creek Trib126 21.0
END DESCRIPTION:
XS GIS Cut Line= 3
      1380355.00      6933238.00      1382348.53      6934644.75
      1384255.01      6935638.00
#Sta/Elev= 30
  2560.1 2056.75  2603.2 2053.07  2912.3 2045.81  3012.9 2046.71  3284.1 2038.94
  3563.7 2037.86  3729.9 2031.33  3979.8 2029.56  4380.5 2025.92  4482.2 2024.20
  4532.7 2026.49  4640.8 2023.40  4699.0 2025.54  4879.3 2021.94  5176.4 2024.22
  5622.7 2022.24  5747.3 2021.39  5747.7 2020.89  5752.2 2021.39  5775.5 2021.86
  6047.8 2025.53  6431.5 2031.98  6606.6 2035.90  6648.4 2038.08  6758.4 2039.36
  6898.4 2042.75  6935.5 2046.02  6980.6 2044.63  7025.3 2047.99  7149.7 2049.55
#Mann=13,-1,0
  2560.1   0.045       0  3979.8   0.035       0  4380.5   0.045       0
  4879.3   0.035       0  5622.7    0.07       0  5747.3   0.035       0
  5752.2    0.07       0  5775.5   0.035       0  6047.8    0.07       0
  6431.5   0.035       0  6606.6    0.07       0  6648.4   0.035       0
  6758.4   0.045       0
Bank Sta=5747.3,5752.2
Exp/Cntr=0.3,0.1

Type RM Length L Ch R = 1,10000,500,500,500
BEGIN DESCRIPTION:
Cottonwood Creek Trib126 20.0
END DESCRIPTION:
XS GIS Cut Line= 3
      1380555.00      6935488.00      1382254.64      6935108.00
      1384155.02      6935638.01
#Sta/Elev= 30
  3258.4 2044.81  3340.4 2045.58  3466.5 2039.49  3524.8 2041.54  3576.0 2037.96
  3645.3 2039.39  3668.3 2036.43  3737.3 2037.62  3791.2 2034.36  3852.7 2035.79
  4094.6 2026.94  4160.1 2028.27  4292.0 2024.43  4831.3 2021.36  5143.3 2017.45
  5143.6 2016.95  5148.2 2017.45  5160.3 2020.98  5181.7 2023.68  5243.1 2022.19
  5270.3 2026.63  5291.1 2021.41  5363.7 2020.56  5789.4 2023.64  6170.4 2029.66
  6475.1 2038.96  6516.1 2037.39  6661.5 2042.36  6713.2 2041.28  6972.9 2046.96
#Mann=9,-1,0
  3258.4   0.045       0  4094.6   0.035       0  4292.0   0.045       0
  4831.3    0.07       0  5143.3    0.07       0  5148.2    0.07       0
  5160.3   0.033       0  5181.7    0.07       0  6713.2   0.045       0
Bank Sta=5143.3,5148.2
Exp/Cntr=0.3,0.1

Type RM Length L Ch R = 1,9500,500,500,500
BEGIN DESCRIPTION:
Cottonwood Creek Trib126 19.0
END DESCRIPTION:
XS GIS Cut Line= 3
      1380655.04      6935538.00      1382355.12      6935575.80
      1383654.97      6935538.00
#Sta/Elev= 30
  3299.5 2045.49  3339.5 2041.97  3409.5 2042.72  3449.5 2039.27  3499.5 2041.11
  3569.5 2037.76  3619.5 2039.58  3659.5 2036.25  3709.6 2037.62  3759.6 2034.24
  3819.6 2035.69  3859.6 2032.42  3909.6 2033.94  3959.6 2030.28  4009.6 2031.52
  4149.7 2024.66  4189.7 2026.59  4429.7 2020.42  4479.8 2022.20  4539.8 2019.20
  4849.2 2018.85  4926.9 2013.75  4927.4 2013.25  4932.9 2013.75  5310.0 2017.44
  5400.0 2020.70  5430.1 2019.37  5730.2 2026.71  5770.2 2025.46  6300.4 2038.81
#Mann=4,-1,0
  3299.5   0.045       0  4849.2    0.07       0  4926.9    0.07       0
  4932.9    0.07       0
Bank Sta=4926.9,4932.9
Exp/Cntr=0.3,0.1

Type RM Length L Ch R = 1,9000,500,500,500
BEGIN DESCRIPTION:
Cottonwood Creek Trib126 18.0
END DESCRIPTION:
XS GIS Cut Line= 3
      1380855.00      6935688.00      1382555.01      6936013.00
      1383504.98      6935638.01
#Sta/Elev= 30
  3269.2 2040.68  3340.5 2037.72  3391.4 2039.49  3421.9 2036.16  3483.0 2037.46
  3544.1 2033.89  3595.0 2035.78  3645.9 2032.15  3696.8 2033.60  3869.9 2026.13
  3971.7 2026.89  4032.8 2023.05  4096.8 2024.10  4134.6 2020.93  4195.7 2021.75
  4297.5 2017.73  4357.2 2019.19  4389.1 2017.02  4853.3 2014.70  4877.8 2015.25
  4994.2 2007.38  4994.7 2006.88  5000.6 2007.38  5140.7 2016.28  5622.3 2023.14
  5814.4 2030.30  5849.5 2028.80  5928.0 2032.99  5967.6 2032.05  6021.3 2035.84
#Mann=4,-1,0
  3269.2   0.045       0  4853.3    0.07       0  4994.2    0.07       0
  5000.6    0.07       0
Bank Sta=4994.2,5000.6
Exp/Cntr=0.3,0.1

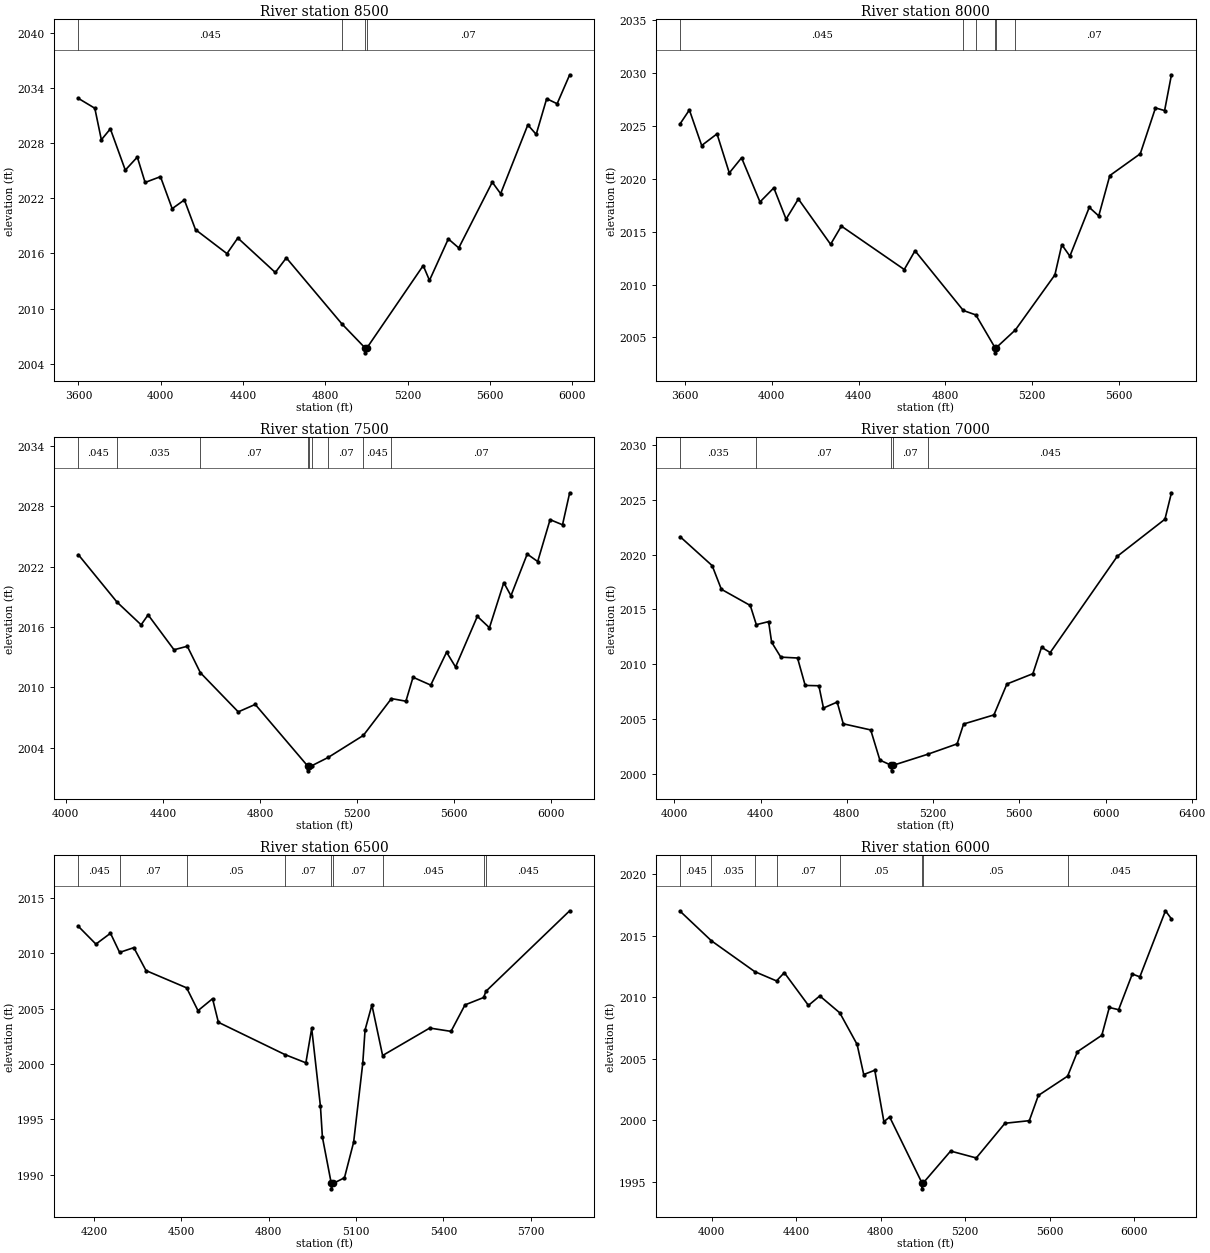
Type RM Length L Ch R = 1,8500,500,500,500
BEGIN DESCRIPTION:
Cottonwood Creek Trib126 17.0
END DESCRIPTION:
XS GIS Cut Line= 3
      1381255.02      6935788.01      1382484.13      6936458.51
      1383454.98      6936638.00
#Sta/Elev= 30
  3599.9 2032.85  3679.6 2031.78  3711.4 2028.35  3755.1 2029.54  3827.7 2025.05
  3886.1 2026.47  3924.0 2023.71  3998.6 2024.34  4055.5 2020.86  4114.8 2021.81
  4168.9 2018.58  4321.8 2015.97  4374.5 2017.67  4556.7 2013.92  4610.3 2015.51
  4879.1 2008.36  4994.4 2005.68  4994.9 2005.18  5000.9 2005.68  5275.5 2014.67
  5306.0 2013.06  5397.5 2017.57  5448.3 2016.59  5611.1 2023.74  5651.7 2022.49
  5783.9 2029.97  5824.6 2028.94  5875.5 2032.82  5926.3 2032.27  5987.3 2035.42
#Mann=4,-1,0
  3599.9   0.045       0  4879.1    0.07       0  4994.4    0.07       0
  5000.9    0.07       0
Bank Sta=4994.4,5000.9
Exp/Cntr=0.3,0.1

Type RM Length L Ch R = 1,8000,500,500,500
BEGIN DESCRIPTION:
Cottonwood Creek Trib126 16.0
END DESCRIPTION:
XS GIS Cut Line= 3
      1381454.98      6935937.98      1382455.01      6936948.80
      1383254.97      6936688.01
#Sta/Elev= 30
  3578.1 2025.19  3620.5 2026.49  3677.1 2023.13  3747.8 2024.23  3804.4 2020.54
  3860.9 2021.97  3945.8 2017.80  4009.5 2019.13  4066.0 2016.18  4122.6 2018.08
  4271.1 2013.80  4320.6 2015.52  4610.5 2011.42  4660.0 2013.19  4882.5 2007.55
  4940.3 2007.13  5028.2 2004.05  5028.7 2003.55  5034.9 2004.05  5122.7 2005.72
  5304.4 2010.91  5336.3 2013.76  5373.5 2012.68  5462.8 2017.29  5506.4 2016.48
  5557.4 2020.29  5697.8 2022.35  5767.8 2026.68  5809.9 2026.43  5841.4 2029.81
#Mann=6,-1,0
  3578.1   0.045       0  4882.5    0.07       0  4940.3   0.035       0
  5028.2   0.035       0  5034.9   0.035       0  5122.7    0.07       0
Bank Sta=5028.2,5034.9
Exp/Cntr=0.3,0.1

Type RM Length L Ch R = 1,7500,500,500,500
BEGIN DESCRIPTION:
Cottonwood Creek Trib126 15.0
END DESCRIPTION:
XS GIS Cut Line= 3
      1381504.96      6937037.98      1382371.73      6937421.68
      1383305.01      6936887.99
#Sta/Elev= 30
  4052.1 2023.18  4211.3 2018.47  4310.3 2016.22  4339.1 2017.21  4445.8 2013.74
  4500.5 2014.09  4554.3 2011.46  4710.3 2007.57  4780.2 2008.31  4995.5 2002.21
  4996.0 2001.71  5002.6 2002.21  5013.2 2002.22  5080.6 2003.04  5225.4 2005.23
  5341.1 2008.89  5400.7 2008.63  5430.0 2011.01  5502.9 2010.23  5568.2 2013.50
  5605.1 2012.03  5694.9 2017.06  5744.7 2015.93  5803.8 2020.41  5833.2 2019.11
  5900.2 2023.25  5943.4 2022.51  5994.4 2026.67  6045.6 2026.16  6075.1 2029.34
#Mann=9,-1,0
  4052.1   0.045       0  4211.3   0.035       0  4554.3    0.07       0
  4995.5    0.07       0  5002.6    0.07       0  5013.2   0.045       0
  5080.6    0.07       0  5225.4   0.045       0  5341.1    0.07       0
Bank Sta=4995.5,5002.6
Exp/Cntr=0.3,0.1

Type RM Length L Ch R = 1,7000,500,500,500
BEGIN DESCRIPTION:
Cottonwood Creek Trib126 14.0
END DESCRIPTION:
XS GIS Cut Line= 3
      1381505.00      6937188.00      1382204.95      6937864.46
      1383504.99      6937988.00
#Sta/Elev= 30
  4026.6 2021.62  4175.2 2018.98  4217.6 2016.83  4351.9 2015.35  4379.9 2013.60
  4436.8 2013.88  4450.9 2012.00  4493.4 2010.64  4571.1 2010.56  4606.6 2008.06
  4670.1 2008.03  4691.4 2006.00  4755.0 2006.54  4783.3 2004.56  4910.6 2004.00
  4953.1 2001.25  5006.6 2000.77  5007.1 2000.27  5013.7 2000.77  5174.9 2001.78
  5311.5 2002.73  5341.6 2004.54  5482.2 2005.37  5542.5 2008.19  5663.0 2009.13
  5703.2 2011.54  5743.4 2011.06  6054.8 2019.84  6275.8 2023.22  6305.9 2025.63
#Mann=5,-1,0
  4026.6   0.035       0  4379.9    0.07       0  5006.6    0.07       0
  5013.7    0.07       0  5174.9   0.045       0
Bank Sta=5006.6,5013.7
Exp/Cntr=0.3,0.1

Type RM Length L Ch R = 1,6500,500,500,500
BEGIN DESCRIPTION:
Cottonwood Creek Trib126 13.0
END DESCRIPTION:
XS GIS Cut Line= 3
      1381405.00      6938388.00      1382257.27      6938332.09
      1383054.96      6938088.01
#Sta/Elev= 30
  4145.9 2012.42  4206.0 2010.82  4256.1 2011.80  4287.5 2010.07  4336.3 2010.50
  4378.2 2008.43  4517.8 2006.87  4556.8 2004.81  4606.9 2005.89  4626.9 2003.76
  4855.2 2000.85  4927.6 2000.10  4947.6 2003.21  4977.7 1996.16  4984.4 1993.39
  5014.8 1989.22  5015.3 1988.72  5022.3 1989.22  5060.2 1989.72  5091.7 1992.93
  5123.1 2000.06  5131.0 2003.07  5154.5 2005.32  5191.3 2000.76  5353.2 2003.24
  5426.4 2002.94  5474.4 2005.33  5538.7 2006.00  5546.0 2006.55  5834.2 2013.83
#Mann=9,-1,0
  4145.9   0.045       0  4287.5    0.07       0  4517.8    0.05       0
  4855.2    0.07       0  5014.8    0.07       0  5022.3    0.07       0
  5191.3   0.045       0  5538.7    0.05       0  5546.0   0.045       0
Bank Sta=5014.8,5022.3
Exp/Cntr=0.3,0.1

Type RM Length L Ch R = 1,6000,500,500,500
BEGIN DESCRIPTION:
Cottonwood Creek Trib126 12.0
END DESCRIPTION:
XS GIS Cut Line= 3
      1381105.04      6938438.01      1382202.89      6938779.05
      1383155.03      6938087.98
#Sta/Elev= 30
  3850.4 2016.99  3998.3 2014.59  4203.9 2012.08  4306.6 2011.33  4343.4 2012.00
  4457.7 2009.34  4511.5 2010.11  4606.3 2008.73  4688.1 2006.17  4719.5 2003.72
  4771.8 2004.07  4815.0 1999.89  4842.3 2000.27  4994.7 1994.93  4995.2 1994.43
  5002.3 1994.93  5130.9 1997.50  5252.3 1996.94  5388.3 1999.76  5503.5 1999.97
  5546.3 2002.02  5684.9 2003.59  5731.6 2005.58  5846.8 2006.91  5882.3 2009.17
  5926.4 2008.99  5991.1 2011.89  6026.9 2011.66  6148.2 2017.03  6176.5 2016.37
#Mann=8,-1,0
  3850.4   0.045       0  3998.3   0.035       0  4203.9   0.045       0
  4306.6    0.07       0  4606.3    0.05       0  4994.7    0.05       0
  5002.3    0.05       0  5684.9   0.045       0
Bank Sta=4994.7,5002.3
Exp/Cntr=0.3,0.1

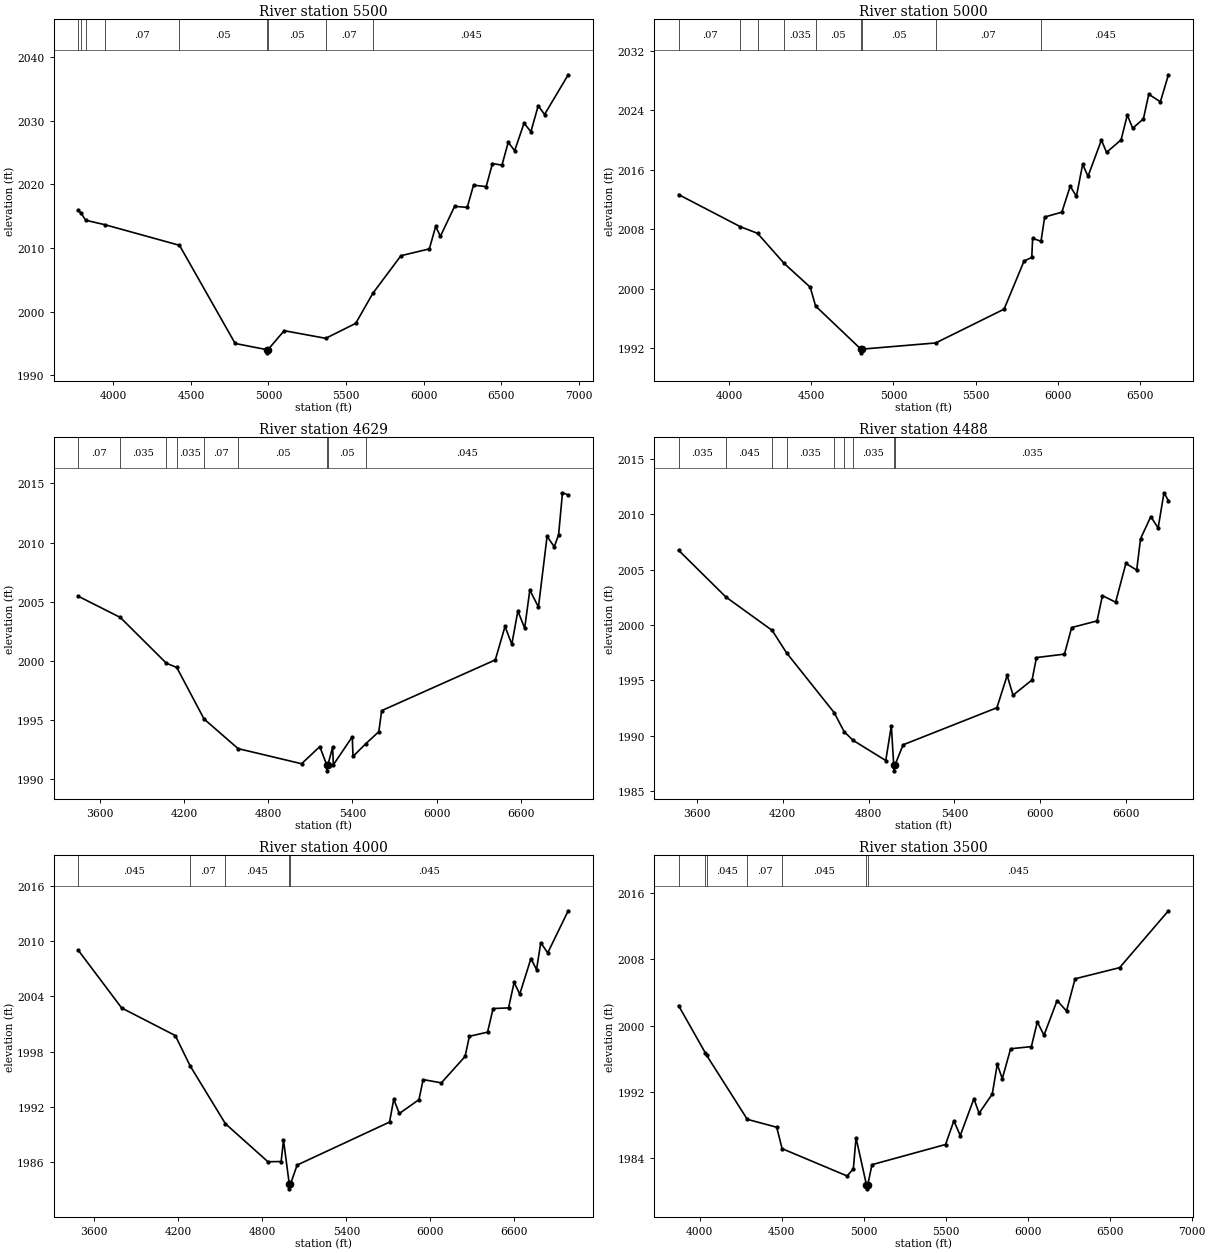
Type RM Length L Ch R = 1,5500,500,500,500
BEGIN DESCRIPTION:
Cottonwood Creek Trib126 11.0
END DESCRIPTION:
XS GIS Cut Line= 3
      1381205.02      6938538.02      1382205.45      6939247.21
      1384104.98      6938888.00
#Sta/Elev= 30
  3773.7 2015.90  3790.0 2015.51  3821.3 2014.36  3947.9 2013.64  4426.0 2010.42
  4785.1 1995.00  4989.2 1994.03  4989.7 1993.53  4996.8 1994.03  5101.3 1997.01
  5369.3 1995.81  5562.6 1998.16  5673.1 2002.88  5854.4 2008.79  6037.6 2009.86
  6078.3 2013.39  6108.9 2011.84  6200.5 2016.54  6281.9 2016.38  6322.6 2019.87
  6404.0 2019.64  6444.7 2023.27  6505.8 2023.01  6546.5 2026.60  6587.8 2025.28
  6648.3 2029.61  6692.5 2028.26  6739.8 2032.35  6780.6 2030.97  6933.2 2037.21
#Mann=9,-1,0
  3773.7   0.045       0  3790.0    0.07       0  3821.3   0.035       0
  3947.9    0.07       0  4426.0    0.05       0  4989.2    0.05       0
  4996.8    0.05       0  5369.3    0.07       0  5673.1   0.045       0
Bank Sta=4989.2,4996.8
Exp/Cntr=0.3,0.1

Type RM Length L Ch R = 1,5000,371,371,371
BEGIN DESCRIPTION:
Cottonwood Creek Trib126 10.0
END DESCRIPTION:
XS GIS Cut Line= 3
      1381155.03      6938888.03      1382154.98      6939731.07
      1383755.02      6939237.99
#Sta/Elev= 30
  3692.1 2012.68  4068.8 2008.35  4173.1 2007.46  4335.1 2003.41  4493.7 2000.21
  4526.2 1997.68  4802.0 1991.88  4802.5 1991.38  4809.6 1991.88  5257.3 1992.71
  5673.8 1997.26  5795.3 2003.73  5842.4 2004.23  5847.6 2006.78  5898.5 2006.40
  5920.9 2009.66  6025.5 2010.31  6076.3 2013.80  6114.2 2012.44  6152.1 2016.75
  6184.8 2015.14  6266.2 2020.01  6297.6 2018.36  6386.1 2020.04  6424.0 2023.39
  6456.7 2021.60  6522.0 2022.87  6554.7 2026.18  6625.3 2025.16  6674.3 2028.80
#Mann=9,-1,0
  3692.1    0.07       0  4068.8   0.035       0  4173.1    0.05       0
  4335.1   0.035       0  4526.2    0.05       0  4802.0    0.05       0
  4809.6    0.05       0  5257.3    0.07       0  5898.5   0.045       0
Bank Sta=4802,4809.6
Exp/Cntr=0.3,0.1

Type RM Length L Ch R = 1,4629,141,141,141
BEGIN DESCRIPTION:
Cottonwood Creek Trib126 9.5
END DESCRIPTION:
XS GIS Cut Line= 3
      1380687.52      6939735.90      1382177.14      6940079.66
      1384091.88      6940511.52
#Sta/Elev= 30
  3446.1 2005.46  3745.1 2003.67  4073.5 1999.80  4147.5 1999.44  4342.3 1995.08
  4584.7 1992.58  5037.4 1991.30  5167.1 1992.75  5216.6 1991.20  5217.1 1990.70
  5224.5 1991.20  5258.7 1992.70  5263.8 1991.21  5398.6 1993.58  5403.7 1991.92
  5492.9 1992.97  5587.7 1994.01  5608.2 1995.79  6418.1 2000.08  6487.3 2002.91
  6535.7 2001.40  6578.9 2004.22  6627.3 2002.76  6664.1 2005.98  6725.6 2004.55
  6787.1 2010.53  6838.4 2009.64  6869.1 2010.66  6896.9 2014.21  6937.7 2014.03
#Mann=9,-1,0
  3446.1    0.07       0  3745.1   0.035       0  4073.5    0.07       0
  4147.5   0.035       0  4342.3    0.07       0  4584.7    0.05       0
  5216.6    0.05       0  5224.5    0.05       0  5492.9   0.045       0
Bank Sta=5216.6,5224.5
Exp/Cntr=0.3,0.1

Type RM Length L Ch R = 1,4488,488,488,488
BEGIN DESCRIPTION:
Cottonwood Creek Trib126 9.0
END DESCRIPTION:
XS GIS Cut Line= 3
      1380661.48      6939886.94      1382151.10      6940209.87
      1384005.27      6940621.33
#Sta/Elev= 30
  3471.8 2006.75  3802.4 2002.53  4126.1 1999.51  4226.8 1997.48  4559.8 1992.08
  4628.4 1990.38  4689.7 1989.60  4919.8 1987.76  4958.8 1990.90  4975.6 1987.33
  4976.1 1986.83  4983.5 1987.33  5041.0 1989.18  5696.6 1992.53  5768.3 1995.45
  5809.2 1993.66  5942.4 1995.04  5973.1 1997.06  6168.7 1997.37  6219.0 1999.77
  6396.7 2000.37  6434.1 2002.65  6526.3 2002.06  6598.0 2005.56  6673.5 2004.96
  6700.4 2007.79  6772.1 2009.79  6823.3 2008.76  6864.3 2011.94  6895.3 2011.23
#Mann=9,-1,0
  3471.8   0.035       0  3802.4   0.045       0  4126.1    0.07       0
  4226.8   0.035       0  4559.8    0.07       0  4628.4   0.045       0
  4689.7   0.035       0  4975.6   0.035       0  4983.5   0.035       0
Bank Sta=4975.6,4983.5
Exp/Cntr=0.3,0.1

Type RM Length L Ch R = 1,4000,500,500,500
BEGIN DESCRIPTION:
Cottonwood Creek Trib126 8.0
END DESCRIPTION:
XS GIS Cut Line= 3
      1380655.02      6940138.01      1382076.74      6940659.68
      1384061.23      6940662.99
#Sta/Elev= 30
  3485.6 2009.00  3795.1 2002.75  4178.0 1999.76  4284.1 1996.47  4536.1 1990.20
  4839.6 1986.08  4934.2 1986.10  4950.9 1988.43  4992.3 1983.64  4992.8 1983.14
  5000.5 1983.64  5048.3 1985.72  5708.3 1990.38  5738.3 1992.85  5778.3 1991.31
  5918.3 1992.81  5948.3 1994.99  6078.3 1994.63  6248.3 1997.50  6278.3 1999.68
  6408.3 2000.13  6448.3 2002.69  6558.3 2002.76  6598.3 2005.53  6638.3 2004.25
  6718.3 2008.11  6758.3 2006.91  6788.3 2009.82  6838.3 2008.73  6984.5 2013.29
#Mann=5,-1,0
  3485.6   0.045       0  4284.1    0.07       0  4536.1   0.045       0
  4992.3   0.045       0  5000.5   0.045       0
Bank Sta=4992.3,5000.5
Exp/Cntr=0.3,0.1

Type RM Length L Ch R = 1,3500,500,500,500
BEGIN DESCRIPTION:
Cottonwood Creek Trib126 7.0
END DESCRIPTION:
XS GIS Cut Line= 3
      1381205.03      6940588.02      1382204.80      6941113.17
      1384030.63      6940767.29
#Sta/Elev= 30
  3870.7 2002.40  4034.9 1996.67  4042.5 1996.39  4289.9 1988.70  4469.3 1987.75
  4502.1 1985.17  4898.6 1981.88  4936.6 1982.74  4953.0 1986.48  5016.4 1980.83
  5016.9 1980.33  5024.7 1980.83  5050.3 1983.24  5498.9 1985.67  5549.8 1988.52
  5588.7 1986.75  5671.9 1991.18  5703.5 1989.44  5783.9 1991.74  5814.4 1995.33
  5845.0 1993.60  5895.9 1997.20  6022.4 1997.46  6058.7 2000.43  6099.4 1998.83
  6179.3 2003.01  6236.7 2001.75  6289.0 2005.63  6560.7 2006.97  6858.3 2013.82
#Mann=7,-1,0
  3870.7   0.045       0  4034.9    0.07       0  4042.5   0.045       0
  4289.9    0.07       0  4502.1   0.045       0  5016.4   0.045       0
  5024.7   0.045       0
Bank Sta=5016.4,5024.7
Exp/Cntr=0.3,0.1

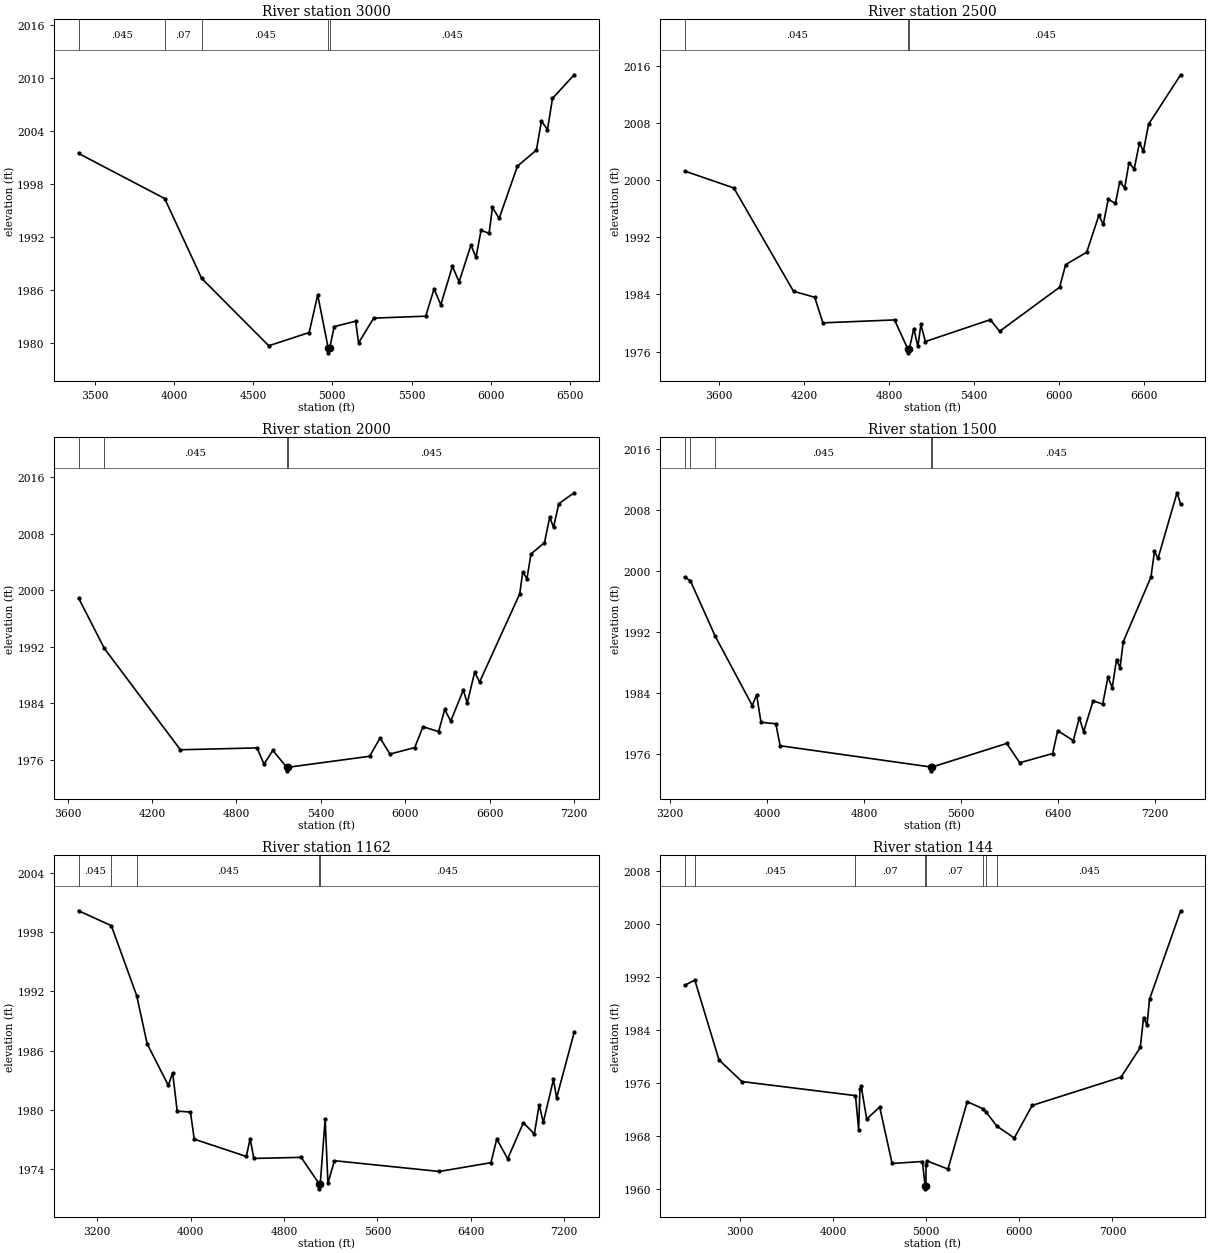
Type RM Length L Ch R = 1,3000,500,500,500
BEGIN DESCRIPTION:
Cottonwood Creek Trib126 6.0
END DESCRIPTION:
XS GIS Cut Line= 3
      1380954.96      6940787.98      1382355.26      6941565.55
      1383805.03      6941087.99
#Sta/Elev= 30
  3398.3 2001.51  3941.5 1996.41  4174.9 1987.37  4598.5 1979.74  4853.6 1981.24
  4907.4 1985.50  4974.2 1979.44  4974.7 1978.94  4982.5 1979.44  5011.8 1981.91
  5147.1 1982.52  5165.4 1980.06  5260.8 1982.87  5589.3 1983.09  5642.0 1986.18
  5684.4 1984.38  5757.8 1988.73  5799.9 1986.98  5875.0 1991.14  5906.8 1989.75
  5938.5 1992.81  5989.4 1992.47  6010.5 1995.40  6052.6 1994.15  6168.4 2000.08
  6288.1 2001.89  6319.8 2005.18  6357.9 2004.21  6389.5 2007.74  6526.4 2010.42
#Mann=5,-1,0
  3398.3   0.045       0  3941.5    0.07       0  4174.9   0.045       0
  4974.2   0.045       0  4982.5   0.045       0
Bank Sta=4974.2,4982.5
Exp/Cntr=0.3,0.1

Type RM Length L Ch R = 1,2500,500,500,500
BEGIN DESCRIPTION:
Cottonwood Creek Trib126 5.0
END DESCRIPTION:
XS GIS Cut Line= 3
      1381051.60      6941038.66      1382355.36      6942033.55
      1383955.00      6941088.00
#Sta/Elev= 30
  3360.0 2001.27  3703.9 1998.92  4125.4 1984.45  4275.0 1983.61  4332.9 1980.03
  4838.3 1980.44  4933.6 1976.33  4934.1 1975.83  4942.4 1976.33  4974.4 1979.22
  5003.2 1976.72  5024.7 1979.81  5055.9 1977.41  5514.3 1980.47  5580.4 1978.85
  6003.9 1985.02  6046.7 1988.19  6195.1 1989.92  6280.8 1995.07  6312.1 1993.83
  6347.1 1997.33  6397.9 1996.75  6428.4 1999.80  6463.2 1998.92  6493.5 2002.44
  6530.5 2001.59  6567.6 2005.26  6594.9 2004.04  6631.9 2007.84  6858.2 2014.77
#Mann=3,-1,0
  3360.0   0.045       0  4933.6   0.045       0  4942.4   0.045       0
Bank Sta=4933.6,4942.4
Exp/Cntr=0.3,0.1

Type RM Length L Ch R = 1,2000,500,500,500
BEGIN DESCRIPTION:
Cottonwood Creek Trib126 4.0
END DESCRIPTION:
XS GIS Cut Line= 3
      1381254.97      6941637.97      1382255.11      6942501.28
      1384154.97      6941388.02
#Sta/Elev= 30
  3678.8 1998.87  3861.7 1991.76  4402.3 1977.44  4947.5 1977.70  4996.6 1975.41
  5059.8 1977.35  5157.7 1974.96  5158.2 1974.46  5166.5 1974.96  5747.8 1976.52
  5822.2 1979.10  5892.4 1976.83  6068.3 1977.75  6127.0 1980.69  6238.5 1980.01
  6281.4 1983.14  6324.4 1981.49  6413.9 1985.88  6441.7 1984.05  6494.5 1988.39
  6529.8 1987.03  6815.0 1999.48  6836.5 2002.58  6865.9 2001.61  6895.2 2005.12
  6991.0 2006.71  7028.1 2010.31  7055.4 2008.88  7092.6 2012.22  7202.0 2013.76
#Mann=4,-1,0
  3678.8    0.07       0  3861.7   0.045       0  5157.7   0.045       0
  5166.5   0.045       0
Bank Sta=5157.7,5166.5
Exp/Cntr=0.3,0.1

Type RM Length L Ch R = 1,1500,338,338,338
BEGIN DESCRIPTION:
Cottonwood Creek Trib126 3.0
END DESCRIPTION:
XS GIS Cut Line= 3
      1381204.98      6941587.98      1382154.94      6942969.00
      1384058.49      6941489.17
#Sta/Elev= 30
  3323.8 1999.14  3367.5 1998.69  3572.5 1991.42  3877.9 1982.34  3913.7 1983.75
  3949.6 1980.15  4072.0 1979.95  4107.9 1977.07  5352.1 1974.28  5352.6 1973.78
  5360.9 1974.28  5976.4 1977.37  6084.1 1974.84  6355.4 1976.05  6397.2 1979.04
  6525.7 1977.75  6575.5 1980.73  6610.8 1978.92  6689.5 1982.96  6768.2 1982.53
  6811.4 1986.07  6847.0 1984.70  6882.3 1988.36  6911.2 1987.31  6938.4 1990.73
  7166.4 1999.18  7195.4 2002.56  7224.3 2001.62  7381.3 2010.23  7411.1 2008.72
#Mann=5,-1,0
  3323.8   0.045       0  3367.5    0.07       0  3572.5   0.045       0
  5352.1   0.045       0  5360.9   0.045       0
Bank Sta=5352.1,5360.9
Exp/Cntr=0.3,0.1

Type RM Length L Ch R = 1,1162,1018,1018,1018
BEGIN DESCRIPTION:
Cottonwood Creek Trib126 2.0
END DESCRIPTION:
XS GIS Cut Line= 5
      1381107.11      6941367.61      1381836.28      6943069.02
      1381914.41      6943164.50      1382122.74      6943147.14
      1383755.01      6941887.99
#Sta/Elev= 30
  3040.2 2000.16  3320.4 1998.65  3537.7 1991.56  3627.1 1986.68  3808.4 1982.48
  3845.7 1983.75  3884.5 1979.86  3998.0 1979.77  4030.7 1977.02  4476.7 1975.27
  4509.4 1977.08  4540.9 1975.07  4946.3 1975.18  5101.2 1972.49  5101.7 1971.99
  5110.0 1972.49  5152.0 1979.06  5175.8 1972.56  5231.7 1974.84  6130.3 1973.75
  6572.3 1974.64  6622.1 1977.05  6715.4 1975.03  6850.4 1978.70  6943.7 1977.54
  6985.4 1980.50  7020.7 1978.72  7107.7 1983.07  7134.8 1981.20  7285.2 1987.85
#Mann=5,-1,0
  3040.2   0.045       0  3320.4    0.07       0  3537.7   0.045       0
  5101.2   0.045       0  5110.0   0.045       0
Bank Sta=5101.2,5110
Exp/Cntr=0.3,0.1

Type RM Length L Ch R = 1,144,0,0,0
BEGIN DESCRIPTION:
Cottonwood Creek Trib126 1.0
END DESCRIPTION:
XS GIS Cut Line= 5
      1381077.34      6941744.97      1381831.27      6943389.97
      1382092.98      6943843.96      1382561.73      6943703.34
      1384110.10      6941744.81
#Sta/Elev= 30
  2411.9 1990.82  2516.1 1991.57  2775.5 1979.54  3022.0 1976.27  4241.0 1974.15
  4275.0 1969.03  4288.4 1975.10  4302.4 1975.55  4361.3 1970.61  4500.6 1972.44
  4634.2 1963.92  4959.6 1964.21  4987.8 1960.59  4988.3 1960.09  4997.5 1960.59
  4998.1 1963.69  5008.6 1964.31  5233.9 1963.07  5440.5 1973.23  5613.3 1972.15
  5641.2 1971.72  5757.4 1969.57  5945.3 1967.75  6137.7 1972.67  7091.4 1976.93
  7298.2 1981.41  7333.4 1985.93  7370.4 1984.77  7397.6 1988.69  7731.5 2002.03
#Mann=8,-1,0
  2411.9    0.07       0  2516.1   0.045       0  4241.0    0.07       0
  4987.8    0.07       0  4997.5    0.07       0  5613.3   0.045       0
  5641.2    0.07       0  5757.4   0.045       0
Bank Sta=4987.8,4997.5
Exp/Cntr=0.3,0.1

Chan Stop Cuts=-1