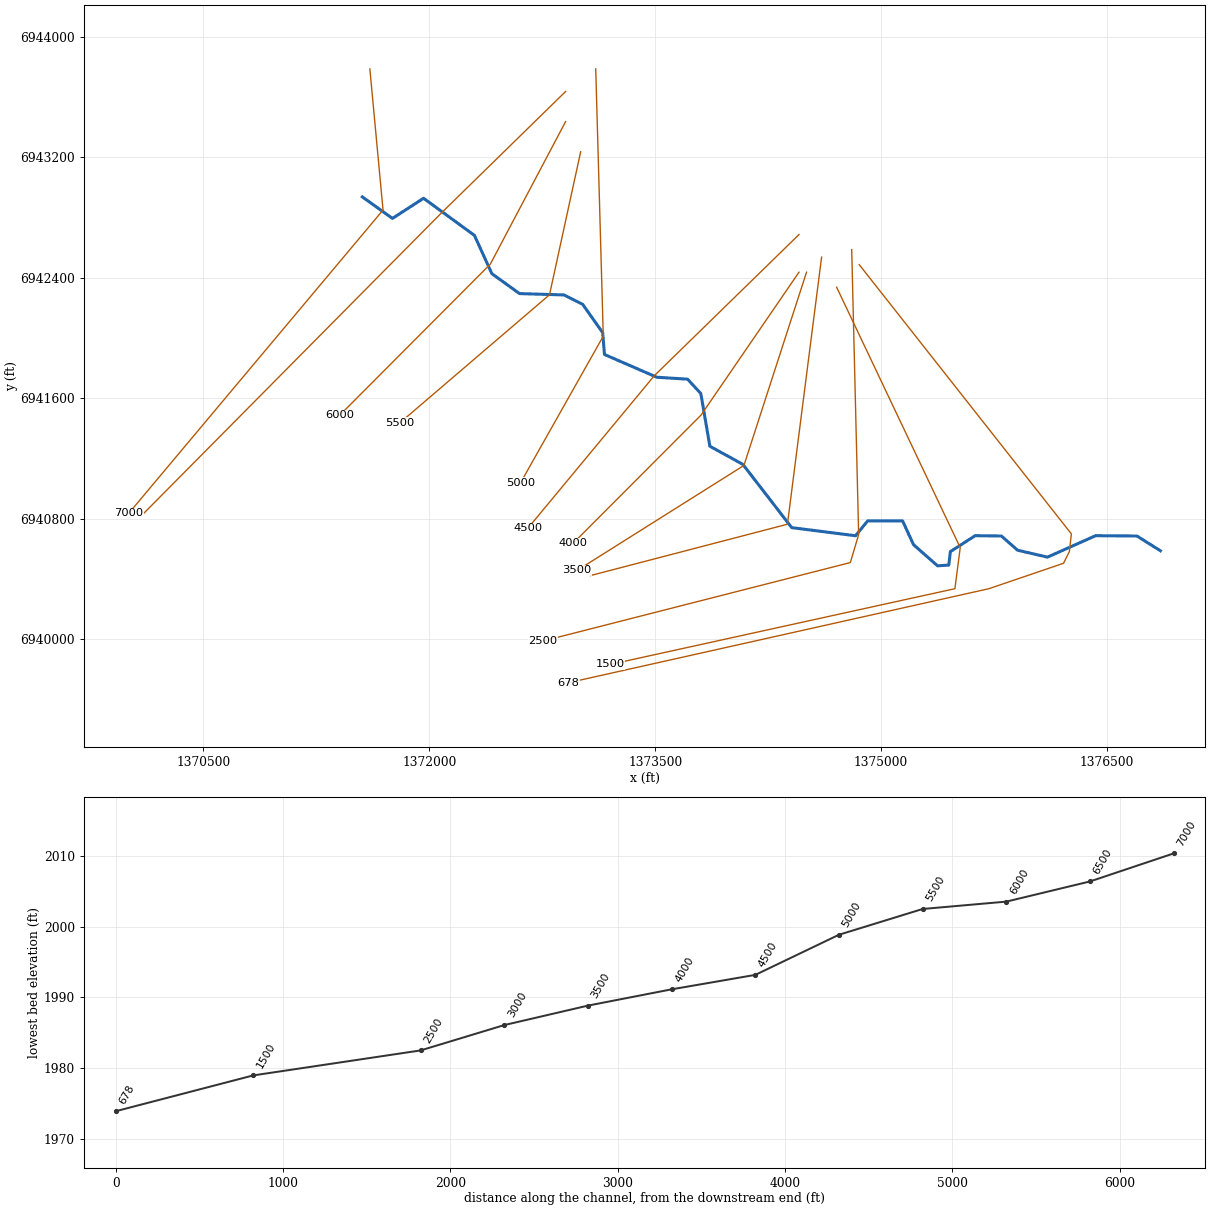
--- Cottonwood Creek Trib150.prj (project) ---

Proj Title=Cottonwood Creek Trib150 Base Level Engineering
Current Plan=p01
Default Exp/Contr=0.3,0.1
English Units
Geom File=g01
Flow File=f01
Plan File=p01
BEGIN DESCRIPTION:
Cottonwood Creek Trib150
END DESCRIPTION:

--- Cottonwood Creek Trib150.p01 (plan) ---

Plan Title=Multiple Run
Short Identifier=Multiple
Geom File=g01
Flow File=f01
Subcritical Flow
K Sum by GR= 0
Std Step Tol= 0.01
Critical Tol= 0.01
Num of Std Step Trials= 20
Max Error Tol= 0.3
Flow Tol Ratio= 0.001
Split Flow NTrial= 30
Split Flow Tol= 0.02
Split Flow Ratio= 0.02
Log Output Level= 0
Friction Slope Method= 1
Unsteady Friction Slope Method= 2
Unsteady Bridges Friction Slope Method= 1
Parabolic Critical Depth
Global Vel Dist=  1 , 1 , 1
Global Log Level= 0
CheckData=True
Encroach Param= -1, 0, 0, 0
BEGIN DESCRIPTION:
Multiple Run
END DESCRIPTION:

--- Cottonwood Creek Trib150.f01 (steady flow) ---

Flow Title=Multiple
Number of Profiles=7
Profile Names=10-year,25-year,50-year,1pct_min,100-year,1pct_plu,500-year
River Rch & RM= Cottonwood Creek,Reach-1,7000
     292     418     524     327     652    1301    1024
River Rch & RM= Cottonwood Creek,Reach-1,5500
     357     514     647     405     808    1612    1277
Boundary for River Rch & Prof#=Cottonwood Creek,Reach-1,1
Up Type=0
Dn Type=3
Dn Slope=0.005
Boundary for River Rch & Prof#=Cottonwood Creek,Reach-1,2
Up Type=0
Dn Type=3
Dn Slope=0.005
Boundary for River Rch & Prof#=Cottonwood Creek,Reach-1,3
Up Type=0
Dn Type=3
Dn Slope=0.005
Boundary for River Rch & Prof#=Cottonwood Creek,Reach-1,4
Up Type=0
Dn Type=3
Dn Slope=0.005
Boundary for River Rch & Prof#=Cottonwood Creek,Reach-1,5
Up Type=0
Dn Type=3
Dn Slope=0.005
Boundary for River Rch & Prof#=Cottonwood Creek,Reach-1,6
Up Type=0
Dn Type=3
Dn Slope=0.005
Boundary for River Rch & Prof#=Cottonwood Creek,Reach-1,7
Up Type=0
Dn Type=3
Dn Slope=0.005

--- Cottonwood Creek Trib150.g01 (geometry) ---

Geom Title=Existing Conditions

River Reach=Cottonwood Creek,Reach-1
Reach XY= 30
      1371555.00      6942938.00      1371755.00      6942795.09
      1371961.72      6942928.87      1372299.38      6942682.38
      1372415.39      6942427.90      1372598.81      6942295.83
      1372894.50      6942286.80      1373018.24      6942224.39
      1373151.24      6942036.44      1373163.10      6941891.35
      1373510.94      6941740.26      1373714.83      6941727.53
      1373802.95      6941632.16      1373863.13      6941281.92
      1374081.93      6941161.84      1374406.46      6940741.54
      1374830.19      6940687.65      1374910.68      6940785.99
      1375143.10      6940786.10      1375215.53      6940628.25
      1375375.23      6940487.71      1375449.86      6940493.02
      1375460.29      6940582.45      1375624.98      6940688.04
      1375799.14      6940685.94      1375906.47      6940591.56
      1376105.00      6940545.56      1376424.98      6940688.04
      1376699.15      6940685.94      1376855.00      6940588.00

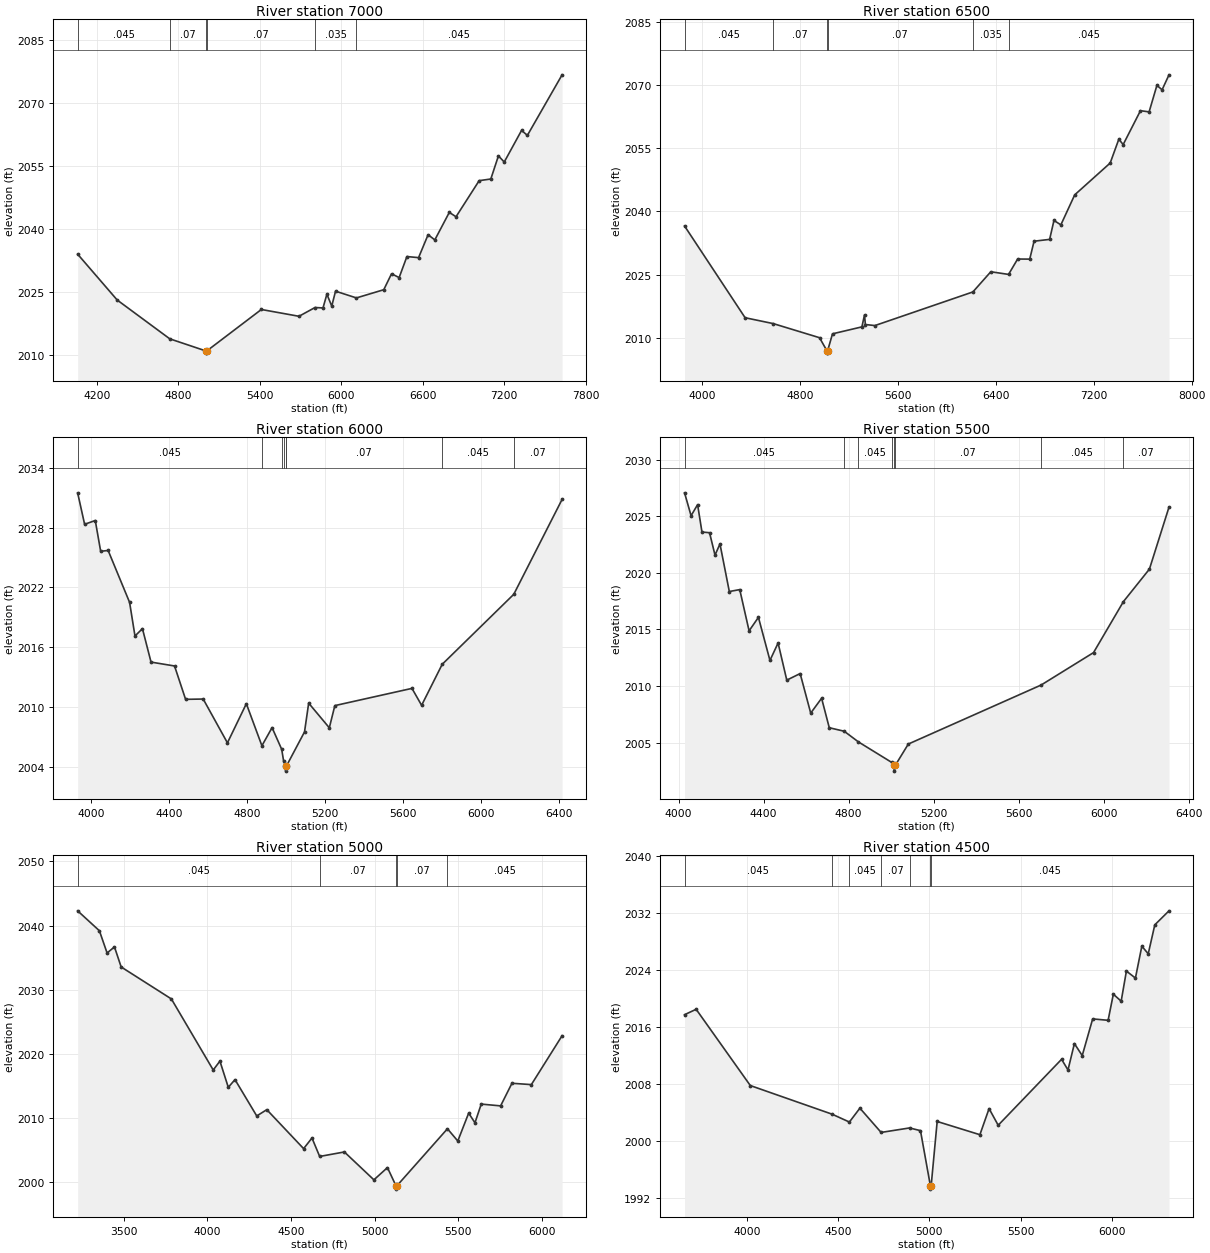
Type RM Length L Ch R = 1,7000,500,500,500
BEGIN DESCRIPTION:
Cottonwood Creek Trib150 14.0
END DESCRIPTION:
XS GIS Cut Line= 3
      1371605.00      6943788.04      1371692.51      6942850.72
      1370005.03      6940838.03
#Sta/Elev= 30
  4058.6 2033.96  4349.9 2023.02  4737.2 2013.76  5005.0 2010.85  5005.2 2010.35
  5009.0 2010.85  5411.6 2020.76  5688.7 2019.14  5806.9 2021.23  5865.7 2021.13
  5894.3 2024.41  5930.1 2021.57  5958.0 2025.13  6111.7 2023.52  6313.2 2025.48
  6370.4 2029.28  6426.4 2028.37  6483.6 2033.39  6569.5 2033.13  6639.7 2038.60
  6689.2 2037.36  6795.9 2043.93  6845.3 2042.88  7015.7 2051.49  7101.6 2051.89
  7157.6 2057.40  7200.5 2055.94  7328.0 2063.48  7370.9 2062.30  7626.5 2076.74
#Mann=6,-1,0
  4058.6   0.045       0  4737.2    0.07       0  5005.0    0.07       0
  5009.0    0.07       0  5806.9   0.035       0  6111.7   0.045       0
Bank Sta=5005,5009
Exp/Cntr=0.3,0.1

Type RM Length L Ch R = 1,6500,500,500,500
BEGIN DESCRIPTION:
Cottonwood Creek Trib150 13.0
END DESCRIPTION:
XS GIS Cut Line= 3
      1372905.03      6943638.03      1372086.32      6942837.43
      1370105.03      6940838.03
#Sta/Elev= 30
  3854.9 2036.56  4349.9 2014.79  4579.4 2013.40  4958.2 2010.05  5019.8 2006.89
  5020.0 2006.39  5023.8 2006.89  5064.2 2010.97  5304.6 2012.62  5325.8 2015.46
  5332.9 2013.18  5410.6 2012.93  6211.7 2020.91  6358.2 2025.70  6503.3 2025.07
  6577.4 2028.72  6676.4 2028.70  6711.8 2032.95  6839.0 2033.38  6874.4 2037.87
  6930.9 2036.83  7044.1 2043.95  7334.0 2051.50  7404.7 2057.16  7440.1 2055.88
  7581.5 2063.92  7652.2 2063.64  7715.9 2069.93  7758.3 2068.88  7814.8 2072.43
#Mann=6,-1,0
  3854.9   0.045       0  4579.4    0.07       0  5019.8    0.07       0
  5023.8    0.07       0  6211.7   0.035       0  6503.3   0.045       0
Bank Sta=5019.8,5023.8
Exp/Cntr=0.3,0.1

Type RM Length L Ch R = 1,6000,500,500,500
BEGIN DESCRIPTION:
Cottonwood Creek Trib150 12.0
END DESCRIPTION:
XS GIS Cut Line= 3
      1372905.00      6943438.00      1372405.02      6942491.54
      1371405.03      6941488.03
#Sta/Elev= 30
  3929.6 2031.49  3965.4 2028.33  4020.1 2028.71  4047.8 2025.62  4086.2 2025.70
  4196.3 2020.49  4224.0 2017.11  4262.3 2017.85  4306.4 2014.49  4427.1 2014.10
  4483.8 2010.75  4574.2 2010.78  4698.6 2006.38  4795.7 2010.31  4875.6 2006.09
  4927.8 2007.91  4977.2 2005.73  4986.8 2004.58  4997.2 2004.04  4997.4 2003.54
  5001.2 2004.04  5094.4 2007.48  5115.7 2010.37  5221.7 2007.89  5250.0 2010.12
  5646.0 2011.85  5695.5 2010.15  5801.3 2014.27  6168.7 2021.30  6416.7 2030.83
#Mann=8,-1,0
  3929.6   0.045       0  4875.6    0.07       0  4977.2   0.045       0
  4986.8    0.07       0  4997.2    0.07       0  5001.2    0.07       0
  5801.3   0.045       0  6168.7    0.07       0
Bank Sta=4997.2,5001.2
Exp/Cntr=0.3,0.1

Type RM Length L Ch R = 1,5500,500,500,500
BEGIN DESCRIPTION:
Cottonwood Creek Trib150 11.0
END DESCRIPTION:
XS GIS Cut Line= 3
      1373005.00      6943237.99      1372798.08      6942288.06
      1371805.01      6941438.01
#Sta/Elev= 30
  4027.8 2027.06  4058.5 2025.04  4089.2 2026.02  4109.7 2023.60  4145.4 2023.54
  4171.1 2021.56  4194.4 2022.55  4238.4 2018.35  4287.5 2018.52  4331.4 2014.88
  4375.4 2016.07  4429.6 2012.27  4467.9 2013.81  4508.8 2010.53  4571.7 2011.11
  4621.4 2007.62  4672.6 2008.93  4708.7 2006.33  4779.0 2006.02  4845.8 2005.08
  5001.6 2003.28  5014.8 2003.00  5015.1 2002.50  5019.0 2003.00  5080.6 2004.89
  5705.7 2010.10  5952.1 2012.96  6092.7 2017.46  6215.1 2020.33  6307.2 2025.80
#Mann=8,-1,0
  4027.8   0.045       0  4779.0    0.07       0  4845.8   0.045       0
  5001.6    0.07       0  5014.8   0.045       0  5019.0    0.07       0
  5705.7   0.045       0  6092.7    0.07       0
Bank Sta=5014.8,5019
Exp/Cntr=0.3,0.1

Type RM Length L Ch R = 1,5000,500,500,500
BEGIN DESCRIPTION:
Cottonwood Creek Trib150 10.0
END DESCRIPTION:
XS GIS Cut Line= 3
      1373105.00      6943787.97      1373155.16      6942013.28
      1372604.98      6941037.96
#Sta/Elev= 30
  3224.6 2042.29  3354.6 2039.18  3400.6 2035.71  3444.7 2036.66  3484.7 2033.53
  3784.8 2028.54  4034.9 2017.45  4074.9 2018.84  4124.9 2014.75  4165.0 2015.95
  4295.0 2010.28  4355.0 2011.26  4575.1 2005.18  4625.1 2006.84  4671.0 2003.96
  4818.7 2004.66  4995.1 2000.31  5076.1 2002.22  5127.4 1999.36  5127.7 1998.86
  5131.9 1999.36  5434.7 2008.28  5496.5 2006.37  5561.5 2010.72  5599.1 2009.21
  5636.6 2012.13  5752.4 2011.85  5820.1 2015.38  5936.1 2015.17  6119.8 2022.80
#Mann=5,-1,0
  3224.6   0.045       0  4671.0    0.07       0  5127.4    0.07       0
  5131.9    0.07       0  5434.7   0.045       0
Bank Sta=5127.4,5131.9
Exp/Cntr=0.3,0.1

Type RM Length L Ch R = 1,4500,500,500,500
BEGIN DESCRIPTION:
Cottonwood Creek Trib150 9.0
END DESCRIPTION:
XS GIS Cut Line= 3
      1374454.98      6942687.98      1373493.80      6941750.15
      1372655.03      6940738.04
#Sta/Elev= 30
  3657.1 2017.71  3720.7 2018.47  4017.8 2007.75  4465.8 2003.73  4561.3 2002.62
  4618.9 2004.57  4735.3 2001.16  4891.3 2001.79  4951.2 2001.41  5005.4 1993.69
  5005.7 1993.19  5009.9 1993.69  5042.8 2002.70  5277.2 2000.84  5327.5 2004.51
  5377.5 2002.17  5725.2 2011.44  5760.4 2009.94  5795.5 2013.65  5838.5 2011.96
  5895.8 2017.12  5980.5 2016.92  6009.1 2020.59  6052.1 2019.61  6080.8 2023.84
  6130.3 2022.86  6165.4 2027.34  6200.6 2026.27  6236.6 2030.34  6314.5 2032.31
#Mann=7,-1,0
  3657.1   0.045       0  4465.8    0.07       0  4561.3   0.045       0
  4735.3    0.07       0  4891.3   0.045       0  5005.4   0.045       0
  5009.9   0.045       0
Bank Sta=5005.4,5009.9
Exp/Cntr=0.3,0.1

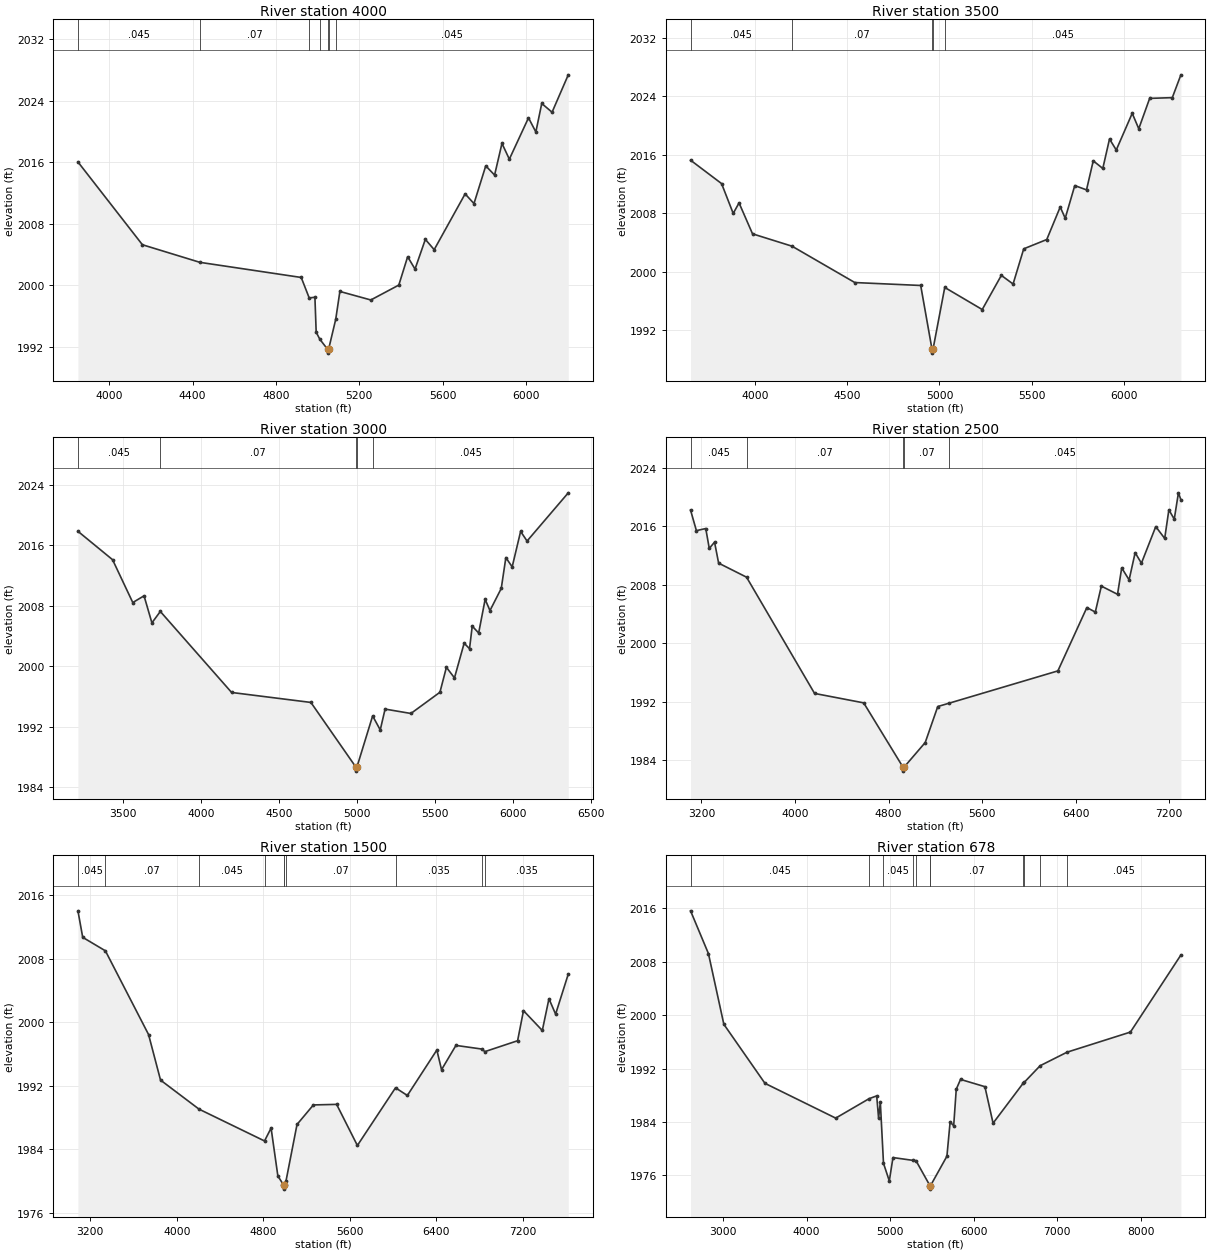
Type RM Length L Ch R = 1,4000,500,500,500
BEGIN DESCRIPTION:
Cottonwood Creek Trib150 8.0
END DESCRIPTION:
XS GIS Cut Line= 3
      1374455.01      6942438.01      1373804.93      6941489.51
      1372955.00      6940638.00
#Sta/Elev= 30
  3850.1 2016.04  4159.5 2005.26  4435.2 2002.97  4921.6 2001.00  4959.8 1998.34
  4987.3 1998.42  4993.4 1993.87  5010.8 1992.96  5048.1 1991.65  5048.4 1991.15
  5053.0 1991.65  5087.2 1995.56  5107.1 1999.18  5255.6 1998.07  5389.9 2000.01
  5432.3 2003.70  5467.7 2002.09  5517.2 2005.96  5559.6 2004.62  5708.1 2011.88
  5750.6 2010.62  5807.1 2015.53  5849.5 2014.33  5884.9 2018.45  5920.3 2016.40
  6012.2 2021.78  6047.5 2019.94  6075.8 2023.65  6125.3 2022.51  6203.1 2027.38
#Mann=7,-1,0
  3850.1   0.045       0  4435.2    0.07       0  4959.8   0.045       0
  5010.8    0.07       0  5048.1   0.045       0  5053.0    0.07       0
  5087.2   0.045       0
Bank Sta=5048.1,5053
Exp/Cntr=0.3,0.1

Type RM Length L Ch R = 1,3500,500,500,500
BEGIN DESCRIPTION:
Cottonwood Creek Trib150 7.0
END DESCRIPTION:
XS GIS Cut Line= 3
      1374504.99      6942437.96      1374089.23      6941154.53
      1372981.72      6940457.49
#Sta/Elev= 30
  3650.9 2015.23  3819.0 2012.03  3882.1 2007.95  3913.7 2009.39  3986.8 2005.16
  4201.0 2003.47  4541.2 1998.50  4898.3 1998.10  4959.8 1989.35  4960.2 1988.85
  4964.8 1989.35  5028.7 1997.83  5231.8 1994.81  5335.4 1999.48  5399.0 1998.30
  5456.7 2003.11  5581.5 2004.38  5654.5 2008.83  5681.6 2007.29  5733.4 2011.76
  5797.0 2011.17  5833.5 2015.14  5885.3 2014.10  5921.7 2018.13  5958.2 2016.62
  6044.8 2021.64  6080.2 2019.53  6139.3 2023.68  6262.0 2023.78  6308.6 2026.90
#Mann=5,-1,0
  3650.9   0.045       0  4201.0    0.07       0  4959.8    0.07       0
  4964.8    0.07       0  5028.7   0.045       0
Bank Sta=4959.8,4964.8
Exp/Cntr=0.3,0.1

Type RM Length L Ch R = 1,3000,500,500,500
BEGIN DESCRIPTION:
Cottonwood Creek Trib150 6.0
END DESCRIPTION:
XS GIS Cut Line= 3
      1374605.00      6942538.02      1374378.15      6940764.17
      1373069.68      6940423.06
#Sta/Elev= 30
  3211.7 2017.84  3433.5 2014.08  3563.0 2008.41  3635.1 2009.30  3685.5 2005.72
  3739.4 2007.23  4195.9 1996.51  4703.8 1995.19  4993.0 1986.60  4993.4 1986.10
  4998.0 1986.60  5099.2 1993.41  5147.9 1991.55  5178.9 1994.31  5344.3 1993.73
  5530.3 1996.54  5571.6 1999.84  5623.3 1998.44  5685.3 2003.03  5719.8 2002.30
  5737.0 2005.29  5778.3 2004.38  5819.7 2008.83  5850.7 2007.35  5923.0 2010.28
  5952.4 2014.36  5992.9 2013.13  6047.0 2017.82  6088.3 2016.55  6352.2 2022.93
#Mann=5,-1,0
  3211.7   0.045       0  3739.4    0.07       0  4993.0    0.07       0
  4998.0    0.07       0  5099.2   0.045       0
Bank Sta=4993,4998
Exp/Cntr=0.3,0.1

Type RM Length L Ch R = 1,2500,1000,1000,1000
BEGIN DESCRIPTION:
Cottonwood Creek Trib150 5.0
END DESCRIPTION:
XS GIS Cut Line= 4
      1374805.00      6942587.98      1374851.10      6940695.44
      1374795.92      6940509.56      1372755.96      6939988.72
#Sta/Elev= 30
  3106.9 2018.20  3156.9 2015.39  3236.9 2015.68  3266.9 2012.96  3312.1 2013.82
  3346.9 2010.95  3585.7 2009.03  4167.2 1993.14  4587.3 1991.85  4924.9 1983.02
  4925.3 1982.52  4930.0 1983.02  5113.3 1986.43  5220.5 1991.35  5318.3 1991.81
  6247.6 1996.22  6495.3 2004.88  6567.5 2004.26  6619.1 2007.81  6757.5 2006.69
  6793.2 2010.30  6856.5 2008.66  6908.1 2012.38  6961.7 2010.94  7084.3 2015.94
  7160.8 2014.33  7196.5 2018.24  7242.5 2016.96  7278.2 2020.56  7299.3 2019.62
#Mann=5,-1,0
  3106.9   0.045       0  3585.7    0.07       0  4924.9    0.07       0
  4930.0    0.07       0  5318.3   0.045       0
Bank Sta=4924.9,4930
Exp/Cntr=0.3,0.1

Type RM Length L Ch R = 1,1500,822,822,822
BEGIN DESCRIPTION:
Cottonwood Creek Trib150 3.0
END DESCRIPTION:
XS GIS Cut Line= 4
      1374705.02      6942337.96      1375525.68      6940608.71
      1375490.36      6940335.95      1373200.52      6939832.87
#Sta/Elev= 30
  3085.9 2014.06  3130.1 2010.72  3339.8 2009.02  3738.9 1998.47  3849.6 1992.73
  4205.4 1989.07  4811.0 1985.06  4871.8 1986.68  4934.4 1980.65  4988.4 1979.49
  4988.8 1978.99  4993.6 1979.49  5009.7 1980.02  5111.6 1987.14  5262.9 1989.60
  5477.7 1989.67  5669.6 1984.49  6022.2 1991.76  6131.5 1990.79  6404.4 1996.52
  6447.7 1994.04  6580.8 1997.10  6826.3 1996.63  6846.8 1996.31  7151.0 1997.69
  7205.4 2001.48  7379.4 1998.98  7440.9 2002.98  7502.3 2001.04  7619.5 2006.09
#Mann=10,-1,0
  3085.9   0.045       0  3339.8    0.07       0  4205.4   0.045       0
  4811.0   0.035       0  4988.4   0.035       0  4993.6   0.035       0
  5009.7    0.07       0  6022.2   0.035       0  6826.3   0.045       0
  6846.8   0.035       0
Bank Sta=4988.4,4993.6
Exp/Cntr=0.3,0.1

Type RM Length L Ch R = 1,678,0,0,0
BEGIN DESCRIPTION:
Cottonwood Creek Trib150 2.0
END DESCRIPTION:
XS GIS Cut Line= 6
      1374854.99      6942488.01      1376263.70      6940700.13
      1376250.68      6940582.94      1376211.62      6940504.81
      1375716.06      6940335.95      1372920.96      6939710.95
#Sta/Elev= 30
  2610.7 2015.63  2824.8 2009.22  3009.2 1998.63  3501.5 1989.78  4348.1 1984.57
  4747.2 1987.48  4838.7 1987.90  4861.3 1984.56  4882.1 1986.97  4920.1 1977.80
  4989.6 1975.16  5033.5 1978.66  5271.7 1978.24  5308.6 1978.20  5476.8 1974.43
  5477.3 1973.93  5482.1 1974.43  5679.2 1978.86  5717.5 1983.99  5760.2 1983.43
  5791.0 1988.90  5842.2 1990.37  6133.8 1989.28  6231.6 1983.81  6593.1 1989.82
  6605.2 1989.94  6794.8 1992.42  7117.3 1994.45  7875.4 1997.46  8479.8 2009.01
#Mann=11,-1,0
  2610.7   0.045       0  4747.2    0.07       0  4920.1   0.045       0
  5271.7    0.16       0  5308.6    0.07       0  5476.8   0.045       0
  5482.1    0.07       0  6593.1   0.035       0  6605.2    0.07       0
  6794.8   0.035       0  7117.3   0.045       0
Bank Sta=5476.8,5482.1
Exp/Cntr=0.3,0.1

Chan Stop Cuts=-1