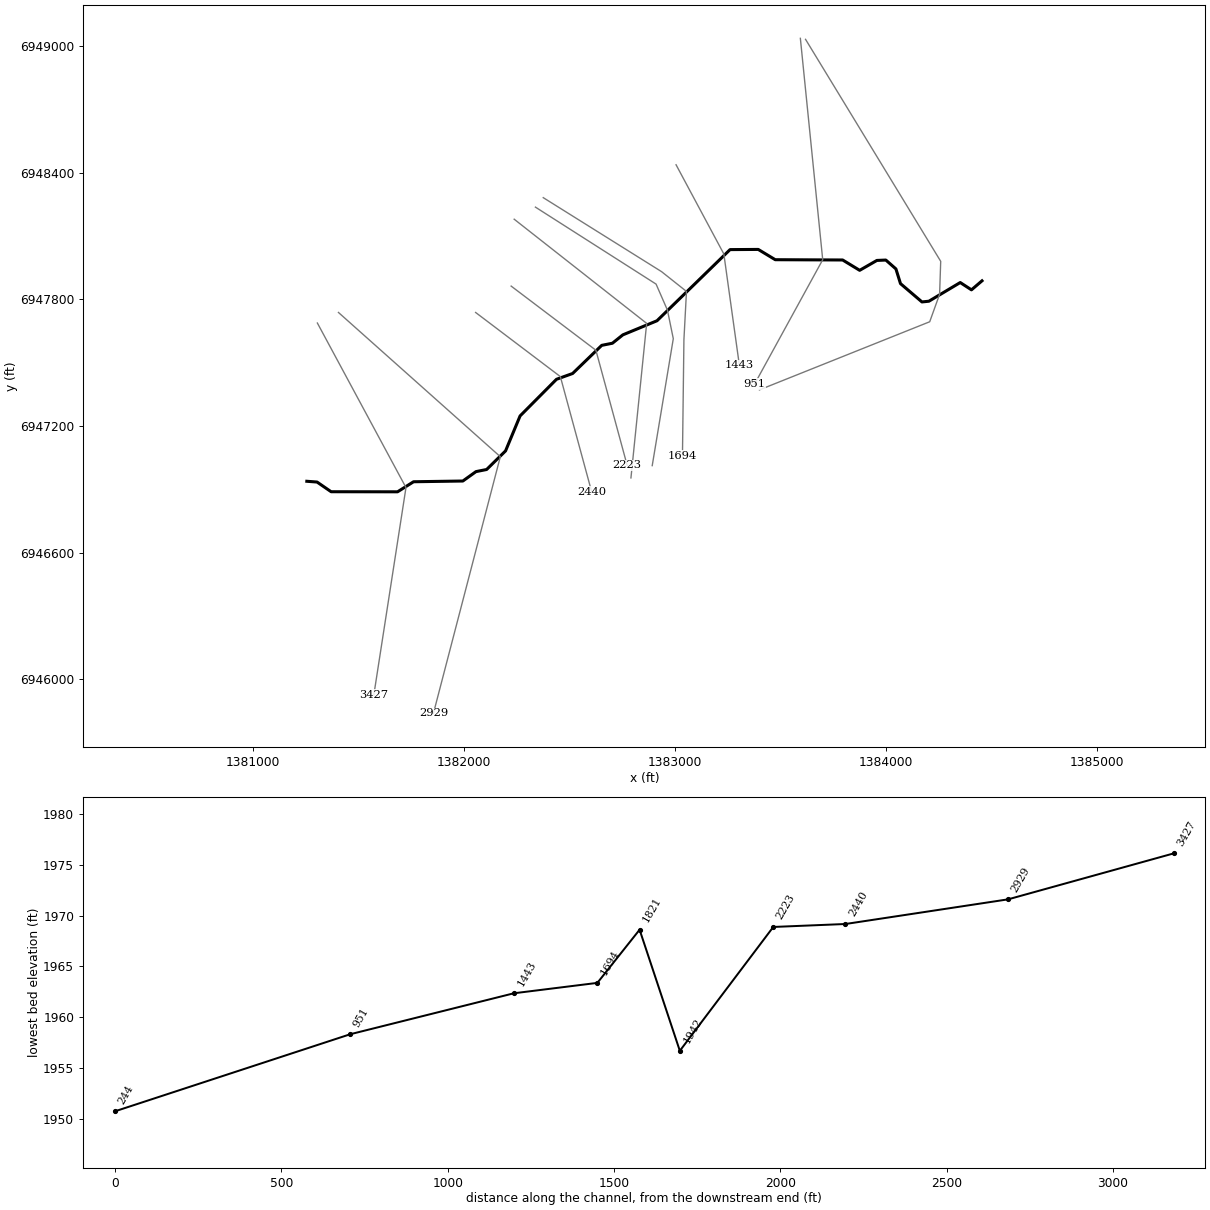
--- Cottonwood Creek Trib151.prj (project) ---

Proj Title=Cottonwood Creek Trib151 Base Level Engineering
Current Plan=p01
Default Exp/Contr=0.3,0.1
English Units
Geom File=g01
Flow File=f01
Plan File=p01
BEGIN DESCRIPTION:
Cottonwood Creek Trib151
END DESCRIPTION:

--- Cottonwood Creek Trib151.p01 (plan) ---

Plan Title=Multiple Run
Short Identifier=Multiple
Geom File=g01
Flow File=f01
Subcritical Flow
K Sum by GR= 0
Std Step Tol= 0.01
Critical Tol= 0.01
Num of Std Step Trials= 20
Max Error Tol= 0.3
Flow Tol Ratio= 0.001
Split Flow NTrial= 30
Split Flow Tol= 0.02
Split Flow Ratio= 0.02
Log Output Level= 0
Friction Slope Method= 1
Unsteady Friction Slope Method= 2
Unsteady Bridges Friction Slope Method= 1
Parabolic Critical Depth
Global Vel Dist=  1 , 1 , 1
Global Log Level= 0
CheckData=True
Encroach Param= -1, 0, 0, 0
BEGIN DESCRIPTION:
Multiple Run
END DESCRIPTION:

--- Cottonwood Creek Trib151.f01 (steady flow) ---

Flow Title=Multiple
Number of Profiles=7
Profile Names=10-year,25-year,50-year,1pct_min,100-year,1pct_plu,500-year
River Rch & RM= Cottonwood Creek,Reach-1,3427
     273     385     479     296     591    1179     912
Boundary for River Rch & Prof#=Cottonwood Creek,Reach-1,1
Up Type=0
Dn Type=3
Dn Slope=0.005
Boundary for River Rch & Prof#=Cottonwood Creek,Reach-1,2
Up Type=0
Dn Type=3
Dn Slope=0.005
Boundary for River Rch & Prof#=Cottonwood Creek,Reach-1,3
Up Type=0
Dn Type=3
Dn Slope=0.005
Boundary for River Rch & Prof#=Cottonwood Creek,Reach-1,4
Up Type=0
Dn Type=3
Dn Slope=0.005
Boundary for River Rch & Prof#=Cottonwood Creek,Reach-1,5
Up Type=0
Dn Type=3
Dn Slope=0.005
Boundary for River Rch & Prof#=Cottonwood Creek,Reach-1,6
Up Type=0
Dn Type=3
Dn Slope=0.005
Boundary for River Rch & Prof#=Cottonwood Creek,Reach-1,7
Up Type=0
Dn Type=3
Dn Slope=0.005

--- Cottonwood Creek Trib151.g01 (geometry) ---

Geom Title=Existing Conditions

River Reach=Cottonwood Creek,Reach-1
Reach XY= 30
      1381255.00      6946938.00      1381303.49      6946934.35
      1381370.19      6946888.45      1381684.97      6946888.07
      1381760.94      6946935.74      1381994.50      6946939.20
      1382056.75      6946983.78      1382107.31      6946993.82
      1382196.87      6947081.93      1382265.76      6947247.68
      1382438.33      6947421.35      1382514.68      6947448.78
      1382652.70      6947582.17      1382703.26      6947592.19
      1382752.80      6947631.92      1382914.68      6947698.76
      1383260.86      6948035.95      1383394.49      6948036.79
      1383475.03      6947988.07      1383794.50      6947986.76
      1383875.18      6947937.73      1383956.76      6947984.64
      1383999.15      6947986.45      1384046.96      6947944.43
      1384068.63      6947874.77      1384170.33      6947787.94
      1384203.26      6947791.31      1384351.77      6947879.88
      1384405.01      6947845.23      1384455.00      6947888.00

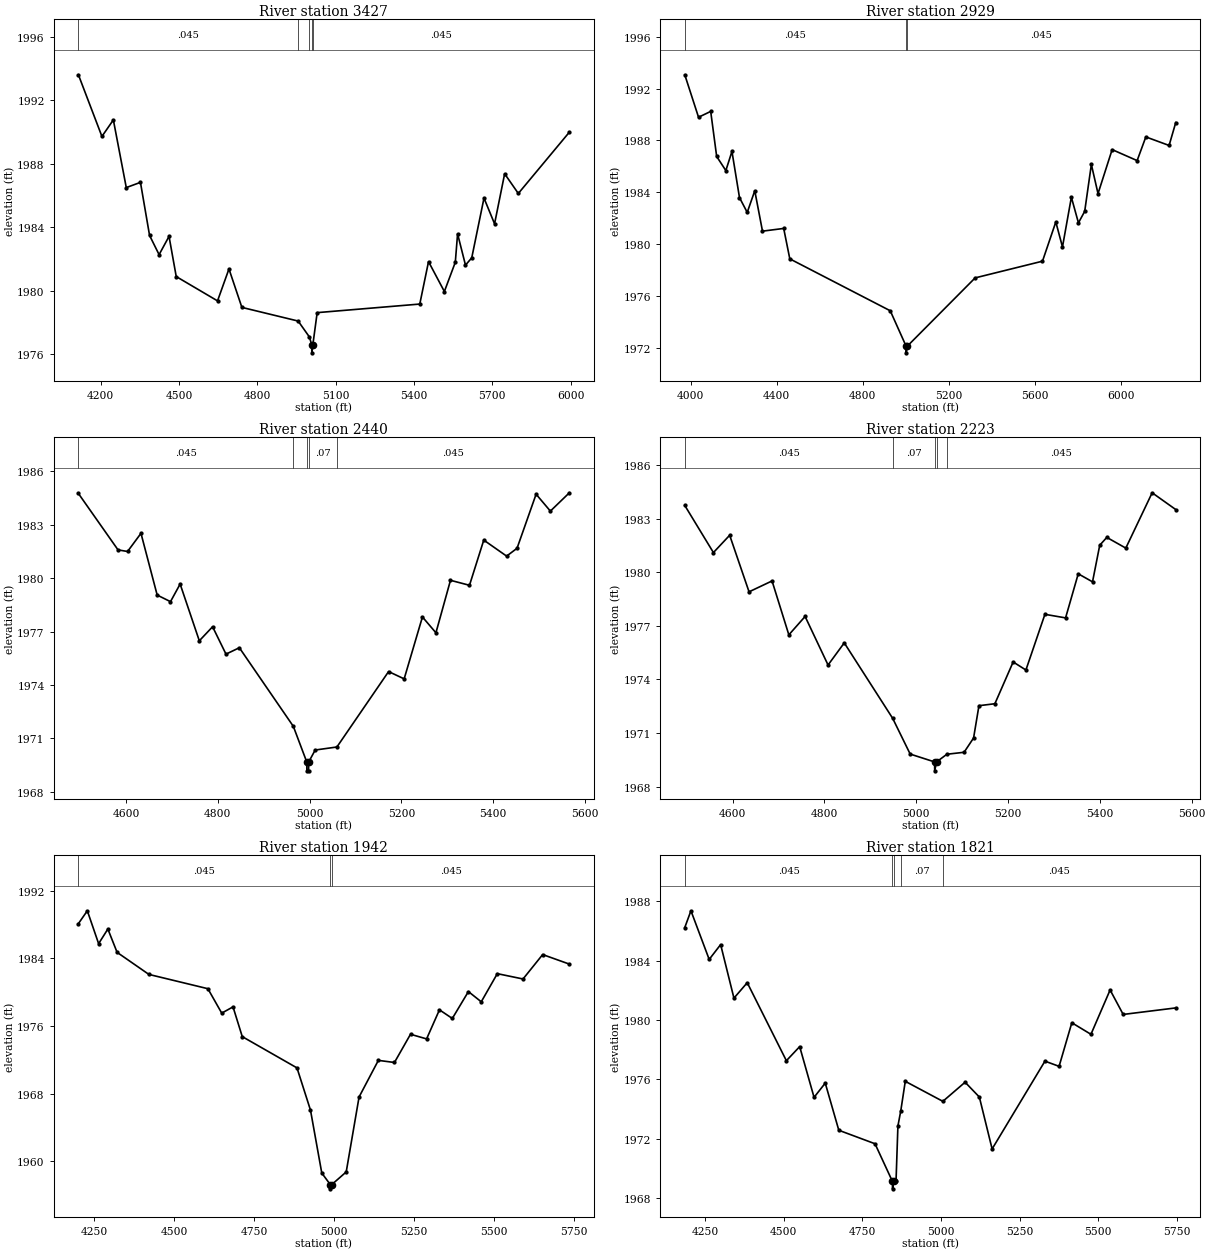
Type RM Length L Ch R = 1,3427,498,498,498
BEGIN DESCRIPTION:
Cottonwood Creek Trib151 6.0
END DESCRIPTION:
XS GIS Cut Line= 3
      1381304.99      6947688.01      1381724.96      6946908.10
      1381572.49      6945924.75
#Sta/Elev= 30
  4114.2 1993.60  4204.3 1989.72  4248.1 1990.76  4297.6 1986.50  4351.9 1986.83
  4386.8 1983.49  4423.3 1982.28  4461.4 1983.43  4489.0 1980.90  4647.2 1979.37
  4691.0 1981.38  4740.5 1978.96  4956.1 1978.10  4999.1 1977.10  5008.2 1976.60
  5008.4 1976.10  5012.3 1976.60  5028.9 1978.63  5422.0 1979.17  5455.5 1981.84
  5516.2 1979.96  5558.1 1981.80  5566.8 1983.59  5597.1 1981.62  5621.1 1982.08
  5668.0 1985.84  5708.5 1984.22  5747.1 1987.37  5799.5 1986.13  5995.1 1989.99
#Mann=5,-1,0
  4114.2   0.045       0  4956.1    0.07       0  4999.1   0.045       0
  5008.2   0.045       0  5012.3   0.045       0
Bank Sta=5008.2,5012.3
Exp/Cntr=0.3,0.1

Type RM Length L Ch R = 1,2929,489,489,489
BEGIN DESCRIPTION:
Cottonwood Creek Trib151 5.0
END DESCRIPTION:
XS GIS Cut Line= 3
      1381404.98      6947738.02      1382172.08      6947054.42
      1381854.99      6945837.97
#Sta/Elev= 30
  3972.5 1993.07  4036.5 1989.79  4093.1 1990.24  4120.9 1986.76  4163.6 1985.67
  4192.0 1987.15  4227.1 1983.58  4263.1 1982.44  4298.2 1984.11  4334.1 1980.99
  4432.8 1981.20  4461.2 1978.85  4928.6 1974.84  5002.8 1972.09  5003.0 1971.59
  5007.0 1972.09  5323.6 1977.38  5637.0 1978.67  5699.0 1981.70  5730.0 1979.77
  5771.4 1983.61  5804.3 1981.63  5833.4 1982.52  5864.4 1986.14  5895.4 1983.89
  5961.1 1987.29  6077.4 1986.44  6117.9 1988.27  6226.1 1987.61  6257.1 1989.38
#Mann=3,-1,0
  3972.5   0.045       0  5002.8   0.045       0  5007.0   0.045       0
Bank Sta=5002.8,5007
Exp/Cntr=0.3,0.1

Type RM Length L Ch R = 1,2440,217,217,217
BEGIN DESCRIPTION:
Cottonwood Creek Trib151 4.0
END DESCRIPTION:
XS GIS Cut Line= 3
      1382055.01      6947738.00      1382456.65      6947434.02
      1382604.99      6946888.02
#Sta/Elev= 30
  4496.3 1984.76  4582.6 1981.59  4603.4 1981.50  4632.6 1982.52  4667.9 1979.05
  4696.9 1978.68  4717.9 1979.67  4759.7 1976.48  4788.6 1977.27  4817.8 1975.73
  4846.9 1976.09  4964.5 1971.67  4993.7 1969.67  4994.0 1969.17  4997.7 1969.17
  4998.0 1969.67  5012.1 1970.34  5059.4 1970.51  5172.0 1974.75  5205.9 1974.34
  5245.7 1977.82  5275.1 1976.93  5306.8 1979.88  5348.2 1979.60  5379.3 1982.14
  5429.1 1981.24  5451.8 1981.68  5493.3 1984.72  5524.4 1983.77  5565.8 1984.80
#Mann=5,-1,0
  4496.3   0.045       0  4964.5    0.07       0  4993.7    0.07       0
  4998.0    0.07       0  5059.4   0.045       0
Bank Sta=4993.7,4998
Exp/Cntr=0.3,0.1

Type RM Length L Ch R = 1,2223,281,281,281
BEGIN DESCRIPTION:
Cottonwood Creek Trib151 3.5
END DESCRIPTION:
XS GIS Cut Line= 3
      1382223.40      6947863.00      1382625.05      6947559.02
      1382773.39      6947013.03
#Sta/Elev= 30
  4495.9 1983.75  4558.3 1981.11  4593.7 1982.08  4635.9 1978.91  4686.0 1979.52
  4722.6 1976.50  4758.0 1977.53  4808.0 1974.81  4843.3 1976.05  4948.8 1971.82
  4986.9 1969.82  5040.0 1969.38  5040.3 1968.88  5044.3 1969.38  5066.9 1969.81
  5104.3 1969.92  5125.0 1970.72  5136.7 1972.53  5171.4 1972.64  5211.2 1974.98
  5239.0 1974.53  5280.4 1977.65  5325.4 1977.45  5353.0 1979.92  5384.1 1979.47
  5399.8 1981.52  5415.2 1981.96  5456.6 1981.36  5514.0 1984.46  5565.4 1983.52
#Mann=5,-1,0
  4495.9   0.045       0  4948.8    0.07       0  5040.0    0.07       0
  5044.3    0.07       0  5066.9   0.045       0
Bank Sta=5040,5044.3
Exp/Cntr=0.3,0.1

Type RM Length L Ch R = 1,1942,121,121,121
BEGIN DESCRIPTION:
Cottonwood Creek Trib151 3.0
END DESCRIPTION:
XS GIS Cut Line= 3
      1382237.74      6948180.00      1382865.70      6947686.30
      1382791.15      6946953.89
#Sta/Elev= 30
  4201.2 1988.10  4229.1 1989.62  4264.4 1985.73  4293.3 1987.46  4322.2 1984.70
  4421.6 1982.09  4606.0 1980.40  4649.3 1977.51  4684.6 1978.25  4713.5 1974.73
  4884.6 1971.03  4926.8 1966.03  4962.1 1958.59  4988.8 1957.22  4989.1 1956.72
  4993.2 1957.22  5038.5 1958.72  5078.7 1967.59  5139.0 1971.92  5189.3 1971.67
  5239.5 1975.01  5289.8 1974.46  5330.0 1977.90  5370.2 1976.88  5420.5 1980.06
  5460.7 1978.85  5510.9 1982.18  5591.3 1981.55  5652.7 1984.44  5736.2 1983.31
#Mann=3,-1,0
  4201.2   0.045       0  4988.8   0.045       0  4993.2   0.045       0
Bank Sta=4988.8,4993.2
Exp/Cntr=0.3,0.1

Type RM Length L Ch R = 1,1821,127,127,127
BEGIN DESCRIPTION:
Cottonwood Creek Trib151 2.6
END DESCRIPTION:
XS GIS Cut Line= 5
      1382338.48      6948237.26      1382910.27      6947872.44
      1382964.09      6947749.17      1382991.86      6947613.76
      1382892.00      6947012.09
#Sta/Elev= 30
  4185.3 1986.23  4204.9 1987.36  4262.9 1984.08  4299.3 1985.08  4341.6 1981.47
  4383.9 1982.51  4508.3 1977.25  4550.6 1978.20  4596.3 1974.78  4631.9 1975.74
  4675.0 1972.56  4790.1 1971.65  4845.5 1969.11  4845.8 1968.61  4849.9 1969.11
  4856.9 1969.12  4862.9 1972.85  4872.0 1973.87  4886.3 1975.86  5005.8 1974.51
  5076.5 1975.80  5121.8 1974.80  5162.4 1971.30  5330.3 1977.22  5375.3 1976.87
  5415.8 1979.81  5476.6 1979.03  5537.5 1982.02  5579.1 1980.37  5746.2 1980.81
#Mann=5,-1,0
  4185.3   0.045       0  4845.5    0.07       0  4849.9   0.045       0
  4872.0    0.07       0  5005.8   0.045       0
Bank Sta=4845.5,4849.9
Exp/Cntr=0.3,0.1

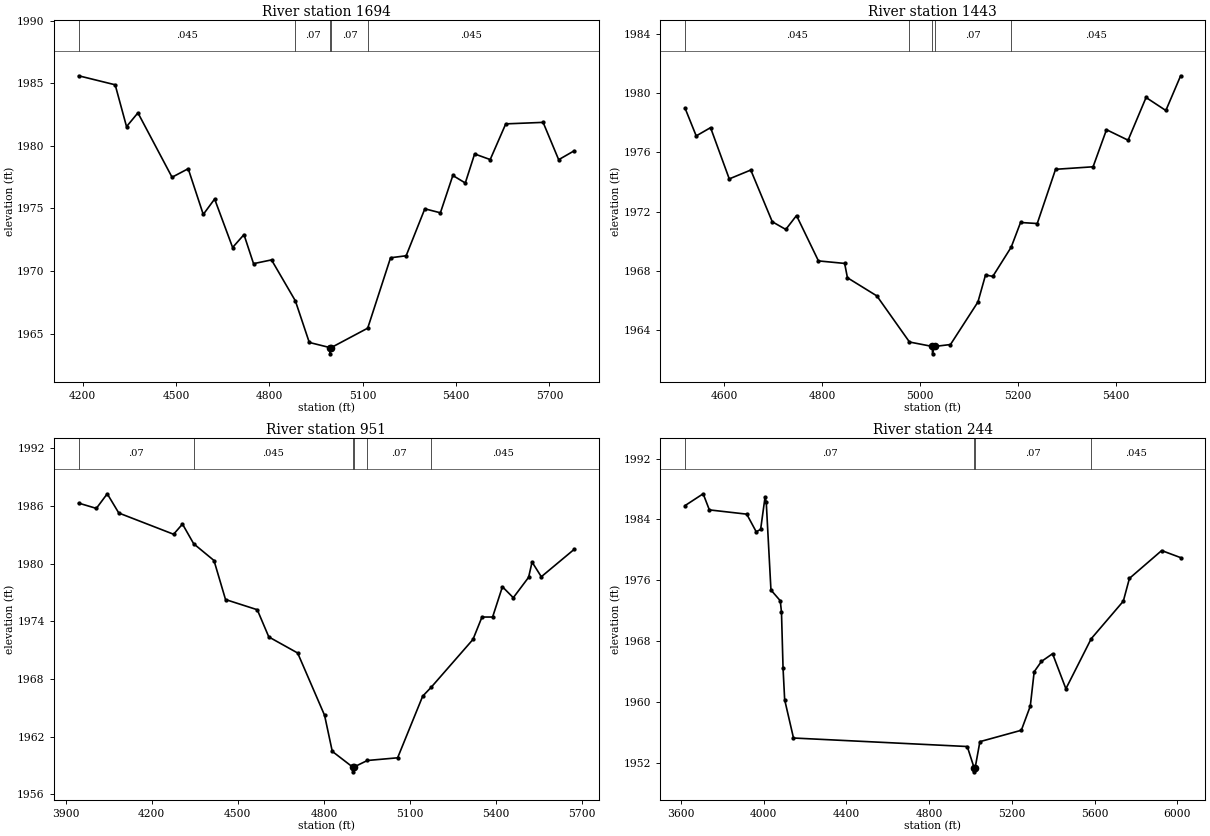
Type RM Length L Ch R = 1,1694,251,251,251
BEGIN DESCRIPTION:
Cottonwood Creek Trib151 2.5
END DESCRIPTION:
XS GIS Cut Line= 5
      1382375.56      6948282.15      1382936.31      6947931.46
      1383054.36      6947837.71      1383042.21      6947608.55
      1383035.27      6947058.21
#Sta/Elev= 30
  4187.5 1985.59  4304.9 1984.87  4341.4 1981.53  4378.0 1982.63  4487.6 1977.49
  4539.5 1978.17  4587.9 1974.52  4624.4 1975.75  4682.2 1971.88  4718.7 1972.91
  4749.4 1970.59  4807.2 1970.89  4883.8 1967.62  4928.5 1964.30  4994.6 1963.89
  4994.9 1963.39  4999.0 1963.89  5116.2 1965.44  5189.6 1971.06  5239.7 1971.22
  5299.7 1974.97  5349.7 1974.65  5389.7 1977.63  5429.7 1977.03  5459.7 1979.35
  5509.7 1978.90  5559.7 1981.75  5679.7 1981.87  5729.7 1978.89  5779.5 1979.60
#Mann=5,-1,0
  4187.5   0.045       0  4883.8    0.07       0  4994.6    0.07       0
  4999.0    0.07       0  5116.2   0.045       0
Bank Sta=4994.6,4999
Exp/Cntr=0.3,0.1

Type RM Length L Ch R = 1,1443,492,492,492
BEGIN DESCRIPTION:
Cottonwood Creek Trib151 2.0
END DESCRIPTION:
XS GIS Cut Line= 3
      1383004.99      6948438.01      1383231.47      6948015.14
      1383304.99      6947488.05
#Sta/Elev= 30
  4520.3 1978.99  4543.0 1977.12  4572.3 1977.68  4610.5 1974.21  4654.4 1974.81
  4698.3 1971.31  4725.9 1970.79  4747.8 1971.73  4792.6 1968.66  4846.1 1968.49
  4851.8 1967.52  4911.9 1966.29  4978.5 1963.17  5025.2 1962.87  5025.5 1962.37
  5029.6 1962.87  5062.2 1963.00  5118.3 1965.88  5133.8 1967.71  5148.6 1967.61
  5186.2 1969.59  5205.3 1971.26  5239.4 1971.19  5276.8 1974.86  5353.4 1975.03
  5380.8 1977.54  5424.9 1976.83  5461.6 1979.72  5502.0 1978.84  5532.2 1981.19
#Mann=5,-1,0
  4520.3   0.045       0  4978.5    0.07       0  5025.2    0.07       0
  5029.6    0.07       0  5186.2   0.045       0
Bank Sta=5025.2,5029.6
Exp/Cntr=0.3,0.1

Type RM Length L Ch R = 1,951,707,707,707
BEGIN DESCRIPTION:
Cottonwood Creek Trib151 1.0
END DESCRIPTION:
XS GIS Cut Line= 3
      1383594.09      6949037.23      1383700.03      6947988.06
      1383377.09      6947398.74
#Sta/Elev= 30
  3945.5 1986.30  4007.2 1985.75  4045.2 1987.27  4085.4 1985.27  4276.4 1983.06
  4307.3 1984.12  4346.4 1982.07  4417.1 1980.33  4457.3 1976.27  4567.9 1975.21
  4608.1 1972.38  4708.6 1970.71  4802.4 1964.23  4829.2 1960.48  4900.1 1958.85
  4900.5 1958.35  4904.6 1958.85  4951.4 1959.53  5056.9 1959.81  5144.2 1966.22
  5173.7 1967.14  5319.4 1972.12  5350.8 1974.45  5387.8 1974.45  5422.0 1977.60
  5459.9 1976.46  5513.2 1978.58  5525.3 1980.17  5557.5 1978.64  5672.0 1981.49
#Mann=6,-1,0
  3945.5    0.07       0  4346.4   0.045       0  4900.1    0.07       0
  4904.6   0.045       0  4951.4    0.07       0  5173.7   0.045       0
Bank Sta=4900.1,4904.6
Exp/Cntr=0.3,0.1

Type RM Length L Ch R = 1,244,0,0,0
BEGIN DESCRIPTION:
Cottonwood Creek Trib151 0.5
END DESCRIPTION:
XS GIS Cut Line= 5
      1383618.60      6949032.52      1384259.21      6947980.46
      1384254.01      6947824.21      1384207.13      6947694.01
      1383399.89      6947371.11
#Sta/Elev= 30
  3620.3 1985.82  3707.6 1987.37  3737.6 1985.25  3918.3 1984.69  3964.2 1982.37
  3985.5 1982.69  4006.8 1986.92  4012.7 1986.25  4035.4 1974.71  4080.4 1973.30
  4086.3 1971.80  4093.9 1964.44  4101.7 1960.27  4144.4 1955.24  4984.6 1954.12
  5018.0 1951.29  5018.3 1950.79  5022.5 1951.29  5045.6 1954.76  5246.0 1956.26
  5289.3 1959.44  5308.1 1963.96  5343.1 1965.31  5397.0 1966.33  5461.4 1961.72
  5583.8 1968.30  5739.0 1973.24  5768.6 1976.24  5924.5 1979.90  6016.2 1978.97
#Mann=4,-1,0
  3620.3    0.07       0  5018.0    0.07       0  5022.5    0.07       0
  5583.8   0.045       0
Bank Sta=5018,5022.5
Exp/Cntr=0.3,0.1

Chan Stop Cuts=-1