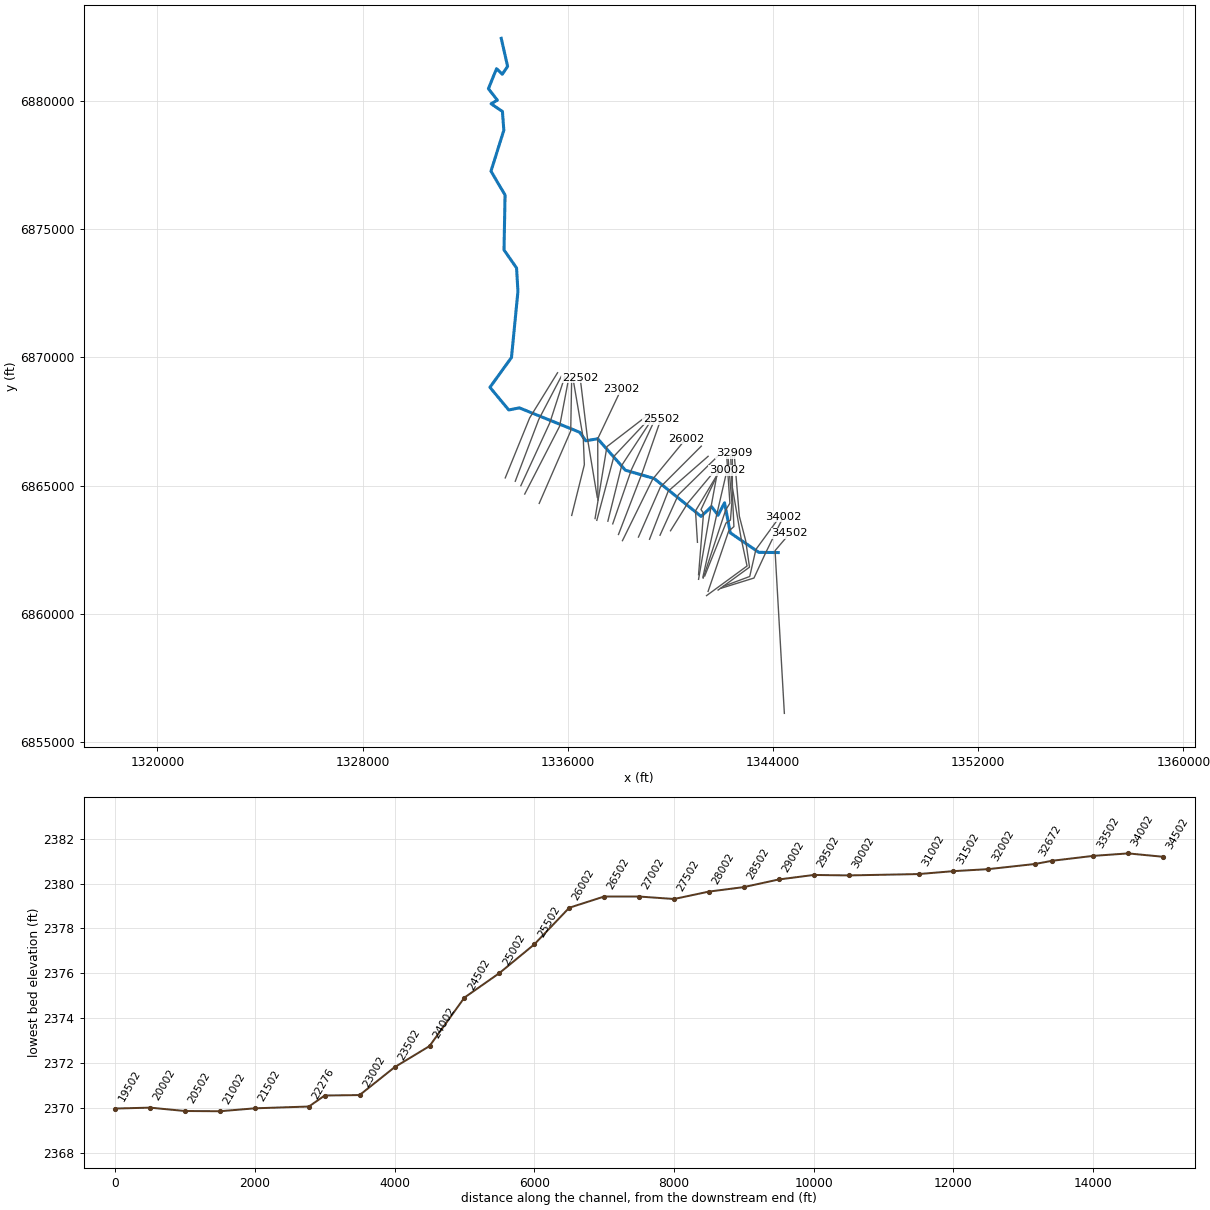
--- Cottonwood Trib044.prj (project) ---

Proj Title=Cottonwood Trib044 Base Level Engineering
Current Plan=p01
Default Exp/Contr=0.3,0.1
English Units
Geom File=g01
Flow File=f01
Plan File=p01
BEGIN DESCRIPTION:
Cottonwood Trib044
END DESCRIPTION:

--- Cottonwood Trib044.p01 (plan) ---

Plan Title=Multiple Run
Short Identifier=Multiple
Geom File=g01
Flow File=f01
Subcritical Flow
K Sum by GR= 0
Std Step Tol= 0.01
Critical Tol= 0.01
Num of Std Step Trials= 20
Max Error Tol= 0.3
Flow Tol Ratio= 0.001
Split Flow NTrial= 30
Split Flow Tol= 0.02
Split Flow Ratio= 0.02
Log Output Level= 0
Friction Slope Method= 1
Unsteady Friction Slope Method= 2
Unsteady Bridges Friction Slope Method= 1
Parabolic Critical Depth
Global Vel Dist=  1 , 1 , 1
Global Log Level= 0
CheckData=True
Encroach Param= -1, 0, 0, 0
BEGIN DESCRIPTION:
Multiple Run
END DESCRIPTION:

--- Cottonwood Trib044.f01 (steady flow) ---

Flow Title=Multiple
Number of Profiles=7
Profile Names=10-year,25-year,50-year,1pct_min,100-year,1pct_plu,500-year
River Rch & RM= Cottonwood Trib0,Reach-1,34502
     144     186     218     126     252     502     341
River Rch & RM= Cottonwood Trib0,Reach-1,26502
     217     290     347     205     409     817     578
River Rch & RM= Cottonwood Trib0,Reach-1,22276
     245     329     393     233     464     926     657
River Rch & RM= Cottonwood Trib0,Reach-1,17002
     572     830    1052     659    1316    2625    2091
River Rch & RM= Cottonwood Trib0,Reach-1,5999
     668     980    1249     788    1573    3139    2531
River Rch & RM= Cottonwood Trib0,Reach-1,962
     732    1078    1378     872    1740    3471    2815
Boundary for River Rch & Prof#=Cottonwood Trib0,Reach-1,1
Up Type=0
Dn Type=3
Dn Slope=0.005
Boundary for River Rch & Prof#=Cottonwood Trib0,Reach-1,2
Up Type=0
Dn Type=3
Dn Slope=0.005
Boundary for River Rch & Prof#=Cottonwood Trib0,Reach-1,3
Up Type=0
Dn Type=3
Dn Slope=0.005
Boundary for River Rch & Prof#=Cottonwood Trib0,Reach-1,4
Up Type=0
Dn Type=3
Dn Slope=0.005
Boundary for River Rch & Prof#=Cottonwood Trib0,Reach-1,5
Up Type=0
Dn Type=3
Dn Slope=0.005
Boundary for River Rch & Prof#=Cottonwood Trib0,Reach-1,6
Up Type=0
Dn Type=3
Dn Slope=0.005
Boundary for River Rch & Prof#=Cottonwood Trib0,Reach-1,7
Up Type=0
Dn Type=3
Dn Slope=0.005

--- Cottonwood Trib044.g01 (geometry) ---

Geom Title=Existing Conditions

River Reach=Cottonwood Trib0,Reach-1
Reach XY= 30
      1344205.00      6862388.00      1343448.33      6862396.97
      1342334.92      6863157.37      1342111.84      6864329.25
      1341857.44      6863843.39      1341605.32      6864180.77
      1341198.21      6863796.77      1339365.32      6865276.89
      1338244.88      6865598.34      1337164.99      6866826.75
      1336701.67      6866745.60      1336461.77      6867078.85
      1334108.35      6868030.41      1333698.31      6867947.28
      1332963.95      6868831.33      1333803.39      6869994.02
      1334055.36      6872567.85      1334002.77      6873482.07
      1333512.33      6874187.90      1333553.80      6876327.50
      1333004.80      6877258.06      1333505.04      6878853.34
      1333451.46      6879586.54      1333010.27      6879885.40
      1333254.30      6880027.24      1332904.18      6880472.88
      1333221.48      6881255.23      1333444.41      6881038.88
      1333653.13      6881343.77      1333405.00      6882438.00

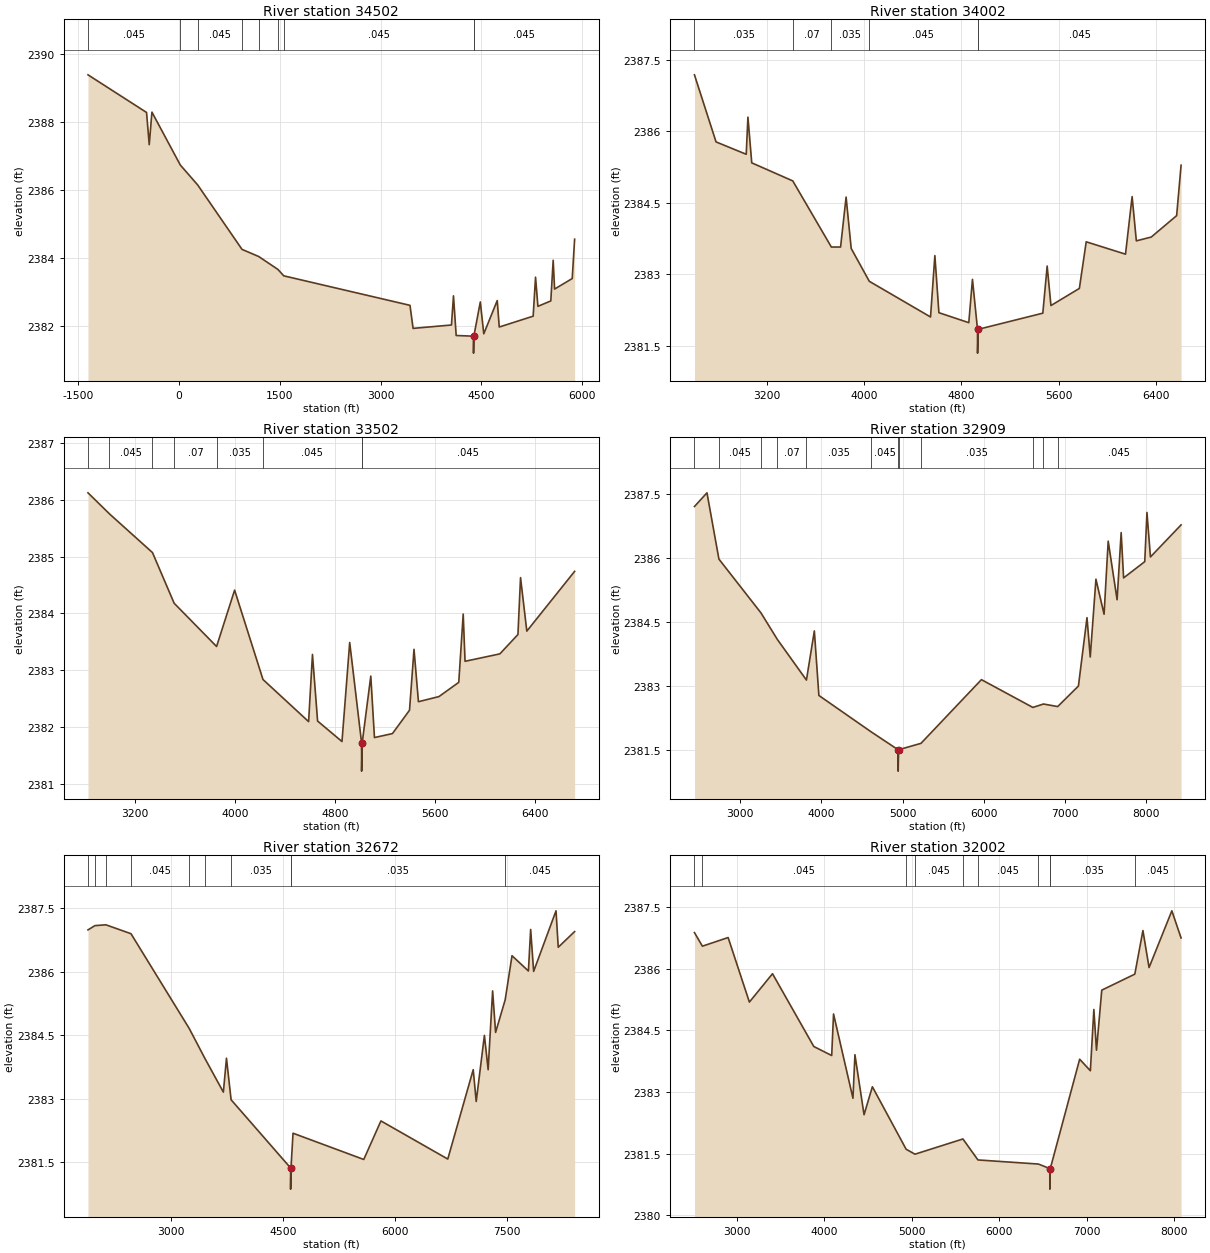
Type RM Length L Ch R = 1,34502,500,500,500
BEGIN DESCRIPTION:
Cottonwood Trib044 66.0
END DESCRIPTION:
XS GIS Cut Line= 3
      1344443.33      6856118.14      1344080.73      6862462.59
      1344654.97      6863137.97
#Sta/Elev= 30
 -1354.8 2389.40  -483.5 2388.29  -443.5 2387.34  -403.4 2388.30    18.7 2386.74
   278.0 2386.15   937.5 2384.25  1185.5 2384.04  1470.8 2383.66  1558.8 2383.47
  3436.7 2382.60  3482.9 2381.92  4053.9 2382.02  4083.9 2382.88  4124.0 2381.71
  4381.9 2381.69  4382.3 2381.19  4386.9 2381.69  4483.3 2382.70  4534.7 2381.76
  4735.0 2382.74  4765.0 2381.96  5269.6 2382.28  5305.0 2383.43  5340.2 2382.57
  5532.1 2382.73  5567.5 2383.93  5588.4 2383.08  5850.8 2383.39  5886.5 2384.55
#Mann=9,-1,0
 -1354.8   0.045       0    18.7    0.07       0   278.0   0.045       0
   937.5    0.07       0  1185.5   0.045       0  1470.8    0.07       0
  1558.8   0.045       0  4381.9   0.045       0  4386.9   0.045       0
Bank Sta=4381.9,4386.9
Exp/Cntr=0.3,0.1

Type RM Length L Ch R = 1,34002,500,500,500
BEGIN DESCRIPTION:
Cottonwood Trib044 65.0
END DESCRIPTION:
XS GIS Cut Line= 4
      1341975.72      6860996.33      1343257.87      6861394.79
      1343699.40      6862346.52      1344404.99      6863787.99
#Sta/Elev= 30
  2608.2 2387.19  2785.5 2385.78  3033.3 2385.52  3047.3 2386.30  3078.7 2385.34
  3415.7 2384.96  3732.6 2383.57  3808.2 2383.57  3853.6 2384.62  3895.5 2383.54
  4044.2 2382.85  4547.1 2382.10  4582.7 2383.39  4615.8 2382.19  4861.3 2381.98
  4891.4 2382.89  4932.9 2381.84  4933.3 2381.34  4938.3 2381.84  5469.3 2382.18
  5505.0 2383.17  5536.1 2382.34  5769.5 2382.70  5825.7 2383.68  6148.4 2383.42
  6202.7 2384.63  6237.5 2383.70  6360.0 2383.78  6568.4 2384.23  6604.9 2385.29
#Mann=6,-1,0
  2608.2   0.035       0  3415.7    0.07       0  3732.6   0.035       0
  4044.2   0.045       0  4932.9   0.045       0  4938.3   0.045       0
Bank Sta=4932.9,4938.3
Exp/Cntr=0.3,0.1

Type RM Length L Ch R = 1,33502,593,593,593
BEGIN DESCRIPTION:
Cottonwood Trib044 64.0
END DESCRIPTION:
XS GIS Cut Line= 4
      1342068.62      6861073.60      1343092.94      6861455.55
      1343333.53      6862509.43      1344343.74      6863893.22
#Sta/Elev= 30
  2825.8 2386.12  2997.5 2385.75  3341.0 2385.07  3514.1 2384.18  3853.0 2383.42
  3997.1 2384.41  4223.7 2382.84  4588.2 2382.10  4619.0 2383.28  4660.0 2382.11
  4854.9 2381.75  4916.5 2383.49  5011.2 2381.73  5011.6 2381.23  5016.6 2381.73
  5085.0 2382.90  5114.3 2381.82  5258.2 2381.89  5394.4 2382.30  5430.2 2383.37
  5465.7 2382.45  5629.7 2382.54  5787.8 2382.79  5823.3 2383.99  5838.0 2383.16
  6116.0 2383.29  6260.5 2383.63  6281.3 2384.63  6331.5 2383.69  6713.3 2384.74
#Mann=8,-1,0
  2825.8   0.035       0  2997.5   0.045       0  3341.0   0.035       0
  3514.1    0.07       0  3853.0   0.035       0  4223.7   0.045       0
  5011.2   0.045       0  5016.6   0.045       0
Bank Sta=5011.2,5016.6
Exp/Cntr=0.3,0.1

Type RM Length L Ch R = 1,32909,237,237,237
BEGIN DESCRIPTION:
Cottonwood Trib044 63.0
END DESCRIPTION:
XS GIS Cut Line= 5
      1341860.32      6860926.05      1343084.26      6861818.40
      1342934.95      6862853.12      1342688.42      6863804.51
      1342485.42      6866254.46
#Sta/Elev= 30
  2433.9 2387.20  2588.2 2387.52  2735.5 2385.97  3254.6 2384.71  3456.4 2384.09
  3814.8 2383.14  3912.4 2384.29  3968.4 2382.78  4612.0 2381.93  4945.7 2381.51
  4946.1 2381.01  4951.2 2381.51  5227.6 2381.66  5972.9 2383.15  6607.3 2382.50
  6737.9 2382.58  6913.3 2382.52  7169.1 2383.00  7274.8 2384.60  7314.9 2383.68
  7385.1 2385.50  7485.5 2384.68  7536.3 2386.39  7646.0 2385.02  7696.2 2386.59
  7726.3 2385.53  7987.2 2385.91  8014.3 2387.06  8057.4 2386.02  8435.2 2386.77
#Mann=12,-1,0
  2433.9   0.035       0  2735.5   0.045       0  3254.6   0.035       0
  3456.4    0.07       0  3814.8   0.035       0  4612.0   0.045       0
  4945.7   0.045       0  4951.2   0.045       0  5227.6   0.035       0
  6607.3   0.045       0  6737.9   0.035       0  6913.3   0.045       0
Bank Sta=4945.7,4951.2
Exp/Cntr=0.3,0.1

Type RM Length L Ch R = 1,32672,670,670,670
BEGIN DESCRIPTION:
Cottonwood Trib044 62.0
END DESCRIPTION:
XS GIS Cut Line= 5
      1341408.93      6860709.04      1342988.77      6861863.54
      1342754.40      6862957.29      1342415.85      6864936.45
      1342415.85      6866377.44
#Sta/Elev= 30
  1886.6 2386.99  1978.7 2387.09  2126.4 2387.11  2462.9 2386.90  3244.7 2384.66
  3452.7 2383.96  3701.5 2383.16  3743.2 2383.96  3805.2 2382.98  4602.7 2381.37
  4603.1 2380.87  4608.2 2381.37  4635.4 2382.19  5583.8 2381.57  5814.0 2382.48
  6710.3 2381.58  7051.4 2383.69  7091.4 2382.94  7201.4 2384.50  7251.4 2383.69
  7311.4 2385.55  7351.4 2384.57  7480.0 2385.34  7571.4 2386.38  7791.4 2386.02
  7821.4 2387.00  7861.4 2386.01  8161.4 2387.44  8191.4 2386.58  8410.8 2386.95
#Mann=10,-1,0
  1886.6   0.035       0  1978.7   0.045       0  2126.4   0.035       0
  2462.9   0.045       0  3244.7   0.035       0  3452.7    0.07       0
  3805.2   0.035       0  4602.7   0.035       0  4608.2   0.035       0
  7480.0   0.045       0
Bank Sta=4602.7,4608.2
Exp/Cntr=0.3,0.1

Type RM Length L Ch R = 1,32002,500,500,500
BEGIN DESCRIPTION:
Cottonwood Trib044 61.0
END DESCRIPTION:
XS GIS Cut Line= 4
      1341469.68      6860873.99      1342270.26      6863222.48
      1342476.51      6863400.12      1342346.43      6866203.41
#Sta/Elev= 30
  2518.8 2386.88  2609.4 2386.55  2903.4 2386.76  3146.4 2385.19  3410.5 2385.88
  3882.1 2384.11  4086.7 2383.89  4107.8 2384.90  4329.7 2382.85  4352.2 2383.91
  4456.4 2382.45  4551.5 2383.13  4937.3 2381.61  5038.4 2381.49  5586.0 2381.86
  5757.7 2381.35  6449.0 2381.25  6578.6 2381.14  6579.1 2380.64  6584.3 2381.14
  6919.8 2383.80  7042.0 2383.52  7082.0 2385.01  7112.1 2384.02  7172.1 2385.48
  7549.9 2385.87  7642.6 2386.93  7712.7 2386.03  7973.0 2387.41  8078.5 2386.75
#Mann=10,-1,0
  2518.8   0.035       0  2609.4   0.045       0  4937.3   0.035       0
  5038.4   0.045       0  5586.0   0.035       0  5757.7   0.045       0
  6449.0   0.035       0  6578.6   0.035       0  6584.3   0.035       0
  7549.9   0.045       0
Bank Sta=6578.6,6584.3
Exp/Cntr=0.3,0.1

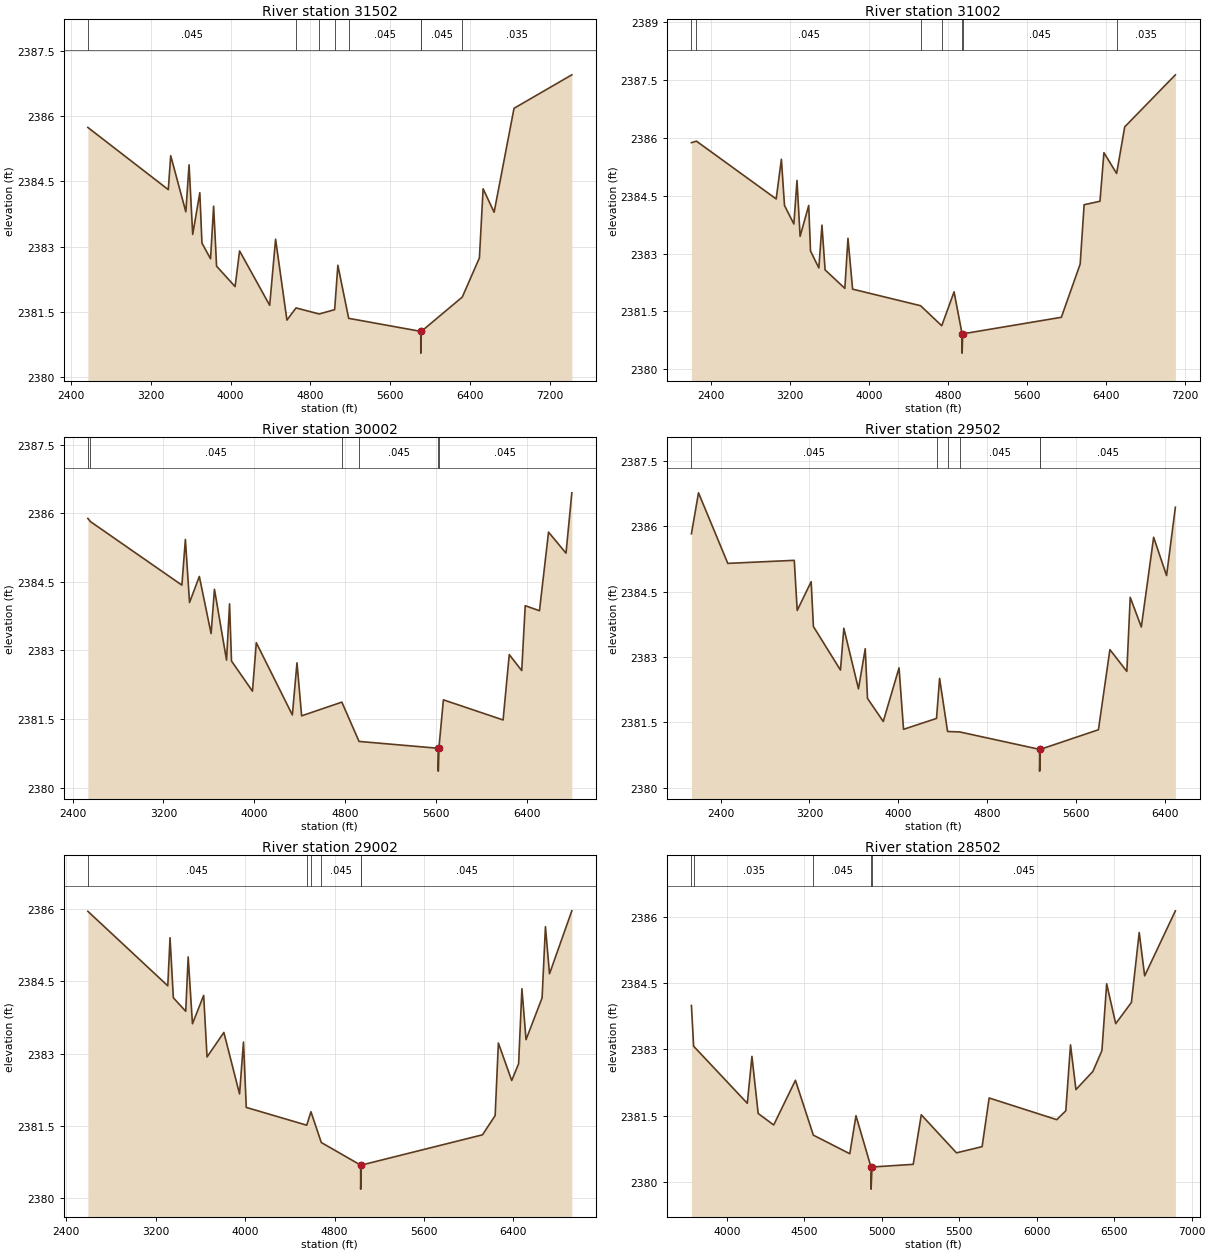
Type RM Length L Ch R = 1,31502,500,500,500
BEGIN DESCRIPTION:
Cottonwood Trib044 60.0
END DESCRIPTION:
XS GIS Cut Line= 5
      1341338.59      6861477.17      1342169.08      6863543.28
      1342340.21      6863653.08      1342398.49      6864337.50
      1342251.01      6866063.92
#Sta/Elev= 30
  2569.9 2385.74  3375.9 2384.31  3400.1 2385.09  3551.6 2383.80  3583.9 2384.88
  3620.5 2383.28  3691.7 2384.24  3713.2 2383.08  3799.4 2382.72  3830.1 2383.93
  3859.7 2382.55  4045.2 2382.08  4090.4 2382.90  4391.9 2381.65  4451.0 2383.17
  4564.7 2381.31  4655.9 2381.59  4887.9 2381.45  5042.8 2381.55  5075.2 2382.57
  5183.4 2381.35  5905.8 2381.05  5906.3 2380.55  5911.6 2381.05  6322.1 2381.84
  6493.5 2382.74  6530.5 2384.33  6640.9 2383.79  6840.3 2386.18  7419.6 2386.95
#Mann=8,-1,0
  2569.9   0.045       0  4655.9   0.035       0  4887.9   0.045       0
  5042.8   0.035       0  5183.4   0.045       0  5905.8   0.045       0
  5911.6   0.045       0  6322.1   0.035       0
Bank Sta=5905.8,5911.6
Exp/Cntr=0.3,0.1

Type RM Length L Ch R = 1,31002,1000,1000,1000
BEGIN DESCRIPTION:
Cottonwood Trib044 59.0
END DESCRIPTION:
XS GIS Cut Line= 4
      1341278.50      6861393.06      1342155.77      6864050.08
      1342320.37      6864311.45      1342198.84      6866099.65
#Sta/Elev= 30
  2201.9 2385.88  2252.5 2385.92  3060.1 2384.42  3112.8 2385.45  3144.4 2384.25
  3239.1 2383.77  3270.7 2384.90  3302.3 2383.45  3389.3 2384.25  3407.6 2383.07
  3491.9 2382.63  3523.5 2383.74  3555.1 2382.58  3755.2 2382.10  3786.7 2383.40
  3833.7 2382.08  4522.0 2381.65  4735.9 2381.13  4860.9 2382.01  4941.9 2380.92
  4942.4 2380.42  4947.7 2380.92  5946.9 2381.35  6137.3 2382.73  6177.4 2384.27
  6337.8 2384.36  6377.9 2385.62  6506.4 2385.08  6588.4 2386.29  7101.2 2387.64
#Mann=7,-1,0
  2201.9   0.035       0  2252.5   0.045       0  4522.0   0.035       0
  4735.9   0.045       0  4941.9   0.045       0  4947.7   0.045       0
  6506.4   0.035       0
Bank Sta=4941.9,4947.7
Exp/Cntr=0.3,0.1

Type RM Length L Ch R = 1,30002,500,500,500
BEGIN DESCRIPTION:
Cottonwood Trib044 58.0
END DESCRIPTION:
XS GIS Cut Line= 3
      1341266.47      6861429.12      1341798.94      6863837.16
      1342205.00      6865587.99
#Sta/Elev= 30
  2533.8 2385.89  2557.0 2385.82  3362.2 2384.43  3392.9 2385.43  3429.5 2384.05
  3515.8 2384.62  3619.4 2383.37  3649.0 2384.34  3755.4 2382.79  3782.1 2384.02
  3799.1 2382.77  3983.9 2382.11  4017.7 2383.17  4335.2 2381.59  4376.1 2382.73
  4417.1 2381.57  4771.2 2381.87  4922.8 2381.01  5620.2 2380.86  5620.7 2380.36
  5626.1 2380.86  5665.8 2381.92  6191.7 2381.48  6246.1 2382.91  6355.9 2382.56
  6386.7 2383.98  6512.3 2383.87  6592.0 2385.59  6746.0 2385.13  6797.3 2386.45
#Mann=6,-1,0
  2533.8   0.035       0  2557.0   0.045       0  4771.2   0.035       0
  4922.8   0.045       0  5620.2   0.045       0  5626.1   0.045       0
Bank Sta=5620.2,5626.1
Exp/Cntr=0.3,0.1

Type RM Length L Ch R = 1,29502,500,500,500
BEGIN DESCRIPTION:
Cottonwood Trib044 57.0
END DESCRIPTION:
XS GIS Cut Line= 3
      1341098.16      6861344.91      1341583.91      6864167.01
      1341855.01      6865638.03
#Sta/Elev= 30
  2136.4 2385.83  2200.4 2386.77  2464.2 2385.15  3062.9 2385.22  3089.4 2384.07
  3215.1 2384.73  3235.4 2383.70  3479.0 2382.70  3509.4 2383.66  3641.3 2382.27
  3702.2 2383.19  3722.5 2382.05  3864.5 2381.52  4006.6 2382.75  4047.2 2381.34
  4344.1 2381.59  4371.9 2382.51  4443.9 2381.29  4552.9 2381.28  5272.5 2380.88
  5273.0 2380.38  5278.6 2380.88  5802.7 2381.33  5906.0 2383.17  6058.5 2382.67
  6089.0 2384.37  6189.0 2383.69  6300.1 2385.75  6416.3 2384.87  6495.8 2386.44
#Mann=6,-1,0
  2136.4   0.045       0  4344.1    0.07       0  4443.9   0.035       0
  4552.9   0.045       0  5272.5   0.045       0  5278.6   0.045       0
Bank Sta=5272.5,5278.6
Exp/Cntr=0.3,0.1

Type RM Length L Ch R = 1,29002,500,500,500
BEGIN DESCRIPTION:
Cottonwood Trib044 56.0
END DESCRIPTION:
XS GIS Cut Line= 4
      1341098.17      6861525.26      1341291.56      6863924.98
      1341192.82      6864064.19      1341939.68      6865648.62
#Sta/Elev= 30
  2592.5 2385.96  3307.5 2384.41  3327.6 2385.41  3357.5 2384.16  3468.1 2383.88
  3489.9 2385.01  3528.3 2383.62  3628.6 2384.21  3658.7 2382.93  3809.2 2383.44
  3949.6 2382.16  3984.7 2383.24  4009.8 2381.88  4550.6 2381.51  4588.3 2381.79
  4680.9 2381.15  5032.8 2380.68  5033.3 2380.18  5038.9 2380.68  6122.9 2381.31
  6236.2 2381.71  6265.1 2383.22  6384.5 2382.44  6446.2 2382.79  6475.7 2384.35
  6512.6 2383.29  6656.3 2384.16  6686.2 2385.64  6722.6 2384.66  6922.3 2385.97
#Mann=6,-1,0
  2592.5   0.045       0  4550.6    0.07       0  4588.3   0.035       0
  4680.9   0.045       0  5032.8   0.045       0  5038.9   0.045       0
Bank Sta=5032.8,5038.9
Exp/Cntr=0.3,0.1

Type RM Length L Ch R = 1,28502,500,500,500
BEGIN DESCRIPTION:
Cottonwood Trib044 55.0
END DESCRIPTION:
XS GIS Cut Line= 3
      1341055.00      6862788.01      1340978.78      6864013.84
      1341955.02      6865638.02
#Sta/Elev= 30
  3771.8 2383.99  3786.2 2383.07  4132.5 2381.78  4162.5 2382.84  4202.6 2381.55
  4302.8 2381.29  4443.1 2382.30  4558.7 2381.06  4793.8 2380.64  4833.8 2381.50
  4930.7 2380.34  4931.2 2379.84  4937.3 2380.34  5203.2 2380.40  5255.2 2381.52
  5482.5 2380.66  5647.7 2380.80  5693.2 2381.90  6129.5 2381.41  6187.8 2381.61
  6218.3 2383.10  6253.3 2382.09  6362.6 2382.50  6420.9 2382.97  6451.6 2384.48
  6509.9 2383.58  6611.3 2384.06  6661.6 2385.64  6696.8 2384.66  6895.0 2386.13
#Mann=5,-1,0
  3771.8   0.045       0  3786.2   0.035       0  4558.7   0.045       0
  4930.7   0.045       0  4937.3   0.045       0
Bank Sta=4930.7,4937.3
Exp/Cntr=0.3,0.1

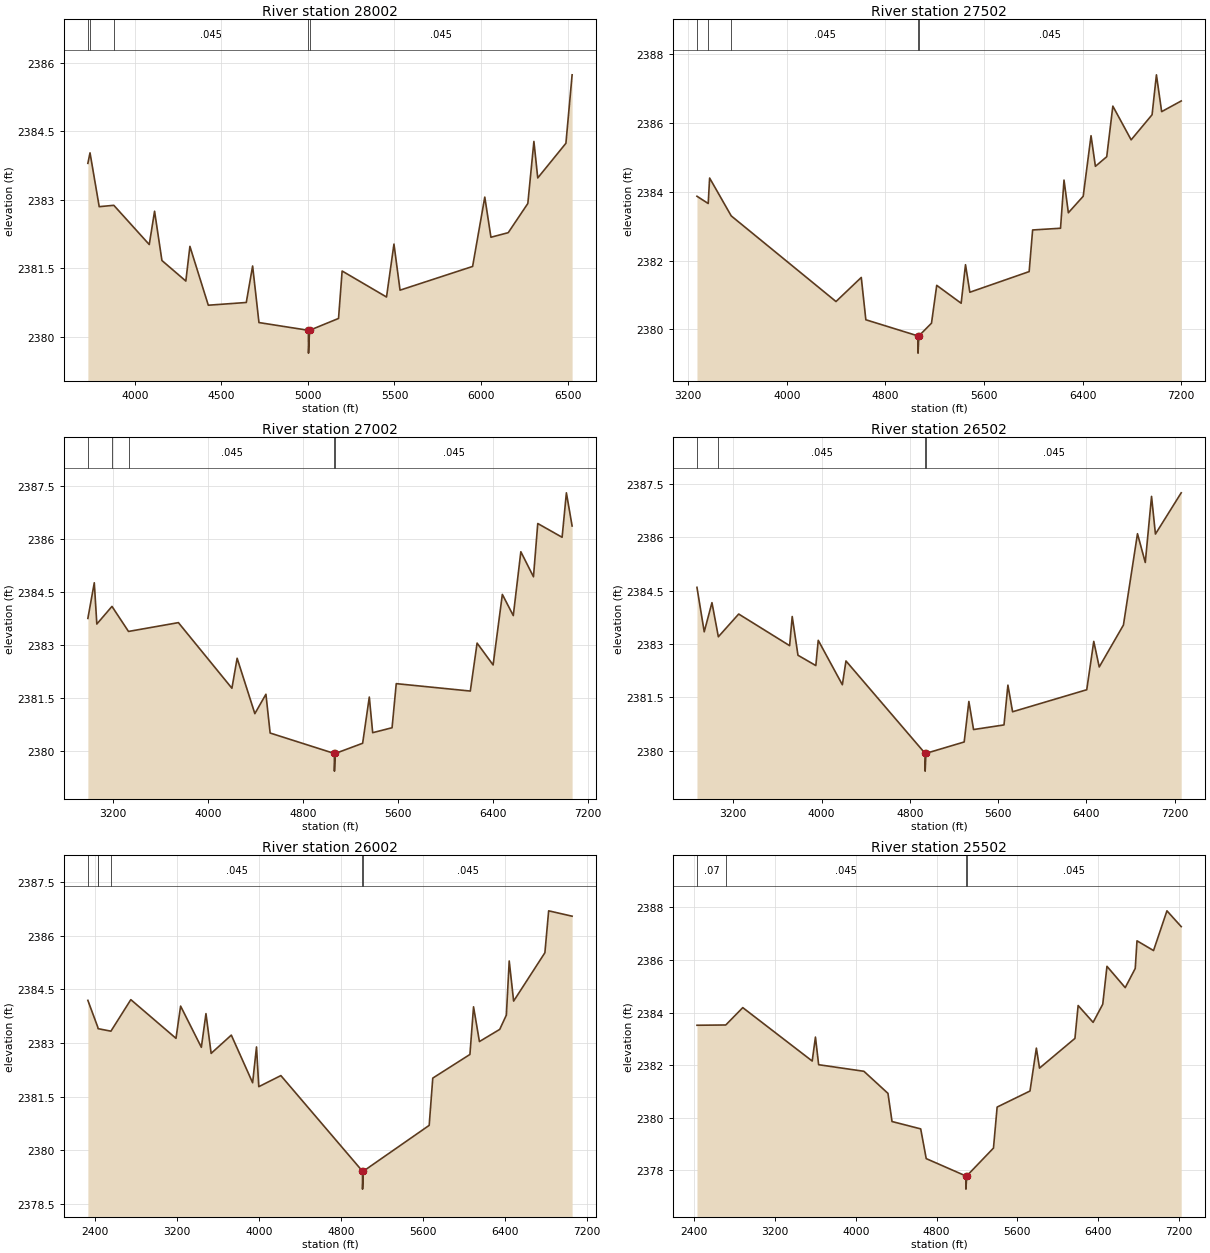
Type RM Length L Ch R = 1,28002,500,500,500
BEGIN DESCRIPTION:
Cottonwood Trib044 54.0
END DESCRIPTION:
XS GIS Cut Line= 3
      1340004.98      6863237.97      1340677.58      6864316.30
      1341655.03      6865488.04
#Sta/Elev= 30
  3729.1 2383.80  3741.5 2384.03  3794.6 2382.85  3878.9 2382.88  4083.6 2382.02
  4114.3 2382.75  4156.8 2381.67  4294.9 2381.22  4318.4 2381.98  4424.6 2380.69
  4644.0 2380.75  4680.6 2381.55  4717.2 2380.31  5002.9 2380.14  5003.4 2379.64
  5009.5 2380.14  5176.8 2380.40  5197.6 2381.44  5454.0 2380.87  5496.9 2382.03
  5532.1 2381.02  5951.2 2381.54  6021.5 2383.06  6057.0 2382.18  6156.9 2382.28
  6270.1 2382.92  6305.2 2384.28  6327.4 2383.48  6490.1 2384.24  6525.9 2385.74
#Mann=5,-1,0
  3729.1   0.045       0  3741.5   0.035       0  3878.9   0.045       0
  5002.9   0.045       0  5009.5   0.045       0
Bank Sta=5002.9,5009.5
Exp/Cntr=0.3,0.1

Type RM Length L Ch R = 1,27502,500,500,500
BEGIN DESCRIPTION:
Cottonwood Trib044 53.0
END DESCRIPTION:
XS GIS Cut Line= 3
      1339595.52      6863064.04      1340308.43      6864638.12
      1341879.56      6866177.54
#Sta/Elev= 30
  3272.0 2383.87  3363.2 2383.66  3374.7 2384.40  3549.8 2383.30  4399.7 2380.81
  4604.7 2381.51  4641.7 2380.28  5064.7 2379.81  5065.2 2379.31  5071.6 2379.81
  5174.3 2380.18  5216.7 2381.28  5414.8 2380.76  5450.1 2381.88  5485.3 2381.08
  5966.3 2381.68  5994.5 2382.89  6220.8 2382.94  6249.1 2384.34  6284.4 2383.39
  6404.7 2383.87  6468.3 2385.63  6503.7 2384.74  6595.6 2385.02  6645.2 2386.49
  6793.6 2385.51  6963.4 2386.24  6998.6 2387.40  7041.1 2386.33  7199.6 2386.64
#Mann=5,-1,0
  3272.0   0.045       0  3363.2   0.035       0  3549.8   0.045       0
  5064.7   0.045       0  5071.6   0.045       0
Bank Sta=5064.7,5071.6
Exp/Cntr=0.3,0.1

Type RM Length L Ch R = 1,27002,500,500,500
BEGIN DESCRIPTION:
Cottonwood Trib044 52.0
END DESCRIPTION:
XS GIS Cut Line= 3
      1339186.77      6862907.70      1339913.89      6864780.39
      1341470.39      6866141.08
#Sta/Elev= 30
  2991.1 2383.75  3045.1 2384.76  3066.5 2383.59  3194.0 2384.09  3333.1 2383.38
  3753.1 2383.63  4203.6 2381.77  4247.6 2382.62  4396.7 2381.05  4489.9 2381.60
  4525.4 2380.50  5066.1 2379.92  5066.6 2379.42  5073.2 2379.92  5304.1 2380.21
  5360.1 2381.52  5388.6 2380.51  5551.8 2380.65  5586.9 2381.90  6210.5 2381.69
  6267.5 2383.05  6402.3 2382.43  6480.1 2384.43  6572.2 2383.83  6635.8 2385.64
  6742.1 2384.93  6778.2 2386.44  6983.2 2386.05  7019.2 2387.31  7067.4 2386.37
#Mann=5,-1,0
  2991.1   0.045       0  3194.0   0.035       0  3333.1   0.045       0
  5066.1   0.045       0  5073.2   0.045       0
Bank Sta=5066.1,5073.2
Exp/Cntr=0.3,0.1

Type RM Length L Ch R = 1,26502,500,500,500
BEGIN DESCRIPTION:
Cottonwood Trib044 51.0
END DESCRIPTION:
XS GIS Cut Line= 3
      1338754.00      6862991.84      1339608.54      6864940.94
      1341205.03      6866538.03
#Sta/Elev= 30
  2871.8 2384.59  2937.6 2383.34  3007.7 2384.16  3065.6 2383.20  3249.8 2383.84
  3711.2 2382.95  3734.6 2383.77  3786.8 2382.68  3948.6 2382.39  3970.4 2383.10
  4188.8 2381.85  4221.5 2382.52  4938.3 2379.92  4938.8 2379.42  4946.0 2379.92
  5292.4 2380.24  5334.8 2381.38  5377.3 2380.59  5653.0 2380.72  5688.4 2381.84
  5730.8 2381.09  6402.6 2381.71  6466.2 2383.07  6515.7 2382.35  6734.9 2383.53
  6862.2 2386.10  6932.9 2385.29  6989.5 2387.15  7024.8 2386.09  7258.2 2387.25
#Mann=4,-1,0
  2871.8   0.035       0  3065.6   0.045       0  4938.3   0.045       0
  4946.0   0.045       0
Bank Sta=4938.3,4946
Exp/Cntr=0.3,0.1

Type RM Length L Ch R = 1,26002,500,500,500
BEGIN DESCRIPTION:
Cottonwood Trib044 50.0
END DESCRIPTION:
XS GIS Cut Line= 3
      1338130.89      6862852.13      1339306.96      6865245.93
      1340612.54      6866833.17
#Sta/Elev= 30
  2332.9 2384.19  2429.9 2383.44  2432.3 2383.40  2557.7 2383.33  2751.7 2384.21
  3192.2 2383.13  3237.2 2384.03  3439.5 2382.88  3484.5 2383.82  3535.0 2382.71
  3731.7 2383.22  3939.6 2381.89  3977.3 2382.89  3999.6 2381.78  4215.0 2382.09
  5011.0 2379.42  5011.5 2378.92  5018.7 2379.42  5661.3 2380.70  5696.4 2382.02
  6058.7 2382.68  6093.9 2384.01  6151.3 2383.04  6349.3 2383.38  6414.0 2383.78
  6441.8 2385.29  6484.9 2384.17  6789.8 2385.52  6826.4 2386.69  7055.2 2386.54
#Mann=6,-1,0
  2332.9   0.035       0  2429.9    0.07       0  2432.3   0.035       0
  2557.7   0.045       0  5011.0   0.045       0  5018.7   0.045       0
Bank Sta=5011,5018.7
Exp/Cntr=0.3,0.1

Type RM Length L Ch R = 1,25502,500,500,500
BEGIN DESCRIPTION:
Cottonwood Trib044 49.0
END DESCRIPTION:
XS GIS Cut Line= 3
      1337975.80      6863093.46      1338899.30      6865493.74
      1339630.17      6867591.25
#Sta/Elev= 30
  2428.2 2383.52  2713.4 2383.53  2881.6 2384.19  3568.8 2382.16  3601.0 2383.07
  3632.6 2382.02  4080.4 2381.77  4318.8 2380.93  4358.9 2379.86  4642.8 2379.58
  4697.4 2378.45  5089.9 2377.79  5090.4 2377.29  5098.0 2377.79  5363.0 2378.85
  5399.4 2380.41  5724.6 2381.02  5787.6 2382.65  5818.7 2381.89  6169.4 2383.02
  6201.1 2384.27  6349.4 2383.63  6444.7 2384.32  6486.5 2385.76  6667.1 2384.95
  6766.3 2385.68  6783.6 2386.73  6947.4 2386.36  7080.1 2387.87  7221.2 2387.27
#Mann=4,-1,0
  2428.2    0.07       0  2713.4   0.045       0  5089.9   0.045       0
  5098.0   0.045       0
Bank Sta=5089.9,5098
Exp/Cntr=0.3,0.1

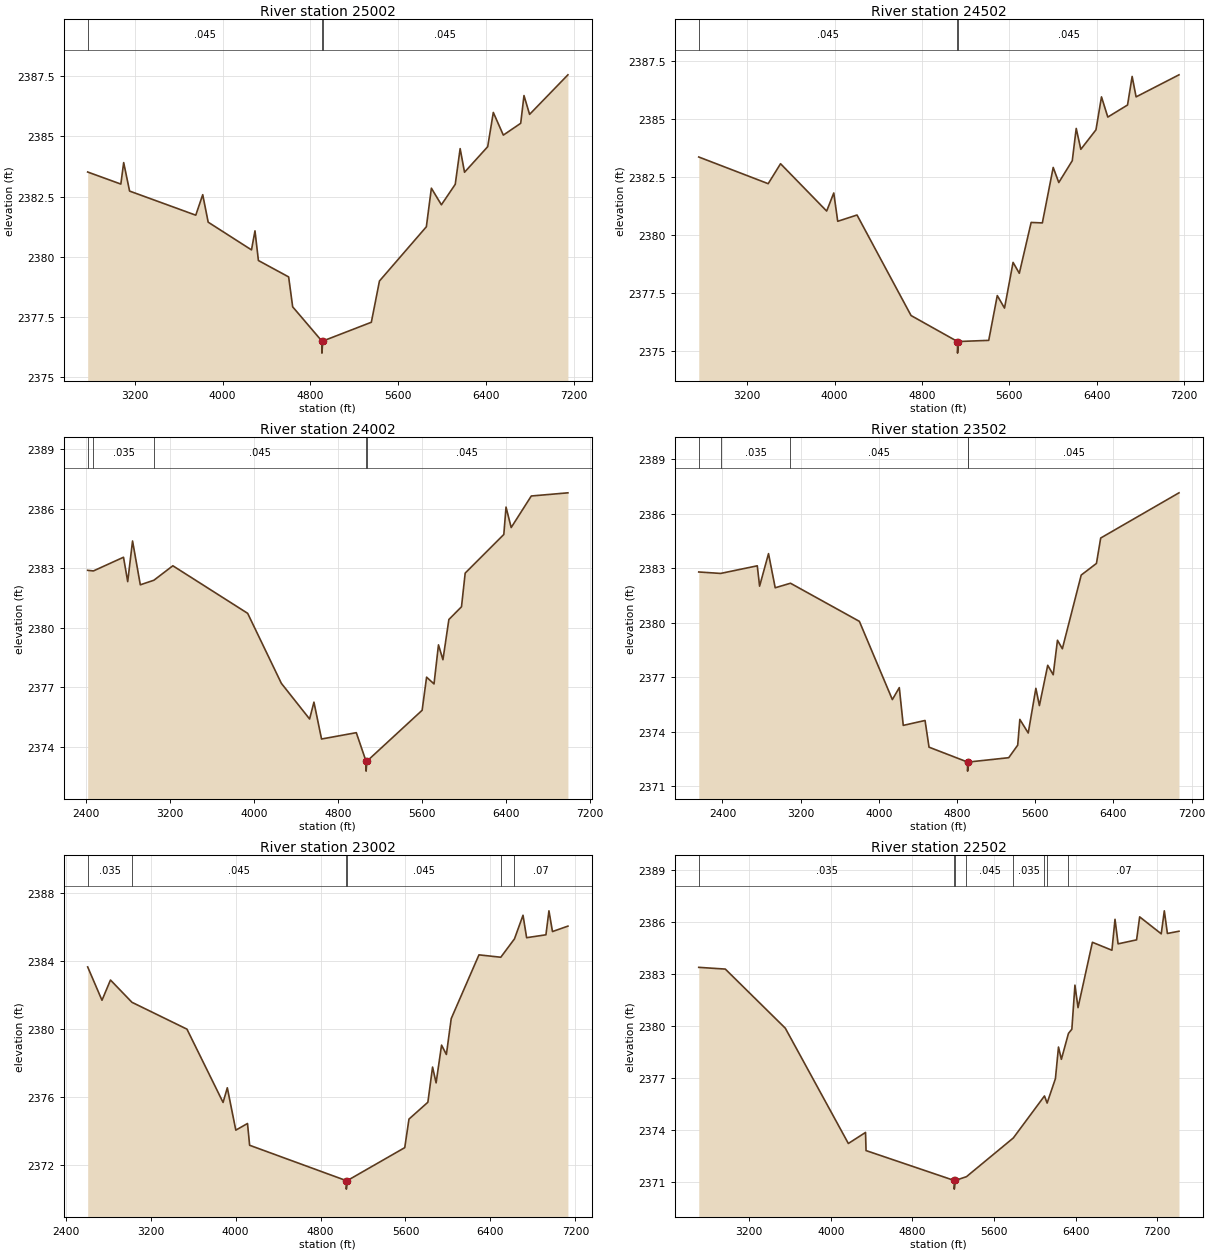
Type RM Length L Ch R = 1,25002,500,500,500
BEGIN DESCRIPTION:
Cottonwood Trib044 48.0
END DESCRIPTION:
XS GIS Cut Line= 3
      1337751.72      6863507.03      1338478.09      6865615.10
      1339389.06      6867557.27
#Sta/Elev= 30
  2770.3 2383.52  3072.4 2383.02  3098.3 2383.91  3152.1 2382.73  3755.0 2381.73
  3818.4 2382.58  3868.1 2381.44  4262.7 2380.29  4294.4 2381.08  4325.7 2379.85
  4601.1 2379.17  4637.8 2377.93  4903.8 2376.51  4904.3 2376.01  4911.9 2376.51
  5354.4 2377.29  5428.4 2379.00  5855.7 2381.25  5901.4 2382.85  5992.6 2382.16
  6118.8 2383.01  6163.4 2384.49  6203.5 2383.51  6414.4 2384.57  6465.6 2385.99
  6556.9 2385.05  6715.2 2385.54  6745.0 2386.69  6796.1 2385.91  7145.2 2387.55
#Mann=3,-1,0
  2770.3   0.045       0  4903.8   0.045       0  4911.9   0.045       0
Bank Sta=4903.8,4911.9
Exp/Cntr=0.3,0.1

Type RM Length L Ch R = 1,24502,500,500,500
BEGIN DESCRIPTION:
Cottonwood Trib044 47.0
END DESCRIPTION:
XS GIS Cut Line= 3
      1337562.15      6863610.48      1338103.49      6865789.54
      1339285.64      6867591.72
#Sta/Elev= 30
  2754.7 2383.37  3391.0 2382.22  3504.3 2383.08  3926.8 2381.04  3991.9 2381.82
  4028.1 2380.60  4205.0 2380.87  4700.0 2376.54  5125.6 2375.42  5126.1 2374.92
  5133.9 2375.42  5411.9 2375.47  5490.2 2377.40  5556.5 2376.86  5634.9 2378.83
  5692.1 2378.36  5800.6 2380.55  5903.2 2380.53  6002.7 2382.92  6053.8 2382.27
  6177.4 2383.21  6213.6 2384.60  6255.8 2383.70  6394.5 2384.54  6445.2 2385.96
  6503.0 2385.09  6683.8 2385.61  6726.0 2386.84  6762.2 2385.96  7155.3 2386.91
#Mann=3,-1,0
  2754.7   0.045       0  5125.6   0.045       0  5133.9   0.045       0
Bank Sta=5125.6,5133.9
Exp/Cntr=0.3,0.1

Type RM Length L Ch R = 1,24002,500,500,500
BEGIN DESCRIPTION:
Cottonwood Trib044 46.0
END DESCRIPTION:
XS GIS Cut Line= 3
      1337131.28      6863644.95      1337799.53      6866143.01
      1339165.00      6867591.73
#Sta/Elev= 30
  2414.1 2382.89  2468.9 2382.86  2755.6 2383.55  2795.6 2382.32  2841.7 2384.37
  2915.8 2382.16  3045.1 2382.39  3225.8 2383.12  3938.9 2380.72  4259.8 2377.19
  4529.0 2375.39  4570.4 2376.24  4642.9 2374.38  4974.1 2374.70  5067.0 2373.26
  5067.5 2372.76  5075.3 2373.26  5601.5 2375.83  5644.0 2377.50  5714.8 2377.16
  5757.3 2379.13  5799.8 2378.38  5856.4 2380.41  5976.6 2381.05  6011.8 2382.75
  6380.0 2384.70  6401.0 2386.08  6450.3 2385.05  6641.7 2386.64  6990.8 2386.80
#Mann=5,-1,0
  2414.1    0.07       0  2468.9   0.035       0  3045.1   0.045       0
  5067.0   0.045       0  5075.3   0.045       0
Bank Sta=5067,5075.3
Exp/Cntr=0.3,0.1

Type RM Length L Ch R = 1,23502,500,500,500
BEGIN DESCRIPTION:
Cottonwood Trib044 45.0
END DESCRIPTION:
XS GIS Cut Line= 3
      1337062.34      6863713.89      1337524.80      6866518.52
      1339165.00      6867781.31
#Sta/Elev= 30
  2157.5 2382.79  2381.3 2382.71  2756.2 2383.13  2779.9 2382.01  2871.1 2383.80
  2939.6 2381.92  3095.8 2382.17  3800.6 2380.07  4138.0 2375.76  4208.9 2376.42
  4249.5 2374.34  4472.4 2374.61  4513.0 2373.14  4907.0 2372.32  4907.5 2371.82
  4915.3 2372.32  5328.4 2372.56  5420.1 2373.25  5442.0 2374.67  5527.9 2373.92
  5606.0 2376.38  5642.1 2375.43  5727.3 2377.65  5783.4 2377.13  5826.9 2379.03
  5876.8 2378.56  6069.8 2382.62  6225.6 2383.26  6269.1 2384.66  7070.0 2387.15
#Mann=5,-1,0
  2157.5    0.07       0  2381.3   0.035       0  3095.8   0.045       0
  4907.0   0.045       0  4915.3   0.045       0
Bank Sta=4907,4915.3
Exp/Cntr=0.3,0.1

Type RM Length L Ch R = 1,23002,500,500,500
BEGIN DESCRIPTION:
Cottonwood Trib044 44.0
END DESCRIPTION:
XS GIS Cut Line= 3
      1337172.69      6864433.34      1337166.80      6866825.44
      1338078.94      6868749.36
#Sta/Elev= 30
  2607.9 2383.65  2742.6 2381.69  2822.6 2382.88  3024.6 2381.57  3542.6 2379.99
  3882.6 2375.68  3922.6 2376.54  4002.6 2374.05  4112.6 2374.44  4132.6 2373.16
  5042.6 2371.08  5043.1 2370.58  5051.7 2371.08  5593.0 2373.02  5632.9 2374.70
  5810.7 2375.69  5855.0 2377.76  5888.2 2376.83  5939.6 2379.05  5985.1 2378.50
  6030.5 2380.61  6291.7 2384.36  6497.3 2384.22  6626.0 2385.30  6706.6 2386.69
  6740.4 2385.37  6922.3 2385.54  6950.6 2386.95  6983.8 2385.73  7129.2 2386.05
#Mann=6,-1,0
  2607.9   0.035       0  3024.6   0.045       0  5042.6   0.045       0
  5051.7   0.045       0  6497.3   0.035       0  6626.0    0.07       0
Bank Sta=5042.6,5051.7
Exp/Cntr=0.3,0.1

Type RM Length L Ch R = 1,22502,226,226,226
BEGIN DESCRIPTION:
Cottonwood Trib044 43.0
END DESCRIPTION:
XS GIS Cut Line= 3
      1337148.51      6864541.17      1336771.89      6866804.75
      1336481.72      6869200.74
#Sta/Elev= 30
  2705.3 2383.39  2965.7 2383.29  3554.0 2379.87  4172.0 2373.20  4340.3 2373.84
  4345.4 2372.79  5210.1 2371.06  5210.6 2370.56  5219.5 2371.06  5329.9 2371.28
  5789.4 2373.52  6094.8 2375.95  6120.7 2375.54  6202.0 2376.95  6232.2 2378.78
  6260.4 2378.07  6330.0 2379.57  6363.1 2379.81  6393.4 2382.36  6423.6 2381.06
  6564.6 2384.84  6756.0 2384.38  6786.2 2386.17  6816.4 2384.75  6997.7 2384.98
  7028.0 2386.31  7239.5 2385.33  7269.7 2386.66  7299.9 2385.35  7413.5 2385.48
#Mann=8,-1,0
  2705.3   0.035       0  5210.1   0.035       0  5219.5   0.035       0
  5329.9   0.045       0  5789.4   0.035       0  6094.8   0.045       0
  6120.7   0.035       0  6330.0    0.07       0
Bank Sta=5210.1,5219.5
Exp/Cntr=0.3,0.1

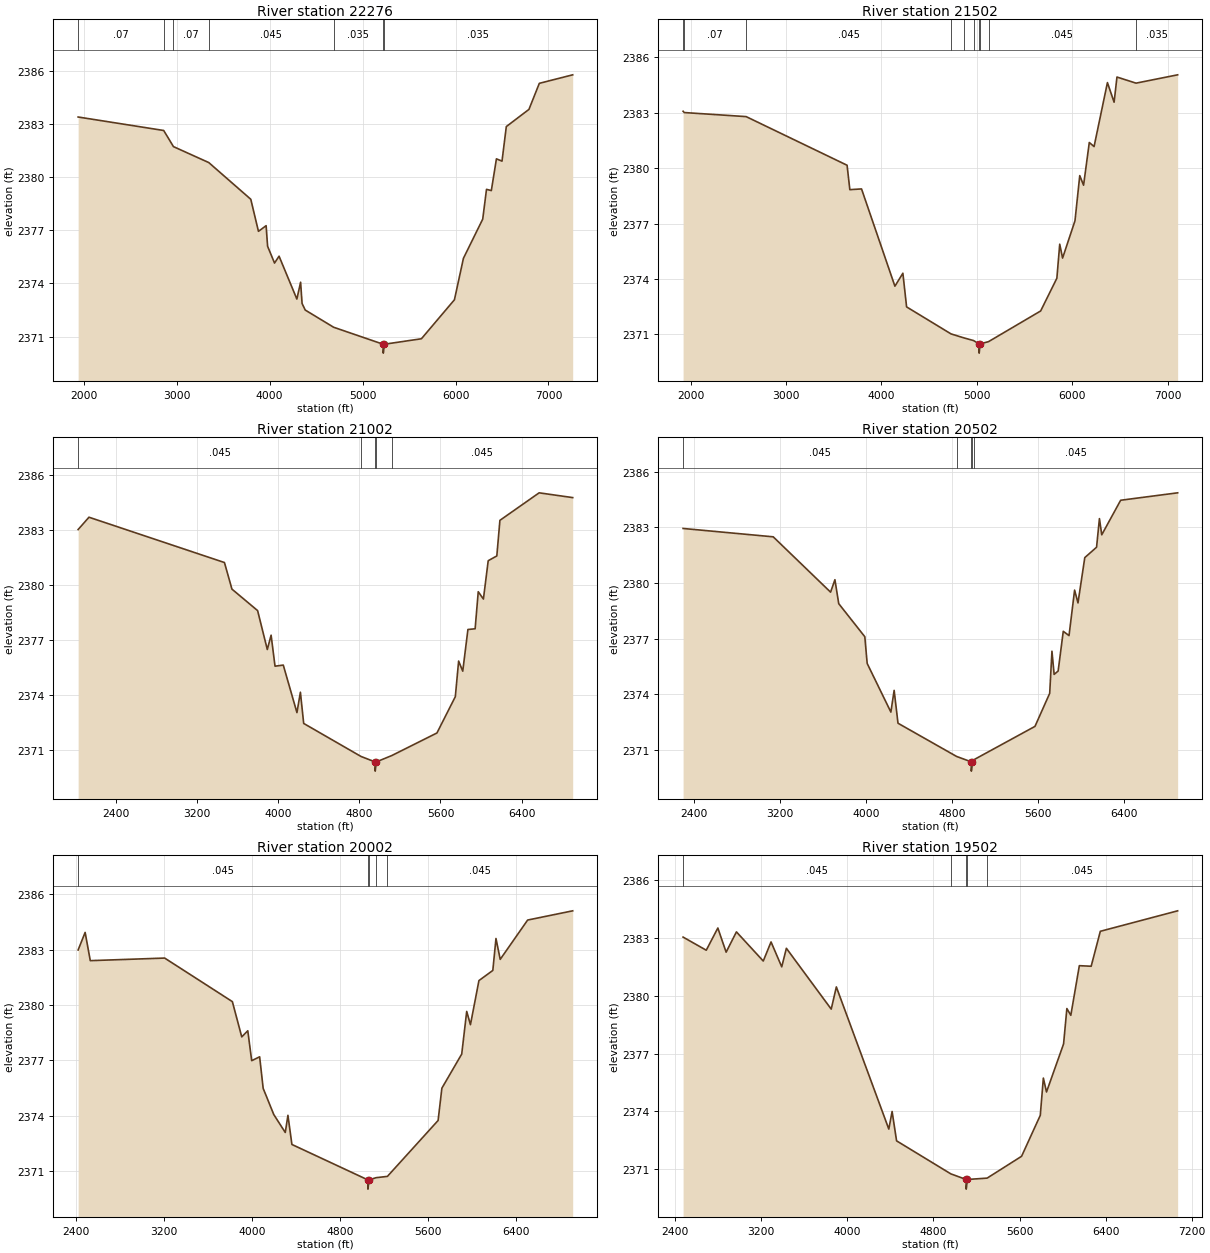
Type RM Length L Ch R = 1,22276,774,774,774
BEGIN DESCRIPTION:
Cottonwood Trib044 42.0
END DESCRIPTION:
XS GIS Cut Line= 4
      1336151.85      6863836.14      1336645.16      6865813.76
      1336603.49      6866834.59      1336221.31      6869061.84
#Sta/Elev= 30
  1940.8 2383.39  2861.2 2382.63  2966.0 2381.72  3346.0 2380.82  3797.9 2378.75
  3880.3 2376.94  3962.8 2377.26  3978.6 2376.10  4053.3 2375.15  4101.9 2375.54
  4293.5 2373.12  4333.6 2374.07  4349.6 2372.87  4383.6 2372.50  4689.0 2371.53
  5222.5 2370.57  5223.0 2370.07  5232.3 2370.57  5633.2 2370.88  5988.3 2373.08
  6085.2 2375.42  6292.7 2377.63  6333.3 2379.31  6385.2 2379.24  6440.1 2381.03
  6500.1 2380.90  6546.4 2382.85  6789.9 2383.82  6901.5 2385.29  7260.5 2385.77
#Mann=7,-1,0
  1940.8    0.07       0  2861.2   0.035       0  2966.0    0.07       0
  3346.0   0.045       0  4689.0   0.035       0  5222.5   0.035       0
  5232.3   0.035       0
Bank Sta=5222.5,5232.3
Exp/Cntr=0.3,0.1

Type RM Length L Ch R = 1,21502,500,500,500
BEGIN DESCRIPTION:
Cottonwood Trib044 41.0
END DESCRIPTION:
XS GIS Cut Line= 3
      1334884.49      6864304.90      1336113.54      6867129.05
      1336151.84      6869234.20
#Sta/Elev= 30
  1920.0 2383.07  1932.6 2383.00  2581.3 2382.78  3639.5 2380.15  3668.4 2378.83
  3791.0 2378.87  4140.9 2373.61  4224.5 2374.31  4263.5 2372.49  4729.2 2371.03
  4860.6 2370.82  4965.1 2370.67  5024.0 2370.49  5024.5 2369.99  5033.9 2370.49
  5122.3 2370.61  5669.1 2372.27  5839.1 2374.04  5869.1 2375.88  5899.1 2375.13
  6029.1 2377.15  6079.1 2379.59  6119.1 2379.07  6179.1 2381.38  6229.2 2381.16
  6369.2 2384.62  6439.2 2383.56  6469.2 2384.92  6669.1 2384.59  7105.5 2385.04
#Mann=10,-1,0
  1920.0   0.035       0  1932.6    0.07       0  2581.3   0.045       0
  4729.2   0.035       0  4860.6   0.045       0  4965.1   0.035       0
  5024.0   0.035       0  5033.9   0.035       0  5122.3   0.045       0
  6669.1   0.035       0
Bank Sta=5024,5033.9
Exp/Cntr=0.3,0.1

Type RM Length L Ch R = 1,21002,500,500,500
BEGIN DESCRIPTION:
Cottonwood Trib044 40.0
END DESCRIPTION:
XS GIS Cut Line= 3
      1334320.27      6864669.51      1335680.60      6867312.70
      1336034.64      6869183.19
#Sta/Elev= 30
  2027.3 2383.03  2134.2 2383.70  3469.9 2381.23  3543.9 2379.78  3796.9 2378.61
  3892.5 2376.49  3929.9 2377.27  3968.6 2375.58  4050.0 2375.64  4184.7 2373.05
  4218.7 2374.16  4251.2 2372.46  4816.2 2370.66  4955.9 2370.36  4956.4 2369.86
  4966.0 2370.36  5120.3 2370.71  5565.2 2371.94  5746.4 2373.92  5778.9 2375.86
  5819.6 2375.31  5870.5 2377.58  5941.7 2377.62  5972.3 2379.64  6023.3 2379.24
  6070.6 2381.33  6155.5 2381.59  6186.0 2383.53  6572.7 2385.03  6903.7 2384.77
#Mann=5,-1,0
  2027.3   0.045       0  4816.2   0.035       0  4955.9   0.035       0
  4966.0   0.035       0  5120.3   0.045       0
Bank Sta=4955.9,4966
Exp/Cntr=0.3,0.1

Type RM Length L Ch R = 1,20502,500,500,500
BEGIN DESCRIPTION:
Cottonwood Trib044 39.0
END DESCRIPTION:
XS GIS Cut Line= 3
      1334168.37      6864995.06      1335297.75      6867445.64
      1335882.76      6869248.50
#Sta/Elev= 30
  2301.7 2382.94  3139.0 2382.49  3671.6 2379.51  3712.0 2380.18  3747.4 2378.89
  3989.6 2377.11  4011.6 2375.67  4231.8 2373.05  4262.0 2374.22  4297.9 2372.45
  4842.3 2370.66  4978.6 2370.37  4979.1 2369.87  4988.9 2370.37  5004.7 2370.49
  5570.2 2372.28  5706.9 2374.06  5727.9 2376.33  5748.1 2375.08  5785.3 2375.26
  5833.0 2377.40  5886.5 2377.17  5938.2 2379.62  5969.7 2378.93  6032.8 2381.37
  6142.2 2381.93  6168.9 2383.47  6190.5 2382.60  6366.0 2384.46  6895.4 2384.86
#Mann=5,-1,0
  2301.7   0.045       0  4842.3   0.035       0  4978.6   0.035       0
  4988.9   0.035       0  5004.7   0.045       0
Bank Sta=4978.6,4988.9
Exp/Cntr=0.3,0.1

Type RM Length L Ch R = 1,20002,500,500,500
BEGIN DESCRIPTION:
Cottonwood Trib044 38.0
END DESCRIPTION:
XS GIS Cut Line= 3
      1333951.34      6865168.62      1334866.68      6867576.62
      1335752.57      6869270.21
#Sta/Elev= 30
  2423.9 2382.98  2487.4 2383.93  2534.1 2382.40  3208.9 2382.54  3823.3 2380.18
  3908.3 2378.27  3963.2 2378.60  3998.7 2376.98  4070.7 2377.19  4102.8 2375.48
  4199.1 2374.06  4303.3 2373.09  4327.5 2374.02  4363.5 2372.44  5052.8 2370.52
  5053.3 2370.02  5063.2 2370.52  5127.5 2370.64  5230.1 2370.71  5690.0 2373.74
  5724.3 2375.49  5904.4 2377.34  5949.5 2379.65  5983.5 2378.93  6060.5 2381.32
  6186.5 2381.87  6215.1 2383.60  6253.6 2382.47  6502.5 2384.60  6911.3 2385.10
#Mann=5,-1,0
  2423.9   0.045       0  5052.8   0.045       0  5063.2   0.045       0
  5127.5   0.035       0  5230.1   0.045       0
Bank Sta=5052.8,5063.2
Exp/Cntr=0.3,0.1

Type RM Length L Ch R = 1,19502,500,500,500
BEGIN DESCRIPTION:
Cottonwood Trib044 37.0
END DESCRIPTION:
XS GIS Cut Line= 3
      1333560.73      6865298.88      1334513.08      6867639.13
      1335600.33      6869399.89
#Sta/Elev= 30
  2473.4 2383.03  2688.7 2382.35  2796.3 2383.50  2873.4 2382.25  2969.1 2383.30
  3218.5 2381.79  3290.7 2382.78  3390.1 2381.49  3433.3 2382.45  3850.0 2379.30
  3897.6 2380.45  4385.2 2373.09  4415.8 2374.00  4457.4 2372.48  4961.5 2370.77
  5104.0 2370.48  5104.5 2369.98  5114.7 2370.48  5298.9 2370.55  5619.0 2371.68
  5792.8 2373.80  5821.4 2375.73  5850.7 2375.01  6009.4 2377.50  6039.9 2379.33
  6076.6 2378.98  6155.8 2381.55  6265.7 2381.52  6350.8 2383.33  7069.4 2384.39
#Mann=5,-1,0
  2473.4   0.045       0  4961.5   0.035       0  5104.0   0.035       0
  5114.7   0.035       0  5298.9   0.045       0
Bank Sta=5104,5114.7
Exp/Cntr=0.3,0.1