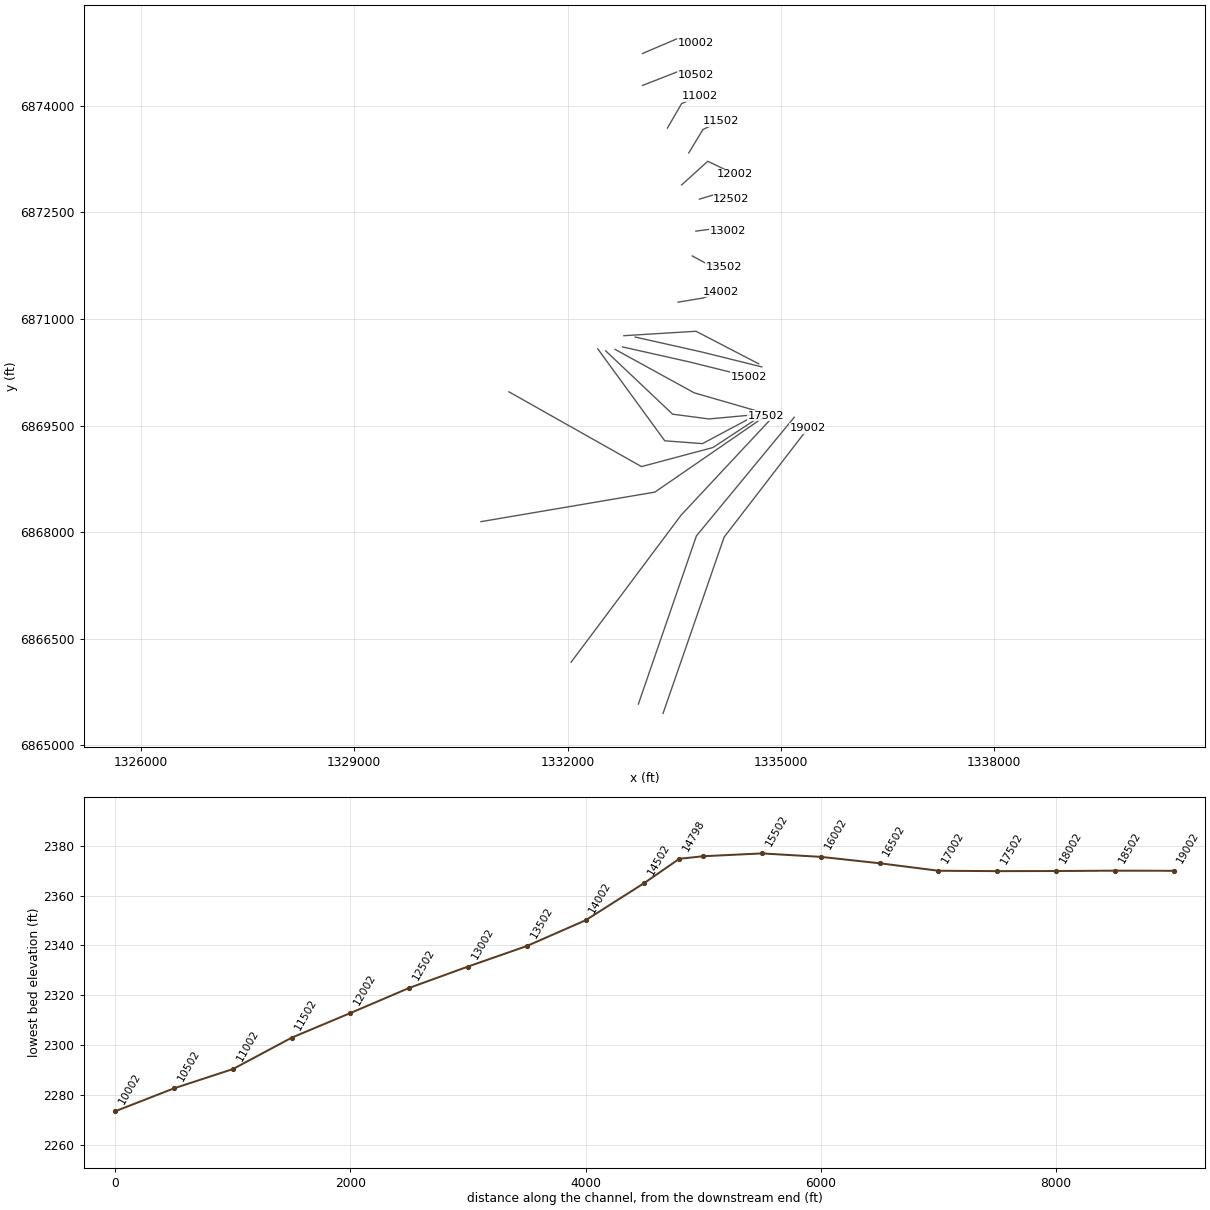
HEC-RAS study Cottonwood Trib044.prj: Cottonwood Trib044 Base Level Engineering

--- Cottonwood Trib044.g01 (geometry) --- (continued)

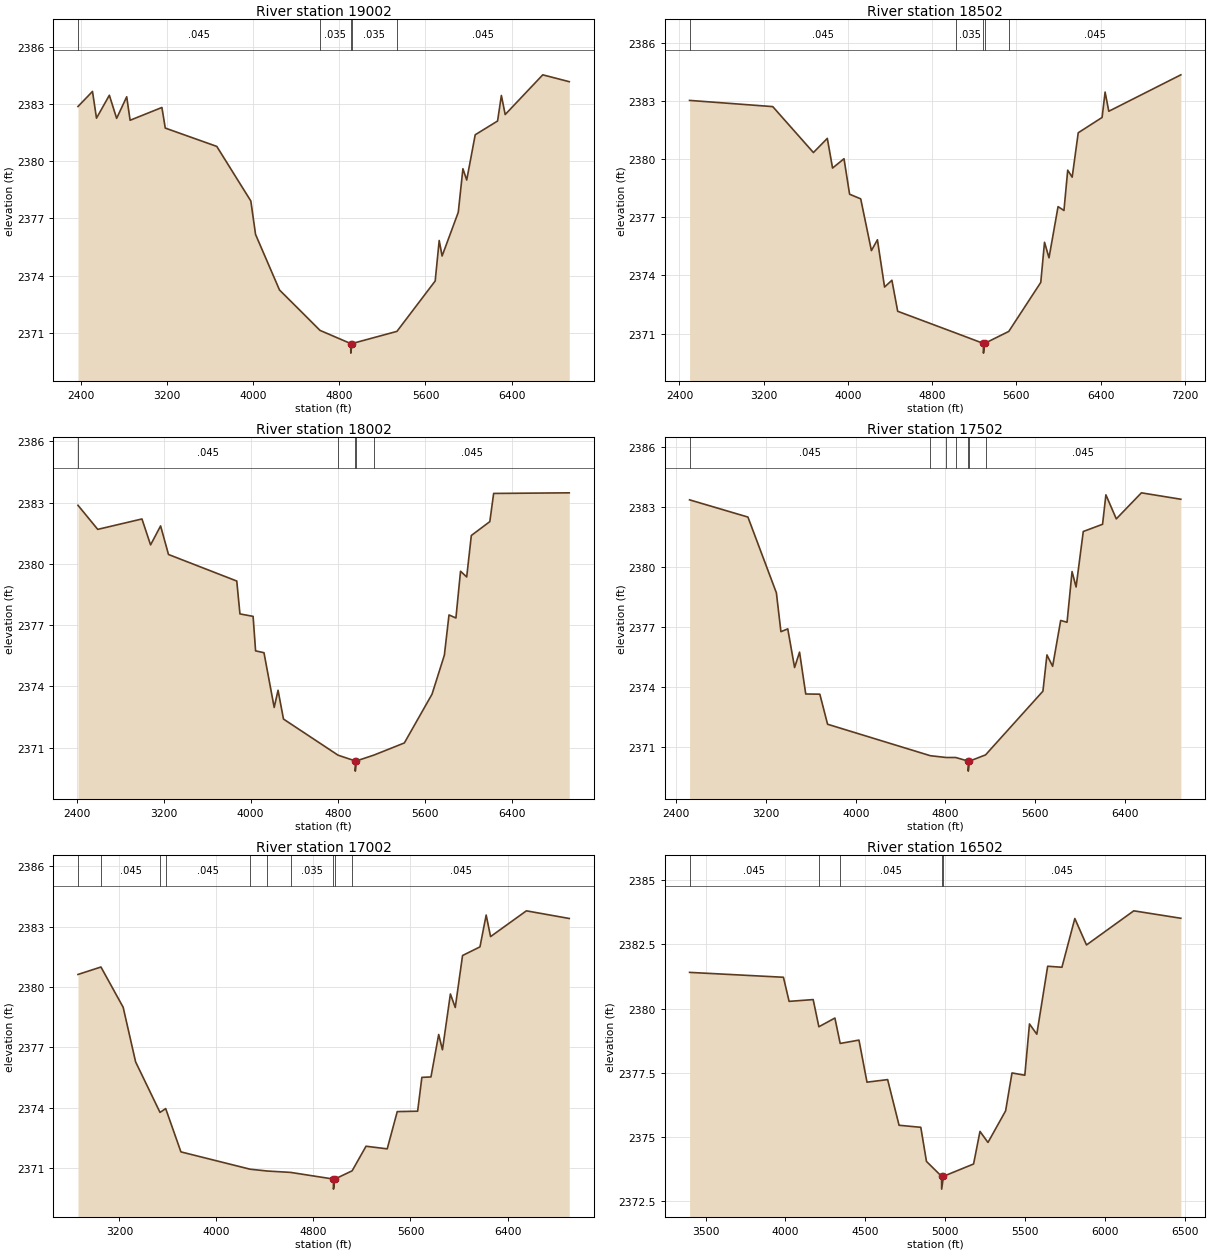
Type RM Length L Ch R = 1,19002,500,500,500
BEGIN DESCRIPTION:
Cottonwood Trib044 36.0
END DESCRIPTION:
XS GIS Cut Line= 3
      1333343.70      6865450.75      1334202.67      6867930.92
      1335382.66      6869464.24
#Sta/Elev= 30
  2375.3 2382.86  2510.0 2383.65  2547.2 2382.25  2666.5 2383.45  2734.1 2382.24
  2827.5 2383.37  2859.2 2382.14  3154.3 2382.81  3185.5 2381.73  3663.5 2380.77
  3979.6 2377.91  4023.3 2376.16  4245.5 2373.25  4622.0 2371.13  4906.9 2370.44
  4907.4 2369.94  4917.7 2370.44  5335.6 2371.08  5690.5 2373.72  5727.7 2375.84
  5754.8 2375.03  5904.8 2377.32  5947.8 2379.60  5983.1 2379.01  6062.0 2381.38
  6269.5 2382.10  6304.8 2383.44  6340.2 2382.44  6689.0 2384.52  6934.8 2384.16
#Mann=5,-1,0
  2375.3   0.045       0  4622.0   0.035       0  4906.9   0.035       0
  4917.7   0.035       0  5335.6   0.045       0
Bank Sta=4906.9,4917.7
Exp/Cntr=0.3,0.1

Type RM Length L Ch R = 1,18502,500,500,500
BEGIN DESCRIPTION:
Cottonwood Trib044 35.0
END DESCRIPTION:
XS GIS Cut Line= 3
      1332996.46      6865580.92      1333812.81      6867948.43
      1335188.34      6869617.44
#Sta/Elev= 30
  2495.7 2383.03  3285.9 2382.71  3672.2 2380.34  3804.3 2381.07  3854.1 2379.54
  3962.9 2380.02  4015.8 2378.19  4121.6 2377.95  4223.3 2375.28  4280.3 2375.84
  4348.1 2373.40  4417.8 2373.75  4472.9 2372.15  5023.8 2371.03  5287.2 2370.49
  5287.7 2369.99  5298.1 2370.49  5528.1 2371.11  5832.1 2373.64  5867.7 2375.71
  5910.3 2374.91  5996.3 2377.55  6052.3 2377.35  6088.0 2379.43  6130.5 2379.07
  6187.9 2381.36  6414.5 2382.15  6443.2 2383.46  6478.4 2382.47  7162.8 2384.35
#Mann=5,-1,0
  2495.7   0.045       0  5023.8   0.035       0  5287.2   0.045       0
  5298.1   0.035       0  5528.1   0.045       0
Bank Sta=5287.2,5298.1
Exp/Cntr=0.3,0.1

Type RM Length L Ch R = 1,18002,500,500,500
BEGIN DESCRIPTION:
Cottonwood Trib044 34.0
END DESCRIPTION:
XS GIS Cut Line= 3
      1332049.55      6866169.90      1333598.35      6868241.67
      1334914.17      6869650.85
#Sta/Elev= 30
  2413.3 2382.87  2594.9 2381.69  3001.3 2382.20  3080.5 2380.93  3172.5 2381.86
  3245.2 2380.46  3872.5 2379.16  3901.7 2377.55  4022.6 2377.43  4045.5 2375.74
  4122.6 2375.65  4216.4 2372.97  4251.9 2373.81  4301.9 2372.40  4803.8 2370.63
  4961.1 2370.35  4961.6 2369.85  4972.5 2370.35  5134.9 2370.64  5412.5 2371.23
  5667.0 2373.62  5780.3 2375.53  5822.8 2377.50  5886.4 2377.35  5928.9 2379.64
  5985.5 2379.36  6028.0 2381.39  6198.0 2382.07  6233.2 2383.45  6928.0 2383.48
#Mann=5,-1,0
  2413.3   0.045       0  4803.8   0.035       0  4961.1   0.035       0
  4972.5   0.035       0  5134.9   0.045       0
Bank Sta=4961.1,4972.5
Exp/Cntr=0.3,0.1

Type RM Length L Ch R = 1,17502,500,500,500
BEGIN DESCRIPTION:
Cottonwood Trib044 33.0
END DESCRIPTION:
XS GIS Cut Line= 3
      1330782.16      6868149.09      1333228.33      6868564.59
      1334791.29      6869641.23
#Sta/Elev= 30
  2518.8 2383.34  3039.0 2382.48  3292.6 2378.70  3333.1 2376.76  3394.0 2376.90
  3454.9 2374.97  3499.1 2375.74  3554.3 2373.65  3679.9 2373.64  3749.0 2372.14
  4664.5 2370.57  4806.5 2370.48  4891.4 2370.48  5002.4 2370.30  5002.9 2369.80
  5013.9 2370.30  5157.0 2370.61  5668.5 2373.79  5704.3 2375.60  5755.0 2375.03
  5826.7 2377.32  5883.5 2377.23  5928.2 2379.76  5964.0 2378.99  6028.1 2381.76
  6200.0 2382.12  6229.8 2383.59  6322.5 2382.39  6546.3 2383.69  6897.9 2383.37
#Mann=7,-1,0
  2518.8   0.045       0  4664.5   0.035       0  4806.5   0.045       0
  4891.4   0.035       0  5002.4   0.035       0  5013.9   0.035       0
  5157.0   0.045       0
Bank Sta=5002.4,5013.9
Exp/Cntr=0.3,0.1

Type RM Length L Ch R = 1,17002,500,500,500
BEGIN DESCRIPTION:
Cottonwood Trib044 32.0
END DESCRIPTION:
XS GIS Cut Line= 4
      1331175.91      6869976.34      1333040.62      6868923.72
      1334043.93      6869191.63      1334771.53      6869669.77
#Sta/Elev= 30
  2858.7 2380.62  3048.1 2380.99  3231.3 2378.99  3333.8 2376.28  3535.1 2373.77
  3581.8 2373.96  3707.4 2371.81  4277.5 2370.95  4417.3 2370.86  4612.1 2370.79
  4964.7 2370.46  4965.2 2369.96  4976.5 2370.46  5119.0 2370.87  5233.6 2372.09
  5408.2 2371.96  5491.0 2373.81  5659.0 2373.83  5693.9 2375.51  5768.9 2375.53
  5832.6 2377.64  5863.6 2376.88  5929.2 2379.65  5969.3 2378.98  6029.2 2381.56
  6172.9 2381.99  6224.1 2383.57  6260.3 2382.50  6555.5 2383.78  6909.1 2383.40
#Mann=10,-1,0
  2858.7   0.035       0  3048.1   0.045       0  3535.1   0.035       0
  3581.8   0.045       0  4277.5   0.035       0  4417.3   0.045       0
  4612.1   0.035       0  4964.7   0.035       0  4976.5   0.035       0
  5119.0   0.045       0
Bank Sta=4964.7,4976.5
Exp/Cntr=0.3,0.1

Type RM Length L Ch R = 1,16502,500,500,500
BEGIN DESCRIPTION:
Cottonwood Trib044 31.0
END DESCRIPTION:
XS GIS Cut Line= 4
      1332425.87      6870580.53      1333367.74      6869286.75
      1333898.10      6869247.19      1334730.74      6869691.27
#Sta/Elev= 30
  3399.7 2381.41  3987.4 2381.22  4022.9 2380.28  4173.6 2380.35  4209.2 2379.29
  4309.6 2379.63  4342.6 2378.64  4460.3 2378.77  4510.5 2377.13  4639.7 2377.23
  4711.4 2375.45  4847.4 2375.37  4882.9 2374.04  4977.4 2373.46  4977.9 2372.96
  4989.3 2373.46  5177.8 2373.94  5217.9 2375.21  5268.0 2374.78  5378.3 2376.01
  5418.4 2377.49  5498.6 2377.40  5527.8 2379.40  5573.7 2379.00  5641.7 2381.65
  5731.0 2381.61  5811.7 2383.51  5884.8 2382.48  6180.8 2383.81  6475.5 2383.52
#Mann=5,-1,0
  3399.7   0.045       0  4209.2   0.035       0  4342.6   0.045       0
  4977.4   0.045       0  4989.3   0.045       0
Bank Sta=4977.4,4989.3
Exp/Cntr=0.3,0.1

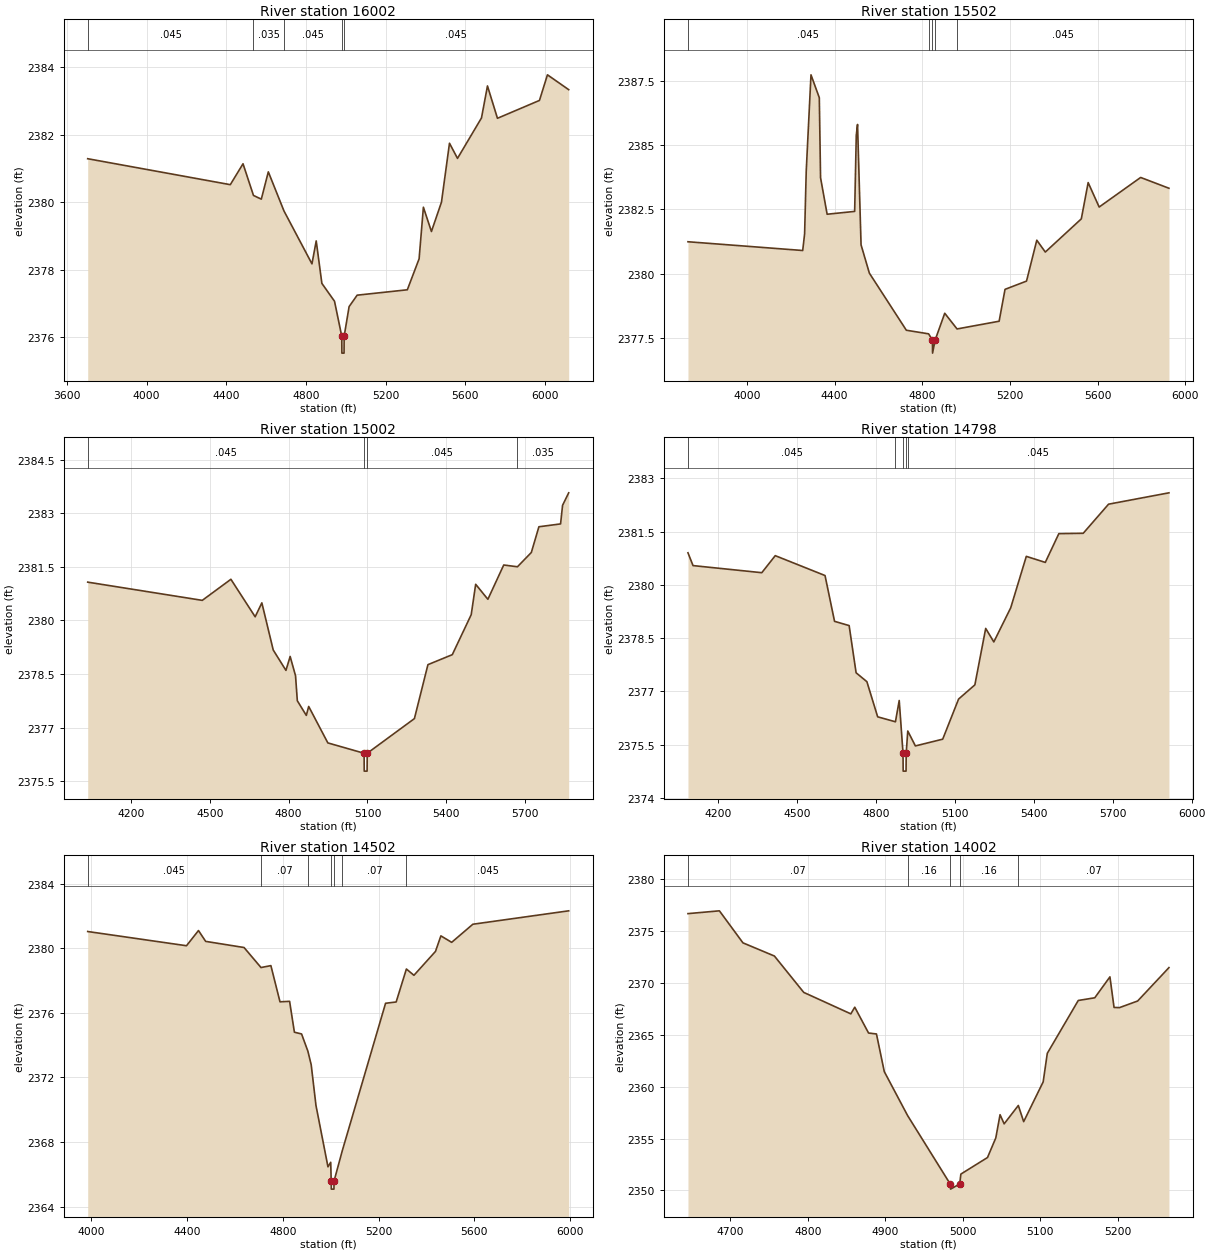
Type RM Length L Ch R = 1,16002,500,500,500
BEGIN DESCRIPTION:
Cottonwood Trib044 30.0
END DESCRIPTION:
XS GIS Cut Line= 4
      1332536.96      6870552.77      1333478.22      6869661.61
      1333988.38      6869594.41      1334591.27      6869649.85
#Sta/Elev= 30
  3703.8 2381.29  4420.1 2380.52  4484.0 2381.14  4536.5 2380.20  4575.9 2380.09
  4611.1 2380.90  4689.7 2379.74  4830.3 2378.17  4851.7 2378.85  4880.1 2377.59
  4943.6 2377.06  4980.1 2376.02  4980.6 2375.52  4991.5 2375.52  4992.0 2376.02
  5016.9 2376.90  5057.3 2377.24  5309.4 2377.40  5368.6 2378.32  5390.1 2379.85
  5430.5 2379.13  5480.9 2380.00  5521.2 2381.75  5561.4 2381.30  5681.9 2382.50
  5712.0 2383.45  5762.2 2382.49  5973.1 2383.02  6013.3 2383.78  6120.0 2383.34
#Mann=5,-1,0
  3703.8   0.045       0  4536.5   0.035       0  4689.7   0.045       0
  4980.1   0.045       0  4992.0   0.045       0
Bank Sta=4980.1,4992
Exp/Cntr=0.3,0.1

Type RM Length L Ch R = 1,15502,500,500,500
BEGIN DESCRIPTION:
Cottonwood Trib044 29.0
END DESCRIPTION:
XS GIS Cut Line= 3
      1332668.91      6870573.59      1333780.44      6869962.56
      1334668.91      6869705.53
#Sta/Elev= 30
  3731.6 2381.24  4254.8 2380.90  4263.5 2381.55  4270.9 2383.99  4292.6 2387.73
  4330.5 2386.84  4336.2 2383.73  4366.2 2382.31  4491.7 2382.42  4499.1 2385.38
  4504.8 2385.80  4520.9 2381.12  4558.8 2380.02  4727.4 2377.80  4829.0 2377.66
  4846.5 2377.41  4847.0 2376.91  4858.4 2377.41  4902.5 2378.46  4958.7 2377.85
  5150.5 2378.15  5177.4 2379.39  5275.4 2379.71  5322.3 2381.30  5361.1 2380.84
  5525.3 2382.13  5556.5 2383.54  5606.7 2382.59  5795.9 2383.74  5924.9 2383.32
#Mann=5,-1,0
  3731.6   0.045       0  4829.0   0.035       0  4846.5   0.045       0
  4858.4   0.035       0  4958.7   0.045       0
Bank Sta=4846.5,4858.4
Exp/Cntr=0.3,0.1

Type RM Length L Ch R = 1,15002,204,204,204
BEGIN DESCRIPTION:
Cottonwood Trib044 28.0
END DESCRIPTION:
XS GIS Cut Line= 3
      1332773.13      6870608.29      1333714.65      6870396.73
      1334555.02      6870188.00
#Sta/Elev= 30
  4035.0 2381.07  4471.1 2380.56  4580.1 2381.15  4672.4 2380.10  4697.9 2380.49
  4741.2 2379.17  4789.6 2378.60  4805.6 2378.99  4826.1 2378.45  4832.9 2377.75
  4867.1 2377.34  4876.2 2377.59  4949.1 2376.57  5087.1 2376.28  5087.6 2375.78
  5098.5 2375.78  5099.0 2376.28  5278.6 2377.25  5330.1 2378.76  5422.8 2379.04
  5494.9 2380.16  5511.8 2381.01  5558.3 2380.59  5618.6 2381.55  5670.8 2381.50
  5723.7 2381.90  5752.5 2382.62  5835.0 2382.70  5842.6 2383.22  5865.9 2383.57
#Mann=4,-1,0
  4035.0   0.045       0  5087.1   0.045       0  5099.0   0.045       0
  5670.8   0.035       0
Bank Sta=5087.1,5099
Exp/Cntr=0.3,0.1

Type RM Length L Ch R = 1,14798,296,296,296
BEGIN DESCRIPTION:
Cottonwood Trib044 27.5
END DESCRIPTION:
XS GIS Cut Line= 3
      1332951.03      6870747.19      1333892.61      6870535.62
      1334731.47      6870327.26
#Sta/Elev= 30
  4084.2 2380.90  4103.5 2380.54  4365.0 2380.34  4416.2 2380.82  4605.5 2380.26
  4641.7 2378.97  4697.2 2378.85  4723.7 2377.52  4764.7 2377.27  4805.7 2376.28
  4873.3 2376.14  4887.7 2376.74  4902.2 2375.25  4902.7 2374.75  4913.7 2374.75
  4914.2 2375.25  4920.2 2375.88  4949.2 2375.46  5053.1 2375.65  5113.5 2376.78
  5175.4 2377.18  5216.6 2378.77  5247.5 2378.39  5311.7 2379.35  5371.1 2380.80
  5443.3 2380.63  5494.8 2381.44  5587.5 2381.45  5683.9 2382.27  5913.6 2382.59
#Mann=5,-1,0
  4084.2   0.045       0  4873.3    0.07       0  4902.2   0.045       0
  4914.2    0.07       0  4920.2   0.045       0
Bank Sta=4902.2,4914.2
Exp/Cntr=0.3,0.1

Type RM Length L Ch R = 1,14502,500,500,500
BEGIN DESCRIPTION:
Cottonwood Trib044 27.0
END DESCRIPTION:
XS GIS Cut Line= 3
      1332793.08      6870766.11      1333806.46      6870828.56
      1334688.86      6870370.30
#Sta/Elev= 30
  3984.7 2381.03  4397.4 2380.15  4447.5 2381.09  4477.5 2380.42  4637.9 2380.04
  4708.8 2378.80  4750.0 2378.92  4788.1 2376.68  4828.2 2376.71  4848.3 2374.80
  4878.3 2374.69  4904.7 2373.62  4918.4 2372.79  4938.4 2370.27  4988.5 2366.47
  5000.0 2366.75  5002.0 2365.59  5002.5 2365.09  5013.5 2365.09  5014.0 2365.59
  5048.2 2367.46  5229.2 2376.59  5273.4 2376.67  5316.2 2378.71  5347.7 2378.32
  5437.8 2379.80  5460.3 2380.76  5505.4 2380.36  5593.9 2381.48  5994.3 2382.31
#Mann=7,-1,0
  3984.7   0.045       0  4708.8    0.07       0  4904.7    0.16       0
  5002.0    0.07       0  5014.0    0.16       0  5048.2    0.07       0
  5316.2   0.045       0
Bank Sta=5002,5014
Exp/Cntr=0.3,0.1

Type RM Length L Ch R = 1,14002,500,500,500
BEGIN DESCRIPTION:
Cottonwood Trib044 26.0
END DESCRIPTION:
XS GIS Cut Line= 3
      1333554.97      6871237.99      1333905.03      6871296.39
      1334154.97      6871387.99
#Sta/Elev= 30
  4645.1 2376.70  4685.7 2376.97  4716.1 2373.88  4756.7 2372.61  4794.6 2369.10
  4855.4 2367.03  4860.5 2367.67  4878.3 2365.18  4888.5 2365.09  4898.6 2361.46
  4928.7 2357.22  4983.7 2350.62  4984.2 2350.12  4996.0 2350.62  4997.5 2351.57
  5031.9 2353.17  5042.6 2355.06  5048.1 2357.30  5053.4 2356.42  5071.7 2358.19
  5078.6 2356.63  5103.8 2360.47  5109.1 2363.22  5149.1 2368.32  5170.4 2368.58
  5190.0 2370.60  5195.3 2367.65  5202.3 2367.63  5225.8 2368.27  5266.2 2371.49
#Mann=5,-1,0
  4645.1    0.07       0  4928.7    0.16       0  4983.7    0.07       0
  4996.0    0.16       0  5071.7    0.07       0
Bank Sta=4983.7,4996
Exp/Cntr=0.3,0.1

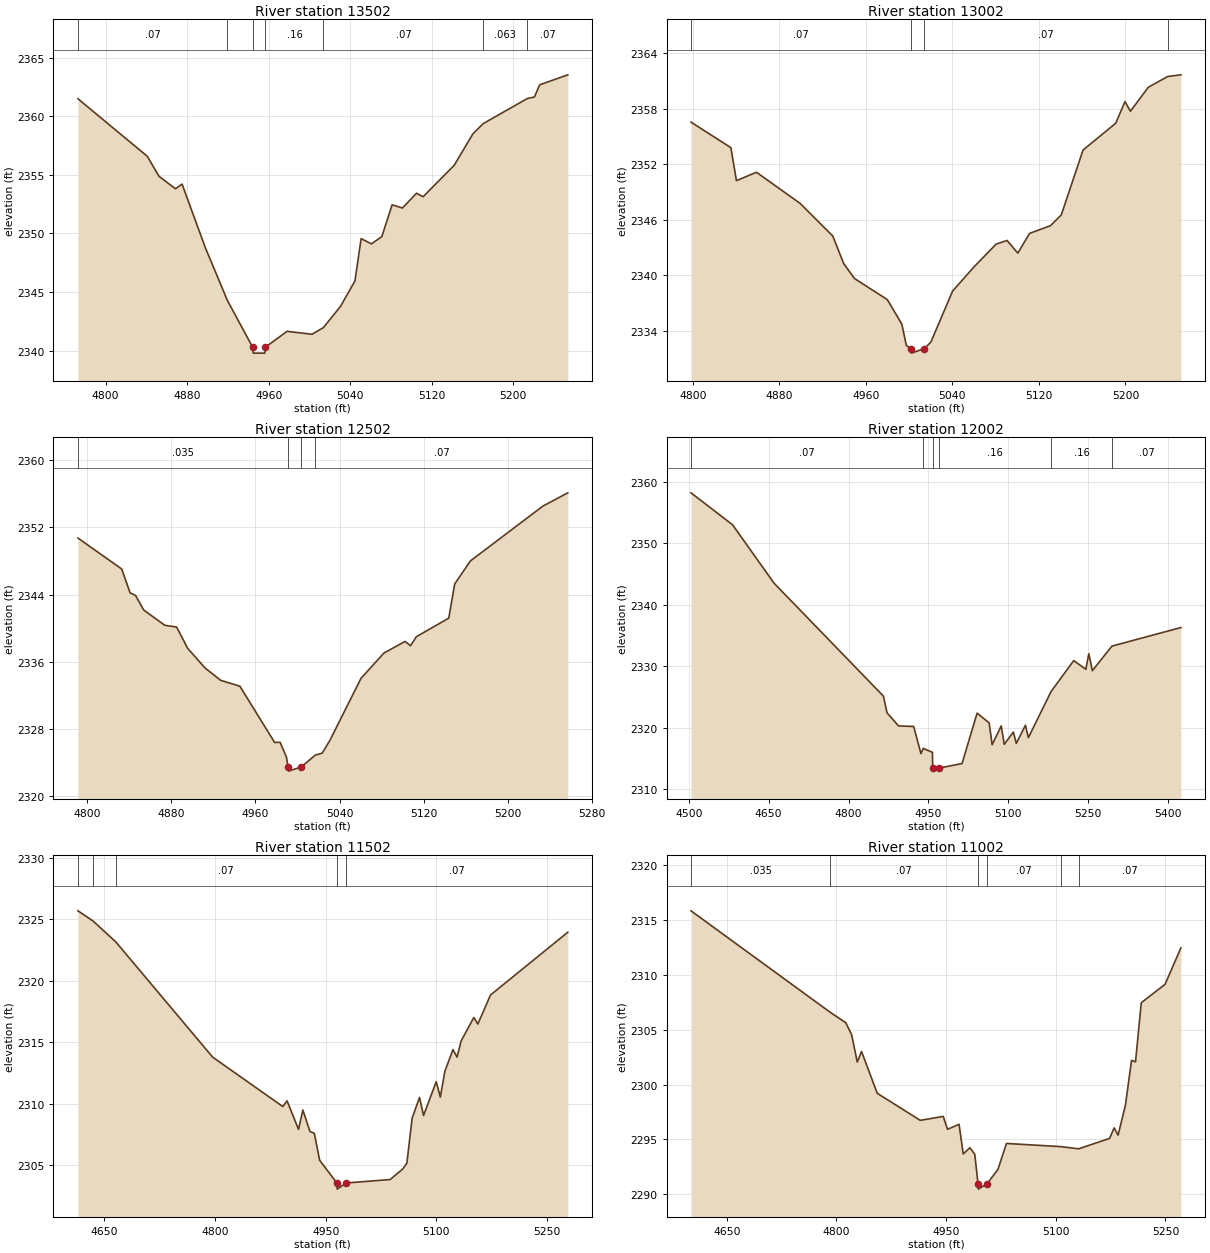
Type RM Length L Ch R = 1,13502,500,500,500
BEGIN DESCRIPTION:
Cottonwood Trib044 25.0
END DESCRIPTION:
XS GIS Cut Line= 3
      1333754.99      6871888.01      1333955.01      6871780.26
      1334204.97      6871738.01
#Sta/Elev= 30
  4772.8 2361.49  4840.9 2356.58  4852.3 2354.88  4868.5 2353.81  4875.0 2354.21
  4897.8 2348.79  4919.5 2344.28  4944.3 2340.29  4944.8 2339.79  4956.2 2339.79
  4956.7 2340.29  4978.0 2341.65  5002.5 2341.40  5013.7 2341.97  5030.4 2343.77
  5044.6 2345.94  5050.7 2349.56  5060.8 2349.11  5071.0 2349.73  5081.1 2352.44
  5091.3 2352.17  5105.0 2353.43  5111.5 2353.13  5142.0 2355.81  5160.4 2358.50
  5170.5 2359.37  5213.8 2361.51  5220.8 2361.64  5225.9 2362.68  5253.5 2363.53
#Mann=7,-1,0
  4772.8    0.07       0  4919.5    0.16       0  4944.3    0.07       0
  4956.7    0.16       0  5013.7    0.07       0  5170.5   0.063       0
  5213.8    0.07       0
Bank Sta=4944.3,4956.7
Exp/Cntr=0.3,0.1

Type RM Length L Ch R = 1,13002,500,500,500
BEGIN DESCRIPTION:
Cottonwood Trib044 24.0
END DESCRIPTION:
XS GIS Cut Line= 3
      1333805.03      6872238.00      1334005.03      6872264.12
      1334254.97      6872238.00
#Sta/Elev= 30
  4798.3 2356.55  4835.2 2353.79  4840.3 2350.22  4858.8 2351.13  4899.1 2347.77
  4929.4 2344.23  4939.5 2341.24  4949.5 2339.63  4979.8 2337.35  4993.2 2334.71
  4997.5 2332.37  5001.7 2332.06  5002.2 2331.56  5014.1 2332.06  5020.1 2332.75
  5040.2 2338.28  5060.3 2340.93  5080.4 2343.35  5090.5 2343.75  5100.5 2342.38
  5111.3 2344.51  5130.7 2345.35  5140.7 2346.52  5160.8 2353.53  5191.0 2356.43
  5199.6 2358.77  5204.6 2357.73  5221.2 2360.33  5239.1 2361.49  5251.3 2361.67
#Mann=4,-1,0
  4798.3    0.07       0  5001.7    0.07       0  5014.1    0.07       0
  5239.1   0.035       0
Bank Sta=5001.7,5014.1
Exp/Cntr=0.3,0.1

Type RM Length L Ch R = 1,12502,500,500,500
BEGIN DESCRIPTION:
Cottonwood Trib044 23.0
END DESCRIPTION:
XS GIS Cut Line= 3
      1333855.02      6872688.01      1334055.03      6872747.98
      1334305.03      6872687.99
#Sta/Elev= 30
  4791.2 2350.73  4832.9 2347.04  4840.8 2344.21  4846.0 2343.90  4853.8 2342.16
  4873.8 2340.35  4885.1 2340.13  4895.6 2337.60  4912.1 2335.27  4926.9 2333.80
  4945.2 2333.10  4978.3 2326.40  4983.5 2326.42  4989.5 2324.67  4991.1 2323.49
  4991.6 2322.99  5003.6 2323.49  5016.9 2324.89  5023.5 2325.13  5030.8 2326.64
  5060.4 2334.03  5082.2 2337.04  5102.4 2338.43  5107.5 2337.91  5113.1 2338.99
  5143.9 2341.20  5149.5 2345.26  5164.5 2348.01  5233.5 2354.54  5257.1 2356.11
#Mann=4,-1,0
  4791.2   0.035       0  4991.1   0.035       0  5003.6   0.035       0
  5016.9    0.07       0
Bank Sta=4991.1,5003.6
Exp/Cntr=0.3,0.1

Type RM Length L Ch R = 1,12002,500,500,500
BEGIN DESCRIPTION:
Cottonwood Trib044 22.0
END DESCRIPTION:
XS GIS Cut Line= 3
      1333605.00      6872888.00      1333972.44      6873220.71
      1334355.04      6873037.98
#Sta/Elev= 30
  4504.3 2358.23  4582.4 2353.02  4660.1 2343.53  4865.6 2325.13  4872.3 2322.42
  4893.9 2320.29  4922.3 2320.20  4936.0 2315.77  4940.3 2316.63  4957.5 2315.99
  4958.0 2313.43  4958.5 2312.93  4970.5 2313.43  5013.1 2314.17  5041.4 2322.37
  5064.0 2320.78  5069.6 2317.23  5086.7 2320.29  5092.3 2317.29  5109.4 2319.29
  5115.0 2317.44  5132.1 2320.40  5137.6 2318.38  5180.3 2325.89  5222.8 2330.93
  5245.5 2329.50  5251.1 2332.05  5257.7 2329.28  5294.5 2333.28  5424.0 2336.30
#Mann=6,-1,0
  4504.3    0.07       0  4940.3    0.16       0  4958.0    0.07       0
  4970.5    0.16       0  5180.3    0.16       0  5294.5    0.07       0
Bank Sta=4958,4970.5
Exp/Cntr=0.3,0.1

Type RM Length L Ch R = 1,11502,500,500,500
BEGIN DESCRIPTION:
Cottonwood Trib044 21.0
END DESCRIPTION:
XS GIS Cut Line= 3
      1333704.98      6873337.97      1333904.55      6873667.68
      1334155.04      6873788.02
#Sta/Elev= 30
  4614.6 2325.68  4635.0 2324.86  4665.8 2323.16  4797.0 2313.78  4892.0 2309.76
  4897.8 2310.22  4913.3 2307.90  4919.2 2309.47  4928.8 2307.73  4934.7 2307.58
  4941.9 2305.39  4965.2 2303.54  4965.7 2303.04  4977.8 2303.54  5037.4 2303.82
  5054.4 2304.68  5060.0 2305.15  5067.1 2308.80  5077.1 2310.50  5082.6 2309.03
  5099.7 2311.78  5105.3 2310.53  5111.4 2312.62  5122.4 2314.39  5127.9 2313.78
  5133.6 2315.11  5150.6 2317.00  5156.1 2316.47  5173.2 2318.83  5277.9 2323.94
#Mann=5,-1,0
  4614.6    0.07       0  4635.0   0.035       0  4665.8    0.07       0
  4965.2    0.07       0  4977.8    0.07       0
Bank Sta=4965.2,4977.8
Exp/Cntr=0.3,0.1

Type RM Length L Ch R = 1,11002,500,500,500
BEGIN DESCRIPTION:
Cottonwood Trib044 20.0
END DESCRIPTION:
XS GIS Cut Line= 3
      1333405.00      6873687.99      1333604.91      6874033.06
      1333854.99      6874138.00
#Sta/Elev= 30
  4601.2 2315.86  4791.9 2306.58  4812.8 2305.65  4820.8 2304.56  4828.6 2302.05
  4834.4 2303.02  4855.9 2299.20  4914.7 2296.73  4946.2 2297.09  4952.0 2295.91
  4967.8 2296.37  4973.5 2293.66  4982.6 2294.23  4989.3 2293.63  4993.7 2290.95
  4994.2 2290.45  5006.3 2290.95  5021.0 2292.26  5032.6 2294.62  5107.3 2294.33
  5131.3 2294.13  5173.6 2295.08  5179.9 2296.04  5185.3 2295.38  5195.3 2298.11
  5203.7 2302.21  5209.1 2302.07  5217.0 2307.47  5249.5 2309.15  5271.2 2312.48
#Mann=6,-1,0
  4601.2   0.035       0  4791.9    0.07       0  4993.7    0.07       0
  5006.3    0.07       0  5107.3   0.035       0  5131.3    0.07       0
Bank Sta=4993.7,5006.3
Exp/Cntr=0.3,0.1

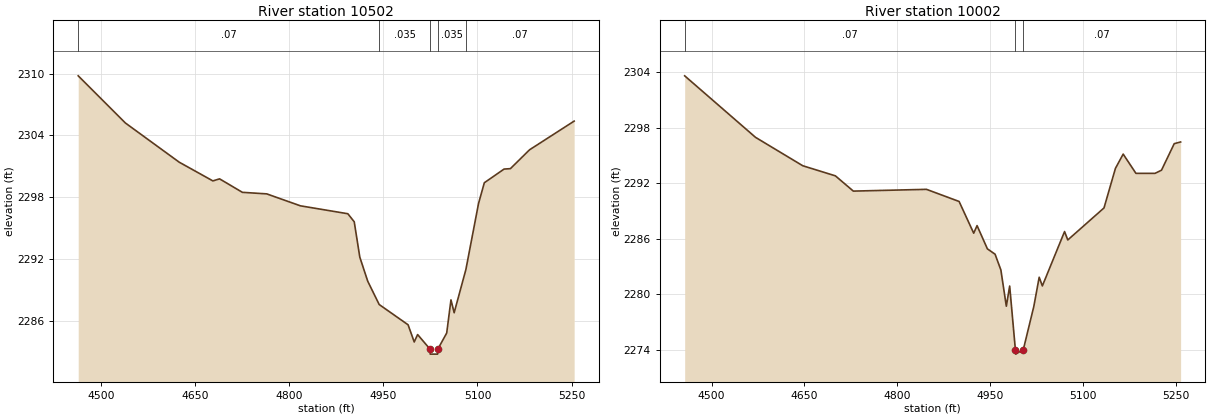
Type RM Length L Ch R = 1,10502,500,500,500
BEGIN DESCRIPTION:
Cottonwood Trib044 19.0
END DESCRIPTION:
XS GIS Cut Line= 3
      1333055.00      6874288.00      1333554.97      6874483.68
      1333805.03      6874438.00
#Sta/Elev= 30
  4463.1 2309.78  4538.3 2305.20  4624.2 2301.39  4677.9 2299.57  4688.6 2299.77
  4725.0 2298.46  4763.8 2298.31  4817.5 2297.15  4893.2 2296.38  4903.4 2295.60
  4912.3 2292.16  4924.9 2289.83  4943.2 2287.56  4989.3 2285.59  4999.1 2283.92
  5004.5 2284.64  5024.1 2283.24  5024.6 2282.74  5036.4 2282.74  5036.9 2283.24
  5050.9 2284.79  5057.7 2288.01  5062.8 2286.76  5081.5 2290.96  5101.7 2297.38
  5110.9 2299.39  5142.4 2300.72  5152.5 2300.76  5183.0 2302.59  5254.2 2305.38
#Mann=5,-1,0
  4463.1    0.07       0  4943.2   0.035       0  5024.1   0.035       0
  5036.9   0.035       0  5081.5    0.07       0
Bank Sta=5024.1,5036.9
Exp/Cntr=0.3,0.1

Type RM Length L Ch R = 1,10002,500,500,500
BEGIN DESCRIPTION:
Cottonwood Trib044 18.0
END DESCRIPTION:
XS GIS Cut Line= 3
      1333055.01      6874738.00      1333555.03      6874951.01
      1333805.01      6874888.00
#Sta/Elev= 30
  4456.5 2303.63  4571.0 2296.98  4647.3 2293.91  4700.0 2292.82  4729.0 2291.17
  4847.2 2291.36  4899.9 2290.05  4923.5 2286.62  4928.9 2287.44  4945.6 2284.93
  4958.0 2284.35  4967.4 2282.65  4976.2 2278.73  4981.6 2280.91  4990.8 2274.05
  4991.3 2273.55  5003.7 2274.05  5020.6 2278.70  5029.3 2281.86  5034.4 2280.92
  5070.3 2286.80  5075.5 2285.89  5134.0 2289.35  5152.5 2293.63  5165.0 2295.17
  5185.6 2293.09  5216.5 2293.09  5226.9 2293.43  5247.5 2296.30  5257.8 2296.48
#Mann=3,-1,0
  4456.5    0.07       0  4990.8    0.07       0  5003.7    0.07       0
Bank Sta=4990.8,5003.7
Exp/Cntr=0.3,0.1