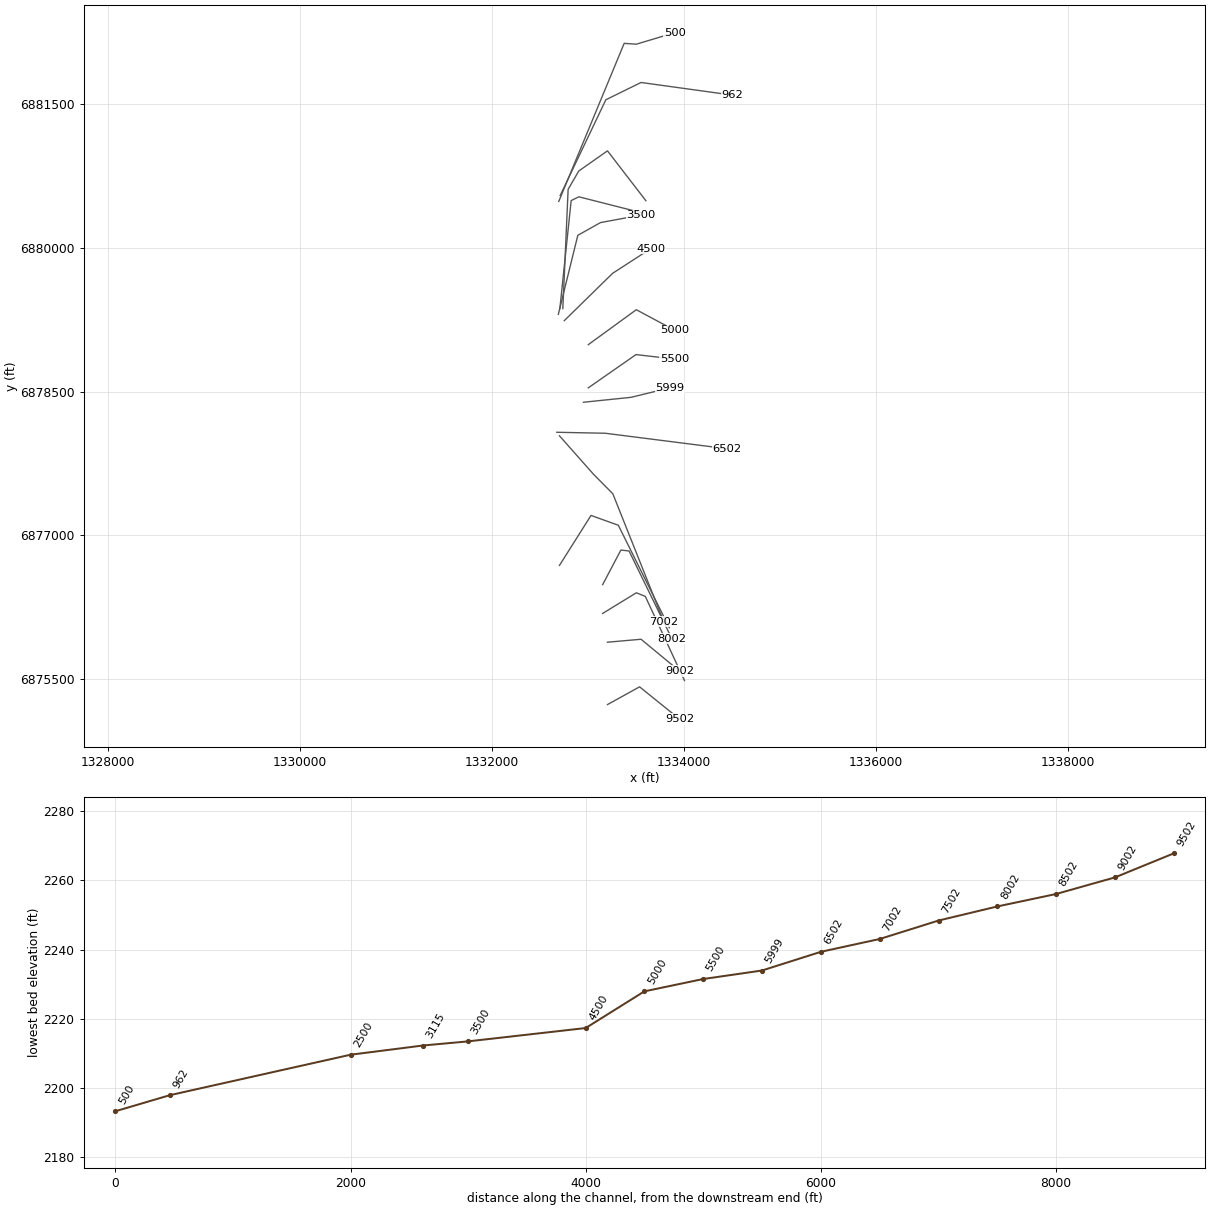
HEC-RAS study Cottonwood Trib044.prj: Cottonwood Trib044 Base Level Engineering

--- Cottonwood Trib044.g01 (geometry) --- (continued)

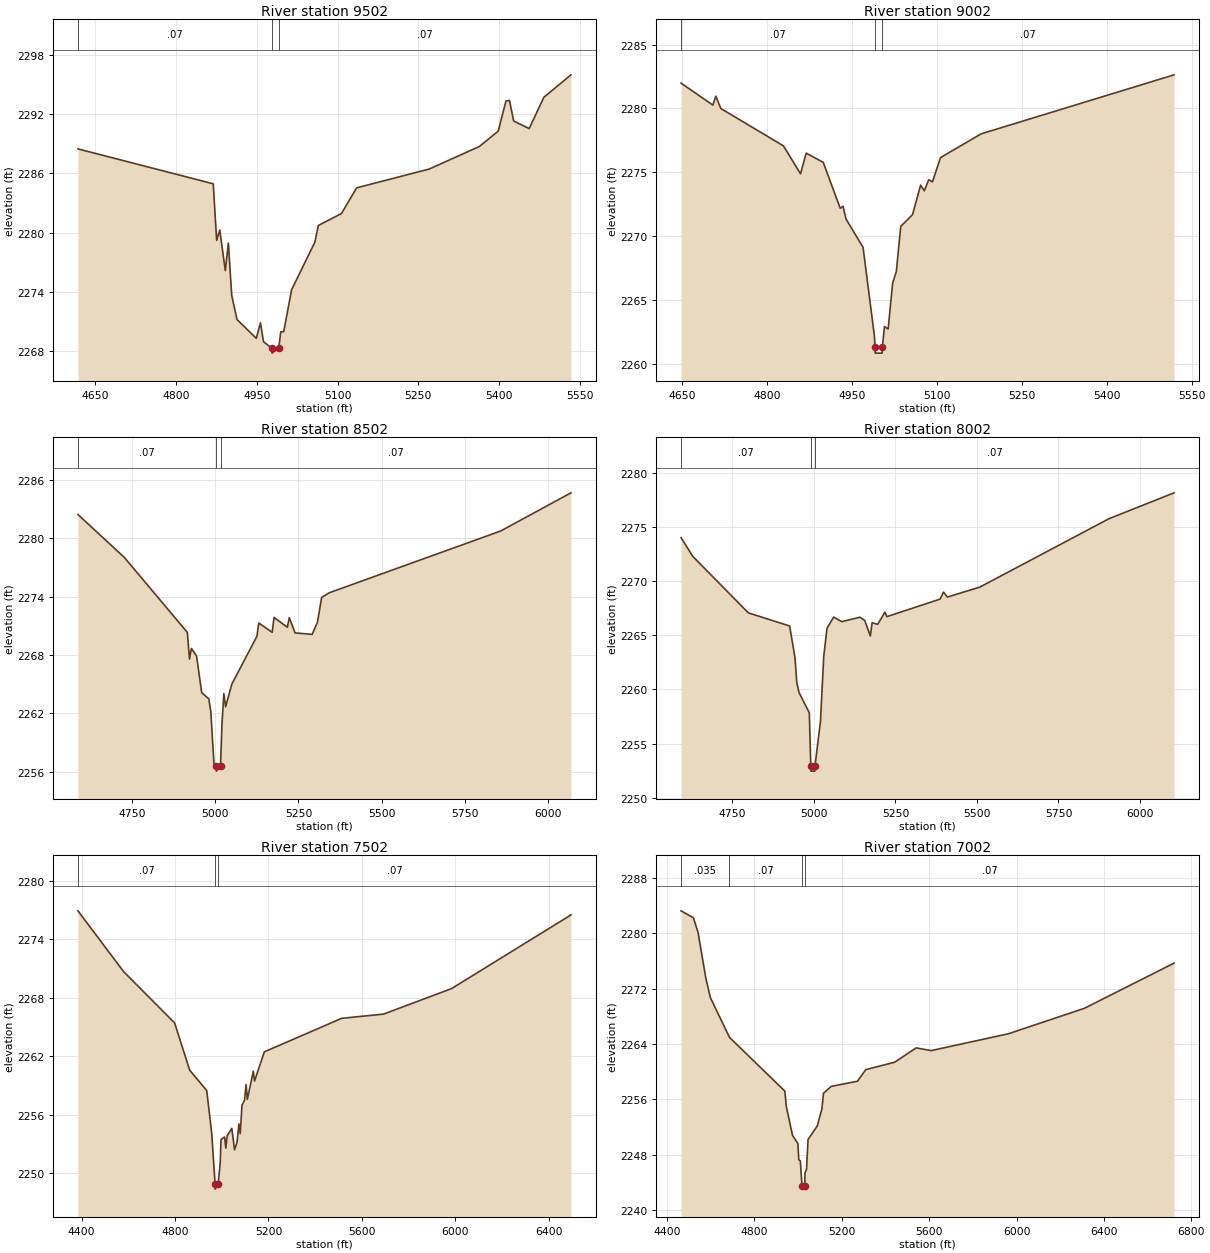
Type RM Length L Ch R = 1,9502,500,500,500
BEGIN DESCRIPTION:
Cottonwood Trib044 17.0
END DESCRIPTION:
XS GIS Cut Line= 3
      1333204.97      6875237.98      1333539.52      6875422.99
      1333954.99      6875088.00
#Sta/Elev= 30
  4617.7 2288.49  4869.1 2284.95  4875.4 2279.22  4881.2 2280.26  4891.5 2276.15
  4897.2 2278.94  4903.4 2273.64  4913.2 2271.19  4949.1 2269.28  4956.8 2270.85
  4962.5 2268.94  4977.8 2268.28  4978.3 2267.78  4990.7 2268.28  4994.6 2269.95
  5000.0 2269.95  5014.7 2274.21  5057.9 2279.03  5064.3 2280.72  5107.4 2281.94
  5135.5 2284.54  5270.6 2286.45  5363.4 2288.73  5398.6 2290.29  5412.9 2293.34
  5419.4 2293.41  5427.3 2291.32  5456.1 2290.55  5483.3 2293.72  5533.7 2296.00
#Mann=3,-1,0
  4617.7    0.07       0  4977.8    0.07       0  4990.7    0.07       0
Bank Sta=4977.8,4990.7
Exp/Cntr=0.3,0.1

Type RM Length L Ch R = 1,9002,500,500,500
BEGIN DESCRIPTION:
Cottonwood Trib044 16.0
END DESCRIPTION:
XS GIS Cut Line= 3
      1333204.96      6875888.00      1333555.01      6875918.73
      1333954.99      6875588.01
#Sta/Elev= 30
  4648.6 2281.98  4704.8 2280.26  4709.9 2280.96  4718.9 2279.99  4829.3 2277.07
  4859.5 2274.88  4869.5 2276.50  4899.6 2275.78  4929.6 2272.18  4934.6 2272.34
  4939.8 2271.34  4969.9 2269.12  4990.0 2262.16  4991.0 2261.34  4991.5 2260.84
  5003.5 2260.84  5004.0 2261.34  5007.7 2262.92  5014.2 2262.73  5022.1 2266.32
  5028.6 2267.22  5036.4 2270.76  5057.2 2271.68  5071.6 2274.00  5078.0 2273.55
  5085.9 2274.42  5092.4 2274.25  5106.7 2276.15  5178.4 2278.01  5519.0 2282.63
#Mann=3,-1,0
  4648.6    0.07       0  4991.0    0.07       0  5004.0    0.07       0
Bank Sta=4991,5004
Exp/Cntr=0.3,0.1

Type RM Length L Ch R = 1,8502,500,500,500
BEGIN DESCRIPTION:
Cottonwood Trib044 15.0
END DESCRIPTION:
XS GIS Cut Line= 4
      1333154.99      6876187.99      1333506.03      6876402.91
      1333599.43      6876365.16      1334007.43      6875488.39
#Sta/Elev= 30
  4588.4 2282.47  4727.6 2278.05  4916.7 2270.33  4923.1 2267.59  4928.9 2268.68
  4944.4 2267.90  4959.8 2264.13  4981.1 2263.49  4987.1 2262.18  4996.5 2256.89
  5003.2 2256.55  5003.7 2256.05  5016.2 2256.55  5020.5 2260.86  5026.2 2264.03
  5031.5 2262.68  5050.3 2265.02  5125.5 2269.93  5131.0 2271.30  5171.3 2270.34
  5176.8 2271.87  5217.0 2270.86  5222.5 2271.85  5239.9 2270.28  5291.2 2270.13
  5307.2 2271.38  5319.6 2273.92  5342.4 2274.41  5856.9 2280.77  6067.8 2284.70
#Mann=3,-1,0
  4588.4    0.07       0  5003.2    0.07       0  5016.2    0.07       0
Bank Sta=5003.2,5016.2
Exp/Cntr=0.3,0.1

Type RM Length L Ch R = 1,8002,500,500,500
BEGIN DESCRIPTION:
Cottonwood Trib044 14.0
END DESCRIPTION:
XS GIS Cut Line= 4
      1333155.00      6876488.00      1333344.96      6876848.28
      1333430.16      6876838.25      1333877.09      6875922.69
#Sta/Elev= 30
  4592.7 2274.02  4628.6 2272.29  4799.1 2267.07  4925.6 2265.86  4942.0 2262.95
  4947.6 2260.63  4954.5 2259.71  4986.0 2257.84  4990.5 2252.95  4991.0 2252.45
  5003.0 2252.45  5003.5 2252.95  5020.2 2257.04  5030.2 2263.04  5040.2 2265.64
  5060.5 2266.68  5085.7 2266.26  5141.7 2266.67  5156.1 2266.36  5173.1 2264.94
  5178.6 2266.16  5195.6 2266.01  5218.1 2267.14  5223.7 2266.72  5386.9 2268.34
  5397.6 2268.99  5409.4 2268.53  5508.9 2269.45  5905.0 2275.77  6104.6 2278.16
#Mann=3,-1,0
  4592.7    0.07       0  4990.5    0.07       0  5003.5    0.07       0
Bank Sta=4990.5,5003.5
Exp/Cntr=0.3,0.1

Type RM Length L Ch R = 1,7502,500,500,500
BEGIN DESCRIPTION:
Cottonwood Trib044 13.0
END DESCRIPTION:
XS GIS Cut Line= 4
      1332704.98      6876687.97      1333033.46      6877208.86
      1333318.18      6877106.48      1333849.41      6876038.81
#Sta/Elev= 30
  4384.2 2276.94  4580.2 2270.69  4798.0 2265.44  4862.7 2260.59  4935.6 2258.50
  4956.8 2254.16  4971.5 2248.88  4972.0 2248.38  4984.5 2248.88  4993.3 2251.08
  4996.8 2253.48  5012.1 2253.73  5017.5 2252.59  5022.9 2253.84  5042.9 2254.62
  5054.8 2252.42  5065.4 2253.18  5073.6 2255.07  5078.9 2254.08  5086.7 2256.99
  5097.3 2257.50  5104.3 2259.11  5109.6 2257.59  5135.0 2260.48  5140.3 2259.47
  5182.3 2262.47  5513.7 2265.91  5692.8 2266.34  5984.0 2268.96  6495.1 2276.52
#Mann=3,-1,0
  4384.2    0.07       0  4971.5    0.07       0  4984.5    0.07       0
Bank Sta=4971.5,4984.5
Exp/Cntr=0.3,0.1

Type RM Length L Ch R = 1,7002,500,500,500
BEGIN DESCRIPTION:
Cottonwood Trib044 12.0
END DESCRIPTION:
XS GIS Cut Line= 4
      1332705.00      6878038.00      1333059.33      6877638.10
      1333260.89      6877434.60      1333791.81      6876102.10
#Sta/Elev= 30
  4465.7 2283.25  4522.2 2282.25  4543.9 2280.06  4579.0 2273.51  4599.9 2270.70
  4687.2 2264.97  4940.4 2257.21  4947.0 2255.01  4975.5 2250.81  5000.0 2249.64
  5004.1 2247.29  5011.2 2247.13  5018.8 2243.55  5019.3 2243.05  5031.9 2243.55
  5032.3 2245.37  5039.5 2245.90  5046.5 2250.22  5088.9 2252.19  5110.2 2254.70
  5117.2 2256.90  5152.6 2257.89  5272.8 2258.64  5310.4 2260.31  5442.5 2261.38
  5541.1 2263.45  5609.7 2263.06  5962.9 2265.49  6310.7 2269.17  6720.8 2275.70
#Mann=4,-1,0
  4465.7   0.035       0  4687.2    0.07       0  5018.8    0.07       0
  5031.9    0.07       0
Bank Sta=5018.8,5031.9
Exp/Cntr=0.3,0.1

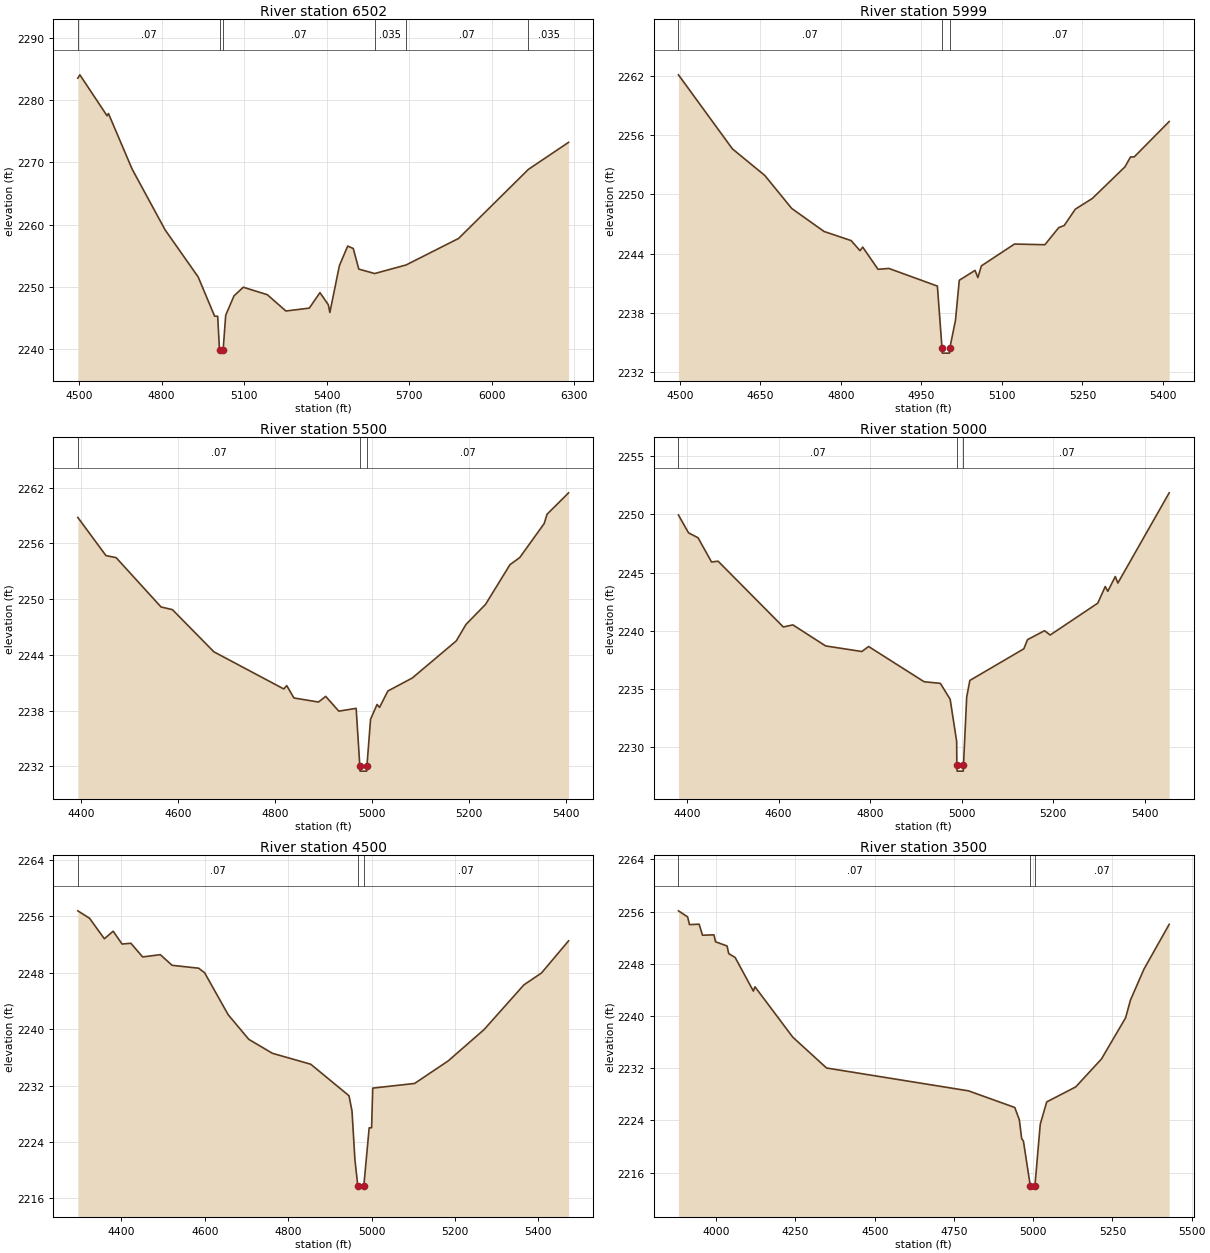
Type RM Length L Ch R = 1,6502,503,503,503
BEGIN DESCRIPTION:
Cottonwood Trib044 11.0
END DESCRIPTION:
XS GIS Cut Line= 3
      1332677.58      6878075.22      1333182.00      6878065.06
      1334451.75      6877903.58
#Sta/Elev= 30
  4495.5 2283.53  4502.9 2284.07  4601.9 2277.49  4606.9 2277.85  4693.0 2268.92
  4813.0 2259.15  4933.0 2251.60  4993.0 2245.29  5004.1 2245.27  5010.7 2239.85
  5011.2 2239.35  5023.8 2239.85  5033.3 2245.45  5063.5 2248.56  5097.2 2249.94
  5184.5 2248.74  5252.1 2246.12  5337.1 2246.58  5376.0 2249.07  5406.3 2247.13
  5412.0 2245.88  5446.6 2253.40  5476.8 2256.55  5497.0 2256.17  5517.2 2252.85
  5575.0 2252.14  5689.4 2253.52  5880.1 2257.78  6134.0 2268.88  6280.0 2273.22
#Mann=6,-1,0
  4495.5    0.07       0  5010.7    0.07       0  5023.8    0.07       0
  5575.0   0.035       0  5689.4    0.07       0  6134.0   0.035       0
Bank Sta=5010.7,5023.8
Exp/Cntr=0.3,0.1

Type RM Length L Ch R = 1,5999,499,499,499
BEGIN DESCRIPTION:
Cottonwood Trib044 10.0
END DESCRIPTION:
XS GIS Cut Line= 3
      1332954.96      6878388.00      1333451.44      6878439.38
      1333855.03      6878538.01
#Sta/Elev= 30
  4497.2 2262.12  4597.8 2254.62  4658.1 2251.93  4708.4 2248.58  4768.7 2246.25
  4819.0 2245.33  4835.6 2244.31  4840.6 2244.67  4869.2 2242.42  4889.3 2242.51
  4979.8 2240.72  4988.4 2234.43  4988.9 2233.93  5002.4 2233.93  5002.9 2234.43
  5013.5 2237.25  5020.6 2241.31  5050.0 2242.31  5055.2 2241.58  5061.8 2242.77
  5123.5 2244.98  5180.1 2244.91  5205.9 2246.64  5216.2 2246.86  5236.8 2248.51
  5268.6 2249.60  5329.4 2252.80  5339.7 2253.80  5346.7 2253.81  5411.8 2257.39
#Mann=3,-1,0
  4497.2    0.07       0  4988.4    0.07       0  5002.9    0.07       0
Bank Sta=4988.4,5002.9
Exp/Cntr=0.3,0.1

Type RM Length L Ch R = 1,5500,500,500,500
BEGIN DESCRIPTION:
Cottonwood Trib044 9.0
END DESCRIPTION:
XS GIS Cut Line= 3
      1333004.99      6878537.99      1333502.24      6878884.55
      1333904.96      6878838.00
#Sta/Elev= 30
  4393.9 2258.80  4451.9 2254.69  4472.9 2254.47  4565.4 2249.16  4588.9 2248.87
  4674.3 2244.33  4818.4 2240.33  4824.5 2240.69  4839.3 2239.36  4890.0 2238.92
  4904.8 2239.53  4931.8 2237.94  4967.6 2238.24  4975.2 2231.98  4975.7 2231.48
  4989.2 2231.48  4989.7 2231.98  4997.3 2237.07  5010.7 2238.66  5015.7 2238.34
  5033.0 2240.11  5083.3 2241.51  5173.9 2245.50  5194.0 2247.28  5234.3 2249.44
  5284.6 2253.71  5304.8 2254.48  5355.1 2258.14  5361.0 2259.14  5405.4 2261.45
#Mann=3,-1,0
  4393.9    0.07       0  4975.2    0.07       0  4989.7    0.07       0
Bank Sta=4975.2,4989.7
Exp/Cntr=0.3,0.1

Type RM Length L Ch R = 1,5000,500,500,500
BEGIN DESCRIPTION:
Cottonwood Trib044 8.0
END DESCRIPTION:
XS GIS Cut Line= 3
      1333005.00      6878988.00      1333505.43      6879352.02
      1333905.00      6879138.00
#Sta/Elev= 30
  4381.2 2249.95  4403.2 2248.42  4424.1 2247.99  4453.5 2245.91  4467.8 2245.98
  4610.3 2240.32  4631.2 2240.50  4702.7 2238.69  4781.9 2238.21  4796.6 2238.64
  4917.9 2235.61  4953.4 2235.47  4974.8 2234.10  4989.0 2230.48  4989.4 2228.42
  4989.9 2227.92  5003.4 2227.92  5003.9 2228.42  5010.9 2234.29  5017.8 2235.72
  5135.7 2238.44  5143.8 2239.23  5181.0 2240.00  5193.3 2239.63  5297.3 2242.37
  5313.6 2243.80  5319.2 2243.39  5335.5 2244.66  5341.2 2244.10  5453.3 2251.86
#Mann=3,-1,0
  4381.2    0.07       0  4989.4    0.07       0  5003.9    0.07       0
Bank Sta=4989.4,5003.9
Exp/Cntr=0.3,0.1

Type RM Length L Ch R = 1,4500,1000,1000,1000
BEGIN DESCRIPTION:
Cottonwood Trib044 7.0
END DESCRIPTION:
XS GIS Cut Line= 3
      1332755.02      6879238.02      1333258.52      6879731.07
      1333655.04      6879988.02
#Sta/Elev= 30
  4295.3 2256.79  4323.5 2255.73  4358.9 2252.83  4380.1 2253.90  4401.4 2252.08
  4422.5 2252.19  4450.8 2250.25  4493.2 2250.57  4521.5 2249.06  4585.2 2248.65
  4599.4 2248.01  4656.0 2242.05  4705.4 2238.56  4762.0 2236.58  4854.0 2235.03
  4945.8 2230.56  4953.0 2228.40  4960.0 2221.51  4966.8 2217.81  4967.3 2217.31
  4981.4 2217.81  4994.2 2226.01  5000.0 2226.01  5002.7 2231.64  5103.1 2232.30
  5184.0 2235.51  5269.9 2239.95  5365.2 2246.28  5407.5 2247.97  5472.5 2252.53
#Mann=3,-1,0
  4295.3    0.07       0  4966.8    0.07       0  4981.4    0.07       0
Bank Sta=4966.8,4981.4
Exp/Cntr=0.3,0.1

Type RM Length L Ch R = 1,3500,385,385,385
BEGIN DESCRIPTION:
Cottonwood Trib044 6.0
END DESCRIPTION:
XS GIS Cut Line= 4
      1332693.17      6879304.35      1332896.30      6880127.31
      1333133.06      6880260.07      1333555.02      6880338.00
#Sta/Elev= 30
  3880.9 2256.13  3909.9 2255.20  3915.6 2254.02  3946.2 2254.08  3956.8 2252.39
  3992.8 2252.45  3998.0 2251.38  4034.3 2250.74  4039.5 2249.57  4059.8 2248.98
  4117.2 2243.83  4122.4 2244.48  4241.6 2236.76  4348.2 2232.03  4795.8 2228.53
  4941.9 2225.98  4956.4 2224.09  4963.6 2221.23  4969.3 2220.81  4990.9 2213.96
  4991.4 2213.46  5005.5 2213.96  5022.3 2223.40  5042.7 2226.83  5134.2 2229.13
  5215.5 2233.42  5291.6 2239.73  5307.0 2242.46  5349.6 2247.20  5429.1 2254.06
#Mann=3,-1,0
  3880.9    0.07       0  4990.9    0.07       0  5005.5    0.07       0
Bank Sta=4990.9,5005.5
Exp/Cntr=0.3,0.1

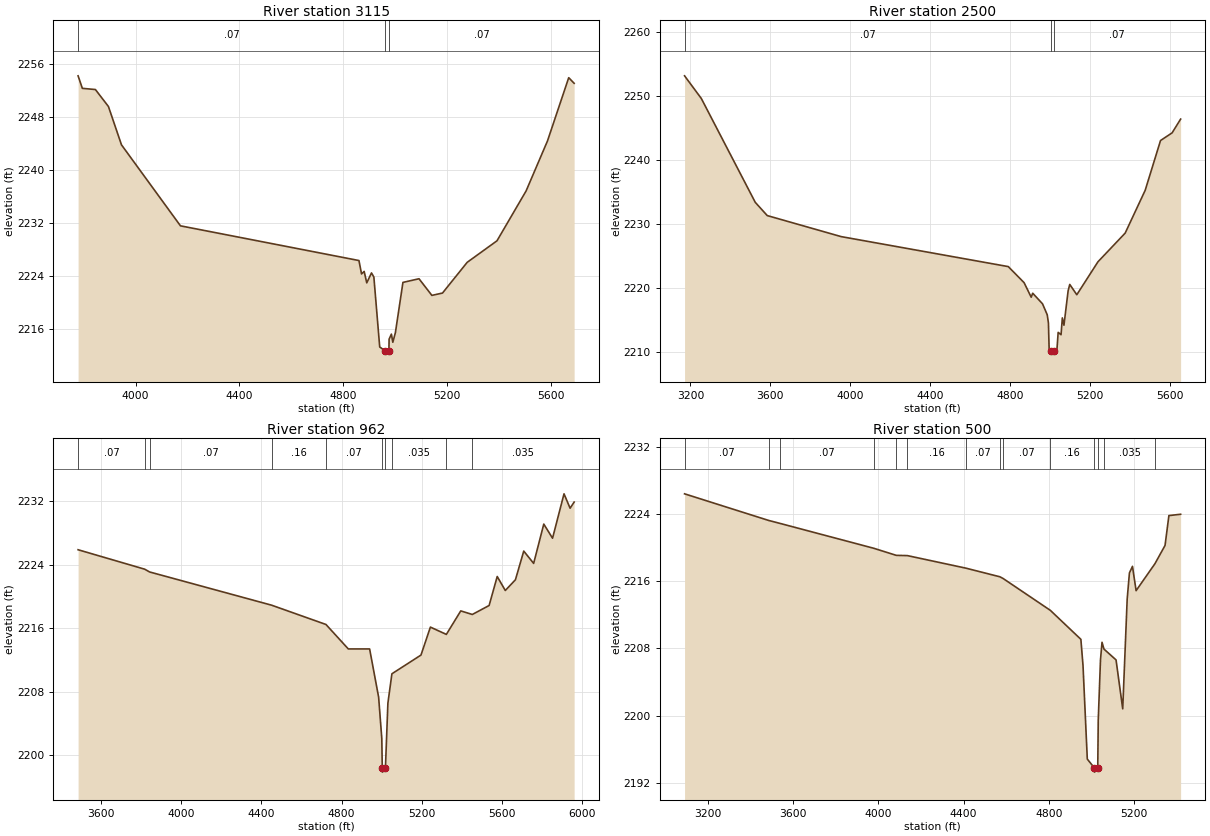
Type RM Length L Ch R = 1,3115,615,615,615
BEGIN DESCRIPTION:
Cottonwood Trib044 5.0
END DESCRIPTION:
XS GIS Cut Line= 4
      1332708.81      6879361.70      1332826.86      6880489.11
      1332906.72      6880528.35      1333574.40      6880358.91
#Sta/Elev= 30
  3778.3 2254.28  3794.7 2252.39  3845.0 2252.21  3895.2 2249.65  3945.5 2243.86
  4172.8 2231.63  4860.5 2226.39  4870.5 2224.37  4880.6 2224.75  4890.6 2223.02
  4908.8 2224.52  4918.0 2223.90  4940.5 2213.34  4961.3 2212.76  4961.8 2212.26
  4975.9 2212.76  4976.7 2214.52  4985.5 2215.28  4991.0 2214.05  5000.9 2215.49
  5030.0 2223.09  5091.9 2223.64  5141.5 2221.13  5182.4 2221.48  5277.6 2226.12
  5392.4 2229.37  5504.6 2236.90  5586.9 2244.44  5668.8 2254.00  5689.7 2253.15
#Mann=3,-1,0
  3778.3    0.07       0  4961.3    0.07       0  4975.9    0.07       0
Bank Sta=4961.3,4975.9
Exp/Cntr=0.3,0.1

Type RM Length L Ch R = 1,2500,1538,1538,1538
BEGIN DESCRIPTION:
Cottonwood Trib044 4.0
END DESCRIPTION:
XS GIS Cut Line= 5
      1332740.06      6879364.15      1332795.26      6880606.21
      1332906.00      6880797.27      1333205.17      6881007.20
      1333604.99      6880488.01
#Sta/Elev= 30
  3170.4 2253.13  3254.3 2249.59  3524.6 2233.34  3584.7 2231.27  3955.0 2227.98
  4792.1 2223.29  4871.2 2220.78  4906.9 2218.50  4914.3 2219.13  4963.6 2217.47
  4987.1 2215.76  4993.2 2214.47  4996.8 2210.24  5005.6 2210.10  5006.1 2209.60
  5020.3 2210.10  5035.6 2210.22  5041.9 2213.00  5056.4 2212.64  5062.8 2215.27
  5070.9 2214.12  5091.8 2219.50  5100.0 2220.50  5135.3 2218.89  5241.2 2224.04
  5377.6 2228.53  5477.8 2235.22  5554.7 2243.01  5612.7 2244.21  5655.3 2246.36
#Mann=3,-1,0
  3170.4    0.07       0  5005.6    0.07       0  5020.3    0.07       0
Bank Sta=5005.6,5020.3
Exp/Cntr=0.3,0.1

Type RM Length L Ch R = 1,962,462,462,462
BEGIN DESCRIPTION:
Cottonwood Trib044 2.0
END DESCRIPTION:
XS GIS Cut Line= 4
      1332712.27      6880541.18      1333188.12      6881539.46
      1333554.87      6881719.58      1334505.02      6881588.00
#Sta/Elev= 30
  3486.1 2225.90  3818.3 2223.45  3842.9 2223.10  4451.0 2218.92  4722.2 2216.49
  4833.6 2213.41  4939.9 2213.41  4984.8 2207.34  5000.6 2202.14  5003.0 2198.40
  5003.5 2197.90  5018.7 2198.40  5031.0 2206.58  5051.0 2210.28  5196.0 2212.64
  5243.0 2216.16  5322.5 2215.24  5394.4 2218.20  5452.0 2217.75  5535.8 2218.88
  5576.2 2222.53  5616.5 2220.77  5667.0 2222.12  5708.5 2225.73  5757.9 2224.18
  5808.4 2229.13  5852.1 2227.35  5909.3 2232.94  5939.6 2231.13  5959.8 2231.90
#Mann=10,-1,0
  3486.1    0.07       0  3818.3    0.16       0  3842.9    0.07       0
  4451.0    0.16       0  4722.2    0.07       0  5003.0    0.07       0
  5018.7    0.07       0  5051.0   0.035       0  5322.5    0.07       0
  5452.0   0.035       0
Bank Sta=5003,5018.7
Exp/Cntr=0.3,0.1

Type RM Length L Ch R = 1,500,0,0,0
BEGIN DESCRIPTION:
Cottonwood Trib044 1.0
END DESCRIPTION:
XS GIS Cut Line= 4
      1332697.66      6880480.42      1333379.21      6882127.18
      1333505.08      6882118.43      1333904.99      6882238.00
#Sta/Elev= 30
  3091.6 2226.38  3486.3 2223.21  3537.9 2222.87  3977.6 2219.91  4084.4 2219.06
  4136.3 2219.03  4410.2 2217.54  4570.1 2216.51  4585.0 2216.31  4806.5 2212.52
  4949.8 2209.07  4959.8 2205.95  4979.9 2194.82  5013.1 2193.77  5013.6 2193.27
  5028.9 2193.77  5031.2 2199.43  5041.7 2206.61  5048.9 2208.72  5058.0 2207.91
  5114.7 2206.62  5146.0 2200.80  5166.9 2213.86  5177.4 2216.97  5191.8 2217.75
  5208.7 2214.86  5297.1 2218.07  5344.4 2220.24  5362.5 2223.79  5417.4 2223.95
#Mann=14,-1,0
  3091.6    0.07       0  3486.3    0.16       0  3537.9    0.07       0
  3977.6    0.16       0  4084.4    0.07       0  4136.3    0.16       0
  4410.2    0.07       0  4570.1    0.16       0  4585.0    0.07       0
  4806.5    0.16       0  5013.1    0.07       0  5028.9    0.16       0
  5058.0   0.035       0  5297.1    0.07       0
Bank Sta=5013.1,5028.9
Exp/Cntr=0.3,0.1

Chan Stop Cuts=-1