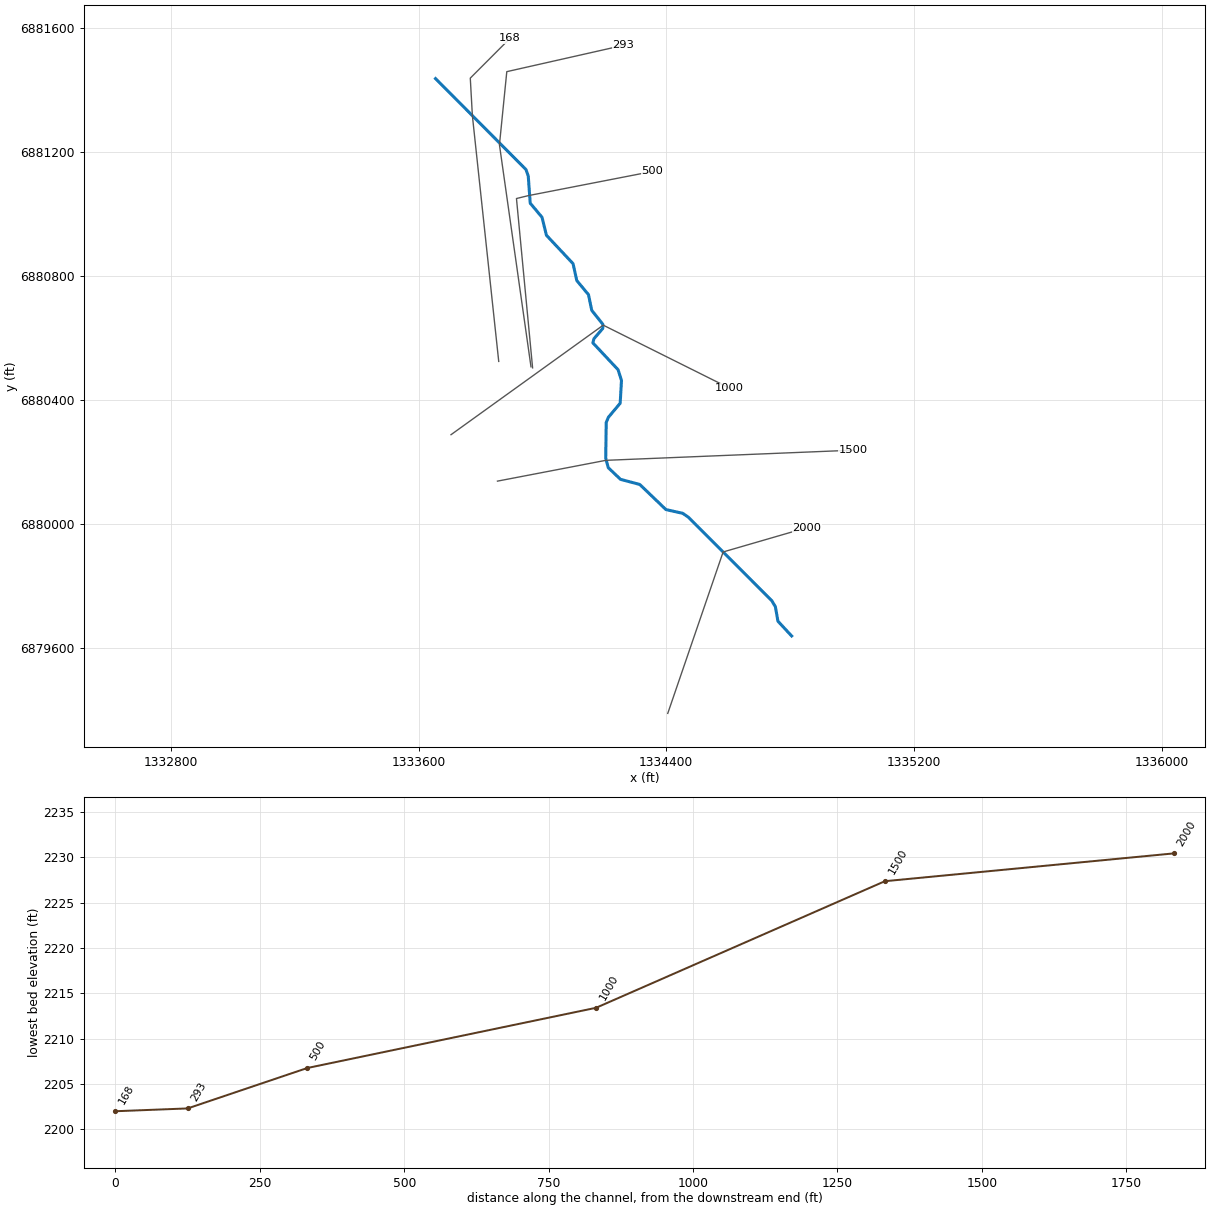
--- Cottonwood Trib044_01.prj (project) ---

Proj Title=Cottonwood Trib044_01 Base Level Engineering
Current Plan=p01
Default Exp/Contr=0.3,0.1
English Units
Geom File=g01
Flow File=f01
Plan File=p01
BEGIN DESCRIPTION:
Cottonwood Trib044_01
END DESCRIPTION:

--- Cottonwood Trib044_01.p01 (plan) ---

Plan Title=Multiple Run
Short Identifier=Multiple
Geom File=g01
Flow File=f01
Subcritical Flow
K Sum by GR= 0
Std Step Tol= 0.01
Critical Tol= 0.01
Num of Std Step Trials= 20
Max Error Tol= 0.3
Flow Tol Ratio= 0.001
Split Flow NTrial= 30
Split Flow Tol= 0.02
Split Flow Ratio= 0.02
Log Output Level= 0
Friction Slope Method= 1
Unsteady Friction Slope Method= 2
Unsteady Bridges Friction Slope Method= 1
Parabolic Critical Depth
Global Vel Dist=  1 , 1 , 1
Global Log Level= 0
CheckData=True
Encroach Param= -1, 0, 0, 0
BEGIN DESCRIPTION:
Multiple Run
END DESCRIPTION:

--- Cottonwood Trib044_01.f01 (steady flow) ---

Flow Title=Multiple
Number of Profiles=7
Profile Names=10-year,25-year,50-year,1pct_min,100-year,1pct_plu,500-year
River Rch & RM= Cottonwood Trib0,Reach-1,2000
     209     296     370     231     460     918     720
Boundary for River Rch & Prof#=Cottonwood Trib0,Reach-1,1
Up Type=0
Dn Type=3
Dn Slope=0.005
Boundary for River Rch & Prof#=Cottonwood Trib0,Reach-1,2
Up Type=0
Dn Type=3
Dn Slope=0.005
Boundary for River Rch & Prof#=Cottonwood Trib0,Reach-1,3
Up Type=0
Dn Type=3
Dn Slope=0.005
Boundary for River Rch & Prof#=Cottonwood Trib0,Reach-1,4
Up Type=0
Dn Type=3
Dn Slope=0.005
Boundary for River Rch & Prof#=Cottonwood Trib0,Reach-1,5
Up Type=0
Dn Type=3
Dn Slope=0.005
Boundary for River Rch & Prof#=Cottonwood Trib0,Reach-1,6
Up Type=0
Dn Type=3
Dn Slope=0.005
Boundary for River Rch & Prof#=Cottonwood Trib0,Reach-1,7
Up Type=0
Dn Type=3
Dn Slope=0.005

--- Cottonwood Trib044_01.g01 (geometry) ---

Geom Title=Existing Conditions

River Reach=Cottonwood Trib0,Reach-1
Reach XY= 30
      1334805.00      6879638.00      1334760.71      6879685.65
      1334752.66      6879732.03      1334741.43      6879751.23
      1334471.67      6880021.35      1334453.35      6880034.03
      1334398.96      6880046.18      1334314.65      6880127.19
      1334252.42      6880143.74      1334212.69      6880181.53
      1334204.64      6880212.80      1334206.21      6880327.49
      1334213.14      6880344.06      1334251.30      6880389.60
      1334255.49      6880463.04      1334244.52      6880497.79
      1334163.01      6880584.67      1334166.69      6880597.99
      1334195.23      6880631.27      1334195.41      6880644.55
      1334159.41      6880689.63      1334148.95      6880740.19
      1334111.11      6880785.81      1334099.15      6880840.29
      1334013.16      6880931.95      1333998.86      6880990.17
      1333960.77      6881035.68      1333954.48      6881122.78
      1333947.14      6881144.17      1333655.00      6881438.00

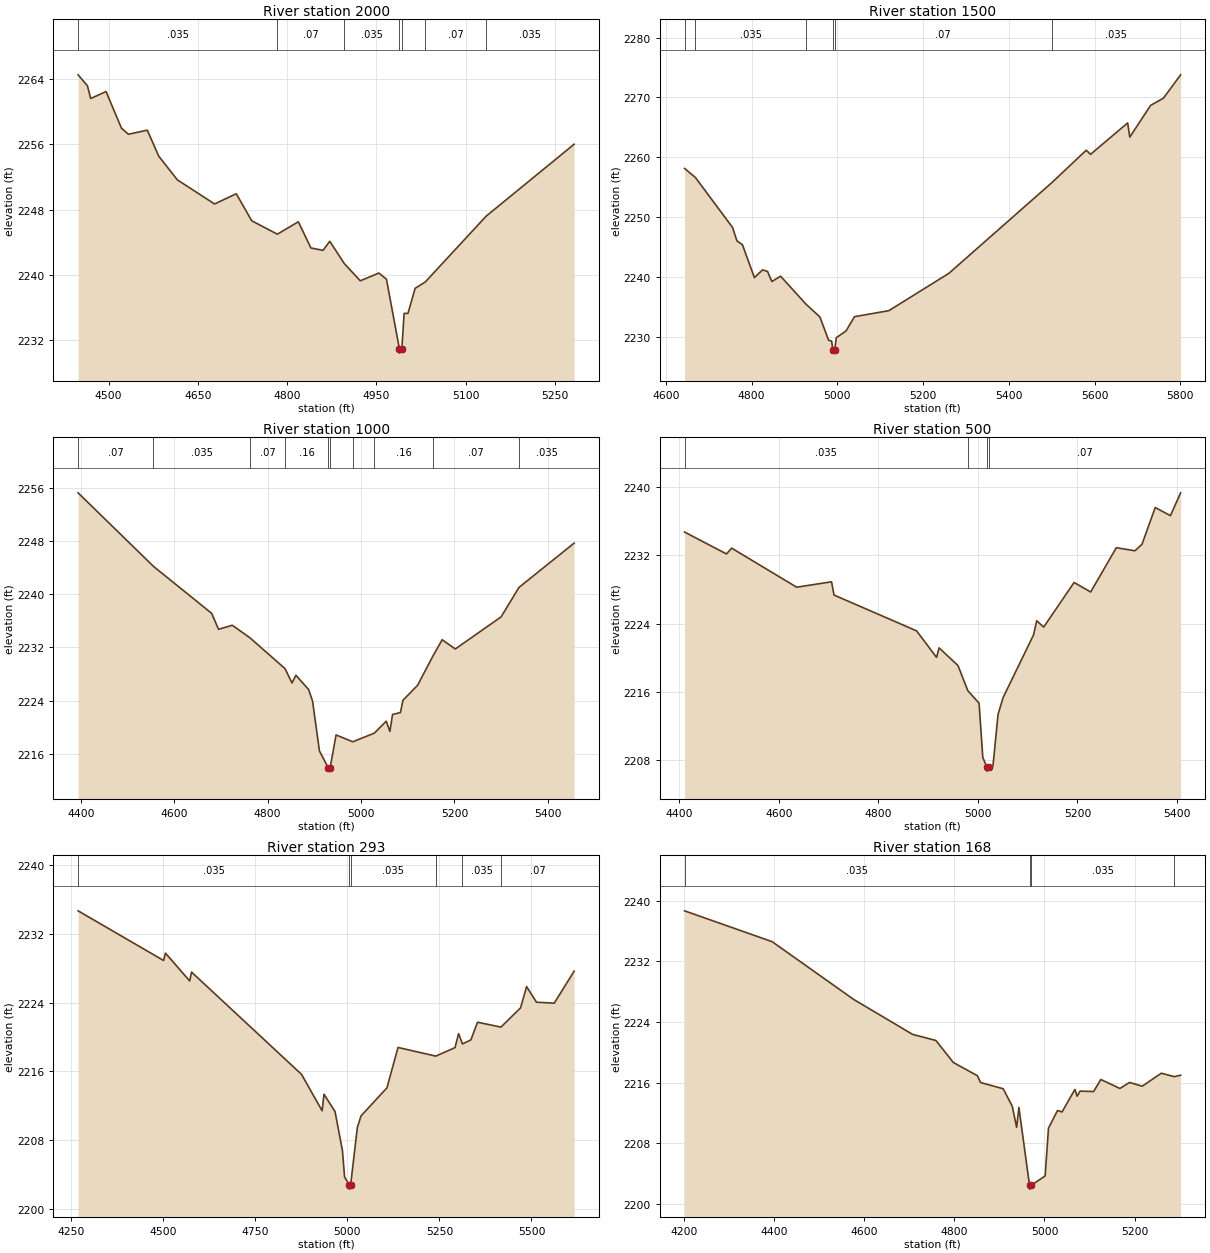
Type RM Length L Ch R = 1,2000,500,500,500
BEGIN DESCRIPTION:
Cottonwood Trib044_01 4.0
END DESCRIPTION:
XS GIS Cut Line= 3
      1334404.98      6879387.96      1334583.78      6879909.25
      1334854.98      6879987.99
#Sta/Elev= 30
  4448.9 2264.53  4464.6 2263.19  4470.1 2261.63  4495.9 2262.48  4521.8 2257.99
  4533.5 2257.25  4565.2 2257.75  4584.4 2254.57  4615.6 2251.67  4678.2 2248.71
  4714.7 2249.96  4740.7 2246.65  4783.7 2245.01  4819.0 2246.53  4840.1 2243.32
  4860.5 2243.03  4871.8 2244.14  4896.1 2241.42  4923.0 2239.30  4954.3 2240.25
  4967.0 2239.50  4988.9 2230.94  4989.1 2230.44  4992.9 2230.94  4996.7 2235.31
  5003.2 2235.31  5015.2 2238.37  5032.3 2239.16  5134.6 2247.22  5282.4 2256.03
#Mann=7,-1,0
  4448.9   0.035       0  4783.7    0.07       0  4896.1   0.035       0
  4988.9   0.035       0  4992.9   0.035       0  5032.3    0.07       0
  5134.6   0.035       0
Bank Sta=4988.9,4992.9
Exp/Cntr=0.3,0.1

Type RM Length L Ch R = 1,1500,500,500,500
BEGIN DESCRIPTION:
Cottonwood Trib044_01 3.0
END DESCRIPTION:
XS GIS Cut Line= 3
      1333855.02      6880138.00      1334205.13      6880205.18
      1335004.96      6880238.00
#Sta/Elev= 30
  4643.5 2258.17  4668.8 2256.66  4755.5 2248.32  4765.7 2246.08  4778.5 2245.45
  4806.4 2239.96  4825.4 2241.25  4837.0 2241.00  4847.1 2239.31  4867.5 2240.20
  4927.2 2235.50  4959.1 2233.41  4979.5 2229.52  4986.5 2229.38  4989.6 2227.87
  4989.8 2227.37  4993.6 2227.87  4997.4 2229.95  5019.9 2231.05  5039.9 2233.45
  5120.0 2234.45  5260.1 2240.68  5500.3 2255.81  5580.4 2261.21  5590.4 2260.52
  5677.0 2265.76  5682.0 2263.40  5730.5 2268.68  5760.5 2269.89  5800.5 2273.78
#Mann=6,-1,0
  4643.5    0.07       0  4668.8   0.035       0  4927.2    0.07       0
  4989.6    0.07       0  4993.6    0.07       0  5500.3   0.035       0
Bank Sta=4989.6,4993.6
Exp/Cntr=0.3,0.1

Type RM Length L Ch R = 1,1000,500,500,500
BEGIN DESCRIPTION:
Cottonwood Trib044_01 2.0
END DESCRIPTION:
XS GIS Cut Line= 3
      1333704.99      6880287.99      1334196.56      6880641.71
      1334604.98      6880438.01
#Sta/Elev= 30
  4394.4 2255.23  4555.7 2244.18  4680.4 2237.11  4695.1 2234.71  4724.6 2235.32
  4762.6 2233.42  4837.4 2228.80  4852.3 2226.65  4860.8 2227.80  4887.9 2225.66
  4896.4 2223.92  4911.1 2216.43  4930.0 2213.89  4930.3 2213.39  4934.0 2213.89
  4946.7 2218.83  4982.4 2217.80  5028.6 2219.10  5054.1 2220.90  5062.0 2219.37
  5067.6 2221.91  5084.4 2222.19  5090.0 2224.05  5121.2 2226.29  5154.9 2230.80
  5173.9 2233.15  5201.9 2231.75  5300.0 2236.58  5338.3 2241.01  5456.4 2247.67
#Mann=10,-1,0
  4394.4    0.07       0  4555.7   0.035       0  4762.6    0.07       0
  4837.4    0.16       0  4930.0    0.07       0  4934.0    0.16       0
  4982.4    0.07       0  5028.6    0.16       0  5154.9    0.07       0
  5338.3   0.035       0
Bank Sta=4930,4934
Exp/Cntr=0.3,0.1

Type RM Length L Ch R = 1,500,207,207,207
BEGIN DESCRIPTION:
Cottonwood Trib044_01 1.0
END DESCRIPTION:
XS GIS Cut Line= 4
      1333968.45      6880503.86      1333916.37      6881050.68
      1333955.14      6881060.12      1334355.03      6881138.00
#Sta/Elev= 30
  4410.8 2234.71  4495.1 2232.15  4505.4 2232.83  4636.0 2228.26  4706.1 2228.89
  4711.1 2227.34  4877.0 2223.15  4917.0 2220.05  4922.1 2221.16  4960.1 2219.10
  4979.9 2216.15  5002.5 2214.69  5010.0 2208.32  5018.2 2207.24  5018.5 2206.74
  5022.2 2207.24  5030.4 2207.34  5040.6 2213.37  5050.8 2215.35  5111.9 2222.67
  5118.3 2224.33  5132.3 2223.59  5193.4 2228.81  5226.7 2227.70  5278.3 2232.88
  5315.7 2232.52  5329.9 2233.29  5356.4 2237.58  5387.0 2236.63  5407.4 2239.30
#Mann=4,-1,0
  4410.8   0.035       0  4979.9    0.07       0  5018.2    0.07       0
  5022.2    0.07       0
Bank Sta=5018.2,5022.2
Exp/Cntr=0.3,0.1

Type RM Length L Ch R = 1,293,125,125,125
BEGIN DESCRIPTION:
Cottonwood Trib044_01 0.6
END DESCRIPTION:
XS GIS Cut Line= 4
      1333963.25      6880507.30      1333861.39      6881224.19
      1333885.12      6881460.41      1334260.97      6881545.27
#Sta/Elev= 30
  4269.1 2234.71  4501.3 2228.92  4506.3 2229.78  4572.1 2226.54  4577.2 2227.57
  4875.8 2215.65  4931.7 2211.41  4936.7 2213.34  4966.7 2211.32  4986.9 2206.75
  4992.6 2203.70  5005.1 2202.78  5005.3 2202.28  5009.1 2202.78  5027.2 2209.45
  5037.2 2210.81  5107.6 2214.08  5137.7 2218.79  5240.3 2217.78  5292.4 2218.77
  5302.2 2220.40  5312.7 2219.20  5335.6 2219.67  5353.5 2221.73  5417.1 2221.16
  5470.4 2223.40  5486.8 2225.88  5513.6 2224.06  5561.9 2223.95  5615.9 2227.68
#Mann=6,-1,0
  4269.1   0.035       0  5005.1   0.035       0  5009.1   0.035       0
  5240.3    0.07       0  5312.7   0.035       0  5417.1    0.07       0
Bank Sta=5005.1,5009.1
Exp/Cntr=0.3,0.1

Type RM Length L Ch R = 1,168,0,0,0
BEGIN DESCRIPTION:
Cottonwood Trib044_01 0.5
END DESCRIPTION:
XS GIS Cut Line= 4
      1333859.09      6880524.62      1333774.01      6881318.05
      1333767.22      6881439.49      1333895.51      6881568.01
#Sta/Elev= 30
  4201.0 2238.68  4395.5 2234.61  4576.5 2226.99  4707.3 2222.38  4758.9 2221.58
  4797.8 2218.67  4851.1 2216.93  4858.1 2216.03  4908.4 2215.21  4928.5 2212.89
  4938.2 2210.12  4943.2 2212.75  4966.8 2202.47  4967.0 2201.97  4970.8 2202.47
  5001.5 2203.72  5008.9 2210.02  5029.0 2212.34  5039.0 2212.15  5067.5 2215.12
  5072.5 2214.23  5079.1 2214.90  5109.1 2214.84  5125.1 2216.43  5167.5 2215.25
  5188.7 2216.04  5217.0 2215.55  5259.4 2217.26  5287.7 2216.81  5302.2 2216.99
#Mann=4,-1,0
  4201.0   0.035       0  4966.8   0.035       0  4970.8   0.035       0
  5287.7    0.07       0
Bank Sta=4966.8,4970.8
Exp/Cntr=0.3,0.1

Chan Stop Cuts=-1