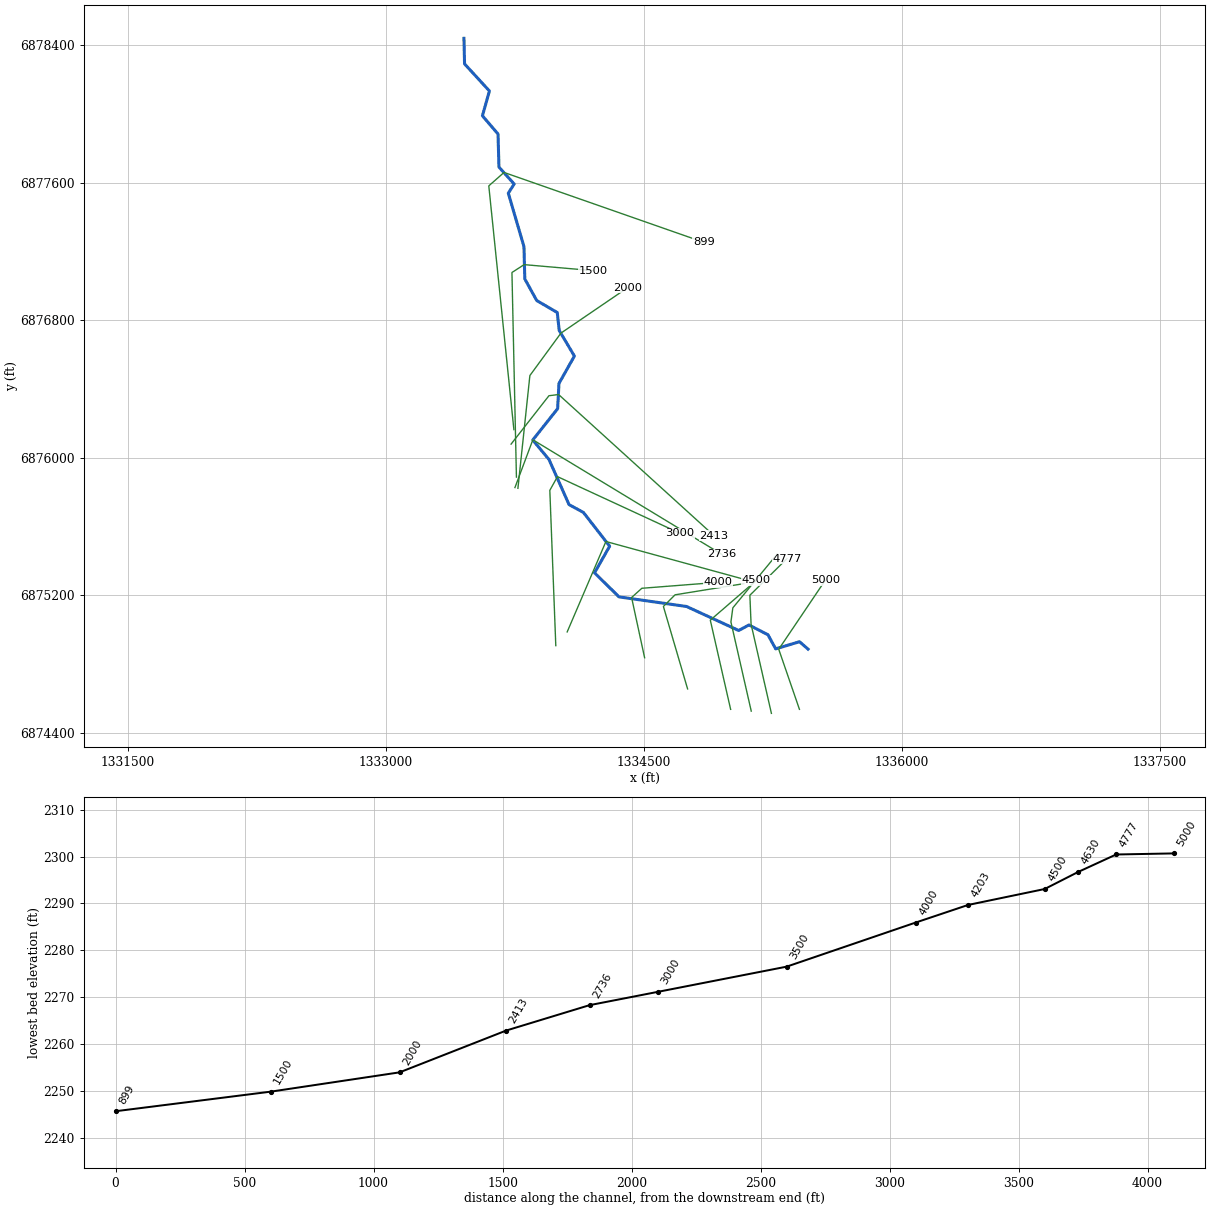
--- Cottonwood Trib044_02.prj (project) ---

Proj Title=Cottonwood Trib044_02 Base Level Engineering
Current Plan=p01
Default Exp/Contr=0.3,0.1
English Units
Geom File=g01
Flow File=f01
Plan File=p01
BEGIN DESCRIPTION:
Cottonwood Trib044_02
END DESCRIPTION:

--- Cottonwood Trib044_02.p01 (plan) ---

Plan Title=Multiple Run
Short Identifier=Multiple
Geom File=g01
Flow File=f01
Subcritical Flow
K Sum by GR= 0
Std Step Tol= 0.01
Critical Tol= 0.01
Num of Std Step Trials= 20
Max Error Tol= 0.3
Flow Tol Ratio= 0.001
Split Flow NTrial= 30
Split Flow Tol= 0.02
Split Flow Ratio= 0.02
Log Output Level= 0
Friction Slope Method= 1
Unsteady Friction Slope Method= 2
Unsteady Bridges Friction Slope Method= 1
Parabolic Critical Depth
Global Vel Dist=  1 , 1 , 1
Global Log Level= 0
CheckData=True
Encroach Param= -1, 0, 0, 0
BEGIN DESCRIPTION:
Multiple Run
END DESCRIPTION:

--- Cottonwood Trib044_02.f01 (steady flow) ---

Flow Title=Multiple
Number of Profiles=7
Profile Names=10-year,25-year,50-year,1pct_min,100-year,1pct_plu,500-year
River Rch & RM= Cottonwood Trib0,Reach-1,5000
     198     278     344     212     422     843     646
Boundary for River Rch & Prof#=Cottonwood Trib0,Reach-1,1
Up Type=0
Dn Type=3
Dn Slope=0.005
Boundary for River Rch & Prof#=Cottonwood Trib0,Reach-1,2
Up Type=0
Dn Type=3
Dn Slope=0.005
Boundary for River Rch & Prof#=Cottonwood Trib0,Reach-1,3
Up Type=0
Dn Type=3
Dn Slope=0.005
Boundary for River Rch & Prof#=Cottonwood Trib0,Reach-1,4
Up Type=0
Dn Type=3
Dn Slope=0.005
Boundary for River Rch & Prof#=Cottonwood Trib0,Reach-1,5
Up Type=0
Dn Type=3
Dn Slope=0.005
Boundary for River Rch & Prof#=Cottonwood Trib0,Reach-1,6
Up Type=0
Dn Type=3
Dn Slope=0.005
Boundary for River Rch & Prof#=Cottonwood Trib0,Reach-1,7
Up Type=0
Dn Type=3
Dn Slope=0.005

--- Cottonwood Trib044_02.g01 (geometry) ---

Geom Title=Existing Conditions

River Reach=Cottonwood Trib0,Reach-1
Reach XY= 30
      1335455.00      6874888.00      1335405.13      6874931.09
      1335266.88      6874889.53      1335222.01      6874971.43
      1335111.55      6875028.42      1335051.78      6874996.28
      1334749.07      6875135.76      1334356.47      6875191.54
      1334213.96      6875331.33      1334301.90      6875486.35
      1334149.35      6875682.37      1334065.69      6875728.02
      1333949.15      6875990.29      1333854.90      6876103.36
      1333999.53      6876285.55      1334007.25      6876432.07
      1334096.98      6876591.31      1334008.83      6876739.59
      1333997.25      6876844.45      1333877.86      6876914.16
      1333808.75      6877039.55      1333803.78      6877227.49
      1333712.81      6877538.10      1333746.99      6877591.33
      1333658.56      6877689.46      1333652.92      6877882.15
      1333562.33      6877987.90      1333603.03      6878132.11
      1333458.50      6878289.45      1333455.00      6878438.00

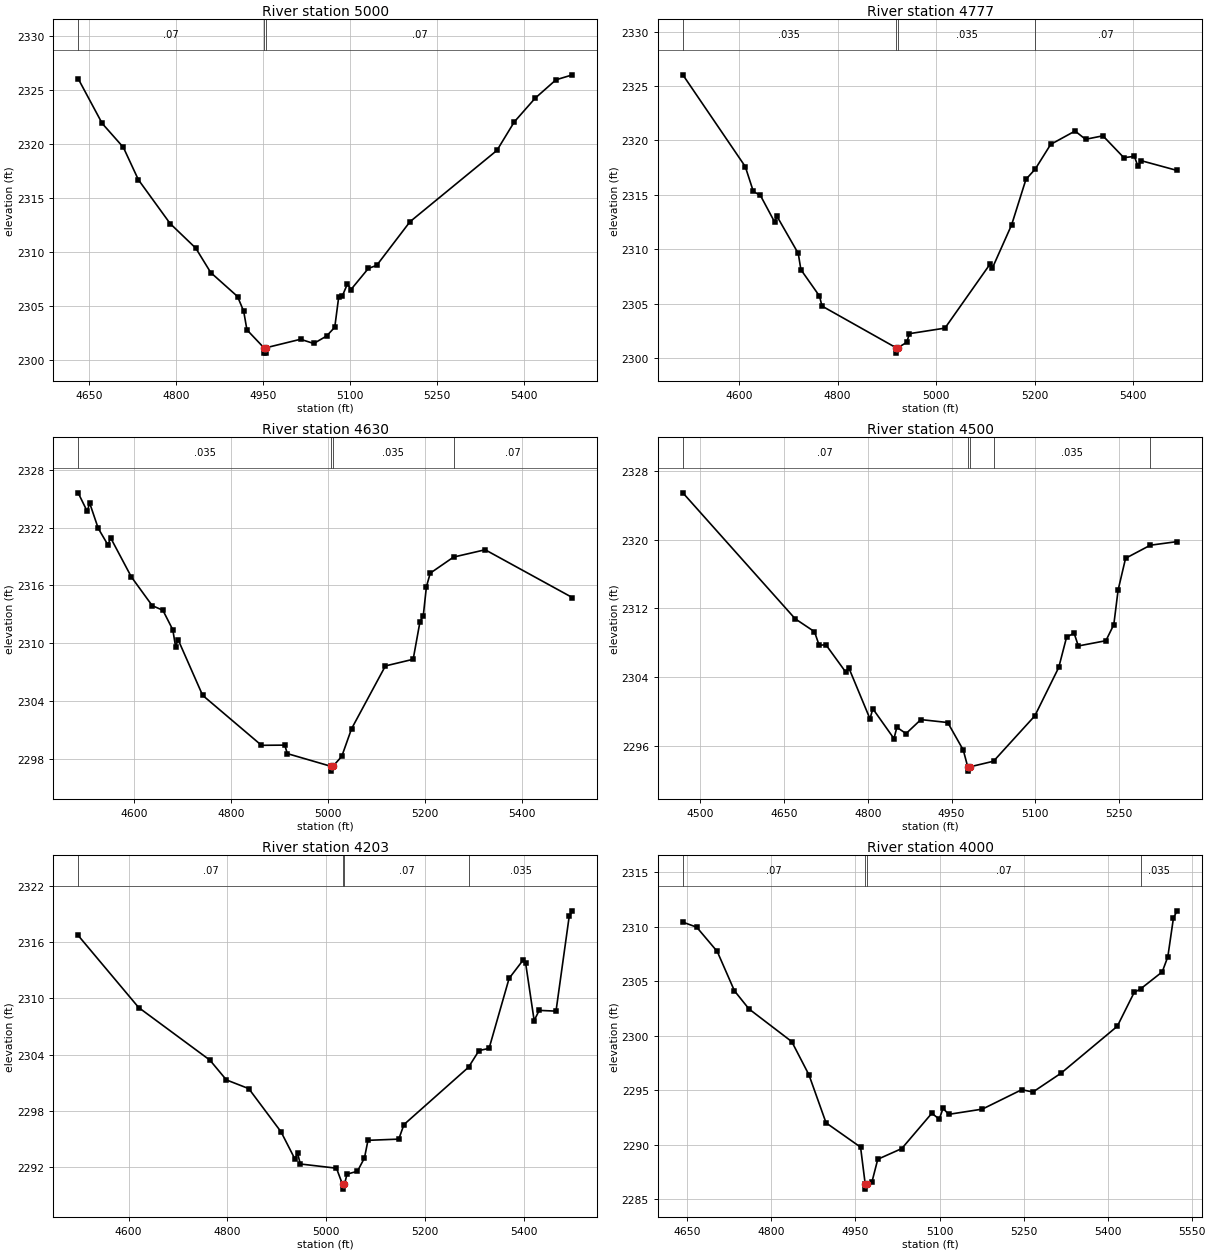
Type RM Length L Ch R = 1,5000,223,223,223
BEGIN DESCRIPTION:
Cottonwood Trib044_02 10.0
END DESCRIPTION:
XS GIS Cut Line= 3
      1335405.00      6874538.00      1335284.62      6874887.24
      1335554.98      6875287.97
#Sta/Elev= 30
  4630.6 2326.03  4672.1 2321.89  4708.6 2319.68  4734.5 2316.69  4789.3 2312.64
  4833.5 2310.37  4859.4 2308.11  4905.6 2305.90  4916.2 2304.54  4921.8 2302.82
  4951.0 2301.17  4951.3 2300.67  4954.8 2300.67  4955.0 2301.17  5014.3 2301.95
  5037.1 2301.56  5059.2 2302.25  5073.3 2303.06  5080.2 2305.89  5086.3 2305.94
  5095.2 2307.07  5101.2 2306.54  5131.2 2308.49  5145.7 2308.78  5203.1 2312.81
  5353.1 2319.40  5383.0 2322.03  5419.0 2324.22  5454.9 2325.92  5483.4 2326.38
#Mann=3,-1,0
  4630.6    0.07       0  4951.0    0.07       0  4955.0    0.07       0
Bank Sta=4951,4955
Exp/Cntr=0.3,0.1

Type RM Length L Ch R = 1,4777,147,147,147
BEGIN DESCRIPTION:
Cottonwood Trib044_02 9.6
END DESCRIPTION:
XS GIS Cut Line= 4
      1335241.98      6874514.57      1335123.84      6875032.86
      1335116.84      6875201.07      1335332.15      6875413.78
#Sta/Elev= 30
  4486.3 2326.04  4612.9 2317.60  4629.2 2315.32  4643.7 2314.94  4672.2 2312.52
  4677.4 2313.01  4720.4 2309.61  4725.7 2308.12  4763.4 2305.69  4768.5 2304.77
  4918.6 2300.94  4918.8 2300.44  4922.6 2300.94  4940.6 2301.44  4945.7 2302.23
  5017.9 2302.74  5109.2 2308.62  5114.2 2308.28  5153.1 2312.24  5182.2 2316.43
  5201.0 2317.37  5232.3 2319.64  5281.8 2320.87  5303.0 2320.11  5338.3 2320.43
  5380.7 2318.42  5402.0 2318.54  5409.0 2317.67  5416.1 2318.14  5488.9 2317.24
#Mann=4,-1,0
  4486.3   0.035       0  4918.6   0.035       0  4922.6   0.035       0
  5201.0    0.07       0
Bank Sta=4918.6,4922.6
Exp/Cntr=0.3,0.1

Type RM Length L Ch R = 1,4630,130,130,130
BEGIN DESCRIPTION:
Cottonwood Trib044_02 9.5
END DESCRIPTION:
XS GIS Cut Line= 4
      1335124.79      6874527.59      1335006.66      6875045.88
      1335017.88      6875128.15      1335275.67      6875440.63
#Sta/Elev= 30
  4484.6 2325.61  4503.3 2323.69  4508.4 2324.55  4526.0 2321.93  4546.3 2320.18
  4551.4 2320.96  4594.4 2316.88  4637.4 2313.90  4659.4 2313.42  4679.9 2311.39
  4685.6 2309.63  4690.7 2310.38  4741.4 2304.59  4862.8 2299.40  4910.9 2299.42
  4916.0 2298.54  5006.1 2297.22  5006.3 2296.72  5010.1 2297.22  5028.4 2298.25
  5048.6 2301.12  5118.4 2307.64  5175.7 2308.33  5189.8 2312.25  5196.5 2312.83
  5203.0 2315.86  5210.9 2317.27  5259.0 2318.94  5324.2 2319.70  5504.3 2314.73
#Mann=4,-1,0
  4484.6   0.035       0  5006.1   0.035       0  5010.1   0.035       0
  5259.0    0.07       0
Bank Sta=5006.1,5010.1
Exp/Cntr=0.3,0.1

Type RM Length L Ch R = 1,4500,297,297,297
BEGIN DESCRIPTION:
Cottonwood Trib044_02 9.0
END DESCRIPTION:
XS GIS Cut Line= 3
      1335005.00      6874537.99      1334886.87      6875056.30
      1335155.02      6875288.02
#Sta/Elev= 30
  4468.4 2325.43  4669.7 2310.79  4704.3 2309.29  4712.7 2307.71  4724.8 2307.77
  4760.8 2304.55  4765.9 2305.08  4803.8 2299.16  4808.9 2300.33  4846.8 2296.86
  4852.0 2298.18  4868.4 2297.44  4895.0 2299.07  4943.1 2298.73  4971.0 2295.53
  4979.0 2293.58  4979.2 2293.08  4983.0 2293.58  5025.2 2294.23  5099.3 2299.51
  5142.1 2305.13  5156.1 2308.64  5169.6 2309.13  5177.2 2307.63  5226.6 2308.24
  5240.8 2310.11  5248.5 2314.12  5261.9 2317.82  5306.2 2319.34  5354.4 2319.76
#Mann=5,-1,0
  4468.4    0.07       0  4979.0    0.07       0  4983.0    0.07       0
  5025.2   0.035       0  5306.2    0.07       0
Bank Sta=4979,4983
Exp/Cntr=0.3,0.1

Type RM Length L Ch R = 1,4203,203,203,203
BEGIN DESCRIPTION:
Cottonwood Trib044_02 8.5
END DESCRIPTION:
XS GIS Cut Line= 4
      1334754.87      6874656.75      1334614.24      6875135.96
      1334681.94      6875203.67      1335081.54      6875268.54
#Sta/Elev= 30
  4498.1 2316.72  4620.6 2309.03  4764.6 2303.43  4798.0 2301.32  4843.3 2300.39
  4908.5 2295.79  4936.7 2292.88  4941.9 2293.54  4947.5 2292.36  5020.7 2291.91
  5032.9 2290.18  5033.1 2289.68  5036.9 2290.18  5041.9 2291.27  5063.1 2291.59
  5077.3 2293.00  5084.4 2294.88  5146.7 2295.01  5157.2 2296.56  5287.8 2302.67
  5309.1 2304.45  5329.4 2304.68  5369.9 2312.14  5398.2 2314.09  5403.2 2313.81
  5420.6 2307.64  5430.7 2308.73  5464.8 2308.65  5491.5 2318.76  5498.1 2319.34
#Mann=4,-1,0
  4498.1    0.07       0  5032.9    0.07       0  5036.9    0.07       0
  5287.8   0.035       0
Bank Sta=5032.9,5036.9
Exp/Cntr=0.3,0.1

Type RM Length L Ch R = 1,4000,500,500,500
BEGIN DESCRIPTION:
Cottonwood Trib044_02 8.0
END DESCRIPTION:
XS GIS Cut Line= 4
      1334505.01      6874837.97      1334429.37      6875188.00
      1334488.84      6875241.63      1334931.61      6875276.22
#Sta/Elev= 30
  4641.9 2310.42  4666.6 2309.96  4703.3 2307.73  4734.0 2304.12  4759.9 2302.46
  4836.3 2299.46  4867.0 2296.41  4897.5 2292.01  4959.1 2289.78  4967.3 2286.43
  4967.6 2285.93  4971.3 2286.43  4979.5 2286.61  4989.8 2288.67  5032.6 2289.65
  5086.3 2292.89  5099.5 2292.35  5106.3 2293.34  5116.4 2292.79  5176.5 2293.27
  5246.7 2295.05  5266.8 2294.84  5317.0 2296.57  5417.3 2300.87  5447.4 2303.97
  5459.2 2304.31  5497.5 2305.86  5507.5 2307.25  5517.6 2310.83  5524.2 2311.46
#Mann=4,-1,0
  4641.9    0.07       0  4967.3    0.07       0  4971.3    0.07       0
  5459.2   0.035       0
Bank Sta=4967.3,4971.3
Exp/Cntr=0.3,0.1

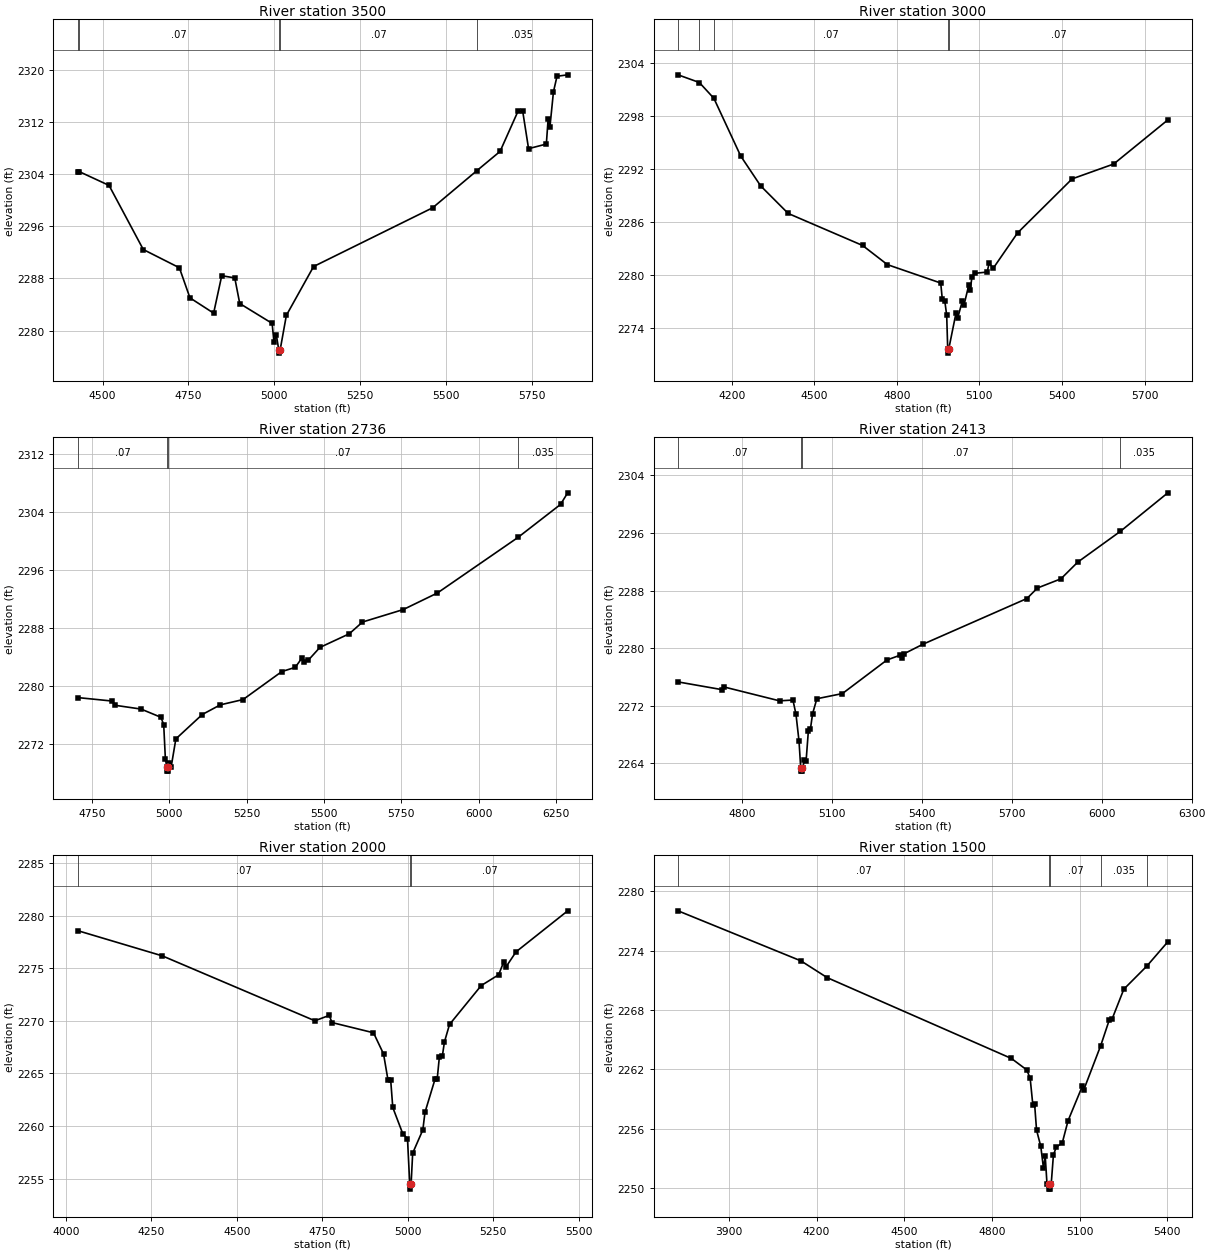
Type RM Length L Ch R = 1,3500,500,500,500
BEGIN DESCRIPTION:
Cottonwood Trib044_02 7.0
END DESCRIPTION:
XS GIS Cut Line= 3
      1334054.98      6874987.96      1334280.17      6875513.55
      1335104.99      6875288.00
#Sta/Elev= 30
  4428.2 2304.37  4432.7 2304.39  4518.9 2302.29  4618.7 2292.44  4723.8 2289.64
  4754.6 2285.02  4823.6 2282.67  4847.2 2288.42  4885.2 2288.08  4899.7 2284.15
  4994.0 2281.10  4999.5 2278.18  5006.1 2279.37  5013.4 2277.03  5013.6 2276.53
  5017.4 2277.03  5035.5 2282.33  5114.8 2289.83  5461.7 2298.85  5590.5 2304.55
  5658.1 2307.51  5710.0 2313.64  5724.0 2313.69  5741.1 2307.93  5792.9 2308.64
  5798.2 2312.55  5803.4 2311.29  5813.6 2316.66  5824.0 2319.05  5855.1 2319.27
#Mann=5,-1,0
  4428.2   0.035       0  4432.7    0.07       0  5013.4    0.07       0
  5017.4    0.07       0  5590.5   0.035       0
Bank Sta=5013.4,5017.4
Exp/Cntr=0.3,0.1

Type RM Length L Ch R = 1,3000,264,264,264
BEGIN DESCRIPTION:
Cottonwood Trib044_02 6.0
END DESCRIPTION:
XS GIS Cut Line= 4
      1333988.84      6874908.25      1333954.12      6875811.08
      1333998.72      6875890.52      1334710.58      6875561.30
#Sta/Elev= 30
  4005.4 2302.63  4082.8 2301.76  4135.6 2299.97  4232.9 2293.45  4305.4 2290.07
  4405.4 2286.95  4675.6 2283.33  4765.7 2281.16  4959.4 2279.08  4965.1 2277.27
  4974.2 2277.05  4981.1 2275.44  4984.8 2271.65  4985.0 2271.15  4988.8 2271.65
  5015.2 2275.72  5020.7 2275.09  5038.1 2277.05  5043.6 2276.55  5061.0 2278.80
  5066.5 2278.33  5073.0 2279.77  5084.0 2280.18  5128.1 2280.32  5135.3 2281.34
  5150.2 2280.75  5238.3 2284.74  5436.6 2290.86  5587.5 2292.54  5784.3 2297.53
#Mann=5,-1,0
  4005.4    0.07       0  4082.8   0.035       0  4135.6    0.07       0
  4984.8    0.07       0  4988.8    0.07       0
Bank Sta=4984.8,4988.8
Exp/Cntr=0.3,0.1

Type RM Length L Ch R = 1,2736,323,323,323
BEGIN DESCRIPTION:
Cottonwood Trib044_02 5.0
END DESCRIPTION:
XS GIS Cut Line= 3
      1333751.34      6875826.96      1333855.51      6876104.74
      1334954.98      6875438.01
#Sta/Elev= 30
  4705.0 2278.45  4816.7 2277.97  4823.6 2277.40  4909.0 2276.87  4973.1 2275.74
  4982.2 2274.74  4987.6 2270.02  4992.5 2268.82  4992.7 2268.32  4996.2 2268.32
  4996.5 2268.82  5000.7 2269.39  5006.0 2268.82  5021.5 2272.76  5106.8 2276.12
  5165.0 2277.45  5238.6 2278.18  5363.6 2282.03  5407.3 2282.62  5428.6 2283.89
  5434.5 2283.40  5450.0 2283.63  5486.8 2285.36  5581.8 2287.24  5624.5 2288.86
  5756.3 2290.58  5866.5 2292.86  6126.7 2300.51  6264.3 2305.06  6287.5 2306.66
#Mann=4,-1,0
  4705.0    0.07       0  4992.5    0.07       0  4996.5    0.07       0
  6126.7   0.035       0
Bank Sta=4992.5,4996.5
Exp/Cntr=0.3,0.1

Type RM Length L Ch R = 1,2413,413,413,413
BEGIN DESCRIPTION:
Cottonwood Trib044_02 5.5
END DESCRIPTION:
XS GIS Cut Line= 4
      1333728.92      6876079.55      1333949.00      6876360.83
      1334005.25      6876367.76      1334908.51      6875547.42
#Sta/Elev= 30
  4586.5 2275.31  4732.4 2274.24  4738.8 2274.62  4925.0 2272.68  4969.8 2272.79
  4979.9 2270.82  4990.0 2267.11  4995.7 2263.41  4995.9 2262.91  4999.4 2262.91
  4999.7 2263.41  5003.5 2263.41  5007.1 2264.52  5013.8 2264.38  5021.3 2268.53
  5028.0 2268.73  5035.4 2270.90  5049.6 2272.97  5134.8 2273.69  5283.5 2278.36
  5325.3 2278.99  5332.8 2278.60  5339.5 2279.20  5403.7 2280.55  5750.4 2286.90
  5785.5 2288.36  5863.9 2289.64  5920.0 2291.96  6062.3 2296.24  6220.5 2301.59
#Mann=4,-1,0
  4586.5    0.07       0  4995.7    0.07       0  4999.7    0.07       0
  6062.3   0.035       0
Bank Sta=4995.7,4999.7
Exp/Cntr=0.3,0.1

Type RM Length L Ch R = 1,2000,500,500,500
BEGIN DESCRIPTION:
Cottonwood Trib044_02 4.0
END DESCRIPTION:
XS GIS Cut Line= 4
      1333768.70      6875822.61      1333838.15      6876478.00
      1334018.83      6876724.77      1334405.04      6876988.03
#Sta/Elev= 30
  4035.1 2278.56  4281.9 2276.17  4728.1 2270.00  4769.9 2270.51  4778.3 2269.83
  4899.5 2268.86  4928.9 2266.85  4942.0 2264.35  4949.7 2264.40  4955.9 2261.76
  4985.2 2259.26  4998.9 2258.79  5005.5 2254.50  5005.7 2254.00  5009.5 2254.50
  5014.1 2257.42  5043.8 2259.63  5050.0 2261.29  5079.8 2264.49  5085.9 2264.50
  5092.2 2266.58  5100.8 2266.63  5106.9 2267.98  5121.8 2269.65  5214.6 2273.35
  5265.4 2274.37  5280.4 2275.60  5286.4 2275.09  5316.3 2276.55  5467.4 2280.45
#Mann=3,-1,0
  4035.1    0.07       0  5005.5    0.07       0  5009.5    0.07       0
Bank Sta=5005.5,5009.5
Exp/Cntr=0.3,0.1

Type RM Length L Ch R = 1,1500,601,601,601
BEGIN DESCRIPTION:
Cottonwood Trib044_02 3.0
END DESCRIPTION:
XS GIS Cut Line= 4
      1333760.02      6875887.74      1333733.98      6877076.96
      1333804.88      6877122.73      1334204.98      6877088.00
#Sta/Elev= 30
  3726.1 2278.02  4146.5 2272.96  4236.5 2271.26  4866.6 2263.09  4919.2 2261.93
  4930.7 2261.07  4939.9 2258.36  4945.9 2258.46  4952.5 2255.85  4967.0 2254.20
  4976.2 2251.99  4982.2 2253.19  4988.2 2250.42  4995.1 2250.38  4995.3 2249.88
  4998.8 2249.88  4999.1 2250.38  5002.6 2250.38  5010.2 2253.33  5020.2 2254.15
  5040.3 2254.53  5060.3 2256.80  5109.0 2260.28  5114.0 2259.92  5172.1 2264.40
  5200.9 2266.95  5210.9 2267.08  5251.1 2270.10  5329.7 2272.43  5401.6 2274.89
#Mann=5,-1,0
  3726.1    0.07       0  4995.1    0.07       0  4999.1    0.07       0
  5172.1   0.035       0  5329.7    0.07       0
Bank Sta=4995.1,4999.1
Exp/Cntr=0.3,0.1

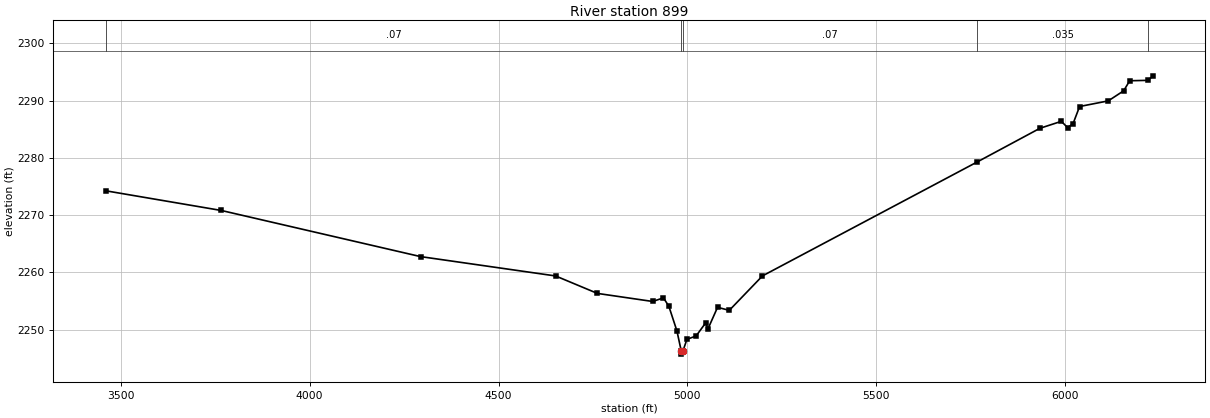
Type RM Length L Ch R = 1,899,0,0,0
BEGIN DESCRIPTION:
Cottonwood Trib044_02 1.0
END DESCRIPTION:
XS GIS Cut Line= 4
      1333745.27      6876163.75      1333599.43      6877580.43
      1333687.97      6877658.56      1334848.47      6877252.64
#Sta/Elev= 30
  3460.6 2274.25  3766.5 2270.81  4293.8 2262.75  4651.1 2259.37  4761.7 2256.32
  4908.0 2254.91  4936.4 2255.54  4950.7 2254.10  4972.2 2249.76  4983.8 2246.21
  4984.0 2245.71  4987.8 2246.21  4998.7 2248.30  5022.9 2248.88  5048.7 2251.21
  5054.0 2250.07  5079.7 2253.89  5110.8 2253.36  5198.6 2259.38  5767.2 2279.30
  5932.8 2285.17  5989.6 2286.39  6006.1 2285.29  6020.6 2285.98  6037.9 2288.98
  6113.7 2289.96  6154.5 2291.72  6170.5 2293.48  6218.7 2293.55  6232.3 2294.34
#Mann=5,-1,0
  3460.6    0.07       0  4983.8    0.07       0  4987.8    0.07       0
  5767.2   0.035       0  6218.7    0.07       0
Bank Sta=4983.8,4987.8
Exp/Cntr=0.3,0.1

Chan Stop Cuts=-1