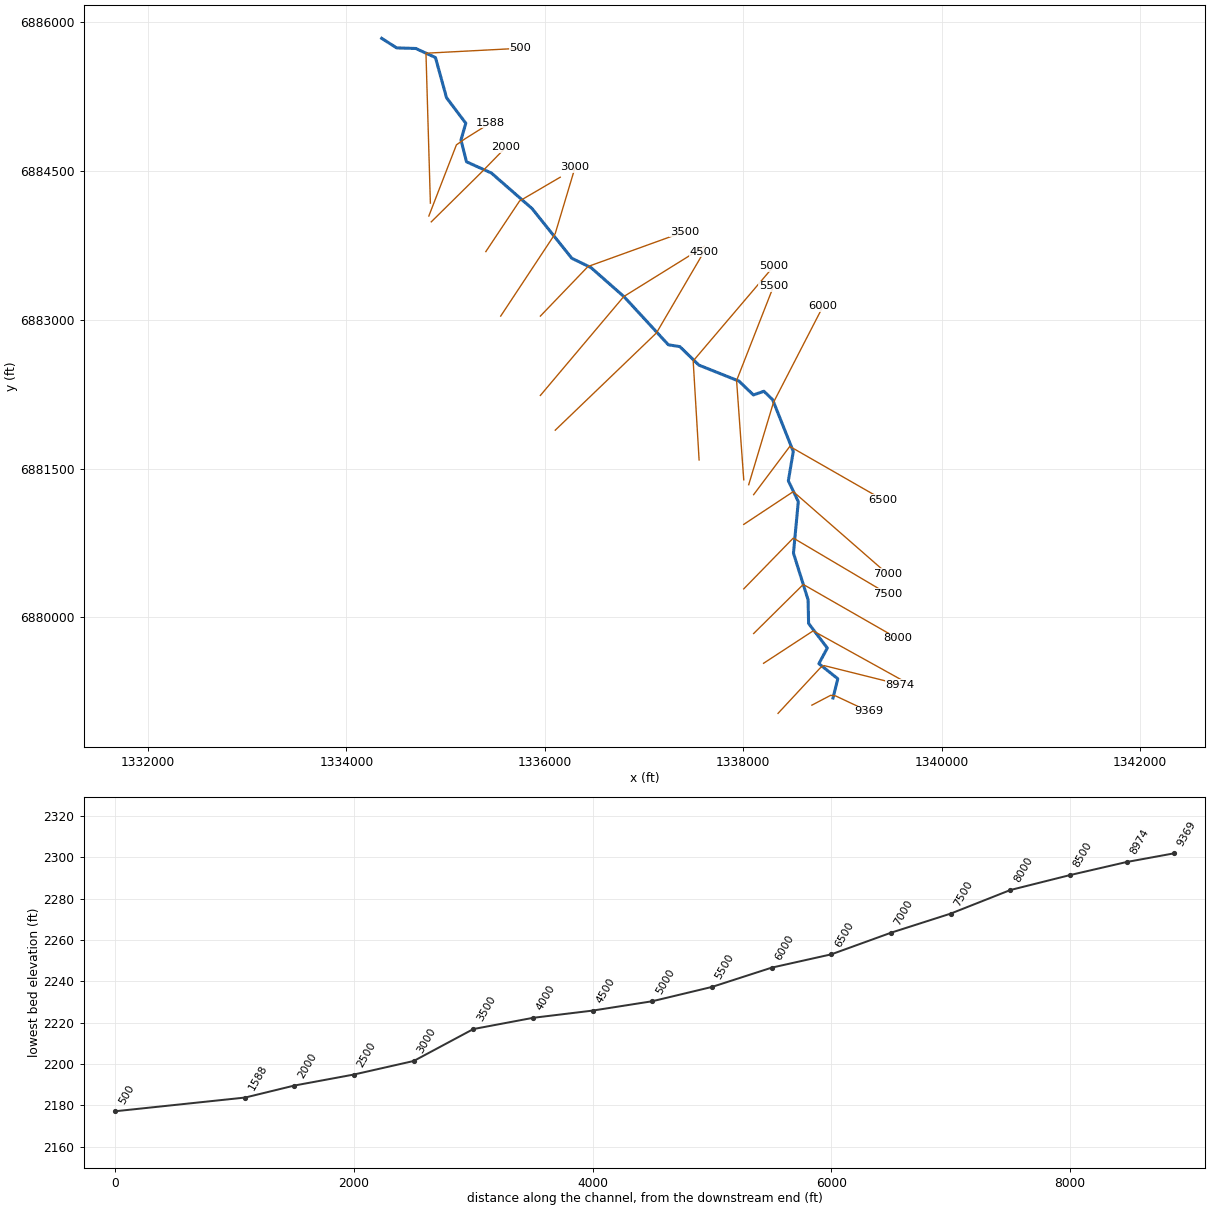
--- Cottonwood Trib048.prj (project) ---

Proj Title=Cottonwood Trib048 Base Level Engineering
Current Plan=p01
Default Exp/Contr=0.3,0.1
English Units
Geom File=g01
Flow File=f01
Plan File=p01
BEGIN DESCRIPTION:
Cottonwood Trib048
END DESCRIPTION:

--- Cottonwood Trib048.p01 (plan) ---

Plan Title=Multiple Run
Short Identifier=Multiple
Geom File=g01
Flow File=f01
Subcritical Flow
K Sum by GR= 0
Std Step Tol= 0.01
Critical Tol= 0.01
Num of Std Step Trials= 20
Max Error Tol= 0.3
Flow Tol Ratio= 0.001
Split Flow NTrial= 30
Split Flow Tol= 0.02
Split Flow Ratio= 0.02
Log Output Level= 0
Friction Slope Method= 1
Unsteady Friction Slope Method= 2
Unsteady Bridges Friction Slope Method= 1
Parabolic Critical Depth
Global Vel Dist=  1 , 1 , 1
Global Log Level= 0
CheckData=True
Encroach Param= -1, 0, 0, 0
BEGIN DESCRIPTION:
Multiple Run
END DESCRIPTION:

--- Cottonwood Trib048.f01 (steady flow) ---

Flow Title=Multiple
Number of Profiles=7
Profile Names=10-year,25-year,50-year,1pct_min,100-year,1pct_plu,500-year
River Rch & RM= Cottonwood Trib0,Reach-1,9369
     263     375     470     294     586    1169     921
River Rch & RM= Cottonwood Trib0,Reach-1,4500
     361     526     667     421     840    1676    1350
Boundary for River Rch & Prof#=Cottonwood Trib0,Reach-1,1
Up Type=0
Dn Type=3
Dn Slope=0.005
Boundary for River Rch & Prof#=Cottonwood Trib0,Reach-1,2
Up Type=0
Dn Type=3
Dn Slope=0.005
Boundary for River Rch & Prof#=Cottonwood Trib0,Reach-1,3
Up Type=0
Dn Type=3
Dn Slope=0.005
Boundary for River Rch & Prof#=Cottonwood Trib0,Reach-1,4
Up Type=0
Dn Type=3
Dn Slope=0.005
Boundary for River Rch & Prof#=Cottonwood Trib0,Reach-1,5
Up Type=0
Dn Type=3
Dn Slope=0.005
Boundary for River Rch & Prof#=Cottonwood Trib0,Reach-1,6
Up Type=0
Dn Type=3
Dn Slope=0.005
Boundary for River Rch & Prof#=Cottonwood Trib0,Reach-1,7
Up Type=0
Dn Type=3
Dn Slope=0.005

--- Cottonwood Trib048.g01 (geometry) ---

Geom Title=Existing Conditions

River Reach=Cottonwood Trib0,Reach-1
Reach XY= 30
      1338905.00      6879188.00      1338953.04      6879382.12
      1338762.67      6879534.34      1338847.30      6879691.64
      1338658.75      6879939.55      1338653.78      6880177.50
      1338506.22      6880648.50      1338554.94      6881167.97
      1338454.50      6881377.83      1338504.49      6881672.78
      1338296.84      6882194.09      1338208.42      6882280.19
      1338102.71      6882243.12      1337957.30      6882382.17
      1337552.64      6882543.75      1337361.19      6882730.14
      1337245.21      6882748.52      1336799.39      6883232.41
      1336464.68      6883527.24      1336271.42      6883620.92
      1335871.67      6884121.35      1335461.17      6884480.14
      1335210.19      6884593.44      1335154.60      6884813.00
      1335203.04      6884982.11      1335008.76      6885239.56
      1334897.32      6885644.52      1334699.06      6885735.74
      1334506.46      6885741.54      1334355.00      6885838.00

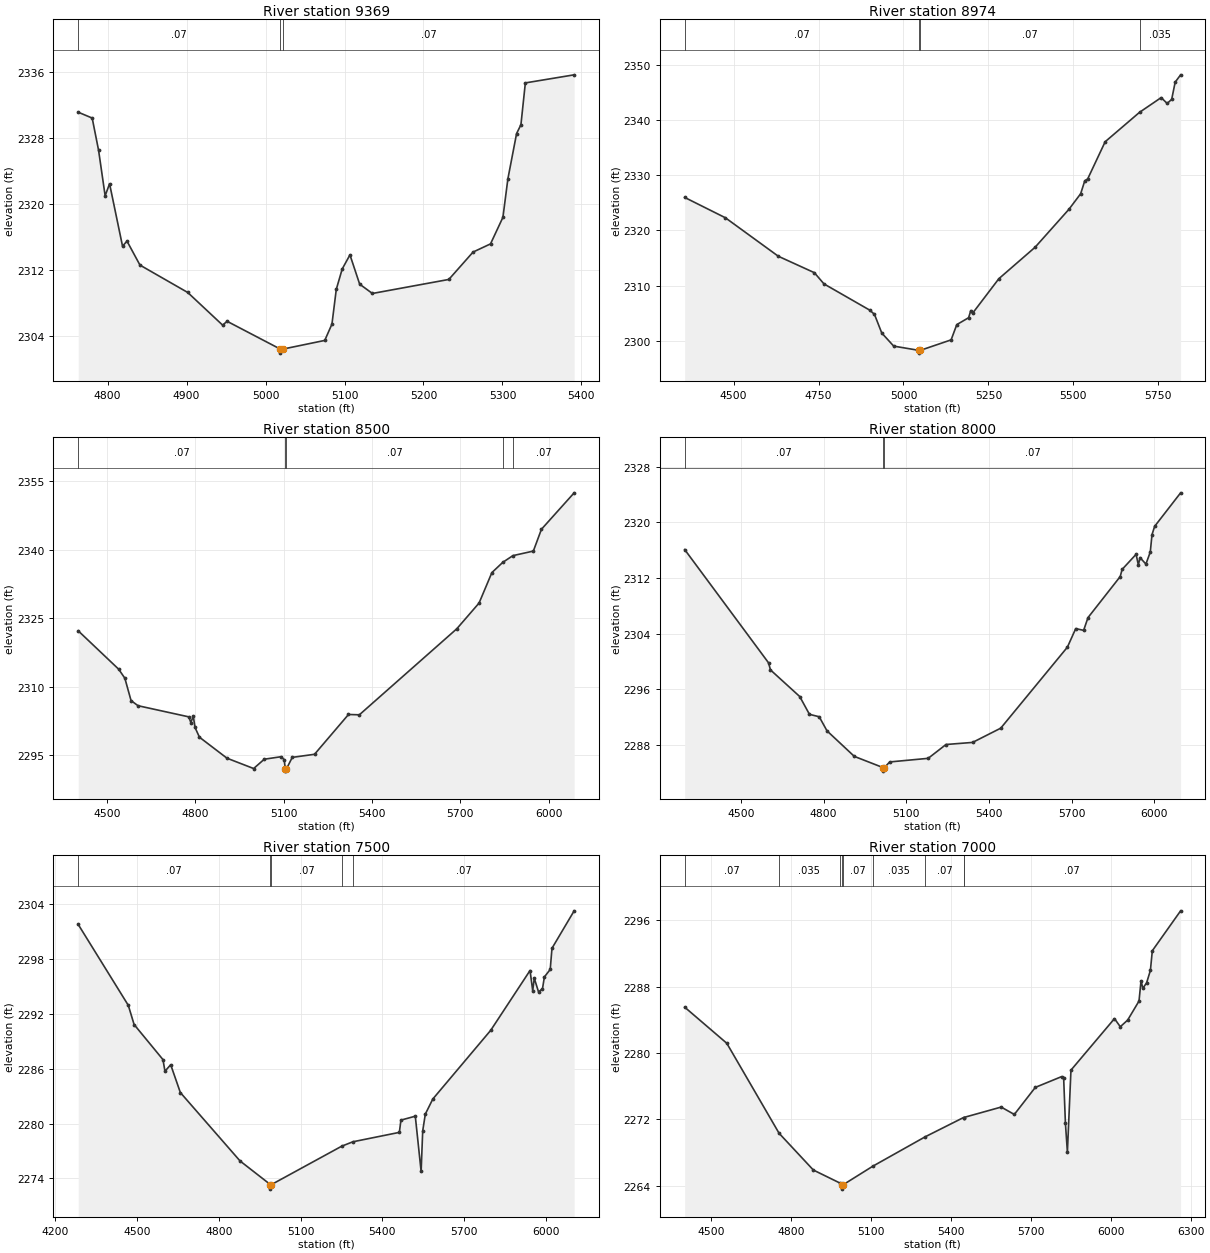
Type RM Length L Ch R = 1,9369,395,395,395
BEGIN DESCRIPTION:
Cottonwood Trib048 18.0
END DESCRIPTION:
XS GIS Cut Line= 4
      1338692.13      6879115.96      1338881.45      6879215.18
      1338931.90      6879208.56      1339260.93      6879054.35
#Sta/Elev= 30
  4762.8 2331.15  4780.5 2330.44  4788.6 2326.53  4796.9 2321.02  4802.5 2322.48
  4818.9 2314.92  4824.6 2315.52  4841.0 2312.62  4901.5 2309.30  4945.7 2305.34
  4951.3 2305.81  5018.5 2302.45  5018.7 2301.95  5022.5 2302.45  5075.0 2303.49
  5084.1 2305.47  5089.6 2309.68  5097.1 2312.15  5106.9 2313.86  5119.2 2310.31
  5135.3 2309.18  5232.1 2310.88  5262.8 2314.20  5284.9 2315.19  5300.6 2318.41
  5306.9 2323.08  5317.9 2328.56  5323.4 2329.63  5329.0 2334.70  5390.8 2335.68
#Mann=3,-1,0
  4762.8    0.07       0  5018.5    0.07       0  5022.5    0.07       0
Bank Sta=5018.5,5022.5
Exp/Cntr=0.3,0.1

Type RM Length L Ch R = 1,8974,474,474,474
BEGIN DESCRIPTION:
Cottonwood Trib048 17.0
END DESCRIPTION:
XS GIS Cut Line= 4
      1338350.56      6879033.00      1338775.91      6879490.90
      1338814.98      6879514.77      1339580.49      6879323.94
#Sta/Elev= 30
  4356.1 2325.96  4475.9 2322.28  4631.8 2315.31  4737.8 2312.34  4766.1 2310.31
  4900.5 2305.57  4914.7 2304.80  4936.2 2301.42  4971.3 2299.05  5045.5 2298.28
  5045.7 2297.78  5049.5 2298.28  5140.3 2300.18  5157.0 2302.94  5191.8 2304.19
  5198.2 2305.47  5203.4 2304.99  5280.8 2311.25  5387.6 2316.95  5487.2 2323.82
  5521.6 2326.63  5533.7 2328.97  5542.2 2329.30  5593.7 2336.04  5695.0 2341.37
  5758.6 2344.03  5776.2 2342.97  5789.5 2343.71  5799.8 2346.83  5815.8 2348.15
#Mann=4,-1,0
  4356.1    0.07       0  5045.5    0.07       0  5049.5    0.07       0
  5695.0   0.035       0
Bank Sta=5045.5,5049.5
Exp/Cntr=0.3,0.1

Type RM Length L Ch R = 1,8500,500,500,500
BEGIN DESCRIPTION:
Cottonwood Trib048 16.0
END DESCRIPTION:
XS GIS Cut Line= 3
      1338205.04      6879538.02      1338704.81      6879864.76
      1339654.97      6879338.01
#Sta/Elev= 30
  4402.9 2322.20  4540.1 2313.80  4561.2 2311.82  4582.3 2306.91  4606.0 2305.79
  4778.3 2303.35  4785.2 2302.10  4793.5 2303.51  4799.4 2301.02  4814.5 2298.89
  4908.0 2294.29  4998.4 2292.03  5034.5 2294.07  5091.8 2294.62  5102.1 2293.96
  5105.8 2291.96  5106.0 2291.46  5109.8 2291.96  5129.5 2294.47  5205.1 2295.15
  5320.4 2303.87  5357.3 2303.80  5688.1 2322.65  5763.7 2328.29  5807.1 2334.95
  5844.3 2337.21  5878.5 2338.67  5947.9 2339.67  5975.4 2344.45  6086.4 2352.43
#Mann=5,-1,0
  4402.9    0.07       0  5105.8    0.07       0  5109.8    0.07       0
  5844.3   0.035       0  5878.5    0.07       0
Bank Sta=5105.8,5109.8
Exp/Cntr=0.3,0.1

Type RM Length L Ch R = 1,8000,500,500,500
BEGIN DESCRIPTION:
Cottonwood Trib048 15.0
END DESCRIPTION:
XS GIS Cut Line= 3
      1338104.99      6879837.99      1338605.24      6880332.76
      1339555.00      6879788.00
#Sta/Elev= 30
  4296.4 2316.10  4600.5 2299.81  4607.5 2298.79  4713.6 2294.96  4748.9 2292.40
  4784.3 2292.05  4812.6 2290.02  4911.6 2286.35  5016.3 2284.73  5016.6 2284.23
  5020.3 2284.73  5039.9 2285.55  5179.4 2286.07  5244.1 2288.06  5340.5 2288.36
  5442.6 2290.41  5684.3 2302.06  5714.5 2304.73  5743.2 2304.48  5759.0 2306.31
  5875.9 2312.22  5882.7 2313.24  5933.5 2315.42  5941.7 2313.87  5947.5 2314.95
  5969.1 2314.01  5984.9 2315.75  5991.1 2318.24  6000.7 2319.44  6094.9 2324.26
#Mann=3,-1,0
  4296.4    0.07       0  5016.3    0.07       0  5020.3    0.07       0
Bank Sta=5016.3,5020.3
Exp/Cntr=0.3,0.1

Type RM Length L Ch R = 1,7500,500,500,500
BEGIN DESCRIPTION:
Cottonwood Trib048 14.0
END DESCRIPTION:
XS GIS Cut Line= 3
      1338005.01      6880288.01      1338504.86      6880800.51
      1339455.03      6880237.98
#Sta/Elev= 30
  4284.1 2301.78  4467.9 2292.93  4489.2 2290.83  4595.2 2286.99  4602.4 2285.72
  4623.5 2286.43  4658.9 2283.39  4878.1 2275.90  4989.3 2273.32  4989.5 2272.82
  4993.3 2273.32  5251.3 2277.52  5292.1 2278.00  5462.7 2279.03  5468.5 2280.37
  5521.2 2280.80  5542.6 2274.75  5548.4 2279.19  5558.0 2281.03  5585.5 2282.68
  5798.1 2290.20  5942.3 2296.74  5952.1 2294.54  5957.9 2295.89  5973.5 2294.40
  5988.0 2294.75  5995.0 2296.04  6016.4 2296.86  6022.8 2299.17  6104.2 2303.27
#Mann=5,-1,0
  4284.1    0.07       0  4989.3    0.07       0  4993.3    0.07       0
  5251.3   0.035       0  5292.1    0.07       0
Bank Sta=4989.3,4993.3
Exp/Cntr=0.3,0.1

Type RM Length L Ch R = 1,7000,500,500,500
BEGIN DESCRIPTION:
Cottonwood Trib048 13.0
END DESCRIPTION:
XS GIS Cut Line= 3
      1338004.99      6880937.99      1338504.46      6881268.47
      1339454.98      6880438.02
#Sta/Elev= 30
  4401.1 2285.51  4559.1 2281.16  4755.4 2270.31  4884.0 2265.88  4982.7 2264.33
  4990.4 2264.08  4990.6 2263.58  4994.4 2264.08  5107.0 2266.34  5303.9 2269.89
  5447.7 2272.21  5448.1 2272.21  5588.8 2273.47  5638.1 2272.58  5716.9 2275.84
  5815.6 2277.14  5823.2 2277.03  5829.9 2271.51  5837.3 2268.05  5850.7 2277.92
  6014.0 2284.13  6035.8 2283.15  6063.4 2283.95  6106.1 2286.25  6113.7 2288.70
  6120.3 2287.78  6134.6 2288.44  6148.8 2289.94  6156.0 2292.31  6262.2 2297.12
#Mann=9,-1,0
  4401.1    0.07       0  4755.4   0.035       0  4982.7    0.07       0
  4990.4    0.07       0  4994.4    0.07       0  5107.0   0.035       0
  5303.9    0.07       0  5447.7   0.035       0  5448.1    0.07       0
Bank Sta=4990.4,4994.4
Exp/Cntr=0.3,0.1

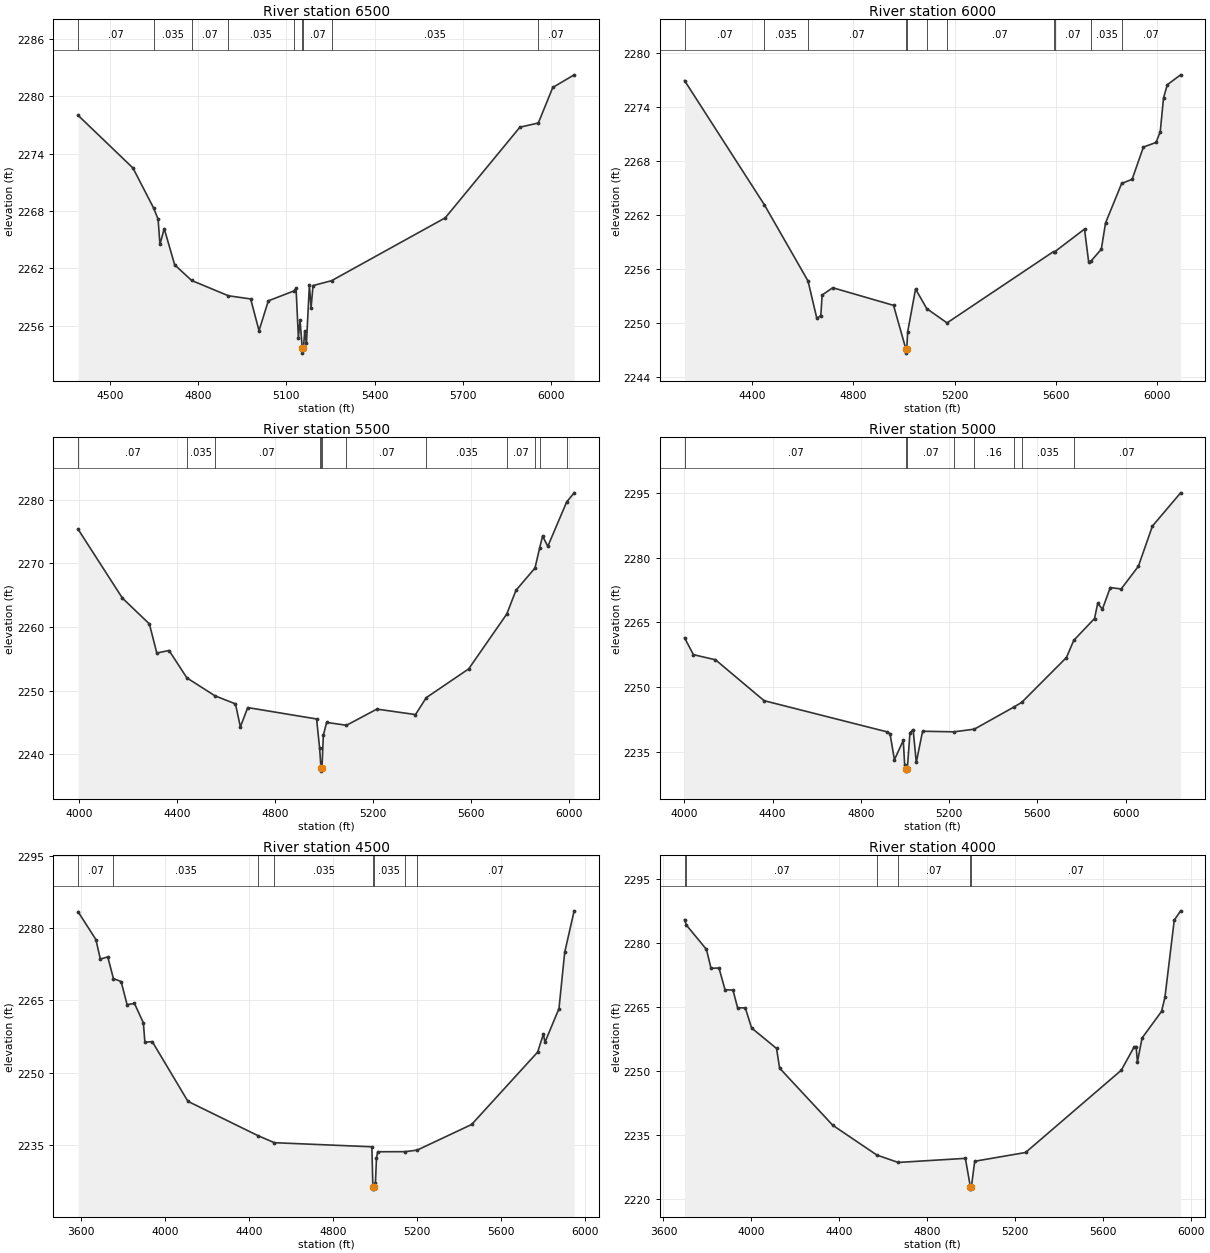
Type RM Length L Ch R = 1,6500,500,500,500
BEGIN DESCRIPTION:
Cottonwood Trib048 12.0
END DESCRIPTION:
XS GIS Cut Line= 3
      1338104.99      6881237.99      1338469.41      6881724.18
      1339404.97      6881188.02
#Sta/Elev= 30
  4392.4 2278.01  4578.9 2272.50  4648.8 2268.33  4664.3 2267.15  4670.6 2264.50
  4685.1 2266.16  4720.6 2262.37  4778.4 2260.73  4903.4 2259.13  4978.9 2258.80
  5007.3 2255.48  5038.9 2258.60  5126.1 2259.64  5133.2 2259.91  5141.1 2254.76
  5146.8 2256.56  5154.3 2253.63  5154.5 2253.13  5158.3 2253.63  5162.6 2255.45
  5168.4 2254.14  5178.5 2260.23  5184.2 2257.87  5190.9 2260.20  5254.0 2260.71
  5640.3 2267.29  5893.9 2276.77  5956.6 2277.21  6005.7 2280.93  6078.3 2282.25
#Mann=9,-1,0
  4392.4    0.07       0  4648.8   0.035       0  4778.4    0.07       0
  4903.4   0.035       0  5126.1    0.07       0  5154.3   0.035       0
  5158.3    0.07       0  5254.0   0.035       0  5956.6    0.07       0
Bank Sta=5154.3,5158.3
Exp/Cntr=0.3,0.1

Type RM Length L Ch R = 1,6000,500,500,500
BEGIN DESCRIPTION:
Cottonwood Trib048 11.0
END DESCRIPTION:
XS GIS Cut Line= 3
      1338054.99      6881337.95      1338304.61      6882167.41
      1338805.00      6883138.01
#Sta/Elev= 30
  4133.8 2276.98  4448.7 2263.18  4621.2 2254.70  4656.0 2250.54  4671.7 2250.86
  4676.9 2253.14  4718.7 2253.95  4958.8 2251.99  5007.0 2247.18  5007.3 2246.68
  5011.0 2247.18  5014.7 2249.08  5045.7 2253.81  5089.8 2251.63  5169.9 2250.04
  5590.3 2257.97  5595.1 2257.95  5712.6 2260.47  5729.1 2256.80  5739.7 2256.96
  5779.1 2258.24  5795.6 2261.15  5859.2 2265.54  5900.7 2266.01  5945.1 2269.59
  5995.1 2270.10  6011.6 2271.30  6024.5 2275.04  6039.4 2276.52  6092.0 2277.62
#Mann=11,-1,0
  4133.8    0.07       0  4448.7   0.035       0  4621.2    0.07       0
  5007.0    0.07       0  5011.0    0.07       0  5089.8   0.035       0
  5169.9    0.07       0  5590.3   0.035       0  5595.1    0.07       0
  5739.7   0.035       0  5859.2    0.07       0
Bank Sta=5007,5011
Exp/Cntr=0.3,0.1

Type RM Length L Ch R = 1,5500,500,500,500
BEGIN DESCRIPTION:
Cottonwood Trib048 10.0
END DESCRIPTION:
XS GIS Cut Line= 3
      1338005.00      6881387.95      1337932.82      6882387.85
      1338304.99      6883337.96
#Sta/Elev= 30
  3997.5 2275.34  4178.0 2264.54  4288.3 2260.47  4318.4 2255.91  4368.5 2256.30
  4441.2 2252.00  4555.6 2249.19  4639.2 2247.92  4659.3 2244.31  4689.3 2247.34
  4970.1 2245.55  4982.3 2241.02  4988.1 2237.86  4988.4 2237.36  4992.1 2237.86
  4997.6 2242.98  5010.9 2245.01  5092.0 2244.56  5216.0 2247.10  5373.4 2246.24
  5417.5 2248.90  5590.5 2253.42  5745.8 2262.04  5783.1 2265.75  5860.7 2269.25
  5879.9 2272.43  5891.6 2274.27  5913.0 2272.66  5989.7 2279.61  6020.4 2281.06
#Mann=12,-1,0
  3997.5    0.07       0  4441.2   0.035       0  4555.6    0.07       0
  4982.3    0.16       0  4988.1    0.07       0  4992.1    0.16       0
  5092.0    0.07       0  5417.5   0.035       0  5745.8    0.07       0
  5860.7    0.16       0  5879.9    0.07       0  5989.7    0.16       0
Bank Sta=4988.1,4992.1
Exp/Cntr=0.3,0.1

Type RM Length L Ch R = 1,5000,500,500,500
BEGIN DESCRIPTION:
Cottonwood Trib048 9.0
END DESCRIPTION:
XS GIS Cut Line= 3
      1337555.00      6881588.00      1337495.28      6882585.82
      1338304.99      6883537.99
#Sta/Elev= 30
  4000.4 2261.42  4040.5 2257.50  4140.6 2256.31  4361.0 2246.81  4919.0 2239.56
  4932.1 2239.15  4952.1 2233.08  4992.2 2237.58  4998.6 2231.86  5006.4 2230.94
  5006.6 2230.44  5010.4 2230.94  5022.6 2239.36  5036.9 2240.10  5051.2 2232.47
  5079.8 2239.71  5221.7 2239.57  5314.5 2240.19  5492.4 2245.29  5529.5 2246.42
  5732.1 2256.83  5765.6 2260.84  5859.5 2265.90  5873.8 2269.39  5895.5 2268.10
  5930.9 2273.10  5980.3 2272.76  6058.3 2278.03  6122.0 2287.37  6249.9 2295.10
#Mann=8,-1,0
  4000.4    0.07       0  5006.4    0.07       0  5010.4    0.07       0
  5221.7   0.035       0  5314.5    0.16       0  5492.4    0.07       0
  5529.5   0.035       0  5765.6    0.07       0
Bank Sta=5006.4,5010.4
Exp/Cntr=0.3,0.1

Type RM Length L Ch R = 1,4500,500,500,500
BEGIN DESCRIPTION:
Cottonwood Trib048 8.0
END DESCRIPTION:
XS GIS Cut Line= 3
      1336104.99      6881887.99      1337124.95      6882868.03
      1337605.02      6883688.04
#Sta/Elev= 30
  3585.5 2283.36  3670.3 2277.62  3691.6 2273.56  3726.9 2274.02  3753.9 2269.53
  3790.7 2268.91  3819.0 2264.13  3854.2 2264.38  3896.7 2260.35  3903.9 2256.33
  3939.1 2256.47  4109.0 2244.10  4442.4 2237.00  4520.9 2235.53  4986.0 2234.68
  4990.7 2226.41  4991.0 2225.91  4995.1 2226.41  5002.9 2227.09  5007.9 2232.36
  5013.7 2233.65  5143.8 2233.67  5201.8 2233.99  5461.5 2239.30  5776.2 2254.30
  5803.5 2258.02  5811.1 2256.34  5877.9 2263.31  5905.1 2274.94  5950.2 2283.56
#Mann=8,-1,0
  3585.5    0.07       0  3753.9   0.035       0  4442.4    0.07       0
  4520.9   0.035       0  4990.7    0.07       0  4995.1   0.035       0
  5143.8   0.035       0  5201.8    0.07       0
Bank Sta=4990.7,4995.1
Exp/Cntr=0.3,0.1

Type RM Length L Ch R = 1,4000,500,500,500
BEGIN DESCRIPTION:
Cottonwood Trib048 7.0
END DESCRIPTION:
XS GIS Cut Line= 3
      1335954.98      6882237.97      1336795.59      6883234.86
      1337604.97      6883737.98
#Sta/Elev= 30
  3696.0 2285.46  3703.8 2284.21  3795.5 2278.49  3816.3 2274.08  3852.7 2274.13
  3880.1 2269.06  3916.4 2268.96  3937.3 2264.83  3972.4 2264.81  4001.0 2260.11
  4114.6 2255.31  4128.4 2250.72  4370.3 2237.35  4570.8 2230.39  4667.9 2228.65
  4973.6 2229.61  4996.6 2222.91  4996.9 2222.41  5001.0 2222.91  5016.2 2228.93
  5247.6 2230.98  5683.2 2250.23  5741.1 2255.64  5750.6 2255.77  5756.5 2252.16
  5777.7 2257.76  5866.3 2263.99  5881.6 2267.25  5924.1 2285.33  5953.0 2287.51
#Mann=6,-1,0
  3696.0   0.035       0  3703.8    0.07       0  4570.8   0.035       0
  4667.9    0.07       0  4996.6    0.07       0  5001.0    0.07       0
Bank Sta=4996.6,5001
Exp/Cntr=0.3,0.1

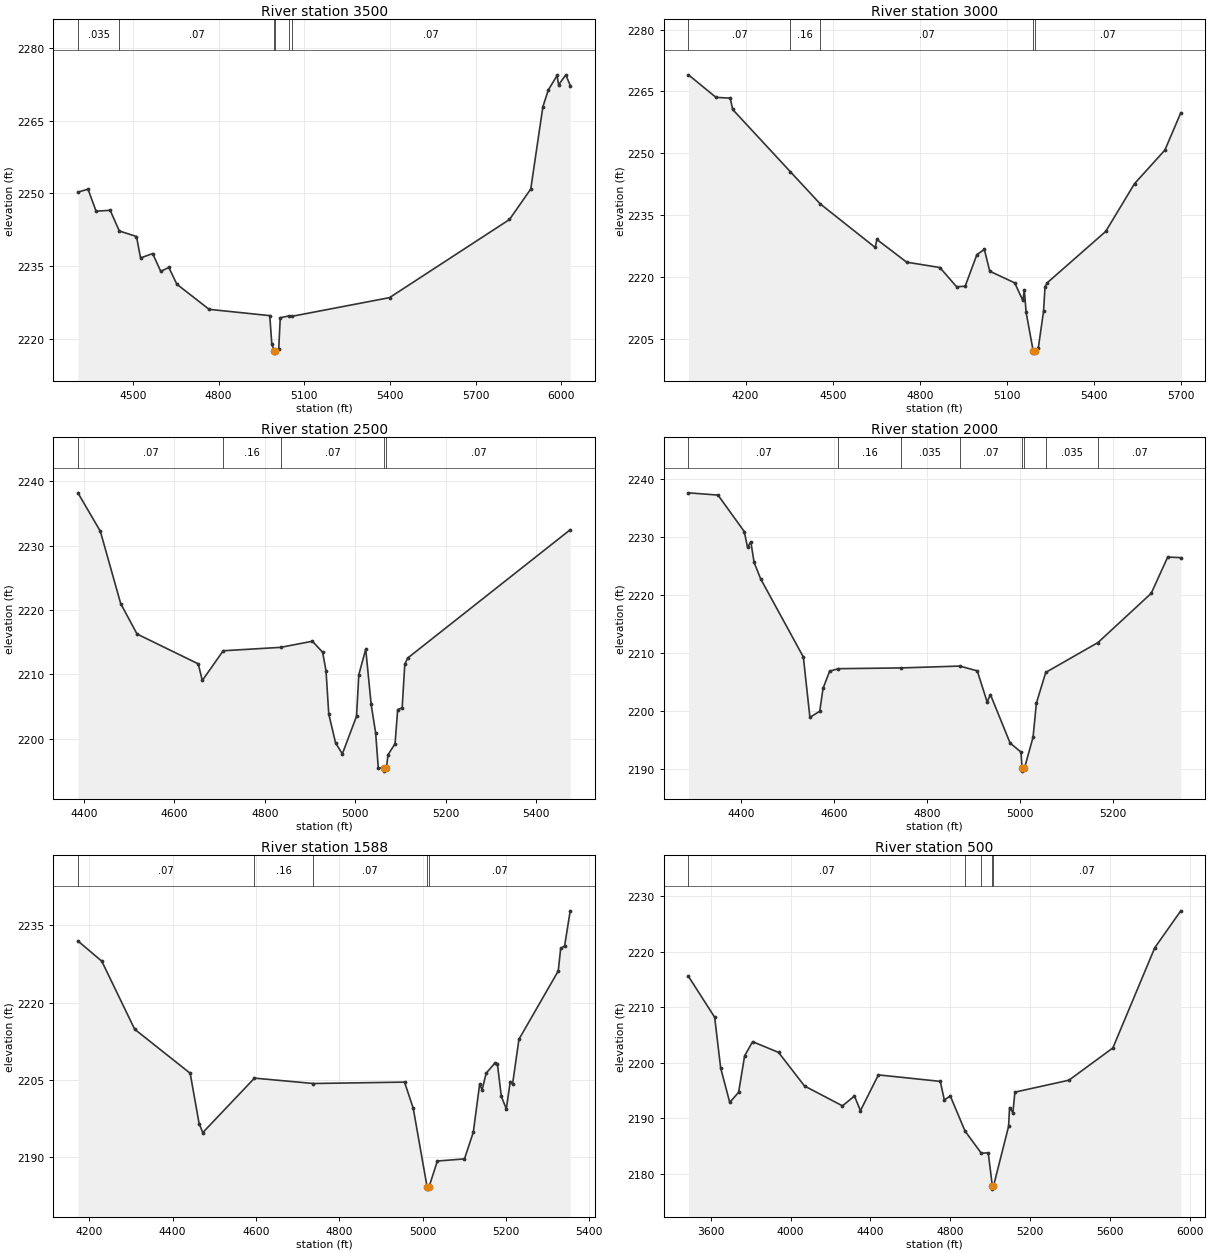
Type RM Length L Ch R = 1,3500,500,500,500
BEGIN DESCRIPTION:
Cottonwood Trib048 6.0
END DESCRIPTION:
XS GIS Cut Line= 3
      1335955.02      6883038.02      1336434.93      6883537.67
      1337405.01      6883888.00
#Sta/Elev= 30
  4307.2 2250.25  4342.6 2250.87  4370.9 2246.32  4420.2 2246.50  4452.2 2242.23
  4512.4 2241.08  4526.5 2236.65  4569.0 2237.56  4597.3 2233.88  4625.6 2234.69
  4653.8 2231.22  4766.8 2226.03  4979.1 2224.73  4986.3 2218.87  4994.6 2217.48
  4994.9 2216.98  4999.0 2217.48  5010.5 2217.86  5015.9 2224.30  5045.8 2224.66
  5055.9 2224.58  5398.6 2228.45  5818.7 2244.60  5893.2 2250.90  5935.7 2267.92
  5954.7 2271.37  5985.4 2274.37  5990.7 2272.43  6016.1 2274.50  6031.4 2272.29
#Mann=6,-1,0
  4307.2   0.035       0  4452.2    0.07       0  4994.6    0.07       0
  4999.0    0.07       0  5045.8    0.16       0  5055.9    0.07       0
Bank Sta=4994.6,4999
Exp/Cntr=0.3,0.1

Type RM Length L Ch R = 1,3000,500,500,500
BEGIN DESCRIPTION:
Cottonwood Trib048 5.0
END DESCRIPTION:
XS GIS Cut Line= 3
      1335555.00      6883038.00      1336104.44      6883869.22
      1336305.00      6884537.99
#Sta/Elev= 30
  4003.6 2269.02  4098.4 2263.55  4147.4 2263.37  4155.6 2260.63  4354.5 2245.50
  4457.3 2237.71  4646.2 2227.16  4652.1 2229.09  4754.5 2223.59  4868.8 2222.29
  4926.6 2217.62  4956.1 2217.76  4996.3 2225.43  5022.1 2226.68  5040.5 2221.40
  5126.5 2218.57  5154.4 2214.31  5159.6 2216.79  5165.8 2211.41  5190.2 2202.03
  5190.6 2201.53  5195.0 2202.03  5207.5 2202.67  5225.7 2211.65  5230.9 2217.65
  5238.8 2218.61  5439.8 2231.05  5539.0 2242.64  5643.4 2250.76  5698.2 2259.82
#Mann=5,-1,0
  4003.6    0.07       0  4354.5    0.16       0  4457.3    0.07       0
  5190.2    0.07       0  5195.0    0.07       0
Bank Sta=5190.2,5195
Exp/Cntr=0.3,0.1

Type RM Length L Ch R = 1,2500,500,500,500
BEGIN DESCRIPTION:
Cottonwood Trib048 4.0
END DESCRIPTION:
XS GIS Cut Line= 3
      1335405.01      6883688.02      1335744.88      6884197.93
      1336154.98      6884437.99
#Sta/Elev= 30
  4387.2 2238.18  4436.8 2232.21  4481.8 2220.98  4517.9 2216.27  4653.1 2211.64
  4662.1 2209.06  4708.3 2213.67  4835.2 2214.20  4905.5 2215.15  4928.0 2213.44
  4935.5 2210.57  4941.6 2203.84  4956.6 2199.39  4971.6 2197.66  5003.0 2203.52
  5008.0 2209.96  5023.3 2213.91  5035.3 2205.34  5045.2 2200.92  5051.0 2195.50
  5064.1 2195.49  5064.5 2194.99  5069.1 2195.49  5072.4 2197.51  5088.1 2199.25
  5093.9 2204.55  5103.8 2204.82  5109.6 2211.59  5116.0 2212.54  5475.2 2232.45
#Mann=5,-1,0
  4387.2    0.07       0  4708.3    0.16       0  4835.2    0.07       0
  5064.1    0.07       0  5069.1    0.07       0
Bank Sta=5064.1,5069.1
Exp/Cntr=0.3,0.1

Type RM Length L Ch R = 1,2000,412,412,412
BEGIN DESCRIPTION:
Cottonwood Trib048 3.0
END DESCRIPTION:
XS GIS Cut Line= 3
      1334855.01      6883988.01      1335363.06      6884489.70
      1335605.01      6884738.01
#Sta/Elev= 30
  4286.0 2237.65  4349.6 2237.26  4406.2 2230.97  4413.2 2228.26  4420.3 2229.21
  4427.4 2225.65  4441.5 2222.81  4533.5 2209.33  4547.6 2198.92  4568.8 2199.98
  4575.9 2203.92  4590.1 2206.88  4608.7 2207.32  4744.0 2207.45  4870.5 2207.77
  4908.2 2206.94  4929.5 2201.57  4936.5 2202.86  4978.9 2194.50  5002.3 2192.93
  5004.7 2190.15  5005.1 2189.65  5009.8 2190.15  5028.4 2195.50  5035.6 2201.41
  5055.8 2206.68  5168.3 2211.83  5283.0 2220.32  5318.5 2226.57  5346.7 2226.47
#Mann=8,-1,0
  4286.0    0.07       0  4608.7    0.16       0  4744.0   0.035       0
  4870.5    0.07       0  5004.7    0.07       0  5009.8    0.07       0
  5055.8   0.035       0  5168.3    0.07       0
Bank Sta=5004.7,5009.8
Exp/Cntr=0.3,0.1

Type RM Length L Ch R = 1,1588,1088,1088,1088
BEGIN DESCRIPTION:
Cottonwood Trib048 2.0
END DESCRIPTION:
XS GIS Cut Line= 4
      1334830.47      6884046.68      1335108.26      6884763.71
      1335191.59      6884822.74      1335454.97      6884987.98
#Sta/Elev= 30
  4172.5 2231.97  4229.7 2228.06  4308.8 2214.85  4442.0 2206.32  4463.5 2196.57
  4472.3 2194.81  4596.4 2205.37  4737.9 2204.33  4956.7 2204.60  4977.6 2199.53
  5010.7 2184.35  5011.1 2183.85  5015.8 2184.35  5035.5 2189.30  5100.6 2189.71
  5121.8 2194.88  5137.1 2204.22  5143.0 2203.07  5152.5 2206.31  5173.7 2208.30
  5179.6 2208.19  5189.0 2201.86  5201.1 2199.41  5210.2 2204.56  5216.1 2204.24
  5231.4 2212.91  5325.7 2226.14  5331.6 2230.51  5341.0 2231.00  5354.5 2237.81
#Mann=5,-1,0
  4172.5    0.07       0  4596.4    0.16       0  4737.9    0.07       0
  5010.7    0.07       0  5015.8    0.07       0
Bank Sta=5010.7,5015.8
Exp/Cntr=0.3,0.1

Type RM Length L Ch R = 1,500,0,0,0
BEGIN DESCRIPTION:
Cottonwood Trib048 1.0
END DESCRIPTION:
XS GIS Cut Line= 3
      1334846.10      6884176.87      1334801.55      6885688.01
      1335755.04      6885738.00
#Sta/Elev= 30
  3488.2 2215.56  3619.4 2208.20  3649.4 2199.06  3694.9 2192.85  3739.4 2194.68
  3769.5 2201.24  3809.5 2203.80  3939.5 2201.86  4069.6 2195.81  4259.7 2192.23
  4319.7 2194.00  4349.7 2191.36  4439.7 2197.81  4749.9 2196.64  4769.9 2193.30
  4799.9 2194.01  4873.6 2187.70  4954.7 2183.72  4990.0 2183.75  5010.9 2177.72
  5011.3 2177.22  5016.0 2177.72  5091.9 2188.52  5096.9 2191.91  5113.6 2191.01
  5123.6 2194.70  5394.0 2196.85  5614.3 2202.66  5824.6 2220.74  5954.8 2227.38
#Mann=5,-1,0
  3488.2    0.07       0  4873.6    0.16       0  4954.7    0.07       0
  5010.9    0.07       0  5016.0    0.07       0
Bank Sta=5010.9,5016
Exp/Cntr=0.3,0.1

Chan Stop Cuts=-1