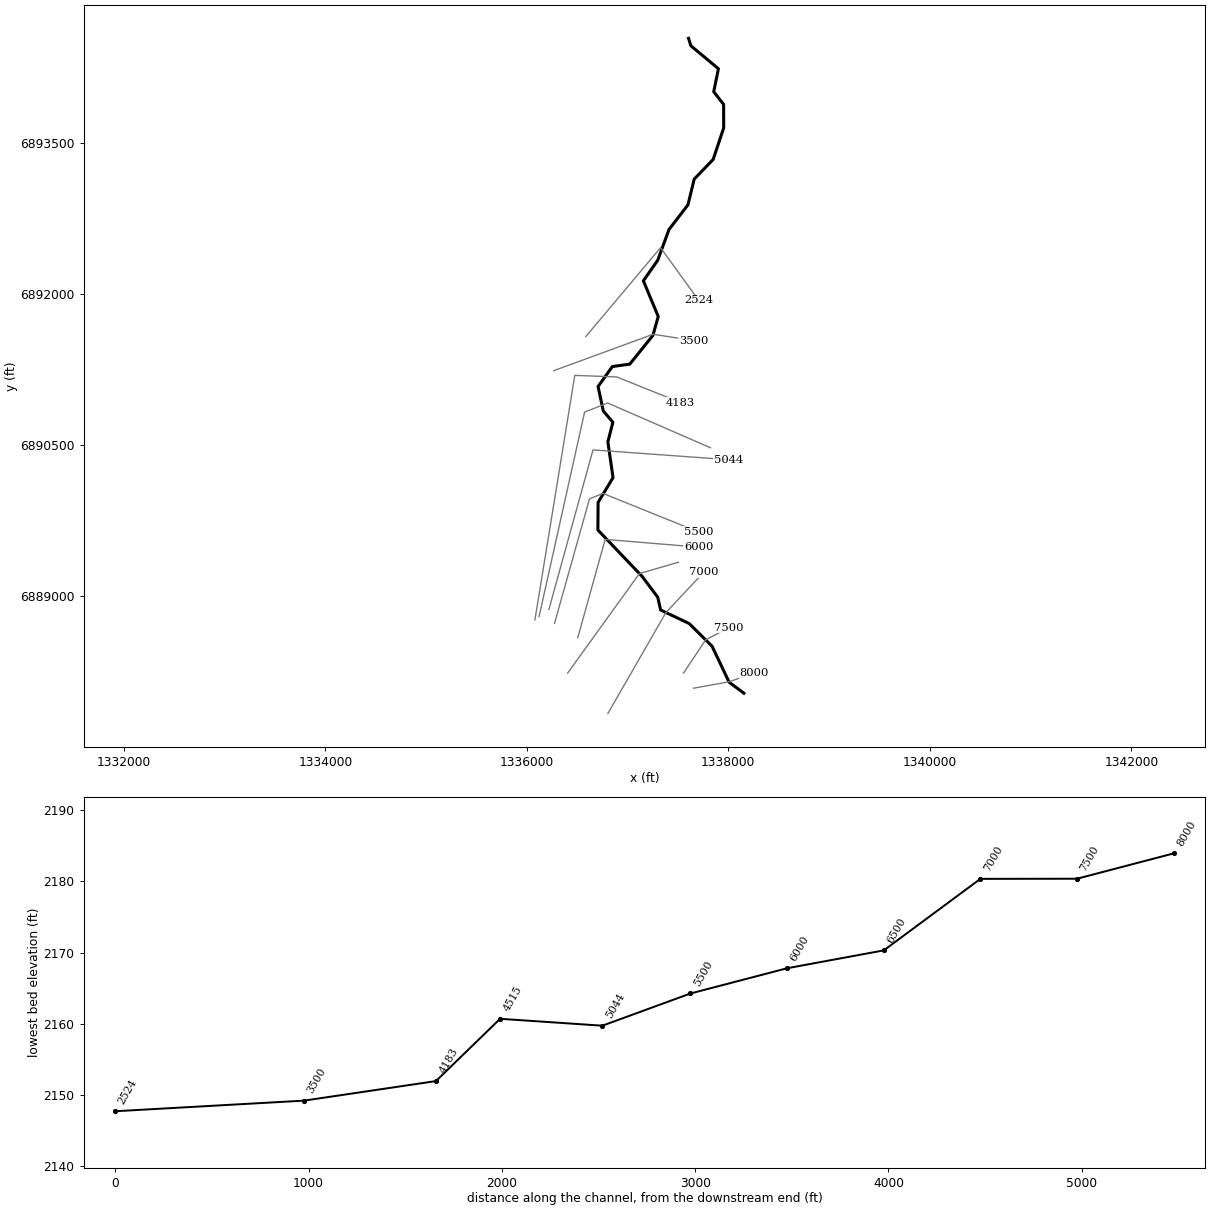
--- Cottonwood Trib050.prj (project) ---

Proj Title=Cottonwood Trib050 Base Level Engineering
Current Plan=p01
Default Exp/Contr=0.3,0.1
English Units
Geom File=g01
Flow File=f01
Plan File=p01
BEGIN DESCRIPTION:
Cottonwood Trib050
END DESCRIPTION:

--- Cottonwood Trib050.p01 (plan) ---

Plan Title=Multiple Run
Short Identifier=Multiple
Geom File=g01
Flow File=f01
Subcritical Flow
K Sum by GR= 0
Std Step Tol= 0.01
Critical Tol= 0.01
Num of Std Step Trials= 20
Max Error Tol= 0.3
Flow Tol Ratio= 0.001
Split Flow NTrial= 30
Split Flow Tol= 0.02
Split Flow Ratio= 0.02
Log Output Level= 0
Friction Slope Method= 1
Unsteady Friction Slope Method= 2
Unsteady Bridges Friction Slope Method= 1
Parabolic Critical Depth
Global Vel Dist=  1 , 1 , 1
Global Log Level= 0
CheckData=True
Encroach Param= -1, 0, 0, 0
BEGIN DESCRIPTION:
Multiple Run
END DESCRIPTION:

--- Cottonwood Trib050.f01 (steady flow) ---

Flow Title=Multiple
Number of Profiles=7
Profile Names=10-year,25-year,50-year,1pct_min,100-year,1pct_plu,500-year
River Rch & RM= Cottonwood Trib0,Reach-1,8000
     367     535     680     431     859    1715    1390
River Rch & RM= Cottonwood Trib0,Reach-1,4183
     381     554     704     445     888    1771    1430
Boundary for River Rch & Prof#=Cottonwood Trib0,Reach-1,1
Up Type=0
Dn Type=3
Dn Slope=0.005
Boundary for River Rch & Prof#=Cottonwood Trib0,Reach-1,2
Up Type=0
Dn Type=3
Dn Slope=0.005
Boundary for River Rch & Prof#=Cottonwood Trib0,Reach-1,3
Up Type=0
Dn Type=3
Dn Slope=0.005
Boundary for River Rch & Prof#=Cottonwood Trib0,Reach-1,4
Up Type=0
Dn Type=3
Dn Slope=0.005
Boundary for River Rch & Prof#=Cottonwood Trib0,Reach-1,5
Up Type=0
Dn Type=3
Dn Slope=0.005
Boundary for River Rch & Prof#=Cottonwood Trib0,Reach-1,6
Up Type=0
Dn Type=3
Dn Slope=0.005
Boundary for River Rch & Prof#=Cottonwood Trib0,Reach-1,7
Up Type=0
Dn Type=3
Dn Slope=0.005

--- Cottonwood Trib050.g01 (geometry) ---

Geom Title=Existing Conditions

River Reach=Cottonwood Trib0,Reach-1
Reach XY= 30
      1338155.00      6888038.00      1338008.50      6888146.47
      1337838.35      6888504.67      1337611.05      6888729.84
      1337327.67      6888863.99      1337299.47      6888990.42
      1337144.22      6889197.68      1336704.96      6889657.98
      1336707.24      6889932.07      1336855.50      6890177.79
      1336804.19      6890532.97      1336854.06      6890727.52
      1336758.62      6890839.50      1336706.97      6891082.11
      1336848.53      6891280.30      1337021.76      6891304.43
      1337251.18      6891589.58      1337304.23      6891777.31
      1337156.52      6892131.60      1337299.23      6892335.68
      1337410.83      6892640.30      1337599.29      6892885.65
      1337660.83      6893140.30      1337849.17      6893335.70
      1337953.78      6893648.50      1337952.93      6893882.14
      1337854.79      6894008.05      1337901.54      6894236.50
      1337627.82      6894464.02      1337605.00      6894538.00

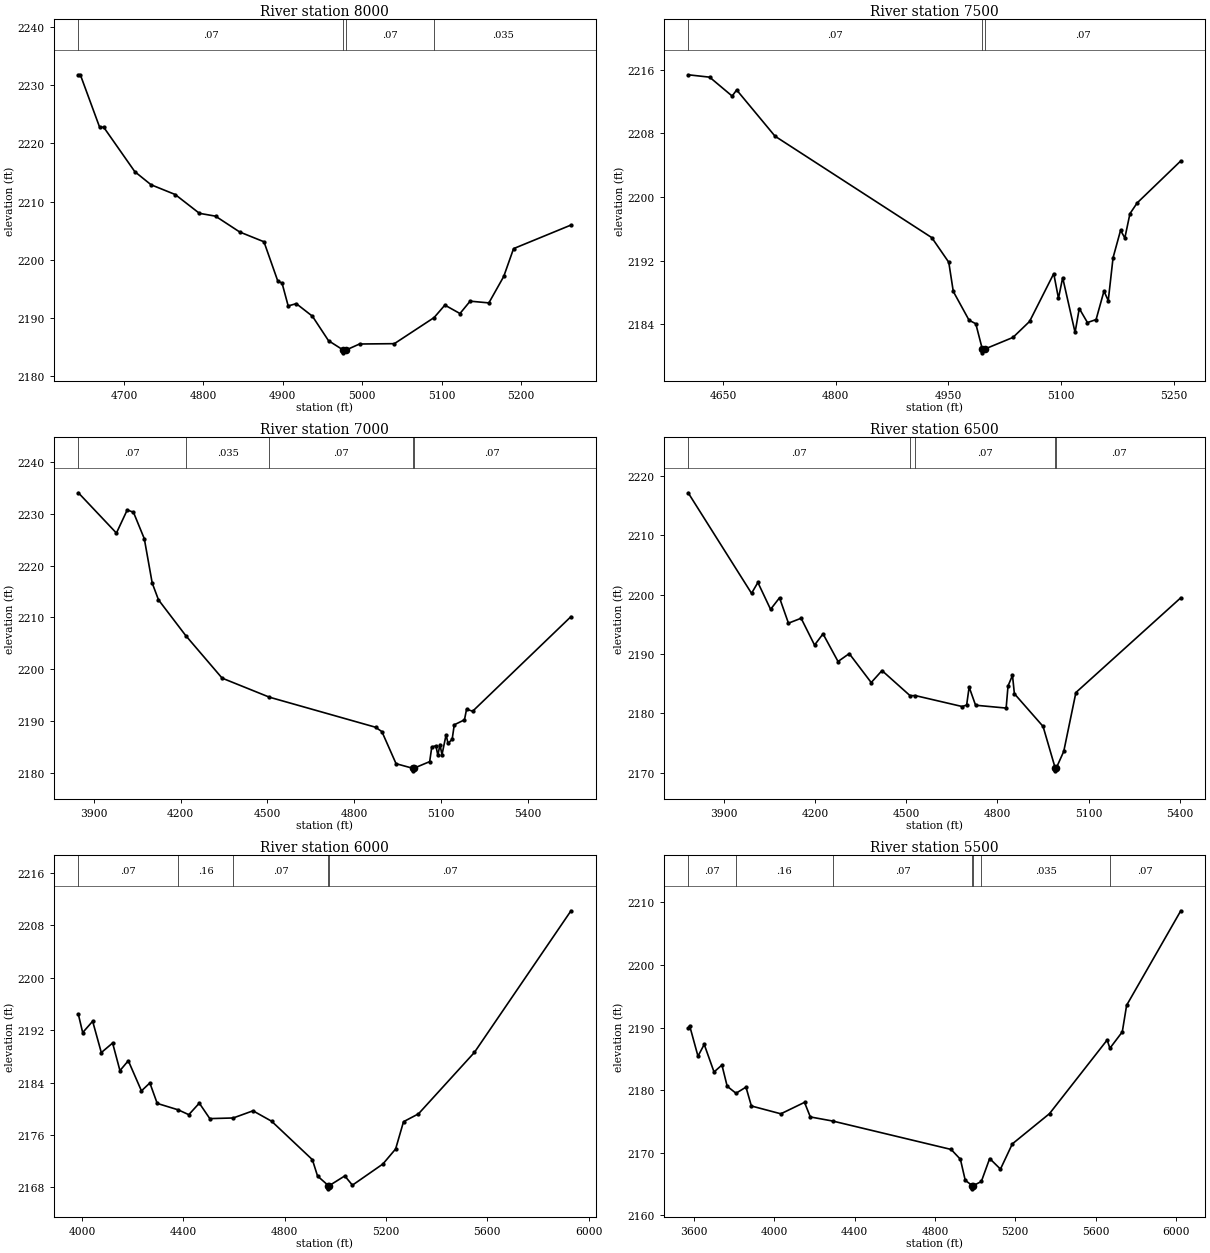
Type RM Length L Ch R = 1,8000,500,500,500
BEGIN DESCRIPTION:
Cottonwood Trib050 16.0
END DESCRIPTION:
XS GIS Cut Line= 3
      1337655.00      6888088.00      1338006.73      6888151.41
      1338254.96      6888237.99
#Sta/Elev= 30
  4642.6 2231.83  4645.1 2231.83  4669.4 2222.79  4674.5 2222.80  4713.7 2215.14
  4734.1 2212.89  4764.5 2211.21  4795.0 2207.97  4815.3 2207.48  4845.8 2204.75
  4876.3 2203.07  4893.9 2196.23  4899.0 2195.99  4906.8 2192.02  4917.0 2192.41
  4937.3 2190.25  4957.6 2186.03  4975.9 2184.44  4976.2 2183.94  4979.9 2184.44
  4996.6 2185.46  5040.5 2185.52  5090.5 2190.01  5104.1 2192.16  5123.1 2190.71
  5135.9 2192.84  5159.5 2192.54  5178.2 2197.09  5190.6 2201.89  5262.9 2205.95
#Mann=4,-1,0
  4642.6    0.07       0  4975.9    0.07       0  4979.9    0.07       0
  5090.5   0.035       0
Bank Sta=4975.9,4979.9
Exp/Cntr=0.3,0.1

Type RM Length L Ch R = 1,7500,500,500,500
BEGIN DESCRIPTION:
Cottonwood Trib050 15.0
END DESCRIPTION:
XS GIS Cut Line= 3
      1337554.99      6888237.98      1337775.01      6888568.07
      1338005.02      6888688.01
#Sta/Elev= 30
  4603.3 2215.38  4631.9 2215.08  4661.9 2212.70  4667.9 2213.47  4719.0 2207.65
  4927.8 2194.88  4950.4 2191.78  4956.4 2188.11  4977.4 2184.49  4986.4 2184.04
  4995.0 2180.88  4995.2 2180.38  4999.0 2180.88  5035.9 2182.32  5058.0 2184.33
  5090.2 2190.35  5096.5 2187.24  5102.1 2189.84  5118.6 2182.95  5124.2 2185.96
  5135.1 2184.19  5146.6 2184.57  5157.1 2188.15  5162.8 2186.95  5169.2 2192.35
  5179.2 2195.80  5184.9 2194.84  5191.7 2197.90  5201.3 2199.25  5259.4 2204.54
#Mann=3,-1,0
  4603.3    0.07       0  4995.0    0.07       0  4999.0    0.07       0
Bank Sta=4995,4999
Exp/Cntr=0.3,0.1

Type RM Length L Ch R = 1,7000,500,500,500
BEGIN DESCRIPTION:
Cottonwood Trib050 14.0
END DESCRIPTION:
XS GIS Cut Line= 3
      1336805.02      6887838.03      1337379.83      6888837.88
      1337755.00      6889238.00
#Sta/Elev= 30
  3846.7 2234.05  3978.2 2226.27  4015.6 2230.74  4037.1 2230.28  4074.5 2225.18
  4101.8 2216.62  4123.5 2213.38  4217.4 2206.49  4343.3 2198.26  4506.8 2194.58
  4873.3 2188.78  4895.3 2187.93  4944.2 2181.74  5001.6 2180.86  5001.9 2180.36
  5005.6 2180.86  5060.3 2182.14  5067.6 2184.96  5081.8 2185.20  5088.6 2183.35
  5095.9 2185.44  5102.8 2183.46  5117.0 2187.31  5123.8 2185.65  5138.0 2186.46
  5145.3 2189.25  5180.5 2190.21  5187.8 2192.26  5208.8 2191.87  5548.5 2210.14
#Mann=5,-1,0
  3846.7    0.07       0  4217.4   0.035       0  4506.8    0.07       0
  5001.6    0.07       0  5005.6    0.07       0
Bank Sta=5001.6,5005.6
Exp/Cntr=0.3,0.1

Type RM Length L Ch R = 1,6500,500,500,500
BEGIN DESCRIPTION:
Cottonwood Trib050 13.0
END DESCRIPTION:
XS GIS Cut Line= 3
      1336404.98      6888237.97      1337117.57      6889225.88
      1337504.98      6889337.99
#Sta/Elev= 30
  3781.9 2217.17  3990.5 2200.22  4011.4 2202.05  4053.2 2197.52  4082.6 2199.47
  4112.0 2195.19  4153.7 2196.02  4197.9 2191.50  4225.8 2193.39  4275.2 2188.73
  4312.1 2190.06  4384.4 2185.18  4419.9 2187.20  4512.5 2182.96  4529.1 2182.99
  4683.8 2181.14  4698.5 2181.39  4706.7 2184.42  4727.9 2181.36  4828.5 2180.88
  4834.7 2184.61  4849.4 2186.40  4855.6 2183.30  4950.0 2177.79  4989.8 2170.80
  4990.0 2170.30  4993.8 2170.80  5018.1 2173.58  5058.1 2183.50  5403.3 2199.47
#Mann=5,-1,0
  3781.9    0.07       0  4512.5   0.035       0  4529.1    0.07       0
  4989.8    0.07       0  4993.8    0.07       0
Bank Sta=4989.8,4993.8
Exp/Cntr=0.3,0.1

Type RM Length L Ch R = 1,6000,500,500,500
BEGIN DESCRIPTION:
Cottonwood Trib050 12.0
END DESCRIPTION:
XS GIS Cut Line= 3
      1336505.01      6888588.03      1336777.42      6889564.96
      1337705.03      6889488.00
#Sta/Elev= 30
  3985.8 2194.40  4002.9 2191.62  4042.2 2193.35  4076.4 2188.57  4121.0 2190.03
  4150.0 2185.82  4183.0 2187.33  4234.9 2182.73  4268.1 2183.94  4297.1 2180.82
  4380.7 2179.83  4421.8 2179.10  4463.3 2180.86  4504.8 2178.50  4597.2 2178.60
  4675.3 2179.69  4748.9 2178.10  4909.7 2172.24  4930.2 2169.74  4972.8 2168.29
  4973.0 2167.79  4976.8 2168.29  5037.7 2169.76  5067.8 2168.35  5188.2 2171.58
  5238.4 2173.87  5269.6 2178.03  5328.7 2179.23  5549.5 2188.60  5930.8 2210.20
#Mann=5,-1,0
  3985.8    0.07       0  4380.7    0.16       0  4597.2    0.07       0
  4972.8    0.07       0  4976.8    0.07       0
Bank Sta=4972.8,4976.8
Exp/Cntr=0.3,0.1

Type RM Length L Ch R = 1,5500,456,456,456
BEGIN DESCRIPTION:
Cottonwood Trib050 11.0
END DESCRIPTION:
XS GIS Cut Line= 4
      1336274.60      6888730.96      1336621.82      6889967.09
      1336755.68      6890021.33      1337705.00      6889638.00
#Sta/Elev= 30
  3571.6 2189.86  3578.9 2190.30  3620.5 2185.42  3651.6 2187.30  3700.4 2182.90
  3739.7 2184.01  3765.9 2180.62  3809.8 2179.50  3859.4 2180.48  3886.4 2177.47
  4033.0 2176.22  4150.8 2178.05  4179.7 2175.72  4291.8 2175.06  4880.6 2170.53
  4926.8 2168.96  4950.9 2165.60  4986.5 2164.74  4986.7 2164.24  4990.5 2164.74
  5031.1 2165.42  5072.5 2169.08  5126.2 2167.39  5185.3 2171.42  5370.4 2176.25
  5657.1 2188.00  5671.0 2186.69  5732.6 2189.30  5754.2 2193.55  6023.8 2208.64
#Mann=7,-1,0
  3571.6    0.07       0  3809.8    0.16       0  4291.8    0.07       0
  4986.5    0.07       0  4990.5    0.07       0  5031.1   0.035       0
  5671.0    0.07       0
Bank Sta=4986.5,4990.5
Exp/Cntr=0.3,0.1

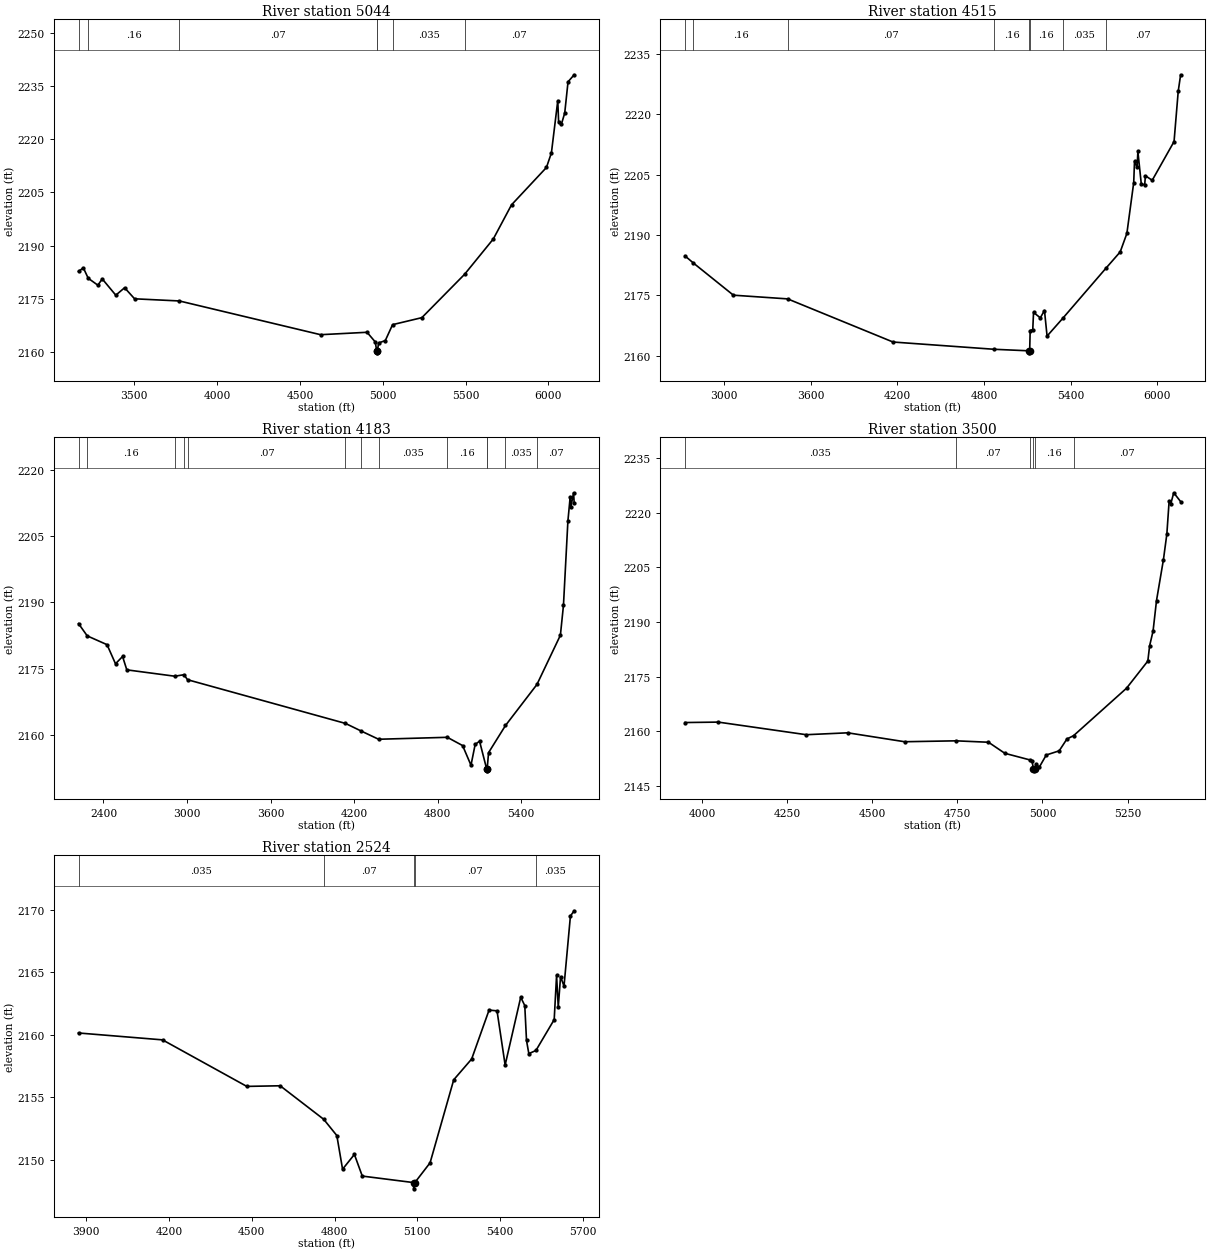
Type RM Length L Ch R = 1,5044,529,529,529
BEGIN DESCRIPTION:
Cottonwood Trib050 10.0
END DESCRIPTION:
XS GIS Cut Line= 3
      1336219.05      6888869.88      1336656.55      6890453.20
      1338001.90      6890356.11
#Sta/Elev= 30
  3163.6 2182.69  3192.8 2183.70  3222.2 2180.75  3280.4 2178.80  3306.9 2180.57
  3388.6 2175.98  3441.8 2178.08  3502.0 2174.96  3772.3 2174.35  4624.5 2164.83
  4905.0 2165.51  4955.1 2162.76  4963.1 2160.21  4963.4 2159.71  4967.1 2160.21
  4975.1 2162.50  5015.2 2163.17  5059.1 2167.66  5235.8 2169.64  5493.3 2181.85
  5666.9 2191.83  5776.9 2201.47  5987.8 2212.02  6017.8 2216.15  6056.2 2230.89
  6061.2 2224.90  6078.0 2224.22  6098.1 2227.38  6118.1 2236.20  6155.1 2238.18
#Mann=7,-1,0
  3163.6    0.07       0  3222.2    0.16       0  3772.3    0.07       0
  4963.1    0.07       0  4967.1    0.07       0  5059.1   0.035       0
  5493.3    0.07       0
Bank Sta=4963.1,4967.1
Exp/Cntr=0.3,0.1

Type RM Length L Ch R = 1,4515,332,332,332
BEGIN DESCRIPTION:
Cottonwood Trib050 9.0
END DESCRIPTION:
XS GIS Cut Line= 4
      1336121.82      6888800.42      1336573.21      6890828.20
      1336802.38      6890918.48      1337821.65      6890474.72
#Sta/Elev= 30
  2727.1 2184.79  2786.0 2183.00  3062.7 2175.02  3438.6 2174.10  4169.1 2163.37
  4871.8 2161.56  5112.2 2161.18  5112.4 2160.68  5116.2 2161.18  5119.6 2166.21
  5137.6 2166.46  5143.0 2170.73  5189.9 2169.39  5218.8 2171.21  5236.8 2164.85
  5345.4 2169.26  5644.9 2181.73  5743.6 2185.78  5789.9 2190.38  5837.3 2203.02
  5842.8 2208.28  5860.8 2206.82  5866.2 2210.76  5889.6 2202.74  5913.1 2202.44
  5918.5 2204.73  5965.4 2203.59  6116.9 2213.23  6145.8 2225.74  6162.5 2229.84
#Mann=8,-1,0
  2727.1    0.07       0  2786.0    0.16       0  3438.6    0.07       0
  4871.8    0.16       0  5112.2    0.07       0  5116.2    0.16       0
  5345.4   0.035       0  5644.9    0.07       0
Bank Sta=5112.2,5116.2
Exp/Cntr=0.3,0.1

Type RM Length L Ch R = 1,4183,683,683,683
BEGIN DESCRIPTION:
Cottonwood Trib050 8.0
END DESCRIPTION:
XS GIS Cut Line= 4
      1336080.16      6888765.73      1336475.99      6891192.78
      1336892.66      6891177.16      1337526.75      6890922.48
#Sta/Elev= 30
  2220.7 2185.21  2283.3 2182.43  2425.6 2180.44  2486.4 2176.12  2537.1 2177.77
  2567.5 2174.75  2912.7 2173.31  2977.7 2173.65  3003.7 2172.52  4137.9 2162.64
  4250.5 2160.92  4375.7 2159.06  4869.2 2159.50  4979.0 2157.63  5039.1 2153.19
  5069.1 2157.88  5100.7 2158.63  5151.0 2152.42  5151.3 2151.92  5155.4 2152.42
  5165.5 2156.04  5286.9 2162.17  5512.7 2171.44  5681.2 2182.58  5703.2 2189.32
  5735.1 2208.39  5751.6 2213.87  5757.0 2211.67  5775.8 2214.78  5780.1 2212.51
#Mann=13,-1,0
  2220.7    0.07       0  2283.3    0.16       0  2912.7    0.07       0
  2977.7    0.16       0  3003.7    0.07       0  4137.9    0.16       0
  4250.5    0.07       0  4375.7   0.035       0  4869.2    0.16       0
  5151.0    0.07       0  5155.4    0.16       0  5286.9   0.035       0
  5512.7    0.07       0
Bank Sta=5151,5155.4
Exp/Cntr=0.3,0.1

Type RM Length L Ch R = 1,3500,976,976,976
BEGIN DESCRIPTION:
Cottonwood Trib050 7.0
END DESCRIPTION:
XS GIS Cut Line= 3
      1336267.63      6891239.65      1337254.03      6891600.98
      1337655.02      6891538.00
#Sta/Elev= 30
  3949.5 2162.43  4047.2 2162.55  4305.8 2159.09  4427.8 2159.61  4594.9 2157.16
  4745.8 2157.41  4841.3 2157.02  4889.4 2153.98  4962.9 2152.17  4969.1 2151.93
  4973.4 2149.67  4973.7 2149.17  4977.9 2149.67  4980.9 2151.05  4990.4 2150.15
  5011.1 2153.52  5049.0 2154.66  5071.8 2157.91  5091.4 2158.83  5246.9 2171.85
  5309.5 2179.31  5314.8 2183.51  5324.9 2187.55  5335.0 2195.91  5355.3 2207.11
  5365.4 2214.19  5372.1 2223.24  5377.1 2222.52  5385.6 2225.51  5405.9 2223.09
#Mann=6,-1,0
  3949.5   0.035       0  4745.8    0.07       0  4962.9    0.16       0
  4973.4    0.07       0  4977.9    0.16       0  5091.4    0.07       0
Bank Sta=4973.4,4977.9
Exp/Cntr=0.3,0.1

Type RM Length L Ch R = 1,2524,0,0,0
BEGIN DESCRIPTION:
Cottonwood Trib050 5.0
END DESCRIPTION:
XS GIS Cut Line= 3
      1336585.35      6891578.18      1337327.30      6892460.33
      1337705.03      6891937.96
#Sta/Elev= 30
  3871.6 2160.14  4176.2 2159.59  4481.8 2155.87  4602.8 2155.92  4760.7 2153.24
  4808.3 2151.94  4829.1 2149.25  4872.0 2150.43  4900.6 2148.70  5086.6 2148.18
  5086.9 2147.68  5091.2 2148.18  5146.4 2149.76  5232.2 2156.40  5297.2 2158.06
  5360.3 2161.97  5389.2 2161.91  5418.6 2157.58  5475.1 2163.00  5489.8 2162.33
  5496.1 2159.54  5504.5 2158.49  5530.2 2158.74  5596.5 2161.21  5605.1 2164.74
  5611.2 2162.21  5619.5 2164.64  5632.1 2163.89  5655.3 2169.49  5668.9 2169.91
#Mann=5,-1,0
  3871.6   0.035       0  4760.7    0.07       0  5086.6    0.07       0
  5091.2    0.07       0  5530.2   0.035       0
Bank Sta=5086.6,5091.2
Exp/Cntr=0.3,0.1

Chan Stop Cuts=-1