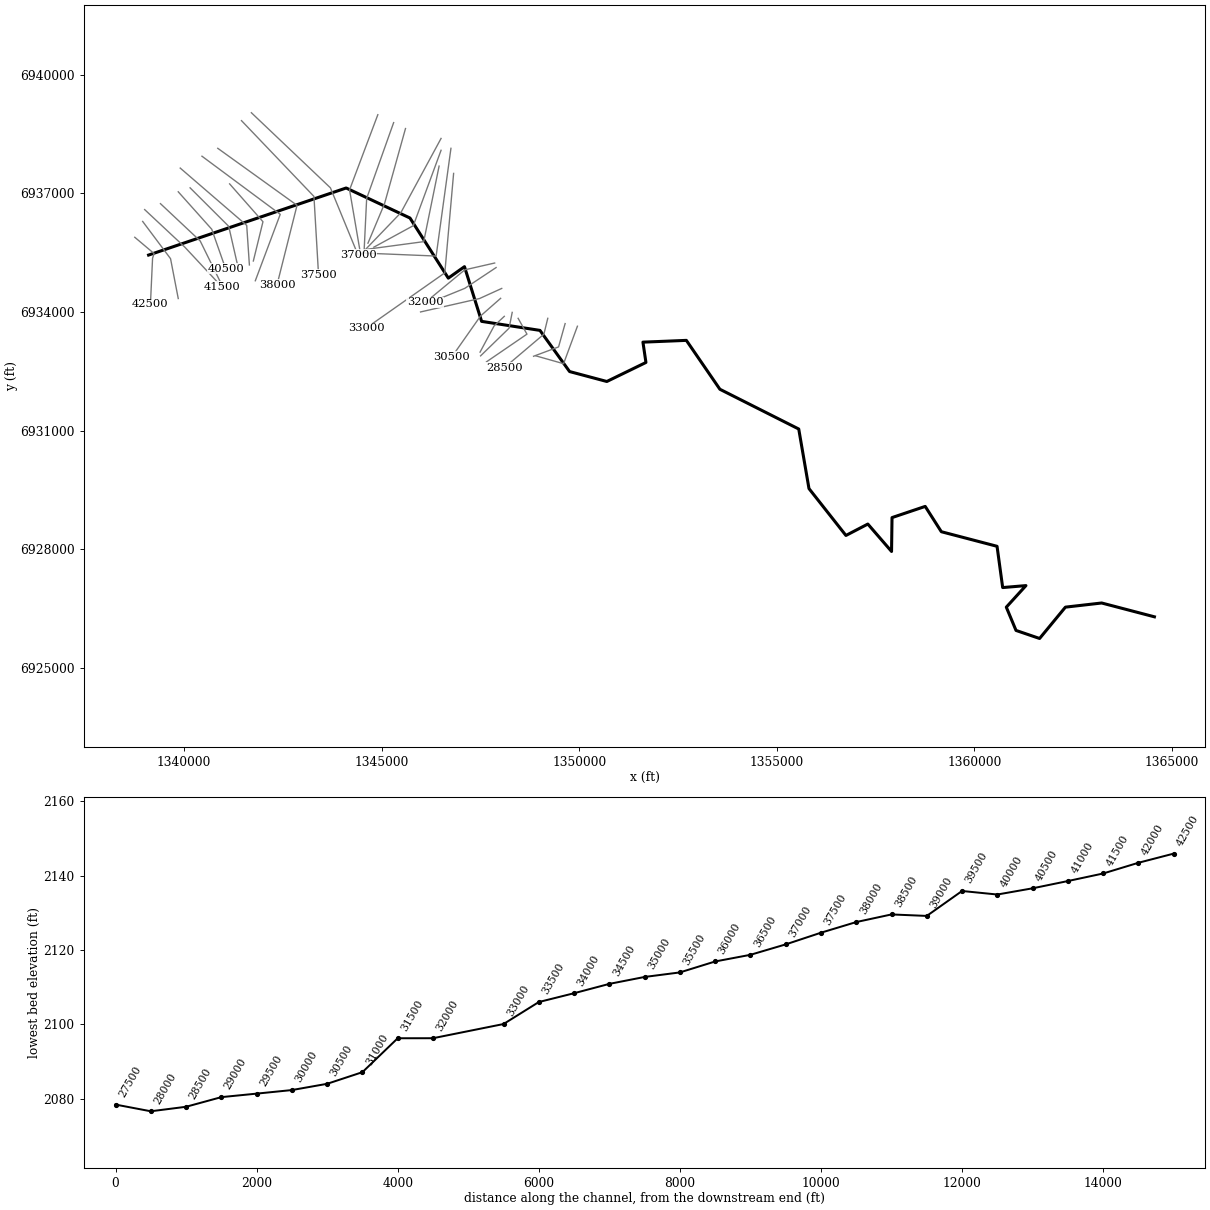
--- Cottonwood Trib100.prj (project) ---

Proj Title=Cottonwood Trib100 Base Level Engineering
Current Plan=p01
Default Exp/Contr=0.3,0.1
English Units
Geom File=g01
Flow File=f01
Plan File=p01
BEGIN DESCRIPTION:
Cottonwood Trib100
END DESCRIPTION:

--- Cottonwood Trib100.p01 (plan) ---

Plan Title=Multiple Run
Short Identifier=Multiple
Geom File=g01
Flow File=f01
Subcritical Flow
K Sum by GR= 0
Std Step Tol= 0.01
Critical Tol= 0.01
Num of Std Step Trials= 20
Max Error Tol= 0.3
Flow Tol Ratio= 0.001
Split Flow NTrial= 30
Split Flow Tol= 0.02
Split Flow Ratio= 0.02
Log Output Level= 0
Friction Slope Method= 1
Unsteady Friction Slope Method= 2
Unsteady Bridges Friction Slope Method= 1
Parabolic Critical Depth
Global Vel Dist=  1 , 1 , 1
Global Log Level= 0
CheckData=True
Encroach Param= -1, 0, 0, 0
BEGIN DESCRIPTION:
Multiple Run
END DESCRIPTION:

--- Cottonwood Trib100.f01 (steady flow) ---

Flow Title=Multiple
Number of Profiles=7
Profile Names=10-year,25-year,50-year,1pct_min,100-year,1pct_plu,500-year
River Rch & RM= Cottonwood Trib1,Reach-1,42500
     300     430     540     338     674    1345    1063
River Rch & RM= Cottonwood Trib1,Reach-1,38000
     451     659     838     530    1057    2109    1704
River Rch & RM= Cottonwood Trib1,Reach-1,32000
     631     936    1203     767    1530    3053    2511
River Rch & RM= Cottonwood Trib1,Reach-1,28500
     708    1053    1356     866    1728    3448    2846
River Rch & RM= Cottonwood Trib1,Reach-1,25947
     814    1218    1574    1008    2012    4014    3334
River Rch & RM= Cottonwood Trib1,Reach-1,23000
     815    1215    1567    1002    1998    3987    3296
River Rch & RM= Cottonwood Trib1,Reach-1,18500
    1115    1681    2185    1405    2804    5595    4686
River Rch & RM= Cottonwood Trib1,Reach-1,13238
    1138    1711    2219    1424    2842    5670    4727
River Rch & RM= Cottonwood Trib1,Reach-1,4500
    1166    1752    2271    1456    2905    5797    4824
Boundary for River Rch & Prof#=Cottonwood Trib1,Reach-1,1
Up Type=0
Dn Type=3
Dn Slope=0.005
Boundary for River Rch & Prof#=Cottonwood Trib1,Reach-1,2
Up Type=0
Dn Type=3
Dn Slope=0.005
Boundary for River Rch & Prof#=Cottonwood Trib1,Reach-1,3
Up Type=0
Dn Type=3
Dn Slope=0.005
Boundary for River Rch & Prof#=Cottonwood Trib1,Reach-1,4
Up Type=0
Dn Type=3
Dn Slope=0.005
Boundary for River Rch & Prof#=Cottonwood Trib1,Reach-1,5
Up Type=0
Dn Type=3
Dn Slope=0.005
Boundary for River Rch & Prof#=Cottonwood Trib1,Reach-1,6
Up Type=0
Dn Type=3
Dn Slope=0.005
Boundary for River Rch & Prof#=Cottonwood Trib1,Reach-1,7
Up Type=0
Dn Type=3
Dn Slope=0.005

--- Cottonwood Trib100.g01 (geometry) ---

Geom Title=Existing Conditions

River Reach=Cottonwood Trib1,Reach-1
Reach XY= 30
      1339105.00      6935438.00      1344103.45      6937134.25
      1345718.63      6936374.54      1346688.30      6934854.18
      1347097.32      6935144.52      1347531.03      6933760.80
      1349007.45      6933532.55      1349756.46      6932491.54
      1350699.15      6932240.04      1351688.78      6932721.32
      1351612.91      6933235.09      1352711.21      6933280.20
      1353560.26      6932043.47      1355555.00      6931038.00
      1355814.22      6929531.42      1356748.86      6928345.73
      1357303.54      6928634.46      1357903.39      6927941.12
      1357915.48      6928797.80      1358755.08      6929080.70
      1359163.10      6928440.43      1360572.69      6928071.57
      1360715.28      6927027.94      1361303.80      6927077.49
      1360807.04      6926532.13      1361052.64      6925943.75
      1361649.15      6925740.06      1362302.57      6926532.60
      1363220.16      6926637.62      1364555.00      6926288.00

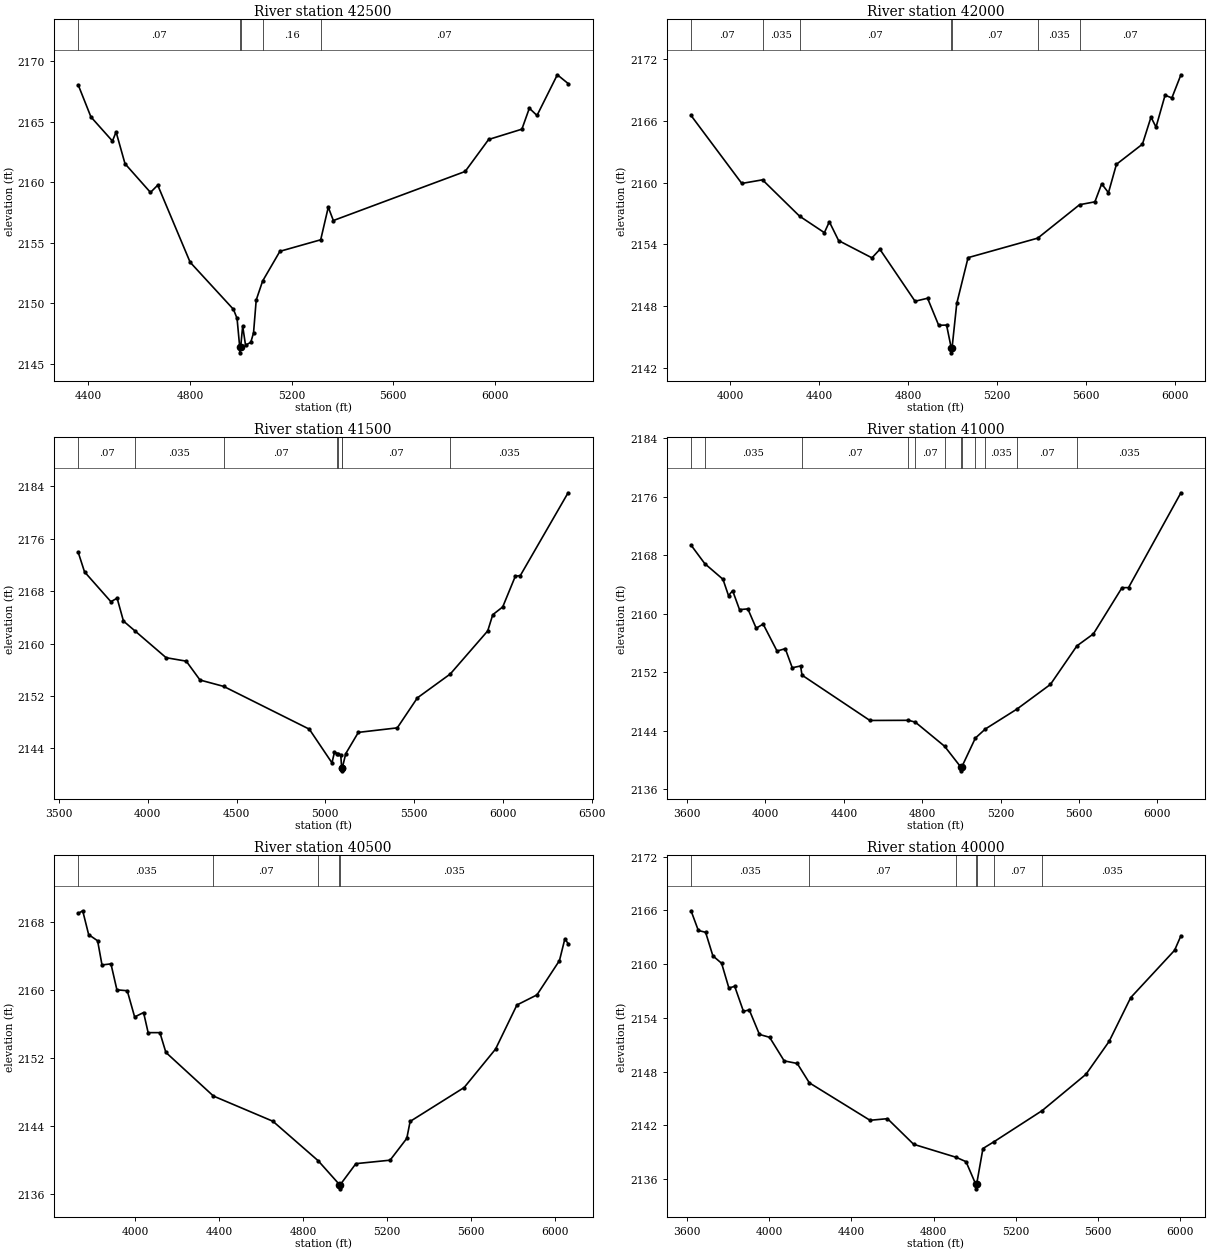
Type RM Length L Ch R = 1,42500,500,500,500
BEGIN DESCRIPTION:
Cottonwood Trib100 83.0
END DESCRIPTION:
XS GIS Cut Line= 4
      1338755.01      6935887.99      1339243.69      6935475.65
      1339205.21      6935357.23      1339151.39      6934195.79
#Sta/Elev= 30
  4360.6 2168.02  4410.6 2165.38  4495.2 2163.39  4509.5 2164.14  4544.6 2161.52
  4644.7 2159.15  4673.3 2159.75  4800.7 2153.39  4971.1 2149.50  4985.3 2148.75
  4995.6 2146.41  4995.8 2145.91  4999.6 2146.41  5007.4 2148.12  5018.6 2146.54
  5039.3 2146.78  5050.1 2147.56  5060.6 2150.27  5085.9 2151.84  5153.8 2154.29
  5314.2 2155.24  5344.0 2157.93  5364.0 2156.83  5882.4 2160.88  5974.7 2163.52
  6105.5 2164.37  6134.8 2166.10  6164.9 2165.50  6244.9 2168.86  6287.2 2168.14
#Mann=5,-1,0
  4360.6    0.07       0  4995.6    0.07       0  4999.6    0.07       0
  5085.9    0.16       0  5314.2    0.07       0
Bank Sta=4995.6,4999.6
Exp/Cntr=0.3,0.1

Type RM Length L Ch R = 1,42000,500,500,500
BEGIN DESCRIPTION:
Cottonwood Trib100 82.0
END DESCRIPTION:
XS GIS Cut Line= 3
      1338955.00      6936288.01      1339660.18      6935346.27
      1339855.00      6934338.02
#Sta/Elev= 30
  3823.5 2166.54  4051.7 2159.93  4144.9 2160.28  4311.4 2156.75  4423.2 2155.14
  4445.5 2156.20  4487.2 2154.37  4637.2 2152.69  4673.0 2153.52  4831.0 2148.47
  4887.3 2148.76  4937.3 2146.13  4972.8 2146.15  4993.6 2143.95  4993.9 2143.45
  4997.6 2143.95  5018.6 2148.25  5069.5 2152.71  5383.0 2154.61  5571.0 2157.86
  5639.9 2158.14  5670.4 2159.89  5701.0 2159.03  5736.8 2161.79  5853.8 2163.75
  5892.3 2166.38  5914.9 2165.41  5955.6 2168.51  5986.2 2168.25  6026.9 2170.50
#Mann=7,-1,0
  3823.5    0.07       0  4144.9   0.035       0  4311.4    0.07       0
  4993.6    0.07       0  4997.6    0.07       0  5383.0   0.035       0
  5571.0    0.07       0
Bank Sta=4993.6,4997.6
Exp/Cntr=0.3,0.1

Type RM Length L Ch R = 1,41500,500,500,500
BEGIN DESCRIPTION:
Cottonwood Trib100 81.0
END DESCRIPTION:
XS GIS Cut Line= 3
      1339004.97      6936588.03      1340021.60      6935637.76
      1340955.03      6934637.97
#Sta/Elev= 30
  3608.4 2173.92  3643.9 2170.94  3792.4 2166.39  3827.5 2166.92  3863.2 2163.43
  3928.8 2161.91  4103.5 2157.84  4216.9 2157.31  4294.5 2154.43  4427.5 2153.46
  4910.1 2146.93  5037.7 2141.79  5051.9 2143.43  5068.6 2143.20  5068.9 2143.19
  5087.1 2142.99  5092.4 2141.07  5092.7 2140.57  5096.4 2141.07  5115.4 2143.20
  5186.3 2146.44  5405.6 2147.13  5518.9 2151.71  5704.1 2155.35  5915.1 2161.93
  5943.5 2164.40  5999.6 2165.59  6070.5 2170.27  6098.8 2170.38  6367.8 2183.01
#Mann=8,-1,0
  3608.4    0.07       0  3928.8   0.035       0  4427.5    0.07       0
  5068.6   0.035       0  5068.9    0.07       0  5092.4    0.07       0
  5096.4    0.07       0  5704.1   0.035       0
Bank Sta=5092.4,5096.4
Exp/Cntr=0.3,0.1

Type RM Length L Ch R = 1,41000,500,500,500
BEGIN DESCRIPTION:
Cottonwood Trib100 80.0
END DESCRIPTION:
XS GIS Cut Line= 3
      1339404.99      6936738.01      1340410.99      6935793.51
      1340905.00      6934788.01
#Sta/Elev= 30
  3620.1 2169.41  3690.1 2166.88  3783.0 2164.74  3811.3 2162.50  3832.3 2163.18
  3867.5 2160.59  3910.0 2160.69  3952.5 2158.05  3988.1 2158.61  4059.0 2154.92
  4101.0 2155.25  4136.6 2152.64  4179.1 2152.88  4186.4 2151.63  4532.8 2145.43
  4729.9 2145.45  4764.6 2145.20  4914.2 2141.90  4997.3 2139.04  4997.6 2138.54
  5001.3 2139.04  5071.2 2143.02  5122.0 2144.26  5283.1 2146.98  5454.3 2150.36
  5589.4 2155.63  5673.6 2157.27  5819.6 2163.59  5852.9 2163.60  6120.3 2176.57
#Mann=12,-1,0
  3620.1    0.07       0  3690.1   0.035       0  4186.4    0.07       0
  4729.9   0.035       0  4764.6    0.07       0  4914.2   0.035       0
  4997.3   0.035       0  5001.3   0.035       0  5071.2    0.07       0
  5122.0   0.035       0  5283.1    0.07       0  5589.4   0.035       0
Bank Sta=4997.3,5001.3
Exp/Cntr=0.3,0.1

Type RM Length L Ch R = 1,40500,500,500,500
BEGIN DESCRIPTION:
Cottonwood Trib100 79.0
END DESCRIPTION:
XS GIS Cut Line= 3
      1339854.99      6937038.01      1340702.26      6936091.00
      1341054.99      6935088.02
#Sta/Elev= 30
  3729.3 2169.07  3750.6 2169.38  3779.0 2166.57  3821.7 2165.84  3842.6 2162.99
  3885.2 2163.12  3913.6 2160.06  3962.9 2159.95  3998.1 2156.86  4040.7 2157.38
  4062.4 2155.01  4118.4 2155.01  4146.9 2152.68  4373.6 2147.53  4656.8 2144.56
  4872.7 2139.90  4974.0 2137.09  4974.3 2136.59  4978.0 2137.09  5052.2 2139.56
  5215.2 2139.97  5294.7 2142.54  5310.6 2144.54  5568.1 2148.54  5717.6 2153.07
  5819.4 2158.27  5914.8 2159.46  6022.1 2163.51  6047.7 2166.06  6063.2 2165.52
#Mann=5,-1,0
  3729.3   0.035       0  4373.6    0.07       0  4872.7   0.035       0
  4974.0   0.035       0  4978.0   0.035       0
Bank Sta=4974,4978
Exp/Cntr=0.3,0.1

Type RM Length L Ch R = 1,40000,500,500,500
BEGIN DESCRIPTION:
Cottonwood Trib100 78.0
END DESCRIPTION:
XS GIS Cut Line= 3
      1340154.99      6937138.01      1341131.79      6936164.90
      1341355.00      6935187.98
#Sta/Elev= 30
  3621.2 2165.95  3656.6 2163.75  3691.9 2163.55  3727.3 2160.92  3769.7 2160.09
  3805.1 2157.33  3833.3 2157.52  3875.8 2154.73  3904.1 2154.89  3953.6 2152.15
  4003.0 2151.83  4073.8 2149.20  4137.4 2148.91  4196.1 2146.75  4491.0 2142.57
  4575.8 2142.75  4703.1 2139.89  4909.6 2138.44  4957.7 2137.95  5005.1 2135.42
  5005.3 2134.92  5009.1 2135.42  5039.9 2139.42  5095.2 2140.20  5327.7 2143.65
  5540.5 2147.70  5653.3 2151.38  5758.1 2156.26  5971.3 2161.54  6002.1 2163.16
#Mann=7,-1,0
  3621.2   0.035       0  4196.1    0.07       0  4909.6   0.035       0
  5005.1   0.035       0  5009.1   0.035       0  5095.2    0.07       0
  5327.7   0.035       0
Bank Sta=5005.1,5009.1
Exp/Cntr=0.3,0.1

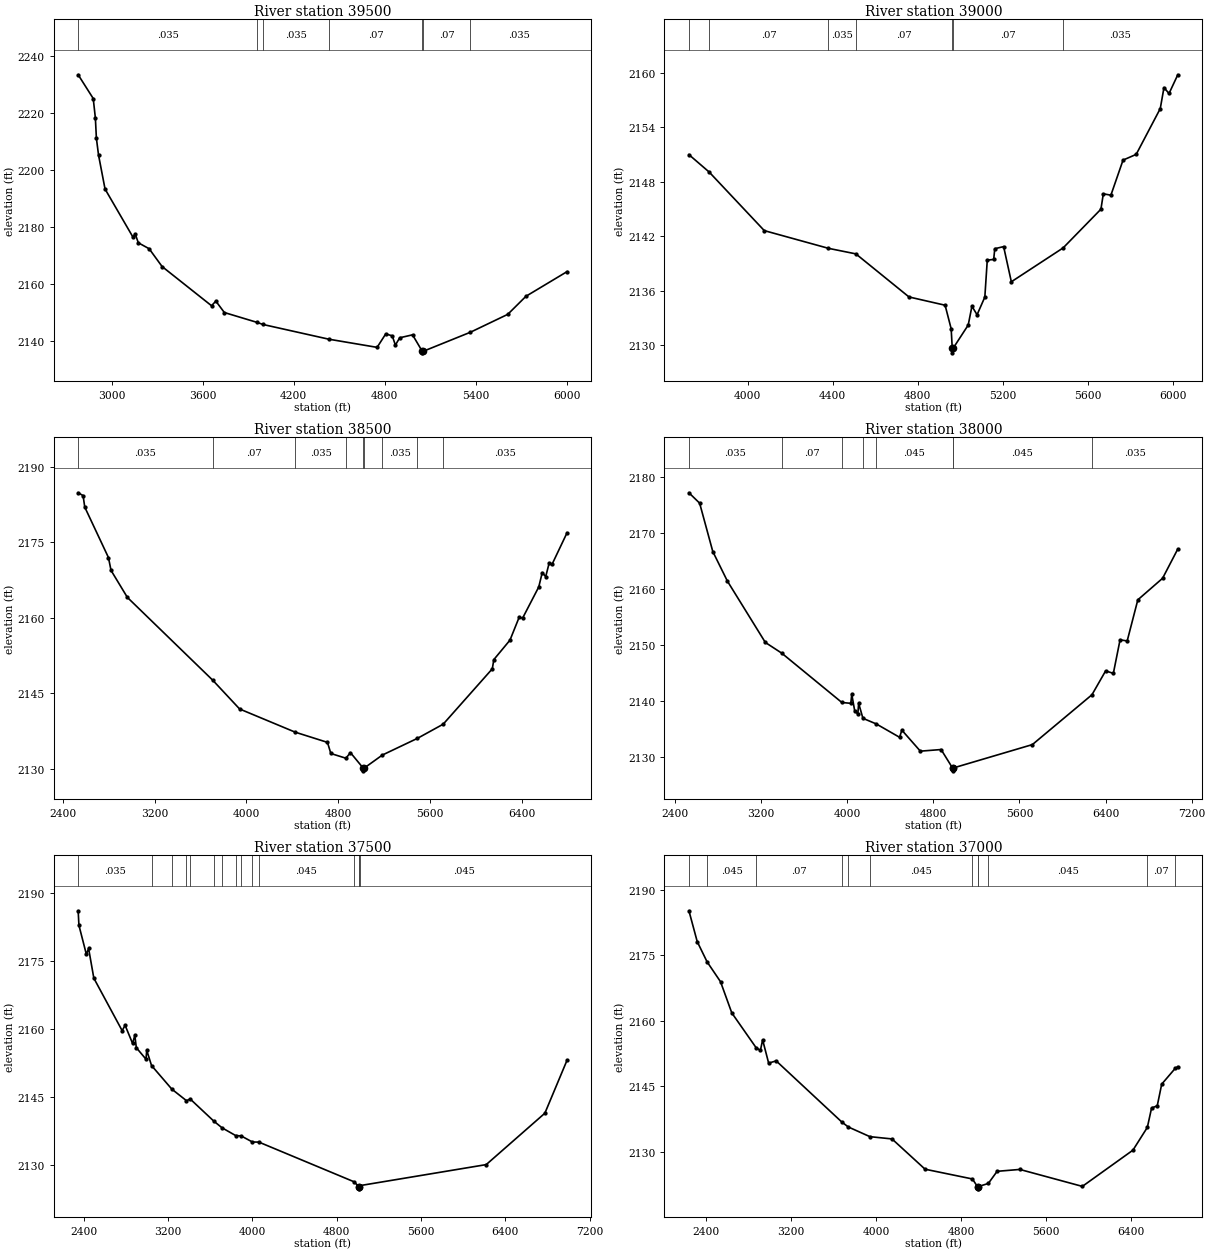
Type RM Length L Ch R = 1,39500,500,500,500
BEGIN DESCRIPTION:
Cottonwood Trib100 77.0
END DESCRIPTION:
XS GIS Cut Line= 3
      1339905.02      6937637.98      1341587.36      6936188.27
      1341655.00      6935187.95
#Sta/Elev= 30
  2779.2 2233.33  2878.5 2225.01  2892.7 2218.15  2899.3 2211.08  2913.6 2205.15
  2956.4 2193.28  3140.7 2176.41  3154.9 2177.59  3175.8 2174.44  3247.1 2172.36
  3332.7 2166.11  3658.5 2152.38  3687.0 2154.00  3743.0 2150.00  3960.9 2146.51
  3997.0 2145.82  4432.0 2140.65  4750.2 2137.79  4807.2 2142.51  4850.0 2141.83
  4870.8 2138.59  4899.4 2141.15  4983.9 2142.18  5048.4 2136.37  5048.6 2135.87
  5052.4 2136.37  5365.8 2143.10  5611.7 2149.36  5731.9 2155.70  6002.6 2164.33
#Mann=7,-1,0
  2779.2   0.035       0  3960.9    0.07       0  3997.0   0.035       0
  4432.0    0.07       0  5048.4    0.07       0  5052.4    0.07       0
  5365.8   0.035       0
Bank Sta=5048.4,5052.4
Exp/Cntr=0.3,0.1

Type RM Length L Ch R = 1,39000,500,500,500
BEGIN DESCRIPTION:
Cottonwood Trib100 76.0
END DESCRIPTION:
XS GIS Cut Line= 3
      1341154.98      6937238.02      1341998.51      6936281.40
      1341755.00      6935288.01
#Sta/Elev= 30
  3724.6 2150.98  3819.6 2149.07  4078.9 2142.62  4380.7 2140.67  4509.4 2140.06
  4759.1 2135.32  4928.9 2134.41  4957.4 2131.82  4962.5 2129.67  4962.8 2129.17
  4966.5 2129.67  5037.6 2132.23  5055.0 2134.30  5079.2 2133.36  5115.7 2135.31
  5127.1 2139.37  5157.3 2139.45  5162.4 2140.63  5204.0 2140.86  5240.3 2136.99
  5483.9 2140.72  5661.5 2144.98  5672.7 2146.67  5708.3 2146.52  5765.4 2150.38
  5827.2 2151.01  5940.4 2156.05  5957.8 2158.36  5981.6 2157.71  6022.8 2159.77
#Mann=7,-1,0
  3724.6   0.035       0  3819.6    0.07       0  4380.7   0.035       0
  4509.4    0.07       0  4962.5    0.07       0  4966.5    0.07       0
  5483.9   0.035       0
Bank Sta=4962.5,4966.5
Exp/Cntr=0.3,0.1

Type RM Length L Ch R = 1,38500,500,500,500
BEGIN DESCRIPTION:
Cottonwood Trib100 75.0
END DESCRIPTION:
XS GIS Cut Line= 3
      1340455.00      6937938.00      1342435.59      6936468.18
      1341805.01      6934788.02
#Sta/Elev= 30
  2533.6 2184.88  2576.4 2184.32  2591.0 2182.03  2797.5 2172.00  2820.0 2169.44
  2962.4 2164.07  3706.8 2147.59  3940.9 2141.87  4425.5 2137.26  4706.6 2135.23
  4735.9 2133.02  4867.1 2132.08  4906.9 2133.19  5019.6 2130.07  5019.8 2129.57
  5023.6 2130.07  5184.8 2132.71  5490.4 2136.03  5715.1 2138.85  6143.1 2149.86
  6156.7 2151.70  6297.3 2155.57  6377.3 2160.12  6407.6 2159.96  6548.2 2166.15
  6578.4 2169.00  6608.7 2168.20  6638.9 2170.91  6663.8 2170.64  6794.6 2176.92
#Mann=9,-1,0
  2533.6   0.035       0  3706.8    0.07       0  4425.5   0.035       0
  4867.1   0.045       0  5019.6   0.045       0  5023.6   0.045       0
  5184.8   0.035       0  5490.4    0.07       0  5715.1   0.035       0
Bank Sta=5019.6,5023.6
Exp/Cntr=0.3,0.1

Type RM Length L Ch R = 1,38000,500,500,500
BEGIN DESCRIPTION:
Cottonwood Trib100 74.0
END DESCRIPTION:
XS GIS Cut Line= 3
      1340855.01      6938137.99      1342860.53      6936696.19
      1342355.01      6934688.04
#Sta/Elev= 30
  2530.0 2177.11  2629.4 2175.26  2751.7 2166.63  2887.2 2161.36  3239.6 2150.42
  3391.9 2148.51  3950.6 2139.71  4033.8 2139.56  4042.4 2141.18  4069.5 2138.25
  4098.9 2137.65  4106.4 2139.56  4146.1 2136.89  4270.7 2135.88  4486.8 2133.50
  4507.7 2134.78  4679.6 2131.03  4872.3 2131.32  4978.8 2128.02  4979.0 2127.52
  4983.0 2128.02  5720.0 2132.20  6273.6 2141.09  6400.6 2145.35  6472.2 2144.90
  6534.6 2150.89  6600.7 2150.68  6699.6 2158.02  6929.5 2161.86  7070.8 2167.08
#Mann=8,-1,0
  2530.0   0.035       0  3391.9    0.07       0  3950.6   0.035       0
  4146.1    0.07       0  4270.7   0.045       0  4978.8   0.045       0
  4983.0   0.045       0  6273.6   0.035       0
Bank Sta=4978.8,4983
Exp/Cntr=0.3,0.1

Type RM Length L Ch R = 1,37500,500,500,500
BEGIN DESCRIPTION:
Cottonwood Trib100 73.0
END DESCRIPTION:
XS GIS Cut Line= 3
      1341454.99      6938838.01      1343288.53      6936921.00
      1343405.00      6934938.02
#Sta/Elev= 30
  2347.3 2186.05  2354.4 2182.85  2425.2 2176.42  2446.2 2177.74  2495.9 2171.17
  2764.5 2159.59  2792.8 2160.76  2863.6 2156.76  2885.0 2158.56  2899.1 2155.82
  2990.9 2153.28  2997.9 2155.24  3043.5 2151.88  3236.2 2146.67  3375.1 2144.12
  3410.6 2144.49  3634.4 2139.61  3712.2 2138.14  3841.2 2136.43  3894.1 2136.34
  4000.8 2135.00  4062.0 2134.98  4964.1 2126.23  5010.9 2125.16  5011.2 2124.66
  5015.2 2125.16  5023.4 2125.38  6219.5 2130.01  6776.1 2141.36  6986.4 2153.05
#Mann=15,-1,0
  2347.3   0.035       0  3043.5    0.07       0  3236.2   0.045       0
  3375.1    0.07       0  3410.6   0.045       0  3634.4    0.07       0
  3712.2   0.045       0  3841.2    0.07       0  3894.1   0.045       0
  4000.8    0.07       0  4062.0   0.045       0  4964.1    0.07       0
  5010.9    0.07       0  5015.2    0.07       0  5023.4   0.045       0
Bank Sta=5010.9,5015.2
Exp/Cntr=0.3,0.1

Type RM Length L Ch R = 1,37000,500,500,500
BEGIN DESCRIPTION:
Cottonwood Trib100 72.0
END DESCRIPTION:
XS GIS Cut Line= 3
      1341704.99      6939038.01      1343705.39      6937138.03
      1344405.02      6935437.96
#Sta/Elev= 30
  2241.1 2185.15  2319.0 2178.10  2411.5 2173.48  2538.2 2168.92  2644.2 2161.78
  2873.1 2153.81  2913.2 2153.20  2934.2 2155.61  2990.8 2150.29  3061.6 2150.80
  3677.9 2136.83  3739.6 2135.68  3943.1 2133.46  4150.9 2132.94  4462.0 2126.01
  4906.7 2123.78  4955.0 2122.02  4955.4 2121.52  4959.9 2122.02  5056.5 2122.75
  5139.4 2125.53  5352.6 2125.96  5940.8 2122.08  6416.6 2130.37  6552.0 2135.58
  6591.9 2140.02  6645.2 2140.52  6687.0 2145.47  6814.5 2149.10  6838.4 2149.47
#Mann=12,-1,0
  2241.1   0.035       0  2411.5   0.045       0  2873.1    0.07       0
  3677.9   0.045       0  3739.6    0.07       0  3943.1   0.045       0
  4906.7    0.07       0  4955.0    0.07       0  4959.9    0.07       0
  5056.5   0.045       0  6552.0    0.07       0  6814.5   0.045       0
Bank Sta=4955,4959.9
Exp/Cntr=0.3,0.1

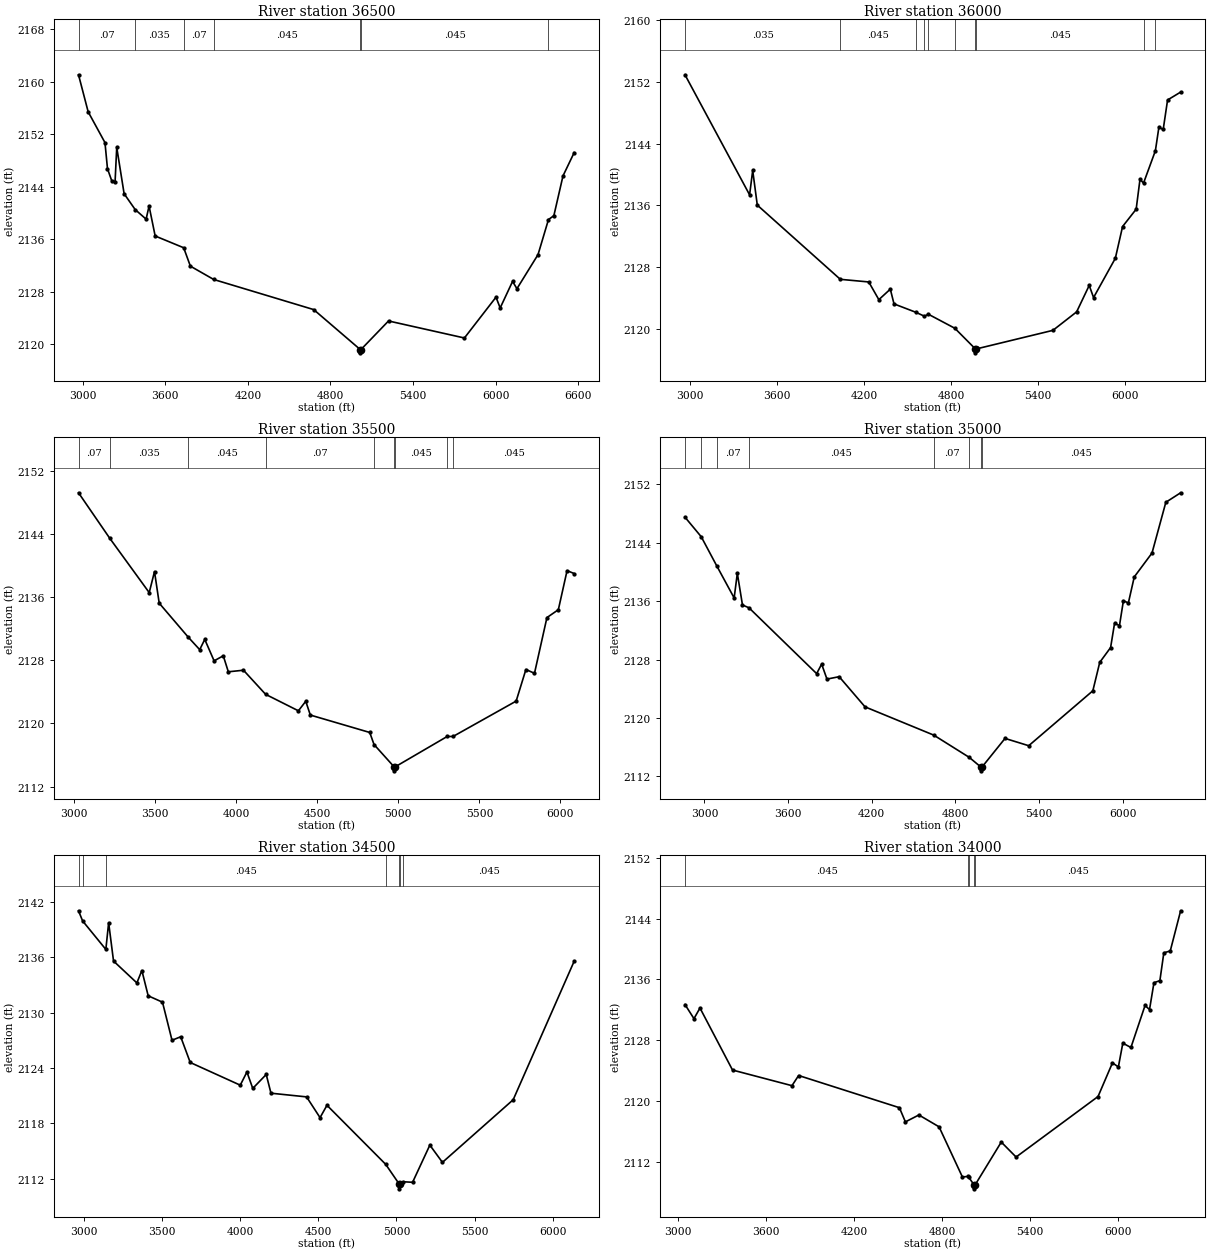
Type RM Length L Ch R = 1,36500,500,500,500
BEGIN DESCRIPTION:
Cottonwood Trib100 71.0
END DESCRIPTION:
XS GIS Cut Line= 3
      1344904.99      6938987.97      1344189.47      6937087.08
      1344455.01      6935537.97
#Sta/Elev= 30
  2968.9 2161.03  3039.1 2155.39  3161.2 2150.71  3179.5 2146.74  3209.7 2144.94
  3234.6 2144.71  3246.7 2149.99  3300.4 2142.93  3380.8 2140.52  3460.3 2139.06
  3481.7 2141.06  3526.1 2136.50  3733.3 2134.71  3782.1 2131.91  3951.9 2129.88
  4678.5 2125.30  5016.9 2119.22  5017.3 2118.72  5021.8 2119.22  5222.3 2123.57
  5773.9 2120.98  6003.5 2127.19  6033.9 2125.55  6124.0 2129.59  6155.7 2128.48
  6309.1 2133.67  6384.9 2139.00  6424.1 2139.59  6490.5 2145.64  6571.7 2149.19
#Mann=7,-1,0
  2968.9    0.07       0  3380.8   0.035       0  3733.3    0.07       0
  3951.9   0.045       0  5016.9   0.045       0  5021.8   0.045       0
  6384.9    0.07       0
Bank Sta=5016.9,5021.8
Exp/Cntr=0.3,0.1

Type RM Length L Ch R = 1,36000,500,500,500
BEGIN DESCRIPTION:
Cottonwood Trib100 70.0
END DESCRIPTION:
XS GIS Cut Line= 3
      1345304.99      6938787.98      1344622.37      6936870.67
      1344555.00      6935488.01
#Sta/Elev= 30
  2964.8 2152.90  3410.6 2137.37  3432.0 2140.52  3463.7 2136.04  4036.4 2126.44
  4232.6 2126.10  4302.3 2123.81  4381.4 2125.17  4406.9 2123.26  4555.7 2122.19
  4616.6 2121.67  4644.4 2121.92  4826.5 2120.11  4968.5 2117.43  4968.9 2116.93
  4973.4 2117.43  5503.3 2119.84  5666.8 2122.23  5753.6 2125.65  5783.6 2124.08
  5933.8 2129.16  5983.8 2133.27  6077.5 2135.51  6104.0 2139.39  6128.2 2138.88
  6210.1 2143.07  6234.1 2146.09  6264.2 2145.84  6294.2 2149.64  6384.3 2150.66
#Mann=10,-1,0
  2964.8   0.035       0  4036.4   0.045       0  4555.7    0.07       0
  4616.6   0.045       0  4644.4    0.07       0  4826.5   0.045       0
  4968.5   0.045       0  4973.4   0.045       0  6128.2    0.07       0
  6210.1   0.045       0
Bank Sta=4968.5,4973.4
Exp/Cntr=0.3,0.1

Type RM Length L Ch R = 1,35500,500,500,500
BEGIN DESCRIPTION:
Cottonwood Trib100 69.0
END DESCRIPTION:
XS GIS Cut Line= 3
      1345605.00      6938638.02      1345074.65      6936738.05
      1344655.01      6935738.03
#Sta/Elev= 30
  3027.4 2149.28  3219.6 2143.52  3463.5 2136.61  3496.1 2139.28  3525.1 2135.27
  3704.4 2130.95  3774.9 2129.37  3806.1 2130.67  3863.7 2127.95  3920.3 2128.59
  3951.4 2126.56  4044.9 2126.76  4181.4 2123.70  4383.6 2121.61  4429.0 2122.82
  4457.2 2121.07  4823.6 2118.86  4850.1 2117.33  4974.2 2114.49  4974.7 2113.99
  4979.9 2114.49  5301.2 2118.35  5337.4 2118.35  5726.7 2122.84  5786.8 2126.85
  5839.8 2126.37  5916.5 2133.44  5986.9 2134.44  6040.7 2139.40  6084.5 2139.03
#Mann=9,-1,0
  3027.4    0.07       0  3219.6   0.035       0  3704.4   0.045       0
  4181.4    0.07       0  4850.1   0.045       0  4974.2   0.045       0
  4979.9   0.045       0  5301.2    0.07       0  5337.4   0.045       0
Bank Sta=4974.2,4979.9
Exp/Cntr=0.3,0.1

Type RM Length L Ch R = 1,35000,500,500,500
BEGIN DESCRIPTION:
Cottonwood Trib100 68.0
END DESCRIPTION:
XS GIS Cut Line= 3
      1346504.99      6938387.98      1345485.83      6936507.05
      1344504.99      6935487.99
#Sta/Elev= 30
  2860.7 2147.50  2977.3 2144.82  3088.0 2140.85  3213.3 2136.44  3236.0 2139.81
  3272.9 2135.48  3319.7 2135.09  3804.7 2126.08  3840.6 2127.38  3878.7 2125.33
  3966.1 2125.66  4151.6 2121.53  4644.5 2117.66  4899.2 2114.61  4983.6 2113.27
  4984.1 2112.77  4989.5 2113.27  5155.4 2117.21  5325.2 2116.21  5785.0 2123.73
  5834.4 2127.62  5912.3 2129.65  5940.6 2132.96  5975.9 2132.66  6004.2 2136.07
  6039.6 2135.75  6081.9 2139.32  6209.2 2142.59  6308.3 2149.54  6414.4 2150.84
#Mann=8,-1,0
  2860.7   0.035       0  2977.3   0.045       0  3088.0    0.07       0
  3319.7   0.045       0  4644.5    0.07       0  4899.2   0.045       0
  4983.6   0.045       0  4989.5   0.045       0
Bank Sta=4983.6,4989.5
Exp/Cntr=0.3,0.1

Type RM Length L Ch R = 1,34500,500,500,500
BEGIN DESCRIPTION:
Cottonwood Trib100 67.0
END DESCRIPTION:
XS GIS Cut Line= 3
      1346505.01      6938088.04      1345802.44      6936181.25
      1344804.99      6935637.99
#Sta/Elev= 30
  2967.9 2141.06  2994.1 2139.96  3142.6 2136.87  3160.5 2139.77  3191.7 2135.61
  3340.9 2133.24  3372.9 2134.58  3413.2 2131.84  3504.6 2131.15  3565.5 2127.02
  3621.0 2127.40  3682.0 2124.61  4001.7 2122.15  4044.3 2123.58  4081.6 2121.80
  4167.6 2123.31  4198.0 2121.28  4425.6 2120.88  4511.6 2118.63  4555.9 2119.97
  4931.1 2113.57  5018.4 2111.41  5018.9 2110.91  5024.4 2111.41  5042.0 2111.68
  5103.1 2111.62  5213.4 2115.65  5293.9 2113.78  5746.0 2120.57  6135.8 2135.59
#Mann=7,-1,0
  2967.9   0.045       0  2994.1    0.07       0  3142.6   0.045       0
  4931.1    0.07       0  5018.4    0.07       0  5024.4    0.07       0
  5042.0   0.045       0
Bank Sta=5018.4,5024.4
Exp/Cntr=0.3,0.1

Type RM Length L Ch R = 1,34000,500,500,500
BEGIN DESCRIPTION:
Cottonwood Trib100 66.0
END DESCRIPTION:
XS GIS Cut Line= 3
      1346455.00      6937688.01      1346065.81      6935777.14
      1344655.04      6935588.00
#Sta/Elev= 30
  3049.9 2132.68  3111.1 2130.82  3152.0 2132.22  3373.5 2124.05  3778.0 2121.99
  3823.5 2123.33  4509.3 2119.09  4550.1 2117.22  4641.9 2118.13  4779.2 2116.57
  4937.9 2109.97  4976.4 2110.03  4980.4 2109.95  5018.0 2108.90  5018.5 2108.40
  5024.0 2108.90  5202.6 2114.56  5303.5 2112.59  5861.2 2120.56  5959.3 2124.99
  5999.7 2124.46  6029.9 2127.59  6085.1 2127.02  6181.3 2132.56  6211.6 2132.01
  6241.8 2135.55  6282.2 2135.83  6309.0 2139.49  6352.8 2139.74  6423.4 2145.03
#Mann=5,-1,0
  3049.9   0.045       0  4976.4    0.07       0  4980.4   0.045       0
  5018.0   0.045       0  5024.0   0.045       0
Bank Sta=5018,5024
Exp/Cntr=0.3,0.1

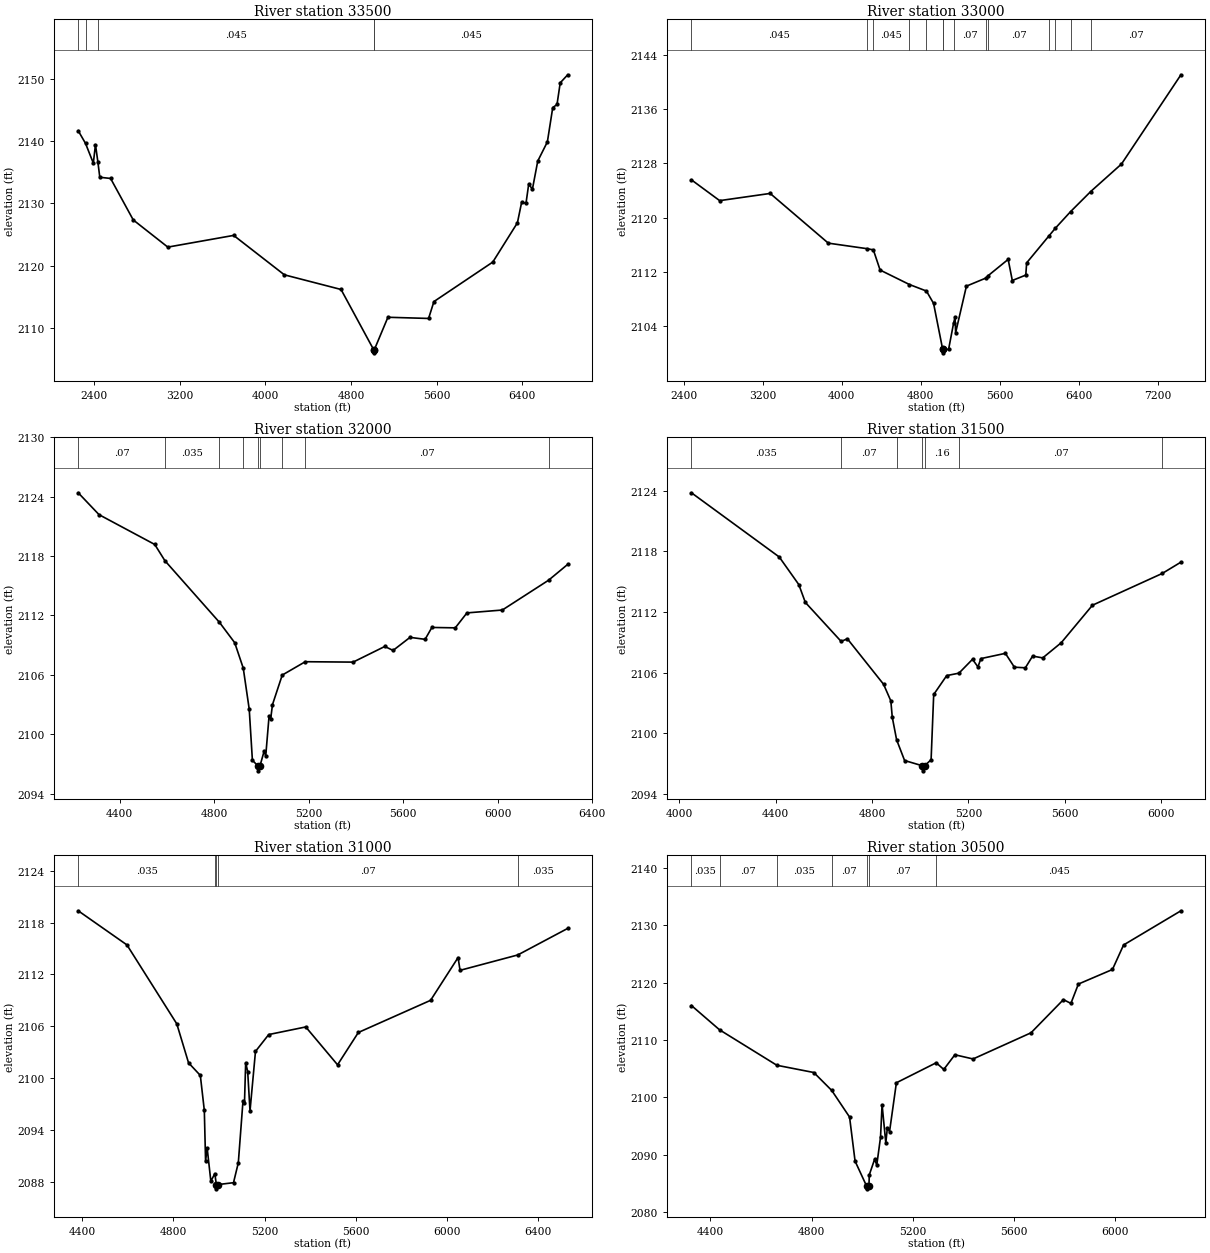
Type RM Length L Ch R = 1,33500,500,500,500
BEGIN DESCRIPTION:
Cottonwood Trib100 65.0
END DESCRIPTION:
XS GIS Cut Line= 3
      1346755.01      6938138.04      1346380.05      6935412.71
      1344555.00      6935488.00
#Sta/Elev= 30
  2249.0 2141.68  2317.3 2139.65  2390.4 2136.48  2410.5 2139.45  2433.6 2136.59
  2450.9 2134.21  2551.9 2134.02  2763.8 2127.36  3086.9 2123.00  3702.6 2124.88
  4177.0 2118.55  4706.9 2116.20  5012.1 2106.53  5012.6 2106.03  5018.1 2106.53
  5145.2 2111.74  5525.5 2111.55  5575.5 2114.26  6126.0 2120.60  6356.2 2126.90
  6396.2 2130.24  6436.3 2130.01  6462.0 2133.14  6496.3 2132.28  6546.4 2136.81
  6636.4 2139.89  6686.5 2145.39  6726.5 2145.89  6756.5 2149.37  6826.6 2150.66
#Mann=5,-1,0
  2249.0   0.045       0  2317.3    0.07       0  2433.6   0.045       0
  5012.1   0.045       0  5018.1   0.045       0
Bank Sta=5012.1,5018.1
Exp/Cntr=0.3,0.1

Type RM Length L Ch R = 1,33000,1000,1000,1000
BEGIN DESCRIPTION:
Cottonwood Trib100 64.0
END DESCRIPTION:
XS GIS Cut Line= 3
      1346822.40      6937503.04      1346599.98      6934987.95
      1344604.98      6933587.99
#Sta/Elev= 30
  2475.1 2125.59  2761.3 2122.53  3273.2 2123.59  3862.6 2116.27  4253.6 2115.46
  4319.3 2115.28  4387.6 2112.31  4684.8 2110.18  4857.2 2109.22  4929.7 2107.40
  5022.1 2100.62  5022.6 2100.12  5028.3 2100.62  5081.9 2100.63  5132.6 2104.49
  5147.2 2105.37  5153.3 2103.09  5262.6 2109.94  5463.2 2111.15  5482.7 2111.48
  5685.8 2113.88  5727.7 2110.77  5864.5 2111.57  5873.2 2113.37  6101.7 2117.38
  6162.3 2118.44  6318.4 2120.91  6522.4 2123.87  6834.5 2127.92  7437.2 2141.06
#Mann=14,-1,0
  2475.1   0.045       0  4253.6    0.07       0  4319.3   0.045       0
  4684.8   0.035       0  4857.2    0.16       0  5022.1    0.07       0
  5028.3    0.16       0  5132.6    0.07       0  5463.2   0.045       0
  5482.7    0.07       0  6101.7   0.035       0  6162.3    0.07       0
  6318.4   0.035       0  6522.4    0.07       0
Bank Sta=5022.1,5028.3
Exp/Cntr=0.3,0.1

Type RM Length L Ch R = 1,32000,500,500,500
BEGIN DESCRIPTION:
Cottonwood Trib100 63.0
END DESCRIPTION:
XS GIS Cut Line= 3
      1347861.00      6935236.57      1347105.02      6935064.13
      1346105.02      6934238.01
#Sta/Elev= 30
  4224.6 2124.39  4312.8 2122.18  4548.7 2119.17  4591.7 2117.53  4822.5 2111.31
  4887.2 2109.25  4923.4 2106.68  4948.7 2102.53  4962.1 2097.38  4985.4 2096.81
  4985.9 2096.31  4994.2 2096.81  5012.0 2098.32  5018.5 2097.80  5032.8 2101.87
  5039.3 2101.52  5047.2 2103.00  5088.4 2105.98  5186.0 2107.33  5388.5 2107.29
  5522.6 2108.87  5557.8 2108.47  5629.5 2109.79  5693.3 2109.59  5722.0 2110.79
  5821.0 2110.75  5870.5 2112.26  6020.3 2112.55  6216.1 2115.56  6297.1 2117.16
#Mann=9,-1,0
  4224.6    0.07       0  4591.7   0.035       0  4822.5    0.16       0
  4923.4    0.07       0  4985.4    0.07       0  4994.2    0.07       0
  5088.4    0.16       0  5186.0    0.07       0  6216.1   0.035       0
Bank Sta=4985.4,4994.2
Exp/Cntr=0.3,0.1

Type RM Length L Ch R = 1,31500,500,500,500
BEGIN DESCRIPTION:
Cottonwood Trib100 62.0
END DESCRIPTION:
XS GIS Cut Line= 3
      1347897.49      6935121.99      1347106.63      6934596.55
      1346105.04      6934188.02
#Sta/Elev= 30
  4050.5 2123.80  4414.9 2117.45  4496.1 2114.72  4523.1 2112.96  4671.7 2109.10
  4697.5 2109.36  4847.8 2104.86  4877.9 2103.22  4883.9 2101.60  4901.9 2099.37
  4935.0 2097.32  5009.2 2096.80  5009.7 2096.30  5018.1 2096.80  5045.0 2097.40
  5055.8 2103.85  5109.8 2105.72  5160.5 2105.96  5216.8 2107.33  5239.4 2106.58
  5251.6 2107.40  5353.2 2107.92  5390.6 2106.55  5436.1 2106.49  5466.2 2107.65
  5508.2 2107.47  5585.0 2108.97  5714.6 2112.68  6004.0 2115.82  6081.7 2116.94
#Mann=7,-1,0
  4050.5   0.035       0  4671.7    0.07       0  4901.9    0.16       0
  5009.2    0.07       0  5018.1    0.16       0  5160.5    0.07       0
  6004.0   0.035       0
Bank Sta=5009.2,5018.1
Exp/Cntr=0.3,0.1

Type RM Length L Ch R = 1,31000,500,500,500
BEGIN DESCRIPTION:
Cottonwood Trib100 61.0
END DESCRIPTION:
XS GIS Cut Line= 3
      1348039.86      6934593.70      1347477.82      6934338.16
      1345986.07      6933999.08
#Sta/Elev= 30
  4382.6 2119.36  4596.4 2115.41  4815.0 2106.28  4866.6 2101.77  4918.3 2100.31
  4935.8 2096.26  4941.3 2090.39  4948.2 2091.93  4964.4 2088.07  4981.9 2088.95
  4988.5 2087.69  4989.0 2087.19  4997.4 2087.69  5063.8 2087.90  5084.9 2090.20
  5105.4 2097.35  5112.0 2097.16  5117.2 2101.79  5126.0 2100.76  5136.2 2096.20
  5160.2 2103.09  5218.3 2105.04  5380.7 2105.92  5520.2 2101.54  5611.4 2105.28
  5928.3 2109.00  6048.9 2113.95  6057.5 2112.47  6310.9 2114.25  6529.8 2117.32
#Mann=5,-1,0
  4382.6   0.035       0  4981.9    0.07       0  4988.5    0.07       0
  4997.4    0.07       0  6310.9   0.035       0
Bank Sta=4988.5,4997.4
Exp/Cntr=0.3,0.1

Type RM Length L Ch R = 1,30500,500,500,500
BEGIN DESCRIPTION:
Cottonwood Trib100 60.0
END DESCRIPTION:
XS GIS Cut Line= 3
      1348012.10      6934343.72      1347504.93      6933898.15
      1346780.30      6932866.27
#Sta/Elev= 30
  4324.9 2116.00  4436.1 2111.77  4662.8 2105.59  4808.9 2104.33  4879.9 2101.20
  4950.3 2096.57  4972.1 2088.89  5017.5 2084.56  5018.0 2084.06  5026.9 2084.56
  5028.4 2086.51  5049.3 2089.20  5058.0 2088.23  5072.8 2093.06  5078.9 2098.72
  5093.7 2092.05  5099.8 2094.70  5108.5 2094.05  5135.5 2102.54  5293.1 2106.03
  5322.9 2104.86  5366.8 2107.42  5438.8 2106.69  5668.0 2111.25  5796.1 2117.03
  5825.7 2116.37  5855.3 2119.74  5990.0 2122.28  6034.0 2126.55  6260.9 2132.51
#Mann=7,-1,0
  4324.9   0.035       0  4436.1    0.07       0  4662.8   0.035       0
  4879.9    0.07       0  5017.5    0.07       0  5026.9    0.07       0
  5293.1   0.045       0
Bank Sta=5017.5,5026.9
Exp/Cntr=0.3,0.1

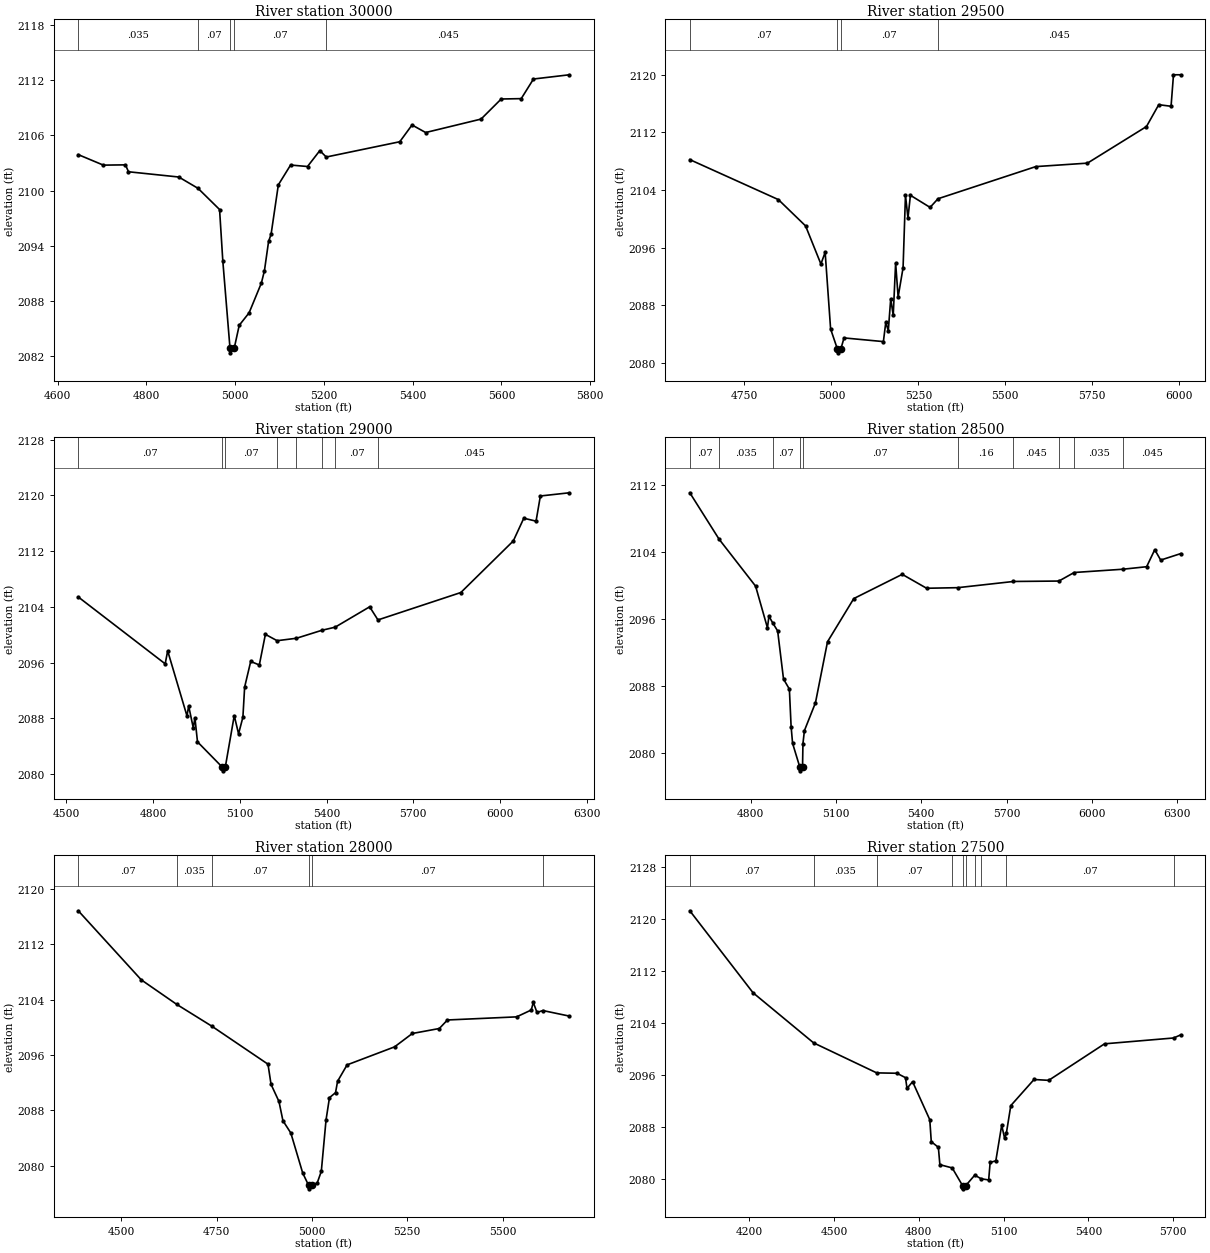
Type RM Length L Ch R = 1,30000,500,500,500
BEGIN DESCRIPTION:
Cottonwood Trib100 59.0
END DESCRIPTION:
XS GIS Cut Line= 3
      1348105.02      6933888.02      1347847.35      6933646.15
      1347491.33      6932982.75
#Sta/Elev= 30
  4646.6 2103.90  4703.1 2102.76  4752.9 2102.79  4759.7 2102.04  4873.0 2101.47
  4916.4 2100.24  4964.9 2097.94  4972.2 2092.36  4988.4 2082.88  4988.9 2082.38
  4997.9 2082.88  5009.2 2085.37  5031.5 2086.73  5059.1 2089.96  5066.0 2091.30
  5075.3 2094.47  5081.0 2095.26  5097.3 2100.62  5124.9 2102.77  5163.0 2102.61
  5190.8 2104.34  5205.2 2103.64  5370.9 2105.30  5398.5 2107.12  5429.2 2106.30
  5554.0 2107.76  5599.4 2109.94  5644.5 2109.98  5672.1 2112.11  5752.9 2112.57
#Mann=5,-1,0
  4646.6   0.035       0  4916.4    0.07       0  4988.4    0.07       0
  4997.9    0.07       0  5205.2   0.045       0
Bank Sta=4988.4,4997.9
Exp/Cntr=0.3,0.1

Type RM Length L Ch R = 1,29500,500,500,500
BEGIN DESCRIPTION:
Cottonwood Trib100 58.0
END DESCRIPTION:
XS GIS Cut Line= 3
      1348304.99      6933987.96      1348225.90      6933588.42
      1347505.02      6932888.02
#Sta/Elev= 30
  4592.7 2108.23  4847.5 2102.68  4925.7 2099.03  4969.8 2093.74  4982.0 2095.37
  4997.7 2084.73  5017.4 2081.92  5017.9 2081.42  5026.9 2081.92  5036.3 2083.49
  5149.5 2082.98  5156.4 2085.65  5163.6 2084.49  5170.6 2088.91  5177.8 2086.62
  5184.7 2093.89  5191.9 2089.18  5206.1 2093.22  5213.0 2103.29  5220.2 2100.13
  5227.2 2103.28  5283.8 2101.60  5306.6 2102.80  5587.8 2107.26  5736.4 2107.74
  5906.2 2112.82  5941.5 2115.85  5976.9 2115.63  5983.9 2120.00  6005.1 2120.00
#Mann=4,-1,0
  4592.7    0.07       0  5017.4    0.07       0  5026.9    0.07       0
  5306.6   0.045       0
Bank Sta=5017.4,5026.9
Exp/Cntr=0.3,0.1

Type RM Length L Ch R = 1,29000,500,500,500
BEGIN DESCRIPTION:
Cottonwood Trib100 57.0
END DESCRIPTION:
XS GIS Cut Line= 3
      1348455.02      6933837.96      1348678.33      6933437.75
      1347655.00      6932738.00
#Sta/Elev= 30
  4541.7 2105.42  4842.2 2095.83  4850.8 2097.69  4917.6 2088.35  4923.3 2089.79
  4939.3 2086.66  4945.0 2088.08  4953.9 2084.64  5040.3 2080.98  5040.8 2080.48
  5049.9 2080.98  5081.0 2088.40  5095.9 2085.79  5110.9 2088.17  5116.9 2092.49
  5137.9 2096.17  5167.7 2095.67  5188.7 2100.06  5229.2 2099.15  5296.2 2099.50
  5383.8 2100.64  5429.9 2101.09  5549.2 2104.01  5577.9 2102.13  5864.5 2106.06
  6045.9 2113.46  6082.2 2116.72  6124.6 2116.30  6139.5 2119.91  6239.7 2120.37
#Mann=8,-1,0
  4541.7    0.07       0  5040.3    0.07       0  5049.9    0.07       0
  5229.2   0.045       0  5296.2    0.07       0  5383.8   0.045       0
  5429.9    0.07       0  5577.9   0.045       0
Bank Sta=5040.3,5049.9
Exp/Cntr=0.3,0.1

Type RM Length L Ch R = 1,28500,500,500,500
BEGIN DESCRIPTION:
Cottonwood Trib100 56.0
END DESCRIPTION:
XS GIS Cut Line= 3
      1349204.99      6933837.97      1349106.61      6933436.44
      1348104.97      6932587.97
#Sta/Elev= 30
  4586.6 2111.06  4689.6 2105.52  4817.9 2099.92  4859.5 2094.95  4864.7 2096.34
  4877.8 2095.55  4895.4 2094.58  4916.0 2088.84  4936.6 2087.64  4942.7 2083.17
  4947.9 2081.17  4972.8 2078.39  4973.3 2077.89  4982.9 2078.39  4984.3 2081.14
  4989.5 2082.69  5028.3 2086.01  5070.7 2093.29  5163.0 2098.44  5333.3 2101.33
  5419.0 2099.67  5528.5 2099.74  5724.4 2100.48  5884.0 2100.53  5937.7 2101.55
  6108.7 2101.94  6192.4 2102.24  6220.9 2104.27  6241.8 2103.03  6312.7 2103.81
#Mann=10,-1,0
  4586.6    0.07       0  4689.6   0.035       0  4877.8    0.07       0
  4972.8    0.07       0  4982.9    0.07       0  5528.5    0.16       0
  5724.4   0.045       0  5884.0    0.07       0  5937.7   0.035       0
  6108.7   0.045       0
Bank Sta=4972.8,4982.9
Exp/Cntr=0.3,0.1

Type RM Length L Ch R = 1,28000,500,500,500
BEGIN DESCRIPTION:
Cottonwood Trib100 55.0
END DESCRIPTION:
XS GIS Cut Line= 3
      1349644.01      6933704.79      1349477.97      6933114.61
      1348845.42      6932878.42
#Sta/Elev= 30
  4386.9 2116.81  4552.2 2106.84  4645.5 2103.29  4737.1 2100.16  4884.6 2094.67
  4892.6 2091.76  4913.4 2089.29  4923.8 2086.51  4944.5 2084.74  4975.7 2078.96
  4991.2 2077.18  4991.7 2076.68  5001.3 2077.18  5013.8 2077.54  5024.5 2079.21
  5036.9 2086.63  5045.9 2089.84  5061.8 2090.56  5067.2 2092.21  5092.1 2094.57
  5216.7 2097.17  5263.3 2099.10  5334.1 2099.82  5355.4 2101.05  5536.9 2101.50
  5575.3 2102.49  5580.6 2103.59  5590.3 2102.14  5605.9 2102.41  5675.2 2101.61
#Mann=6,-1,0
  4386.9    0.07       0  4645.5   0.035       0  4737.1    0.07       0
  4991.2    0.07       0  5001.3    0.07       0  5605.9    0.16       0
Bank Sta=4991.2,5001.3
Exp/Cntr=0.3,0.1

Type RM Length L Ch R = 1,27500,500,500,500
BEGIN DESCRIPTION:
Cottonwood Trib100 54.0
END DESCRIPTION:
XS GIS Cut Line= 3
      1349954.99      6933637.96      1349604.61      6932690.04
      1348904.98      6932888.01
#Sta/Elev= 30
  3989.4 2121.28  4213.2 2108.66  4427.4 2100.95  4650.7 2096.33  4722.3 2096.27
  4752.7 2095.59  4758.0 2093.94  4777.8 2094.97  4838.6 2089.12  4843.9 2085.74
  4869.0 2084.87  4874.3 2082.20  4918.0 2081.70  4954.6 2078.98  4955.1 2078.48
  4965.9 2078.98  4997.8 2080.59  5020.2 2080.03  5047.0 2079.85  5052.2 2082.55
  5072.3 2082.79  5093.1 2088.28  5103.5 2086.24  5110.0 2087.15  5125.3 2091.29
  5207.5 2095.31  5259.4 2095.18  5456.9 2100.80  5701.4 2101.70  5727.1 2102.19
#Mann=10,-1,0
  3989.4    0.07       0  4427.4   0.035       0  4650.7    0.07       0
  4918.0    0.16       0  4954.6    0.07       0  4965.9    0.16       0
  4997.8    0.07       0  5020.2    0.16       0  5110.0    0.07       0
  5701.4    0.16       0
Bank Sta=4954.6,4965.9
Exp/Cntr=0.3,0.1