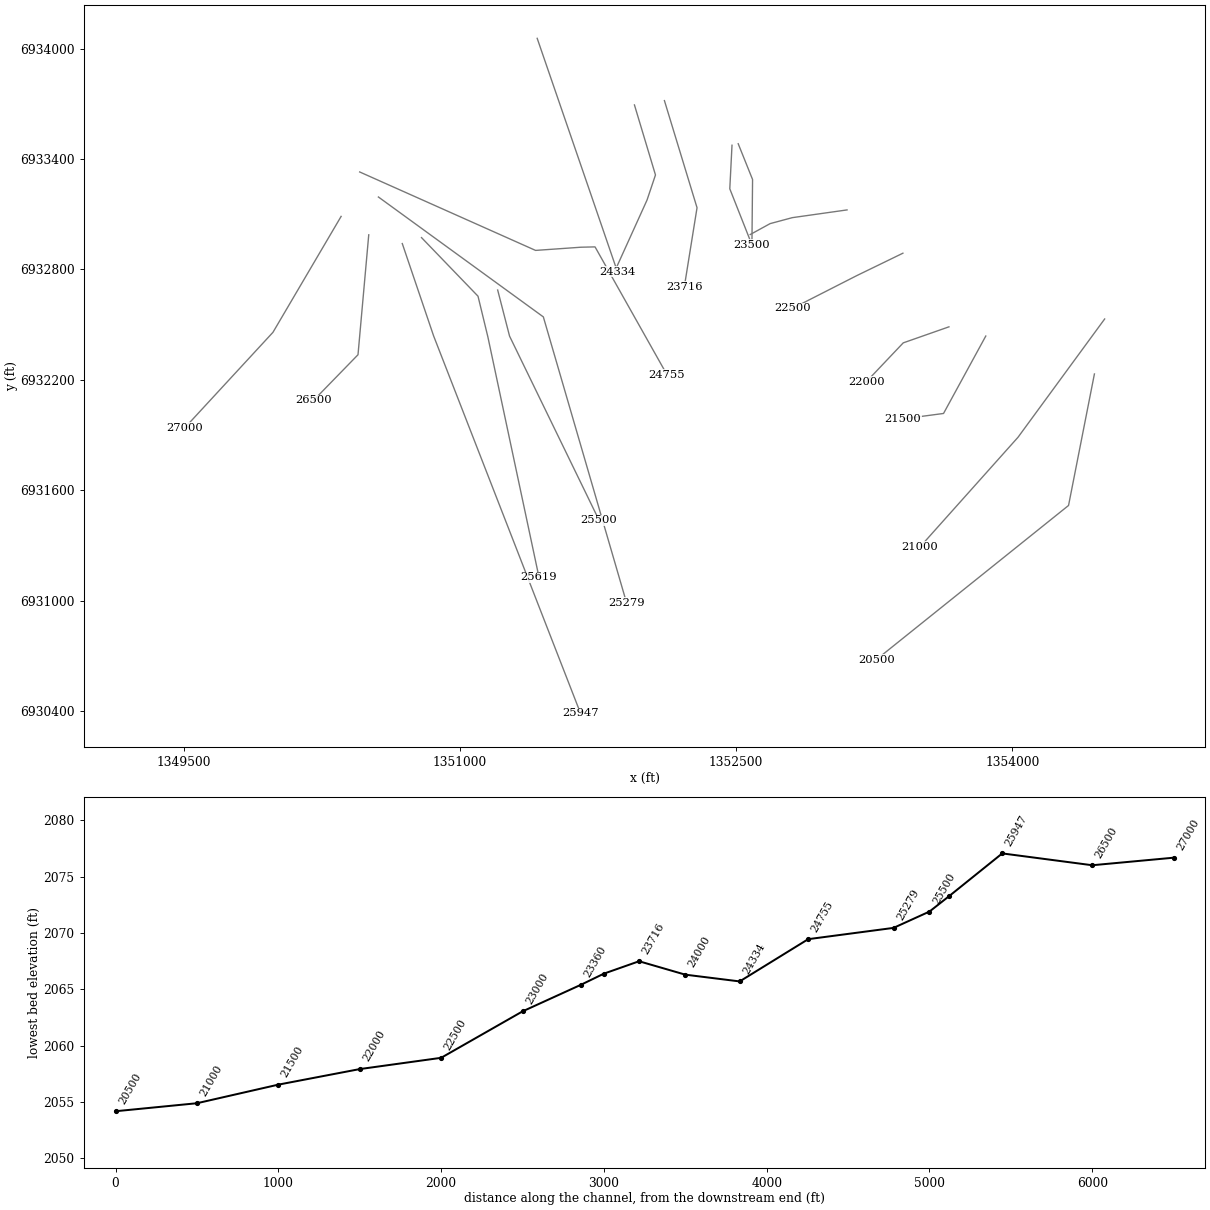
HEC-RAS study Cottonwood Trib100.prj: Cottonwood Trib100 Base Level Engineering

--- Cottonwood Trib100.g01 (geometry) --- (continued)

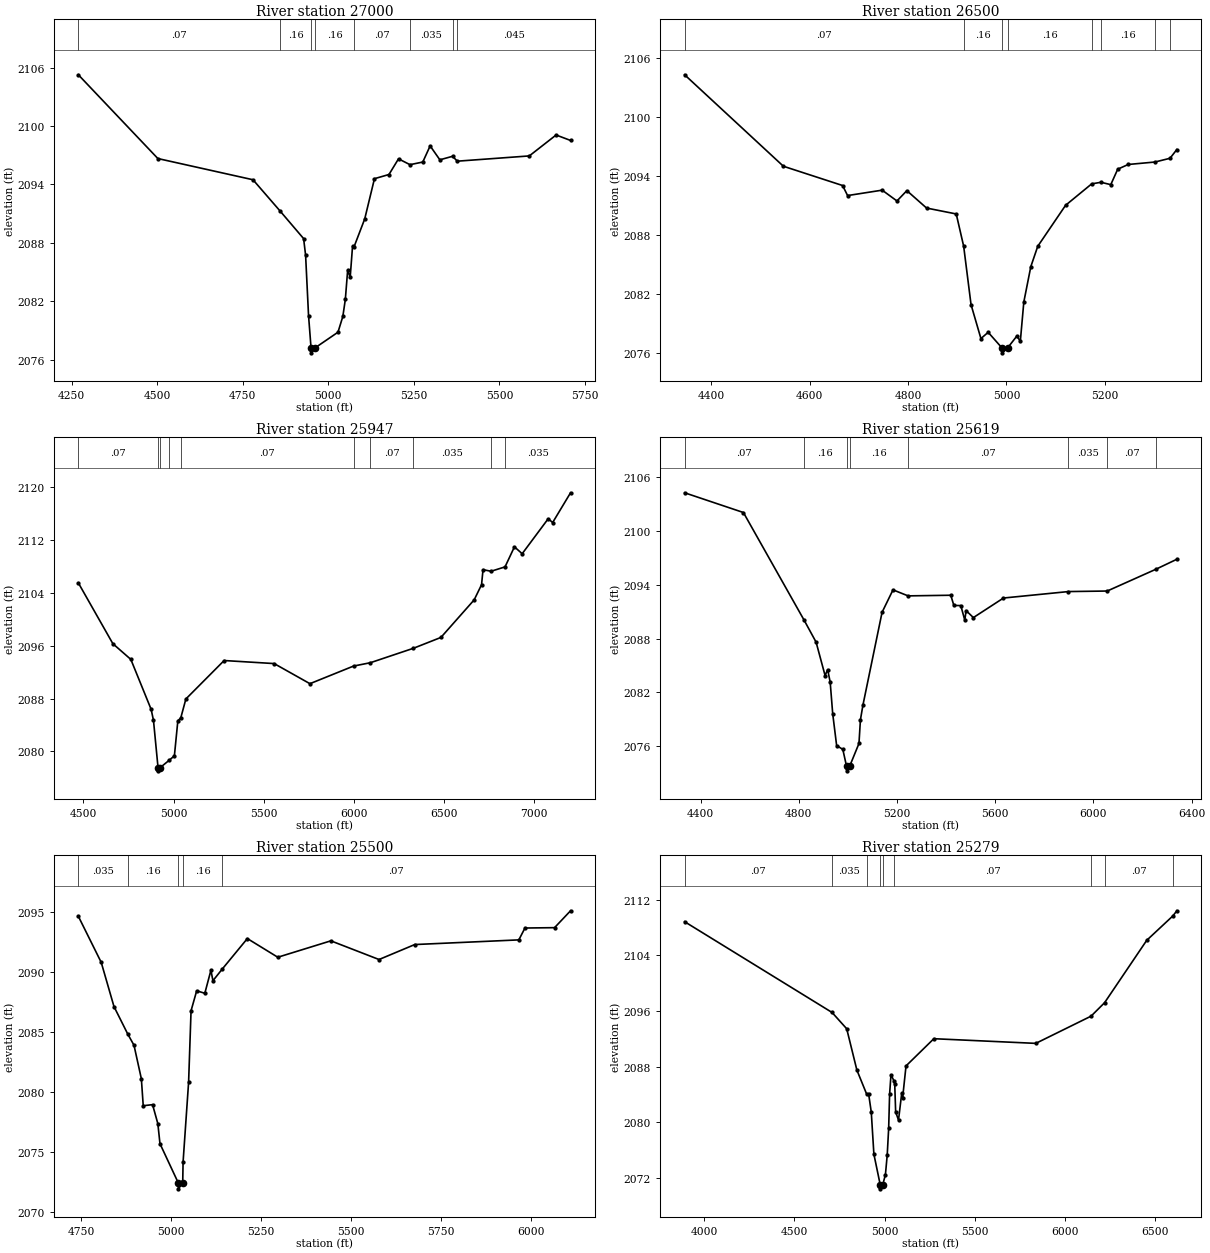
Type RM Length L Ch R = 1,27000,500,500,500
BEGIN DESCRIPTION:
Cottonwood Trib100 53.0
END DESCRIPTION:
XS GIS Cut Line= 3
      1350355.02      6933088.03      1349984.96      6932458.20
      1349505.00      6931938.00
#Sta/Elev= 30
  4269.5 2105.27  4501.9 2096.66  4779.9 2094.48  4858.7 2091.28  4927.8 2088.43
  4933.6 2086.72  4942.2 2080.52  4949.5 2077.19  4950.0 2076.69  4960.8 2077.19
  5028.2 2078.81  5042.4 2080.43  5049.7 2082.18  5056.5 2085.18  5063.9 2084.46
  5070.7 2087.62  5075.2 2087.59  5106.4 2090.46  5134.8 2094.59  5177.2 2095.02
  5205.1 2096.63  5238.6 2096.03  5276.0 2096.30  5297.5 2097.96  5325.9 2096.53
  5362.9 2096.89  5377.0 2096.39  5587.3 2096.93  5665.6 2099.08  5707.8 2098.52
#Mann=8,-1,0
  4269.5    0.07       0  4858.7    0.16       0  4949.5    0.07       0
  4960.8    0.16       0  5075.2    0.07       0  5238.6   0.035       0
  5362.9    0.07       0  5377.0   0.045       0
Bank Sta=4949.5,4960.8
Exp/Cntr=0.3,0.1

Type RM Length L Ch R = 1,26500,553,553,553
BEGIN DESCRIPTION:
Cottonwood Trib100 52.0
END DESCRIPTION:
XS GIS Cut Line= 3
      1350505.00      6932987.96      1350446.67      6932336.37
      1350205.03      6932088.03
#Sta/Elev= 30
  4345.8 2104.29  4546.6 2094.99  4667.0 2093.03  4677.1 2092.01  4747.4 2092.56
  4777.5 2091.46  4797.6 2092.51  4837.7 2090.74  4898.0 2090.14  4913.1 2086.86
  4928.1 2080.92  4948.2 2077.47  4962.9 2078.11  4991.0 2076.52  4991.5 2076.02
  5002.4 2076.52  5021.3 2077.73  5028.3 2077.19  5035.4 2081.19  5049.6 2084.78
  5063.7 2086.85  5120.3 2091.02  5173.4 2093.20  5192.3 2093.36  5212.2 2093.12
  5226.3 2094.69  5247.6 2095.17  5302.0 2095.42  5332.6 2095.80  5346.5 2096.69
#Mann=8,-1,0
  4345.8    0.07       0  4913.1    0.16       0  4991.0    0.07       0
  5002.4    0.16       0  5173.4    0.07       0  5192.3    0.16       0
  5302.0    0.07       0  5332.6    0.16       0
Bank Sta=4991,5002.4
Exp/Cntr=0.3,0.1

Type RM Length L Ch R = 1,25947,328,328,328
BEGIN DESCRIPTION:
Cottonwood Trib100 51.0
END DESCRIPTION:
XS GIS Cut Line= 3
      1350687.06      6932940.38      1350857.21      6932438.59
      1351655.01      6930387.97
#Sta/Elev= 30
  4472.0 2105.47  4663.6 2096.28  4763.2 2093.91  4875.8 2086.36  4888.8 2084.70
  4914.0 2077.57  4914.5 2077.07  4926.4 2077.57  4974.7 2078.64  5004.8 2079.34
  5023.9 2084.62  5040.3 2085.08  5068.5 2087.93  5280.7 2093.74  5558.1 2093.28
  5756.6 2090.24  5998.3 2092.90  6092.0 2093.41  6330.5 2095.59  6483.2 2097.23
  6667.7 2102.91  6708.6 2105.20  6716.7 2107.47  6761.3 2107.23  6838.8 2107.89
  6891.0 2110.92  6933.9 2109.88  7078.4 2115.17  7102.9 2114.59  7202.2 2119.09
#Mann=10,-1,0
  4472.0    0.07       0  4914.0    0.07       0  4926.4    0.07       0
  4974.7    0.16       0  5040.3    0.07       0  5998.3   0.035       0
  6092.0    0.07       0  6330.5   0.035       0  6761.3    0.07       0
  6838.8   0.035       0
Bank Sta=4914,4926.4
Exp/Cntr=0.3,0.1

Type RM Length L Ch R = 1,25619,119,119,119
BEGIN DESCRIPTION:
Cottonwood Trib100 50.5
END DESCRIPTION:
XS GIS Cut Line= 4
      1350791.42      6932972.84      1351098.24      6932654.39
      1351151.70      6932433.57      1351429.42      6931127.37
#Sta/Elev= 30
  4334.7 2104.25  4574.1 2102.05  4821.2 2090.06  4870.2 2087.60  4906.8 2083.88
  4917.2 2084.54  4927.5 2083.16  4937.8 2079.63  4953.8 2076.08  4979.0 2075.65
  4994.3 2073.76  4994.8 2073.26  5006.7 2073.76  5044.8 2076.31  5050.7 2078.94
  5060.9 2080.58  5138.9 2090.93  5183.4 2093.43  5244.9 2092.76  5418.7 2092.83
  5431.4 2091.69  5459.6 2091.68  5475.9 2090.04  5481.0 2091.12  5510.8 2090.34
  5633.4 2092.52  5898.0 2093.24  6055.9 2093.30  6253.6 2095.72  6339.5 2096.84
#Mann=8,-1,0
  4334.7    0.07       0  4821.2    0.16       0  4994.3    0.07       0
  5006.7    0.16       0  5244.9    0.07       0  5898.0   0.035       0
  6055.9    0.07       0  6253.6   0.035       0
Bank Sta=4994.3,5006.7
Exp/Cntr=0.3,0.1

Type RM Length L Ch R = 1,25500,221,221,221
BEGIN DESCRIPTION:
Cottonwood Trib100 50.0
END DESCRIPTION:
XS GIS Cut Line= 3
      1351204.99      6932688.03      1351269.51      6932437.51
      1351755.01      6931437.98
#Sta/Elev= 30
  4741.3 2094.67  4805.0 2090.82  4840.5 2087.13  4879.1 2084.82  4896.2 2083.90
  4916.7 2081.10  4921.9 2078.85  4947.9 2078.94  4962.6 2077.35  4968.5 2075.68
  5019.4 2072.41  5019.9 2071.91  5031.8 2072.41  5032.8 2074.14  5048.2 2080.82
  5055.0 2086.78  5070.7 2088.45  5093.3 2088.24  5110.3 2090.16  5115.9 2089.29
  5142.0 2090.27  5211.7 2092.81  5296.4 2091.25  5444.1 2092.62  5578.2 2091.06
  5677.6 2092.31  5967.3 2092.70  5984.3 2093.69  6066.7 2093.72  6111.2 2095.13
#Mann=5,-1,0
  4741.3   0.035       0  4879.1    0.16       0  5019.4    0.07       0
  5031.8    0.16       0  5142.0    0.07       0
Bank Sta=5019.4,5031.8
Exp/Cntr=0.3,0.1

Type RM Length L Ch R = 1,25279,524,524,524
BEGIN DESCRIPTION:
Cottonwood Trib100 49.0
END DESCRIPTION:
XS GIS Cut Line= 3
      1350557.49      6933193.40      1351452.94      6932541.95
      1351904.99      6930988.02
#Sta/Elev= 30
  3892.8 2108.84  4709.2 2095.80  4790.3 2093.46  4846.7 2087.52  4900.3 2084.10
  4911.7 2084.10  4926.3 2081.50  4940.9 2075.43  4976.6 2070.96  4977.1 2070.46
  4989.0 2070.96  5004.8 2072.51  5014.7 2075.33  5022.7 2079.17  5027.9 2084.07
  5035.5 2086.85  5053.4 2085.91  5056.2 2085.58  5061.4 2081.50  5077.2 2080.34
  5094.9 2084.18  5100.1 2083.56  5118.8 2088.12  5272.9 2092.03  5837.4 2091.36
  6143.5 2095.27  6218.3 2097.20  6451.9 2106.17  6596.9 2109.68  6618.5 2110.41
#Mann=9,-1,0
  3892.8    0.07       0  4709.2   0.035       0  4900.3    0.16       0
  4976.6    0.07       0  4989.0    0.16       0  5053.4    0.07       0
  6143.5   0.035       0  6218.3    0.07       0  6596.9   0.035       0
Bank Sta=4976.6,4989
Exp/Cntr=0.3,0.1

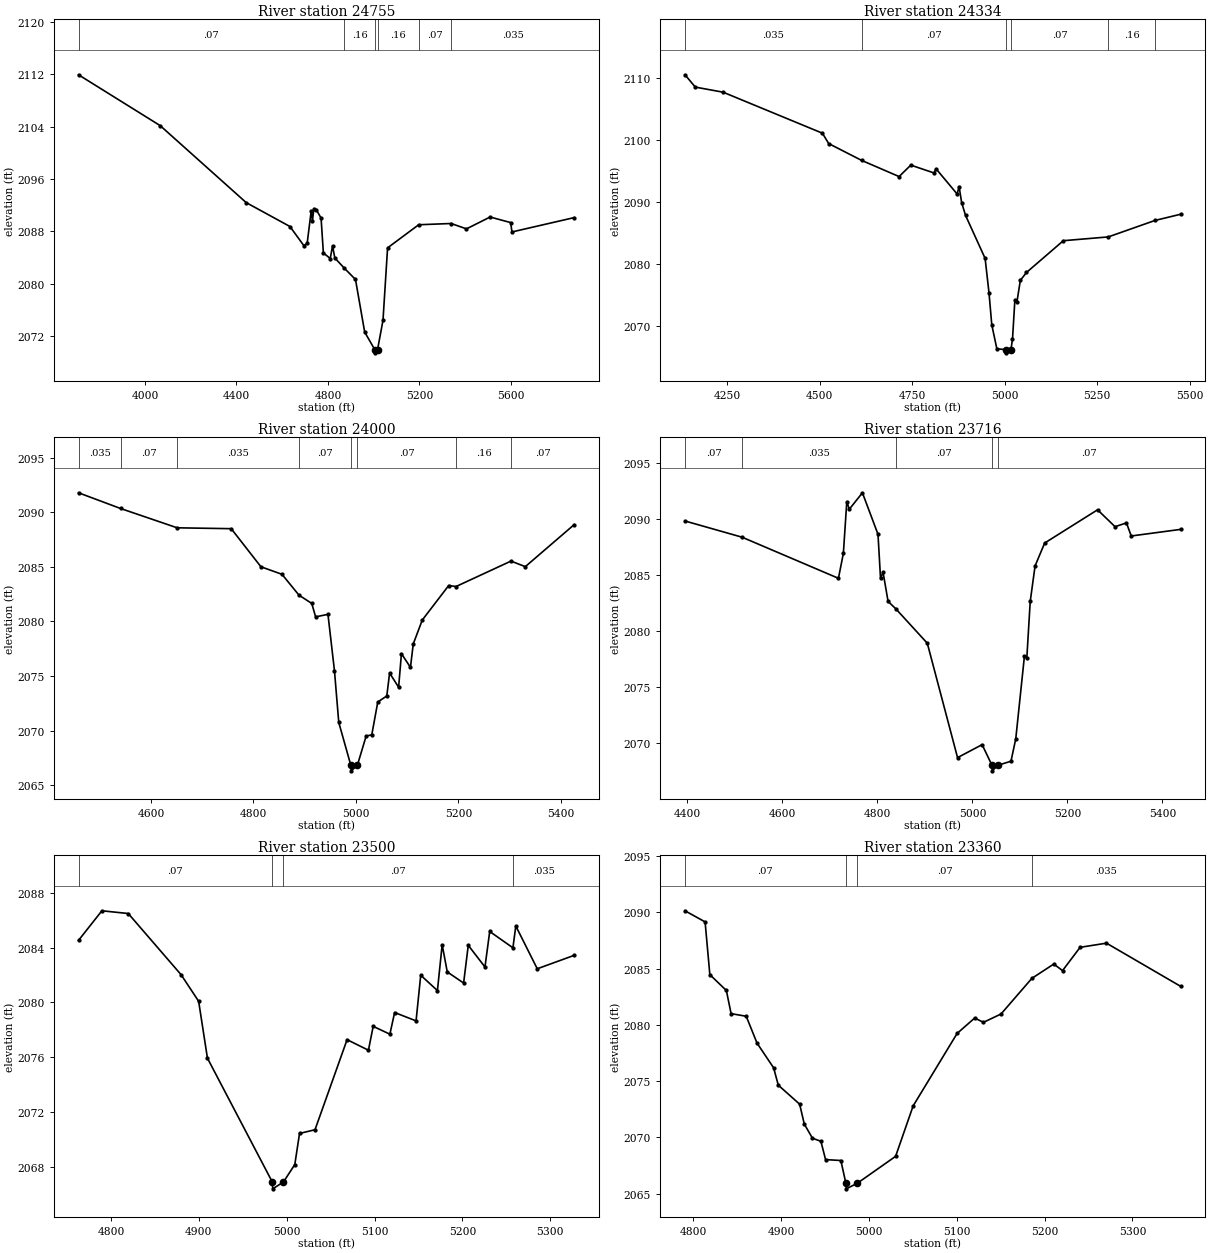
Type RM Length L Ch R = 1,24755,421,421,421
BEGIN DESCRIPTION:
Cottonwood Trib100 48.5
END DESCRIPTION:
XS GIS Cut Line= 5
      1350455.85      6933329.42      1351410.69      6932903.21
      1351657.22      6932920.57      1351733.61      6932922.31
      1352124.25      6932227.83
#Sta/Elev= 30
  3709.9 2111.92  4067.0 2104.15  4442.7 2092.40  4633.9 2088.75  4694.6 2085.83
  4709.0 2086.16  4726.7 2091.11  4732.2 2089.64  4738.4 2091.47  4749.3 2091.29
  4769.9 2090.04  4779.9 2084.72  4810.0 2083.86  4820.0 2085.80  4830.0 2083.94
  4871.5 2082.39  4920.3 2080.66  4960.4 2072.64  5004.3 2069.96  5004.8 2069.46
  5016.7 2069.96  5040.5 2074.43  5060.5 2085.49  5196.5 2089.02  5338.3 2089.21
  5405.3 2088.39  5508.6 2090.20  5598.3 2089.35  5604.1 2087.92  5875.9 2090.11
#Mann=6,-1,0
  3709.9    0.07       0  4871.5    0.16       0  5004.3    0.07       0
  5016.7    0.16       0  5196.5    0.07       0  5338.3   0.035       0
Bank Sta=5004.3,5016.7
Exp/Cntr=0.3,0.1

Type RM Length L Ch R = 1,24334,334,334,334
BEGIN DESCRIPTION:
Cottonwood Trib100 48.0
END DESCRIPTION:
XS GIS Cut Line= 3
      1351419.49      6934055.38      1351700.74      6933237.65
      1351854.99      6932788.02
#Sta/Elev= 30
  4135.8 2110.59  4163.8 2108.60  4238.8 2107.78  4507.4 2101.16  4524.3 2099.49
  4613.1 2096.78  4714.7 2094.16  4746.4 2096.01  4809.2 2094.74  4814.4 2095.43
  4871.6 2091.35  4876.9 2092.54  4883.9 2089.94  4894.4 2087.89  4947.3 2080.95
  4957.9 2075.33  4965.3 2070.23  4979.0 2066.37  5004.4 2066.21  5004.9 2065.71
  5017.0 2066.21  5021.3 2067.89  5027.8 2074.27  5033.1 2073.85  5042.5 2077.40
  5059.1 2078.68  5158.8 2083.81  5280.2 2084.42  5406.7 2087.08  5475.9 2088.08
#Mann=6,-1,0
  4135.8   0.035       0  4613.1    0.07       0  5004.4    0.07       0
  5017.0    0.07       0  5280.2    0.16       0  5406.7    0.07       0
Bank Sta=5004.4,5017
Exp/Cntr=0.3,0.1

Type RM Length L Ch R = 1,24000,284,284,284
BEGIN DESCRIPTION:
Cottonwood Trib100 47.0
END DESCRIPTION:
XS GIS Cut Line= 4
      1351947.48      6933693.65      1352061.68      6933313.11
      1352015.64      6933176.26      1351839.72      6932788.06
#Sta/Elev= 30
  4458.3 2091.79  4540.4 2090.35  4651.0 2088.58  4756.5 2088.50  4814.5 2085.01
  4855.6 2084.32  4888.8 2082.41  4913.8 2081.65  4921.3 2080.42  4945.4 2080.65
  4958.1 2075.49  4966.5 2070.75  4990.1 2066.81  4990.6 2066.31  5002.8 2066.81
  5020.0 2069.50  5031.0 2069.61  5042.7 2072.62  5060.3 2073.17  5065.8 2075.27
  5083.4 2073.97  5088.9 2077.05  5106.5 2075.79  5112.0 2077.94  5129.6 2080.13
  5181.2 2083.29  5195.5 2083.20  5302.8 2085.53  5330.8 2085.02  5426.2 2088.87
#Mann=8,-1,0
  4458.3   0.035       0  4540.4    0.07       0  4651.0   0.035       0
  4888.8    0.07       0  4990.1    0.07       0  5002.8    0.07       0
  5195.5    0.16       0  5302.8    0.07       0
Bank Sta=4990.1,5002.8
Exp/Cntr=0.3,0.1

Type RM Length L Ch R = 1,23716,216,216,216
BEGIN DESCRIPTION:
Cottonwood Trib100 46.5
END DESCRIPTION:
XS GIS Cut Line= 3
      1352110.25      6933717.08      1352287.33      6933135.04
      1352218.32      6932705.33
#Sta/Elev= 30
  4394.8 2089.82  4515.1 2088.37  4717.9 2084.70  4728.3 2086.93  4735.5 2091.55
  4740.8 2090.87  4768.4 2092.34  4801.2 2088.63  4806.5 2084.72  4811.9 2085.23
  4822.4 2082.64  4838.6 2081.98  4905.0 2078.90  4968.7 2068.68  5020.4 2069.84
  5041.2 2068.00  5041.7 2067.50  5053.9 2068.00  5081.2 2068.36  5091.3 2070.37
  5109.5 2077.74  5114.6 2077.61  5121.7 2082.63  5131.9 2085.80  5152.1 2087.85
  5263.5 2090.82  5300.3 2089.31  5324.3 2089.65  5334.4 2088.48  5438.4 2089.07
#Mann=5,-1,0
  4394.8    0.07       0  4515.1   0.035       0  4838.6    0.07       0
  5041.2    0.07       0  5053.9    0.07       0
Bank Sta=5041.2,5053.9
Exp/Cntr=0.3,0.1

Type RM Length L Ch R = 1,23500,140,140,140
BEGIN DESCRIPTION:
Cottonwood Trib100 46.0
END DESCRIPTION:
XS GIS Cut Line= 3
      1352477.15      6933474.52      1352465.20      6933237.92
      1352585.31      6932933.67
#Sta/Elev= 30
  4763.1 2084.52  4789.7 2086.68  4819.7 2086.48  4879.8 2082.02  4899.8 2080.08
  4909.8 2075.93  4983.6 2066.90  4984.1 2066.40  4996.3 2066.90  5009.2 2068.17
  5014.6 2070.44  5032.2 2070.71  5068.7 2077.28  5093.0 2076.51  5098.4 2078.25
  5117.4 2077.68  5122.8 2079.26  5147.2 2078.65  5152.5 2081.98  5171.5 2080.86
  5176.9 2084.20  5182.7 2082.22  5201.3 2081.41  5206.6 2084.16  5225.6 2082.58
  5231.0 2085.17  5257.4 2083.98  5260.7 2085.57  5285.1 2082.45  5327.1 2083.43
#Mann=4,-1,0
  4763.1    0.07       0  4983.6    0.07       0  4996.3    0.07       0
  5257.4   0.035       0
Bank Sta=4983.6,4996.3
Exp/Cntr=0.3,0.1

Type RM Length L Ch R = 1,23360,360,360,360
BEGIN DESCRIPTION:
Cottonwood Trib100 45.5
END DESCRIPTION:
XS GIS Cut Line= 3
      1352510.87      6933482.68      1352588.82      6933288.40
      1352585.33      6932933.65
#Sta/Elev= 30
  4790.7 2090.15  4813.6 2089.16  4819.0 2084.47  4837.8 2083.06  4843.2 2081.00
  4860.4 2080.77  4872.7 2078.38  4891.6 2076.18  4896.9 2074.64  4921.2 2072.95
  4926.5 2071.18  4935.8 2069.92  4945.4 2069.65  4950.7 2068.02  4968.1 2067.94
  4973.8 2065.92  4974.3 2065.42  4986.9 2065.92  5030.4 2068.31  5050.4 2072.80
  5100.4 2079.24  5120.4 2080.61  5130.4 2080.23  5150.4 2080.97  5185.5 2084.14
  5210.4 2085.41  5220.4 2084.83  5240.4 2086.90  5270.4 2087.27  5354.8 2083.43
#Mann=4,-1,0
  4790.7    0.07       0  4973.8    0.07       0  4986.9    0.07       0
  5185.5   0.035       0
Bank Sta=4973.8,4986.9
Exp/Cntr=0.3,0.1

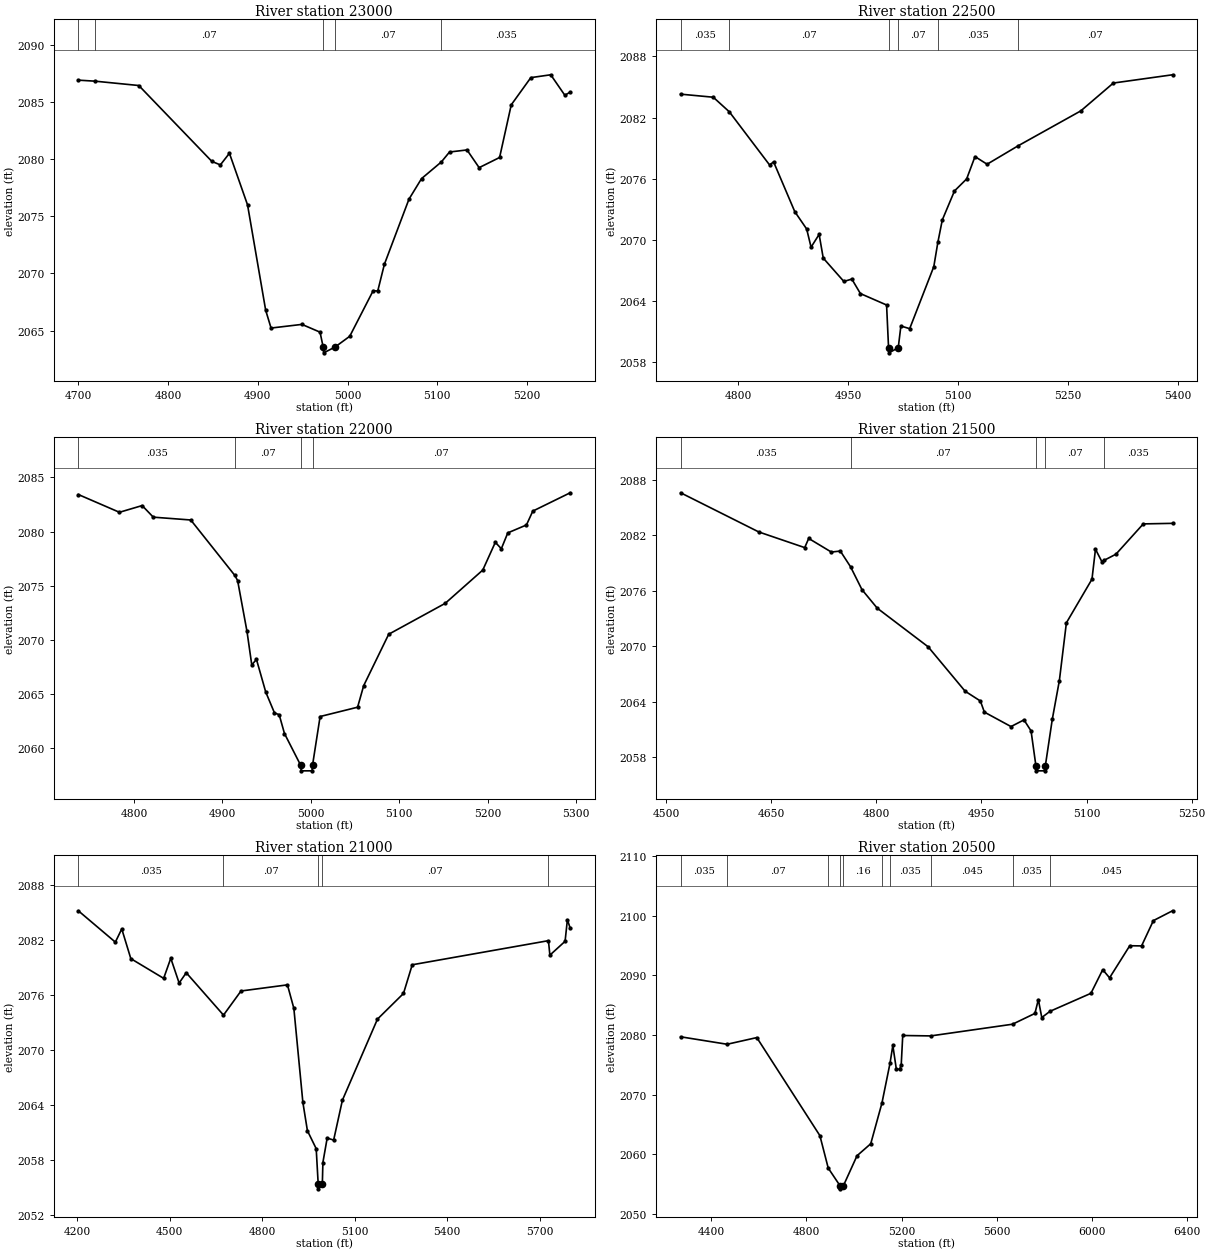
Type RM Length L Ch R = 1,23000,500,500,500
BEGIN DESCRIPTION:
Cottonwood Trib100 45.0
END DESCRIPTION:
XS GIS Cut Line= 4
      1353101.74      6933123.22      1352804.60      6933081.17
      1352684.20      6933048.78      1352575.98      6932989.44
#Sta/Elev= 30
  4699.9 2086.92  4718.6 2086.83  4767.3 2086.45  4848.7 2079.81  4858.2 2079.50
  4868.3 2080.52  4888.5 2076.00  4908.7 2066.78  4914.7 2065.22  4949.1 2065.54
  4969.3 2064.86  4972.8 2063.55  4973.3 2063.05  4985.9 2063.55  5002.4 2064.50
  5028.5 2068.49  5033.6 2068.46  5041.0 2070.80  5068.4 2076.50  5082.4 2078.30
  5104.5 2079.76  5113.6 2080.63  5133.1 2080.81  5146.6 2079.26  5169.4 2080.15
  5182.4 2084.76  5204.2 2087.14  5226.4 2087.39  5242.1 2085.60  5248.1 2085.87
#Mann=5,-1,0
  4699.9   0.035       0  4718.6    0.07       0  4972.8    0.07       0
  4985.9    0.07       0  5104.5   0.035       0
Bank Sta=4972.8,4985.9
Exp/Cntr=0.3,0.1

Type RM Length L Ch R = 1,22500,500,500,500
BEGIN DESCRIPTION:
Cottonwood Trib100 44.0
END DESCRIPTION:
XS GIS Cut Line= 3
      1353405.00      6932888.00      1353154.81      6932766.36
      1352804.96      6932587.98
#Sta/Elev= 30
  4721.8 2084.29  4766.3 2083.99  4788.2 2082.56  4843.1 2077.35  4848.6 2077.65
  4877.5 2072.77  4893.7 2071.07  4899.7 2069.29  4910.7 2070.54  4916.3 2068.22
  4944.4 2065.93  4955.3 2066.16  4967.0 2064.74  5002.7 2063.62  5005.4 2059.43
  5005.9 2058.93  5018.6 2059.43  5022.2 2061.56  5034.2 2061.30  5067.1 2067.38
  5072.6 2069.75  5078.7 2071.96  5095.3 2074.80  5111.9 2075.98  5123.3 2078.17
  5139.8 2077.42  5182.2 2079.23  5267.6 2082.65  5312.0 2085.38  5392.7 2086.19
#Mann=6,-1,0
  4721.8   0.035       0  4788.2    0.07       0  5005.4    0.07       0
  5018.6    0.07       0  5072.6   0.035       0  5182.2    0.07       0
Bank Sta=5005.4,5018.6
Exp/Cntr=0.3,0.1

Type RM Length L Ch R = 1,22000,500,500,500
BEGIN DESCRIPTION:
Cottonwood Trib100 43.0
END DESCRIPTION:
XS GIS Cut Line= 3
      1353655.03      6932488.01      1353406.86      6932400.93
      1353205.01      6932188.01
#Sta/Elev= 30
  4737.0 2083.42  4783.5 2081.78  4809.2 2082.40  4821.8 2081.33  4864.2 2081.07
  4914.1 2075.95  4917.2 2075.48  4927.8 2070.79  4933.2 2067.70  4938.5 2068.21
  4949.0 2065.20  4958.9 2063.27  4964.2 2063.11  4970.2 2061.37  4988.6 2058.43
  4989.1 2057.93  5001.4 2057.93  5001.9 2058.43  5010.5 2062.94  5052.9 2063.80
  5059.8 2065.79  5088.1 2070.53  5152.0 2073.38  5194.5 2076.45  5208.7 2079.01
  5215.5 2078.42  5222.8 2079.88  5243.9 2080.61  5251.1 2081.89  5293.4 2083.58
#Mann=4,-1,0
  4737.0   0.035       0  4914.1    0.07       0  4988.6    0.07       0
  5001.9    0.07       0
Bank Sta=4988.6,5001.9
Exp/Cntr=0.3,0.1

Type RM Length L Ch R = 1,21500,500,500,500
BEGIN DESCRIPTION:
Cottonwood Trib100 42.0
END DESCRIPTION:
XS GIS Cut Line= 3
      1353854.98      6932437.97      1353625.62      6932017.34
      1353404.97      6931988.00
#Sta/Elev= 30
  4520.9 2086.57  4632.4 2082.34  4697.9 2080.65  4703.6 2081.64  4735.9 2080.17
  4748.7 2080.28  4763.3 2078.58  4779.6 2076.11  4801.4 2074.11  4874.0 2069.94
  4926.7 2065.15  4948.5 2064.09  4954.2 2062.89  4992.2 2061.33  5010.7 2062.05
  5020.8 2060.86  5027.8 2057.05  5028.3 2056.55  5040.6 2056.55  5041.1 2057.05
  5051.1 2062.12  5061.2 2066.30  5071.2 2072.53  5107.7 2077.24  5112.7 2080.48
  5121.7 2079.15  5125.1 2079.28  5141.9 2079.94  5180.9 2083.21  5222.6 2083.27
#Mann=5,-1,0
  4520.9   0.035       0  4763.3    0.07       0  5027.8    0.07       0
  5041.1    0.07       0  5125.1   0.035       0
Bank Sta=5027.8,5041.1
Exp/Cntr=0.3,0.1

Type RM Length L Ch R = 1,21000,500,500,500
BEGIN DESCRIPTION:
Cottonwood Trib100 41.0
END DESCRIPTION:
XS GIS Cut Line= 3
      1354500.35      6932530.66      1354030.04      6931888.10
      1353497.70      6931291.99
#Sta/Elev= 30
  4203.7 2085.23  4323.8 2081.81  4344.6 2083.25  4374.0 2080.01  4480.5 2077.86
  4503.6 2080.05  4530.7 2077.35  4553.8 2078.47  4674.6 2073.85  4731.4 2076.48
  4882.0 2077.15  4902.8 2074.59  4932.1 2064.32  4946.8 2061.24  4975.3 2059.28
  4981.8 2055.40  4982.3 2054.90  4995.2 2055.40  4997.0 2057.77  5010.9 2060.44
  5031.9 2060.22  5060.3 2064.57  5174.0 2073.41  5258.4 2076.21  5286.8 2079.34
  5728.6 2081.97  5733.3 2080.39  5782.6 2081.90  5790.1 2084.26  5799.2 2083.33
#Mann=5,-1,0
  4203.7   0.035       0  4674.6    0.07       0  4981.8    0.07       0
  4995.2    0.07       0  5728.6   0.035       0
Bank Sta=4981.8,4995.2
Exp/Cntr=0.3,0.1

Type RM Length L Ch R = 1,20500,500,500,500
BEGIN DESCRIPTION:
Cottonwood Trib100 40.0
END DESCRIPTION:
XS GIS Cut Line= 3
      1354444.77      6932232.01      1354304.31      6931517.48
      1353260.75      6930679.94
#Sta/Elev= 30
  4271.8 2079.68  4467.1 2078.43  4591.8 2079.55  4856.8 2063.11  4891.8 2057.67
  4941.7 2054.69  4942.2 2054.19  4955.3 2054.69  5012.8 2059.74  5070.4 2061.75
  5117.5 2068.58  5151.3 2075.23  5163.2 2078.23  5177.6 2074.34  5191.5 2074.20
  5198.4 2074.95  5204.8 2079.90  5322.3 2079.83  5665.9 2081.79  5760.1 2083.60
  5774.5 2085.92  5788.9 2082.91  5823.3 2083.95  5995.3 2086.97  6044.9 2090.93
  6073.7 2089.57  6158.5 2094.95  6208.1 2094.92  6257.7 2099.16  6338.1 2100.81
#Mann=10,-1,0
  4271.8   0.035       0  4467.1    0.07       0  4891.8    0.16       0
  4941.7    0.07       0  4955.3    0.16       0  5117.5    0.07       0
  5151.3   0.035       0  5322.3   0.045       0  5665.9   0.035       0
  5823.3   0.045       0
Bank Sta=4941.7,4955.3
Exp/Cntr=0.3,0.1