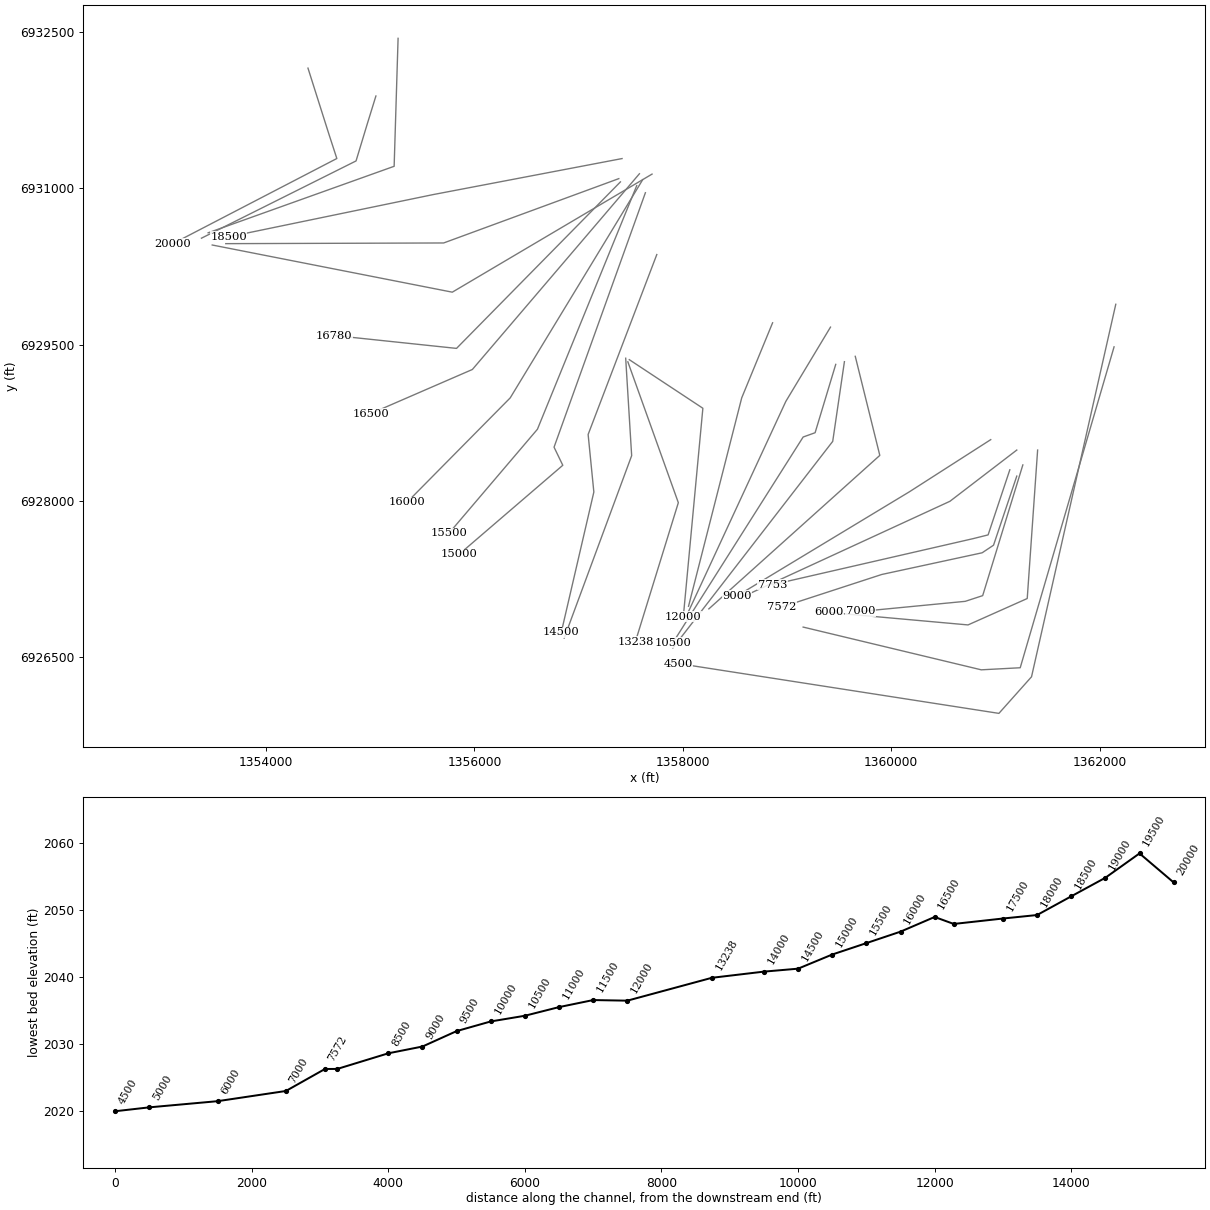
HEC-RAS study Cottonwood Trib100.prj: Cottonwood Trib100 Base Level Engineering

--- Cottonwood Trib100.g01 (geometry) --- (continued)

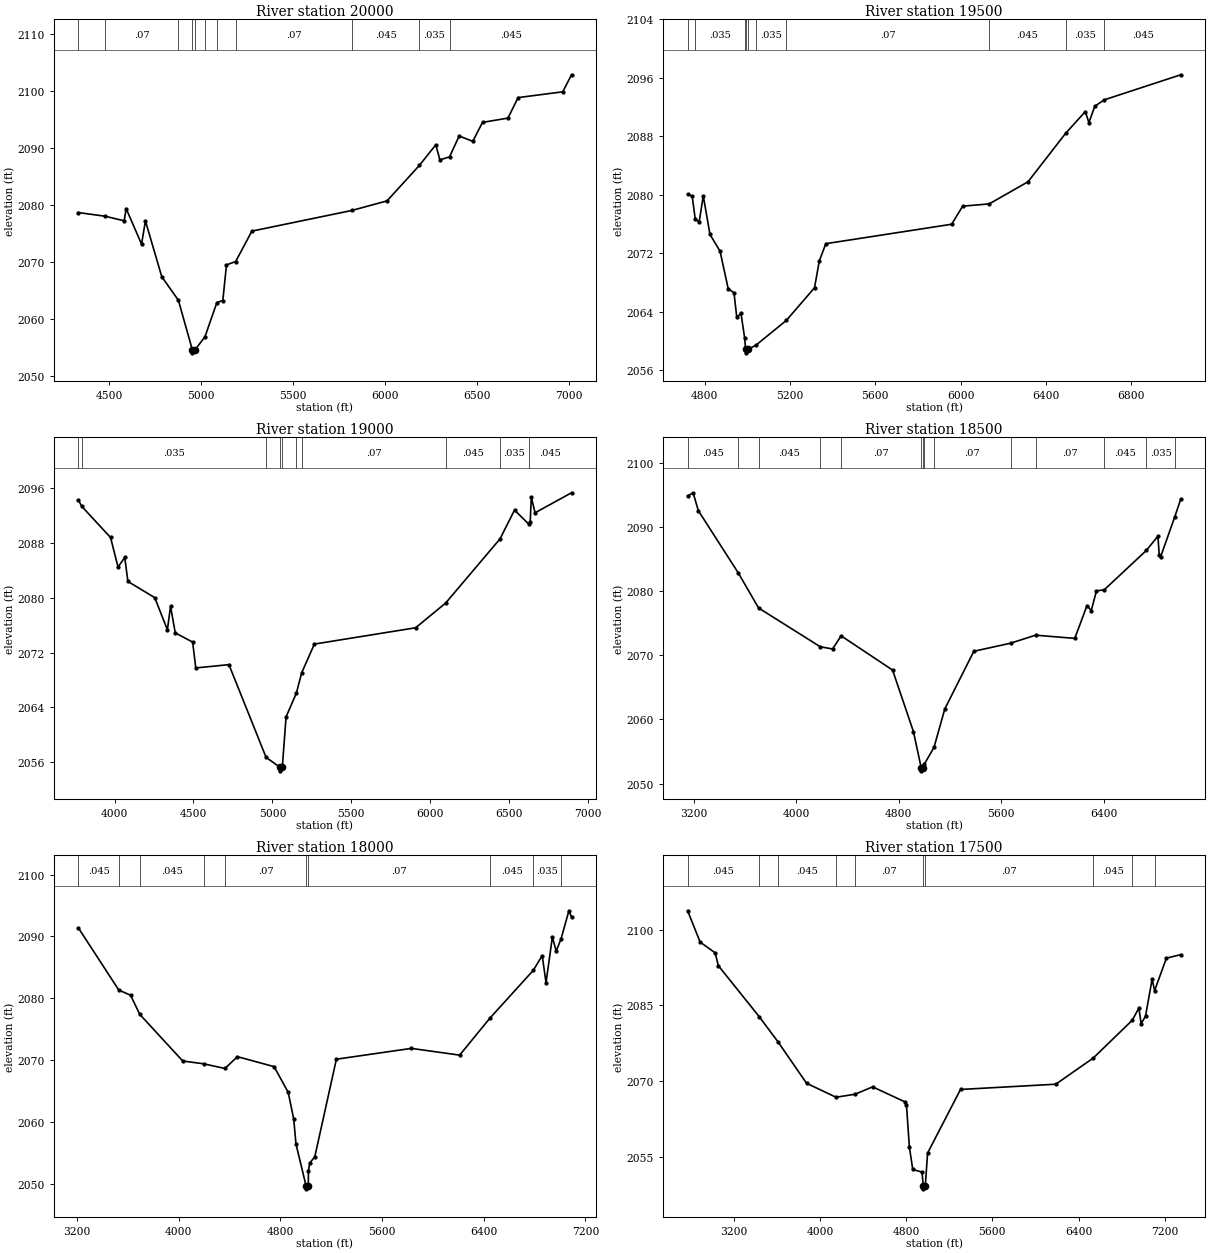
Type RM Length L Ch R = 1,20000,500,500,500
BEGIN DESCRIPTION:
Cottonwood Trib100 39.0
END DESCRIPTION:
XS GIS Cut Line= 4
      1354403.12      6932155.60      1354605.07      6931518.12
      1354680.02      6931287.58      1353108.31      6930470.98
#Sta/Elev= 30
  4331.3 2078.69  4477.3 2078.04  4580.5 2077.24  4591.1 2079.39  4674.9 2073.14
  4695.9 2077.23  4784.8 2067.42  4875.2 2063.29  4951.4 2054.55  4951.9 2054.05
  4965.0 2054.55  5019.6 2056.86  5084.7 2062.89  5117.0 2063.24  5136.8 2069.49
  5186.7 2070.09  5275.1 2075.43  5819.0 2079.06  6010.1 2080.74  6186.1 2086.97
  6275.5 2090.60  6297.6 2087.95  6350.0 2088.46  6402.5 2092.14  6476.4 2091.20
  6529.6 2094.53  6668.0 2095.28  6723.0 2098.88  6966.2 2099.90  7013.6 2102.89
#Mann=11,-1,0
  4331.3   0.035       0  4477.3    0.07       0  4875.2    0.16       0
  4951.4    0.07       0  4965.0    0.16       0  5019.6    0.07       0
  5084.7   0.035       0  5186.7    0.07       0  5819.0   0.045       0
  6186.1   0.035       0  6350.0   0.045       0
Bank Sta=4951.4,4965
Exp/Cntr=0.3,0.1

Type RM Length L Ch R = 1,19500,500,500,500
BEGIN DESCRIPTION:
Cottonwood Trib100 38.0
END DESCRIPTION:
XS GIS Cut Line= 4
      1355055.00      6931888.00      1354972.47      6931621.18
      1354864.38      6931264.35      1353380.83      6930522.57
#Sta/Elev= 30
  4720.7 2080.09  4742.2 2079.80  4756.6 2076.62  4774.9 2076.30  4794.0 2079.86
  4825.4 2074.57  4872.7 2072.27  4910.6 2067.17  4938.0 2066.58  4951.0 2063.23
  4970.6 2063.79  4987.9 2060.42  4992.2 2058.88  4992.7 2058.38  5005.9 2058.88
  5041.0 2059.43  5183.5 2062.82  5315.3 2067.28  5337.7 2070.95  5368.3 2073.31
  5958.2 2075.97  6009.4 2078.44  6134.0 2078.75  6315.9 2081.78  6492.2 2088.41
  6584.3 2091.38  6601.0 2089.87  6629.0 2092.12  6673.8 2092.99  7031.5 2096.41
#Mann=10,-1,0
  4720.7    0.07       0  4756.6   0.035       0  4987.9    0.16       0
  4992.2    0.07       0  5005.9    0.16       0  5041.0   0.035       0
  5183.5    0.07       0  6134.0   0.045       0  6492.2   0.035       0
  6673.8   0.045       0
Bank Sta=4992.2,5005.9
Exp/Cntr=0.3,0.1

Type RM Length L Ch R = 1,19000,500,500,500
BEGIN DESCRIPTION:
Cottonwood Trib100 37.0
END DESCRIPTION:
XS GIS Cut Line= 3
      1355267.81      6932441.69      1355229.96      6931212.87
      1353445.08      6930574.23
#Sta/Elev= 30
  3770.6 2094.25  3791.8 2093.33  3974.4 2088.79  4021.9 2084.47  4064.4 2085.88
  4084.4 2082.38  4254.5 2080.01  4334.6 2075.33  4354.6 2078.74  4384.6 2074.87
  4494.6 2073.53  4514.6 2069.76  4724.7 2070.24  4960.0 2056.72  5049.2 2055.25
  5049.7 2054.75  5062.9 2055.25  5086.8 2062.62  5152.1 2066.09  5185.4 2069.03
  5266.1 2073.24  5908.0 2075.62  6097.9 2079.22  6442.5 2088.58  6534.7 2092.79
  6625.9 2090.71  6633.9 2091.03  6640.9 2094.66  6664.7 2092.39  6895.7 2095.31
#Mann=10,-1,0
  3770.6    0.07       0  3791.8   0.035       0  4960.0    0.07       0
  5049.2    0.07       0  5062.9    0.07       0  5152.1   0.035       0
  5185.4    0.07       0  6097.9   0.045       0  6442.5   0.035       0
  6625.9   0.045       0
Bank Sta=5049.2,5062.9
Exp/Cntr=0.3,0.1

Type RM Length L Ch R = 1,18500,500,500,500
BEGIN DESCRIPTION:
Cottonwood Trib100 36.0
END DESCRIPTION:
XS GIS Cut Line= 3
      1357417.08      6931287.13      1355602.22      6930940.85
      1353640.43      6930535.18
#Sta/Elev= 30
  3152.4 2094.83  3195.2 2095.33  3236.0 2092.54  3546.8 2082.87  3706.5 2077.37
  4188.6 2071.32  4284.5 2070.98  4350.9 2073.03  4752.8 2067.69  4915.7 2058.10
  4976.2 2052.48  4976.7 2051.98  4994.2 2052.48  5002.0 2053.06  5076.4 2055.64
  5160.6 2061.63  5387.4 2070.62  5674.4 2071.88  5869.6 2073.13  6175.6 2072.63
  6270.9 2077.74  6304.2 2076.97  6345.1 2080.03  6406.0 2080.21  6735.0 2086.35
  6825.0 2088.57  6835.2 2085.60  6845.5 2085.32  6955.3 2091.51  7003.3 2094.34
#Mann=14,-1,0
  3152.4   0.045       0  3546.8   0.035       0  3706.5   0.045       0
  4188.6   0.035       0  4350.9    0.07       0  4976.2    0.07       0
  4994.2    0.07       0  5002.0   0.035       0  5076.4    0.07       0
  5674.4   0.035       0  5869.6    0.07       0  6406.0   0.045       0
  6735.0   0.035       0  6955.3   0.045       0
Bank Sta=4976.2,4994.2
Exp/Cntr=0.3,0.1

Type RM Length L Ch R = 1,18000,500,500,500
BEGIN DESCRIPTION:
Cottonwood Trib100 35.0
END DESCRIPTION:
XS GIS Cut Line= 3
      1357385.85      6931094.42      1355705.00      6930476.61
      1353614.41      6930470.07
#Sta/Elev= 30
  3209.2 2091.38  3527.6 2081.32  3619.7 2080.50  3692.5 2077.40  4030.5 2069.86
  4194.2 2069.41  4362.8 2068.65  4460.8 2070.56  4749.6 2068.95  4860.9 2064.78
  4904.1 2060.46  4921.8 2056.45  5001.0 2049.69  5001.5 2049.19  5019.0 2049.69
  5020.0 2052.08  5030.0 2053.35  5070.0 2054.38  5240.0 2070.15  5830.0 2071.90
  6210.0 2070.81  6451.0 2076.85  6789.4 2084.51  6860.0 2086.90  6890.0 2082.53
  6940.0 2089.90  6970.0 2087.63  7008.1 2089.59  7070.0 2094.15  7090.6 2093.14
#Mann=10,-1,0
  3209.2   0.045       0  3527.6   0.035       0  3692.5   0.045       0
  4194.2   0.035       0  4362.8    0.07       0  5001.0    0.07       0
  5019.0    0.07       0  6451.0   0.045       0  6789.4   0.035       0
  7008.1   0.045       0
Bank Sta=5001,5019
Exp/Cntr=0.3,0.1

Type RM Length L Ch R = 1,17500,720,720,720
BEGIN DESCRIPTION:
Cottonwood Trib100 34.0
END DESCRIPTION:
XS GIS Cut Line= 3
      1357704.97      6931137.98      1355788.01      6930004.11
      1353484.21      6930457.05
#Sta/Elev= 30
  2772.8 2103.71  2889.0 2097.51  3028.4 2095.38  3057.5 2092.85  3436.9 2082.75
  3612.1 2077.74  3876.5 2069.56  4149.9 2066.80  4325.9 2067.40  4489.0 2068.86
  4787.3 2065.90  4803.0 2065.28  4830.2 2056.92  4861.5 2052.50  4947.2 2051.99
  4959.7 2049.17  4960.2 2048.67  4977.7 2049.17  4998.8 2055.74  5304.5 2068.34
  6188.4 2069.38  6536.1 2074.56  6897.5 2082.03  6959.4 2084.46  6980.2 2081.35
  7021.0 2082.85  7082.1 2090.17  7105.2 2087.91  7214.6 2094.33  7347.9 2095.03
#Mann=10,-1,0
  2772.8   0.045       0  3436.9   0.035       0  3612.1   0.045       0
  4149.9   0.035       0  4325.9    0.07       0  4959.7    0.07       0
  4977.7    0.07       0  6536.1   0.045       0  6897.5   0.035       0
  7105.2   0.045       0
Bank Sta=4959.7,4977.7
Exp/Cntr=0.3,0.1

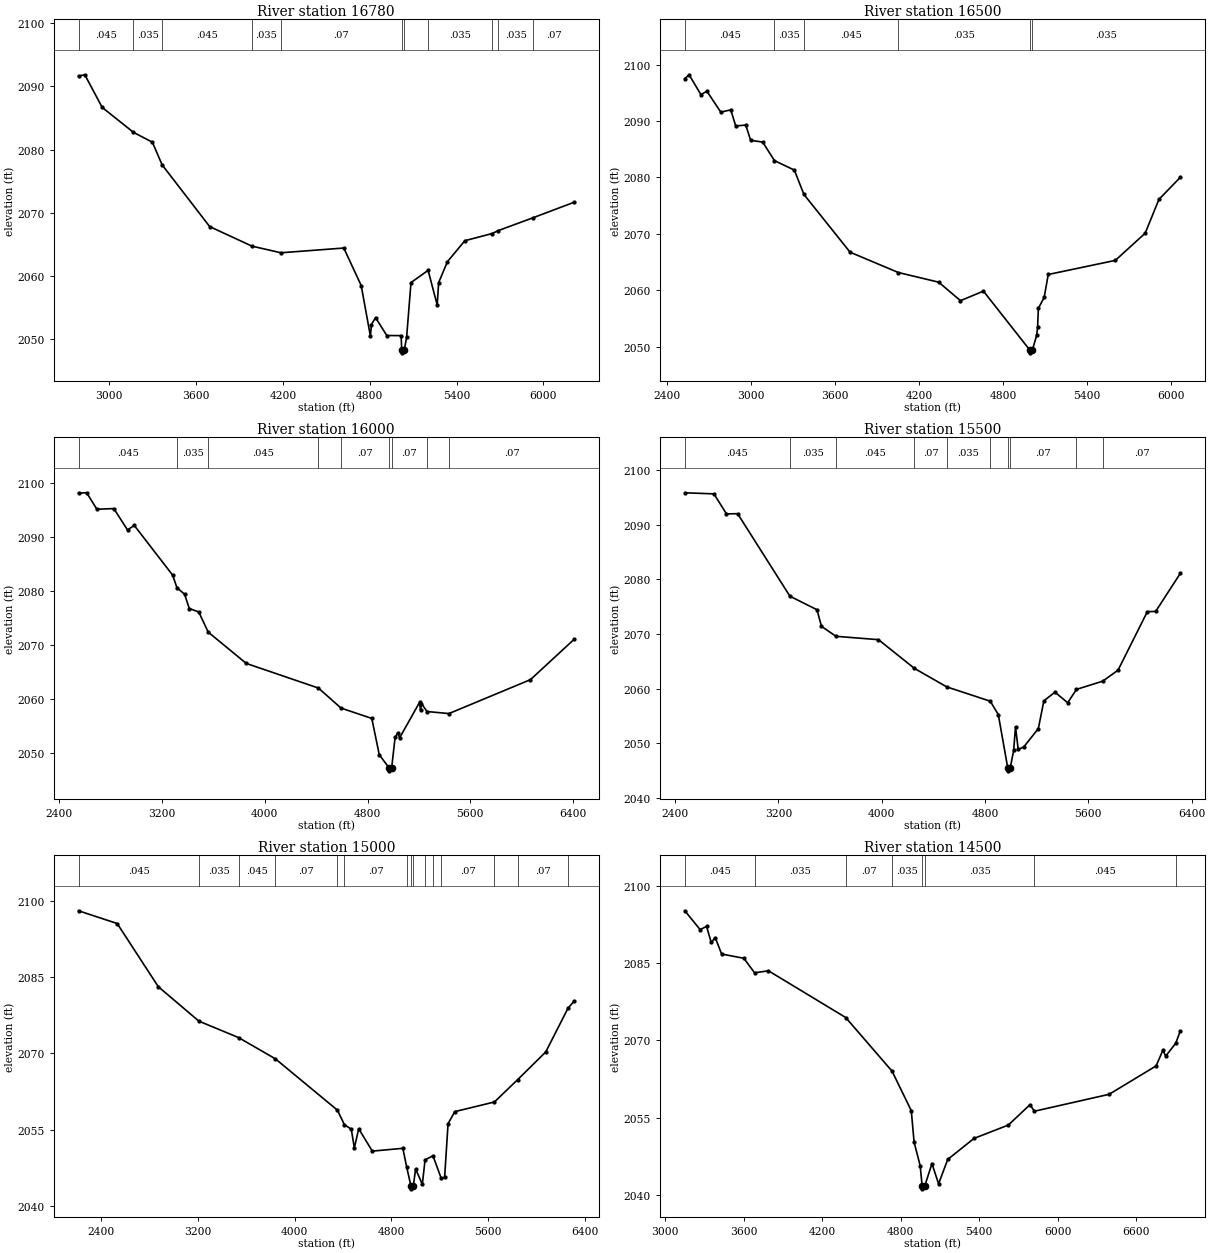
Type RM Length L Ch R = 1,16780,280,280,280
BEGIN DESCRIPTION:
Cottonwood Trib100 33.0
END DESCRIPTION:
XS GIS Cut Line= 3
      1357401.47      6931063.15      1355828.57      6929464.22
      1354654.98      6929588.00
#Sta/Elev= 30
  2788.1 2091.62  2831.7 2091.82  2951.8 2086.66  3167.7 2082.72  3298.4 2081.16
  3365.7 2077.58  3694.3 2067.82  3986.0 2064.73  4186.6 2063.68  4620.7 2064.43
  4740.9 2058.50  4804.5 2050.51  4811.7 2052.33  4840.0 2053.43  4917.7 2050.60
  5016.7 2050.58  5020.7 2048.36  5021.2 2047.86  5039.3 2048.36  5054.7 2050.35
  5084.9 2058.97  5203.2 2060.90  5265.9 2055.43  5275.9 2058.96  5336.3 2062.26
  5456.9 2065.59  5645.4 2066.72  5688.2 2067.19  5929.6 2069.23  6211.1 2071.66
#Mann=11,-1,0
  2788.1   0.045       0  3167.7   0.035       0  3365.7   0.045       0
  3986.0   0.035       0  4186.6    0.07       0  5020.7    0.07       0
  5039.3    0.07       0  5203.2   0.035       0  5645.4    0.07       0
  5688.2   0.035       0  5929.6    0.07       0
Bank Sta=5020.7,5039.3
Exp/Cntr=0.3,0.1

Type RM Length L Ch R = 1,16500,500,500,500
BEGIN DESCRIPTION:
Cottonwood Trib100 32.0
END DESCRIPTION:
XS GIS Cut Line= 3
      1357583.78      6931141.29      1355980.72      6929261.77
      1355004.98      6928837.99
#Sta/Elev= 30
  2529.7 2097.52  2560.0 2098.20  2644.6 2094.69  2687.4 2095.28  2786.2 2091.58
  2857.6 2091.98  2892.7 2089.12  2964.1 2089.29  2999.2 2086.58  3084.9 2086.27
  3169.0 2082.98  3311.0 2081.30  3378.9 2076.99  3708.5 2066.74  4052.6 2063.14
  4339.9 2061.43  4495.8 2058.15  4659.4 2059.84  4989.9 2049.40  4990.4 2048.90
  5008.5 2049.40  5038.9 2052.00  5045.8 2053.45  5051.2 2056.80  5092.7 2058.73
  5121.6 2062.79  5599.9 2065.29  5813.0 2070.11  5911.1 2076.11  6063.8 2080.02
#Mann=6,-1,0
  2529.7   0.045       0  3169.0   0.035       0  3378.9   0.045       0
  4052.6   0.035       0  4989.9   0.035       0  5008.5   0.035       0
Bank Sta=4989.9,5008.5
Exp/Cntr=0.3,0.1

Type RM Length L Ch R = 1,16000,500,500,500
BEGIN DESCRIPTION:
Cottonwood Trib100 31.0
END DESCRIPTION:
XS GIS Cut Line= 3
      1357615.05      6931084.04      1356343.87      6928989.15
      1355354.99      6927987.99
#Sta/Elev= 30
  2549.6 2098.08  2613.2 2098.13  2692.7 2095.08  2824.5 2095.21  2931.2 2091.25
  2983.5 2092.10  3281.9 2082.92  3316.1 2080.57  3375.5 2079.37  3411.9 2076.73
  3485.6 2076.09  3559.4 2072.36  3855.9 2066.57  4417.4 2062.02  4592.9 2058.32
  4832.9 2056.40  4891.0 2049.69  4968.7 2047.21  4969.2 2046.71  4987.3 2047.21
  5014.2 2052.89  5035.4 2053.75  5049.5 2052.81  5205.1 2059.39  5212.2 2057.92
  5219.2 2059.15  5262.9 2057.68  5433.3 2057.30  6067.8 2063.57  6407.2 2071.01
#Mann=9,-1,0
  2549.6   0.045       0  3316.1   0.035       0  3559.4   0.045       0
  4417.4   0.035       0  4592.9    0.07       0  4968.7    0.07       0
  4987.3    0.07       0  5262.9   0.035       0  5433.3    0.07       0
Bank Sta=4968.7,4987.3
Exp/Cntr=0.3,0.1

Type RM Length L Ch R = 1,15500,500,500,500
BEGIN DESCRIPTION:
Cottonwood Trib100 30.0
END DESCRIPTION:
XS GIS Cut Line= 3
      1357557.76      6931026.75      1356605.07      6928687.94
      1355755.03      6927688.03
#Sta/Elev= 30
  2474.6 2095.83  2700.0 2095.63  2797.2 2091.97  2883.6 2092.01  3288.3 2076.93
  3498.1 2074.45  3532.9 2071.42  3645.5 2069.59  3974.1 2068.98  4253.3 2063.72
  4502.9 2060.35  4840.2 2057.73  4902.4 2055.29  4975.9 2045.50  4976.4 2045.00
  4994.7 2045.50  5021.4 2048.72  5035.7 2053.03  5056.6 2048.92  5099.4 2049.36
  5212.5 2052.72  5255.4 2057.80  5341.1 2059.38  5439.9 2057.45  5508.1 2059.89
  5711.0 2061.39  5829.7 2063.40  6057.1 2074.11  6120.8 2074.13  6312.4 2081.10
#Mann=10,-1,0
  2474.6   0.045       0  3288.3   0.035       0  3645.5   0.045       0
  4253.3    0.07       0  4502.9   0.035       0  4840.2    0.07       0
  4975.9    0.07       0  4994.7    0.07       0  5508.1   0.035       0
  5711.0    0.07       0
Bank Sta=4975.9,4994.7
Exp/Cntr=0.3,0.1

Type RM Length L Ch R = 1,15000,500,500,500
BEGIN DESCRIPTION:
Cottonwood Trib100 29.0
END DESCRIPTION:
XS GIS Cut Line= 4
      1357641.08      6930959.02      1356764.45      6928515.55
      1356848.31      6928341.80      1355855.02      6927488.02
#Sta/Elev= 30
  2211.1 2098.14  2530.9 2095.63  2871.0 2083.17  3207.1 2076.37  3535.2 2073.13
  3839.6 2068.94  4353.1 2058.81  4410.0 2055.96  4467.3 2055.07  4492.8 2051.36
  4528.8 2055.15  4641.2 2050.74  4893.8 2051.29  4926.3 2047.52  4961.5 2043.80
  4962.0 2043.30  4980.3 2043.80  4999.3 2047.22  5055.0 2044.20  5077.6 2049.00
  5142.8 2049.83  5211.1 2045.39  5239.4 2045.55  5267.9 2056.16  5323.9 2058.53
  5651.3 2060.43  5844.2 2064.85  6075.6 2070.29  6260.6 2078.95  6309.8 2080.29
#Mann=15,-1,0
  2211.1   0.045       0  3207.1   0.035       0  3535.2   0.045       0
  3839.6    0.07       0  4353.1   0.035       0  4410.0    0.07       0
  4926.3    0.16       0  4961.5    0.07       0  4980.3    0.16       0
  5077.6    0.07       0  5142.8    0.16       0  5211.1    0.07       0
  5651.3   0.035       0  5844.2    0.07       0  6260.6   0.045       0
Bank Sta=4961.5,4980.3
Exp/Cntr=0.3,0.1

Type RM Length L Ch R = 1,14500,500,500,500
BEGIN DESCRIPTION:
Cottonwood Trib100 28.0
END DESCRIPTION:
XS GIS Cut Line= 4
      1357750.44      6930365.25      1357091.52      6928637.64
      1357146.39      6928085.00      1356833.90      6926737.82
#Sta/Elev= 30
  3151.0 2095.17  3267.8 2091.52  3317.3 2092.13  3352.7 2089.02  3383.5 2089.96
  3432.3 2086.77  3602.1 2085.95  3684.1 2083.13  3790.2 2083.52  4380.4 2074.45
  4734.7 2064.04  4881.9 2056.36  4903.3 2050.27  4949.8 2045.67  4965.1 2041.69
  4965.6 2041.19  4984.0 2041.69  5039.8 2046.09  5090.5 2042.16  5160.4 2046.90
  5361.4 2050.98  5623.5 2053.57  5788.4 2057.51  5823.5 2056.26  6394.0 2059.54
  6753.3 2065.06  6804.7 2068.10  6826.6 2066.96  6902.8 2069.44  6938.3 2071.86
#Mann=8,-1,0
  3151.0   0.045       0  3684.1   0.035       0  4380.4    0.07       0
  4734.7   0.035       0  4965.1    0.07       0  4984.0   0.035       0
  5823.5   0.045       0  6902.8   0.035       0
Bank Sta=4965.1,4984
Exp/Cntr=0.3,0.1

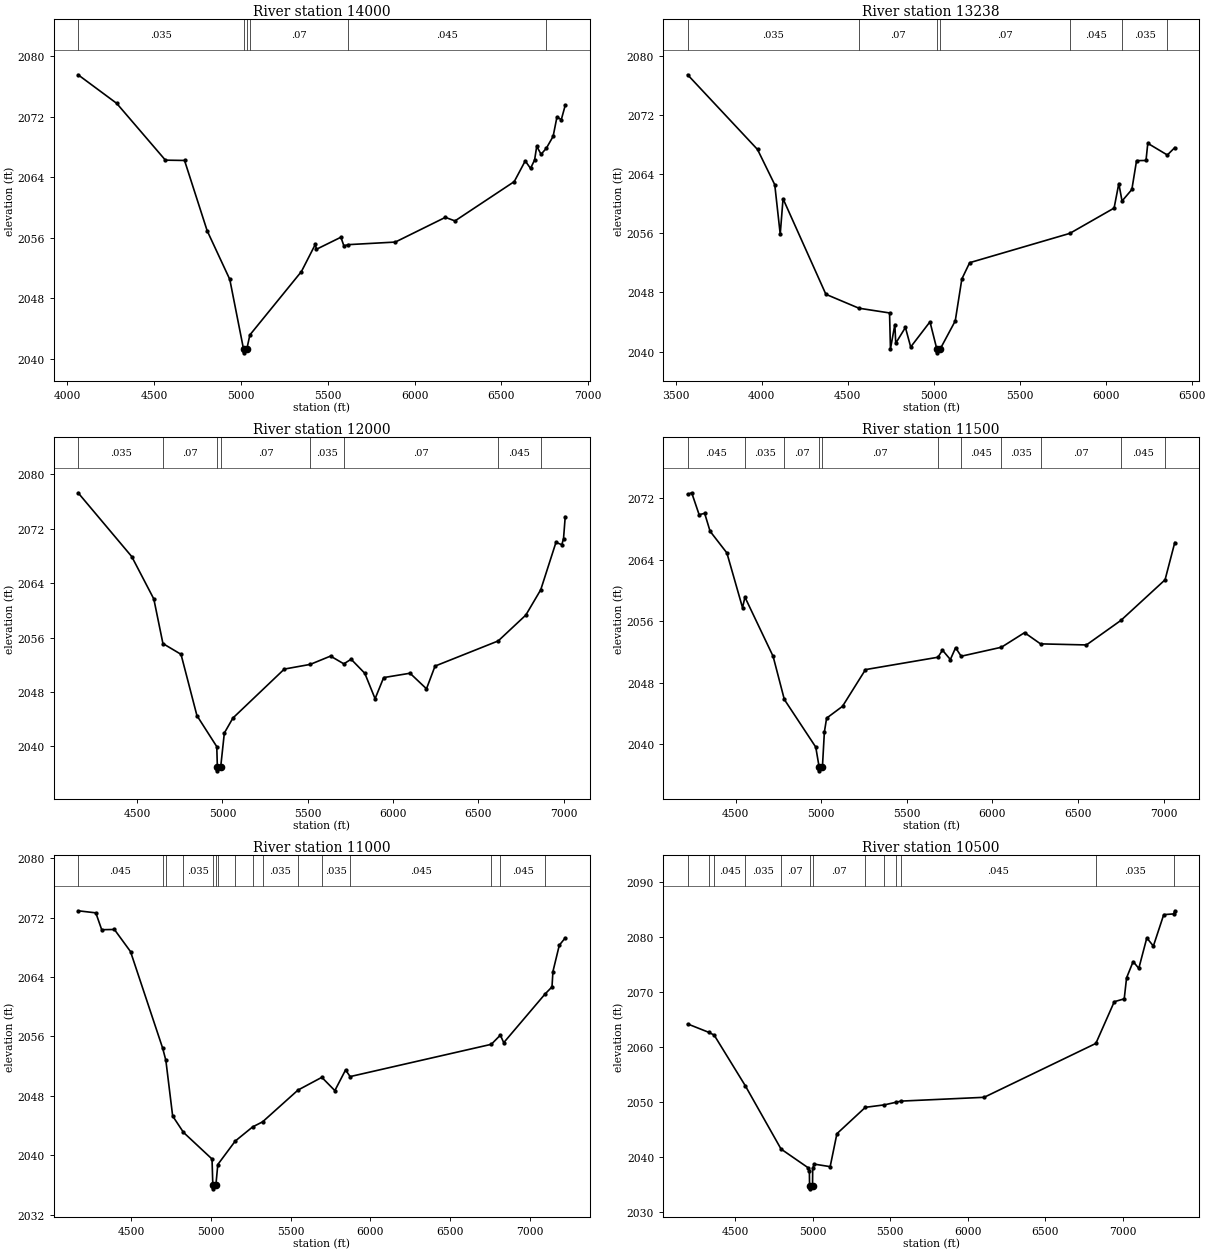
Type RM Length L Ch R = 1,14000,762,762,762
BEGIN DESCRIPTION:
Cottonwood Trib100 27.0
END DESCRIPTION:
XS GIS Cut Line= 3
      1357451.94      6929369.76      1357509.24      6928434.11
      1356861.82      6926682.64
#Sta/Elev= 30
  4062.6 2077.55  4284.8 2073.77  4565.3 2066.25  4675.5 2066.21  4805.7 2056.91
  4936.0 2050.47  5015.1 2041.25  5015.6 2040.75  5034.0 2041.25  5051.7 2043.12
  5348.5 2051.51  5429.0 2055.13  5434.4 2054.45  5575.8 2056.05  5592.9 2054.91
  5619.1 2055.07  5889.0 2055.41  6177.1 2058.68  6232.6 2058.21  6573.7 2063.41
  6637.1 2066.15  6667.5 2065.16  6691.0 2066.28  6703.2 2068.08  6728.3 2067.03
  6758.6 2067.83  6797.6 2069.40  6819.6 2071.95  6844.7 2071.61  6867.3 2073.51
#Mann=6,-1,0
  4062.6   0.035       0  5015.1   0.035       0  5034.0   0.035       0
  5051.7    0.07       0  5619.1   0.045       0  6758.6   0.035       0
Bank Sta=5015.1,5034
Exp/Cntr=0.3,0.1

Type RM Length L Ch R = 1,13238,1238,1238,1238
BEGIN DESCRIPTION:
Cottonwood Trib100 26.0
END DESCRIPTION:
XS GIS Cut Line= 3
      1357472.78      6929334.99      1357957.15      6927982.57
      1357545.26      6926648.14
#Sta/Elev= 30
  3568.7 2077.40  3975.1 2067.31  4075.4 2062.55  4107.2 2055.86  4123.6 2060.65
  4372.8 2047.74  4564.8 2045.86  4743.0 2045.22  4748.3 2040.36  4773.8 2043.65
  4779.1 2041.13  4835.3 2043.26  4866.0 2040.62  4978.2 2044.02  5018.1 2040.33
  5018.6 2039.83  5037.2 2040.33  5125.1 2044.14  5163.5 2049.81  5208.9 2052.01
  5791.4 2055.97  6049.0 2059.39  6076.4 2062.71  6095.1 2060.34  6152.2 2061.90
  6179.6 2065.80  6234.5 2065.82  6244.9 2068.14  6358.6 2066.56  6401.8 2067.56
#Mann=7,-1,0
  3568.7   0.035       0  4564.8    0.07       0  5018.1    0.07       0
  5037.2    0.07       0  5791.4   0.045       0  6095.1   0.035       0
  6358.6   0.045       0
Bank Sta=5018.1,5037.2
Exp/Cntr=0.3,0.1

Type RM Length L Ch R = 1,12000,500,500,500
BEGIN DESCRIPTION:
Cottonwood Trib100 24.0
END DESCRIPTION:
XS GIS Cut Line= 3
      1357486.66      6929355.84      1358192.57      6928889.38
      1358005.00      6926888.05
#Sta/Elev= 30
  4153.9 2077.30  4468.5 2067.92  4597.9 2061.69  4651.4 2055.13  4757.4 2053.55
  4850.7 2044.54  4967.0 2039.98  4970.6 2036.92  4971.1 2036.42  4989.7 2036.92
  5011.4 2041.98  5061.6 2044.18  5363.0 2051.38  5515.1 2052.07  5634.1 2053.29
  5712.1 2052.15  5754.7 2052.83  5835.0 2050.76  5895.3 2047.02  5945.5 2050.13
  6100.2 2050.77  6196.6 2048.48  6246.8 2051.82  6617.2 2055.52  6779.1 2059.32
  6866.5 2063.04  6955.7 2070.00  6990.1 2069.67  7000.1 2070.54  7010.1 2073.79
#Mann=8,-1,0
  4153.9   0.035       0  4651.4    0.07       0  4970.6    0.07       0
  4989.7    0.07       0  5515.1   0.035       0  5712.1    0.07       0
  6617.2   0.045       0  6866.5   0.035       0
Bank Sta=4970.6,4989.7
Exp/Cntr=0.3,0.1

Type RM Length L Ch R = 1,11500,500,500,500
BEGIN DESCRIPTION:
Cottonwood Trib100 23.0
END DESCRIPTION:
XS GIS Cut Line= 3
      1358861.68      6929710.02      1358565.25      6928988.87
      1358055.00      6926988.00
#Sta/Elev= 30
  4220.3 2072.50  4244.1 2072.71  4287.4 2069.86  4319.8 2070.03  4351.5 2067.70
  4449.5 2064.88  4540.9 2057.75  4555.0 2059.12  4719.4 2051.42  4785.0 2045.80
  4968.5 2039.60  4988.2 2037.01  4988.7 2036.51  5007.4 2037.01  5018.8 2041.56
  5031.9 2043.37  5124.7 2044.91  5258.9 2049.69  5682.1 2051.30  5708.5 2052.22
  5754.5 2051.00  5785.1 2052.54  5817.5 2051.43  6052.5 2052.60  6187.7 2054.50
  6281.0 2053.04  6548.9 2052.90  6750.1 2056.09  7008.2 2061.38  7064.9 2066.23
#Mann=11,-1,0
  4220.3   0.045       0  4555.0   0.035       0  4785.0    0.07       0
  4988.2    0.07       0  5007.4    0.07       0  5682.1   0.035       0
  5817.5   0.045       0  6052.5   0.035       0  6281.0    0.07       0
  6750.1   0.045       0  7008.2   0.035       0
Bank Sta=4988.2,5007.4
Exp/Cntr=0.3,0.1

Type RM Length L Ch R = 1,11000,500,500,500
BEGIN DESCRIPTION:
Cottonwood Trib100 22.0
END DESCRIPTION:
XS GIS Cut Line= 3
      1359417.23      6929668.34      1358988.54      6928954.93
      1358055.00      6926938.00
#Sta/Elev= 30
  4167.7 2072.94  4278.9 2072.66  4315.8 2070.39  4395.4 2070.42  4496.5 2067.44
  4698.2 2054.41  4718.1 2052.78  4760.7 2045.28  4828.5 2043.07  5007.6 2039.48
  5012.6 2035.96  5013.1 2035.46  5031.8 2035.96  5043.9 2038.74  5153.2 2041.90
  5262.4 2043.81  5324.7 2044.49  5546.6 2048.77  5696.2 2050.49  5777.8 2048.70
  5845.1 2051.49  5873.6 2050.59  6758.8 2054.94  6815.8 2056.18  6836.8 2055.16
  7096.8 2061.74  7139.5 2062.68  7145.4 2064.75  7185.4 2068.30  7222.5 2069.28
#Mann=16,-1,0
  4167.7   0.045       0  4698.2   0.035       0  4718.1    0.07       0
  4828.5   0.035       0  5012.6   0.035       0  5031.8   0.035       0
  5043.9    0.07       0  5153.2   0.035       0  5262.4    0.07       0
  5324.7   0.035       0  5546.6    0.07       0  5696.2   0.035       0
  5873.6   0.045       0  6758.8    0.07       0  6815.8   0.045       0
  7096.8   0.035       0
Bank Sta=5012.6,5031.8
Exp/Cntr=0.3,0.1

Type RM Length L Ch R = 1,10500,500,500,500
BEGIN DESCRIPTION:
Cottonwood Trib100 21.0
END DESCRIPTION:
XS GIS Cut Line= 4
      1359467.57      6929310.69      1359269.65      6928654.44
      1359154.80      6928613.13      1357905.02      6926638.03
#Sta/Elev= 30
  4192.5 2064.13  4327.7 2062.62  4363.6 2062.11  4564.6 2052.91  4795.6 2041.40
  4972.0 2037.97  4978.5 2037.44  4979.6 2034.67  4980.1 2034.17  4998.8 2034.67
  5000.0 2037.95  5010.5 2038.66  5112.6 2038.20  5156.3 2044.19  5339.8 2048.98
  5463.4 2049.43  5538.9 2049.91  5570.0 2050.11  6106.5 2050.80  6827.9 2060.59
  6946.8 2068.17  7011.0 2068.69  7026.2 2072.51  7068.6 2075.46  7105.1 2074.22
  7156.8 2079.76  7199.2 2078.28  7266.1 2083.99  7330.7 2084.12  7337.3 2084.69
#Mann=13,-1,0
  4192.5   0.045       0  4327.7   0.035       0  4363.6   0.045       0
  4564.6   0.035       0  4795.6    0.07       0  4979.6    0.07       0
  4998.8    0.07       0  5339.8   0.035       0  5463.4    0.07       0
  5538.9   0.035       0  5570.0   0.045       0  6827.9   0.035       0
  7330.7   0.045       0
Bank Sta=4979.6,4998.8
Exp/Cntr=0.3,0.1

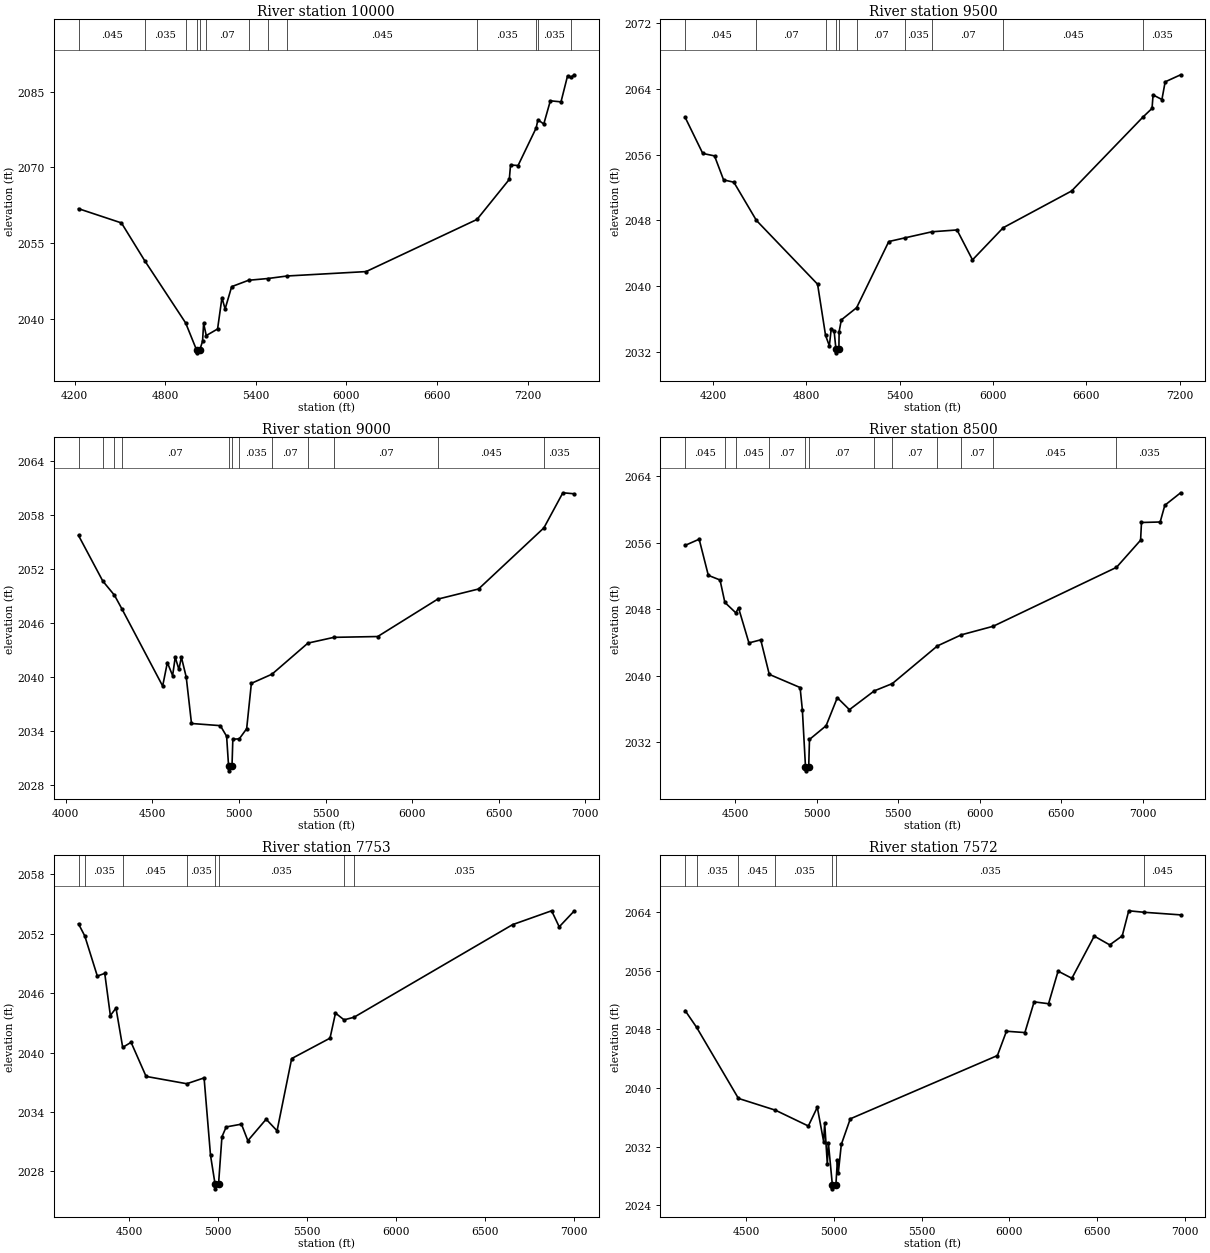
Type RM Length L Ch R = 1,10000,500,500,500
BEGIN DESCRIPTION:
Cottonwood Trib100 20.0
END DESCRIPTION:
XS GIS Cut Line= 3
      1359550.90      6929336.71      1359438.65      6928571.39
      1357904.98      6926587.98
#Sta/Elev= 30
  4226.5 2061.85  4510.8 2059.03  4664.1 2051.59  4936.0 2039.23  5009.1 2033.82
  5009.6 2033.32  5028.3 2033.82  5047.7 2035.58  5054.9 2039.15  5072.3 2036.74
  5147.3 2038.04  5176.3 2044.24  5197.1 2042.00  5240.6 2046.42  5352.3 2047.68
  5480.5 2048.03  5608.2 2048.53  6130.7 2049.40  6864.9 2059.72  7078.8 2067.65
  7087.0 2070.50  7136.8 2070.39  7256.7 2077.83  7268.2 2079.45  7307.0 2078.60
  7350.5 2083.20  7421.1 2082.99  7464.6 2088.15  7487.6 2087.82  7507.2 2088.35
#Mann=13,-1,0
  4226.5   0.045       0  4664.1   0.035       0  4936.0    0.16       0
  5009.1    0.07       0  5028.3    0.16       0  5072.3    0.07       0
  5352.3   0.035       0  5480.5    0.07       0  5608.2   0.045       0
  6864.9   0.035       0  7256.7   0.045       0  7268.2   0.035       0
  7487.6   0.045       0
Bank Sta=5009.1,5028.3
Exp/Cntr=0.3,0.1

Type RM Length L Ch R = 1,9500,500,500,500
BEGIN DESCRIPTION:
Cottonwood Trib100 19.0
END DESCRIPTION:
XS GIS Cut Line= 3
      1359655.01      6929387.96      1359890.56      6928436.69
      1358250.08      6926962.86
#Sta/Elev= 30
  4020.0 2060.53  4133.3 2056.14  4208.9 2055.84  4267.2 2052.92  4333.1 2052.64
  4478.2 2047.99  4871.4 2040.23  4922.6 2034.01  4947.1 2032.73  4959.3 2034.84
  4978.0 2034.48  4989.2 2032.38  4989.7 2031.88  5008.4 2032.38  5009.9 2034.46
  5024.1 2035.89  5122.3 2037.37  5329.0 2045.42  5430.8 2045.86  5606.9 2046.61
  5767.8 2046.83  5867.2 2043.19  6064.5 2047.10  6504.1 2051.57  6962.7 2060.56
  7021.4 2061.62  7028.1 2063.26  7084.9 2062.70  7105.8 2064.85  7205.3 2065.71
#Mann=10,-1,0
  4020.0   0.045       0  4478.2    0.07       0  4922.6    0.16       0
  4989.2    0.07       0  5008.4    0.16       0  5122.3    0.07       0
  5430.8   0.035       0  5606.9    0.07       0  6064.5   0.045       0
  6962.7   0.035       0
Bank Sta=4989.2,5008.4
Exp/Cntr=0.3,0.1

Type RM Length L Ch R = 1,9000,500,500,500
BEGIN DESCRIPTION:
Cottonwood Trib100 18.0
END DESCRIPTION:
XS GIS Cut Line= 3
      1360954.96      6928587.98      1360175.35      6928087.73
      1358519.80      6927086.82
#Sta/Elev= 30
  4073.7 2055.73  4214.0 2050.66  4281.2 2049.09  4323.2 2047.61  4559.6 2039.00
  4586.7 2041.61  4617.1 2040.16  4632.1 2042.20  4653.4 2040.85  4667.7 2042.21
  4695.7 2039.99  4726.1 2034.84  4892.6 2034.60  4928.9 2033.42  4940.3 2030.08
  4940.8 2029.58  4959.9 2030.08  4964.8 2033.10  5001.8 2033.13  5044.6 2034.26
  5071.8 2039.30  5191.0 2040.32  5398.4 2043.77  5548.4 2044.41  5801.2 2044.50
  6147.2 2048.65  6383.3 2049.78  6760.7 2056.57  6870.3 2060.47  6934.6 2060.36
#Mann=12,-1,0
  4073.7   0.045       0  4214.0   0.035       0  4281.2   0.045       0
  4323.2    0.07       0  4940.3    0.07       0  4959.9    0.07       0
  5001.8   0.035       0  5191.0    0.07       0  5398.4   0.035       0
  5548.4    0.07       0  6147.2   0.045       0  6760.7   0.035       0
Bank Sta=4940.3,4959.9
Exp/Cntr=0.3,0.1

Type RM Length L Ch R = 1,8500,747,747,747
BEGIN DESCRIPTION:
Cottonwood Trib100 17.0
END DESCRIPTION:
XS GIS Cut Line= 3
      1361205.00      6928488.00      1360563.44      6927995.98
      1358535.30      6927060.70
#Sta/Elev= 30
  4191.5 2055.66  4277.6 2056.40  4333.8 2052.06  4405.7 2051.50  4435.3 2048.81
  4502.9 2047.55  4519.1 2048.16  4583.1 2043.94  4655.6 2044.31  4708.0 2040.16
  4897.2 2038.58  4911.2 2035.88  4930.3 2029.07  4930.8 2028.57  4950.1 2029.07
  4954.8 2032.34  5056.9 2033.99  5125.7 2037.36  5200.1 2035.92  5352.8 2038.18
  5463.2 2039.05  5740.2 2043.58  5886.8 2044.91  6082.5 2045.94  6839.5 2053.02
  6987.5 2056.28  6993.0 2058.41  7107.8 2058.47  7136.3 2060.48  7233.4 2061.98
#Mann=12,-1,0
  4191.5   0.045       0  4435.3   0.035       0  4502.9   0.045       0
  4708.0    0.07       0  4930.3    0.07       0  4950.1    0.07       0
  5352.8   0.035       0  5463.2    0.07       0  5740.2   0.035       0
  5886.8    0.07       0  6082.5   0.045       0  6839.5   0.035       0
Bank Sta=4930.3,4950.1
Exp/Cntr=0.3,0.1

Type RM Length L Ch R = 1,7753,181,181,181
BEGIN DESCRIPTION:
Cottonwood Trib100 16.0
END DESCRIPTION:
XS GIS Cut Line= 4
      1361138.15      6928298.35      1360929.81      6927673.32
      1360783.98      6927636.86      1358858.49      6927194.52
#Sta/Elev= 30
  4214.4 2052.99  4249.6 2051.77  4320.2 2047.72  4361.9 2047.99  4393.5 2043.73
  4425.1 2044.49  4462.8 2040.52  4509.9 2041.03  4594.2 2037.59  4822.9 2036.85
  4920.2 2037.44  4956.3 2029.63  4981.7 2026.74  4982.2 2026.24  5001.5 2026.74
  5020.5 2031.49  5044.5 2032.49  5130.2 2032.77  5166.2 2031.10  5269.0 2033.27
  5330.3 2032.10  5412.4 2039.39  5627.9 2041.45  5658.7 2043.98  5706.8 2043.30
  5762.7 2043.56  6653.9 2052.91  6873.3 2054.31  6916.1 2052.69  6999.2 2054.27
#Mann=8,-1,0
  4214.4   0.045       0  4249.6   0.035       0  4462.8   0.045       0
  4822.9   0.035       0  4981.7   0.035       0  5001.5   0.035       0
  5706.8    0.07       0  5762.7   0.035       0
Bank Sta=4981.7,5001.5
Exp/Cntr=0.3,0.1

Type RM Length L Ch R = 1,7572,572,572,572
BEGIN DESCRIPTION:
Cottonwood Trib100 15.0
END DESCRIPTION:
XS GIS Cut Line= 5
      1361205.01      6928238.03      1360981.89      6927574.36
      1360872.52      6927501.45      1359908.98      6927293.11
      1358950.66      6926980.62
#Sta/Elev= 30
  4150.5 2050.57  4215.7 2048.29  4454.3 2038.58  4665.2 2036.97  4853.0 2034.81
  4904.1 2037.37  4940.2 2032.69  4946.2 2035.20  4961.2 2029.65  4967.2 2032.53
  4990.1 2026.73  4990.6 2026.23  5010.0 2026.73  5018.7 2030.13  5023.9 2028.42
  5041.0 2032.29  5092.1 2035.79  5931.1 2044.43  5982.6 2047.75  6087.8 2047.57
  6140.4 2051.76  6222.8 2051.51  6277.1 2055.96  6355.7 2054.98  6483.3 2060.74
  6571.6 2059.54  6642.8 2060.77  6680.0 2064.20  6764.8 2064.00  6975.9 2063.64
#Mann=7,-1,0
  4150.5   0.045       0  4215.7   0.035       0  4454.3   0.045       0
  4665.2   0.035       0  4990.1   0.035       0  5010.0   0.035       0
  6764.8   0.045       0
Bank Sta=4990.1,5010
Exp/Cntr=0.3,0.1

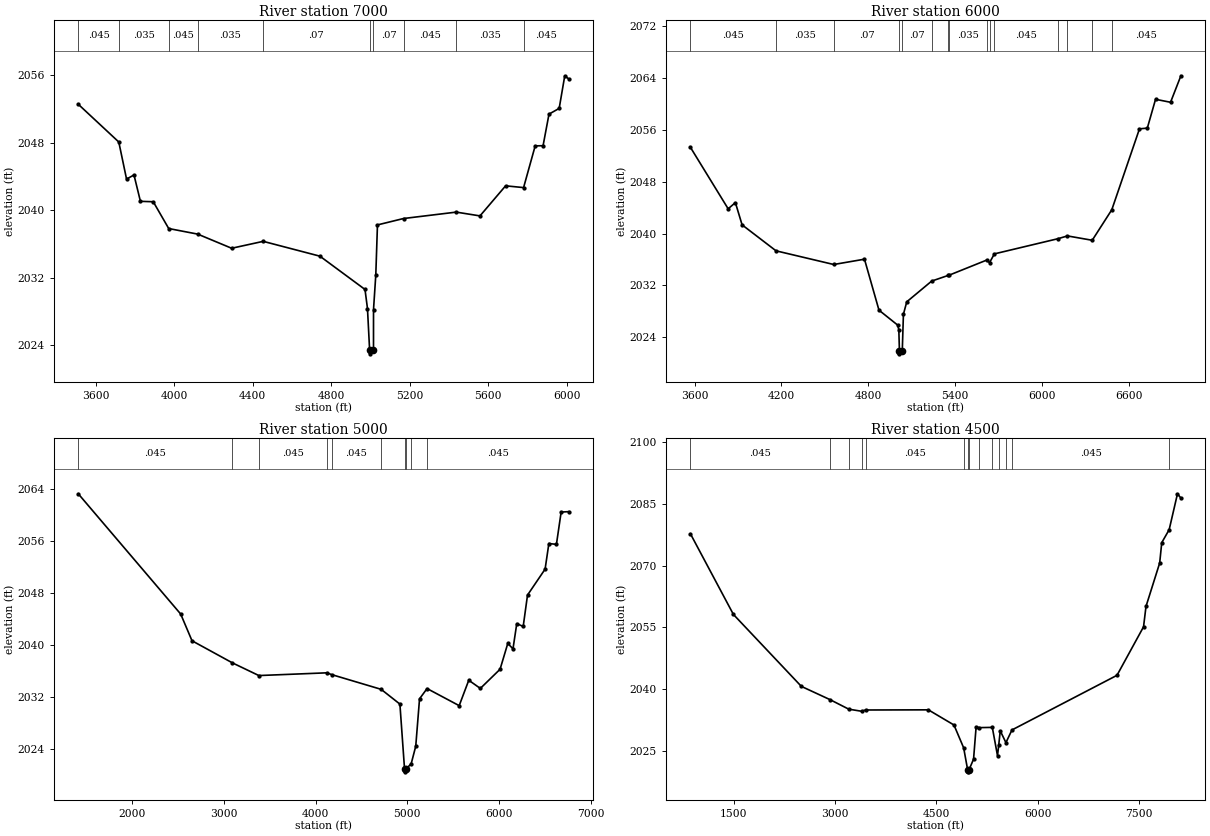
Type RM Length L Ch R = 1,7000,1000,1000,1000
BEGIN DESCRIPTION:
Cottonwood Trib100 14.0
END DESCRIPTION:
XS GIS Cut Line= 4
      1361263.16      6928345.25      1360877.73      6927089.99
      1360710.34      6927035.26      1359705.04      6926938.00
#Sta/Elev= 30
  3510.8 2052.57  3717.4 2048.09  3756.9 2043.69  3794.8 2044.18  3827.6 2041.05
  3893.0 2041.00  3971.8 2037.82  4119.4 2037.16  4292.5 2035.48  4453.3 2036.30
  4742.3 2034.54  4972.0 2030.59  4984.6 2028.33  4995.4 2023.45  4995.9 2022.95
  5015.3 2023.45  5015.4 2028.21  5027.0 2032.31  5035.5 2038.25  5168.3 2039.01
  5437.0 2039.77  5557.9 2039.32  5688.5 2042.89  5780.1 2042.68  5839.2 2047.63
  5879.4 2047.65  5909.6 2051.40  5961.5 2052.08  5989.9 2055.95  6010.0 2055.58
#Mann=10,-1,0
  3510.8   0.045       0  3717.4   0.035       0  3971.8   0.045       0
  4119.4   0.035       0  4453.3    0.07       0  4995.4    0.07       0
  5015.3    0.07       0  5168.3   0.045       0  5437.0   0.035       0
  5780.1   0.045       0
Bank Sta=4995.4,5015.3
Exp/Cntr=0.3,0.1

Type RM Length L Ch R = 1,6000,1000,1000,1000
BEGIN DESCRIPTION:
Cottonwood Trib100 12.0
END DESCRIPTION:
XS GIS Cut Line= 4
      1361405.00      6928487.98      1361305.25      6927062.27
      1360737.10      6926808.74      1359403.82      6926928.53
#Sta/Elev= 30
  3570.8 2053.30  3831.4 2043.82  3881.5 2044.77  3927.8 2041.34  4162.4 2037.33
  4561.2 2035.22  4773.7 2036.04  4874.0 2028.17  5002.9 2025.87  5011.2 2025.14
  5015.2 2021.93  5015.7 2021.43  5035.1 2021.93  5042.9 2027.54  5066.0 2029.46
  5238.2 2032.66  5353.1 2033.54  5361.0 2033.59  5617.2 2035.89  5638.3 2035.51
  5671.6 2036.86  6110.9 2039.20  6176.8 2039.63  6347.9 2038.96  6483.2 2043.67
  6674.5 2056.16  6728.7 2056.27  6785.6 2060.72  6889.3 2060.26  6960.8 2064.35
#Mann=15,-1,0
  3570.8   0.045       0  4162.4   0.035       0  4561.2    0.07       0
  5015.2    0.07       0  5035.1    0.07       0  5238.2   0.035       0
  5353.1    0.07       0  5361.0   0.035       0  5617.2   0.045       0
  5638.3   0.035       0  5671.6   0.045       0  6110.9   0.035       0
  6176.8   0.045       0  6347.9   0.035       0  6483.2   0.045       0
Bank Sta=5015.2,5035.1
Exp/Cntr=0.3,0.1

Type RM Length L Ch R = 1,5000,500,500,500
BEGIN DESCRIPTION:
Cottonwood Trib100 10.0
END DESCRIPTION:
XS GIS Cut Line= 4
      1362138.57      6929479.08      1361237.97      6926397.50
      1360864.29      6926377.57      1359154.98      6926788.00
#Sta/Elev= 30
  1415.3 2063.28  2531.2 2044.78  2654.5 2040.67  3094.7 2037.27  3382.7 2035.32
  4122.7 2035.74  4177.2 2035.46  4714.8 2033.20  4919.2 2030.93  4969.3 2021.01
  4969.8 2020.51  4989.2 2021.01  5042.0 2021.75  5091.8 2024.46  5133.0 2031.74
  5215.0 2033.32  5564.9 2030.69  5669.3 2034.60  5795.3 2033.34  6010.3 2036.29
  6094.3 2040.26  6151.1 2039.43  6192.2 2043.31  6262.2 2042.87  6309.3 2047.70
  6500.8 2051.69  6541.9 2055.63  6624.2 2055.50  6675.6 2060.47  6757.9 2060.53
#Mann=10,-1,0
  1415.3   0.045       0  3094.7   0.035       0  3382.7   0.045       0
  4122.7   0.035       0  4177.2   0.045       0  4714.8    0.07       0
  4969.3    0.07       0  4989.2    0.07       0  5042.0   0.035       0
  5215.0   0.045       0
Bank Sta=4969.3,4989.2
Exp/Cntr=0.3,0.1

Type RM Length L Ch R = 1,4500,0,0,0
BEGIN DESCRIPTION:
Cottonwood Trib100 9.0
END DESCRIPTION:
XS GIS Cut Line= 4
      1362155.00      6929887.99      1361346.48      6926310.69
      1361033.44      6925959.35      1357955.03      6926438.00
#Sta/Elev= 30
   861.9 2077.70  1497.5 2058.13  2502.3 2040.67  2928.0 2037.44  3203.6 2035.14
  3394.7 2034.63  3451.4 2034.94  4380.5 2034.98  4759.3 2031.30  4902.7 2025.75
  4961.5 2020.43  4962.0 2019.93  4981.9 2020.43  5049.0 2023.00  5086.6 2030.80
  5128.7 2030.66  5326.3 2030.72  5403.2 2023.85  5422.0 2026.53  5443.7 2029.88
  5527.6 2027.02  5617.3 2030.10  7170.4 2043.36  7563.0 2055.13  7599.3 2060.08
  7801.7 2070.62  7832.1 2075.55  7942.0 2078.71  8064.8 2087.42  8115.4 2086.38
#Mann=14,-1,0
   861.9   0.045       0  2928.0   0.035       0  3203.6   0.045       0
  3394.7    0.07       0  3451.4   0.045       0  4902.7    0.07       0
  4961.5    0.07       0  4981.9    0.07       0  5128.7   0.045       0
  5326.3    0.07       0  5422.0   0.035       0  5527.6    0.07       0
  5617.3   0.045       0  7942.0   0.035       0
Bank Sta=4961.5,4981.9
Exp/Cntr=0.3,0.1

Chan Stop Cuts=-1