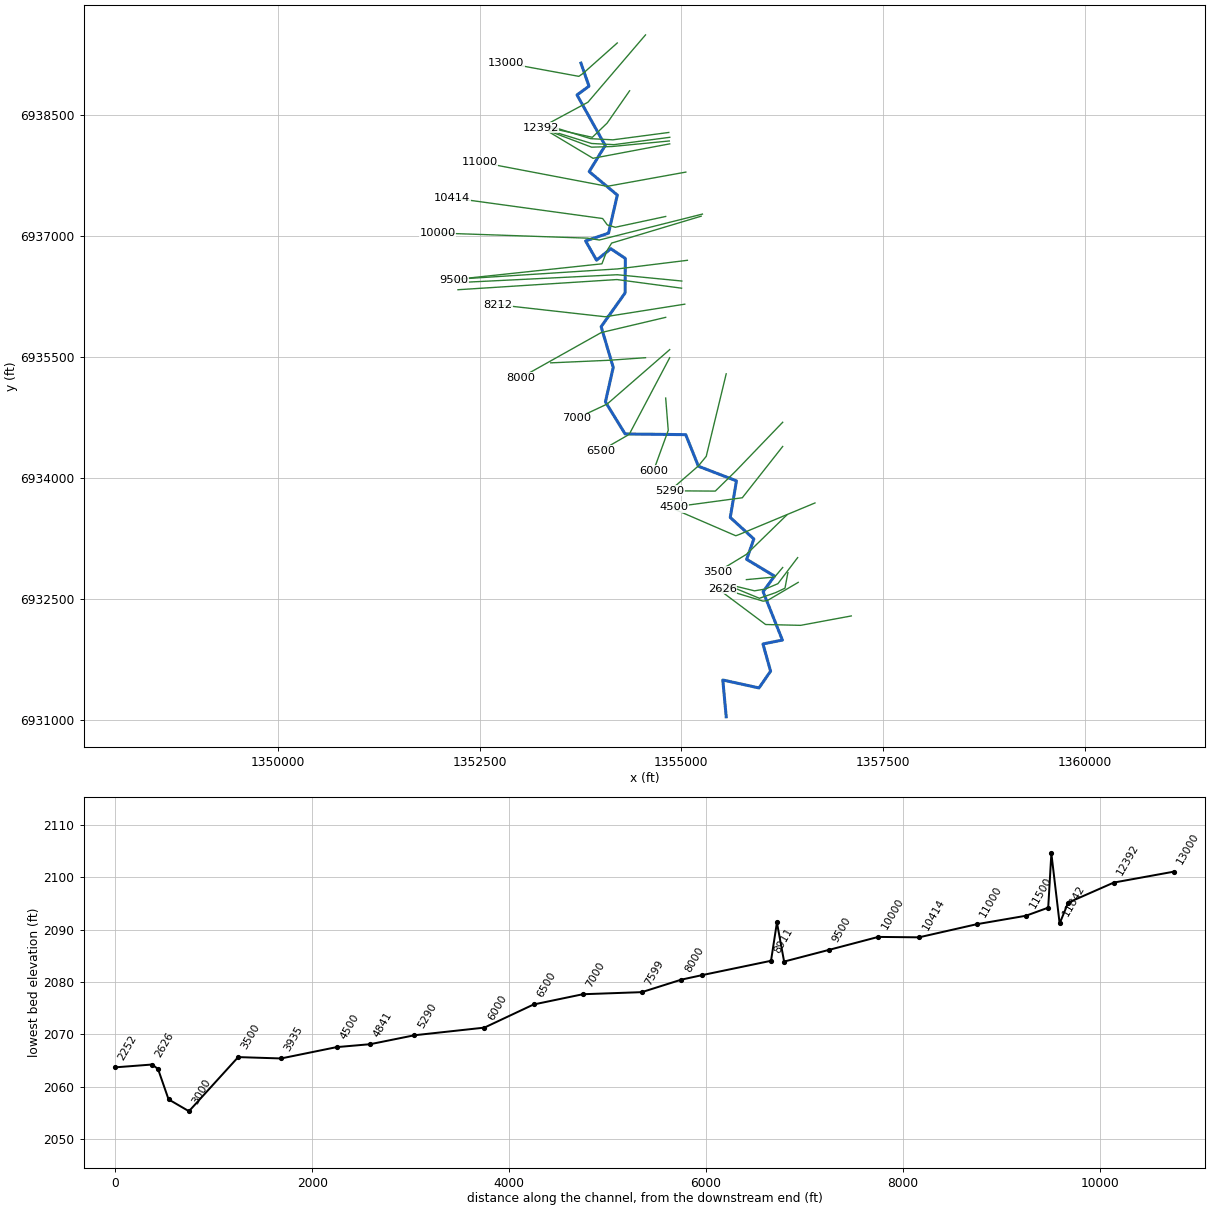
--- Cottonwood Trib100_4.prj (project) ---

Proj Title=Cottonwood Trib100_4 Base Level Engineering
Current Plan=p01
Default Exp/Contr=0.3,0.1
English Units
Geom File=g01
Flow File=f01
Plan File=p01
BEGIN DESCRIPTION:
Cottonwood Trib100_4
END DESCRIPTION:

--- Cottonwood Trib100_4.p01 (plan) ---

Plan Title=Multiple Run
Short Identifier=Multiple
Geom File=g01
Flow File=f01
Subcritical Flow
K Sum by GR= 0
Std Step Tol= 0.01
Critical Tol= 0.01
Num of Std Step Trials= 20
Max Error Tol= 0.3
Flow Tol Ratio= 0.001
Split Flow NTrial= 30
Split Flow Tol= 0.02
Split Flow Ratio= 0.02
Log Output Level= 0
Friction Slope Method= 1
Unsteady Friction Slope Method= 2
Unsteady Bridges Friction Slope Method= 1
Parabolic Critical Depth
Global Vel Dist=  1 , 1 , 1
Global Log Level= 0
CheckData=True
Encroach Param= -1, 0, 0, 0
BEGIN DESCRIPTION:
Multiple Run
END DESCRIPTION:

--- Cottonwood Trib100_4.f01 (steady flow) ---

Flow Title=Multiple
Number of Profiles=7
Profile Names=10-year,25-year,50-year,1pct_min,100-year,1pct_plu,500-year
River Rch & RM= Cottonwood Trib1,Reach-1,13000
     256     362     451     279     557    1111     862
River Rch & RM= Cottonwood Trib1,Reach-1,10414
     334     476     596     371     740    1476    1155
River Rch & RM= Cottonwood Trib1,Reach-1,4500
     413     594     747     467     932    1859    1468
Boundary for River Rch & Prof#=Cottonwood Trib1,Reach-1,1
Up Type=0
Dn Type=3
Dn Slope=0.005
Boundary for River Rch & Prof#=Cottonwood Trib1,Reach-1,2
Up Type=0
Dn Type=3
Dn Slope=0.005
Boundary for River Rch & Prof#=Cottonwood Trib1,Reach-1,3
Up Type=0
Dn Type=3
Dn Slope=0.005
Boundary for River Rch & Prof#=Cottonwood Trib1,Reach-1,4
Up Type=0
Dn Type=3
Dn Slope=0.005
Boundary for River Rch & Prof#=Cottonwood Trib1,Reach-1,5
Up Type=0
Dn Type=3
Dn Slope=0.005
Boundary for River Rch & Prof#=Cottonwood Trib1,Reach-1,6
Up Type=0
Dn Type=3
Dn Slope=0.005
Boundary for River Rch & Prof#=Cottonwood Trib1,Reach-1,7
Up Type=0
Dn Type=3
Dn Slope=0.005

--- Cottonwood Trib100_4.g01 (geometry) ---

Geom Title=Existing Conditions

River Reach=Cottonwood Trib1,Reach-1
Reach XY= 30
      1353755.00      6939138.00      1353854.76      6938852.95
      1353706.50      6938743.95      1354055.50      6938117.77
      1353856.96      6937793.88      1354205.91      6937503.43
      1354097.00      6937031.61      1353812.83      6936934.79
      1353948.05      6936696.84      1354125.16      6936838.47
      1354305.39      6936717.63      1354301.58      6936289.56
      1354005.32      6935872.60      1354154.93      6935367.97
      1354058.34      6934939.72      1354302.30      6934543.36
      1355053.44      6934534.24      1355210.18      6934143.44
      1355682.14      6933961.56      1355605.12      6933508.37
      1355897.52      6933241.62      1355808.44      6932989.25
      1356153.50      6932781.61      1356012.30      6932588.08
      1356251.47      6931988.99      1356010.40      6931940.72
      1356104.99      6931603.41      1355961.19      6931395.75
      1355512.86      6931494.21      1355555.00      6931038.00

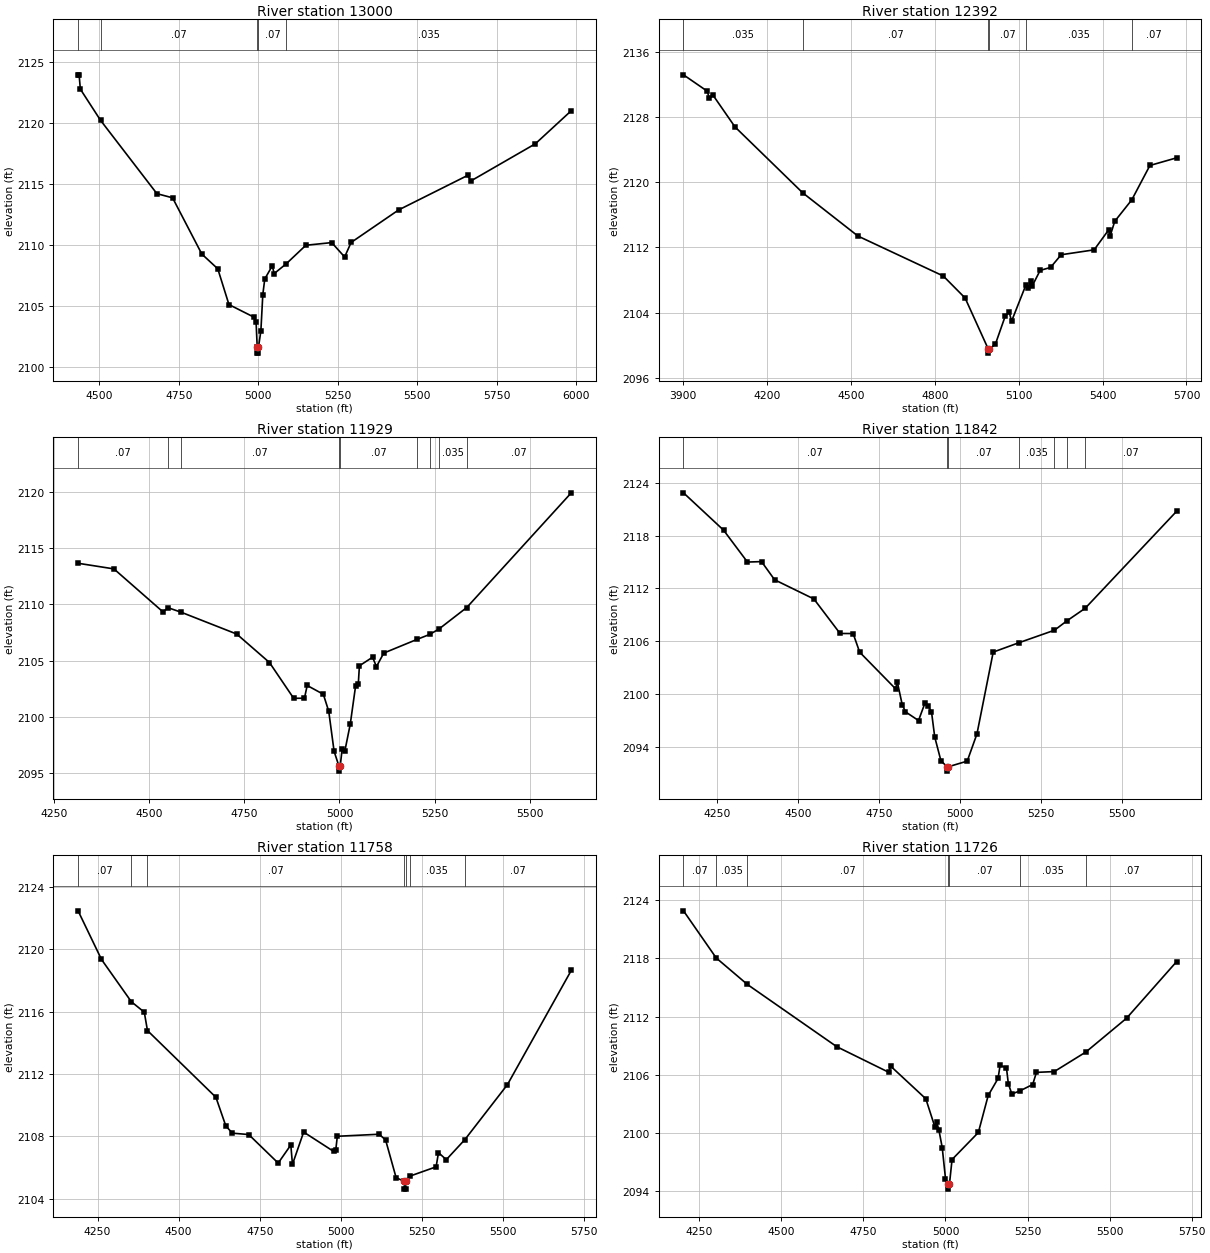
Type RM Length L Ch R = 1,13000,608,608,608
BEGIN DESCRIPTION:
Cottonwood Trib100_4 25.0
END DESCRIPTION:
XS GIS Cut Line= 4
      1354204.98      6939387.99      1353781.57      6939010.88
      1353728.92      6938974.39      1352823.94      6939140.74
#Sta/Elev= 30
  4433.0 2123.92  4436.3 2123.92  4440.1 2122.75  4503.7 2120.19  4680.9 2114.18
  4730.2 2113.84  4822.2 2109.23  4872.4 2108.02  4907.5 2105.09  4985.2 2104.07
  4992.8 2103.69  4996.4 2101.61  4996.7 2101.11  5000.2 2101.11  5000.4 2101.61
  5007.9 2102.92  5014.0 2105.91  5020.2 2107.19  5043.7 2108.26  5049.8 2107.63
  5087.6 2108.43  5149.4 2109.95  5230.7 2110.17  5271.4 2108.99  5291.7 2110.18
  5441.4 2112.85  5657.8 2115.67  5668.9 2115.23  5871.3 2118.27  5984.2 2120.98
#Mann=5,-1,0
  4433.0   0.035       0  4503.7    0.07       0  4996.4    0.07       0
  5000.4    0.07       0  5087.6   0.035       0
Bank Sta=4996.4,5000.4
Exp/Cntr=0.3,0.1

Type RM Length L Ch R = 1,12392,463,463,463
BEGIN DESCRIPTION:
Cottonwood Trib100_4 24.0
END DESCRIPTION:
XS GIS Cut Line= 3
      1354554.99      6939487.99      1353840.97      6938653.24
      1353254.96      6938337.98
#Sta/Elev= 30
  3901.1 2133.17  3986.2 2131.16  3993.2 2130.28  4007.0 2130.66  4085.3 2126.78
  4327.3 2118.70  4525.1 2113.39  4830.3 2108.49  4908.3 2105.79  4991.1 2099.53
  4991.4 2099.03  4995.1 2099.53  5016.6 2100.13  5051.8 2103.57  5066.1 2104.05
  5074.5 2102.95  5125.0 2107.33  5131.8 2106.96  5142.4 2107.86  5148.1 2107.26
  5176.7 2109.18  5213.8 2109.54  5251.9 2111.10  5369.7 2111.70  5421.5 2114.14
  5427.2 2113.42  5443.4 2115.20  5504.3 2117.83  5569.2 2122.05  5665.0 2122.99
#Mann=6,-1,0
  3901.1   0.035       0  4327.3    0.07       0  4991.1    0.07       0
  4995.1    0.07       0  5125.0   0.035       0  5504.3    0.07       0
Bank Sta=4991.1,4995.1
Exp/Cntr=0.3,0.1

Type RM Length L Ch R = 1,11929,87,87,87
BEGIN DESCRIPTION:
Cottonwood Trib100_4 23.0
END DESCRIPTION:
XS GIS Cut Line= 4
      1354357.99      6938795.36      1354079.38      6938395.04
      1353896.19      6938218.97      1353355.03      6938337.99
#Sta/Elev= 30
  4313.2 2113.66  4407.4 2113.16  4536.3 2109.34  4549.8 2109.71  4584.8 2109.30
  4730.1 2107.37  4816.1 2104.84  4879.7 2101.66  4908.0 2101.67  4915.2 2102.80
  4957.6 2102.02  4971.8 2100.51  4985.9 2096.95  4998.1 2095.69  4998.3 2095.19
  5002.1 2095.69  5007.0 2097.13  5014.2 2096.99  5028.4 2099.37  5042.5 2102.79
  5049.5 2102.94  5052.4 2104.55  5086.9 2105.31  5097.2 2104.48  5116.4 2105.68
  5203.3 2106.89  5237.3 2107.34  5261.9 2107.83  5334.5 2109.73  5609.1 2119.92
#Mann=9,-1,0
  4313.2    0.07       0  4549.8   0.035       0  4584.8    0.07       0
  4998.1    0.07       0  5002.1    0.07       0  5203.3   0.035       0
  5237.3    0.07       0  5261.9   0.035       0  5334.5    0.07       0
Bank Sta=4998.1,5002.1
Exp/Cntr=0.3,0.1

Type RM Length L Ch R = 1,11842,84,84,84
BEGIN DESCRIPTION:
Cottonwood Trib100_4 22.7
END DESCRIPTION:
XS GIS Cut Line= 4
      1354843.57      6938278.99      1354151.26      6938187.84
      1353874.33      6938202.24      1353353.66      6938363.31
#Sta/Elev= 30
  4147.7 2122.88  4271.3 2118.63  4344.9 2115.00  4388.3 2115.05  4428.7 2112.98
  4549.7 2110.80  4630.4 2106.87  4670.7 2106.86  4690.9 2104.74  4801.6 2100.57
  4806.7 2101.39  4822.0 2098.78  4832.1 2097.95  4872.3 2096.96  4892.3 2098.96
  4902.3 2098.59  4912.3 2097.96  4922.3 2095.09  4941.4 2092.38  4960.4 2091.70
  4960.6 2091.20  4964.4 2091.70  5022.5 2092.34  5052.5 2095.44  5102.6 2104.75
  5181.3 2105.81  5291.5 2107.24  5328.8 2108.28  5386.2 2109.74  5668.3 2120.79
#Mann=7,-1,0
  4147.7    0.07       0  4960.4    0.07       0  4964.4    0.07       0
  5181.3   0.035       0  5291.5    0.07       0  5328.8   0.035       0
  5386.2    0.07       0
Bank Sta=4960.4,4964.4
Exp/Cntr=0.3,0.1

Type RM Length L Ch R = 1,11758,32,32,32
BEGIN DESCRIPTION:
Cottonwood Trib100_4 22.6
END DESCRIPTION:
XS GIS Cut Line= 4
      1354856.58      6938219.09      1354164.28      6938127.94
      1353887.35      6938142.34      1353366.87      6938303.35
#Sta/Elev= 30
  4190.1 2122.46  4262.3 2119.34  4354.3 2116.63  4394.2 2115.96  4404.0 2114.78
  4615.0 2110.50  4645.6 2108.66  4665.8 2108.20  4716.2 2108.11  4807.0 2106.28
  4845.9 2107.44  4851.0 2106.20  4885.5 2108.27  4977.8 2107.03  4984.3 2107.09
  4989.3 2108.00  5118.0 2108.13  5138.0 2107.77  5170.6 2105.34  5196.0 2105.11
  5196.3 2104.61  5199.8 2104.61  5200.0 2105.11  5212.5 2105.44  5293.8 2106.04
  5301.1 2106.95  5325.2 2106.50  5382.6 2107.79  5513.6 2111.31  5710.5 2118.64
#Mann=7,-1,0
  4190.1    0.07       0  4354.3   0.035       0  4404.0    0.07       0
  5196.0    0.07       0  5200.0    0.07       0  5212.5   0.035       0
  5382.6    0.07       0
Bank Sta=5196,5200
Exp/Cntr=0.3,0.1

Type RM Length L Ch R = 1,11726,226,226,226
BEGIN DESCRIPTION:
Cottonwood Trib100_4 22.5
END DESCRIPTION:
XS GIS Cut Line= 4
      1354850.05      6938173.51      1354138.35      6938104.72
      1353887.35      6938096.77      1353385.19      6938286.37
#Sta/Elev= 30
  4201.6 2122.88  4301.3 2118.03  4396.3 2115.30  4668.8 2108.89  4827.6 2106.25
  4832.6 2106.90  4940.0 2103.53  4968.0 2100.60  4973.0 2101.15  4980.0 2100.30
  4990.0 2098.51  5000.0 2095.32  5008.0 2094.73  5008.3 2094.23  5012.0 2094.73
  5020.0 2097.28  5100.1 2100.06  5130.1 2103.87  5160.1 2105.62  5166.4 2106.98
  5185.8 2106.70  5191.6 2105.06  5202.3 2104.02  5228.2 2104.37  5265.7 2105.00
  5277.1 2106.25  5331.4 2106.33  5428.0 2108.35  5551.6 2111.82  5704.5 2117.66
#Mann=7,-1,0
  4201.6    0.07       0  4301.3   0.035       0  4396.3    0.07       0
  5008.0    0.07       0  5012.0    0.07       0  5228.2   0.035       0
  5428.0    0.07       0
Bank Sta=5008,5012
Exp/Cntr=0.3,0.1

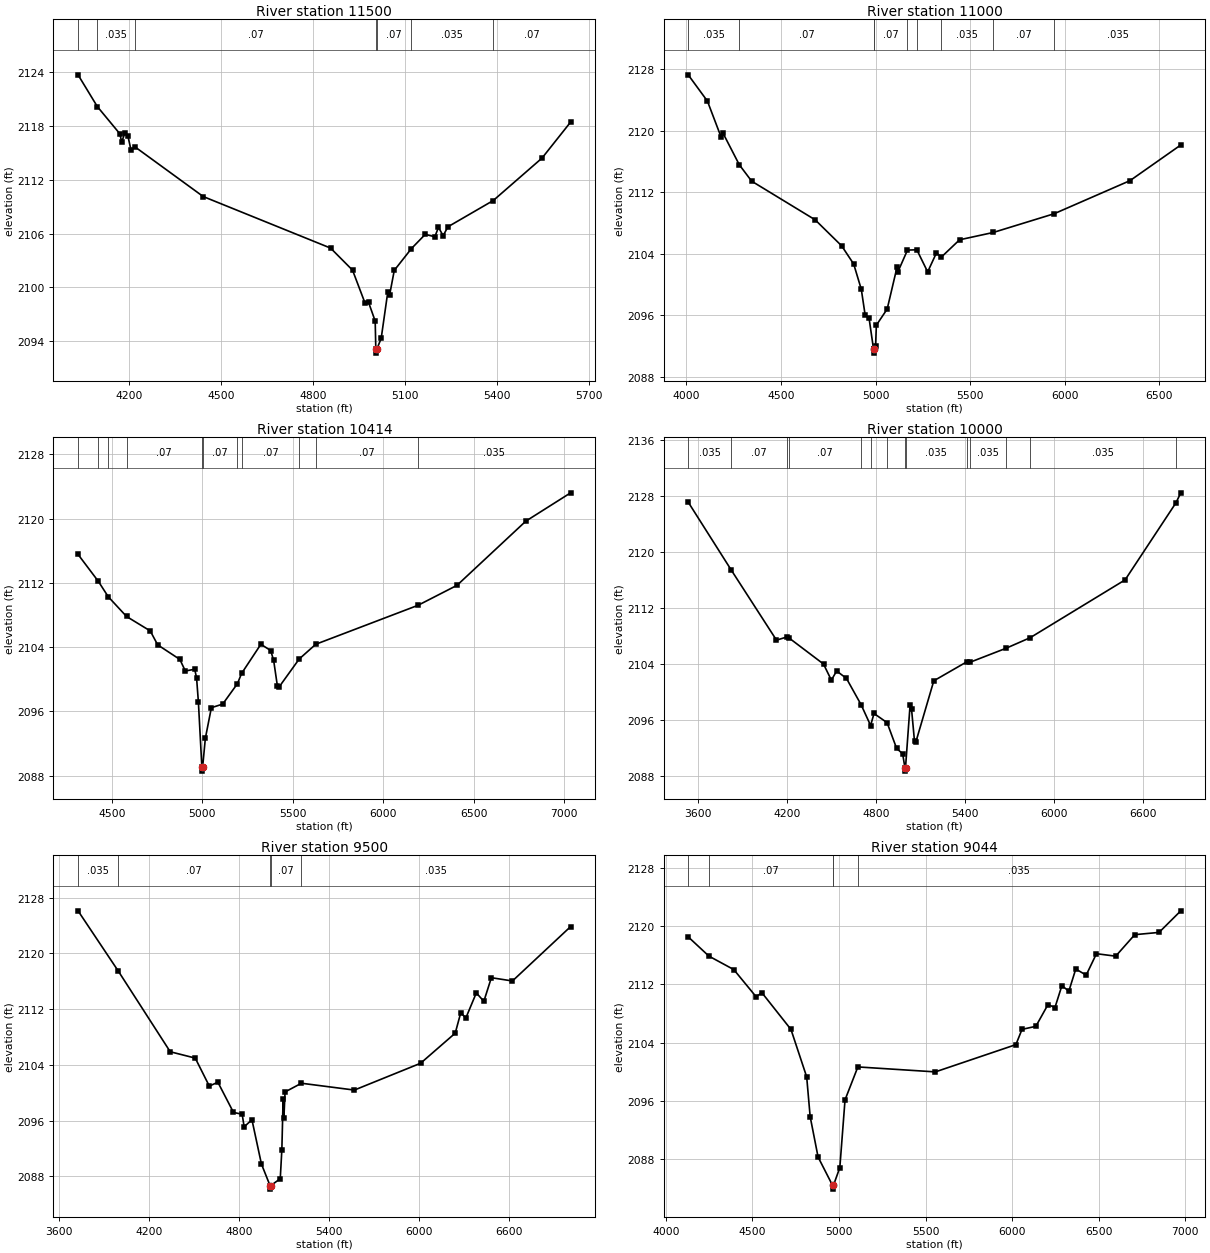
Type RM Length L Ch R = 1,11500,500,500,500
BEGIN DESCRIPTION:
Cottonwood Trib100_4 22.0
END DESCRIPTION:
XS GIS Cut Line= 3
      1354855.00      6938138.00      1353904.52      6937958.94
      1353355.01      6938287.99
#Sta/Elev= 30
  4032.8 2123.68  4095.8 2120.14  4169.0 2117.12  4175.3 2116.21  4185.4 2117.16
  4195.6 2116.83  4205.8 2115.30  4218.4 2115.66  4441.4 2110.12  4857.0 2104.38
  4928.7 2101.92  4969.0 2098.29  4981.1 2098.32  5002.6 2096.25  5004.6 2093.18
  5004.8 2092.68  5008.6 2093.18  5022.2 2094.33  5043.5 2099.44  5049.4 2099.11
  5064.9 2101.90  5121.0 2104.33  5166.0 2105.91  5197.2 2105.64  5209.2 2106.69
  5224.4 2105.76  5239.9 2106.75  5388.0 2109.68  5547.2 2114.41  5640.5 2118.42
#Mann=7,-1,0
  4032.8    0.07       0  4095.8   0.035       0  4218.4    0.07       0
  5004.6    0.07       0  5008.6    0.07       0  5121.0   0.035       0
  5388.0    0.07       0
Bank Sta=5004.6,5008.6
Exp/Cntr=0.3,0.1

Type RM Length L Ch R = 1,11000,586,586,586
BEGIN DESCRIPTION:
Cottonwood Trib100_4 21.0
END DESCRIPTION:
XS GIS Cut Line= 3
      1355054.97      6937788.00      1354081.02      6937611.60
      1352496.99      6937913.26
#Sta/Elev= 30
  4010.2 2127.28  4111.8 2123.86  4182.9 2119.25  4193.1 2119.74  4280.3 2115.57
  4345.5 2113.44  4680.9 2108.41  4821.0 2105.02  4884.6 2102.65  4924.8 2099.35
  4945.1 2096.00  4965.5 2095.64  4989.5 2091.56  4989.8 2091.06  4993.5 2091.56
  5000.0 2091.93  5004.3 2094.70  5061.5 2096.80  5113.7 2102.27  5118.8 2101.68
  5168.6 2104.47  5218.1 2104.51  5275.3 2101.63  5321.7 2104.11  5347.6 2103.56
  5443.9 2105.81  5621.3 2106.76  5943.4 2109.20  6344.3 2113.51  6612.5 2118.15
#Mann=9,-1,0
  4010.2   0.035       0  4280.3    0.07       0  4989.5    0.07       0
  4993.5    0.07       0  5168.6   0.035       0  5218.1    0.07       0
  5347.6   0.035       0  5621.3    0.07       0  5943.4   0.035       0
Bank Sta=4989.5,4993.5
Exp/Cntr=0.3,0.1

Type RM Length L Ch R = 1,10414,414,414,414
BEGIN DESCRIPTION:
Cottonwood Trib100_4 20.0
END DESCRIPTION:
XS GIS Cut Line= 5
      1354805.05      6937238.01      1354180.21      6937104.30
      1354081.78      6937133.47      1354023.44      6937212.64
      1352159.62      6937468.59
#Sta/Elev= 30
  4313.6 2115.54  4425.9 2112.18  4480.7 2110.26  4581.6 2107.81  4712.5 2106.01
  4753.4 2104.28  4876.1 2102.46  4906.3 2101.02  4958.0 2101.24  4968.4 2100.17
  4978.4 2097.17  4997.7 2089.05  4997.9 2088.55  5001.8 2089.05  5016.9 2092.64
  5050.1 2096.45  5112.8 2096.90  5194.3 2099.45  5216.9 2100.71  5323.6 2104.35
  5377.9 2103.57  5394.3 2102.33  5414.5 2099.21  5424.5 2099.04  5535.5 2102.52
  5626.9 2104.35  6191.6 2109.20  6407.2 2111.69  6787.2 2119.68  7034.9 2123.21
#Mann=11,-1,0
  4313.6   0.035       0  4425.9    0.07       0  4480.7   0.035       0
  4581.6    0.07       0  4997.7    0.07       0  5001.8    0.07       0
  5194.3   0.035       0  5216.9    0.07       0  5535.5   0.035       0
  5626.9    0.07       0  6191.6   0.035       0
Bank Sta=4997.7,5001.8
Exp/Cntr=0.3,0.1

Type RM Length L Ch R = 1,10000,500,500,500
BEGIN DESCRIPTION:
Cottonwood Trib100_4 19.0
END DESCRIPTION:
XS GIS Cut Line= 4
      1355260.38      6937267.70      1353982.92      6936946.30
      1353835.40      6936969.48      1351979.60      6937033.30
#Sta/Elev= 30
  3533.4 2127.14  3822.6 2117.46  4129.2 2107.38  4196.8 2107.82  4210.7 2107.74
  4446.4 2103.96  4499.2 2101.66  4535.2 2102.96  4601.0 2101.91  4700.2 2098.13
  4764.2 2095.16  4787.0 2096.88  4875.3 2095.57  4939.7 2091.88  4980.2 2091.12
  4995.6 2089.13  4995.9 2088.63  4999.7 2089.13  5030.4 2098.07  5040.4 2097.49
  5060.4 2092.88  5070.4 2092.87  5190.5 2101.56  5411.7 2104.26  5434.2 2104.21
  5676.9 2106.21  5840.7 2107.73  6481.3 2116.01  6824.3 2127.04  6856.9 2128.47
#Mann=14,-1,0
  3533.4   0.035       0  3822.6    0.07       0  4196.8   0.035       0
  4210.7    0.07       0  4700.2   0.035       0  4764.2    0.07       0
  4875.3   0.035       0  4995.6   0.035       0  4999.7   0.035       0
  5411.7    0.07       0  5434.2   0.035       0  5676.9    0.07       0
  5840.7   0.035       0  6824.3    0.07       0
Bank Sta=4995.6,4999.7
Exp/Cntr=0.3,0.1

Type RM Length L Ch R = 1,9500,456,456,456
BEGIN DESCRIPTION:
Cottonwood Trib100_4 18.0
END DESCRIPTION:
XS GIS Cut Line= 5
      1355244.70      6937241.64      1354135.36      6936908.32
      1354074.70      6936808.43      1354014.96      6936651.36
      1352178.53      6936455.35
#Sta/Elev= 30
  3724.8 2126.10  3994.5 2117.42  4340.5 2105.87  4507.6 2104.96  4601.6 2100.94
  4658.7 2101.50  4763.0 2097.16  4820.9 2096.90  4834.3 2095.09  4886.2 2096.12
  4949.6 2089.76  5007.2 2086.65  5007.6 2086.15  5011.8 2086.65  5075.4 2087.65
  5086.1 2091.83  5094.5 2099.13  5099.9 2096.43  5107.4 2100.10  5216.8 2101.35
  5570.3 2100.37  6012.8 2104.22  6244.1 2108.54  6281.3 2111.50  6314.5 2110.69
  6384.9 2114.32  6435.2 2113.11  6485.4 2116.50  6626.2 2116.03  7014.9 2123.84
#Mann=5,-1,0
  3724.8   0.035       0  3994.5    0.07       0  5007.2    0.07       0
  5011.8    0.07       0  5216.8   0.035       0
Bank Sta=5007.2,5011.8
Exp/Cntr=0.3,0.1

Type RM Length L Ch R = 1,9044,73,73,73
BEGIN DESCRIPTION:
Cottonwood Trib100_4 17.5
END DESCRIPTION:
XS GIS Cut Line= 3
      1355074.14      6936694.93      1354209.72      6936588.27
      1352239.73      6936462.15
#Sta/Elev= 30
  4128.7 2118.51  4248.3 2115.87  4392.1 2114.02  4520.8 2110.30  4554.4 2110.85
  4722.3 2105.81  4813.0 2099.31  4833.1 2093.86  4878.9 2088.31  4962.7 2084.41
  4963.1 2083.91  4967.4 2084.41  5004.5 2086.87  5034.5 2096.15  5108.6 2100.67
  5556.1 2099.99  6021.4 2103.73  6056.6 2105.82  6136.7 2106.24  6206.9 2109.23
  6246.9 2108.81  6287.0 2111.82  6327.1 2111.06  6367.2 2114.10  6427.3 2113.26
  6486.6 2116.20  6597.7 2115.86  6707.9 2118.81  6848.2 2119.12  6973.7 2122.08
#Mann=5,-1,0
  4128.7   0.035       0  4248.3    0.07       0  4962.7    0.07       0
  4967.4    0.07       0  5108.6   0.035       0
Bank Sta=4962.7,4967.4
Exp/Cntr=0.3,0.1

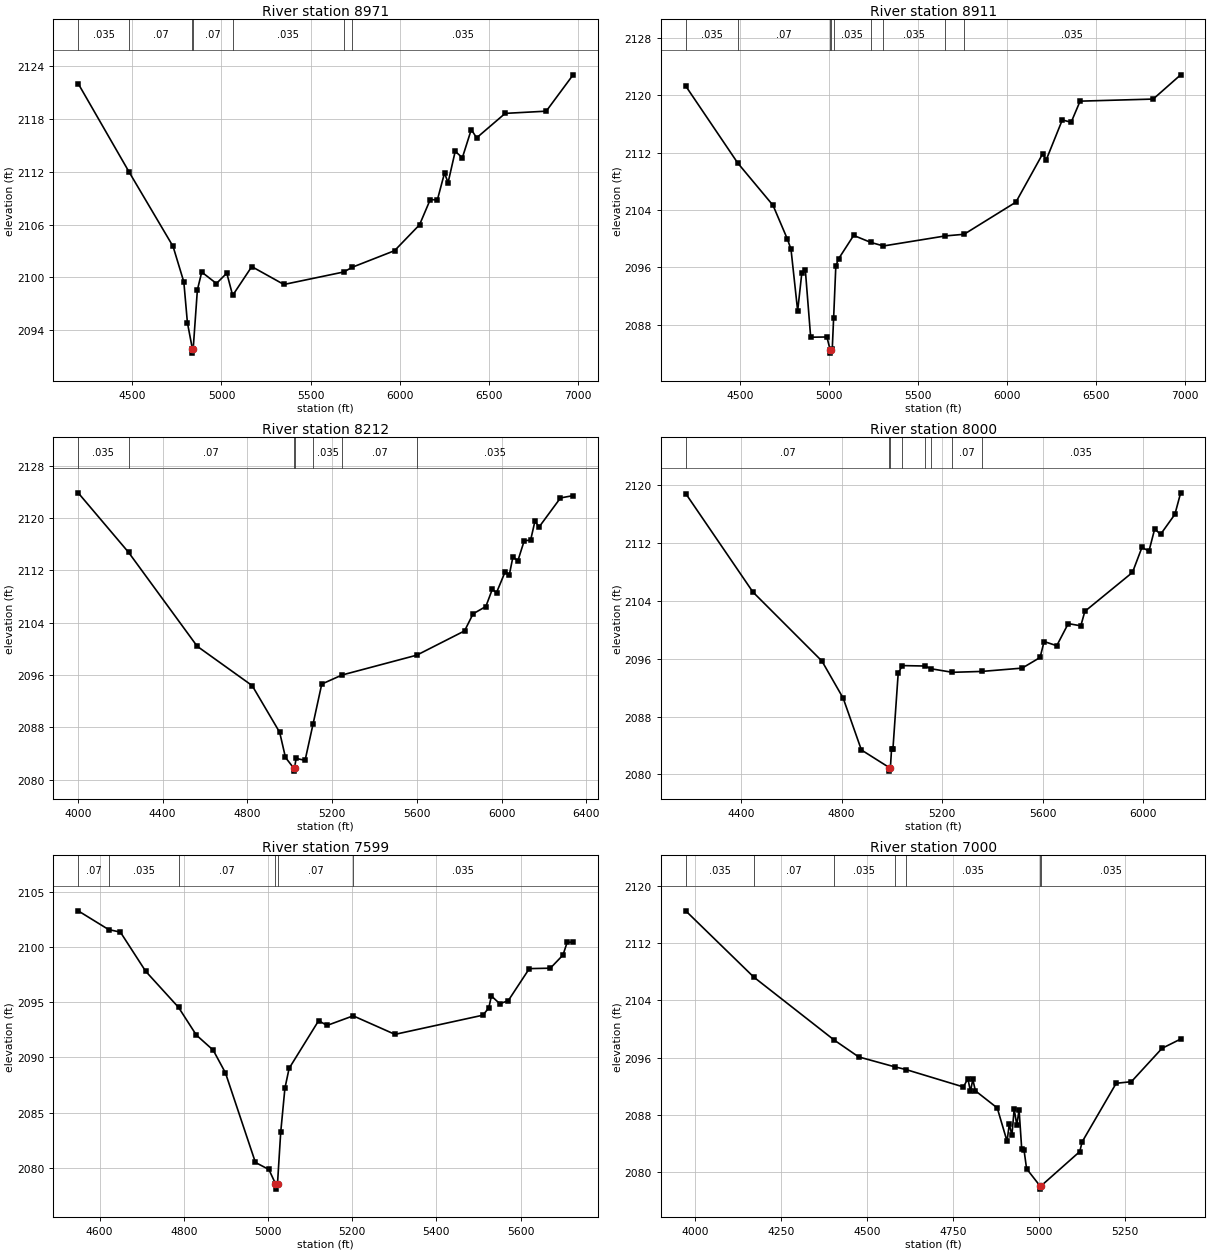
Type RM Length L Ch R = 1,8971,60,60,60
BEGIN DESCRIPTION:
Cottonwood Trib100_4 17.0
END DESCRIPTION:
XS GIS Cut Line= 3
      1355005.02      6936438.00      1354204.35      6936516.11
      1352234.32      6936418.73
#Sta/Elev= 30
  4195.9 2122.02  4481.9 2111.96  4728.4 2103.51  4788.7 2099.48  4808.8 2094.85
  4836.6 2091.89  4837.0 2091.39  4841.3 2091.89  4864.7 2098.57  4889.2 2100.60
  4971.5 2099.30  5029.8 2100.48  5062.6 2097.95  5169.9 2101.22  5350.1 2099.19
  5686.0 2100.61  5733.9 2101.15  5970.9 2103.03  6111.1 2105.97  6171.1 2108.83
  6211.2 2108.80  6251.2 2111.85  6271.3 2110.76  6311.3 2114.32  6351.4 2113.59
  6401.4 2116.79  6431.5 2115.85  6591.7 2118.63  6821.9 2118.88  6972.8 2123.01
#Mann=7,-1,0
  4195.9   0.035       0  4481.9    0.07       0  4836.6    0.07       0
  4841.3    0.07       0  5062.6   0.035       0  5686.0    0.07       0
  5733.9   0.035       0
Bank Sta=4836.6,4841.3
Exp/Cntr=0.3,0.1

Type RM Length L Ch R = 1,8911,699,699,699
BEGIN DESCRIPTION:
Cottonwood Trib100_4 16.5
END DESCRIPTION:
XS GIS Cut Line= 3
      1355001.53      6936349.46      1354201.04      6936456.32
      1352230.87      6936330.19
#Sta/Elev= 30
  4196.0 2121.30  4489.1 2110.54  4686.8 2104.66  4767.6 2099.95  4787.7 2098.55
  4825.2 2089.95  4848.3 2095.18  4868.4 2095.61  4898.3 2086.28  4989.5 2086.31
  5007.3 2084.56  5007.6 2084.06  5012.0 2084.56  5019.7 2084.69  5027.4 2088.99
  5039.7 2096.22  5055.2 2097.21  5139.9 2100.47  5237.0 2099.49  5307.4 2099.00
  5655.3 2100.40  5760.5 2100.63  6051.8 2105.11  6202.1 2111.84  6222.1 2111.00
  6312.5 2116.57  6362.4 2116.25  6412.5 2119.19  6823.3 2119.48  6977.8 2122.86
#Mann=9,-1,0
  4196.0   0.035       0  4489.1    0.07       0  5007.3    0.07       0
  5012.0    0.07       0  5027.4   0.035       0  5237.0    0.07       0
  5307.4   0.035       0  5655.3    0.07       0  5760.5   0.035       0
Bank Sta=5007.3,5012
Exp/Cntr=0.3,0.1

Type RM Length L Ch R = 1,8212,212,212,212
BEGIN DESCRIPTION:
Cottonwood Trib100_4 16.0
END DESCRIPTION:
XS GIS Cut Line= 3
      1355041.57      6936151.36      1354055.04      6935995.28
      1352725.68      6936144.42
#Sta/Elev= 30
  4001.5 2123.87  4239.2 2114.78  4563.4 2100.41  4823.0 2094.39  4952.8 2087.25
  4980.1 2083.41  5018.1 2081.82  5018.4 2081.32  5022.8 2081.82  5030.5 2083.26
  5072.7 2082.97  5110.8 2088.59  5151.3 2094.63  5246.6 2096.01  5599.9 2099.05
  5825.5 2102.76  5865.7 2105.37  5926.1 2106.49  5956.3 2109.11  5976.4 2108.61
  6016.7 2111.76  6036.8 2111.34  6054.0 2114.09  6077.1 2113.47  6107.2 2116.55
  6137.4 2116.64  6157.6 2119.51  6177.7 2118.66  6278.3 2123.09  6338.0 2123.44
#Mann=7,-1,0
  4001.5   0.035       0  4239.2    0.07       0  5018.1    0.07       0
  5022.8    0.07       0  5110.8   0.035       0  5246.6    0.07       0
  5599.9   0.035       0
Bank Sta=5018.1,5022.8
Exp/Cntr=0.3,0.1

Type RM Length L Ch R = 1,8000,401,401,401
BEGIN DESCRIPTION:
Cottonwood Trib100_4 15.0
END DESCRIPTION:
XS GIS Cut Line= 3
      1354805.04      6935988.01      1354006.70      6935799.47
      1353005.02      6935238.01
#Sta/Elev= 30
  4179.7 2118.85  4446.9 2105.23  4721.4 2095.68  4806.0 2090.54  4878.4 2083.38
  4989.0 2080.95  4989.4 2080.45  4993.9 2080.95  4998.3 2083.47  5003.8 2083.47
  5024.9 2094.03  5041.6 2095.05  5131.7 2094.99  5155.7 2094.61  5240.2 2094.12
  5356.2 2094.24  5517.8 2094.70  5589.1 2096.17  5605.1 2098.38  5655.4 2097.80
  5701.2 2100.86  5751.2 2100.55  5767.1 2102.55  5956.6 2107.94  5994.3 2111.40
  6022.2 2110.89  6045.2 2113.98  6068.1 2113.19  6125.4 2115.98  6148.3 2118.95
#Mann=8,-1,0
  4179.7    0.07       0  4989.0    0.07       0  4993.9    0.07       0
  5041.6   0.035       0  5131.7    0.07       0  5155.7   0.035       0
  5240.2    0.07       0  5356.2   0.035       0
Bank Sta=4989,4993.9
Exp/Cntr=0.3,0.1

Type RM Length L Ch R = 1,7599,599,599,599
BEGIN DESCRIPTION:
Cottonwood Trib100_4 14.0
END DESCRIPTION:
XS GIS Cut Line= 3
      1354555.02      6935488.00      1354106.04      6935456.21
      1353380.96      6935424.09
#Sta/Elev= 30
  4549.1 2103.29  4621.5 2101.59  4649.4 2101.36  4709.5 2097.81  4787.5 2094.54
  4829.8 2092.03  4869.9 2090.66  4899.0 2088.60  4970.2 2080.48  5002.2 2079.84
  5017.8 2078.56  5018.2 2078.06  5022.7 2078.56  5030.3 2083.21  5040.3 2087.21
  5050.3 2089.01  5120.4 2093.33  5140.4 2092.90  5202.5 2093.77  5301.7 2092.09
  5510.7 2093.83  5524.7 2094.49  5530.8 2095.57  5550.8 2094.87  5570.8 2095.14
  5620.9 2098.05  5670.9 2098.09  5700.9 2099.28  5710.9 2100.44  5725.0 2100.45
#Mann=6,-1,0
  4549.1    0.07       0  4621.5   0.035       0  4787.5    0.07       0
  5017.8    0.07       0  5022.7    0.07       0  5202.5   0.035       0
Bank Sta=5017.8,5022.7
Exp/Cntr=0.3,0.1

Type RM Length L Ch R = 1,7000,500,500,500
BEGIN DESCRIPTION:
Cottonwood Trib100_4 13.0
END DESCRIPTION:
XS GIS Cut Line= 3
      1354855.04      6935588.03      1354079.45      6934913.31
      1353704.96      6934737.98
#Sta/Elev= 30
  3972.0 2116.47  4170.2 2107.23  4404.4 2098.45  4475.7 2096.10  4580.3 2094.72
  4613.2 2094.34  4780.6 2091.91  4793.8 2093.05  4801.4 2091.29  4808.1 2092.96
  4815.7 2091.37  4879.3 2088.98  4907.8 2084.35  4914.4 2086.70  4922.0 2085.16
  4928.6 2088.82  4936.3 2086.62  4942.9 2088.73  4950.5 2083.30  4957.1 2083.18
  4964.8 2080.50  5003.0 2078.16  5003.4 2077.66  5008.1 2078.16  5119.7 2082.90
  5126.4 2084.24  5225.7 2092.42  5269.9 2092.64  5359.1 2097.29  5413.5 2098.59
#Mann=7,-1,0
  3972.0   0.035       0  4170.2    0.07       0  4404.4   0.035       0
  4580.3    0.07       0  4613.2   0.035       0  5003.0   0.035       0
  5008.1   0.035       0
Bank Sta=5003,5008.1
Exp/Cntr=0.3,0.1

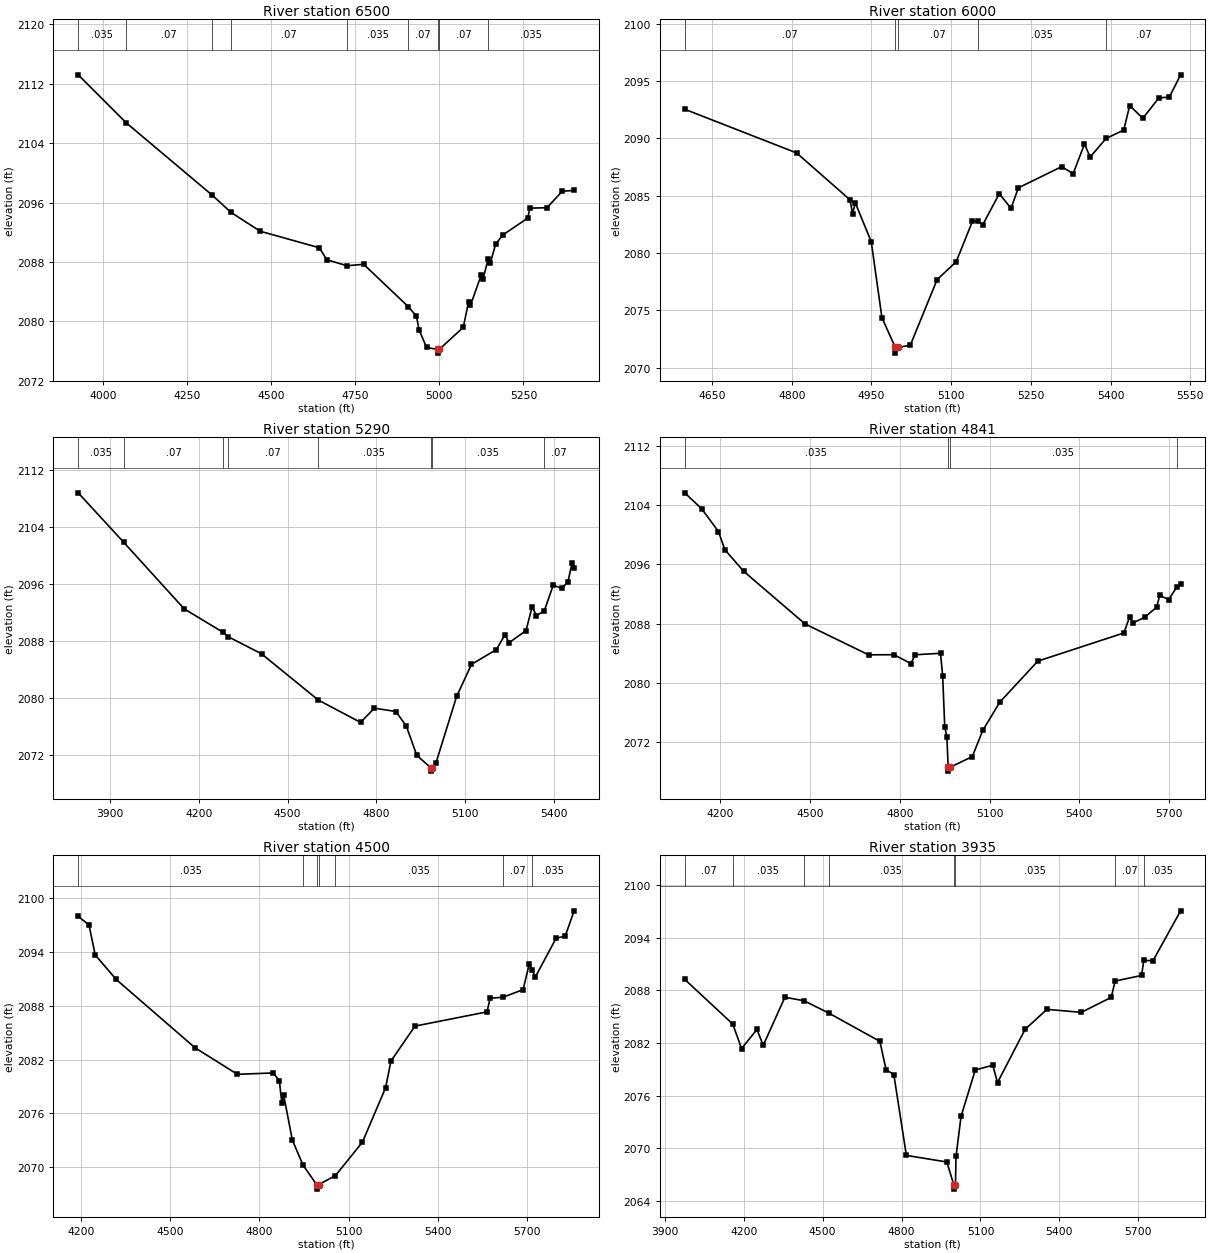
Type RM Length L Ch R = 1,6500,500,500,500
BEGIN DESCRIPTION:
Cottonwood Trib100_4 12.0
END DESCRIPTION:
XS GIS Cut Line= 3
      1354854.98      6935487.97      1354352.91      6934537.53
      1354004.97      6934337.98
#Sta/Elev= 30
  3925.1 2113.21  4067.3 2106.77  4324.6 2096.96  4380.0 2094.66  4466.6 2092.13
  4642.8 2089.90  4664.8 2088.29  4725.0 2087.48  4774.8 2087.67  4907.9 2081.94
  4931.6 2080.70  4939.6 2078.84  4961.7 2076.47  4994.4 2076.20  4994.8 2075.70
  4999.5 2076.20  5071.0 2079.17  5086.8 2082.58  5092.5 2082.14  5124.2 2086.18
  5129.9 2085.70  5145.7 2088.45  5151.5 2087.83  5167.3 2090.37  5188.9 2091.63
  5262.7 2093.89  5269.5 2095.24  5320.4 2095.30  5365.8 2097.53  5401.1 2097.62
#Mann=9,-1,0
  3925.1   0.035       0  4067.3    0.07       0  4324.6   0.035       0
  4380.0    0.07       0  4725.0   0.035       0  4907.9    0.07       0
  4994.4    0.07       0  4999.5    0.07       0  5145.7   0.035       0
Bank Sta=4994.4,4999.5
Exp/Cntr=0.3,0.1

Type RM Length L Ch R = 1,6000,710,710,710
BEGIN DESCRIPTION:
Cottonwood Trib100_4 11.0
END DESCRIPTION:
XS GIS Cut Line= 3
      1354805.00      6934988.00      1354836.75      6934587.76
      1354655.00      6934087.99
#Sta/Elev= 30
  4598.5 2092.53  4809.2 2088.72  4909.5 2084.64  4914.5 2083.43  4919.6 2084.37
  4949.6 2080.98  4969.7 2074.36  4994.8 2071.77  4995.2 2071.27  5000.0 2071.77
  5023.1 2071.96  5073.6 2077.68  5109.5 2079.24  5140.1 2082.77  5151.2 2082.77
  5159.4 2082.46  5190.6 2085.17  5212.6 2083.89  5226.5 2085.68  5307.7 2087.52
  5329.6 2086.92  5350.9 2089.50  5361.5 2088.36  5391.4 2089.98  5424.7 2090.71
  5436.0 2092.85  5460.6 2091.74  5491.2 2093.53  5510.5 2093.58  5531.8 2095.53
#Mann=5,-1,0
  4598.5    0.07       0  4994.8    0.07       0  5000.0    0.07       0
  5151.2   0.035       0  5391.4    0.07       0
Bank Sta=4994.8,5000
Exp/Cntr=0.3,0.1

Type RM Length L Ch R = 1,5290,449,449,449
BEGIN DESCRIPTION:
Cottonwood Trib100_4 10.0
END DESCRIPTION:
XS GIS Cut Line= 4
      1355555.00      6935287.99      1355307.57      6934265.53
      1355209.92      6934146.17      1354855.02      6933838.02
#Sta/Elev= 30
  3792.4 2108.76  3946.3 2101.83  4150.6 2092.52  4281.7 2089.24  4299.0 2088.63
  4411.9 2086.23  4603.4 2079.77  4746.6 2076.63  4793.5 2078.62  4866.3 2078.15
  4901.5 2076.10  4936.7 2072.01  4983.6 2070.31  4984.0 2069.81  4988.9 2070.31
  5001.0 2070.88  5071.3 2080.26  5121.6 2084.75  5206.0 2086.83  5234.5 2088.89
  5248.8 2087.79  5305.8 2089.47  5326.6 2092.80  5340.9 2091.59  5367.3 2092.20
  5397.9 2095.83  5426.4 2095.39  5447.3 2096.26  5461.5 2098.93  5468.6 2098.17
#Mann=8,-1,0
  3792.4   0.035       0  3946.3    0.07       0  4281.7   0.035       0
  4299.0    0.07       0  4603.4   0.035       0  4983.6   0.035       0
  4988.9   0.035       0  5367.3    0.07       0
Bank Sta=4983.6,4988.9
Exp/Cntr=0.3,0.1

Type RM Length L Ch R = 1,4841,341,341,341
BEGIN DESCRIPTION:
Cottonwood Trib100_4 9.0
END DESCRIPTION:
XS GIS Cut Line= 4
      1356254.98      6934687.98      1355672.59      6934082.37
      1355419.99      6933834.97      1354954.97      6933838.00
#Sta/Elev= 30
  4080.3 2105.65  4136.7 2103.52  4193.3 2100.43  4214.7 2097.97  4278.2 2095.04
  4483.3 2087.95  4695.5 2083.79  4780.4 2083.81  4837.0 2082.61  4851.2 2083.80
  4936.0 2084.00  4943.2 2080.96  4950.1 2074.12  4957.3 2072.71  4961.6 2068.60
  4962.0 2068.10  4967.0 2068.60  5042.2 2070.06  5077.4 2073.59  5134.0 2077.39
  5261.3 2082.94  5549.1 2086.74  5569.1 2088.95  5579.1 2088.09  5619.1 2088.86
  5659.1 2090.23  5669.1 2091.80  5699.1 2091.25  5726.7 2092.95  5739.1 2093.38
#Mann=4,-1,0
  4080.3   0.035       0  4961.6   0.035       0  4967.0   0.035       0
  5726.7    0.07       0
Bank Sta=4961.6,4967
Exp/Cntr=0.3,0.1

Type RM Length L Ch R = 1,4500,565,565,565
BEGIN DESCRIPTION:
Cottonwood Trib100_4 8.0
END DESCRIPTION:
XS GIS Cut Line= 3
      1356255.03      6934388.04      1355754.67      6933752.45
      1354905.04      6933638.01
#Sta/Elev= 30
  4191.1 2097.98  4227.3 2097.04  4248.1 2093.69  4318.6 2090.95  4583.3 2083.33
  4725.7 2080.36  4846.2 2080.51  4867.0 2079.63  4875.1 2077.11  4881.5 2078.02
  4910.4 2073.03  4946.3 2070.23  4992.2 2068.04  4992.7 2067.54  4998.4 2068.04
  5055.3 2069.05  5145.9 2072.78  5223.7 2078.85  5241.8 2081.84  5322.6 2085.74
  5564.7 2087.33  5574.8 2088.85  5617.6 2088.96  5685.8 2089.81  5706.0 2092.63
  5717.1 2092.04  5726.2 2091.18  5796.8 2095.56  5827.1 2095.78  5857.3 2098.61
#Mann=7,-1,0
  4191.1   0.035       0  4946.3    0.07       0  4992.2    0.07       0
  4998.4    0.07       0  5055.3   0.035       0  5617.6    0.07       0
  5717.1   0.035       0
Bank Sta=4992.2,4998.4
Exp/Cntr=0.3,0.1

Type RM Length L Ch R = 1,3935,435,435,435
BEGIN DESCRIPTION:
Cottonwood Trib100_4 7.0
END DESCRIPTION:
XS GIS Cut Line= 4
      1356655.01      6933688.00      1355710.35      6933294.61
      1355673.89      6933281.59      1354918.66      6933607.86
#Sta/Elev= 30
  3975.9 2089.26  4158.7 2084.16  4192.1 2081.38  4250.6 2083.55  4274.4 2081.74
  4356.8 2087.22  4429.4 2086.82  4522.7 2085.43  4717.6 2082.20  4741.4 2078.96
  4770.7 2078.42  4818.4 2069.21  4972.2 2068.46  4998.6 2065.87  4999.1 2065.37
  5004.9 2065.87  5007.1 2069.10  5026.1 2073.65  5080.3 2078.94  5146.7 2079.48
  5164.8 2077.51  5269.7 2083.57  5352.6 2085.84  5483.3 2085.50  5597.0 2087.21
  5611.6 2089.06  5712.1 2089.70  5720.8 2091.41  5755.7 2091.38  5860.6 2097.06
#Mann=8,-1,0
  3975.9    0.07       0  4158.7   0.035       0  4429.4    0.07       0
  4522.7   0.035       0  4998.6   0.035       0  5004.9   0.035       0
  5611.6    0.07       0  5720.8   0.035       0
Bank Sta=4998.6,5004.9
Exp/Cntr=0.3,0.1

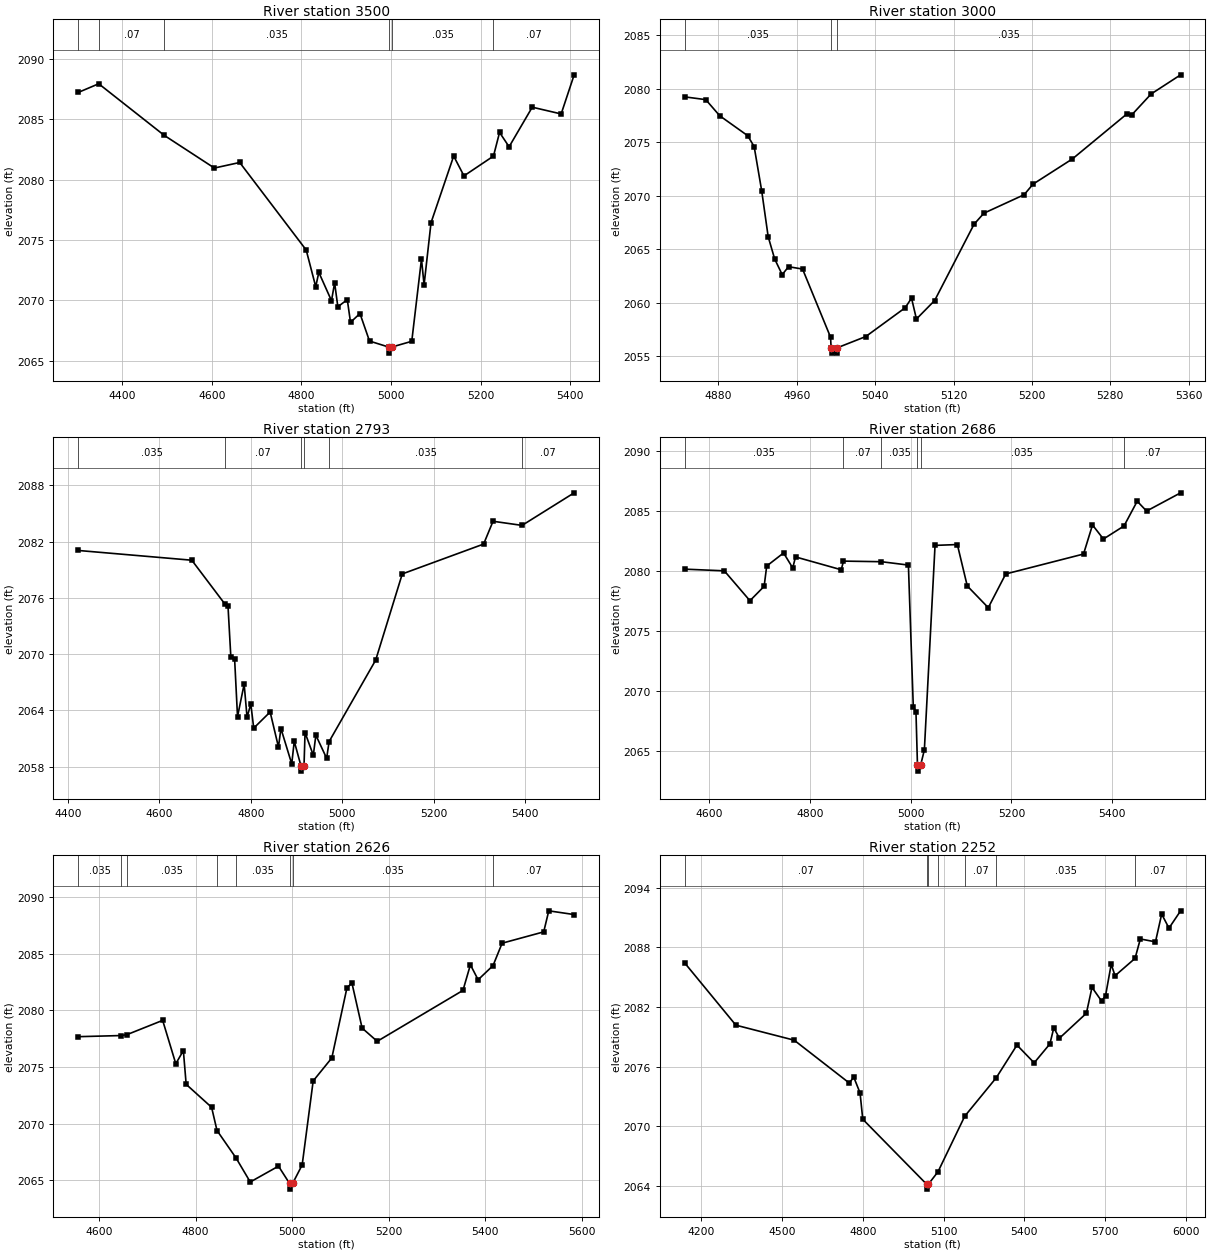
Type RM Length L Ch R = 1,3500,500,500,500
BEGIN DESCRIPTION:
Cottonwood Trib100_4 6.0
END DESCRIPTION:
XS GIS Cut Line= 3
      1356305.00      6933538.00      1355804.52      6933050.45
      1355455.02      6932838.01
#Sta/Elev= 30
  4301.3 2087.22  4347.1 2087.94  4493.3 2083.67  4605.4 2080.96  4662.0 2081.42
  4810.5 2074.17  4831.8 2071.13  4838.7 2072.32  4867.0 2069.97  4874.0 2071.45
  4881.2 2069.47  4902.3 2070.06  4909.5 2068.18  4930.6 2068.91  4951.9 2066.63
  4995.0 2066.13  4995.5 2065.63  5001.3 2066.13  5046.3 2066.61  5068.0 2073.42
  5073.8 2071.28  5089.3 2076.43  5139.9 2081.95  5162.9 2080.31  5228.8 2081.95
  5242.4 2083.91  5263.7 2082.72  5315.4 2086.00  5380.0 2085.44  5409.0 2088.68
#Mann=6,-1,0
  4301.3   0.035       0  4347.1    0.07       0  4493.3   0.035       0
  4995.0   0.035       0  5001.3   0.035       0  5228.8    0.07       0
Bank Sta=4995,5001.3
Exp/Cntr=0.3,0.1

Type RM Length L Ch R = 1,3000,207,207,207
BEGIN DESCRIPTION:
Cottonwood Trib100_4 5.0
END DESCRIPTION:
XS GIS Cut Line= 3
      1356255.03      6932888.03      1356155.27      6932770.19
      1355805.04      6932738.00
#Sta/Elev= 30
  4845.6 2079.23  4867.1 2078.97  4881.4 2077.46  4909.9 2075.60  4916.5 2074.58
  4924.2 2070.44  4930.8 2066.16  4937.4 2064.08  4945.1 2062.61  4951.6 2063.35
  4965.9 2063.13  4994.5 2056.75  4995.0 2055.77  4995.5 2055.27  5000.8 2055.27
  5001.3 2055.77  5030.4 2056.82  5070.6 2059.51  5077.1 2060.41  5082.1 2058.46
  5100.7 2060.19  5140.9 2067.32  5150.9 2068.35  5192.0 2070.08  5201.1 2071.07
  5241.3 2073.43  5296.8 2077.63  5301.8 2077.54  5321.6 2079.50  5351.7 2081.29
#Mann=3,-1,0
  4845.6   0.035       0  4995.0   0.035       0  5001.3   0.035       0
Bank Sta=4995,5001.3
Exp/Cntr=0.3,0.1

Type RM Length L Ch R = 1,2793,107,107,107
BEGIN DESCRIPTION:
Cottonwood Trib100_4 4.7
END DESCRIPTION:
XS GIS Cut Line= 5
      1356440.28      6933010.54      1356195.49      6932687.61
      1356040.97      6932621.64      1355905.55      6932599.07
      1355542.71      6932687.61
#Sta/Elev= 30
  4423.0 2081.05  4671.3 2080.01  4743.8 2075.33  4750.4 2075.12  4756.6 2069.71
  4764.9 2069.45  4771.2 2063.34  4785.7 2066.81  4792.0 2063.29  4800.3 2064.69
  4806.6 2062.12  4842.5 2063.84  4860.7 2060.11  4866.1 2062.08  4889.7 2058.31
  4895.2 2060.72  4910.2 2058.04  4910.7 2057.54  4916.5 2058.04  4918.8 2061.64
  4936.9 2059.23  4942.4 2061.37  4966.0 2058.91  4971.4 2060.69  5073.2 2069.37
  5131.3 2078.55  5309.1 2081.73  5329.7 2084.16  5393.1 2083.72  5507.0 2087.19
#Mann=6,-1,0
  4423.0   0.035       0  4743.8    0.07       0  4910.2   0.035       0
  4916.5    0.07       0  4971.4   0.035       0  5393.1    0.07       0
Bank Sta=4910.2,4916.5
Exp/Cntr=0.3,0.1

Type RM Length L Ch R = 1,2686,60,60,60
BEGIN DESCRIPTION:
Cottonwood Trib100_4 4.6
END DESCRIPTION:
XS GIS Cut Line= 5
      1356319.72      6932825.39      1356283.27      6932631.85
      1356168.29      6932577.05      1355966.43      6932506.85
      1355553.22      6932676.99
#Sta/Elev= 30
  4551.1 2080.18  4629.8 2080.04  4680.7 2077.55  4708.9 2078.75  4714.0 2080.44
  4747.5 2081.53  4765.7 2080.28  4771.2 2081.20  4862.0 2080.13  4866.5 2080.85
  4941.8 2080.80  4995.4 2080.52  5005.1 2068.71  5010.4 2068.31  5013.4 2063.85
  5013.9 2063.35  5019.7 2063.85  5027.1 2065.12  5048.3 2082.16  5092.6 2082.23
  5112.3 2078.78  5154.0 2076.97  5188.7 2079.78  5343.2 2081.44  5361.0 2083.86
  5382.7 2082.69  5423.6 2083.78  5449.8 2085.84  5468.4 2085.02  5536.0 2086.54
#Mann=6,-1,0
  4551.1   0.035       0  4866.5    0.07       0  4941.8   0.035       0
  5013.4   0.035       0  5019.7   0.035       0  5423.6    0.07       0
Bank Sta=5013.4,5019.7
Exp/Cntr=0.3,0.1

Type RM Length L Ch R = 1,2626,374,374,374
BEGIN DESCRIPTION:
Cottonwood Trib100_4 4.5
END DESCRIPTION:
XS GIS Cut Line= 4
      1356447.31      6932703.89      1356064.52      6932478.20
      1356011.56      6932471.30      1355504.65      6932625.77
#Sta/Elev= 30
  4556.7 2077.68  4645.6 2077.78  4657.7 2077.86  4731.7 2079.12  4758.9 2075.29
  4774.6 2076.45  4780.4 2073.47  4833.1 2071.44  4844.3 2069.39  4883.8 2066.96
  4913.2 2064.84  4971.7 2066.24  4994.7 2064.71  4995.2 2064.21  5001.0 2064.71
  5020.8 2066.35  5043.6 2073.77  5082.2 2075.80  5113.6 2082.00  5123.9 2082.42
  5145.0 2078.44  5176.3 2077.27  5354.0 2081.77  5369.4 2084.03  5385.4 2082.71
  5416.3 2083.96  5435.1 2085.94  5521.3 2086.94  5531.8 2088.80  5584.4 2088.47
#Mann=8,-1,0
  4556.7   0.035       0  4645.6    0.07       0  4657.7   0.035       0
  4844.3    0.07       0  4883.8   0.035       0  4994.7   0.035       0
  5001.0   0.035       0  5416.3    0.07       0
Bank Sta=4994.7,5001
Exp/Cntr=0.3,0.1

Type RM Length L Ch R = 1,2252,252,252,252
BEGIN DESCRIPTION:
Cottonwood Trib100_4 4.0
END DESCRIPTION:
XS GIS Cut Line= 4
      1357104.99      6932288.00      1356476.95      6932171.31
      1356043.36      6932181.73      1355428.78      6932641.44
#Sta/Elev= 30
  4139.5 2086.42  4329.4 2080.16  4545.7 2078.65  4749.8 2074.35  4767.0 2074.92
  4790.2 2073.34  4800.2 2070.70  5036.9 2064.17  5037.4 2063.67  5043.8 2064.17
  5079.4 2065.42  5178.5 2071.00  5295.7 2074.88  5372.3 2078.16  5436.1 2076.37
  5494.4 2078.27  5509.0 2079.89  5529.9 2078.85  5629.9 2081.36  5650.7 2083.96
  5686.2 2082.59  5700.8 2083.10  5722.0 2086.29  5736.2 2085.13  5810.5 2086.88
  5830.0 2088.83  5886.2 2088.54  5909.2 2091.33  5936.3 2089.92  5979.5 2091.66
#Mann=7,-1,0
  4139.5    0.07       0  5036.9    0.07       0  5043.8    0.07       0
  5079.4   0.035       0  5178.5    0.07       0  5295.7   0.035       0
  5810.5    0.07       0
Bank Sta=5036.9,5043.8
Exp/Cntr=0.3,0.1