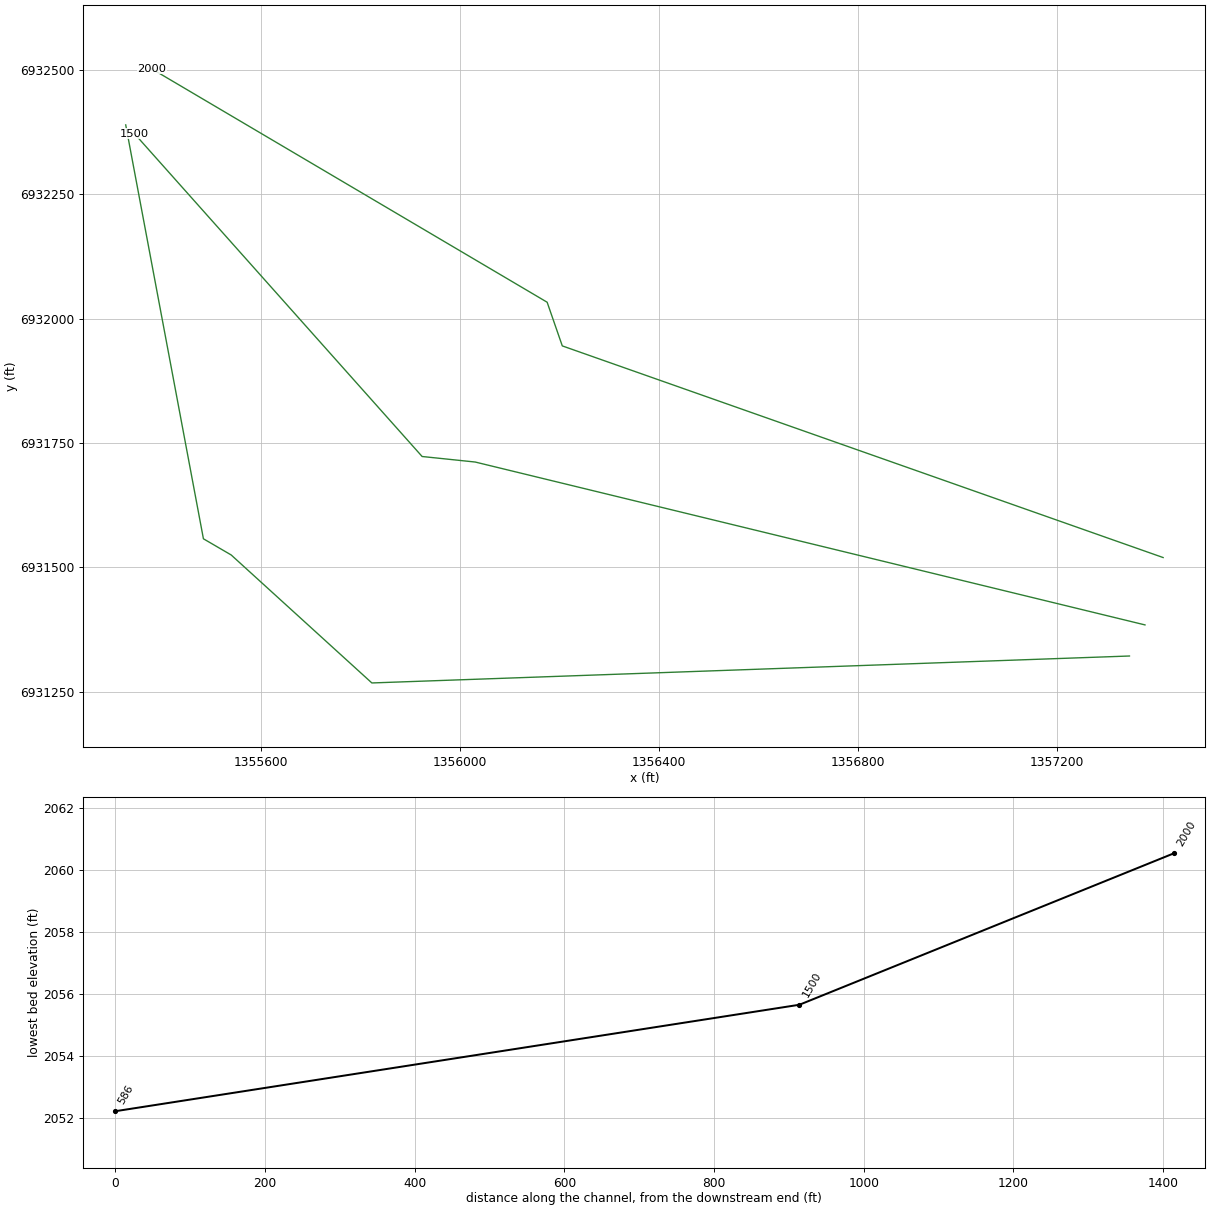
HEC-RAS study Cottonwood Trib100_4.prj: Cottonwood Trib100_4 Base Level Engineering

--- Cottonwood Trib100_4.g01 (geometry) --- (continued)

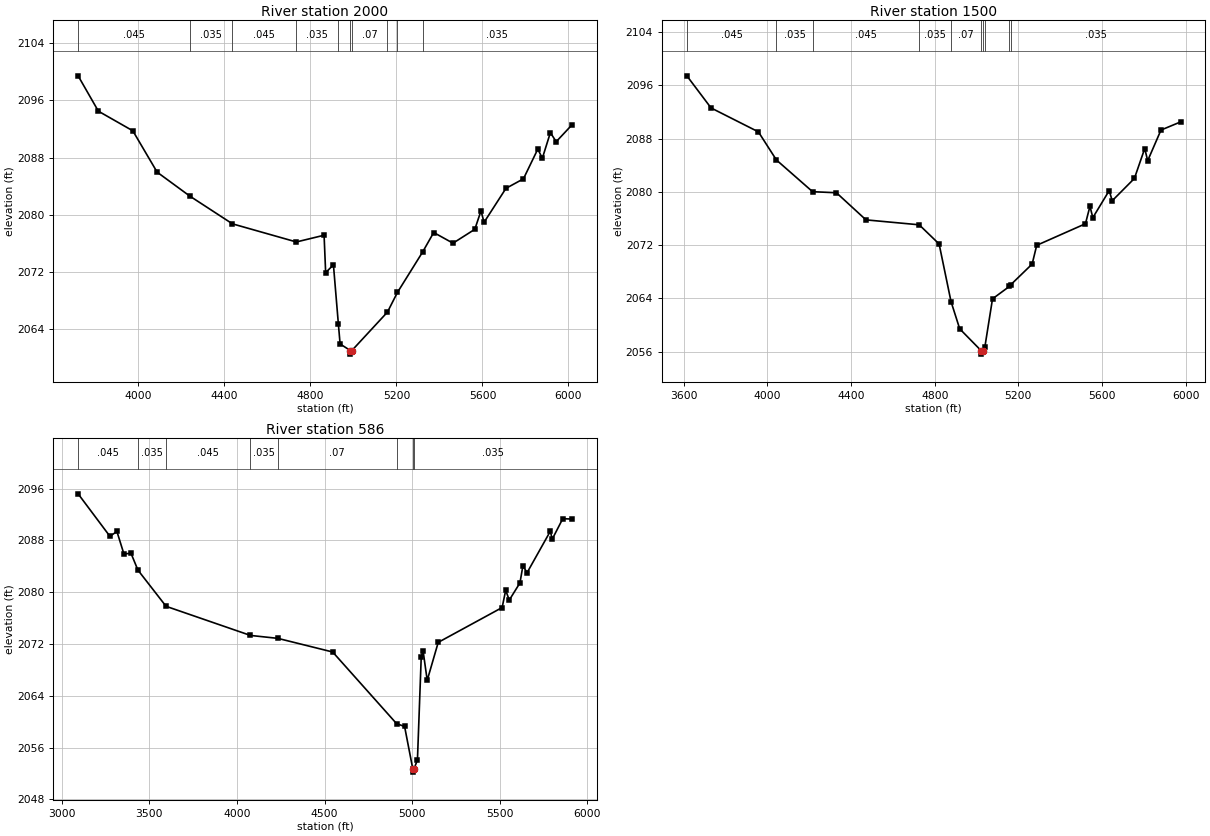
Type RM Length L Ch R = 1,2000,500,500,500
BEGIN DESCRIPTION:
Cottonwood Trib100_4 3.0
END DESCRIPTION:
XS GIS Cut Line= 4
      1357413.94      6931519.90      1356206.18      6931945.33
      1356175.71      6932033.12      1355380.62      6932502.43
#Sta/Elev= 30
  3719.5 2099.42  3813.8 2094.48  3973.9 2091.74  4087.1 2085.96  4238.9 2082.62
  4437.3 2078.74  4734.5 2076.21  4863.4 2077.15  4870.7 2071.93  4906.9 2073.01
  4929.9 2064.73  4937.9 2061.96  4985.7 2061.04  4986.2 2060.54  4992.6 2061.04
  5158.0 2066.41  5204.7 2069.17  5321.7 2074.81  5373.2 2077.53  5463.0 2076.04
  5564.4 2077.98  5593.1 2080.56  5607.3 2078.95  5709.2 2083.70  5790.5 2085.03
  5857.1 2089.17  5878.6 2087.92  5915.7 2091.48  5942.9 2090.22  6016.2 2092.57
#Mann=10,-1,0
  3719.5   0.045       0  4238.9   0.035       0  4437.3   0.045       0
  4734.5   0.035       0  4929.9    0.07       0  4985.7    0.07       0
  4992.6    0.07       0  5158.0   0.035       0  5204.7    0.07       0
  5321.7   0.035       0
Bank Sta=4985.7,4992.6
Exp/Cntr=0.3,0.1

Type RM Length L Ch R = 1,1500,914,914,914
BEGIN DESCRIPTION:
Cottonwood Trib100_4 2.0
END DESCRIPTION:
XS GIS Cut Line= 4
      1357377.49      6931384.48      1356031.13      6931711.88
      1355924.41      6931723.01      1355345.95      6932372.18
#Sta/Elev= 30
  3614.4 2097.42  3730.1 2092.60  3956.6 2089.01  4042.8 2084.79  4215.8 2080.03
  4329.9 2079.87  4471.2 2075.80  4725.8 2075.06  4821.1 2072.18  4878.0 2063.54
  4919.5 2059.45  5022.8 2056.15  5023.3 2055.65  5029.7 2056.15  5040.1 2056.76
  5076.5 2063.95  5157.6 2065.82  5165.0 2066.10  5266.1 2069.17  5287.9 2071.98
  5521.1 2075.22  5542.6 2077.85  5556.3 2076.13  5634.8 2080.20  5649.0 2078.67
  5755.2 2082.02  5804.6 2086.51  5818.8 2084.68  5882.3 2089.28  5976.8 2090.51
#Mann=10,-1,0
  3614.4   0.045       0  4042.8   0.035       0  4215.8   0.045       0
  4725.8   0.035       0  4878.0    0.07       0  5022.8    0.07       0
  5029.7    0.07       0  5040.1   0.035       0  5157.6    0.07       0
  5165.0   0.035       0
Bank Sta=5022.8,5029.7
Exp/Cntr=0.3,0.1

Type RM Length L Ch R = 1,586,0,0,0
BEGIN DESCRIPTION:
Cottonwood Trib100_4 1.0
END DESCRIPTION:
XS GIS Cut Line= 5
      1357346.29      6931321.97      1355823.37      6931267.80
      1355540.58      6931525.08      1355484.79      6931557.59
      1355328.57      6932389.58
#Sta/Elev= 30
  3094.3 2095.21  3275.7 2088.65  3315.7 2089.39  3355.8 2085.90  3395.8 2086.04
  3435.4 2083.43  3596.1 2077.83  4077.6 2073.33  4233.3 2072.88  4546.5 2070.77
  4910.7 2059.71  4956.8 2059.26  5003.5 2052.71  5004.0 2052.21  5010.5 2052.71
  5030.1 2054.11  5051.7 2070.01  5062.1 2070.99  5085.8 2066.39  5148.6 2072.26
  5513.2 2077.64  5533.5 2080.31  5553.9 2078.79  5614.9 2081.45  5631.6 2084.08
  5655.6 2083.03  5787.9 2089.42  5799.3 2088.22  5859.1 2091.37  5911.6 2091.31
#Mann=8,-1,0
  3094.3   0.045       0  3435.4   0.035       0  3596.1   0.045       0
  4077.6   0.035       0  4233.3    0.07       0  4910.7   0.035       0
  5003.5   0.035       0  5010.5   0.035       0
Bank Sta=5003.5,5010.5
Exp/Cntr=0.3,0.1

Chan Stop Cuts=-1