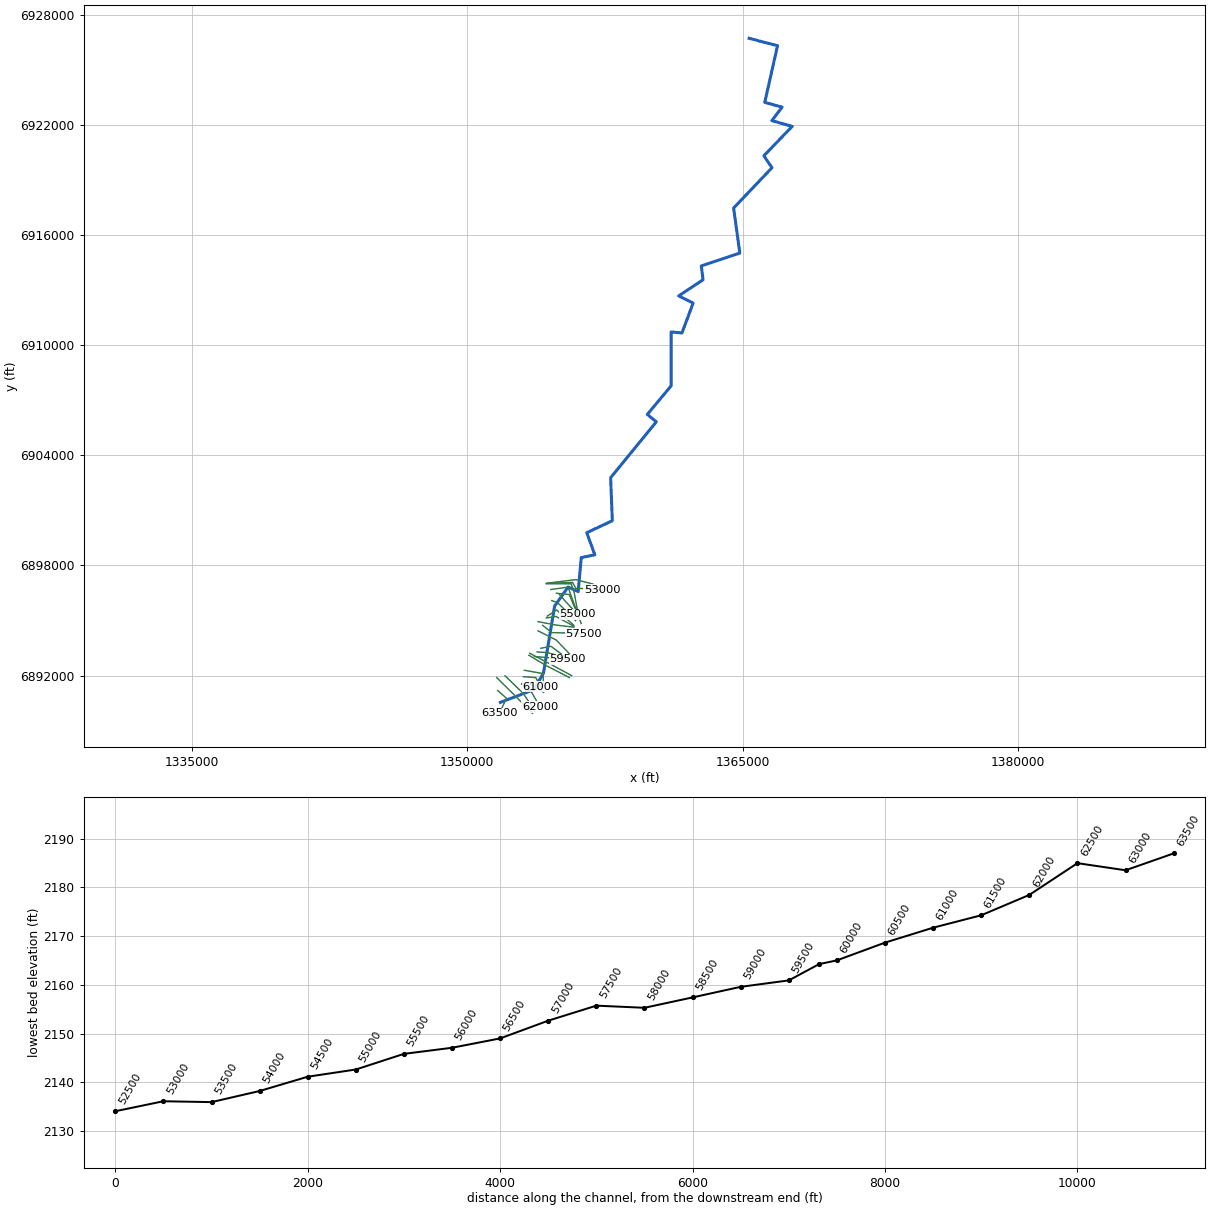
--- East Cottonwood Creek.prj (project) ---

Proj Title=East Cottonwood Creek Base Level Engineering
Current Plan=p01
Default Exp/Contr=0.3,0.1
English Units
Geom File=g01
Flow File=f01
Plan File=p01
BEGIN DESCRIPTION:
East Cottonwood Creek
END DESCRIPTION:

--- East Cottonwood Creek.p01 (plan) ---

Plan Title=Multiple Run
Short Identifier=Multiple
Geom File=g01
Flow File=f01
Subcritical Flow
K Sum by GR= 0
Std Step Tol= 0.01
Critical Tol= 0.01
Num of Std Step Trials= 20
Max Error Tol= 0.3
Flow Tol Ratio= 0.001
Split Flow NTrial= 30
Split Flow Tol= 0.02
Split Flow Ratio= 0.02
Log Output Level= 0
Friction Slope Method= 1
Unsteady Friction Slope Method= 2
Unsteady Bridges Friction Slope Method= 1
Parabolic Critical Depth
Global Vel Dist=  1 , 1 , 1
Global Log Level= 0
CheckData=True
Encroach Param= -1, 0, 0, 0
BEGIN DESCRIPTION:
Multiple Run
END DESCRIPTION:

--- East Cottonwood Creek.f01 (steady flow) ---

Flow Title=Multiple
Number of Profiles=7
Profile Names=10-year,25-year,50-year,1pct_min,100-year,1pct_plu,500-year
River Rch & RM= East Cottonwood ,Reach-1,63500
     315     455     576     362     723    1443    1156
River Rch & RM= East Cottonwood ,Reach-1,62500
     400     584     744     472     941    1877    1524
River Rch & RM= East Cottonwood ,Reach-1,59815
     551     819    1054     674    1344    2682    2218
River Rch & RM= East Cottonwood ,Reach-1,57000
     646     964    1245     798    1591    3175    2638
River Rch & RM= East Cottonwood ,Reach-1,53000
     678    1013    1309     839    1675    3342    2781
River Rch & RM= East Cottonwood ,Reach-1,52000
     786    1179    1529     983    1961    3912    3271
River Rch & RM= East Cottonwood ,Reach-1,48000
     892    1346    1749    1127    2249    4487    3771
River Rch & RM= East Cottonwood ,Reach-1,45000
     954    1440    1872    1207    2407    4804    4038
River Rch & RM= East Cottonwood ,Reach-1,41000
    1083    1640    2137    1380    2753    5494    4635
River Rch & RM= East Cottonwood ,Reach-1,36500
    1218    1849    2416    1562    3117    6219    5263
River Rch & RM= East Cottonwood ,Reach-1,32499
    1327    2015    2631    1700    3392    6767    5718
River Rch & RM= East Cottonwood ,Reach-1,23768
    1444    2194    2865    1850    3692    7367    6221
River Rch & RM= East Cottonwood ,Reach-1,15500
    1454    2207    2882    1861    3713    7407    6250
River Rch & RM= East Cottonwood ,Reach-1,12675
    1869    2858    3749    2431    4851    9679    8235
River Rch & RM= East Cottonwood ,Reach-1,6000
    1891    2887    3785    2452    4891    9760    8286
Boundary for River Rch & Prof#=East Cottonwood ,Reach-1,1
Up Type=0
Dn Type=3
Dn Slope=0.005
Boundary for River Rch & Prof#=East Cottonwood ,Reach-1,2
Up Type=0
Dn Type=3
Dn Slope=0.005
Boundary for River Rch & Prof#=East Cottonwood ,Reach-1,3
Up Type=0
Dn Type=3
Dn Slope=0.005
Boundary for River Rch & Prof#=East Cottonwood ,Reach-1,4
Up Type=0
Dn Type=3
Dn Slope=0.005
Boundary for River Rch & Prof#=East Cottonwood ,Reach-1,5
Up Type=0
Dn Type=3
Dn Slope=0.005
Boundary for River Rch & Prof#=East Cottonwood ,Reach-1,6
Up Type=0
Dn Type=3
Dn Slope=0.005
Boundary for River Rch & Prof#=East Cottonwood ,Reach-1,7
Up Type=0
Dn Type=3
Dn Slope=0.005

--- East Cottonwood Creek.g01 (geometry) ---

Geom Title=Existing Conditions

River Reach=East Cottonwood ,Reach-1
Reach XY= 30
      1351805.00      6890538.00      1353647.30      6891241.51
      1354149.66      6892135.26      1354758.12      6895786.37
      1355494.94      6896826.93      1356041.47      6896574.61
      1356208.40      6898429.56      1356947.24      6898584.58
      1356508.46      6899786.50      1357901.97      6900439.39
      1357808.75      6902786.45      1360297.24      6905831.83
      1359808.47      6906236.49      1361101.88      6907789.62
      1361107.25      6910732.07      1361694.54      6910678.17
      1362305.04      6912307.98      1361514.38      6912694.59
      1362844.72      6913577.84      1362748.83      6914330.22
      1364847.14      6915031.81      1364508.75      6917486.45
      1366597.19      6919681.81      1366158.74      6920336.48
      1367701.54      6921939.50      1366591.68      6922251.37
      1367151.34      6922986.45      1366206.04      6923248.42
      1366901.90      6926336.35      1365355.00      6926738.00

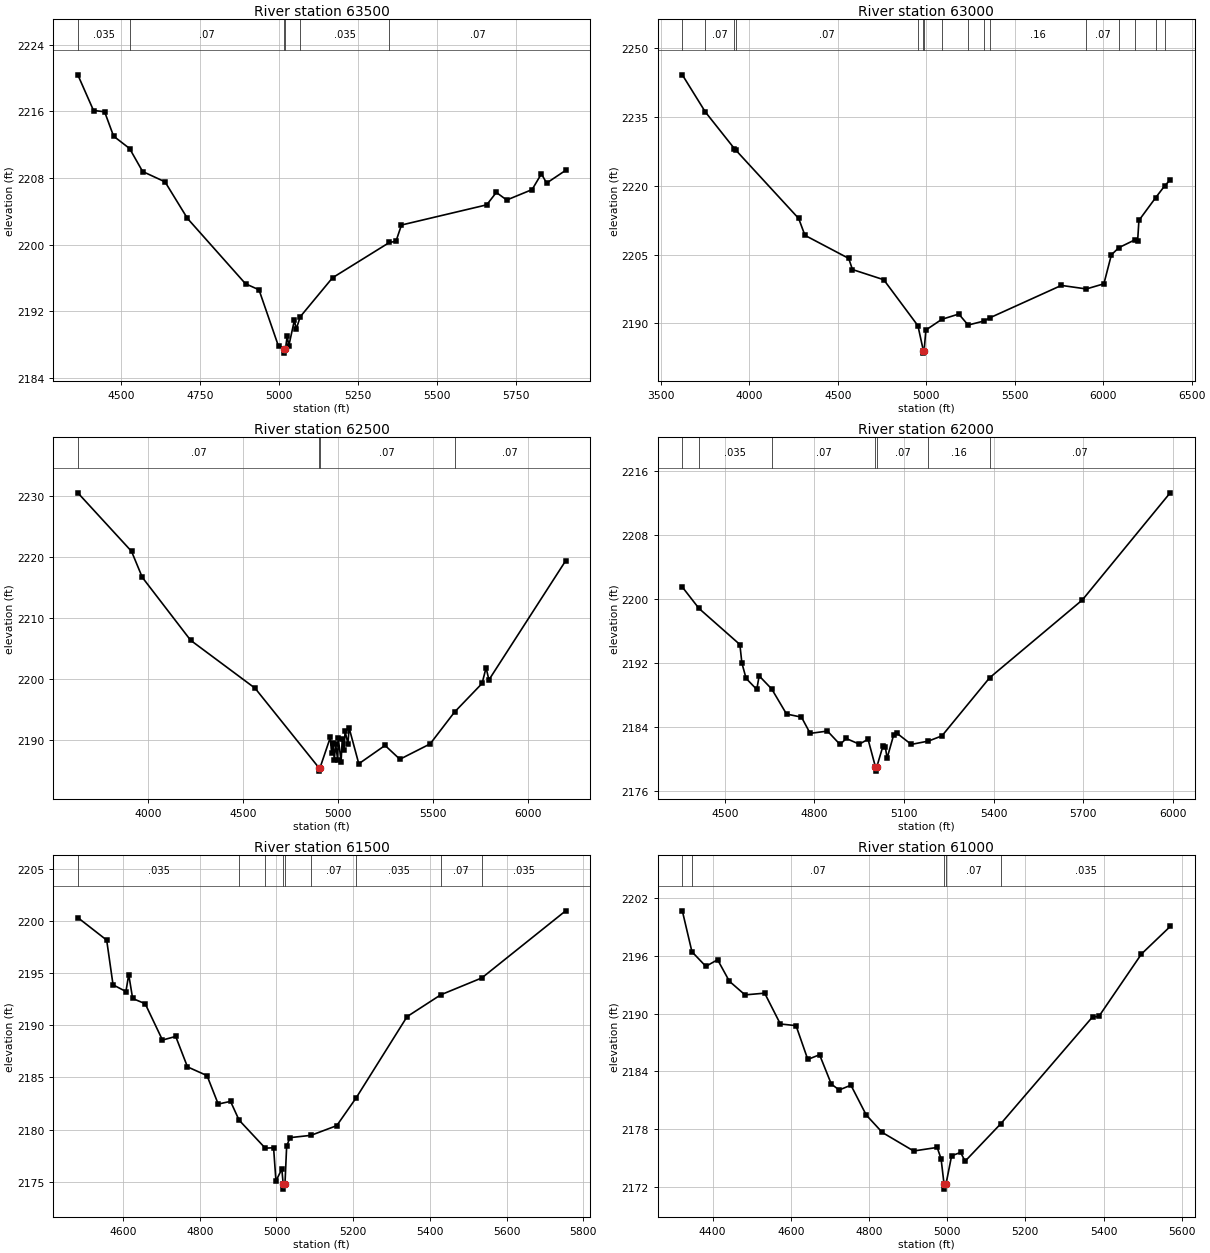
Type RM Length L Ch R = 1,63500,500,500,500
BEGIN DESCRIPTION:
East Cottonwood Creek 124.0
END DESCRIPTION:
XS GIS Cut Line= 3
      1351654.97      6891188.03      1352131.64      6890765.17
      1351754.99      6889937.99
#Sta/Elev= 30
  4362.8 2220.37  4412.6 2216.09  4447.7 2215.94  4476.2 2213.01  4526.9 2211.53
  4568.2 2208.77  4639.2 2207.53  4710.3 2203.14  4894.3 2195.30  4937.0 2194.58
  4998.9 2187.80  5016.9 2187.48  5017.1 2186.98  5020.9 2187.48  5026.2 2189.00
  5031.7 2187.89  5049.3 2190.95  5054.8 2189.85  5067.8 2191.35  5170.0 2196.02
  5350.4 2200.26  5371.0 2200.39  5388.5 2202.35  5658.6 2204.77  5689.1 2206.26
  5722.1 2205.35  5802.4 2206.60  5832.0 2208.49  5848.5 2207.38  5908.9 2208.91
#Mann=6,-1,0
  4362.8   0.035       0  4526.9    0.07       0  5016.9    0.07       0
  5020.9    0.07       0  5067.8   0.035       0  5350.4    0.07       0
Bank Sta=5016.9,5020.9
Exp/Cntr=0.3,0.1

Type RM Length L Ch R = 1,63000,500,500,500
BEGIN DESCRIPTION:
East Cottonwood Creek 123.0
END DESCRIPTION:
XS GIS Cut Line= 3
      1351604.97      6891888.03      1352583.49      6890916.07
      1353555.02      6889937.98
#Sta/Elev= 30
  3620.8 2244.18  3751.0 2236.08  3914.7 2228.12  3921.9 2227.82  4278.5 2212.87
  4313.8 2209.20  4561.3 2204.17  4582.5 2201.74  4759.3 2199.52  4952.6 2189.49
  4983.6 2184.02  4983.8 2183.52  4987.6 2184.02  4997.5 2188.55  5087.2 2190.88
  5183.5 2192.04  5236.5 2189.64  5324.3 2190.50  5358.7 2191.21  5763.4 2198.28
  5904.8 2197.51  6003.8 2198.63  6046.2 2204.95  6088.7 2206.51  6180.0 2208.23
  6194.7 2208.04  6201.8 2212.44  6295.8 2217.37  6346.7 2219.94  6378.6 2221.29
#Mann=16,-1,0
  3620.8    0.16       0  3751.0    0.07       0  3914.7    0.16       0
  3921.9    0.07       0  4952.6   0.035       0  4983.6   0.035       0
  4987.6   0.035       0  5087.2    0.07       0  5236.5    0.16       0
  5324.3    0.07       0  5358.7    0.16       0  5904.8    0.07       0
  6088.7   0.035       0  6180.0    0.07       0  6295.8   0.035       0
  6346.7    0.07       0
Bank Sta=4983.6,4987.6
Exp/Cntr=0.3,0.1

Type RM Length L Ch R = 1,62500,500,500,500
BEGIN DESCRIPTION:
East Cottonwood Creek 122.0
END DESCRIPTION:
XS GIS Cut Line= 3
      1352054.97      6891988.03      1353039.66      6891037.68
      1353704.97      6890038.04
#Sta/Elev= 30
  3631.5 2230.46  3914.4 2220.90  3971.0 2216.65  4225.7 2206.36  4565.0 2198.53
  4902.5 2185.48  4902.8 2184.98  4906.6 2185.48  4961.2 2190.48  4968.1 2187.90
  4975.3 2189.60  4982.3 2186.81  4989.5 2189.36  5000.0 2186.85  5003.1 2190.37
  5018.1 2186.55  5024.2 2190.22  5033.2 2188.38  5039.2 2191.49  5054.2 2189.43
  5060.2 2192.06  5111.3 2186.18  5249.6 2189.18  5327.7 2186.92  5487.0 2189.43
  5615.5 2194.63  5760.5 2199.31  5781.6 2201.88  5796.6 2199.89  6200.8 2219.36
#Mann=4,-1,0
  3631.5    0.07       0  4902.5   0.035       0  4906.6    0.07       0
  5615.5    0.07       0
Bank Sta=4902.5,4906.6
Exp/Cntr=0.3,0.1

Type RM Length L Ch R = 1,62000,500,500,500
BEGIN DESCRIPTION:
East Cottonwood Creek 121.0
END DESCRIPTION:
XS GIS Cut Line= 3
      1352955.01      6891538.00      1353470.43      6891153.73
      1353954.99      6890288.02
#Sta/Elev= 30
  4357.1 2201.49  4413.0 2198.81  4550.0 2194.30  4556.7 2191.99  4570.8 2190.07
  4606.6 2188.68  4614.6 2190.38  4656.7 2188.74  4706.3 2185.61  4756.4 2185.22
  4785.6 2183.19  4843.5 2183.48  4885.7 2181.80  4906.5 2182.55  4950.3 2181.84
  4979.5 2182.46  5004.5 2178.97  5004.8 2178.47  5008.6 2178.97  5029.5 2181.61
  5037.6 2181.45  5043.4 2180.09  5065.1 2182.96  5075.3 2183.24  5124.4 2181.81
  5182.1 2182.23  5227.2 2182.88  5386.9 2190.14  5697.6 2199.87  5992.1 2213.27
#Mann=7,-1,0
  4357.1    0.07       0  4413.0   0.035       0  4656.7    0.07       0
  5004.5    0.07       0  5008.6    0.07       0  5182.1    0.16       0
  5386.9    0.07       0
Bank Sta=5004.5,5008.6
Exp/Cntr=0.3,0.1

Type RM Length L Ch R = 1,61500,500,500,500
BEGIN DESCRIPTION:
East Cottonwood Creek 120.0
END DESCRIPTION:
XS GIS Cut Line= 3
      1353004.98      6891588.00      1353512.42      6891482.92
      1354154.97      6891088.02
#Sta/Elev= 30
  4481.8 2200.34  4557.1 2198.18  4573.7 2193.89  4607.3 2193.25  4614.6 2194.88
  4624.8 2192.58  4657.5 2192.08  4702.6 2188.59  4737.1 2188.94  4767.8 2186.02
  4818.8 2185.18  4848.0 2182.45  4880.1 2182.71  4902.4 2180.91  4970.7 2178.22
  4992.4 2178.26  4998.6 2175.07  5013.9 2176.22  5017.4 2174.79  5017.8 2174.29
  5022.1 2174.79  5026.5 2178.42  5035.2 2179.23  5089.9 2179.45  5157.1 2180.38
  5208.2 2183.07  5340.6 2190.84  5428.3 2192.93  5535.4 2194.55  5754.2 2200.99
#Mann=9,-1,0
  4481.8   0.035       0  4902.4    0.07       0  4970.7    0.16       0
  5017.4    0.07       0  5022.1    0.16       0  5089.9    0.07       0
  5208.2   0.035       0  5428.3    0.07       0  5535.4   0.035       0
Bank Sta=5017.4,5022.1
Exp/Cntr=0.3,0.1

Type RM Length L Ch R = 1,61000,500,500,500
BEGIN DESCRIPTION:
East Cottonwood Creek 119.0
END DESCRIPTION:
XS GIS Cut Line= 3
      1353055.00      6891938.00      1353730.46      6891888.03
      1354004.98      6891388.04
#Sta/Elev= 30
  4322.7 2200.71  4347.3 2196.45  4382.9 2194.93  4412.9 2195.62  4443.0 2193.38
  4483.1 2191.96  4533.3 2192.14  4573.4 2188.93  4613.5 2188.76  4643.6 2185.24
  4673.7 2185.73  4703.7 2182.68  4723.8 2182.06  4753.9 2182.56  4793.0 2179.46
  4834.1 2177.64  4914.3 2175.71  4974.5 2176.08  4984.5 2174.89  4992.1 2172.24
  4992.5 2171.74  4996.9 2172.24  5011.4 2175.21  5034.3 2175.56  5046.0 2174.65
  5137.7 2178.57  5371.9 2189.67  5387.9 2189.71  5497.0 2196.22  5570.4 2199.08
#Mann=5,-1,0
  4322.7   0.035       0  4347.3    0.07       0  4992.1    0.07       0
  4996.9    0.07       0  5137.7   0.035       0
Bank Sta=4992.1,4996.9
Exp/Cntr=0.3,0.1

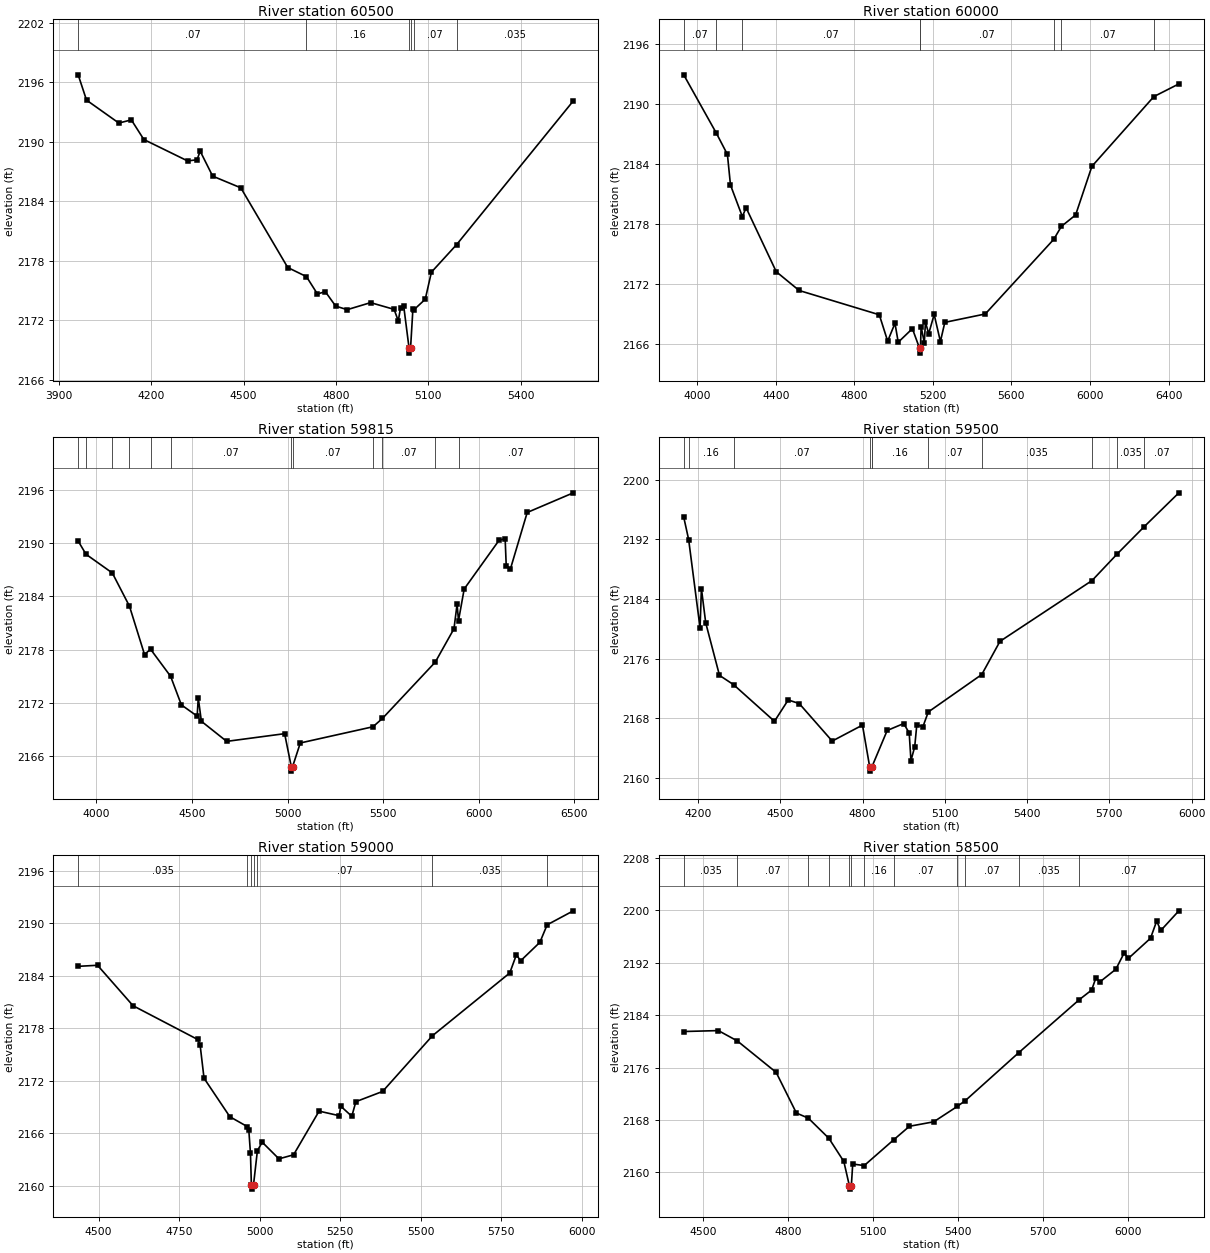
Type RM Length L Ch R = 1,60500,500,500,500
BEGIN DESCRIPTION:
East Cottonwood Creek 118.0
END DESCRIPTION:
XS GIS Cut Line= 3
      1353105.02      6892288.00      1354126.03      6892107.76
      1354155.00      6891538.00
#Sta/Elev= 30
  3963.2 2196.73  3990.3 2194.18  4095.2 2191.87  4135.8 2192.19  4176.4 2190.21
  4318.6 2188.05  4349.1 2188.17  4359.2 2189.04  4399.8 2186.52  4491.2 2185.34
  4643.5 2177.31  4704.3 2176.39  4739.9 2174.64  4765.4 2174.88  4799.1 2173.42
  4836.5 2173.06  4912.5 2173.77  4988.8 2173.09  5002.4 2171.93  5009.8 2173.27
  5019.8 2173.47  5037.4 2169.18  5037.8 2168.68  5042.2 2169.18  5049.8 2173.09
  5052.7 2173.04  5089.9 2174.11  5109.9 2176.84  5191.8 2179.62  5570.5 2194.10
#Mann=6,-1,0
  3963.2    0.07       0  4704.3    0.16       0  5037.4    0.07       0
  5042.2    0.16       0  5052.7    0.07       0  5191.8   0.035       0
Bank Sta=5037.4,5042.2
Exp/Cntr=0.3,0.1

Type RM Length L Ch R = 1,60000,185,185,185
BEGIN DESCRIPTION:
East Cottonwood Creek 117.0
END DESCRIPTION:
XS GIS Cut Line= 3
      1353357.30      6893106.36      1354272.93      6892556.01
      1355564.31      6891890.66
#Sta/Elev= 30
  3931.7 2192.90  4098.3 2187.04  4154.1 2184.93  4169.7 2181.87  4230.1 2178.71
  4249.3 2179.59  4402.8 2173.19  4519.4 2171.31  4927.4 2168.88  4970.1 2166.24
  5007.3 2168.03  5023.8 2166.13  5095.9 2167.49  5132.2 2165.54  5132.6 2165.04
  5137.1 2165.54  5140.3 2167.68  5156.8 2166.09  5162.4 2168.14  5179.0 2166.99
  5206.8 2168.91  5238.6 2166.20  5261.1 2168.12  5467.1 2168.96  5816.1 2176.44
  5854.6 2177.73  5927.0 2178.87  6010.0 2183.74  6325.4 2190.72  6452.7 2191.99
#Mann=8,-1,0
  3931.7    0.07       0  4098.3    0.16       0  4230.1    0.07       0
  5132.2    0.07       0  5137.1    0.07       0  5816.1    0.16       0
  5854.6    0.07       0  6325.4   0.035       0
Bank Sta=5132.2,5137.1
Exp/Cntr=0.3,0.1

Type RM Length L Ch R = 1,59815,315,315,315
BEGIN DESCRIPTION:
East Cottonwood Creek 116.5
END DESCRIPTION:
XS GIS Cut Line= 3
      1353402.87      6893214.44      1354374.92      6892703.58
      1355687.14      6891995.69
#Sta/Elev= 30
  3905.1 2190.25  3946.2 2188.76  4083.6 2186.65  4173.3 2182.90  4252.1 2177.44
  4283.5 2178.04  4388.4 2174.98  4444.8 2171.75  4527.4 2170.48  4533.0 2172.55
  4549.4 2169.90  4681.7 2167.63  4984.7 2168.50  5019.6 2164.77  5020.1 2164.27
  5026.2 2164.77  5066.7 2167.45  5446.7 2169.28  5496.2 2170.22  5772.4 2176.58
  5870.3 2180.35  5886.5 2183.12  5894.0 2181.27  5923.7 2184.84  6105.4 2190.32
  6137.8 2190.54  6143.5 2187.47  6165.4 2187.10  6253.2 2193.48  6494.2 2195.70
#Mann=12,-1,0
  3905.1    0.16       0  3946.2    0.07       0  4083.6    0.16       0
  4173.3    0.07       0  4283.5    0.16       0  4388.4    0.07       0
  5019.6    0.07       0  5026.2    0.07       0  5446.7    0.16       0
  5496.2    0.07       0  5772.4    0.16       0  5894.0    0.07       0
Bank Sta=5019.6,5026.2
Exp/Cntr=0.3,0.1

Type RM Length L Ch R = 1,59500,500,500,500
BEGIN DESCRIPTION:
East Cottonwood Creek 116.0
END DESCRIPTION:
XS GIS Cut Line= 3
      1353655.03      6893038.00      1354505.21      6892971.24
      1355454.97      6892888.00
#Sta/Elev= 30
  4147.2 2194.98  4165.1 2191.98  4206.7 2180.16  4211.7 2185.40  4227.4 2180.81
  4277.6 2173.77  4329.4 2172.51  4478.2 2167.61  4528.3 2170.47  4568.5 2169.99
  4688.8 2164.96  4799.2 2167.10  4825.9 2161.43  4826.4 2160.93  4832.6 2161.43
  4832.9 2161.44  4889.4 2166.38  4949.6 2167.31  4969.7 2166.05  4976.1 2162.34
  4989.8 2164.19  4997.4 2167.13  5019.9 2166.90  5039.3 2168.86  5234.4 2173.88
  5300.9 2178.33  5636.7 2186.48  5727.3 2190.00  5826.9 2193.70  5953.4 2198.24
#Mann=11,-1,0
  4147.2    0.07       0  4165.1    0.16       0  4329.4    0.07       0
  4825.9    0.07       0  4832.6    0.07       0  4832.9    0.16       0
  5039.3    0.07       0  5234.4   0.035       0  5636.7    0.07       0
  5727.3   0.035       0  5826.9    0.07       0
Bank Sta=4825.9,4832.6
Exp/Cntr=0.3,0.1

Type RM Length L Ch R = 1,59000,500,500,500
BEGIN DESCRIPTION:
East Cottonwood Creek 115.0
END DESCRIPTION:
XS GIS Cut Line= 3
      1353805.00      6893288.00      1354367.28      6893251.05
      1355304.99      6892988.00
#Sta/Elev= 30
  4436.5 2185.06  4496.6 2185.18  4606.9 2180.56  4807.3 2176.71  4815.0 2176.12
  4827.3 2172.28  4907.5 2167.88  4961.3 2166.76  4966.4 2166.33  4971.5 2163.69
  4974.3 2160.11  4974.8 2159.61  4981.0 2160.11  4993.0 2164.00  5008.0 2164.97
  5059.9 2163.07  5105.3 2163.53  5184.6 2168.52  5246.8 2168.00  5252.0 2169.08
  5286.1 2167.93  5298.8 2169.60  5381.9 2170.77  5536.5 2177.13  5776.6 2184.30
  5797.4 2186.40  5810.1 2185.68  5870.1 2187.80  5892.7 2189.80  5973.9 2191.40
#Mann=7,-1,0
  4436.5   0.035       0  4961.3    0.16       0  4974.3    0.07       0
  4981.0    0.16       0  4993.0    0.07       0  5536.5   0.035       0
  5892.7    0.07       0
Bank Sta=4974.3,4981
Exp/Cntr=0.3,0.1

Type RM Length L Ch R = 1,58500,500,500,500
BEGIN DESCRIPTION:
East Cottonwood Creek 114.0
END DESCRIPTION:
XS GIS Cut Line= 3
      1354005.00      6893488.00      1354562.17      6893593.69
      1355505.02      6892887.99
#Sta/Elev= 30
  4432.9 2181.51  4555.0 2181.65  4621.8 2180.07  4758.6 2175.27  4829.9 2169.06
  4872.0 2168.28  4944.4 2165.20  4997.1 2161.66  5016.7 2157.94  5017.2 2157.44
  5023.5 2157.94  5028.4 2161.27  5069.0 2161.04  5173.5 2165.00  5228.4 2167.04
  5313.9 2167.72  5396.5 2170.06  5425.3 2170.96  5614.0 2178.30  5827.0 2186.38
  5870.3 2187.84  5884.9 2189.64  5899.5 2189.09  5955.7 2191.02  5984.9 2193.50
  5999.5 2192.66  6077.8 2195.75  6099.5 2198.37  6114.1 2196.94  6177.7 2199.94
#Mann=12,-1,0
  4432.9   0.035       0  4621.8    0.07       0  4872.0    0.16       0
  4944.4    0.07       0  5016.7    0.07       0  5023.5    0.07       0
  5069.0    0.16       0  5173.5    0.07       0  5396.5    0.16       0
  5425.3    0.07       0  5614.0   0.035       0  5827.0    0.07       0
Bank Sta=5016.7,5023.5
Exp/Cntr=0.3,0.1

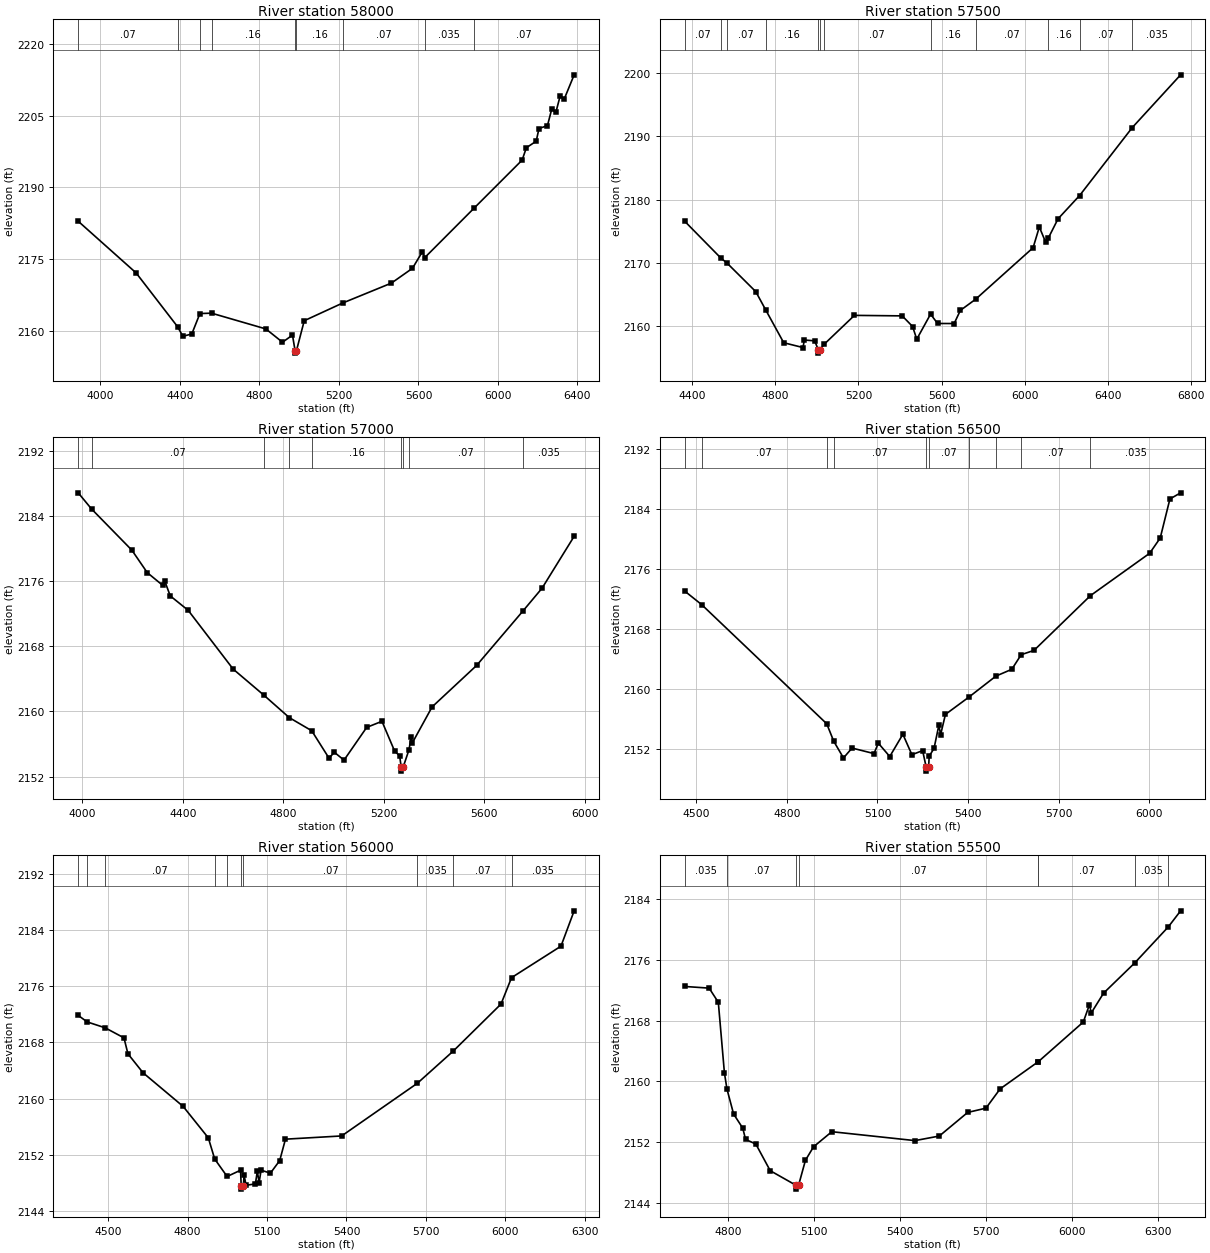
Type RM Length L Ch R = 1,58000,500,500,500
BEGIN DESCRIPTION:
East Cottonwood Creek 113.0
END DESCRIPTION:
XS GIS Cut Line= 3
      1353855.04      6894437.98      1354847.34      6893936.10
      1355804.98      6892938.02
#Sta/Elev= 30
  3888.0 2182.90  4179.3 2172.09  4387.7 2160.85  4414.6 2158.83  4459.5 2159.32
  4500.3 2163.59  4558.8 2163.67  4832.3 2160.37  4915.8 2157.59  4966.0 2159.08
  4979.2 2155.81  4979.7 2155.31  4986.0 2155.81  5025.2 2162.09  5219.0 2165.80
  5463.8 2169.96  5569.8 2173.06  5619.5 2176.52  5632.0 2175.31  5879.0 2185.61
  6121.4 2195.69  6142.8 2198.28  6192.2 2199.64  6206.3 2202.30  6248.8 2202.90
  6270.2 2206.32  6291.2 2205.68  6312.6 2209.08  6333.7 2208.51  6383.2 2213.53
#Mann=9,-1,0
  3888.0    0.07       0  4387.7    0.16       0  4500.3    0.07       0
  4558.8    0.16       0  4979.2    0.07       0  4986.0    0.16       0
  5219.0    0.07       0  5632.0   0.035       0  5879.0    0.07       0
Bank Sta=4979.2,4986
Exp/Cntr=0.3,0.1

Type RM Length L Ch R = 1,57500,500,500,500
BEGIN DESCRIPTION:
East Cottonwood Creek 112.0
END DESCRIPTION:
XS GIS Cut Line= 3
      1354104.98      6894738.02      1354604.51      6894342.91
      1356355.05      6894288.00
#Sta/Elev= 30
  4363.1 2176.57  4539.4 2170.69  4565.3 2170.02  4705.4 2165.46  4754.0 2162.53
  4840.0 2157.39  4932.9 2156.63  4939.3 2157.82  4989.0 2157.69  5007.0 2156.25
  5007.5 2155.75  5013.9 2156.25  5033.8 2157.12  5180.6 2161.71  5410.7 2161.63
  5460.7 2159.95  5480.7 2157.95  5547.3 2161.91  5580.8 2160.43  5660.8 2160.42
  5690.8 2162.50  5764.0 2164.25  6041.0 2172.39  6071.0 2175.66  6101.0 2173.29
  6114.0 2173.89  6161.1 2176.95  6265.0 2180.63  6518.7 2191.36  6751.4 2199.68
#Mann=12,-1,0
  4363.1    0.07       0  4539.4    0.16       0  4565.3    0.07       0
  4754.0    0.16       0  5007.0    0.07       0  5013.9    0.16       0
  5033.8    0.07       0  5547.3    0.16       0  5764.0    0.07       0
  6114.0    0.16       0  6265.0    0.07       0  6518.7   0.035       0
Bank Sta=5007,5013.9
Exp/Cntr=0.3,0.1

Type RM Length L Ch R = 1,57000,500,500,500
BEGIN DESCRIPTION:
East Cottonwood Creek 111.0
END DESCRIPTION:
XS GIS Cut Line= 3
      1353854.97      6894938.01      1354853.99      6894748.73
      1355804.97      6894638.00
#Sta/Elev= 30
  3983.2 2186.85  4036.2 2184.87  4197.0 2179.80  4258.0 2177.05  4319.1 2175.50
  4328.3 2175.96  4349.6 2174.19  4420.9 2172.42  4600.0 2165.20  4722.2 2162.00
  4823.5 2159.24  4912.7 2157.63  4981.4 2154.27  5003.0 2154.98  5041.3 2154.02
  5131.5 2158.04  5192.3 2158.79  5242.6 2155.14  5262.8 2154.54  5268.8 2153.17
  5269.3 2152.67  5276.8 2153.17  5299.9 2155.29  5308.5 2156.83  5313.6 2156.16
  5392.0 2160.56  5569.1 2165.65  5753.4 2172.33  5829.7 2175.14  5957.4 2181.51
#Mann=9,-1,0
  3983.2   0.035       0  4036.2    0.07       0  4722.2    0.16       0
  4823.5    0.07       0  4912.7    0.16       0  5268.8    0.07       0
  5276.8    0.16       0  5299.9    0.07       0  5753.4   0.035       0
Bank Sta=5268.8,5276.8
Exp/Cntr=0.3,0.1

Type RM Length L Ch R = 1,56500,500,500,500
BEGIN DESCRIPTION:
East Cottonwood Creek 110.0
END DESCRIPTION:
XS GIS Cut Line= 3
      1354305.02      6895138.00      1354837.54      6895221.33
      1355804.98      6894688.01
#Sta/Elev= 30
  4461.0 2173.06  4517.3 2171.25  4931.8 2155.35  4955.0 2153.02  4987.3 2150.79
  5015.7 2152.11  5088.4 2151.37  5102.8 2152.76  5140.7 2150.98  5184.2 2153.95
  5214.1 2151.22  5249.6 2151.77  5261.6 2149.53  5262.1 2149.03  5269.6 2149.53
  5271.3 2151.02  5287.4 2152.06  5303.5 2155.17  5309.2 2153.89  5325.2 2156.60
  5403.4 2158.92  5492.5 2161.71  5545.2 2162.62  5576.3 2164.57  5618.7 2165.14
  5805.8 2172.45  6002.0 2178.10  6037.1 2180.14  6069.2 2185.35  6104.7 2186.17
#Mann=10,-1,0
  4461.0   0.035       0  4517.3    0.07       0  4931.8    0.16       0
  4955.0    0.07       0  5261.6    0.07       0  5269.6    0.07       0
  5403.4    0.16       0  5492.5   0.035       0  5576.3    0.07       0
  5805.8   0.035       0
Bank Sta=5261.6,5269.6
Exp/Cntr=0.3,0.1

Type RM Length L Ch R = 1,56000,500,500,500
BEGIN DESCRIPTION:
East Cottonwood Creek 109.0
END DESCRIPTION:
XS GIS Cut Line= 3
      1354355.03      6895238.02      1354865.52      6895577.75
      1355805.02      6894737.99
#Sta/Elev= 30
  4386.8 2171.84  4420.5 2170.91  4488.6 2170.07  4559.6 2168.64  4574.6 2166.37
  4631.7 2163.67  4783.2 2158.88  4878.2 2154.41  4902.4 2151.39  4949.3 2148.91
  5000.0 2149.80  5002.4 2147.61  5002.9 2147.11  5010.8 2147.61  5013.3 2149.11
  5020.8 2147.66  5055.9 2147.85  5063.4 2149.64  5070.1 2148.05  5077.6 2149.81
  5112.7 2149.38  5147.9 2151.17  5169.6 2154.22  5381.9 2154.68  5668.0 2162.18
  5804.3 2166.79  5983.8 2173.45  6023.6 2177.21  6210.3 2181.69  6260.1 2186.72
#Mann=10,-1,0
  4386.8    0.07       0  4420.5   0.035       0  4488.6    0.07       0
  4902.4    0.16       0  4949.3    0.07       0  5002.4    0.07       0
  5010.8    0.07       0  5668.0   0.035       0  5804.3    0.07       0
  6023.6   0.035       0
Bank Sta=5002.4,5010.8
Exp/Cntr=0.3,0.1

Type RM Length L Ch R = 1,55500,500,500,500
BEGIN DESCRIPTION:
East Cottonwood Creek 108.0
END DESCRIPTION:
XS GIS Cut Line= 3
      1354604.98      6896088.01      1354933.72      6895966.75
      1355905.01      6894987.99
#Sta/Elev= 30
  4649.6 2172.47  4734.9 2172.25  4766.9 2170.39  4788.2 2161.11  4797.1 2158.99
  4820.2 2155.72  4852.1 2153.87  4861.9 2152.39  4897.7 2151.78  4947.9 2148.28
  5038.1 2146.36  5038.6 2145.86  5046.7 2146.36  5070.7 2149.65  5099.0 2151.42
  5162.7 2153.40  5452.6 2152.23  5537.4 2152.83  5636.4 2155.93  5700.1 2156.49
  5749.5 2159.02  5882.1 2162.58  5882.9 2162.60  6039.5 2167.80  6060.7 2170.04
  6067.8 2169.02  6110.2 2171.59  6218.9 2175.56  6335.9 2180.29  6378.9 2182.40
#Mann=8,-1,0
  4649.6   0.035       0  4797.1    0.07       0  5038.1    0.07       0
  5046.7    0.07       0  5882.1   0.035       0  5882.9    0.07       0
  6218.9   0.035       0  6335.9    0.07       0
Bank Sta=5038.1,5046.7
Exp/Cntr=0.3,0.1

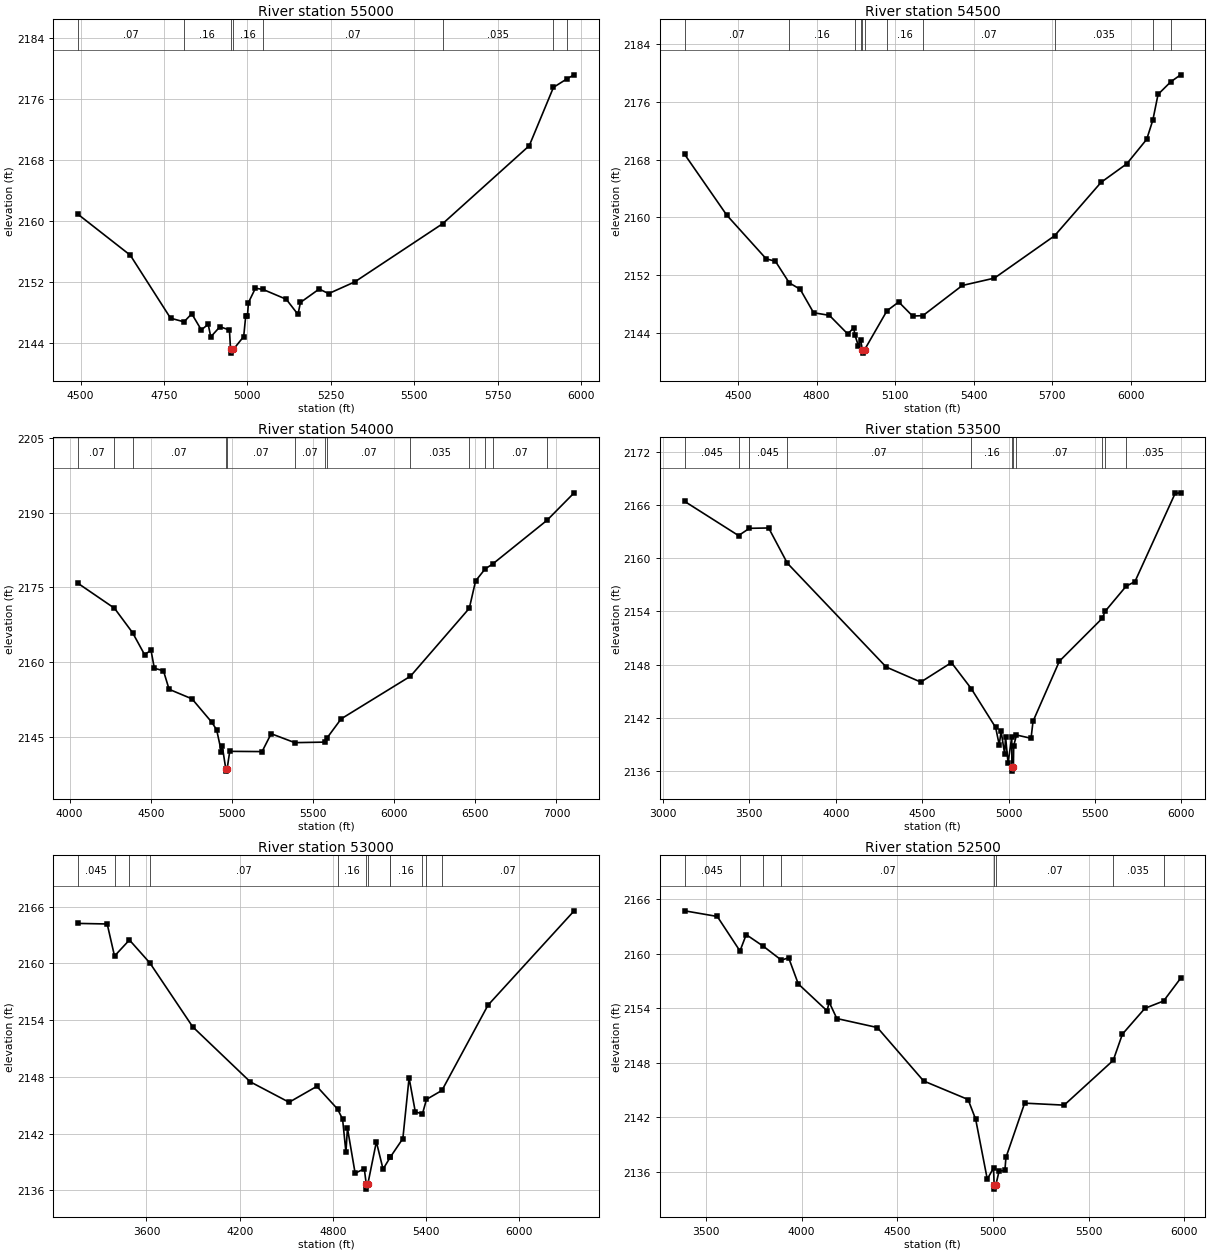
Type RM Length L Ch R = 1,55000,500,500,500
BEGIN DESCRIPTION:
East Cottonwood Creek 107.0
END DESCRIPTION:
XS GIS Cut Line= 3
      1355005.02      6896437.98      1355337.89      6896055.16
      1356005.02      6895337.98
#Sta/Elev= 30
  4492.7 2160.82  4648.9 2155.48  4769.5 2147.23  4809.9 2146.75  4833.1 2147.81
  4861.6 2145.70  4882.4 2146.42  4890.1 2144.78  4917.6 2146.11  4946.1 2145.68
  4949.3 2143.15  4949.8 2142.65  4958.0 2143.15  4988.8 2144.82  4994.8 2147.48
  5000.0 2147.48  5003.0 2149.27  5024.0 2151.16  5047.1 2150.99  5116.4 2149.71
  5151.6 2147.72  5158.9 2149.29  5215.1 2151.05  5243.4 2150.45  5321.6 2151.98
  5585.2 2159.61  5844.9 2169.83  5917.5 2177.48  5959.3 2178.63  5979.5 2179.12
#Mann=8,-1,0
  4492.7    0.07       0  4809.9    0.16       0  4949.3    0.07       0
  4958.0    0.16       0  5047.1    0.07       0  5585.2   0.035       0
  5917.5    0.07       0  5959.3   0.035       0
Bank Sta=4949.3,4958
Exp/Cntr=0.3,0.1

Type RM Length L Ch R = 1,54500,500,500,500
BEGIN DESCRIPTION:
East Cottonwood Creek 106.0
END DESCRIPTION:
XS GIS Cut Line= 3
      1354854.96      6896488.00      1355555.56      6896416.88
      1356015.74      6895318.49
#Sta/Elev= 30
  4295.8 2168.72  4456.7 2160.30  4607.4 2154.24  4642.5 2153.91  4695.3 2150.92
  4737.2 2150.02  4788.4 2146.77  4848.7 2146.41  4919.0 2143.82  4941.8 2144.69
  4945.9 2143.74  4959.2 2142.22  4967.7 2143.02  4974.9 2141.67  4975.4 2141.17
  4983.7 2141.67  5068.9 2147.05  5113.8 2148.26  5166.8 2146.31  5206.1 2146.37
  5356.6 2150.55  5479.3 2151.57  5709.2 2157.44  5886.9 2164.85  5985.4 2167.43
  6061.3 2170.82  6084.8 2173.49  6104.7 2177.05  6153.5 2178.80  6190.9 2179.76
#Mann=11,-1,0
  4295.8    0.07       0  4695.3    0.16       0  4945.9    0.07       0
  4967.7    0.16       0  4974.9    0.07       0  4983.7    0.16       0
  5068.9    0.16       0  5206.1    0.07       0  5709.2   0.035       0
  6084.8    0.07       0  6153.5   0.035       0
Bank Sta=4974.9,4983.7
Exp/Cntr=0.3,0.1

Type RM Length L Ch R = 1,54000,500,500,500
BEGIN DESCRIPTION:
East Cottonwood Creek 105.0
END DESCRIPTION:
XS GIS Cut Line= 3
      1354550.47      6896690.06      1355487.92      6896821.42
      1356205.01      6894837.97
#Sta/Elev= 30
  4053.4 2175.80  4276.8 2170.84  4388.3 2165.95  4461.9 2161.58  4502.1 2162.40
  4522.5 2158.82  4578.5 2158.34  4613.3 2154.62  4754.7 2152.70  4875.9 2148.04
  4906.2 2146.52  4935.4 2142.14  4940.4 2143.35  4962.4 2138.74  4962.9 2138.24
  4971.2 2138.74  4987.0 2142.20  5186.2 2142.15  5242.2 2145.73  5387.7 2143.94
  5575.2 2144.05  5588.6 2144.97  5673.5 2148.70  6100.7 2157.24  6463.0 2170.83
  6501.9 2176.31  6560.9 2178.72  6606.9 2179.69  6941.8 2188.44  7109.1 2193.94
#Mann=13,-1,0
  4053.4    0.07       0  4276.8   0.035       0  4388.3    0.07       0
  4962.4    0.07       0  4971.2    0.07       0  5387.7    0.07       0
  5575.2    0.16       0  5588.6    0.07       0  6100.7   0.035       0
  6463.0    0.07       0  6560.9   0.035       0  6606.9    0.07       0
  6941.8   0.035       0
Bank Sta=4962.4,4971.2
Exp/Cntr=0.3,0.1

Type RM Length L Ch R = 1,53500,500,500,500
BEGIN DESCRIPTION:
East Cottonwood Creek 104.0
END DESCRIPTION:
XS GIS Cut Line= 4
      1354299.07      6897002.55      1355660.17      6897002.55
      1355826.02      6896516.79      1356005.00      6895538.02
#Sta/Elev= 30
  3125.6 2166.43  3437.1 2162.57  3500.1 2163.39  3611.5 2163.43  3719.6 2159.45
  4291.5 2147.72  4491.7 2146.02  4668.9 2148.22  4783.6 2145.28  4924.8 2140.89
  4945.5 2138.94  4956.5 2140.46  4976.8 2137.90  4982.1 2139.85  4996.7 2136.88
  5018.1 2139.84  5018.7 2136.46  5019.2 2135.96  5027.5 2136.46  5029.3 2138.83
  5045.4 2140.04  5129.6 2139.67  5141.1 2141.59  5293.6 2148.38  5541.9 2153.23
  5558.1 2154.01  5679.2 2156.84  5730.7 2157.37  5963.3 2167.34  5995.0 2167.40
#Mann=11,-1,0
  3125.6   0.045       0  3437.1    0.07       0  3500.1   0.045       0
  3719.6    0.07       0  4783.6    0.16       0  5018.7    0.07       0
  5027.5    0.16       0  5045.4    0.07       0  5541.9   0.035       0
  5558.1    0.07       0  5679.2   0.035       0
Bank Sta=5018.7,5027.5
Exp/Cntr=0.3,0.1

Type RM Length L Ch R = 1,53000,500,500,500
BEGIN DESCRIPTION:
East Cottonwood Creek 103.0
END DESCRIPTION:
XS GIS Cut Line= 5
      1354368.53      6897023.39      1355729.61      6897078.94
      1355932.35      6896735.02      1356005.20      6896761.91
      1357354.62      6896662.28
#Sta/Elev= 30
  3160.9 2164.22  3347.5 2164.16  3394.6 2160.77  3490.5 2162.47  3622.2 2160.04
  3898.0 2153.29  4268.3 2147.48  4518.3 2145.32  4696.8 2147.00  4830.3 2144.60
  4862.6 2143.54  4884.1 2140.04  4893.9 2142.59  4943.3 2137.82  5002.4 2138.29
  5015.1 2136.64  5015.6 2136.14  5024.6 2136.64  5080.0 2141.14  5123.1 2138.25
  5169.0 2139.50  5169.6 2139.52  5250.5 2141.48  5290.6 2147.90  5330.7 2144.30
  5376.7 2144.10  5402.5 2145.62  5502.0 2146.57  5798.5 2155.58  6353.1 2165.55
#Mann=12,-1,0
  3160.9   0.045       0  3394.6    0.07       0  3490.5   0.045       0
  3622.2    0.07       0  4830.3    0.16       0  5015.1    0.07       0
  5024.6    0.16       0  5169.0    0.07       0  5169.6    0.16       0
  5376.7    0.07       0  5402.5    0.16       0  5502.0    0.07       0
Bank Sta=5015.1,5024.6
Exp/Cntr=0.3,0.1

Type RM Length L Ch R = 1,52500,500,500,500
BEGIN DESCRIPTION:
East Cottonwood Creek 102.0
END DESCRIPTION:
XS GIS Cut Line= 3
      1354306.00      6897030.33      1355904.92      6897229.71
      1356854.96      6896988.01
#Sta/Elev= 30
  3388.7 2164.71  3559.0 2164.09  3677.7 2160.29  3710.2 2162.09  3799.8 2160.81
  3894.3 2159.28  3931.9 2159.55  3982.3 2156.67  4133.0 2153.70  4143.5 2154.67
  4183.8 2152.86  4395.4 2151.87  4637.3 2145.99  4869.6 2143.95  4909.4 2141.77
  4969.9 2135.19  5002.6 2136.41  5005.7 2134.59  5006.2 2134.09  5015.2 2134.59
  5031.7 2136.08  5062.0 2136.14  5067.5 2137.57  5165.2 2143.55  5371.6 2143.33
  5628.2 2148.26  5676.0 2151.14  5793.6 2153.98  5891.4 2154.79  5980.3 2157.29
#Mann=8,-1,0
  3388.7   0.045       0  3677.7    0.07       0  3799.8   0.045       0
  3894.3    0.07       0  5005.7    0.07       0  5015.2    0.07       0
  5628.2   0.035       0  5891.4    0.07       0
Bank Sta=5005.7,5015.2
Exp/Cntr=0.3,0.1