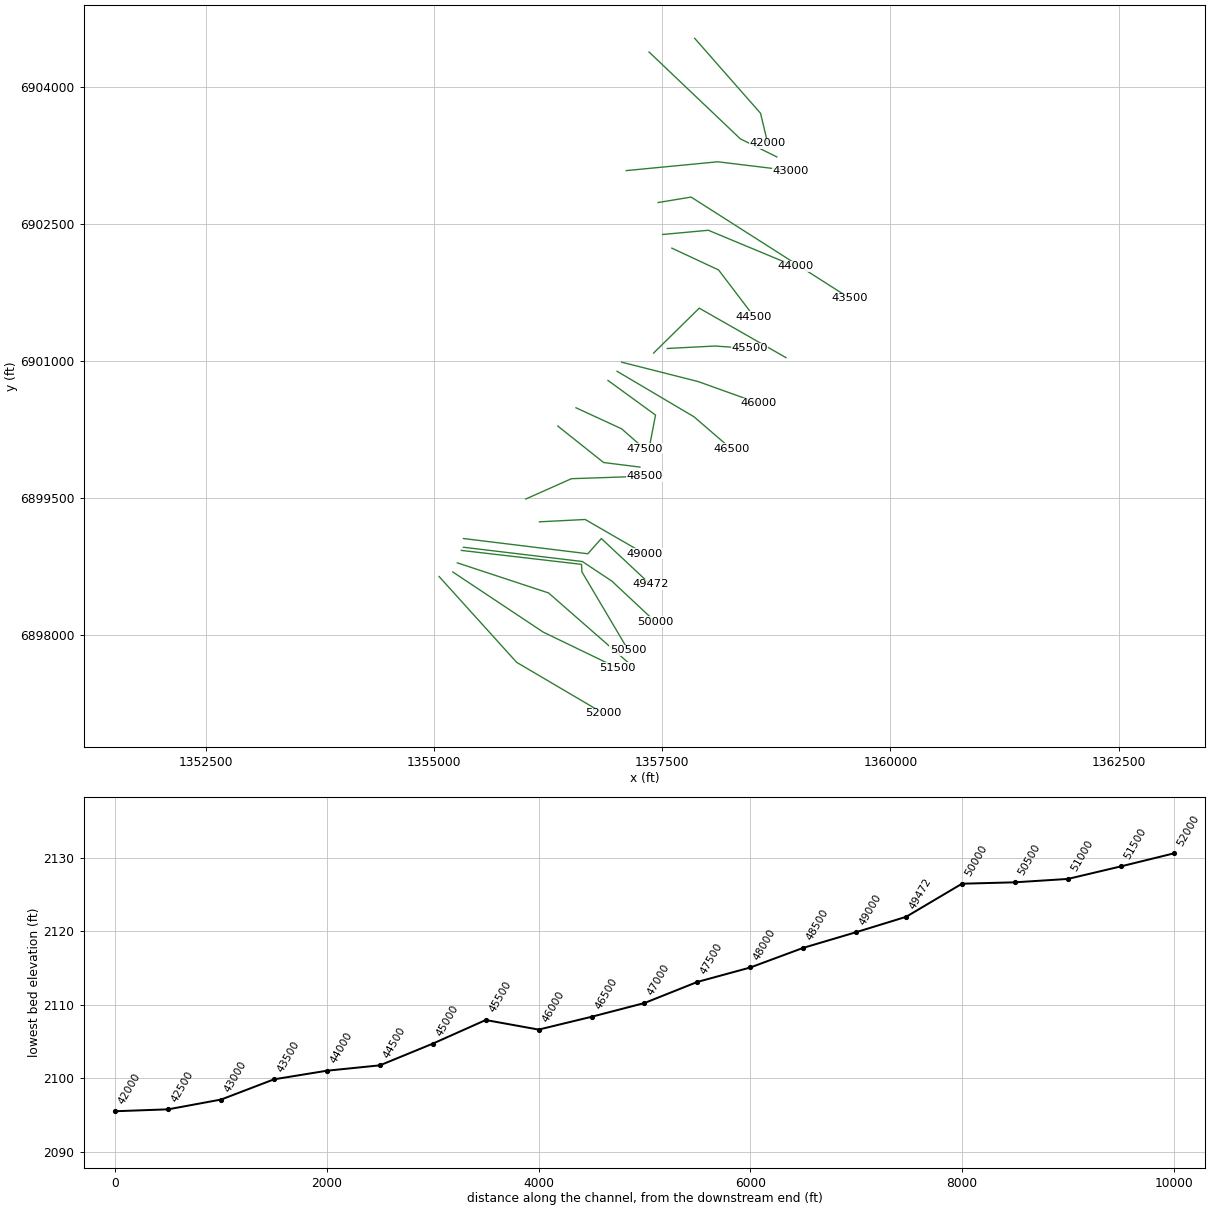
HEC-RAS study East Cottonwood Creek.prj: East Cottonwood Creek Base Level Engineering

--- East Cottonwood Creek.g01 (geometry) --- (continued)

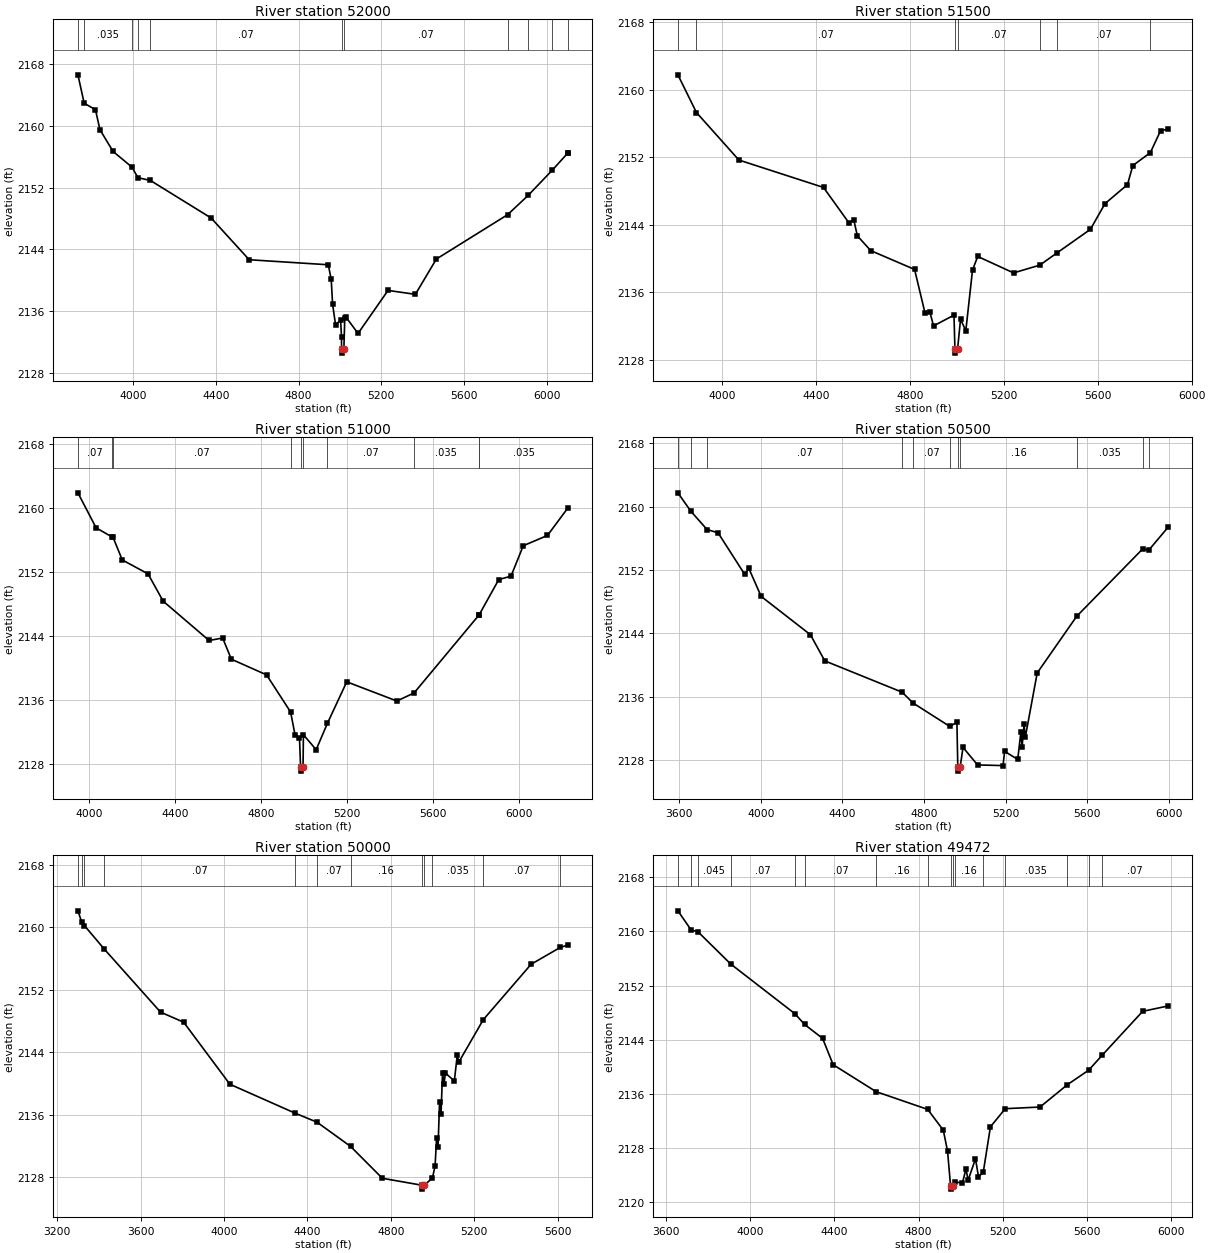
Type RM Length L Ch R = 1,52000,500,500,500
BEGIN DESCRIPTION:
East Cottonwood Creek 101.0
END DESCRIPTION:
XS GIS Cut Line= 3
      1355055.00      6898638.01      1355904.56      6897697.50
      1356855.00      6897138.00
#Sta/Elev= 30
  3732.6 2166.60  3762.9 2162.92  3817.4 2162.09  3839.1 2159.50  3902.6 2156.68
  3994.5 2154.64  4022.7 2153.28  4082.9 2152.93  4377.1 2148.06  4561.0 2142.66
  4943.6 2142.01  4957.8 2140.11  4964.5 2136.90  4978.7 2134.26  5003.2 2134.83
  5007.6 2132.68  5007.7 2131.07  5008.2 2130.57  5019.0 2131.07  5023.3 2135.08
  5029.1 2135.23  5087.6 2133.12  5232.6 2138.69  5364.9 2138.18  5466.4 2142.75
  5811.4 2148.50  5910.4 2150.99  6027.3 2154.26  6101.1 2156.44  6102.9 2156.44
#Mann=11,-1,0
  3732.6    0.07       0  3762.9   0.035       0  3994.5    0.07       0
  4022.7   0.035       0  4082.9    0.07       0  5007.7    0.07       0
  5019.0    0.07       0  5811.4   0.035       0  5910.4    0.07       0
  6027.3   0.035       0  6101.1    0.07       0
Bank Sta=5007.7,5019
Exp/Cntr=0.3,0.1

Type RM Length L Ch R = 1,51500,500,500,500
BEGIN DESCRIPTION:
East Cottonwood Creek 100.0
END DESCRIPTION:
XS GIS Cut Line= 3
      1355204.98      6898688.01      1356195.68      6898028.94
      1357005.00      6897638.00
#Sta/Elev= 30
  3810.1 2161.79  3889.3 2157.32  4070.1 2151.69  4430.8 2148.44  4539.0 2144.25
  4560.1 2144.56  4575.1 2142.70  4632.2 2140.95  4819.0 2138.72  4863.7 2133.52
  4884.7 2133.62  4899.7 2132.03  4986.9 2133.30  4990.9 2129.30  4991.4 2128.80
  5002.3 2129.30  5014.8 2132.80  5037.4 2131.47  5065.9 2138.65  5088.1 2140.26
  5240.8 2138.31  5352.7 2139.23  5427.4 2140.71  5568.3 2143.47  5630.6 2146.52
  5726.5 2148.78  5749.1 2151.03  5824.0 2152.57  5867.7 2155.18  5898.8 2155.33
#Mann=7,-1,0
  3810.1   0.035       0  3889.3    0.07       0  4990.9    0.07       0
  5002.3    0.07       0  5352.7   0.035       0  5427.4    0.07       0
  5824.0   0.035       0
Bank Sta=4990.9,5002.3
Exp/Cntr=0.3,0.1

Type RM Length L Ch R = 1,51000,500,500,500
BEGIN DESCRIPTION:
East Cottonwood Creek 99.0
END DESCRIPTION:
XS GIS Cut Line= 3
      1355254.96      6898788.01      1356254.22      6898458.16
      1357179.51      6897648.37
#Sta/Elev= 30
  3947.7 2161.91  4032.4 2157.53  4107.4 2156.38  4110.3 2156.41  4154.1 2153.52
  4274.2 2151.77  4344.6 2148.36  4558.5 2143.44  4621.7 2143.75  4662.1 2141.10
  4826.1 2139.14  4938.0 2134.50  4958.7 2131.65  4979.5 2131.26  4984.5 2127.60
  4985.0 2127.10  4996.0 2127.60  4997.8 2131.65  5057.1 2129.78  5109.5 2133.08
  5199.5 2138.27  5433.0 2135.87  5513.1 2136.88  5813.7 2146.57  5815.2 2146.61
  5907.5 2151.06  5964.5 2151.49  6021.4 2155.29  6134.3 2156.58  6229.6 2160.03
#Mann=10,-1,0
  3947.7    0.07       0  4107.4   0.045       0  4110.3    0.07       0
  4938.0    0.16       0  4984.5    0.07       0  4996.0    0.16       0
  5109.5    0.07       0  5513.1   0.035       0  5813.7    0.07       0
  5815.2   0.035       0
Bank Sta=4984.5,4996
Exp/Cntr=0.3,0.1

Type RM Length L Ch R = 1,50500,500,500,500
BEGIN DESCRIPTION:
East Cottonwood Creek 98.0
END DESCRIPTION:
XS GIS Cut Line= 4
      1355299.31      6898924.43      1356615.26      6898771.65
      1356619.66      6898689.26      1357126.71      6897831.87
#Sta/Elev= 30
  3592.7 2161.73  3656.0 2159.42  3735.7 2157.10  3789.7 2156.69  3920.6 2151.44
  3940.7 2152.20  4001.1 2148.67  4242.7 2143.84  4313.2 2140.54  4692.8 2136.59
  4745.9 2135.23  4926.5 2132.27  4961.2 2132.81  4965.5 2127.14  4966.0 2126.64
  4977.0 2127.14  4991.2 2129.63  5062.5 2127.42  5187.3 2127.34  5195.1 2129.13
  5259.5 2128.12  5275.1 2131.59  5280.9 2129.74  5290.7 2132.53  5296.5 2130.90
  5355.0 2139.02  5548.6 2146.16  5873.2 2154.68  5901.8 2154.49  5996.1 2157.37
#Mann=11,-1,0
  3592.7    0.07       0  3656.0   0.045       0  3735.7    0.07       0
  4692.8    0.16       0  4745.9    0.07       0  4926.5    0.16       0
  4965.5    0.07       0  4977.0    0.16       0  5548.6   0.035       0
  5873.2    0.07       0  5901.8   0.035       0
Bank Sta=4965.5,4977
Exp/Cntr=0.3,0.1

Type RM Length L Ch R = 1,50000,528,528,528
BEGIN DESCRIPTION:
East Cottonwood Creek 97.0
END DESCRIPTION:
XS GIS Cut Line= 4
      1355321.83      6898959.15      1356623.94      6898802.90
      1356947.69      6898588.06      1357421.31      6898144.34
#Sta/Elev= 30
  3300.0 2162.11  3318.4 2160.65  3331.1 2160.22  3427.2 2157.18  3696.0 2149.13
  3806.8 2147.84  4028.4 2139.89  4342.2 2136.17  4446.0 2135.03  4607.2 2131.92
  4759.3 2127.84  4949.1 2126.95  4949.6 2126.45  4960.6 2126.95  4999.3 2127.88
  5012.1 2129.41  5019.4 2133.06  5026.3 2131.89  5033.6 2137.59  5040.5 2136.02
  5047.8 2141.35  5054.6 2139.97  5061.9 2141.31  5104.4 2140.31  5118.6 2143.66
  5125.4 2142.71  5243.4 2148.17  5472.3 2155.26  5612.7 2157.43  5649.0 2157.72
#Mann=12,-1,0
  3300.0   0.045       0  3318.4    0.07       0  3331.1   0.045       0
  3427.2    0.07       0  4342.2    0.16       0  4446.0    0.07       0
  4607.2    0.16       0  4949.1   0.035       0  4960.6    0.16       0
  4999.3   0.035       0  5243.4    0.07       0  5612.7   0.035       0
Bank Sta=4949.1,4960.6
Exp/Cntr=0.3,0.1

Type RM Length L Ch R = 1,49472,472,472,472
BEGIN DESCRIPTION:
East Cottonwood Creek 96.0
END DESCRIPTION:
XS GIS Cut Line= 4
      1355321.86      6899054.64      1356684.28      6898887.74
      1356832.28      6899054.64      1357369.26      6898552.29
#Sta/Elev= 30
  3655.1 2163.04  3718.4 2160.20  3749.5 2159.98  3907.0 2155.17  4212.0 2147.84
  4257.9 2146.26  4343.4 2144.21  4393.7 2140.32  4598.0 2136.34  4843.4 2133.72
  4917.6 2130.65  4937.8 2127.57  4952.1 2122.45  4952.6 2121.95  4963.7 2122.45
  4971.7 2123.07  5008.3 2122.81  5025.6 2124.96  5035.5 2123.25  5070.7 2126.43
  5084.9 2123.80  5107.6 2124.42  5141.8 2131.15  5212.5 2133.83  5377.7 2134.07
  5507.9 2137.37  5609.1 2139.51  5672.2 2141.68  5865.9 2148.20  5986.1 2148.99
#Mann=16,-1,0
  3655.1   0.045       0  3718.4    0.07       0  3749.5   0.045       0
  3907.0    0.07       0  4212.0   0.035       0  4257.9    0.07       0
  4598.0    0.16       0  4843.4    0.07       0  4952.1    0.07       0
  4963.7    0.07       0  4971.7    0.16       0  5107.6    0.07       0
  5212.5   0.035       0  5507.9    0.07       0  5609.1    0.16       0
  5672.2    0.07       0
Bank Sta=4952.1,4963.7
Exp/Cntr=0.3,0.1

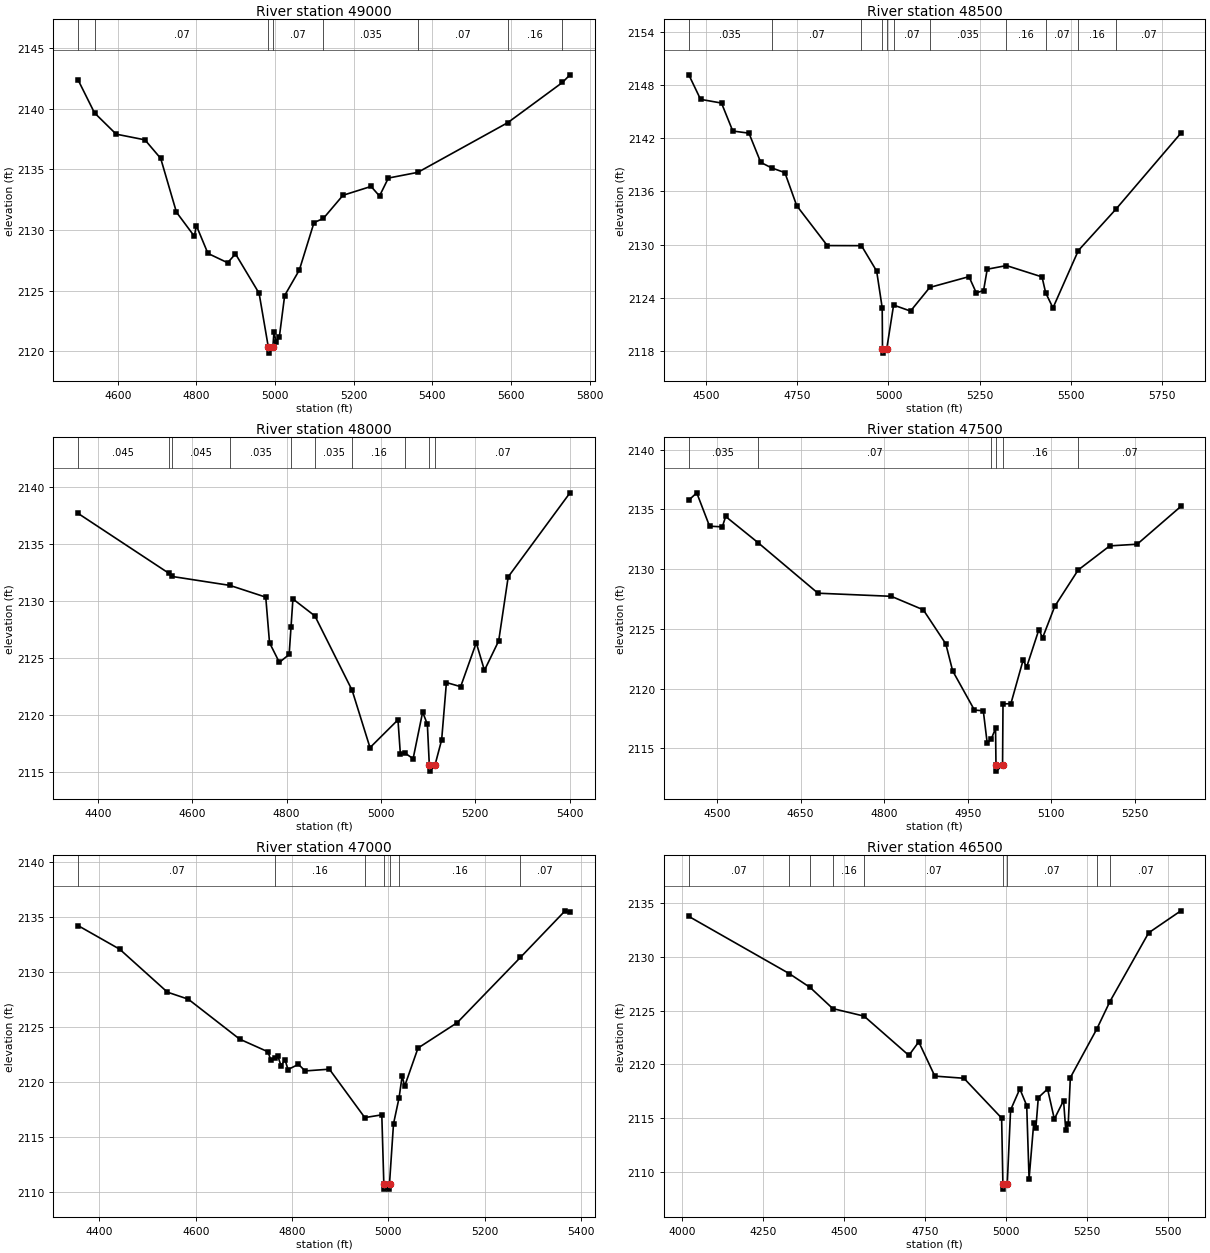
Type RM Length L Ch R = 1,49000,500,500,500
BEGIN DESCRIPTION:
East Cottonwood Creek 95.0
END DESCRIPTION:
XS GIS Cut Line= 3
      1356154.97      6899238.00      1356655.33      6899263.35
      1357304.99      6898888.00
#Sta/Elev= 30
  4499.0 2142.39  4541.0 2139.66  4596.0 2137.91  4669.2 2137.44  4709.3 2135.91
  4749.3 2131.48  4794.9 2129.49  4799.9 2130.38  4829.4 2128.08  4879.5 2127.31
  4899.5 2128.04  4959.6 2124.79  4983.0 2120.36  4983.5 2119.86  4994.6 2120.36
  4997.3 2121.57  5003.0 2120.80  5011.2 2121.23  5024.6 2124.61  5061.9 2126.71
  5099.2 2130.62  5122.9 2130.96  5172.9 2132.87  5244.3 2133.60  5265.8 2132.81
  5288.3 2134.29  5363.2 2134.76  5592.1 2138.86  5731.0 2142.17  5750.3 2142.80
#Mann=8,-1,0
  4499.0   0.035       0  4541.0    0.07       0  4983.0    0.07       0
  4994.6    0.07       0  5122.9   0.035       0  5363.2    0.07       0
  5592.1    0.16       0  5731.0    0.07       0
Bank Sta=4983,4994.6
Exp/Cntr=0.3,0.1

Type RM Length L Ch R = 1,48500,500,500,500
BEGIN DESCRIPTION:
East Cottonwood Creek 94.0
END DESCRIPTION:
XS GIS Cut Line= 3
      1356005.04      6899488.02      1356504.64      6899710.50
      1357304.97      6899738.00
#Sta/Elev= 30
  4453.1 2149.17  4485.2 2146.40  4542.6 2145.98  4573.5 2142.82  4617.8 2142.58
  4650.1 2139.28  4679.6 2138.66  4716.2 2138.12  4748.6 2134.39  4832.4 2129.88
  4926.0 2129.87  4967.6 2127.00  4982.8 2122.85  4983.6 2118.23  4984.1 2117.73
  4995.3 2118.23  5014.0 2123.16  5060.4 2122.48  5113.0 2125.15  5220.5 2126.37
  5240.5 2124.54  5260.5 2124.80  5270.5 2127.21  5323.2 2127.62  5420.6 2126.34
  5430.6 2124.54  5450.6 2122.84  5520.1 2129.32  5623.0 2133.99  5800.8 2142.57
#Mann=11,-1,0
  4453.1   0.035       0  4679.6    0.07       0  4926.0    0.16       0
  4983.6    0.07       0  4995.3    0.16       0  5014.0    0.07       0
  5113.0   0.035       0  5323.2    0.16       0  5430.6    0.07       0
  5520.1    0.16       0  5623.0    0.07       0
Bank Sta=4983.6,4995.3
Exp/Cntr=0.3,0.1

Type RM Length L Ch R = 1,48000,500,500,500
BEGIN DESCRIPTION:
East Cottonwood Creek 93.0
END DESCRIPTION:
XS GIS Cut Line= 3
      1356355.01      6900287.99      1356857.23      6899887.89
      1357255.01      6899838.00
#Sta/Elev= 30
  4357.9 2137.67  4549.9 2132.43  4556.5 2132.14  4679.9 2131.35  4755.9 2130.32
  4763.9 2126.32  4784.7 2124.60  4805.5 2125.29  4809.4 2127.66  4813.5 2130.16
  4860.1 2128.67  4939.0 2122.15  4976.9 2117.12  5036.2 2119.56  5041.2 2116.60
  5050.6 2116.66  5068.3 2116.15  5088.5 2120.24  5098.5 2119.17  5102.7 2115.56
  5103.2 2115.06  5114.5 2115.56  5128.8 2117.80  5138.9 2122.83  5169.1 2122.47
  5202.2 2126.32  5219.5 2123.90  5249.7 2126.48  5269.9 2132.10  5400.9 2139.47
#Mann=10,-1,0
  4357.9   0.045       0  4549.9   0.035       0  4556.5   0.045       0
  4679.9   0.035       0  4809.4    0.07       0  4860.1   0.035       0
  4939.0    0.16       0  5050.6    0.07       0  5102.7    0.07       0
  5114.5    0.07       0
Bank Sta=5102.7,5114.5
Exp/Cntr=0.3,0.1

Type RM Length L Ch R = 1,47500,500,500,500
BEGIN DESCRIPTION:
East Cottonwood Creek 92.0
END DESCRIPTION:
XS GIS Cut Line= 3
      1356554.99      6900488.00      1357054.95      6900257.34
      1357304.98      6900038.01
#Sta/Elev= 30
  4449.4 2135.78  4463.6 2136.39  4486.6 2133.60  4509.5 2133.54  4515.5 2134.41
  4573.4 2132.23  4681.2 2127.99  4812.8 2127.73  4870.3 2126.60  4910.7 2123.75
  4923.0 2121.49  4962.1 2118.21  4978.0 2118.15  4985.0 2115.46  4992.1 2115.76
  5000.0 2116.68  5000.8 2113.60  5001.3 2113.10  5012.6 2113.60  5013.4 2118.73
  5027.5 2118.74  5049.4 2122.37  5056.0 2121.83  5077.8 2124.94  5084.5 2124.26
  5106.3 2126.89  5148.3 2129.93  5205.0 2131.95  5254.3 2132.09  5332.6 2135.25
#Mann=6,-1,0
  4449.4   0.035       0  4573.4    0.07       0  4992.1    0.16       0
  5000.8    0.07       0  5012.6    0.16       0  5148.3    0.07       0
Bank Sta=5000.8,5012.6
Exp/Cntr=0.3,0.1

Type RM Length L Ch R = 1,47000,500,500,500
BEGIN DESCRIPTION:
East Cottonwood Creek 91.0
END DESCRIPTION:
XS GIS Cut Line= 3
      1356905.02      6900787.99      1357425.88      6900408.40
      1357355.00      6900038.02
#Sta/Elev= 30
  4355.5 2134.18  4442.1 2132.03  4541.1 2128.13  4584.5 2127.49  4691.2 2123.86
  4749.9 2122.71  4756.1 2121.92  4764.7 2122.18  4770.7 2122.29  4776.9 2121.46
  4785.4 2121.96  4791.6 2121.10  4813.3 2121.57  4827.1 2120.97  4877.4 2121.13
  4951.0 2116.73  4986.3 2116.98  4990.5 2110.73  4991.0 2110.23  5001.8 2110.23
  5002.3 2110.73  5010.6 2116.16  5022.2 2118.54  5028.6 2120.52  5033.7 2119.58
  5061.5 2123.05  5143.0 2125.36  5274.2 2131.29  5366.9 2135.52  5377.1 2135.39
#Mann=7,-1,0
  4355.5    0.07       0  4764.7    0.16       0  4951.0    0.07       0
  4990.5    0.07       0  5002.3    0.07       0  5022.2    0.16       0
  5274.2    0.07       0
Bank Sta=4990.5,5002.3
Exp/Cntr=0.3,0.1

Type RM Length L Ch R = 1,46500,500,500,500
BEGIN DESCRIPTION:
East Cottonwood Creek 90.0
END DESCRIPTION:
XS GIS Cut Line= 3
      1357005.00      6900888.00      1357847.09      6900389.48
      1358254.97      6900038.03
#Sta/Elev= 30
  4021.4 2133.77  4330.5 2128.45  4395.4 2127.15  4465.3 2125.18  4561.7 2124.48
  4699.9 2120.82  4730.3 2122.08  4779.9 2118.89  4869.6 2118.69  4985.9 2114.98
  4989.8 2108.86  4990.3 2108.36  5003.2 2108.86  5013.5 2115.73  5042.0 2117.70
  5063.2 2116.15  5070.5 2109.31  5084.8 2114.49  5091.4 2114.02  5099.0 2116.89
  5127.6 2117.69  5148.4 2114.89  5176.9 2116.61  5183.5 2113.89  5191.2 2114.41
  5197.8 2118.75  5279.2 2123.27  5319.8 2125.84  5439.2 2132.24  5538.4 2134.29
#Mann=9,-1,0
  4021.4    0.07       0  4330.5    0.16       0  4395.4    0.07       0
  4465.3    0.16       0  4561.7    0.07       0  4989.8    0.07       0
  5003.2    0.07       0  5279.2    0.16       0  5319.8    0.07       0
Bank Sta=4989.8,5003.2
Exp/Cntr=0.3,0.1

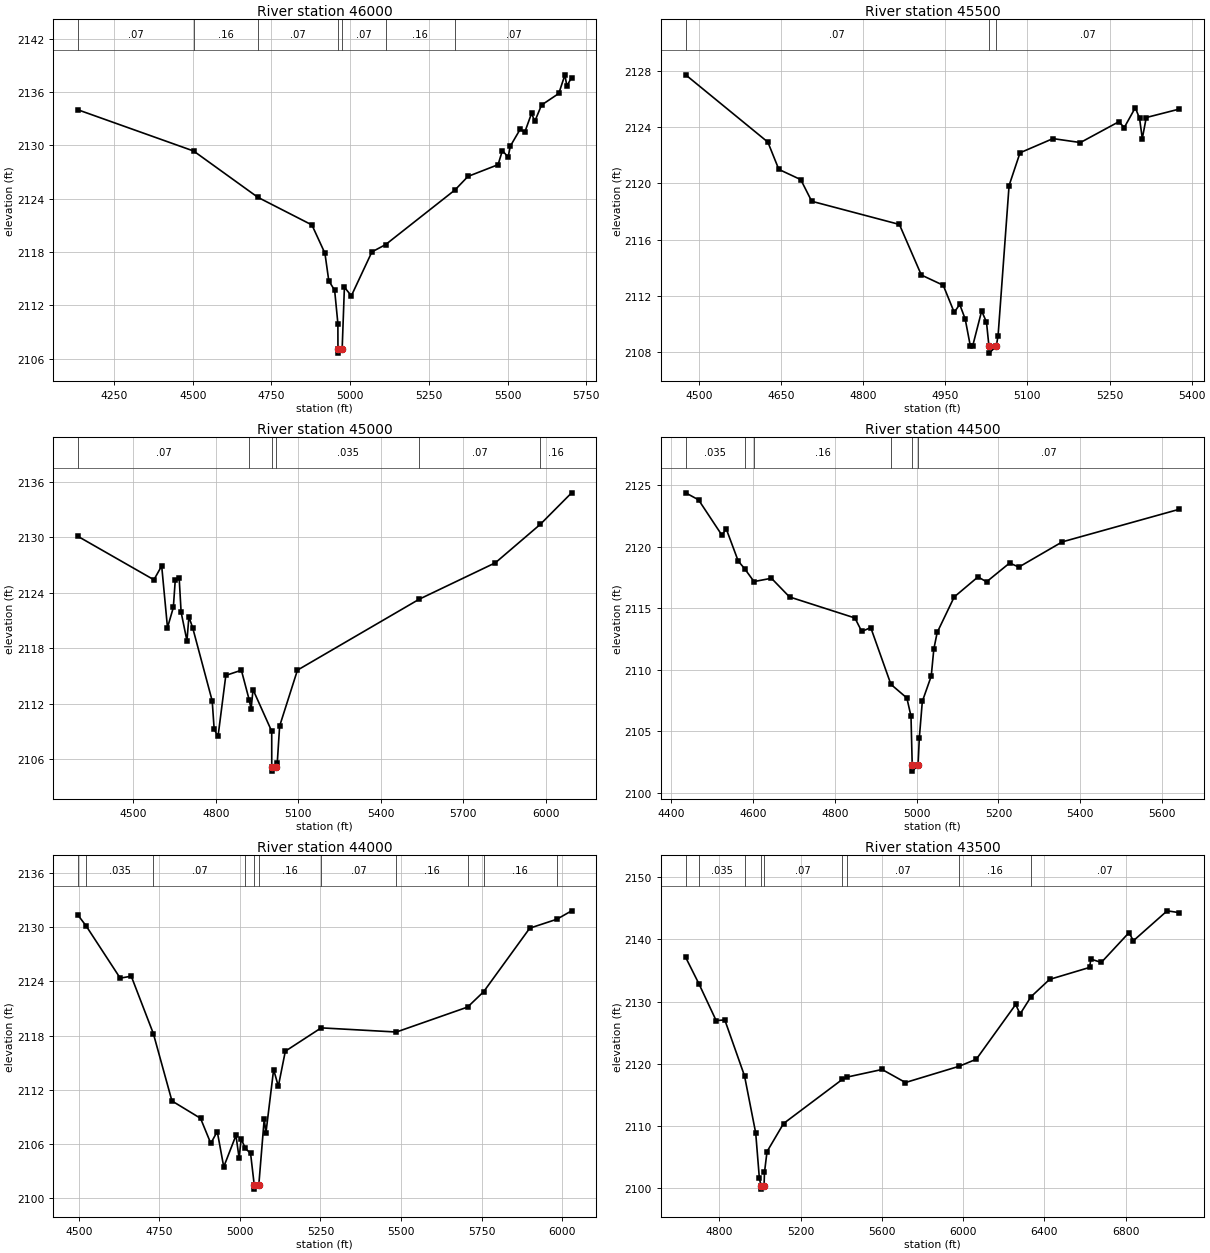
Type RM Length L Ch R = 1,46000,500,500,500
BEGIN DESCRIPTION:
East Cottonwood Creek 89.0
END DESCRIPTION:
XS GIS Cut Line= 3
      1357054.99      6900988.00      1357892.77      6900775.54
      1358554.96      6900538.01
#Sta/Elev= 30
  4135.7 2133.99  4502.6 2129.36  4706.8 2124.15  4878.5 2121.04  4919.8 2117.86
  4932.1 2114.76  4950.7 2113.69  4961.0 2109.94  4961.2 2107.12  4961.7 2106.62
  4974.6 2107.12  4981.7 2114.03  5003.8 2113.07  5069.1 2118.01  5112.6 2118.83
  5333.4 2124.99  5374.2 2126.50  5469.8 2127.82  5483.6 2129.41  5501.7 2128.67
  5509.0 2129.92  5539.8 2131.79  5554.8 2131.49  5576.1 2133.58  5586.7 2132.71
  5607.9 2134.53  5662.7 2135.83  5682.3 2137.93  5688.2 2136.67  5703.5 2137.62
#Mann=7,-1,0
  4135.7    0.07       0  4502.6    0.16       0  4706.8    0.07       0
  4961.2    0.07       0  4974.6    0.07       0  5112.6    0.16       0
  5333.4    0.07       0
Bank Sta=4961.2,4974.6
Exp/Cntr=0.3,0.1

Type RM Length L Ch R = 1,45500,500,500,500
BEGIN DESCRIPTION:
East Cottonwood Creek 88.0
END DESCRIPTION:
XS GIS Cut Line= 3
      1357554.99      6901138.00      1358078.69      6901165.09
      1358455.01      6901138.00
#Sta/Elev= 30
  4475.6 2127.73  4625.8 2122.94  4645.8 2121.00  4685.9 2120.27  4705.9 2118.73
  4866.1 2117.08  4906.2 2113.48  4946.2 2112.75  4966.3 2110.82  4976.3 2111.39
  4986.3 2110.35  4995.7 2108.43  5000.0 2108.43  5016.4 2110.92  5025.2 2110.13
  5029.7 2108.42  5030.2 2107.92  5043.1 2108.42  5046.4 2109.16  5066.5 2119.85
  5086.5 2122.18  5146.7 2123.19  5196.8 2122.91  5267.0 2124.39  5277.0 2123.98
  5297.1 2125.39  5304.9 2124.63  5309.9 2123.19  5317.1 2124.69  5377.3 2125.29
#Mann=3,-1,0
  4475.6    0.07       0  5029.7    0.07       0  5043.1    0.07       0
Bank Sta=5029.7,5043.1
Exp/Cntr=0.3,0.1

Type RM Length L Ch R = 1,45000,500,500,500
BEGIN DESCRIPTION:
East Cottonwood Creek 87.0
END DESCRIPTION:
XS GIS Cut Line= 3
      1357405.00      6901088.00      1357904.93      6901580.11
      1358855.04      6901037.98
#Sta/Elev= 30
  4298.5 2130.11  4574.3 2125.42  4602.6 2126.92  4623.7 2120.24  4645.0 2122.42
  4652.0 2125.40  4666.2 2125.61  4673.3 2121.91  4694.5 2118.82  4701.6 2121.41
  4715.7 2120.19  4786.4 2112.31  4793.5 2109.24  4807.6 2108.47  4835.9 2115.07
  4892.5 2115.63  4921.0 2112.42  4927.9 2111.43  4934.9 2113.53  5002.9 2109.02
  5003.0 2105.21  5003.5 2104.71  5017.2 2105.21  5023.1 2105.62  5031.7 2109.59
  5096.5 2115.64  5539.7 2123.32  5816.6 2127.26  5980.0 2131.42  6093.9 2134.83
#Mann=6,-1,0
  4298.5    0.07       0  4921.0   0.035       0  5003.0   0.035       0
  5017.2   0.035       0  5539.7    0.07       0  5980.0    0.16       0
Bank Sta=5003,5017.2
Exp/Cntr=0.3,0.1

Type RM Length L Ch R = 1,44500,500,500,500
BEGIN DESCRIPTION:
East Cottonwood Creek 86.0
END DESCRIPTION:
XS GIS Cut Line= 3
      1357604.98      6902238.01      1358116.64      6901999.07
      1358505.01      6901487.99
#Sta/Elev= 30
  4435.3 2124.40  4466.8 2123.83  4523.6 2120.97  4534.7 2121.45  4563.8 2118.85
  4579.4 2118.23  4602.4 2117.18  4645.0 2117.45  4689.2 2115.93  4849.1 2114.22
  4865.8 2113.12  4887.8 2113.44  4937.1 2108.82  4976.1 2107.71  4986.2 2106.23
  4989.2 2102.26  4989.7 2101.76  5003.5 2102.26  5006.6 2104.48  5013.9 2107.43
  5035.7 2109.49  5042.0 2111.68  5050.2 2113.04  5091.9 2115.93  5150.0 2117.56
  5170.9 2117.16  5227.4 2118.69  5249.9 2118.36  5356.0 2120.41  5641.9 2123.06
#Mann=6,-1,0
  4435.3   0.035       0  4579.4    0.07       0  4602.4    0.16       0
  4937.1    0.07       0  4989.2    0.07       0  5003.5    0.07       0
Bank Sta=4989.2,5003.5
Exp/Cntr=0.3,0.1

Type RM Length L Ch R = 1,44000,500,500,500
BEGIN DESCRIPTION:
East Cottonwood Creek 85.0
END DESCRIPTION:
XS GIS Cut Line= 3
      1357504.98      6902388.00      1358004.98      6902433.87
      1358955.00      6902038.00
#Sta/Elev= 30
  4497.9 2131.31  4523.6 2130.09  4628.5 2124.36  4662.9 2124.57  4731.4 2118.23
  4789.1 2110.78  4877.8 2108.86  4909.6 2106.09  4929.7 2107.40  4949.8 2103.49
  4987.7 2106.97  4997.5 2104.47  5003.9 2106.57  5017.0 2105.54  5033.1 2104.97
  5044.3 2101.53  5044.8 2101.03  5058.7 2101.53  5075.4 2108.79  5080.8 2107.27
  5104.6 2114.25  5119.2 2112.40  5140.9 2116.28  5252.2 2118.86  5485.5 2118.40
  5706.5 2121.16  5756.3 2122.86  5899.2 2129.88  5983.4 2130.87  6029.2 2131.80
#Mann=11,-1,0
  4497.9   0.045       0  4523.6   0.035       0  4731.4    0.07       0
  5017.0    0.16       0  5044.3    0.07       0  5058.7    0.16       0
  5252.2    0.07       0  5485.5    0.16       0  5706.5    0.07       0
  5756.3    0.16       0  5983.4    0.07       0
Bank Sta=5044.3,5058.7
Exp/Cntr=0.3,0.1

Type RM Length L Ch R = 1,43500,500,500,500
BEGIN DESCRIPTION:
East Cottonwood Creek 84.0
END DESCRIPTION:
XS GIS Cut Line= 3
      1357454.96      6902737.99      1357815.85      6902797.74
      1359554.96      6901688.03
#Sta/Elev= 30
  4634.2 2137.13  4700.3 2132.82  4784.3 2126.96  4826.8 2127.07  4923.8 2118.08
  4978.9 2108.89  4997.0 2101.58  5005.6 2100.36  5006.1 2099.86  5020.0 2100.36
  5022.1 2102.55  5034.6 2105.89  5116.0 2110.41  5405.1 2117.50  5429.0 2117.88
  5600.9 2119.10  5716.0 2117.00  5980.4 2119.62  6064.6 2120.75  6258.4 2129.55
  6280.1 2128.02  6333.9 2130.80  6425.0 2133.58  6622.2 2135.51  6628.1 2136.85
  6679.7 2136.31  6816.0 2141.10  6837.7 2139.80  7003.8 2144.61  7063.0 2144.32
#Mann=9,-1,0
  4634.2   0.045       0  4700.3   0.035       0  4923.8    0.07       0
  5005.6    0.07       0  5020.0    0.07       0  5405.1    0.16       0
  5429.0    0.07       0  5980.4    0.16       0  6333.9    0.07       0
Bank Sta=5005.6,5020
Exp/Cntr=0.3,0.1

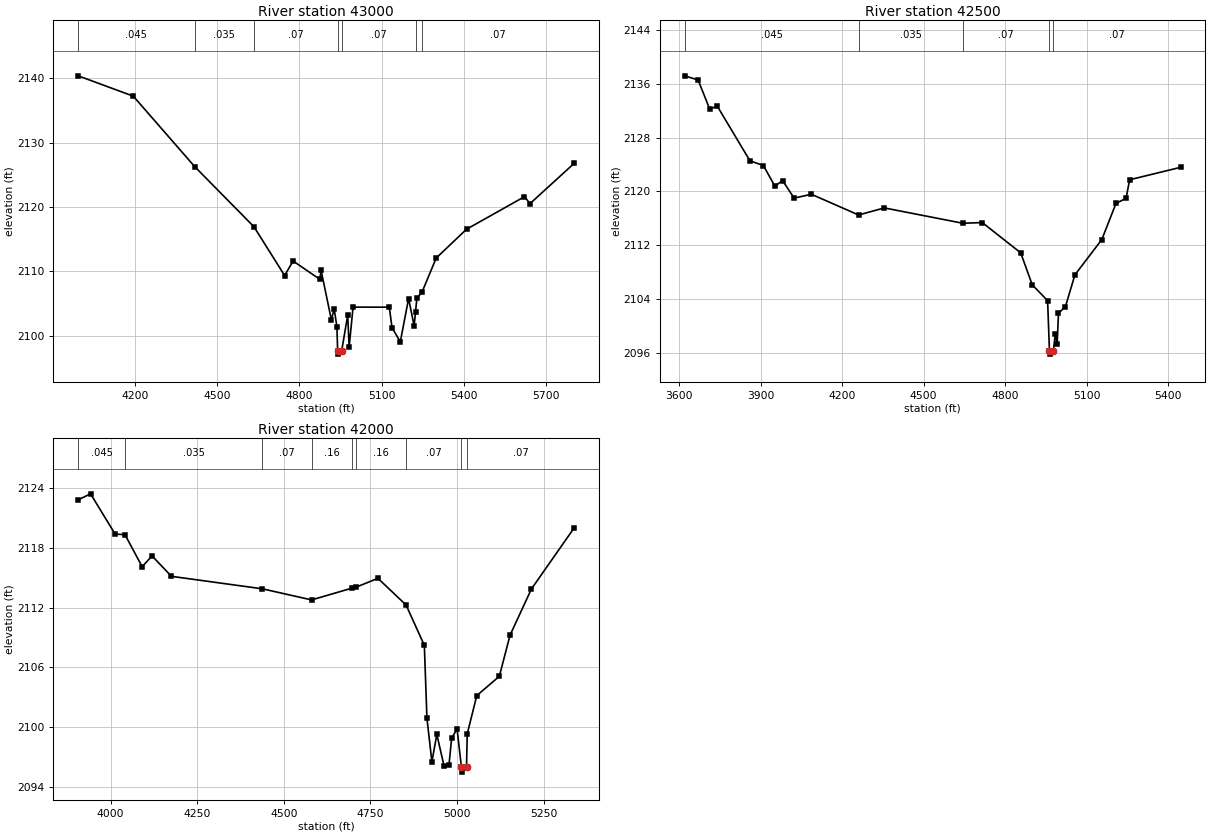
Type RM Length L Ch R = 1,43000,500,500,500
BEGIN DESCRIPTION:
East Cottonwood Creek 83.0
END DESCRIPTION:
XS GIS Cut Line= 3
      1357104.98      6903088.00      1358107.51      6903184.82
      1358904.96      6903088.01
#Sta/Elev= 30
  3992.8 2140.38  4193.8 2137.22  4417.9 2126.27  4634.6 2116.90  4746.3 2109.33
  4777.3 2111.59  4874.5 2108.75  4879.5 2110.12  4917.1 2102.43  4927.2 2104.16
  4937.2 2101.36  4939.9 2097.61  4940.4 2097.11  4954.5 2097.61  4976.7 2103.17
  4981.8 2098.20  4996.2 2104.42  5128.4 2104.41  5138.5 2101.21  5168.7 2099.02
  5198.9 2105.75  5219.1 2101.50  5224.2 2103.67  5229.2 2105.80  5248.0 2106.76
  5299.7 2112.05  5410.5 2116.53  5622.0 2121.59  5642.2 2120.51  5803.3 2126.77
#Mann=7,-1,0
  3992.8   0.045       0  4417.9   0.035       0  4634.6    0.07       0
  4939.9    0.07       0  4954.5    0.07       0  5224.2    0.16       0
  5248.0    0.07       0
Bank Sta=4939.9,4954.5
Exp/Cntr=0.3,0.1

Type RM Length L Ch R = 1,42500,500,500,500
BEGIN DESCRIPTION:
East Cottonwood Creek 82.0
END DESCRIPTION:
XS GIS Cut Line= 3
      1357355.03      6904387.97      1358354.98      6903436.35
      1358755.01      6903238.00
#Sta/Elev= 30
  3619.6 2137.18  3669.1 2136.56  3711.6 2132.25  3739.9 2132.65  3860.0 2124.54
  3909.5 2123.84  3951.9 2120.76  3980.2 2121.60  4022.6 2118.99  4086.5 2119.56
  4260.1 2116.48  4355.1 2117.53  4644.0 2115.25  4715.9 2115.35  4857.4 2110.85
  4899.9 2106.09  4956.5 2103.74  4963.3 2096.28  4963.8 2095.78  4978.0 2096.28
  4984.8 2098.81  4991.7 2097.27  4996.6 2101.87  5022.3 2102.85  5057.0 2107.57
  5156.3 2112.83  5208.3 2118.19  5245.6 2118.97  5258.7 2121.72  5446.5 2123.57
#Mann=5,-1,0
  3619.6   0.045       0  4260.1   0.035       0  4644.0    0.07       0
  4963.3    0.07       0  4978.0    0.07       0
Bank Sta=4963.3,4978
Exp/Cntr=0.3,0.1

Type RM Length L Ch R = 1,42000,500,500,500
BEGIN DESCRIPTION:
East Cottonwood Creek 81.0
END DESCRIPTION:
XS GIS Cut Line= 3
      1357854.98      6904538.03      1358576.35      6903716.62
      1358655.00      6903388.00
#Sta/Elev= 30
  3906.8 2122.78  3942.4 2123.38  4013.3 2119.35  4041.8 2119.29  4091.4 2116.08
  4119.8 2117.17  4175.9 2115.12  4438.3 2113.87  4580.3 2112.76  4697.7 2113.95
  4707.5 2114.02  4771.7 2114.92  4852.9 2112.25  4905.6 2108.21  4913.1 2100.91
  4927.4 2096.56  4941.6 2099.30  4962.5 2096.13  4976.7 2096.24  4984.3 2098.89
  5000.0 2099.86  5012.6 2096.02  5013.1 2095.52  5027.3 2096.02  5029.4 2099.35
  5056.9 2103.18  5122.0 2105.11  5152.8 2109.22  5214.5 2113.85  5337.9 2119.97
#Mann=9,-1,0
  3906.8   0.045       0  4041.8   0.035       0  4438.3    0.07       0
  4580.3    0.16       0  4697.7    0.07       0  4707.5    0.16       0
  4852.9    0.07       0  5012.6    0.07       0  5027.3    0.07       0
Bank Sta=5012.6,5027.3
Exp/Cntr=0.3,0.1