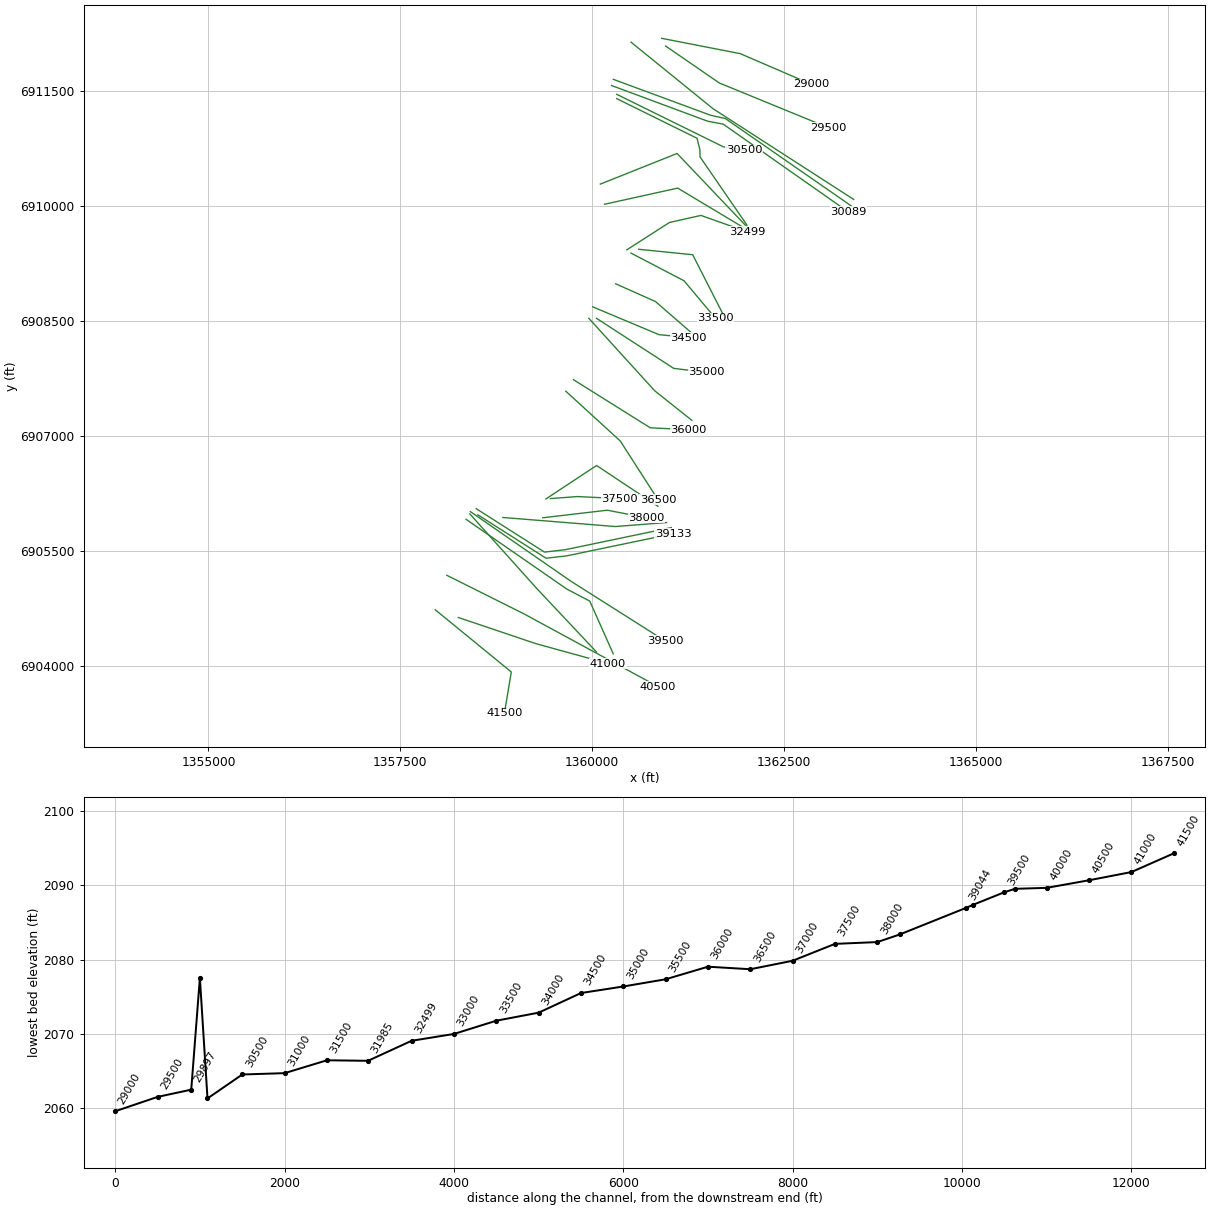
HEC-RAS study East Cottonwood Creek.prj: East Cottonwood Creek Base Level Engineering

--- East Cottonwood Creek.g01 (geometry) --- (continued)

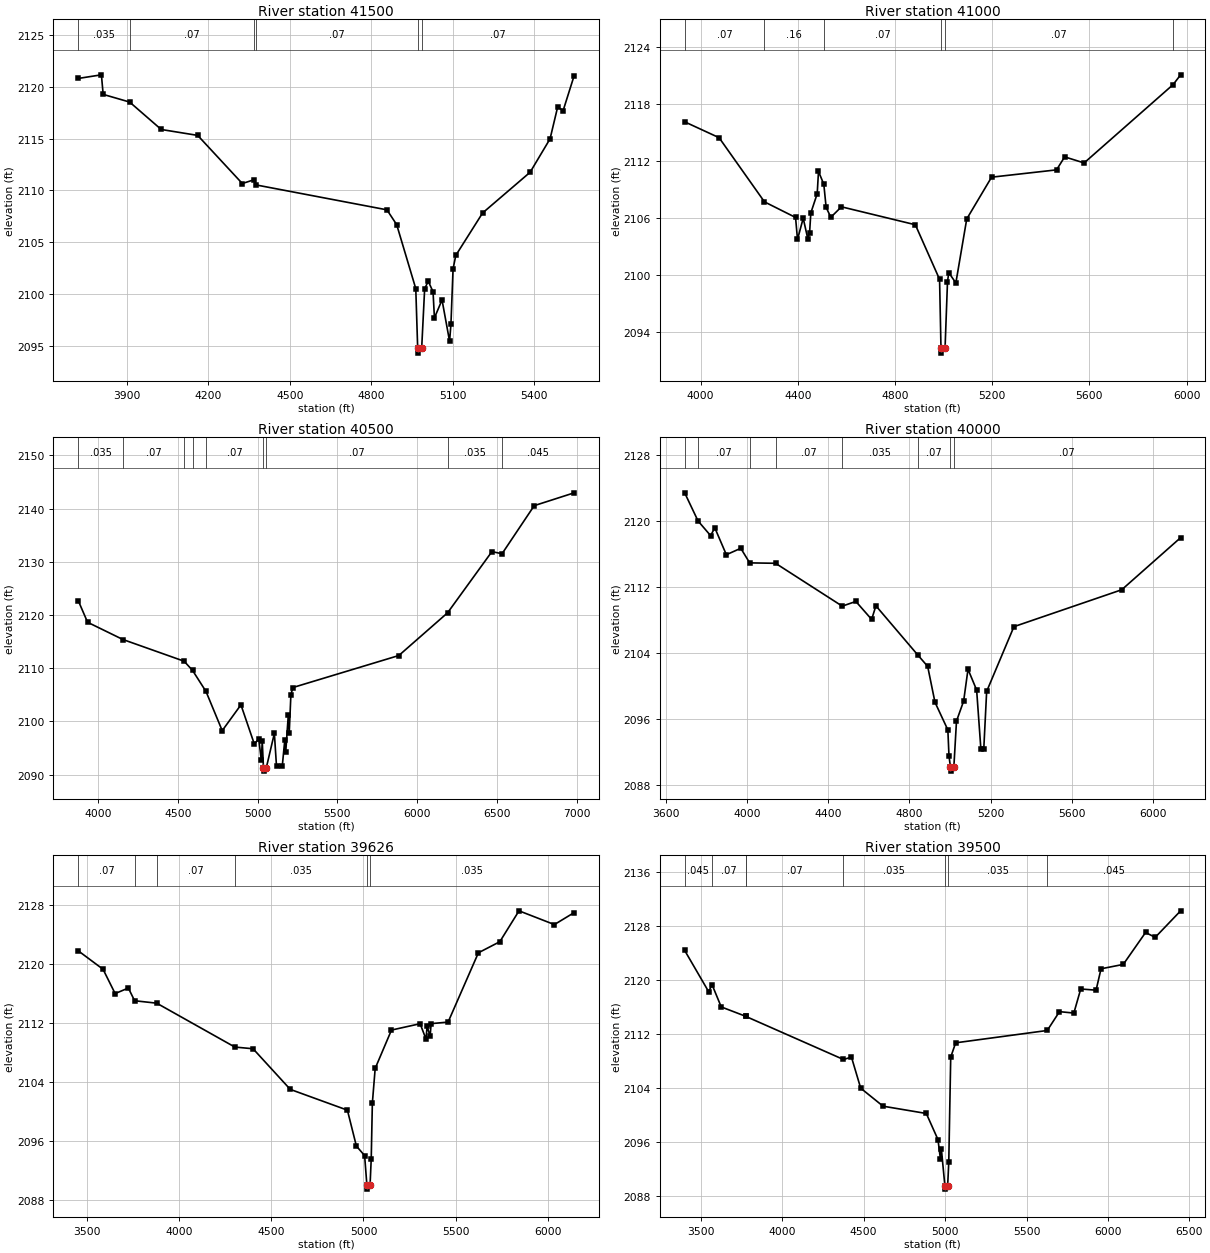
Type RM Length L Ch R = 1,41500,500,500,500
BEGIN DESCRIPTION:
East Cottonwood Creek 80.0
END DESCRIPTION:
XS GIS Cut Line= 3
      1357955.01      6904737.99      1358944.95      6903927.98
      1358855.00      6903388.02
#Sta/Elev= 30
  3720.9 2120.80  3806.3 2121.15  3812.8 2119.26  3910.3 2118.52  4026.7 2115.87
  4160.9 2115.30  4325.3 2110.65  4368.8 2111.02  4377.0 2110.51  4857.9 2108.11
  4893.8 2106.68  4964.1 2100.50  4971.1 2094.77  4971.6 2094.27  4985.9 2094.77
  4996.8 2100.49  5010.1 2101.21  5027.7 2100.20  5032.8 2097.67  5060.8 2099.41
  5088.6 2095.42  5093.6 2097.04  5101.4 2102.40  5111.5 2103.71  5210.3 2107.81
  5385.2 2111.74  5458.7 2114.97  5486.6 2118.04  5506.9 2117.70  5547.4 2121.07
#Mann=6,-1,0
  3720.9   0.035       0  3910.3    0.07       0  4368.8    0.16       0
  4377.0    0.07       0  4971.1    0.07       0  4985.9    0.07       0
Bank Sta=4971.1,4985.9
Exp/Cntr=0.3,0.1

Type RM Length L Ch R = 1,41000,500,500,500
BEGIN DESCRIPTION:
East Cottonwood Creek 79.0
END DESCRIPTION:
XS GIS Cut Line= 3
      1358255.03      6904637.99      1359264.80      6904297.29
      1360205.00      6904038.00
#Sta/Elev= 30
  3934.3 2116.12  4075.9 2114.45  4262.7 2107.69  4390.6 2106.05  4398.6 2103.73
  4422.1 2105.97  4440.9 2103.81  4448.3 2104.43  4453.5 2106.53  4479.7 2108.55
  4485.0 2110.90  4506.9 2109.54  4516.5 2107.10  4535.8 2106.07  4579.4 2107.17
  4883.6 2105.28  4983.3 2099.53  4989.1 2092.26  4989.6 2091.76  5005.8 2092.26
  5015.9 2099.27  5021.1 2100.24  5050.3 2099.15  5095.1 2105.89  5197.3 2110.29
  5464.7 2111.06  5498.1 2112.43  5578.1 2111.79  5944.4 2120.04  5975.3 2121.07
#Mann=6,-1,0
  3934.3    0.07       0  4262.7    0.16       0  4506.9    0.07       0
  4989.1    0.07       0  5005.8    0.07       0  5944.4   0.035       0
Bank Sta=4989.1,5005.8
Exp/Cntr=0.3,0.1

Type RM Length L Ch R = 1,40500,500,500,500
BEGIN DESCRIPTION:
East Cottonwood Creek 78.0
END DESCRIPTION:
XS GIS Cut Line= 3
      1358104.97      6905188.01      1359110.44      6904685.17
      1360855.00      6903738.00
#Sta/Elev= 30
  3875.8 2122.72  3934.5 2118.64  4155.9 2115.40  4539.8 2111.32  4592.9 2109.58
  4677.0 2105.63  4778.6 2098.27  4896.0 2103.12  4979.8 2095.76  5007.7 2096.69
  5023.9 2092.68  5029.6 2096.29  5037.4 2091.16  5037.9 2090.66  5054.1 2091.16
  5105.6 2097.77  5119.0 2091.56  5155.0 2091.55  5171.2 2096.60  5176.9 2094.27
  5193.1 2101.28  5198.7 2097.85  5209.2 2105.00  5221.4 2106.37  5885.9 2112.39
  6191.6 2120.42  6469.5 2131.92  6533.0 2131.52  6734.8 2140.56  6985.1 2142.97
#Mann=9,-1,0
  3875.8   0.035       0  4155.9    0.07       0  4539.8    0.16       0
  4592.9   0.035       0  4677.0    0.07       0  5037.4    0.07       0
  5054.1    0.07       0  6191.6   0.035       0  6533.0   0.045       0
Bank Sta=5037.4,5054.1
Exp/Cntr=0.3,0.1

Type RM Length L Ch R = 1,40000,374,374,374
BEGIN DESCRIPTION:
East Cottonwood Creek 77.0
END DESCRIPTION:
XS GIS Cut Line= 3
      1358404.98      6905988.02      1359277.27      6905015.64
      1360054.99      6904188.01
#Sta/Elev= 30
  3693.7 2123.41  3759.4 2120.00  3821.2 2118.22  3842.1 2119.16  3898.9 2115.90
  3969.9 2116.68  4013.8 2114.91  4141.2 2114.86  4469.5 2109.66  4536.6 2110.23
  4614.3 2108.05  4635.3 2109.70  4842.3 2103.71  4890.2 2102.35  4926.1 2098.00
  4989.6 2094.64  4995.1 2091.50  5002.2 2090.14  5002.7 2089.64  5019.1 2090.14
  5032.1 2095.71  5067.3 2098.14  5088.8 2102.00  5131.3 2099.48  5152.3 2092.28
  5166.4 2092.31  5180.6 2099.31  5314.9 2107.17  5845.8 2111.65  6135.7 2117.97
#Mann=8,-1,0
  3693.7   0.045       0  3759.4    0.07       0  4013.8   0.045       0
  4141.2    0.07       0  4469.5   0.035       0  4842.3    0.07       0
  5002.2    0.07       0  5019.1    0.07       0
Bank Sta=5002.2,5019.1
Exp/Cntr=0.3,0.1

Type RM Length L Ch R = 1,39626,126,126,126
BEGIN DESCRIPTION:
East Cottonwood Creek 76.5
END DESCRIPTION:
XS GIS Cut Line= 4
      1358356.41      6905917.44      1359670.28      6905007.41
      1359967.49      6904851.49      1360273.04      6904164.01
#Sta/Elev= 30
  3454.8 2121.77  3589.3 2119.27  3654.8 2115.98  3726.4 2116.73  3760.2 2115.01
  3880.0 2114.68  4303.2 2108.74  4401.9 2108.51  4603.4 2103.01  4912.8 2100.20
  4961.5 2095.34  5006.1 2094.05  5018.5 2090.01  5019.0 2089.51  5035.5 2090.01
  5041.9 2093.62  5048.0 2101.16  5063.3 2105.85  5151.5 2111.04  5306.8 2111.90
  5338.7 2109.80  5344.4 2111.57  5360.8 2110.20  5366.4 2111.91  5458.2 2112.12
  5622.3 2121.50  5738.4 2123.00  5842.3 2127.18  6033.9 2125.32  6141.0 2126.94
#Mann=6,-1,0
  3454.8    0.07       0  3760.2   0.045       0  3880.0    0.07       0
  4303.2   0.035       0  5018.5   0.035       0  5035.5   0.035       0
Bank Sta=5018.5,5035.5
Exp/Cntr=0.3,0.1

Type RM Length L Ch R = 1,39500,367,367,367
BEGIN DESCRIPTION:
East Cottonwood Creek 76.0
END DESCRIPTION:
XS GIS Cut Line= 3
      1358411.93      6906018.16      1359725.84      6905108.10
      1360946.67      6904334.12
#Sta/Elev= 30
  3401.7 2124.42  3548.3 2118.33  3570.2 2119.32  3626.0 2116.05  3775.1 2114.67
  3775.5 2114.66  4376.2 2108.26  4425.3 2108.61  4482.0 2104.01  4619.2 2101.34
  4884.7 2100.26  4956.3 2096.39  4971.2 2093.55  4977.3 2094.95  4998.7 2089.55
  4999.2 2089.05  5015.7 2089.55  5022.5 2093.01  5034.5 2108.61  5064.8 2110.73
  5627.0 2112.56  5702.0 2115.35  5790.2 2115.14  5832.5 2118.71  5926.6 2118.53
  5957.1 2121.70  6093.5 2122.35  6230.4 2127.08  6289.6 2126.36  6445.5 2130.29
#Mann=8,-1,0
  3401.7   0.045       0  3570.2    0.07       0  3775.1   0.045       0
  3775.5    0.07       0  4376.2   0.035       0  4998.7   0.035       0
  5015.7   0.035       0  5627.0   0.045       0
Bank Sta=4998.7,5015.7
Exp/Cntr=0.3,0.1

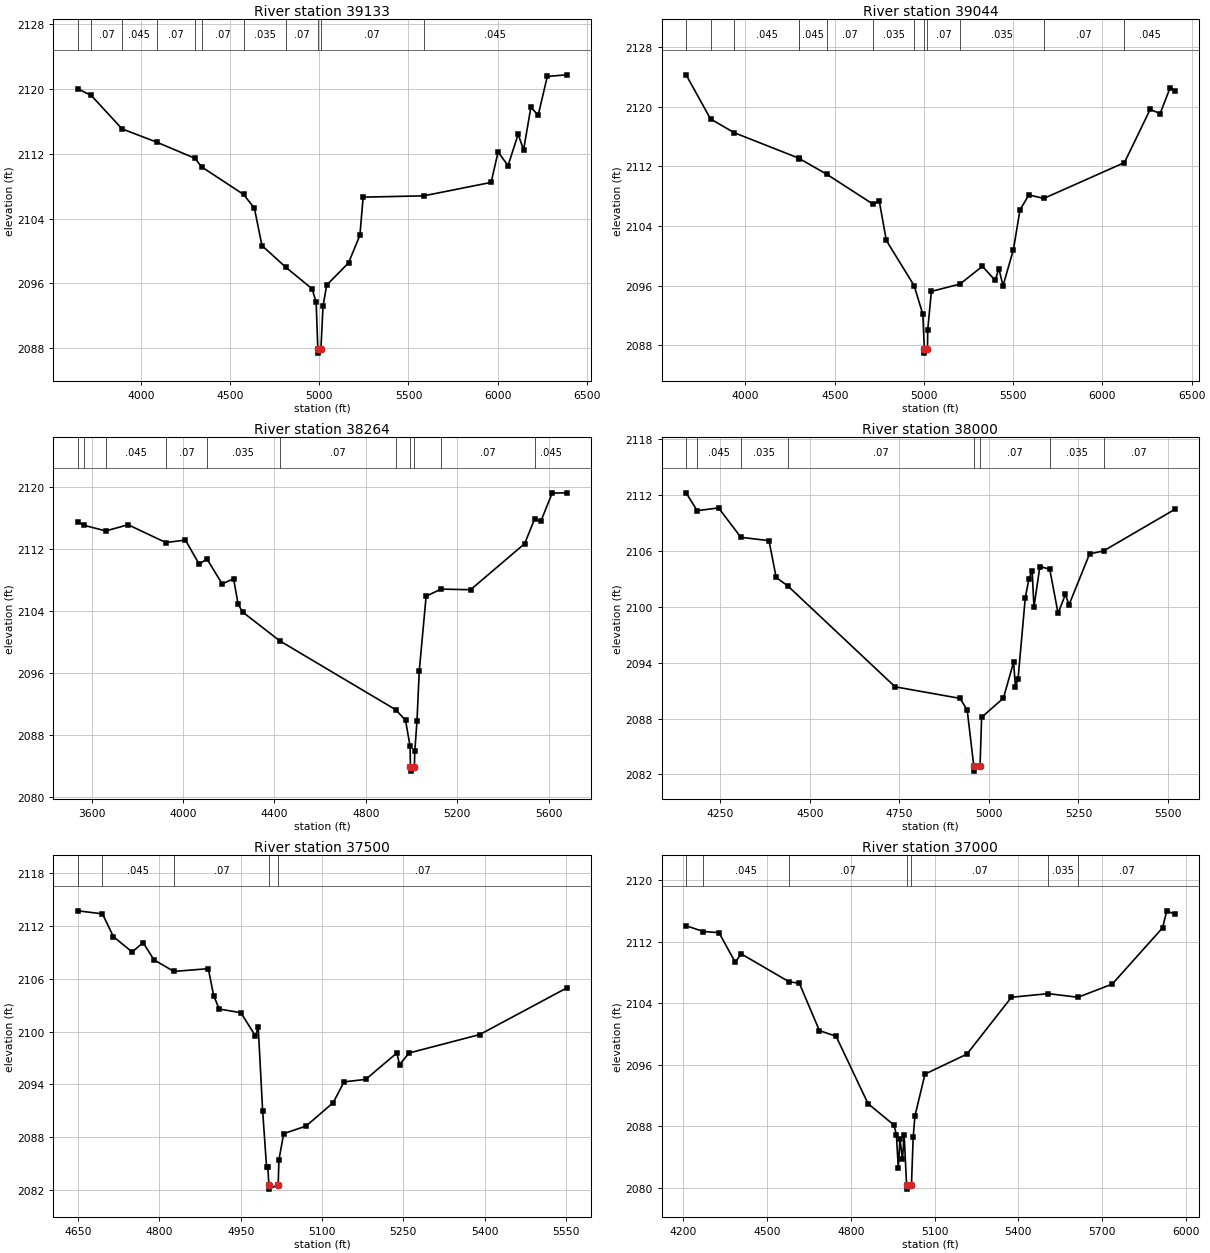
Type RM Length L Ch R = 1,39133,89,89,89
BEGIN DESCRIPTION:
East Cottonwood Creek 75.5
END DESCRIPTION:
XS GIS Cut Line= 4
      1358509.15      6905976.50      1359398.05      6905410.52
      1359668.88      6905441.77      1361050.43      6905729.88
#Sta/Elev= 30
  3647.7 2120.02  3722.4 2119.21  3895.5 2115.07  4088.5 2113.44  4302.7 2111.45
  4342.4 2110.36  4576.3 2106.97  4636.8 2105.27  4679.2 2100.66  4812.6 2097.98
  4960.2 2095.31  4982.8 2093.63  4992.2 2087.87  4992.7 2087.37  5009.4 2087.87
  5021.2 2093.15  5041.7 2095.77  5164.2 2098.52  5227.9 2101.94  5246.0 2106.64
  5584.9 2106.80  5963.0 2108.46  6001.9 2112.22  6057.9 2110.53  6114.3 2114.41
  6144.9 2112.48  6185.8 2117.75  6226.6 2116.75  6277.7 2121.55  6385.4 2121.75
#Mann=11,-1,0
  3647.7   0.045       0  3722.4    0.07       0  3895.5   0.045       0
  4088.5    0.07       0  4302.7   0.045       0  4342.4    0.07       0
  4576.3   0.035       0  4812.6    0.07       0  4992.2    0.07       0
  5009.4    0.07       0  5584.9   0.045       0
Bank Sta=4992.2,5009.4
Exp/Cntr=0.3,0.1

Type RM Length L Ch R = 1,39044,780,780,780
BEGIN DESCRIPTION:
East Cottonwood Creek 75.0
END DESCRIPTION:
XS GIS Cut Line= 4
      1358488.30      6906056.37      1359377.22      6905490.38
      1359648.05      6905521.63      1361029.97      6905809.82
#Sta/Elev= 30
  3667.3 2124.26  3804.3 2118.34  3937.5 2116.49  4297.8 2113.09  4302.0 2113.03
  4454.9 2110.93  4717.0 2106.88  4749.1 2107.39  4789.3 2102.04  4944.9 2095.99
  4993.7 2092.15  5002.4 2087.43  5002.9 2086.93  5019.7 2087.43  5021.3 2090.09
  5041.7 2095.21  5202.1 2096.20  5327.7 2098.58  5399.2 2096.68  5419.7 2098.27
  5443.3 2095.97  5501.4 2100.83  5538.2 2106.15  5588.2 2108.15  5671.6 2107.68
  6123.5 2112.49  6267.5 2119.62  6323.4 2119.06  6379.9 2122.56  6405.4 2122.04
#Mann=13,-1,0
  3667.3   0.045       0  3804.3    0.07       0  3937.5   0.045       0
  4297.8    0.07       0  4302.0   0.045       0  4454.9    0.07       0
  4717.0   0.035       0  4944.9    0.07       0  5002.4    0.07       0
  5019.7    0.07       0  5202.1   0.035       0  5671.6    0.07       0
  6123.5   0.045       0
Bank Sta=5002.4,5019.7
Exp/Cntr=0.3,0.1

Type RM Length L Ch R = 1,38264,264,264,264
BEGIN DESCRIPTION:
East Cottonwood Creek 74.0
END DESCRIPTION:
XS GIS Cut Line= 3
      1358835.58      6905941.76      1360300.83      6905823.71
      1360967.50      6905875.79
#Sta/Elev= 30
  3539.4 2115.57  3566.1 2115.11  3661.6 2114.38  3759.5 2115.18  3924.4 2112.88
  4010.3 2113.20  4070.5 2110.08  4104.3 2110.78  4170.9 2107.54  4221.0 2108.20
  4241.1 2104.89  4261.2 2103.89  4423.6 2100.18  4930.9 2091.29  4973.5 2089.93
  4993.5 2086.59  4994.9 2083.87  4995.4 2083.37  5012.2 2083.87  5014.0 2085.94
  5023.6 2089.79  5033.6 2096.31  5063.7 2105.96  5129.2 2106.87  5258.2 2106.79
  5495.0 2112.74  5538.1 2115.89  5565.3 2115.60  5615.4 2119.26  5678.1 2119.30
#Mann=11,-1,0
  3539.4   0.045       0  3566.1    0.07       0  3661.6   0.045       0
  3924.4    0.07       0  4104.3   0.035       0  4423.6    0.07       0
  4930.9   0.035       0  4994.9   0.035       0  5012.2   0.035       0
  5129.2    0.07       0  5538.1   0.045       0
Bank Sta=4994.9,5012.2
Exp/Cntr=0.3,0.1

Type RM Length L Ch R = 1,38000,500,500,500
BEGIN DESCRIPTION:
East Cottonwood Creek 73.0
END DESCRIPTION:
XS GIS Cut Line= 3
      1359354.97      6905938.00      1360195.30      6906036.68
      1360705.03      6905937.99
#Sta/Elev= 30
  4153.9 2112.26  4184.8 2110.34  4244.5 2110.64  4307.0 2107.48  4385.5 2107.12
  4405.6 2103.16  4437.9 2102.26  4737.9 2091.41  4919.2 2090.17  4939.3 2088.92
  4957.8 2082.85  4958.3 2082.35  4975.1 2082.85  4979.6 2088.14  5040.4 2090.19
  5068.9 2094.06  5074.0 2091.43  5081.2 2092.21  5101.6 2101.00  5111.7 2102.99
  5120.7 2103.90  5125.8 2099.99  5142.3 2104.34  5169.9 2104.05  5193.2 2099.31
  5213.6 2101.34  5223.8 2100.23  5281.1 2105.69  5320.4 2106.02  5519.2 2110.48
#Mann=8,-1,0
  4153.9    0.07       0  4184.8   0.045       0  4307.0   0.035       0
  4437.9    0.07       0  4957.8    0.07       0  4975.1    0.07       0
  5169.9   0.035       0  5320.4    0.07       0
Bank Sta=4957.8,4975.1
Exp/Cntr=0.3,0.1

Type RM Length L Ch R = 1,37500,500,500,500
BEGIN DESCRIPTION:
East Cottonwood Creek 72.0
END DESCRIPTION:
XS GIS Cut Line= 3
      1359455.00      6906188.00      1359804.59      6906214.59
      1360355.04      6906188.00
#Sta/Elev= 30
  4649.4 2113.71  4694.8 2113.37  4715.0 2110.78  4749.7 2109.03  4769.8 2110.11
  4789.8 2108.15  4826.5 2106.83  4890.1 2107.14  4900.1 2104.07  4910.2 2102.56
  4950.3 2102.14  4977.2 2099.49  4982.2 2100.52  4990.4 2090.98  4997.7 2084.57
  5000.0 2084.57  5001.8 2082.61  5002.3 2082.11  5019.1 2082.61  5020.4 2085.42
  5029.2 2088.41  5070.5 2089.27  5120.6 2091.93  5140.6 2094.29  5180.6 2094.57
  5238.0 2097.57  5243.0 2096.25  5260.7 2097.57  5390.9 2099.66  5551.1 2104.94
#Mann=5,-1,0
  4649.4    0.07       0  4694.8   0.045       0  4826.5    0.07       0
  5001.8    0.07       0  5019.1    0.07       0
Bank Sta=5001.8,5019.1
Exp/Cntr=0.3,0.1

Type RM Length L Ch R = 1,37000,500,500,500
BEGIN DESCRIPTION:
East Cottonwood Creek 71.0
END DESCRIPTION:
XS GIS Cut Line= 3
      1359396.77      6906183.58      1360055.73      6906619.32
      1360855.03      6906087.98
#Sta/Elev= 30
  4210.0 2114.09  4271.7 2113.34  4327.8 2113.19  4386.0 2109.34  4407.0 2110.44
  4578.4 2106.81  4615.5 2106.61  4687.4 2100.45  4747.1 2099.72  4861.4 2090.96
  4954.7 2088.16  4963.2 2086.86  4969.8 2082.55  4975.8 2086.38  4984.8 2083.70
  4990.8 2086.91  4999.6 2080.34  5000.1 2079.84  5016.9 2080.34  5023.1 2086.57
  5029.3 2089.33  5065.4 2094.80  5215.7 2097.40  5375.0 2104.79  5506.8 2105.26
  5613.2 2104.79  5735.8 2106.50  5916.2 2113.82  5931.2 2116.03  5959.8 2115.58
#Mann=7,-1,0
  4210.0    0.07       0  4271.7   0.045       0  4578.4    0.07       0
  4999.6    0.07       0  5016.9    0.07       0  5506.8   0.035       0
  5613.2    0.07       0
Bank Sta=4999.6,5016.9
Exp/Cntr=0.3,0.1

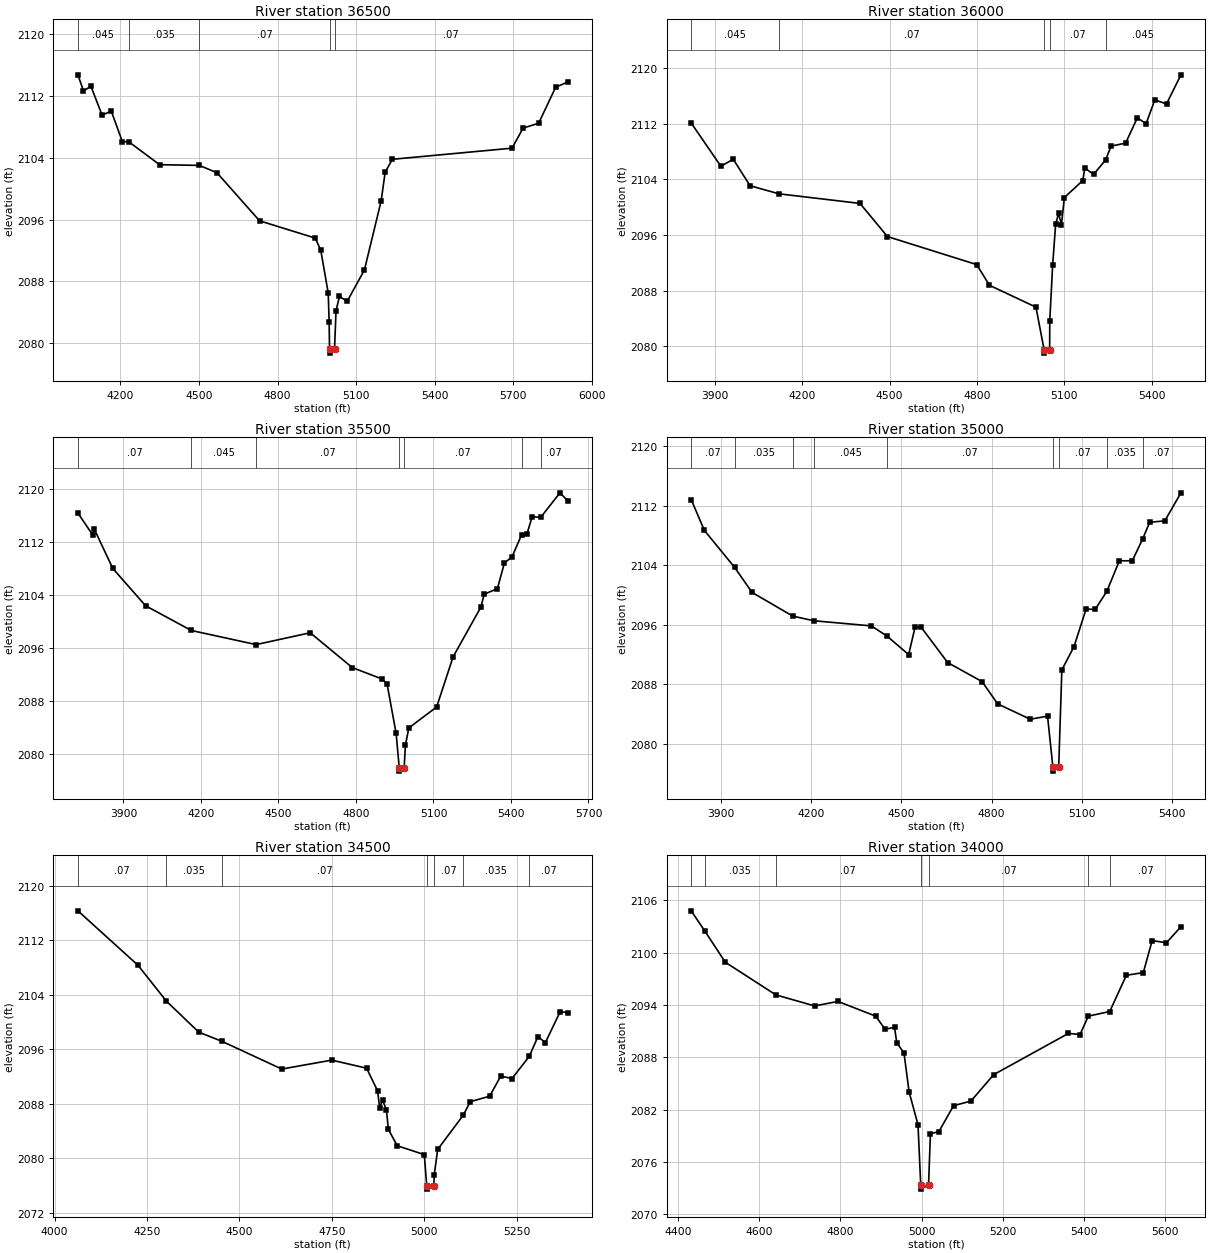
Type RM Length L Ch R = 1,36500,500,500,500
BEGIN DESCRIPTION:
East Cottonwood Creek 70.0
END DESCRIPTION:
XS GIS Cut Line= 3
      1359654.97      6907588.03      1360365.23      6906938.32
      1360855.09      6906174.86
#Sta/Elev= 30
  4037.4 2114.75  4058.7 2112.67  4087.1 2113.27  4129.6 2109.53  4164.8 2110.05
  4207.3 2106.07  4230.7 2106.10  4349.2 2103.11  4500.8 2103.02  4568.1 2102.07
  4730.9 2095.84  4943.7 2093.60  4964.6 2092.02  4993.0 2086.49  4996.5 2082.71
  4998.0 2079.20  4998.5 2078.70  5017.1 2079.20  5022.8 2084.18  5036.0 2086.06
  5065.1 2085.40  5131.1 2089.46  5195.2 2098.43  5210.4 2102.15  5238.0 2103.81
  5694.7 2105.25  5737.0 2107.85  5796.4 2108.48  5861.2 2113.14  5907.1 2113.82
#Mann=5,-1,0
  4037.4   0.045       0  4230.7   0.035       0  4500.8    0.07       0
  4998.0    0.07       0  5017.1    0.07       0
Bank Sta=4998,5017.1
Exp/Cntr=0.3,0.1

Type RM Length L Ch R = 1,36000,500,500,500
BEGIN DESCRIPTION:
East Cottonwood Creek 69.0
END DESCRIPTION:
XS GIS Cut Line= 3
      1359755.03      6907737.98      1360755.23      6907110.94
      1361254.43      6907086.33
#Sta/Elev= 30
  3819.5 2112.08  3921.4 2105.87  3963.8 2106.87  4021.6 2103.07  4120.6 2101.91
  4398.7 2100.53  4493.0 2095.77  4799.1 2091.75  4842.9 2088.78  5002.4 2085.64
  5030.3 2079.54  5030.8 2079.04  5049.4 2079.54  5049.8 2083.69  5059.8 2091.75
  5069.9 2097.51  5079.9 2099.09  5089.9 2097.49  5099.9 2101.37  5163.1 2103.82
  5170.0 2105.63  5200.0 2104.69  5241.4 2106.77  5260.1 2108.76  5310.1 2109.18
  5350.2 2112.83  5380.2 2111.97  5410.3 2115.39  5450.3 2114.81  5499.8 2118.99
#Mann=5,-1,0
  3819.5   0.045       0  4120.6    0.07       0  5030.3    0.07       0
  5049.4    0.07       0  5241.4   0.045       0
Bank Sta=5030.3,5049.4
Exp/Cntr=0.3,0.1

Type RM Length L Ch R = 1,35500,500,500,500
BEGIN DESCRIPTION:
East Cottonwood Creek 68.0
END DESCRIPTION:
XS GIS Cut Line= 3
      1359954.98      6908538.02      1360813.15      6907593.58
      1361297.79      6907207.86
#Sta/Elev= 30
  3723.9 2116.41  3780.4 2113.14  3787.8 2113.94  3858.7 2108.04  3985.8 2102.38
  4162.7 2098.64  4413.5 2096.50  4623.0 2098.29  4785.9 2093.02  4899.4 2091.32
  4920.3 2090.58  4955.5 2083.06  4967.6 2077.85  4968.1 2077.35  4986.7 2077.85
  4991.3 2081.27  5004.8 2083.90  5112.2 2087.05  5176.2 2094.66  5283.5 2102.17
  5296.3 2104.12  5347.4 2104.97  5374.8 2108.88  5403.7 2109.74  5441.4 2113.16
  5461.4 2113.20  5482.2 2115.88  5514.8 2115.74  5589.5 2119.47  5619.4 2118.29
#Mann=7,-1,0
  3723.9    0.07       0  4162.7   0.045       0  4413.5    0.07       0
  4967.6    0.07       0  4986.7    0.07       0  5441.4   0.045       0
  5514.8    0.07       0
Bank Sta=4967.6,4986.7
Exp/Cntr=0.3,0.1

Type RM Length L Ch R = 1,35000,500,500,500
BEGIN DESCRIPTION:
East Cottonwood Creek 67.0
END DESCRIPTION:
XS GIS Cut Line= 3
      1360054.97      6908538.02      1361061.40      6907885.41
      1361488.19      6907832.93
#Sta/Elev= 30
  3800.5 2112.81  3844.4 2108.67  3944.9 2103.72  4003.1 2100.35  4138.6 2097.17
  4208.5 2096.55  4400.1 2095.86  4452.5 2094.48  4524.1 2092.01  4545.2 2095.65
  4566.3 2095.65  4654.0 2090.94  4768.7 2088.38  4820.1 2085.40  4928.9 2083.34
  4986.2 2083.76  5004.1 2076.88  5004.6 2076.38  5023.3 2076.88  5033.8 2089.95
  5074.2 2093.08  5114.5 2098.12  5144.7 2098.07  5183.4 2100.50  5225.3 2104.60
  5268.1 2104.59  5302.7 2107.53  5326.0 2109.76  5376.4 2109.95  5430.0 2113.71
#Mann=9,-1,0
  3800.5    0.07       0  3944.9   0.035       0  4138.6    0.07       0
  4208.5   0.045       0  4452.5    0.07       0  5004.1    0.07       0
  5023.3    0.07       0  5183.4   0.035       0  5302.7    0.07       0
Bank Sta=5004.1,5023.3
Exp/Cntr=0.3,0.1

Type RM Length L Ch R = 1,34500,500,500,500
BEGIN DESCRIPTION:
East Cottonwood Creek 66.0
END DESCRIPTION:
XS GIS Cut Line= 3
      1360005.00      6908688.00      1360869.01      6908325.18
      1361255.03      6908288.00
#Sta/Elev= 30
  4062.9 2116.34  4225.5 2108.35  4302.3 2103.09  4389.7 2098.54  4453.0 2097.18
  4614.4 2093.12  4749.5 2094.43  4843.8 2093.25  4873.7 2089.91  4879.1 2087.47
  4887.2 2088.56  4897.5 2087.10  4902.9 2084.26  4926.7 2081.87  5000.0 2080.56
  5006.5 2076.00  5007.0 2075.50  5025.7 2076.00  5027.0 2077.64  5036.2 2081.33
  5105.4 2086.35  5124.3 2088.33  5176.8 2089.14  5206.9 2092.10  5237.1 2091.72
  5283.9 2094.98  5307.4 2097.89  5327.5 2097.00  5367.7 2101.56  5387.8 2101.40
#Mann=7,-1,0
  4062.9    0.07       0  4302.3   0.035       0  4453.0    0.07       0
  5006.5    0.07       0  5025.7    0.07       0  5105.4   0.035       0
  5283.9    0.07       0
Bank Sta=5006.5,5025.7
Exp/Cntr=0.3,0.1

Type RM Length L Ch R = 1,34000,500,500,500
BEGIN DESCRIPTION:
East Cottonwood Creek 65.0
END DESCRIPTION:
XS GIS Cut Line= 3
      1360304.98      6908988.01      1360823.34      6908756.78
      1361305.04      6908337.97
#Sta/Elev= 30
  4432.4 2104.81  4466.5 2102.46  4516.4 2098.91  4640.9 2095.16  4736.4 2093.89
  4793.8 2094.41  4886.7 2092.72  4909.9 2091.21  4933.1 2091.45  4938.6 2089.66
  4956.4 2088.49  4969.0 2084.02  4990.9 2080.26  4997.6 2073.36  4998.1 2072.86
  5016.9 2073.36  5021.5 2079.21  5042.4 2079.47  5078.5 2082.44  5121.3 2082.97
  5177.2 2086.00  5361.4 2090.74  5389.9 2090.61  5410.2 2092.72  5463.0 2093.25
  5503.9 2097.41  5545.7 2097.72  5567.5 2101.40  5602.6 2101.14  5638.3 2102.99
#Mann=7,-1,0
  4432.4    0.07       0  4466.5   0.035       0  4640.9    0.07       0
  4997.6    0.07       0  5016.9    0.07       0  5410.2   0.035       0
  5463.0    0.07       0
Bank Sta=4997.6,5016.9
Exp/Cntr=0.3,0.1

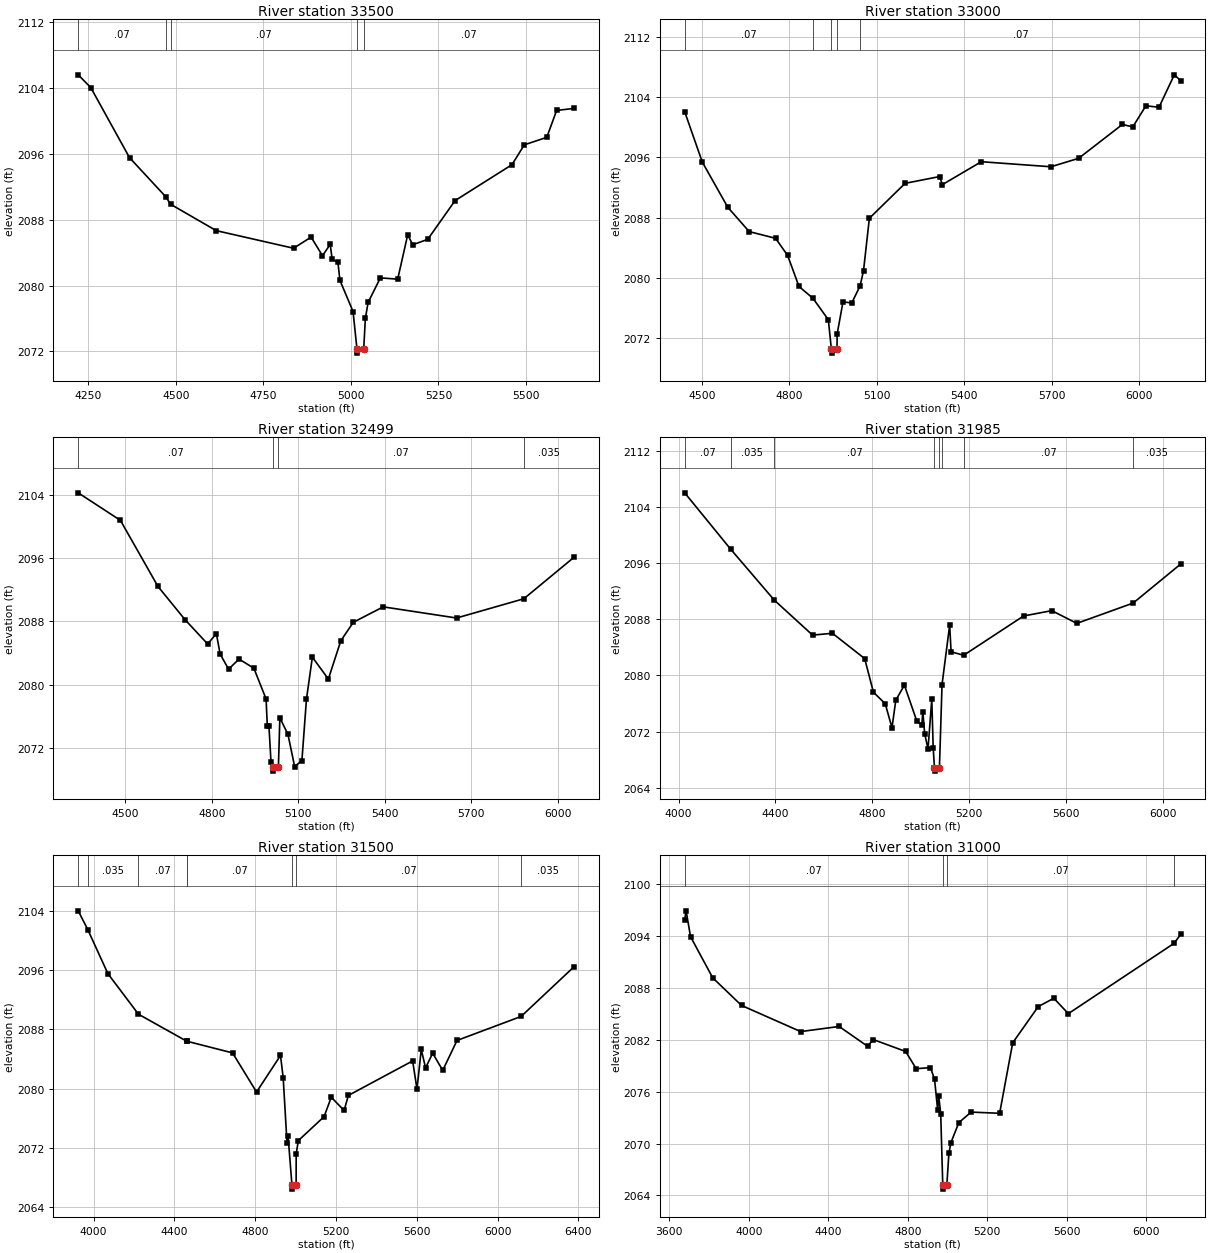
Type RM Length L Ch R = 1,33500,500,500,500
BEGIN DESCRIPTION:
East Cottonwood Creek 64.0
END DESCRIPTION:
XS GIS Cut Line= 3
      1360505.04      6909387.98      1361195.77      6909027.35
      1361604.99      6908538.01
#Sta/Elev= 30
  4220.8 2105.61  4256.7 2104.06  4367.4 2095.54  4471.4 2090.77  4484.6 2089.88
  4615.2 2086.67  4836.1 2084.53  4886.3 2085.88  4918.8 2083.62  4940.8 2085.00
  4946.5 2083.19  4962.9 2082.82  4968.6 2080.63  5006.1 2076.84  5017.3 2072.28
  5017.8 2071.78  5036.6 2072.28  5041.3 2075.99  5049.1 2077.94  5084.2 2080.93
  5133.7 2080.77  5162.3 2086.17  5176.6 2084.95  5219.5 2085.61  5297.6 2090.32
  5460.3 2094.69  5495.4 2097.10  5559.7 2098.01  5587.8 2101.28  5637.9 2101.53
#Mann=5,-1,0
  4220.8    0.07       0  4471.4   0.035       0  4484.6    0.07       0
  5017.3    0.07       0  5036.6    0.07       0
Bank Sta=5017.3,5036.6
Exp/Cntr=0.3,0.1

Type RM Length L Ch R = 1,33000,501,501,501
BEGIN DESCRIPTION:
East Cottonwood Creek 63.0
END DESCRIPTION:
XS GIS Cut Line= 4
      1360605.04      6909438.00      1361161.12      6909381.92
      1361307.79      6909367.33      1361758.96      6908481.94
#Sta/Elev= 30
  4441.1 2102.07  4501.4 2095.38  4588.7 2089.38  4662.2 2086.14  4752.6 2085.25
  4793.9 2082.98  4833.0 2078.85  4880.9 2077.28  4933.5 2074.44  4944.0 2070.50
  4944.5 2070.00  4963.3 2070.50  4963.7 2072.54  4983.8 2076.80  5013.9 2076.67
  5042.5 2078.94  5054.1 2080.94  5074.2 2087.91  5196.7 2092.55  5315.0 2093.45
  5324.5 2092.38  5457.9 2095.42  5696.6 2094.75  5791.5 2095.87  5941.5 2100.37
  5977.2 2100.04  6022.1 2102.85  6067.0 2102.65  6119.4 2106.96  6141.1 2106.20
#Mann=5,-1,0
  4441.1    0.07       0  4880.9    0.16       0  4944.0    0.07       0
  4963.3    0.16       0  5042.5    0.07       0
Bank Sta=4944,4963.3
Exp/Cntr=0.3,0.1

Type RM Length L Ch R = 1,32499,514,514,514
BEGIN DESCRIPTION:
East Cottonwood Creek 62.0
END DESCRIPTION:
XS GIS Cut Line= 4
      1360450.51      6909431.48      1361005.68      6909787.55
      1361415.36      6909879.44      1362020.18      6909665.07
#Sta/Elev= 30
  4336.4 2104.25  4482.9 2100.77  4613.1 2092.42  4706.9 2088.23  4785.5 2085.15
  4815.9 2086.45  4828.8 2083.89  4858.2 2081.96  4894.5 2083.24  4946.1 2082.08
  4988.4 2078.19  4992.6 2074.83  4998.2 2074.83  5005.5 2070.19  5010.7 2069.58
  5011.2 2069.08  5031.1 2069.58  5036.2 2075.81  5064.2 2073.74  5087.5 2069.65
  5112.7 2070.41  5128.5 2078.18  5149.0 2083.48  5204.5 2080.72  5247.8 2085.56
  5291.2 2087.89  5394.9 2089.84  5649.4 2088.43  5882.8 2090.86  6057.5 2096.12
#Mann=4,-1,0
  4336.4    0.07       0  5010.7    0.07       0  5031.1    0.07       0
  5882.8   0.035       0
Bank Sta=5010.7,5031.1
Exp/Cntr=0.3,0.1

Type RM Length L Ch R = 1,31985,485,485,485
BEGIN DESCRIPTION:
East Cottonwood Creek 61.0
END DESCRIPTION:
XS GIS Cut Line= 3
      1360159.54      6910024.94      1361112.88      6910235.52
      1362030.89      6909684.72
#Sta/Elev= 30
  4025.5 2105.98  4215.1 2097.97  4394.9 2090.73  4553.4 2085.74  4635.3 2086.00
  4768.4 2082.40  4804.5 2077.62  4853.3 2075.97  4881.1 2072.56  4896.9 2076.48
  4932.3 2078.62  4983.5 2073.52  5004.3 2072.92  5008.4 2074.87  5016.0 2071.70
  5029.8 2069.56  5045.4 2076.60  5051.2 2069.72  5056.4 2066.89  5056.9 2066.39
  5077.0 2066.89  5087.7 2078.71  5119.2 2087.16  5125.0 2083.37  5177.0 2082.87
  5424.1 2088.46  5540.7 2089.22  5644.0 2087.41  5876.6 2090.30  6072.4 2095.84
#Mann=8,-1,0
  4025.5    0.07       0  4215.1   0.035       0  4394.9    0.07       0
  5056.4    0.07       0  5077.0    0.07       0  5087.7    0.16       0
  5177.0    0.07       0  5876.6   0.035       0
Bank Sta=5056.4,5077
Exp/Cntr=0.3,0.1

Type RM Length L Ch R = 1,31500,500,500,500
BEGIN DESCRIPTION:
East Cottonwood Creek 60.0
END DESCRIPTION:
XS GIS Cut Line= 3
      1360105.04      6910288.01      1361104.70      6910686.88
      1362055.00      6909688.01
#Sta/Elev= 30
  3923.7 2104.01  3971.5 2101.45  4070.5 2095.54  4221.9 2090.06  4461.5 2086.41
  4462.2 2086.41  4687.7 2084.84  4806.5 2079.56  4925.0 2084.49  4938.3 2081.52
  4957.2 2072.71  4962.6 2073.61  4981.9 2066.96  4982.4 2066.46  5002.5 2066.96
  5002.7 2071.22  5013.4 2073.01  5140.8 2076.24  5176.4 2078.86  5239.9 2077.07
  5261.0 2079.10  5579.3 2083.76  5600.7 2079.93  5621.8 2085.30  5643.2 2082.82
  5678.4 2084.80  5728.1 2082.48  5798.9 2086.52  6116.2 2089.76  6378.7 2096.48
#Mann=8,-1,0
  3923.7    0.07       0  3971.5   0.035       0  4221.9    0.07       0
  4461.5   0.035       0  4462.2    0.07       0  4981.9    0.07       0
  5002.5    0.07       0  6116.2   0.035       0
Bank Sta=4981.9,5002.5
Exp/Cntr=0.3,0.1

Type RM Length L Ch R = 1,31000,500,500,500
BEGIN DESCRIPTION:
East Cottonwood Creek 59.0
END DESCRIPTION:
XS GIS Cut Line= 5
      1360318.51      6911401.89      1361364.54      6910885.38
      1361401.91      6910734.65      1361403.60      6910642.33
      1362015.45      6909752.77
#Sta/Elev= 30
  3678.1 2095.87  3685.3 2096.88  3707.6 2093.89  3819.2 2089.14  3963.9 2085.95
  4261.3 2082.93  4454.9 2083.52  4598.0 2081.23  4626.0 2082.01  4789.5 2080.63
  4842.2 2078.64  4914.1 2078.77  4934.7 2077.41  4950.3 2073.84  4955.5 2075.47
  4965.6 2073.44  4975.9 2065.23  4976.4 2064.73  4996.5 2065.23  5006.7 2068.85
  5016.7 2070.09  5056.7 2072.41  5118.5 2073.63  5261.9 2073.49  5327.6 2081.63
  5456.1 2085.82  5534.5 2086.78  5607.3 2085.00  6139.4 2093.13  6172.0 2094.15
#Mann=4,-1,0
  3678.1    0.07       0  4975.9    0.07       0  4996.5    0.07       0
  6139.4   0.035       0
Bank Sta=4975.9,4996.5
Exp/Cntr=0.3,0.1

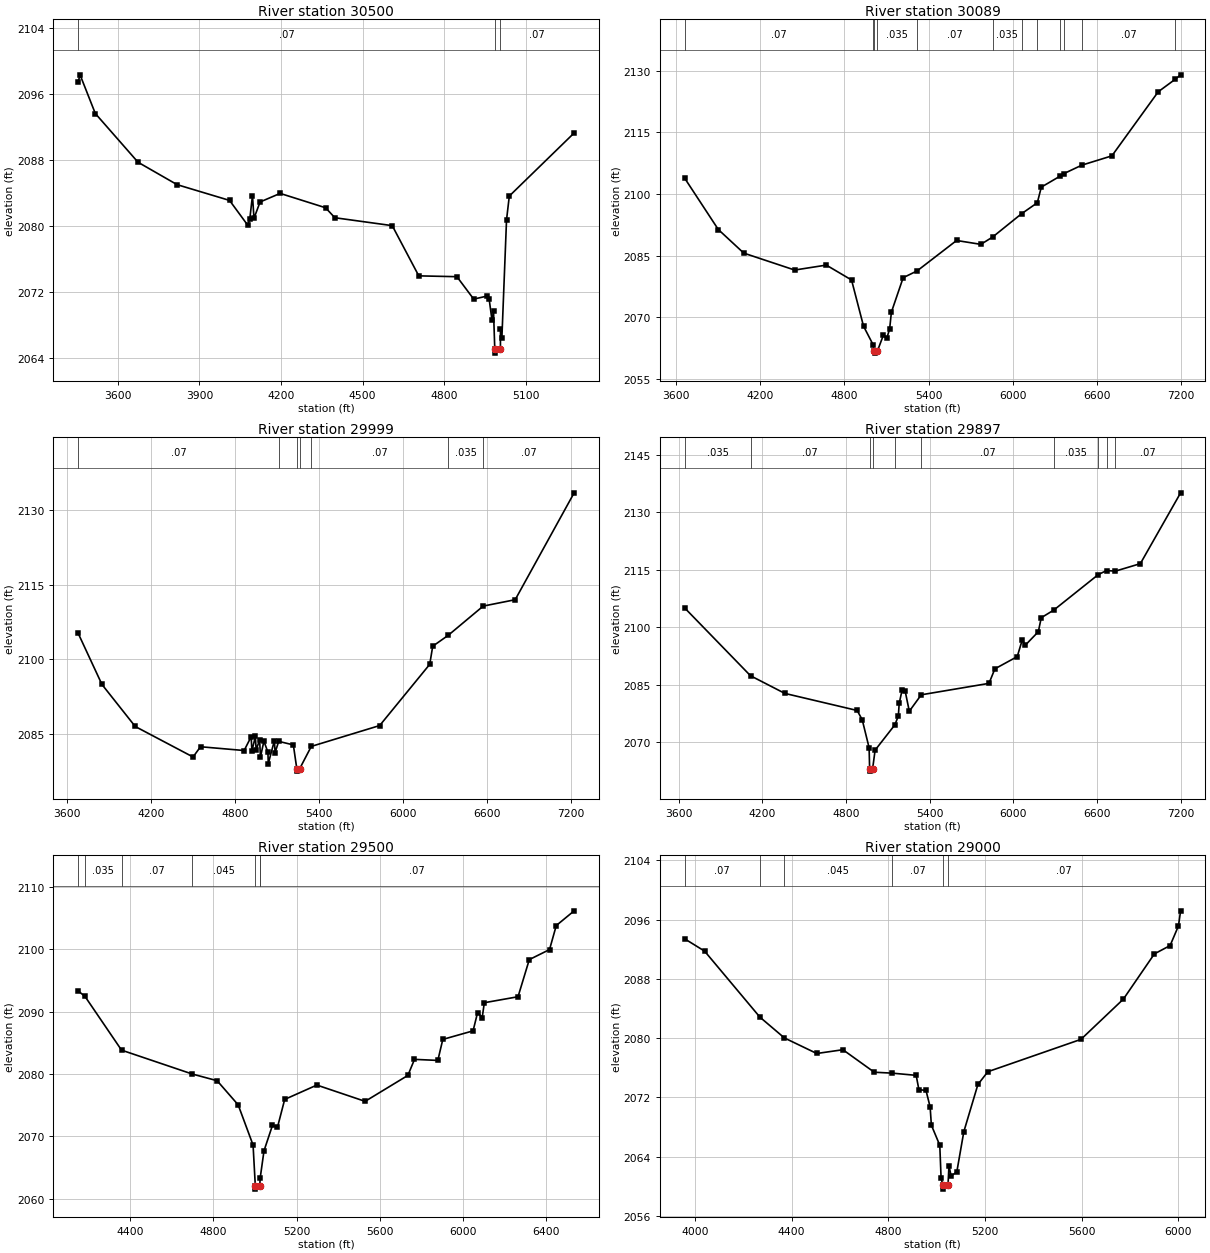
Type RM Length L Ch R = 1,30500,411,411,411
BEGIN DESCRIPTION:
East Cottonwood Creek 58.0
END DESCRIPTION:
XS GIS Cut Line= 3
      1360318.56      6911458.28      1361705.47      6910774.74
      1361980.42      6910729.20
#Sta/Elev= 30
  3453.8 2097.48  3460.6 2098.30  3516.7 2093.61  3673.9 2087.70  3817.7 2084.98
  4010.7 2083.07  4078.1 2080.04  4085.3 2080.86  4095.0 2083.65  4100.6 2080.90
  4123.0 2082.88  4196.8 2083.92  4364.0 2082.18  4398.1 2080.97  4609.3 2080.01
  4707.0 2073.92  4847.3 2073.82  4909.1 2071.10  4959.6 2071.48  4966.0 2071.08
  4976.5 2068.52  4982.0 2069.64  4986.6 2065.05  4987.1 2064.55  5007.4 2065.05
  5007.6 2067.51  5012.7 2066.33  5029.9 2080.72  5040.1 2083.60  5278.7 2091.25
#Mann=3,-1,0
  3453.8    0.07       0  4986.6    0.07       0  5007.4    0.07       0
Bank Sta=4986.6,5007.4
Exp/Cntr=0.3,0.1

Type RM Length L Ch R = 1,30089,90,90,90
BEGIN DESCRIPTION:
East Cottonwood Creek 57.6
END DESCRIPTION:
XS GIS Cut Line= 4
      1360250.21      6911573.28      1361503.43      6911107.60
      1361705.05      6911069.82      1363335.59      6909924.78
#Sta/Elev= 30
  3661.9 2103.83  3901.7 2091.36  4083.1 2085.63  4445.8 2081.52  4671.3 2082.72
  4851.2 2079.10  4936.5 2067.88  5005.2 2063.34  5014.4 2061.83  5014.9 2061.33
  5035.3 2061.83  5077.4 2065.63  5102.2 2064.96  5122.5 2067.17  5135.1 2071.28
  5219.0 2079.66  5318.0 2081.30  5599.8 2088.70  5772.4 2087.76  5856.0 2089.52
  6062.4 2095.19  6175.0 2097.86  6203.7 2101.67  6338.8 2104.36  6363.4 2104.93
  6492.1 2107.00  6706.5 2109.26  7036.8 2124.83  7159.8 2127.92  7196.4 2128.95
#Mann=12,-1,0
  3661.9    0.07       0  5005.2   0.035       0  5014.4    0.07       0
  5035.3   0.035       0  5318.0    0.07       0  5856.0   0.035       0
  6062.4    0.07       0  6175.0   0.035       0  6338.8    0.07       0
  6363.4   0.035       0  6492.1    0.07       0  7159.8   0.035       0
Bank Sta=5014.4,5035.3
Exp/Cntr=0.3,0.1

Type RM Length L Ch R = 1,29999,102,102,102
BEGIN DESCRIPTION:
East Cottonwood Creek 57.5
END DESCRIPTION:
XS GIS Cut Line= 4
      1360274.51      6911653.14      1361545.10      6911183.99
      1361732.83      6911142.73      1363375.89      6910002.12
#Sta/Elev= 30
  3678.6 2105.21  3848.3 2094.95  4086.4 2086.50  4499.9 2080.37  4553.2 2082.43
  4865.2 2081.67  4915.4 2084.45  4920.7 2081.57  4945.8 2084.50  4951.1 2081.77
  4976.2 2083.83  4981.6 2080.35  5006.7 2083.54  5035.3 2081.34  5037.9 2079.05
  5081.6 2083.66  5086.7 2081.27  5112.5 2083.51  5217.2 2082.80  5241.8 2078.03
  5242.3 2077.53  5262.7 2078.03  5345.5 2082.50  5834.5 2086.69  6192.5 2098.99
  6213.9 2102.63  6325.0 2104.83  6575.1 2110.70  6803.7 2111.98  7225.4 2133.46
#Mann=7,-1,0
  3678.6    0.07       0  5112.5   0.035       0  5241.8    0.07       0
  5262.7   0.035       0  5345.5    0.07       0  6325.0   0.035       0
  6575.1    0.07       0
Bank Sta=5241.8,5262.7
Exp/Cntr=0.3,0.1

Type RM Length L Ch R = 1,29897,397,397,397
BEGIN DESCRIPTION:
East Cottonwood Creek 57.0
END DESCRIPTION:
XS GIS Cut Line= 3
      1360504.98      6912138.02      1361572.87      6911270.80
      1363404.98      6910088.01
#Sta/Elev= 30
  3643.7 2105.07  4115.7 2087.39  4362.1 2082.78  4880.4 2078.33  4916.7 2075.93
  4966.2 2068.62  4970.1 2063.01  4970.6 2062.51  4991.0 2063.01  5009.2 2067.98
  5150.9 2074.58  5176.0 2076.90  5181.9 2080.16  5203.0 2083.69  5224.2 2083.48
  5254.5 2078.13  5340.2 2082.42  5825.9 2085.40  5868.2 2089.19  6028.5 2092.38
  6064.8 2096.77  6085.9 2095.34  6179.6 2098.87  6200.8 2102.53  6291.1 2104.53
  6609.5 2113.77  6668.7 2114.82  6732.7 2114.68  6911.4 2116.63  7200.1 2135.10
#Mann=10,-1,0
  3643.7   0.035       0  4115.7    0.07       0  4970.1    0.07       0
  4991.0    0.07       0  5150.9   0.035       0  5340.2    0.07       0
  6291.1   0.035       0  6609.5    0.07       0  6668.7   0.035       0
  6732.7    0.07       0
Bank Sta=4970.1,4991
Exp/Cntr=0.3,0.1

Type RM Length L Ch R = 1,29500,500,500,500
BEGIN DESCRIPTION:
East Cottonwood Creek 56.0
END DESCRIPTION:
XS GIS Cut Line= 3
      1360954.98      6912088.01      1361654.88      6911606.05
      1363074.58      6911023.41
#Sta/Elev= 30
  4150.2 2093.31  4183.0 2092.42  4358.5 2083.82  4698.5 2079.99  4818.0 2078.92
  4919.2 2075.05  4990.9 2068.60  5001.7 2062.04  5002.2 2061.54  5022.7 2062.04
  5025.3 2063.36  5043.4 2067.68  5084.1 2071.76  5108.1 2071.44  5142.9 2075.92
  5297.6 2078.22  5529.6 2075.61  5735.2 2079.77  5767.0 2082.34  5879.2 2082.17
  5903.1 2085.54  6048.6 2086.91  6070.3 2089.84  6092.6 2089.05  6102.7 2091.42
  6264.8 2092.38  6318.9 2098.33  6416.2 2099.94  6448.6 2103.79  6534.6 2106.15
#Mann=7,-1,0
  4150.2    0.07       0  4183.0   0.035       0  4358.5    0.07       0
  4698.5   0.045       0  5001.7   0.045       0  5022.7   0.045       0
  5025.3    0.07       0
Bank Sta=5001.7,5022.7
Exp/Cntr=0.3,0.1

Type RM Length L Ch R = 1,29000,500,500,500
BEGIN DESCRIPTION:
East Cottonwood Creek 55.0
END DESCRIPTION:
XS GIS Cut Line= 3
      1360905.00      6912188.00      1361928.17      6911988.18
      1362854.97      6911588.01
#Sta/Elev= 30
  3957.5 2093.40  4039.9 2091.74  4268.7 2082.83  4370.1 2080.02  4504.0 2077.92
  4612.2 2078.43  4742.0 2075.39  4815.4 2075.27  4915.3 2074.97  4926.6 2073.04
  4956.0 2072.93  4973.1 2070.70  4978.2 2068.25  5013.0 2065.53  5018.4 2061.11
  5025.9 2060.11  5026.4 2059.61  5047.0 2060.11  5051.0 2062.76  5060.0 2061.38
  5083.5 2061.94  5112.5 2067.37  5170.8 2073.74  5211.9 2075.46  5597.2 2079.83
  5772.6 2085.26  5901.0 2091.37  5966.0 2092.49  6000.5 2095.14  6009.5 2097.18
#Mann=6,-1,0
  3957.5    0.07       0  4268.7   0.035       0  4370.1   0.045       0
  4815.4    0.07       0  5025.9    0.07       0  5047.0    0.07       0
Bank Sta=5025.9,5047
Exp/Cntr=0.3,0.1