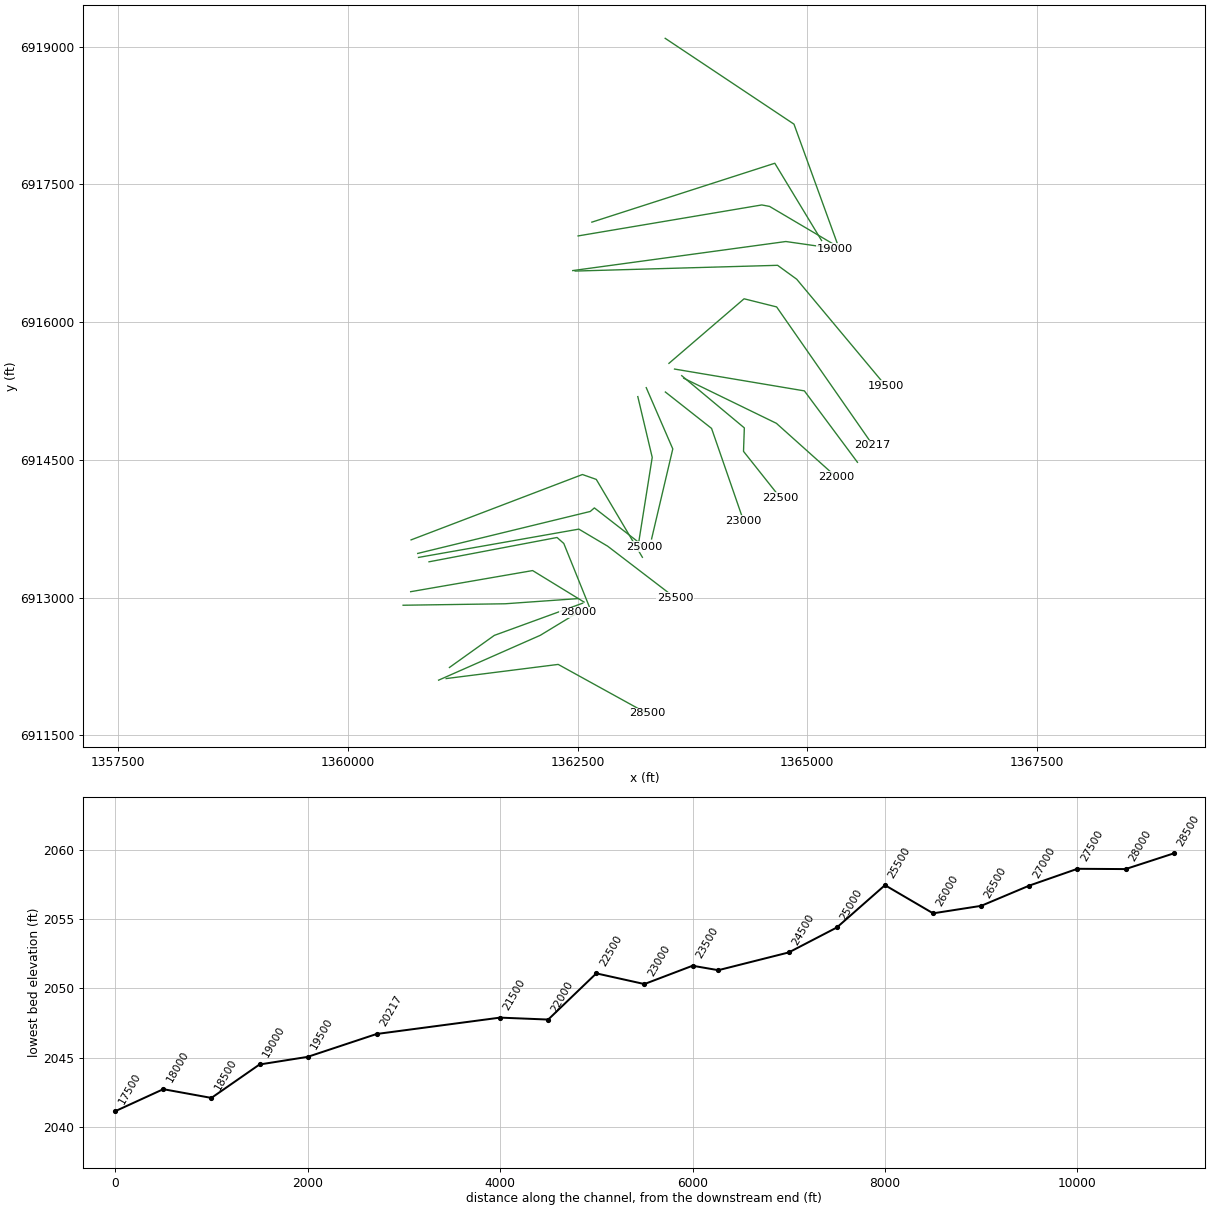
HEC-RAS study East Cottonwood Creek.prj: East Cottonwood Creek Base Level Engineering

--- East Cottonwood Creek.g01 (geometry) --- (continued)

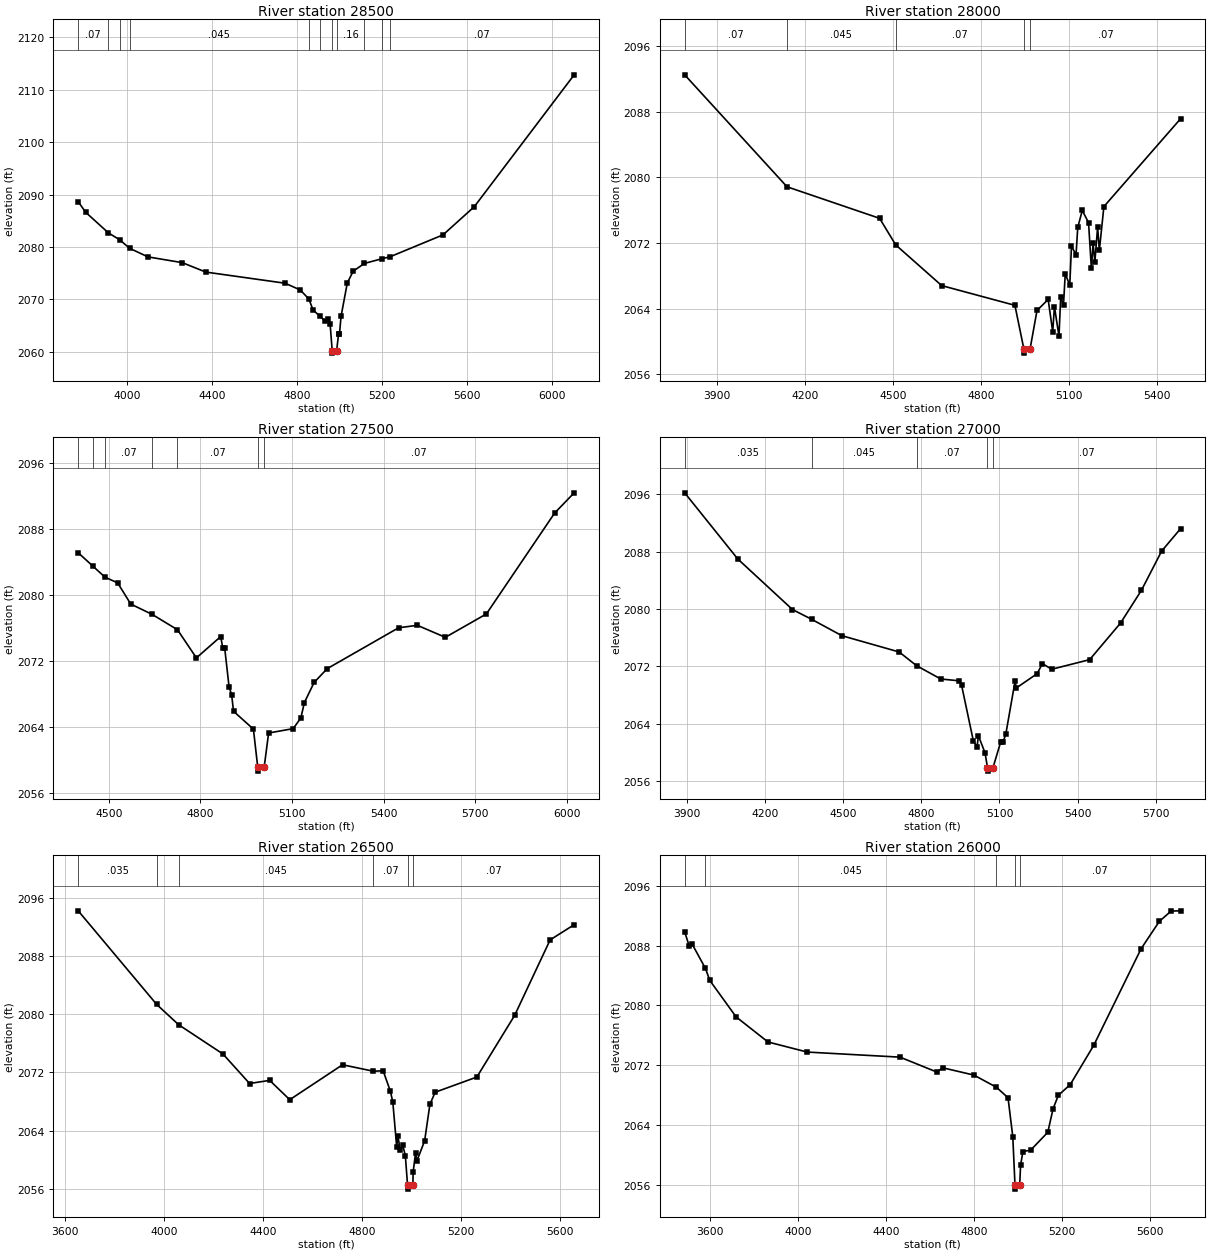
Type RM Length L Ch R = 1,28500,500,500,500
BEGIN DESCRIPTION:
East Cottonwood Creek 54.0
END DESCRIPTION:
XS GIS Cut Line= 3
      1361069.42      6912117.15      1362288.52      6912271.23
      1363254.98      6911738.01
#Sta/Elev= 30
  3771.2 2088.63  3807.1 2086.59  3913.1 2082.69  3966.8 2081.35  4012.5 2079.75
  4099.4 2078.10  4260.6 2077.00  4371.3 2075.20  4744.5 2073.07  4815.0 2071.79
  4856.3 2070.06  4875.5 2067.96  4908.7 2066.76  4932.6 2065.82  4946.1 2066.18
  4956.1 2065.21  4965.7 2060.22  4966.2 2059.72  4986.8 2060.22  4995.7 2063.36
  5000.0 2063.36  5007.4 2066.73  5036.8 2073.12  5064.5 2075.37  5117.2 2076.85
  5199.3 2077.74  5237.9 2078.12  5487.1 2082.31  5634.0 2087.68  6103.8 2112.87
#Mann=11,-1,0
  3771.2    0.07       0  3913.1   0.035       0  3966.8    0.07       0
  4012.5   0.045       0  4856.3    0.07       0  4908.7    0.16       0
  4965.7    0.07       0  4986.8    0.16       0  5117.2    0.07       0
  5199.3    0.16       0  5237.9    0.07       0
Bank Sta=4965.7,4986.8
Exp/Cntr=0.3,0.1

Type RM Length L Ch R = 1,28000,500,500,500
BEGIN DESCRIPTION:
East Cottonwood Creek 53.0
END DESCRIPTION:
XS GIS Cut Line= 3
      1360986.95      6912099.80      1362093.31      6912588.02
      1362504.96      6912837.98
#Sta/Elev= 30
  3790.7 2092.47  4139.6 2078.84  4455.3 2075.00  4510.1 2071.77  4667.0 2066.81
  4916.6 2064.41  4947.2 2059.09  4947.7 2058.59  4968.3 2059.09  4992.0 2063.79
  5030.0 2065.12  5045.5 2061.20  5051.4 2064.24  5066.9 2060.65  5072.7 2065.37
  5082.3 2064.48  5088.2 2068.22  5103.7 2066.89  5109.5 2071.63  5125.0 2070.55
  5130.9 2073.89  5146.3 2075.96  5167.7 2074.47  5177.3 2068.90  5183.2 2071.97
  5189.2 2069.68  5198.6 2073.92  5204.5 2071.10  5220.0 2076.43  5481.6 2087.13
#Mann=5,-1,0
  3790.7    0.07       0  4139.6   0.045       0  4510.1    0.07       0
  4947.2    0.07       0  4968.3    0.07       0
Bank Sta=4947.2,4968.3
Exp/Cntr=0.3,0.1

Type RM Length L Ch R = 1,27500,500,500,500
BEGIN DESCRIPTION:
East Cottonwood Creek 52.0
END DESCRIPTION:
XS GIS Cut Line= 3
      1361105.01      6912238.01      1361593.32      6912587.35
      1362554.99      6912937.99
#Sta/Elev= 30
  4399.6 2085.13  4448.1 2083.49  4487.4 2082.16  4528.6 2081.48  4571.7 2078.90
  4642.0 2077.64  4724.7 2075.78  4786.6 2072.36  4866.4 2074.96  4872.6 2073.59
  4879.1 2073.62  4893.5 2068.87  4902.1 2067.85  4908.2 2065.88  4973.3 2063.71
  4987.4 2059.11  4987.9 2058.61  5008.6 2059.11  5023.1 2063.24  5103.5 2063.77
  5128.7 2065.07  5140.2 2066.94  5172.1 2069.38  5214.7 2071.05  5448.8 2076.02
  5510.1 2076.32  5601.8 2074.86  5736.2 2077.70  5959.8 2089.96  6023.6 2092.41
#Mann=7,-1,0
  4399.6    0.07       0  4448.1   0.035       0  4487.4    0.07       0
  4642.0   0.045       0  4724.7    0.07       0  4987.4    0.07       0
  5008.6    0.07       0
Bank Sta=4987.4,5008.6
Exp/Cntr=0.3,0.1

Type RM Length L Ch R = 1,27000,500,500,500
BEGIN DESCRIPTION:
East Cottonwood Creek 51.0
END DESCRIPTION:
XS GIS Cut Line= 3
      1360600.62      6912915.76      1361710.61      6912931.68
      1362505.01      6912988.00
#Sta/Elev= 30
  3889.9 2096.22  4094.3 2086.98  4304.3 2079.94  4377.8 2078.58  4494.3 2076.29
  4714.4 2074.02  4781.3 2072.11  4874.4 2070.25  4944.4 2070.00  4954.4 2069.38
  4999.7 2061.60  5014.0 2060.82  5019.0 2062.34  5044.5 2059.95  5054.0 2057.90
  5054.5 2057.40  5075.2 2057.90  5104.7 2061.46  5114.7 2061.51  5124.7 2062.63
  5159.9 2069.92  5164.9 2069.00  5245.0 2071.00  5265.1 2072.40  5300.8 2071.61
  5446.7 2072.95  5565.8 2078.07  5646.0 2082.64  5723.4 2088.09  5796.4 2091.23
#Mann=5,-1,0
  3889.9   0.035       0  4377.8   0.045       0  4781.3    0.07       0
  5054.0    0.07       0  5075.2    0.07       0
Bank Sta=5054,5075.2
Exp/Cntr=0.3,0.1

Type RM Length L Ch R = 1,26500,500,500,500
BEGIN DESCRIPTION:
East Cottonwood Creek 50.0
END DESCRIPTION:
XS GIS Cut Line= 3
      1360683.10      6913063.33      1362010.32      6913293.28
      1362569.73      6912950.46
#Sta/Elev= 30
  3653.0 2094.25  3970.1 2081.36  4058.3 2078.58  4237.7 2074.54  4345.1 2070.48
  4426.3 2070.91  4507.4 2068.25  4720.6 2073.06  4845.0 2072.17  4884.6 2072.23
  4913.4 2069.46  4923.6 2067.96  4939.3 2061.76  4944.3 2063.20  4954.0 2061.28
  4964.1 2061.95  4974.3 2060.54  4983.3 2056.44  4983.8 2055.94  5004.6 2056.44
  5005.9 2058.34  5015.5 2060.89  5021.4 2059.86  5052.2 2062.59  5073.5 2067.62
  5094.8 2069.28  5263.1 2071.37  5415.8 2079.86  5559.1 2090.25  5656.1 2092.34
#Mann=6,-1,0
  3653.0   0.035       0  3970.1    0.07       0  4058.3   0.045       0
  4845.0    0.07       0  4983.3    0.07       0  5004.6    0.07       0
Bank Sta=4983.3,5004.6
Exp/Cntr=0.3,0.1

Type RM Length L Ch R = 1,26000,500,500,500
BEGIN DESCRIPTION:
East Cottonwood Creek 49.0
END DESCRIPTION:
XS GIS Cut Line= 4
      1360882.73      6913388.85      1362276.00      6913653.61
      1362349.54      6913588.53      1362626.05      6912902.89
#Sta/Elev= 30
  3483.6 2089.85  3503.5 2088.00  3516.4 2088.27  3578.0 2084.95  3597.9 2083.34
  3717.5 2078.46  3862.5 2075.10  4041.1 2073.75  4463.1 2073.07  4630.9 2071.07
  4656.5 2071.65  4799.0 2070.67  4901.5 2069.04  4954.3 2067.63  4976.0 2062.41
  4986.0 2055.90  4986.5 2055.40  5007.3 2055.90  5011.4 2058.61  5022.1 2060.43
  5057.3 2060.62  5135.1 2063.01  5159.3 2066.17  5183.4 2067.97  5237.1 2069.39
  5344.5 2074.67  5559.3 2087.57  5642.5 2091.25  5696.2 2092.63  5739.3 2092.66
#Mann=5,-1,0
  3483.6   0.035       0  3578.0   0.045       0  4901.5    0.07       0
  4986.0    0.07       0  5007.3    0.07       0
Bank Sta=4986,5007.3
Exp/Cntr=0.3,0.1

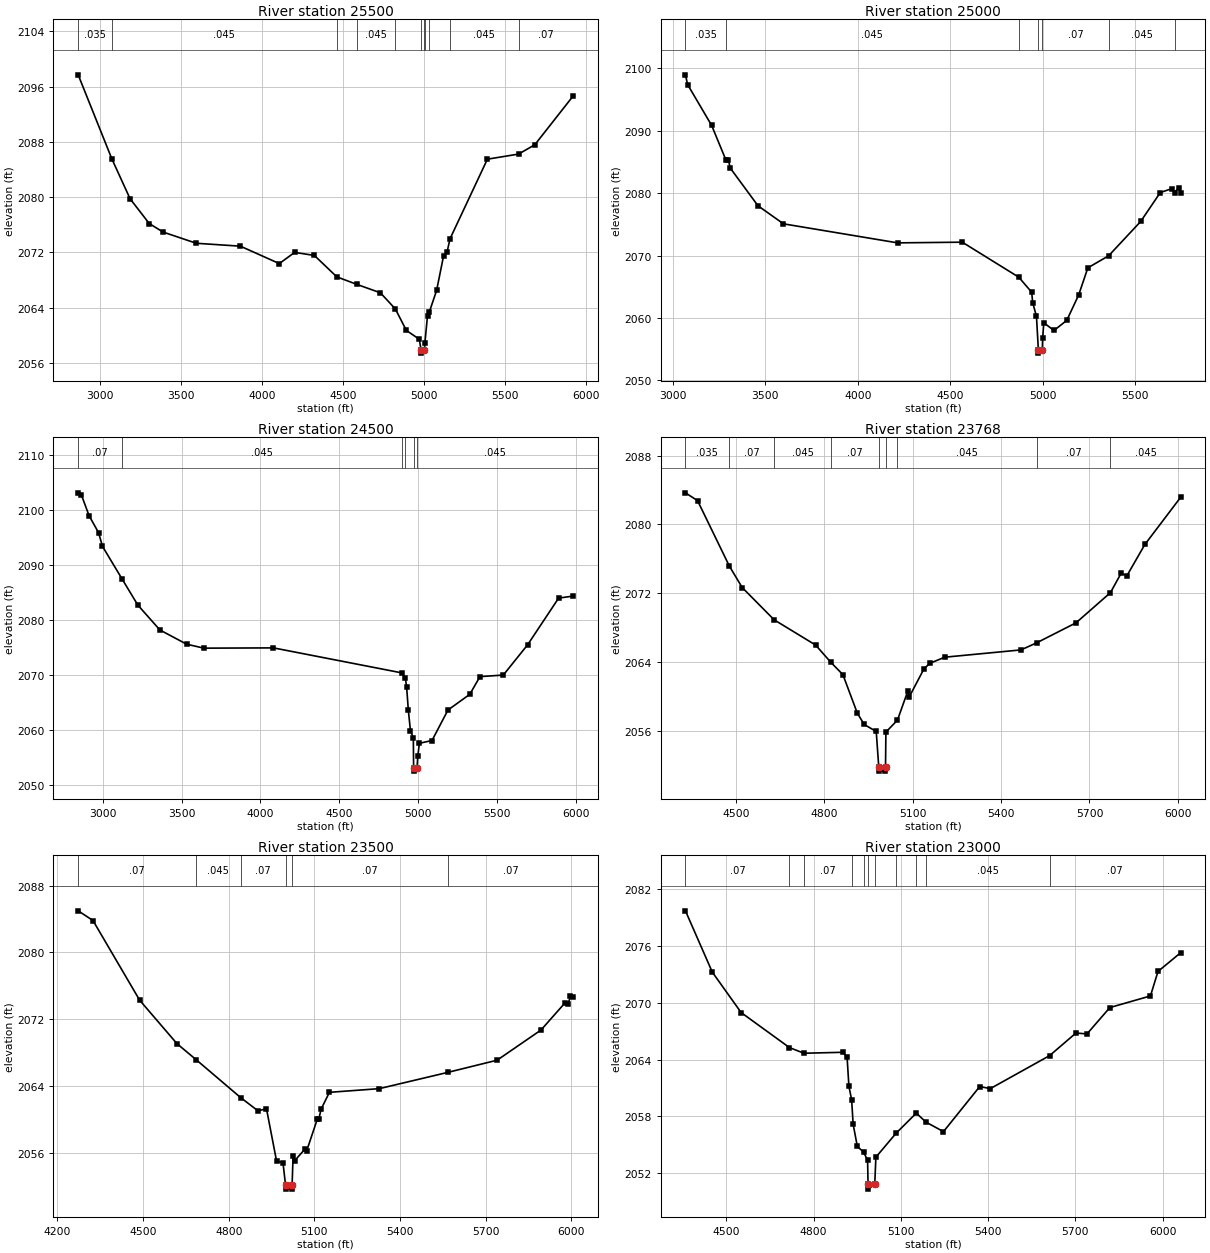
Type RM Length L Ch R = 1,25500,500,500,500
BEGIN DESCRIPTION:
East Cottonwood Creek 48.0
END DESCRIPTION:
XS GIS Cut Line= 4
      1360768.45      6913436.59      1362513.27      6913744.76
      1362827.07      6913558.78      1363559.24      6912998.25
#Sta/Elev= 30
  2863.4 2097.71  3071.7 2085.53  3183.8 2079.78  3302.2 2076.19  3387.9 2074.95
  3593.2 2073.33  3865.2 2072.91  4105.8 2070.39  4200.3 2072.01  4322.2 2071.57
  4460.8 2068.47  4584.7 2067.38  4730.2 2066.16  4822.6 2063.82  4890.4 2060.72
  4970.3 2059.44  4981.0 2057.93  4981.5 2057.43  5002.5 2057.93  5005.1 2058.93
  5021.1 2062.85  5032.7 2063.41  5077.3 2066.50  5120.8 2071.56  5141.7 2072.03
  5160.2 2073.98  5391.0 2085.50  5583.7 2086.24  5683.9 2087.59  5922.1 2094.69
#Mann=11,-1,0
  2863.4   0.035       0  3071.7   0.045       0  4460.8    0.07       0
  4584.7   0.045       0  4822.6    0.07       0  4981.0    0.07       0
  5002.5    0.07       0  5005.1   0.035       0  5032.7    0.07       0
  5160.2   0.045       0  5583.7    0.07       0
Bank Sta=4981,5002.5
Exp/Cntr=0.3,0.1

Type RM Length L Ch R = 1,25000,500,500,500
BEGIN DESCRIPTION:
East Cottonwood Creek 47.0
END DESCRIPTION:
XS GIS Cut Line= 4
      1360759.80      6913480.00      1362637.47      6913937.06
      1362682.41      6913975.66      1363225.08      6913553.78
#Sta/Elev= 30
  3067.5 2098.98  3079.1 2097.42  3209.4 2090.86  3285.8 2085.37  3299.3 2085.41
  3309.6 2084.05  3459.8 2078.00  3597.7 2075.10  4215.3 2072.05  4565.2 2072.16
  4870.8 2066.55  4940.7 2064.14  4946.0 2062.48  4966.6 2060.26  4976.8 2054.88
  4977.3 2054.38  4998.3 2054.88  5000.0 2056.82  5006.2 2059.24  5061.4 2058.01
  5130.5 2059.63  5194.7 2063.69  5244.5 2068.05  5357.0 2069.98  5530.4 2075.48
  5636.3 2080.11  5700.6 2080.76  5713.5 2080.11  5735.9 2080.90  5746.6 2080.09
#Mann=7,-1,0
  3067.5   0.035       0  3285.8   0.045       0  4870.8    0.07       0
  4976.8    0.07       0  4998.3    0.07       0  5357.0   0.045       0
  5713.5    0.07       0
Bank Sta=4976.8,4998.3
Exp/Cntr=0.3,0.1

Type RM Length L Ch R = 1,24500,732,732,732
BEGIN DESCRIPTION:
East Cottonwood Creek 46.0
END DESCRIPTION:
XS GIS Cut Line= 4
      1360687.43      6913627.56      1362552.33      6914339.37
      1362703.09      6914286.17      1363204.97      6913438.04
#Sta/Elev= 30
  2844.0 2103.05  2863.7 2102.73  2913.2 2098.90  2973.3 2095.83  2998.0 2093.35
  3120.7 2087.51  3222.6 2082.69  3362.3 2078.18  3532.0 2075.60  3641.6 2074.88
  4083.0 2074.93  4898.4 2070.39  4920.0 2069.39  4927.8 2067.79  4938.4 2063.65
  4951.9 2059.91  4970.2 2058.62  4972.0 2053.08  4972.5 2052.58  4993.5 2053.08
  4998.4 2055.26  5008.6 2057.63  5088.6 2058.13  5189.9 2063.66  5328.4 2066.51
  5392.9 2069.72  5541.0 2070.00  5695.0 2075.48  5892.0 2083.96  5985.5 2084.33
#Mann=6,-1,0
  2844.0    0.07       0  3120.7   0.045       0  4898.4    0.07       0
  4920.0   0.045       0  4972.0   0.045       0  4993.5   0.045       0
Bank Sta=4972,4993.5
Exp/Cntr=0.3,0.1

Type RM Length L Ch R = 1,23768,268,268,268
BEGIN DESCRIPTION:
East Cottonwood Creek 45.0
END DESCRIPTION:
XS GIS Cut Line= 3
      1363155.00      6915188.02      1363311.88      6914526.01
      1363155.00      6913538.03
#Sta/Elev= 30
  4328.7 2083.67  4369.8 2082.76  4477.8 2075.14  4521.4 2072.65  4629.7 2068.90
  4770.6 2065.96  4822.3 2063.95  4863.1 2062.52  4911.8 2058.06  4935.1 2056.73
  4976.2 2055.91  4984.7 2051.80  4985.2 2051.30  5007.2 2051.30  5007.7 2051.80
  5009.0 2055.84  5048.2 2057.23  5083.9 2060.66  5088.9 2059.98  5138.7 2063.23
  5158.9 2063.85  5208.4 2064.55  5467.6 2065.40  5521.1 2066.23  5654.3 2068.55
  5771.1 2072.06  5806.9 2074.29  5827.2 2074.04  5887.9 2077.66  6009.4 2083.15
#Mann=9,-1,0
  4328.7   0.035       0  4477.8    0.07       0  4629.7   0.045       0
  4822.3    0.07       0  4984.7    0.07       0  5007.7    0.07       0
  5048.2   0.045       0  5521.1    0.07       0  5771.1   0.045       0
Bank Sta=4984.7,5007.7
Exp/Cntr=0.3,0.1

Type RM Length L Ch R = 1,23500,500,500,500
BEGIN DESCRIPTION:
East Cottonwood Creek 44.0
END DESCRIPTION:
XS GIS Cut Line= 3
      1363246.78      6915285.53      1363535.75      6914618.32
      1363305.00      6913638.01
#Sta/Elev= 30
  4272.9 2084.97  4324.7 2083.81  4488.2 2074.26  4618.9 2069.05  4686.4 2067.12
  4841.5 2062.60  4902.3 2061.01  4932.4 2061.24  4967.7 2054.98  4990.2 2054.77
  4999.1 2052.12  4999.6 2051.62  5021.6 2051.62  5022.1 2052.12  5025.5 2055.60
  5031.1 2055.03  5067.9 2056.45  5073.1 2056.21  5110.3 2060.00  5115.4 2059.99
  5123.6 2061.20  5152.7 2063.22  5327.3 2063.66  5567.3 2065.61  5740.0 2067.07
  5893.5 2070.68  5976.3 2073.88  5988.5 2073.84  5996.8 2074.72  6007.1 2074.63
#Mann=6,-1,0
  4272.9    0.07       0  4686.4   0.045       0  4841.5    0.07       0
  4999.1    0.07       0  5022.1    0.07       0  5567.3    0.07       0
Bank Sta=4999.1,5022.1
Exp/Cntr=0.3,0.1

Type RM Length L Ch R = 1,23000,500,500,500
BEGIN DESCRIPTION:
East Cottonwood Creek 43.0
END DESCRIPTION:
XS GIS Cut Line= 3
      1363455.01      6915237.99      1363957.84      6914841.42
      1364305.01      6913837.98
#Sta/Elev= 30
  4359.6 2079.73  4451.8 2073.25  4551.1 2068.97  4717.0 2065.27  4766.8 2064.67
  4900.7 2064.77  4915.2 2064.24  4921.5 2061.16  4930.8 2059.76  4936.0 2057.17
  4950.4 2054.81  4971.7 2054.22  4985.7 2053.36  4987.2 2050.80  4987.7 2050.30
  5010.2 2050.80  5014.2 2053.68  5083.6 2056.21  5153.1 2058.34  5186.2 2057.39
  5246.5 2056.38  5371.2 2061.15  5407.6 2060.93  5611.4 2064.42  5702.0 2066.81
  5739.8 2066.71  5818.4 2069.50  5958.0 2070.73  5983.9 2073.32  6061.8 2075.30
#Mann=11,-1,0
  4359.6    0.07       0  4717.0   0.045       0  4766.8    0.07       0
  4930.8   0.045       0  4971.7    0.07       0  4987.2    0.07       0
  5010.2    0.07       0  5083.6   0.045       0  5153.1    0.07       0
  5186.2   0.045       0  5611.4    0.07       0
Bank Sta=4987.2,5010.2
Exp/Cntr=0.3,0.1

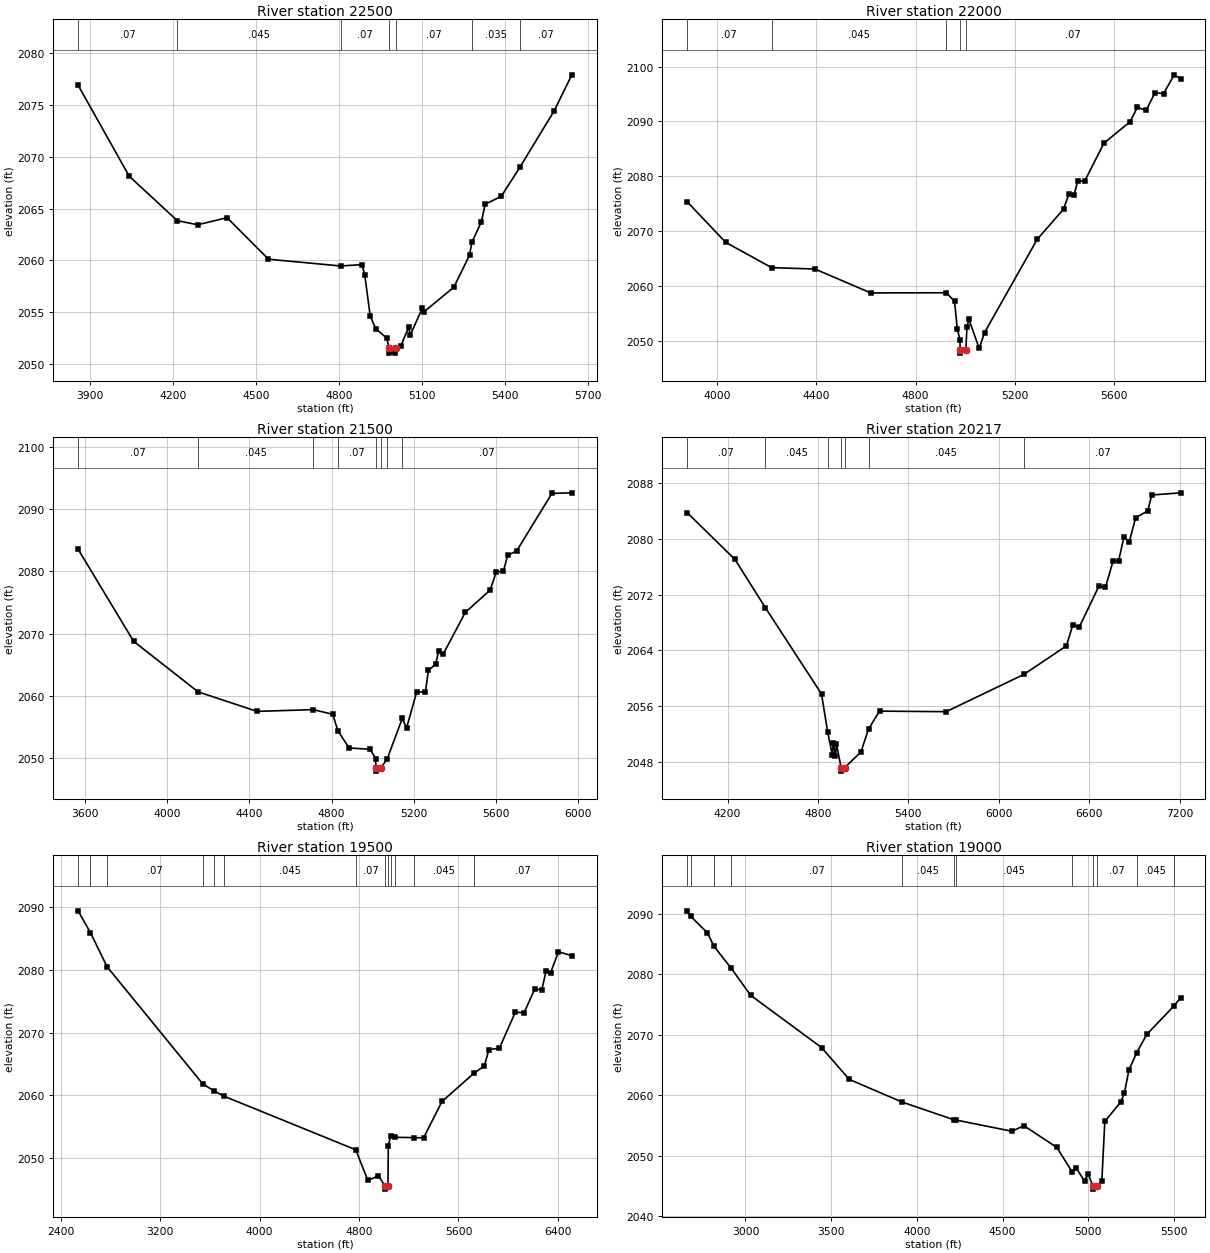
Type RM Length L Ch R = 1,22500,500,500,500
BEGIN DESCRIPTION:
East Cottonwood Creek 42.0
END DESCRIPTION:
XS GIS Cut Line= 4
      1363633.04      6915415.78      1364314.48      6914847.19
      1364305.51      6914591.65      1364704.97      6914088.04
#Sta/Elev= 30
  3856.8 2076.89  4041.7 2068.12  4215.4 2063.84  4289.1 2063.44  4395.8 2064.12
  4545.5 2060.12  4806.4 2059.47  4883.6 2059.60  4893.6 2058.64  4913.6 2054.63
  4933.6 2053.43  4973.6 2052.51  4982.1 2051.57  4982.6 2051.07  5004.7 2051.07
  5005.2 2051.57  5023.6 2051.72  5052.4 2053.55  5058.8 2052.83  5102.1 2055.41
  5108.5 2055.06  5215.8 2057.42  5272.7 2060.50  5281.3 2061.76  5315.2 2063.69
  5329.6 2065.43  5387.3 2066.17  5454.8 2068.98  5579.0 2074.42  5642.8 2077.89
#Mann=7,-1,0
  3856.8    0.07       0  4215.4   0.045       0  4806.4    0.07       0
  4982.1    0.07       0  5005.2    0.07       0  5281.3   0.035       0
  5454.8    0.07       0
Bank Sta=4982.1,5005.2
Exp/Cntr=0.3,0.1

Type RM Length L Ch R = 1,22000,500,500,500
BEGIN DESCRIPTION:
East Cottonwood Creek 41.0
END DESCRIPTION:
XS GIS Cut Line= 3
      1363655.00      6915388.00      1364663.50      6914896.94
      1365310.83      6914316.58
#Sta/Elev= 30
  3878.3 2075.37  4034.0 2067.95  4219.4 2063.33  4393.9 2063.08  4619.3 2058.72
  4924.1 2058.75  4957.2 2057.18  4968.6 2052.07  4979.4 2050.14  4979.5 2048.24
  4980.0 2047.74  5002.7 2048.24  5007.3 2052.48  5014.8 2053.96  5056.6 2048.59
  5078.3 2051.50  5290.7 2068.50  5396.8 2074.00  5418.4 2076.74  5439.4 2076.58
  5453.6 2079.13  5482.0 2079.11  5559.8 2086.04  5665.9 2089.96  5694.3 2092.59
  5729.5 2091.99  5765.4 2095.20  5800.5 2095.08  5843.1 2098.49  5869.4 2097.77
#Mann=5,-1,0
  3878.3    0.07       0  4219.4   0.045       0  4924.1    0.07       0
  4979.5    0.07       0  5002.7    0.07       0
Bank Sta=4979.5,5002.7
Exp/Cntr=0.3,0.1

Type RM Length L Ch R = 1,21500,1283,1283,1283
BEGIN DESCRIPTION:
East Cottonwood Creek 40.0
END DESCRIPTION:
XS GIS Cut Line= 3
      1363554.97      6915488.01      1364968.00      6915250.25
      1365545.70      6914472.53
#Sta/Elev= 30
  3567.1 2083.57  3837.1 2068.76  4150.9 2060.63  4437.6 2057.49  4711.7 2057.77
  4806.0 2057.01  4830.8 2054.37  4885.4 2051.60  4987.7 2051.40  5014.6 2049.90
  5016.1 2048.38  5016.6 2047.88  5039.3 2048.38  5070.2 2049.80  5144.2 2056.37
  5164.7 2054.82  5214.6 2060.65  5256.5 2060.57  5271.1 2064.08  5306.6 2065.10
  5321.2 2067.26  5342.1 2066.64  5450.6 2073.40  5571.6 2077.01  5600.7 2079.87
  5636.2 2080.08  5657.1 2082.60  5700.4 2083.28  5872.0 2092.55  5968.8 2092.64
#Mann=8,-1,0
  3567.1    0.07       0  4150.9   0.045       0  4711.7   0.035       0
  4830.8    0.07       0  5016.1    0.07       0  5039.3    0.07       0
  5070.2   0.035       0  5144.2    0.07       0
Bank Sta=5016.1,5039.3
Exp/Cntr=0.3,0.1

Type RM Length L Ch R = 1,20217,717,717,717
BEGIN DESCRIPTION:
East Cottonwood Creek 39.0
END DESCRIPTION:
XS GIS Cut Line= 4
      1363493.96      6915550.21      1364311.66      6916253.33
      1364665.83      6916164.79      1365712.72      6914659.55
#Sta/Elev= 30
  3930.6 2083.77  4248.5 2077.05  4451.5 2070.10  4823.3 2057.76  4863.9 2052.35
  4894.7 2049.05  4901.2 2050.73  4915.5 2048.83  4922.1 2050.63  4953.2 2047.20
  4953.7 2046.70  4976.5 2047.20  5084.6 2049.42  5135.5 2052.74  5208.3 2055.30
  5650.3 2055.22  6167.3 2060.57  6449.0 2064.66  6490.8 2067.62  6535.4 2067.40
  6663.7 2073.18  6708.2 2073.07  6758.8 2076.82  6794.6 2076.79  6830.4 2080.22
  6866.2 2079.59  6908.1 2083.00  6988.4 2084.00  7015.4 2086.28  7207.6 2086.59
#Mann=7,-1,0
  3930.6    0.07       0  4451.5   0.045       0  4863.9    0.07       0
  4953.2    0.07       0  4976.5    0.07       0  5135.5   0.045       0
  6167.3    0.07       0
Bank Sta=4953.2,4976.5
Exp/Cntr=0.3,0.1

Type RM Length L Ch R = 1,19500,500,500,500
BEGIN DESCRIPTION:
East Cottonwood Creek 38.0
END DESCRIPTION:
XS GIS Cut Line= 4
      1362473.08      6916555.41      1364676.24      6916617.91
      1364884.35      6916466.51      1365853.32      6915305.42
#Sta/Elev= 30
  2538.6 2089.41  2637.4 2085.95  2772.7 2080.47  3541.4 2061.83  3630.2 2060.73
  3710.8 2059.88  4773.5 2051.32  4870.5 2046.44  4956.2 2047.17  5009.4 2045.55
  5009.9 2045.05  5032.7 2045.55  5035.3 2051.96  5053.5 2053.51  5091.9 2053.31
  5243.3 2053.26  5319.1 2053.22  5467.4 2059.02  5726.6 2063.56  5808.4 2064.68
  5844.7 2067.29  5929.5 2067.51  6057.0 2073.24  6128.6 2073.17  6213.2 2076.91
  6270.5 2076.84  6305.6 2079.81  6340.8 2079.50  6404.7 2082.88  6512.3 2082.26
#Mann=13,-1,0
  2538.6    0.07       0  2637.4   0.035       0  2772.7    0.07       0
  3541.4   0.045       0  3630.2    0.07       0  3710.8   0.045       0
  4773.5    0.07       0  5009.4    0.07       0  5032.7    0.07       0
  5053.5   0.045       0  5091.9    0.07       0  5243.3   0.045       0
  5726.6    0.07       0
Bank Sta=5009.4,5032.7
Exp/Cntr=0.3,0.1

Type RM Length L Ch R = 1,19000,500,500,500
BEGIN DESCRIPTION:
East Cottonwood Creek 37.0
END DESCRIPTION:
XS GIS Cut Line= 3
      1362447.04      6916560.61      1364766.35      6916877.07
      1365300.66      6916800.29
#Sta/Elev= 30
  2659.2 2090.51  2681.2 2089.58  2778.3 2086.87  2817.1 2084.62  2916.5 2081.04
  3030.6 2076.54  3444.4 2067.90  3605.9 2062.64  3911.7 2058.92  4217.9 2055.95
  4231.0 2055.91  4554.6 2054.07  4625.2 2054.98  4817.0 2051.39  4905.6 2047.39
  4928.0 2048.07  4978.5 2045.84  5000.0 2047.00  5027.4 2045.00  5027.9 2044.50
  5050.7 2045.00  5079.5 2045.85  5096.8 2055.69  5190.6 2058.94  5210.8 2060.35
  5237.8 2064.22  5282.4 2067.03  5342.1 2070.09  5499.5 2074.77  5539.8 2076.14
#Mann=12,-1,0
  2659.2   0.035       0  2681.2    0.07       0  2817.1   0.035       0
  2916.5    0.07       0  3911.7   0.045       0  4217.9    0.07       0
  4231.0   0.045       0  4905.6    0.07       0  5027.4    0.07       0
  5050.7    0.07       0  5282.4   0.045       0  5499.5    0.07       0
Bank Sta=5027.4,5050.7
Exp/Cntr=0.3,0.1

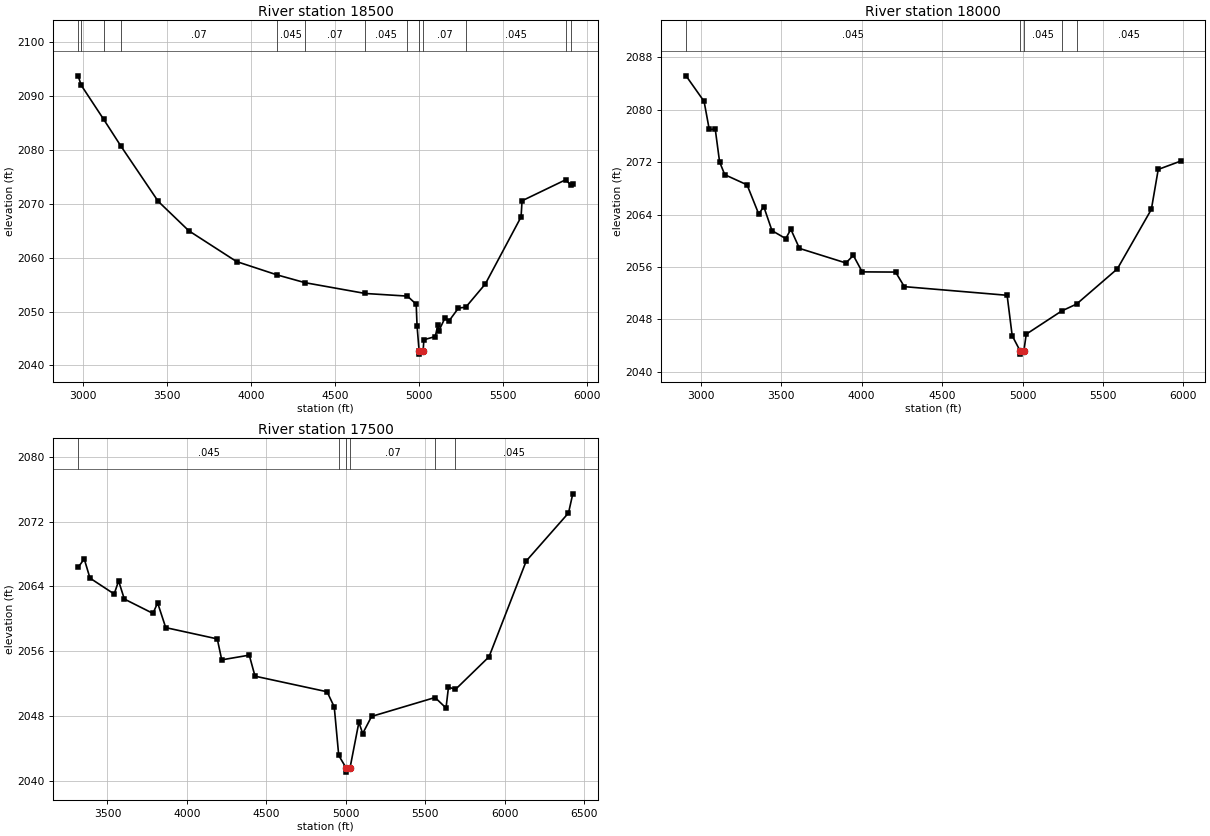
Type RM Length L Ch R = 1,18500,500,500,500
BEGIN DESCRIPTION:
East Cottonwood Creek 36.0
END DESCRIPTION:
XS GIS Cut Line= 4
      1362505.05      6916938.01      1364504.57      6917275.48
      1364588.90      6917259.40      1365305.06      6916836.22
#Sta/Elev= 30
  2972.2 2093.76  2989.9 2092.04  3124.6 2085.66  3227.3 2080.69  3448.8 2070.46
  3631.3 2064.99  3915.3 2059.28  4157.9 2056.79  4323.8 2055.35  4682.3 2053.35
  4933.1 2052.86  4985.2 2051.35  4990.3 2047.36  5002.8 2042.59  5003.3 2042.09
  5026.2 2042.59  5031.0 2044.76  5098.6 2045.35  5114.2 2047.48  5120.0 2046.42
  5157.1 2048.82  5178.6 2048.17  5237.1 2050.65  5280.1 2050.79  5397.0 2055.12
  5609.7 2067.56  5615.6 2070.56  5875.2 2074.46  5904.7 2073.52  5917.7 2073.65
#Mann=13,-1,0
  2972.2   0.035       0  2989.9    0.07       0  3124.6   0.035       0
  3227.3    0.07       0  4157.9   0.045       0  4323.8    0.07       0
  4682.3   0.045       0  4933.1    0.07       0  5002.8    0.07       0
  5026.2    0.07       0  5280.1   0.045       0  5875.2    0.07       0
  5904.7   0.045       0
Bank Sta=5002.8,5026.2
Exp/Cntr=0.3,0.1

Type RM Length L Ch R = 1,18000,500,500,500
BEGIN DESCRIPTION:
East Cottonwood Creek 35.0
END DESCRIPTION:
XS GIS Cut Line= 3
      1362654.99      6917088.00      1364646.09      6917729.52
      1365154.98      6916888.03
#Sta/Elev= 30
  2908.1 2085.15  3020.3 2081.25  3052.4 2076.97  3089.7 2077.01  3116.5 2072.05
  3148.6 2070.08  3287.4 2068.53  3359.9 2064.09  3391.4 2065.20  3442.4 2061.55
  3528.0 2060.33  3559.5 2061.76  3613.2 2058.84  3901.8 2056.62  3948.2 2057.77
  4003.3 2055.26  4210.9 2055.23  4265.0 2053.01  4904.3 2051.69  4935.8 2045.53
  4985.0 2043.22  4985.5 2042.72  5008.6 2043.22  5023.1 2045.76  5243.5 2049.30
  5336.0 2050.35  5589.6 2055.72  5801.1 2064.79  5843.8 2070.88  5983.4 2072.15
#Mann=5,-1,0
  2908.1   0.045       0  4985.0   0.045       0  5008.6   0.045       0
  5243.5   0.035       0  5336.0   0.045       0
Bank Sta=4985,5008.6
Exp/Cntr=0.3,0.1

Type RM Length L Ch R = 1,17500,500,500,500
BEGIN DESCRIPTION:
East Cottonwood Creek 34.0
END DESCRIPTION:
XS GIS Cut Line= 3
      1363453.23      6919089.97      1364854.81      6918155.21
      1365341.92      6916812.65
#Sta/Elev= 30
  3315.3 2066.34  3353.5 2067.40  3389.6 2065.03  3542.0 2063.07  3569.9 2064.68
  3605.9 2062.45  3786.2 2060.68  3815.4 2061.98  3866.4 2058.93  4190.9 2057.54
  4218.9 2054.96  4392.2 2055.54  4428.3 2052.95  4881.9 2051.03  4927.0 2049.16
  4955.2 2043.19  5002.1 2041.63  5002.6 2041.13  5026.1 2041.63  5082.1 2047.27
  5106.0 2045.88  5161.9 2047.99  5561.3 2050.32  5630.5 2049.03  5645.9 2051.60
  5689.9 2051.32  5901.2 2055.34  6135.3 2067.14  6401.2 2073.05  6428.2 2075.41
#Mann=6,-1,0
  3315.3   0.045       0  4955.2    0.07       0  5002.1    0.07       0
  5026.1    0.07       0  5561.3   0.035       0  5689.9   0.045       0
Bank Sta=5002.1,5026.1
Exp/Cntr=0.3,0.1