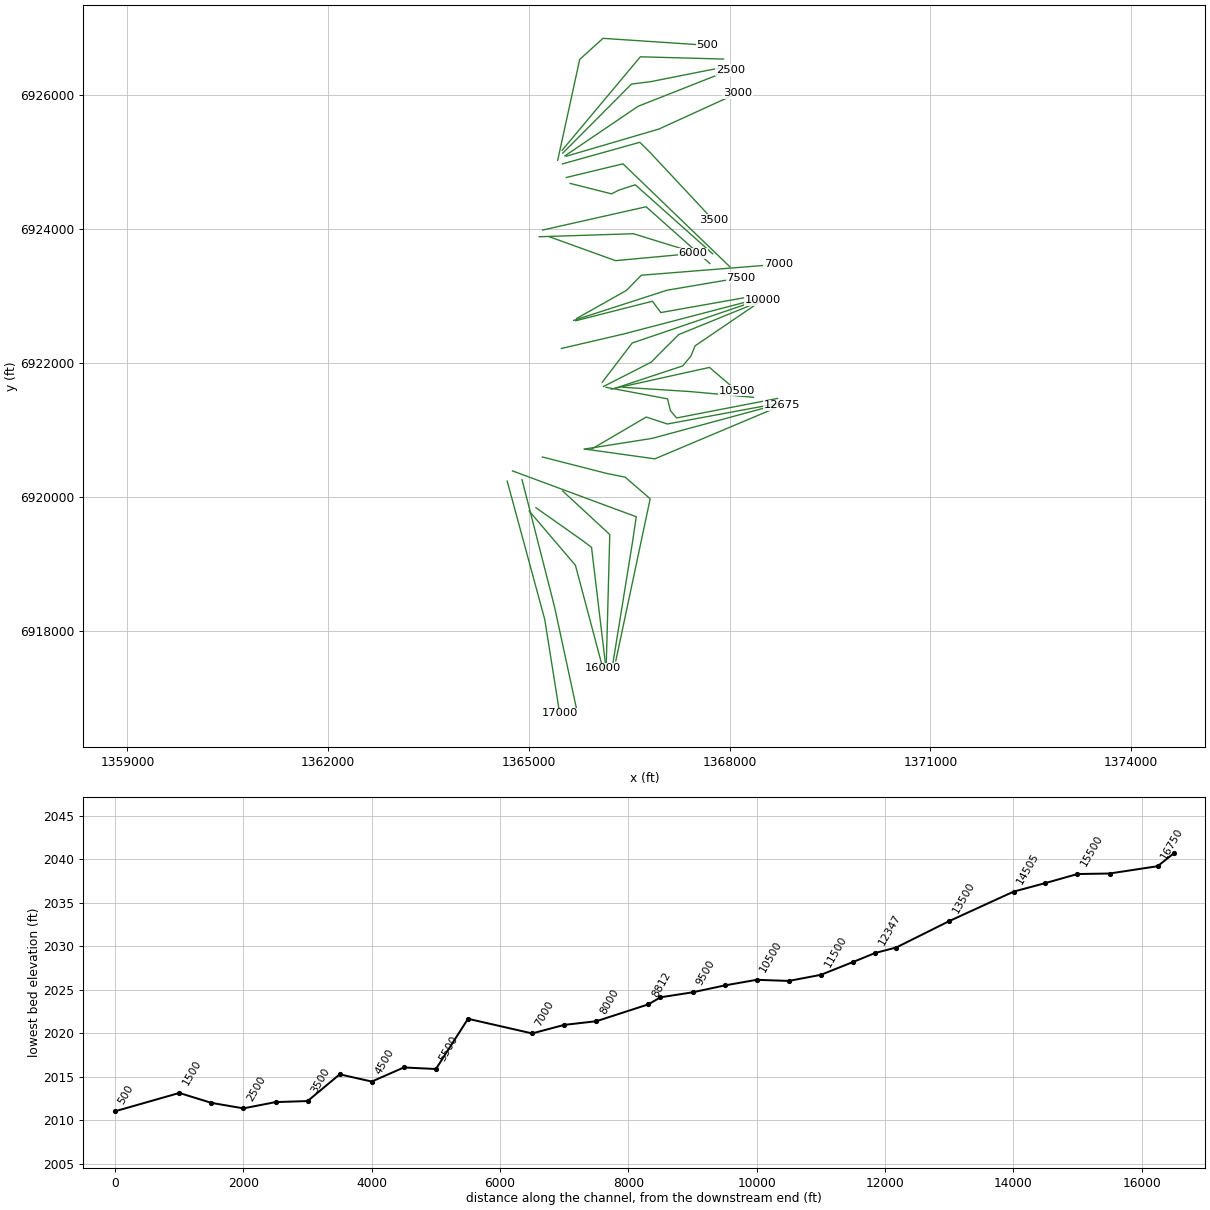
HEC-RAS study East Cottonwood Creek.prj: East Cottonwood Creek Base Level Engineering

--- East Cottonwood Creek.g01 (geometry) --- (continued)

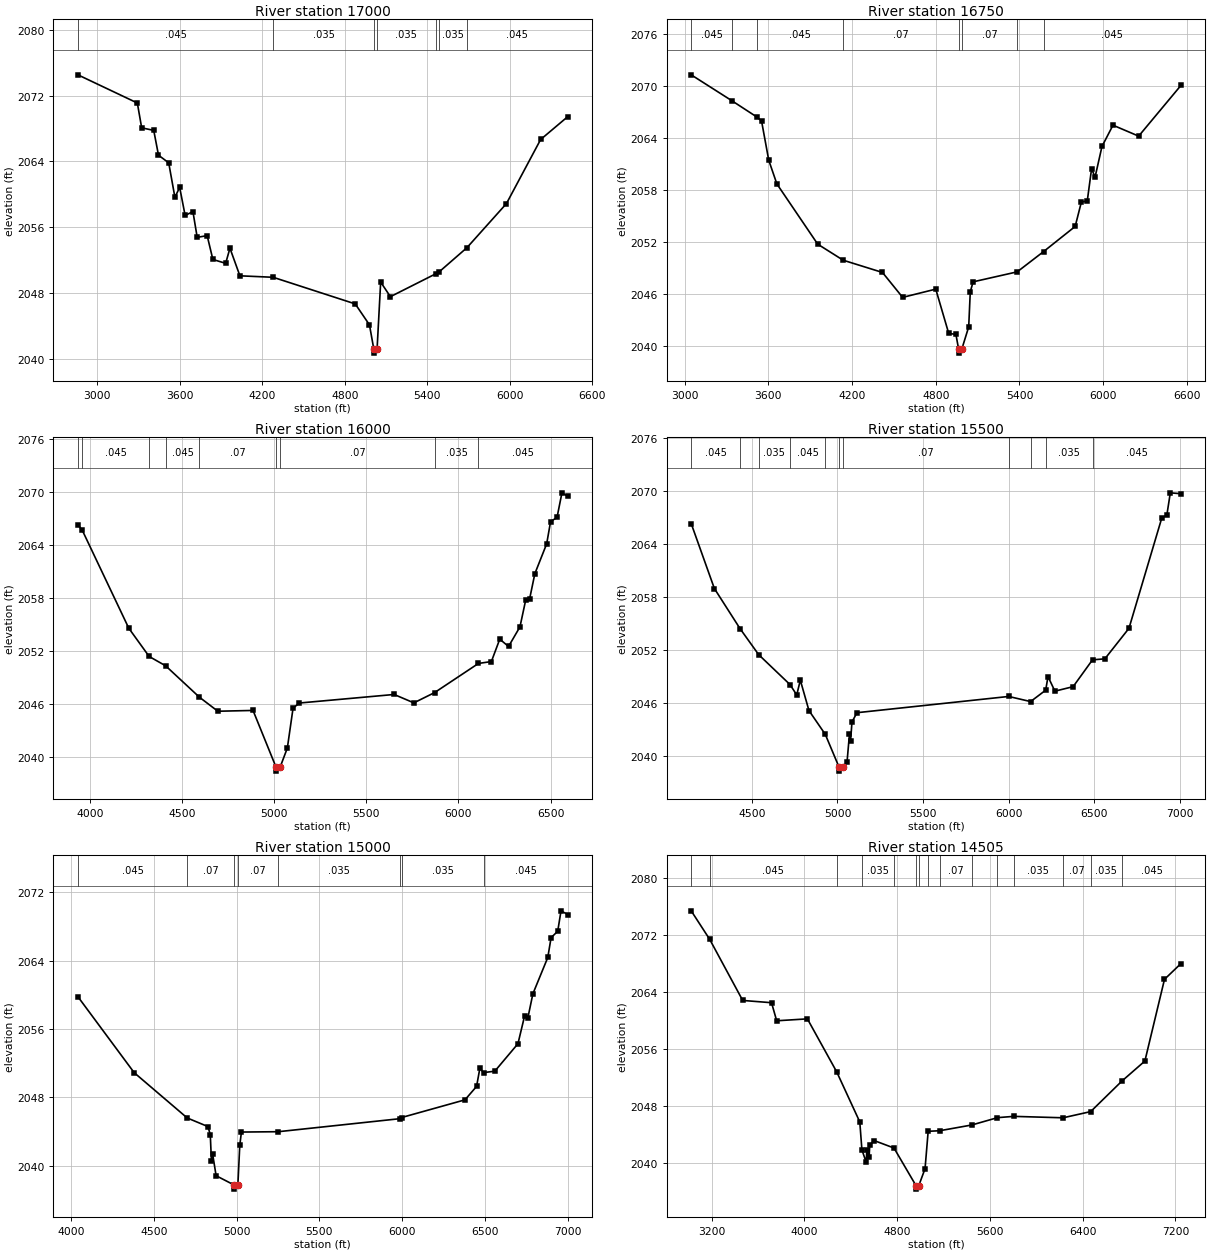
Type RM Length L Ch R = 1,17000,250,250,250
BEGIN DESCRIPTION:
East Cottonwood Creek 33.0
END DESCRIPTION:
XS GIS Cut Line= 3
      1364675.41      6920235.84      1365236.70      6918168.99
      1365460.07      6916764.04
#Sta/Elev= 30
  2858.3 2074.54  3290.8 2071.11  3322.4 2068.09  3410.2 2067.78  3444.8 2064.76
  3519.2 2063.83  3564.3 2059.63  3598.9 2060.85  3638.7 2057.42  3695.4 2057.90
  3726.5 2054.76  3799.0 2054.97  3840.5 2052.07  3933.7 2051.60  3964.8 2053.44
  4037.3 2050.08  4279.3 2049.90  4876.7 2046.66  4980.3 2044.11  5011.7 2041.17
  5012.2 2040.67  5035.7 2041.17  5061.8 2049.32  5132.6 2047.54  5461.1 2050.31
  5486.8 2050.55  5689.5 2053.50  5977.2 2058.87  6226.1 2066.67  6422.6 2069.44
#Mann=7,-1,0
  2858.3   0.045       0  4279.3   0.035       0  5011.7   0.035       0
  5035.7   0.035       0  5461.1   0.045       0  5486.8   0.035       0
  5689.5   0.045       0
Bank Sta=5011.7,5035.7
Exp/Cntr=0.3,0.1

Type RM Length L Ch R = 1,16750,750,750,750
BEGIN DESCRIPTION:
East Cottonwood Creek 32.0
END DESCRIPTION:
XS GIS Cut Line= 3
      1364897.64      6920256.64      1365383.75      6918353.88
      1365709.75      6916841.79
#Sta/Elev= 30
  3046.6 2071.25  3338.0 2068.27  3518.5 2066.38  3550.9 2065.94  3602.5 2061.42
  3660.7 2058.69  3953.5 2051.75  4136.2 2049.90  4417.9 2048.49  4562.4 2045.62
  4799.8 2046.57  4892.7 2041.47  4944.3 2041.36  4963.2 2039.70  4963.7 2039.20
  4987.3 2039.70  5036.0 2042.23  5047.2 2046.26  5067.6 2047.41  5383.6 2048.56
  5573.1 2050.90  5799.2 2053.79  5843.4 2056.59  5886.0 2056.74  5916.7 2060.42
  5942.0 2059.48  5991.3 2063.00  6070.2 2065.45  6254.3 2064.19  6557.3 2070.03
#Mann=8,-1,0
  3046.6   0.045       0  3338.0   0.035       0  3518.5   0.045       0
  4136.2    0.07       0  4963.2    0.07       0  4987.3    0.07       0
  5383.6   0.035       0  5573.1   0.045       0
Bank Sta=4963.2,4987.3
Exp/Cntr=0.3,0.1

Type RM Length L Ch R = 1,16000,500,500,500
BEGIN DESCRIPTION:
East Cottonwood Creek 31.0
END DESCRIPTION:
XS GIS Cut Line= 3
      1365005.00      6919788.00      1365695.48      6918977.29
      1366104.99      6917438.03
#Sta/Elev= 30
  3935.1 2066.29  3958.3 2065.69  4211.3 2054.56  4321.7 2051.36  4411.2 2050.30
  4594.6 2046.74  4694.5 2045.15  4885.5 2045.24  5009.3 2038.86  5009.8 2038.36
  5033.4 2038.86  5071.7 2040.98  5102.7 2045.50  5136.6 2046.08  5651.2 2047.05
  5758.2 2046.10  5870.5 2047.26  6108.9 2050.57  6178.9 2050.78  6224.4 2053.32
  6272.1 2052.49  6334.1 2054.72  6365.2 2057.76  6385.9 2057.83  6414.8 2060.74
  6479.0 2064.13  6500.2 2066.65  6535.2 2067.12  6561.8 2069.91  6592.8 2069.52
#Mann=9,-1,0
  3935.1   0.035       0  3958.3   0.045       0  4321.7    0.07       0
  4411.2   0.045       0  4594.6    0.07       0  5009.3    0.07       0
  5033.4    0.07       0  5870.5   0.035       0  6108.9   0.045       0
Bank Sta=5009.3,5033.4
Exp/Cntr=0.3,0.1

Type RM Length L Ch R = 1,15500,500,500,500
BEGIN DESCRIPTION:
East Cottonwood Creek 30.0
END DESCRIPTION:
XS GIS Cut Line= 4
      1365104.99      6919838.01      1365804.08      6919345.43
      1365936.27      6919245.69      1366154.58      6917416.37
#Sta/Elev= 30
  4144.8 2066.35  4280.3 2058.99  4430.2 2054.45  4539.6 2051.49  4722.3 2048.11
  4761.9 2046.93  4782.8 2048.61  4833.3 2045.16  4928.9 2042.46  5008.2 2038.80
  5008.7 2038.30  5032.4 2038.80  5055.7 2039.28  5070.2 2042.52  5076.5 2041.72
  5084.8 2043.87  5113.9 2044.92  6001.0 2046.76  6129.0 2046.18  6217.2 2047.47
  6230.8 2049.01  6271.1 2047.36  6377.7 2047.87  6491.0 2050.91  6563.1 2051.02
  6704.1 2054.48  6895.5 2066.95  6925.7 2067.32  6945.8 2069.83  7007.9 2069.73
#Mann=11,-1,0
  4144.8   0.045       0  4430.2    0.07       0  4539.6   0.035       0
  4722.3   0.045       0  4928.9    0.07       0  5008.2    0.07       0
  5032.4    0.07       0  6001.0   0.035       0  6129.0    0.07       0
  6217.2   0.035       0  6491.0   0.045       0
Bank Sta=5008.2,5032.4
Exp/Cntr=0.3,0.1

Type RM Length L Ch R = 1,15000,495,495,495
BEGIN DESCRIPTION:
East Cottonwood Creek 29.0
END DESCRIPTION:
XS GIS Cut Line= 3
      1365505.03      6920087.97      1366208.88      6919437.19
      1366155.00      6917438.02
#Sta/Elev= 30
  4041.4 2059.78  4381.3 2050.89  4701.7 2045.59  4826.9 2044.58  4841.1 2043.64
  4847.9 2040.59  4855.3 2041.36  4876.3 2038.83  4983.6 2037.76  4984.1 2037.26
  5007.8 2037.76  5019.2 2042.37  5029.2 2043.94  5251.5 2043.98  5989.7 2045.51
  5997.0 2045.64  6379.7 2047.71  6449.7 2049.28  6469.7 2051.41  6492.1 2050.90
  6559.8 2051.06  6699.8 2054.28  6739.8 2057.53  6759.8 2057.32  6789.8 2060.11
  6879.9 2064.37  6899.9 2066.69  6939.9 2067.44  6959.9 2069.83  6999.9 2069.40
#Mann=8,-1,0
  4041.4   0.045       0  4701.7    0.07       0  4983.6    0.07       0
  5007.8    0.07       0  5251.5   0.035       0  5989.7    0.07       0
  5997.0   0.035       0  6492.1   0.045       0
Bank Sta=4983.6,5007.8
Exp/Cntr=0.3,0.1

Type RM Length L Ch R = 1,14505,1005,1005,1005
BEGIN DESCRIPTION:
East Cottonwood Creek 28.0
END DESCRIPTION:
XS GIS Cut Line= 4
      1364754.98      6920388.01      1366604.56      6919702.73
      1366548.68      6919325.23      1366250.06      6917477.97
#Sta/Elev= 30
  3022.8 2075.41  3182.8 2071.39  3467.2 2062.81  3716.0 2062.49  3760.4 2059.95
  4025.3 2060.22  4278.2 2052.77  4477.4 2045.73  4495.7 2041.81  4532.9 2040.05
  4538.2 2041.85  4557.9 2040.78  4563.3 2042.51  4601.1 2043.11  4772.5 2042.06
  4962.1 2036.78  4962.6 2036.28  4986.6 2036.78  5040.5 2039.16  5067.3 2044.41
  5166.6 2044.49  5444.1 2045.30  5665.4 2046.33  5805.7 2046.51  6231.3 2046.31
  6469.4 2047.18  6739.3 2051.48  6937.1 2054.29  7106.3 2065.78  7248.1 2067.99
#Mann=15,-1,0
  3022.8   0.035       0  3182.8   0.045       0  4278.2    0.07       0
  4495.7   0.035       0  4772.5    0.07       0  4962.1    0.07       0
  4986.6    0.07       0  5067.3   0.035       0  5166.6    0.07       0
  5444.1   0.035       0  5665.4    0.07       0  5805.7   0.035       0
  6231.3    0.07       0  6469.4   0.035       0  6739.3   0.045       0
Bank Sta=4962.1,4986.6
Exp/Cntr=0.3,0.1

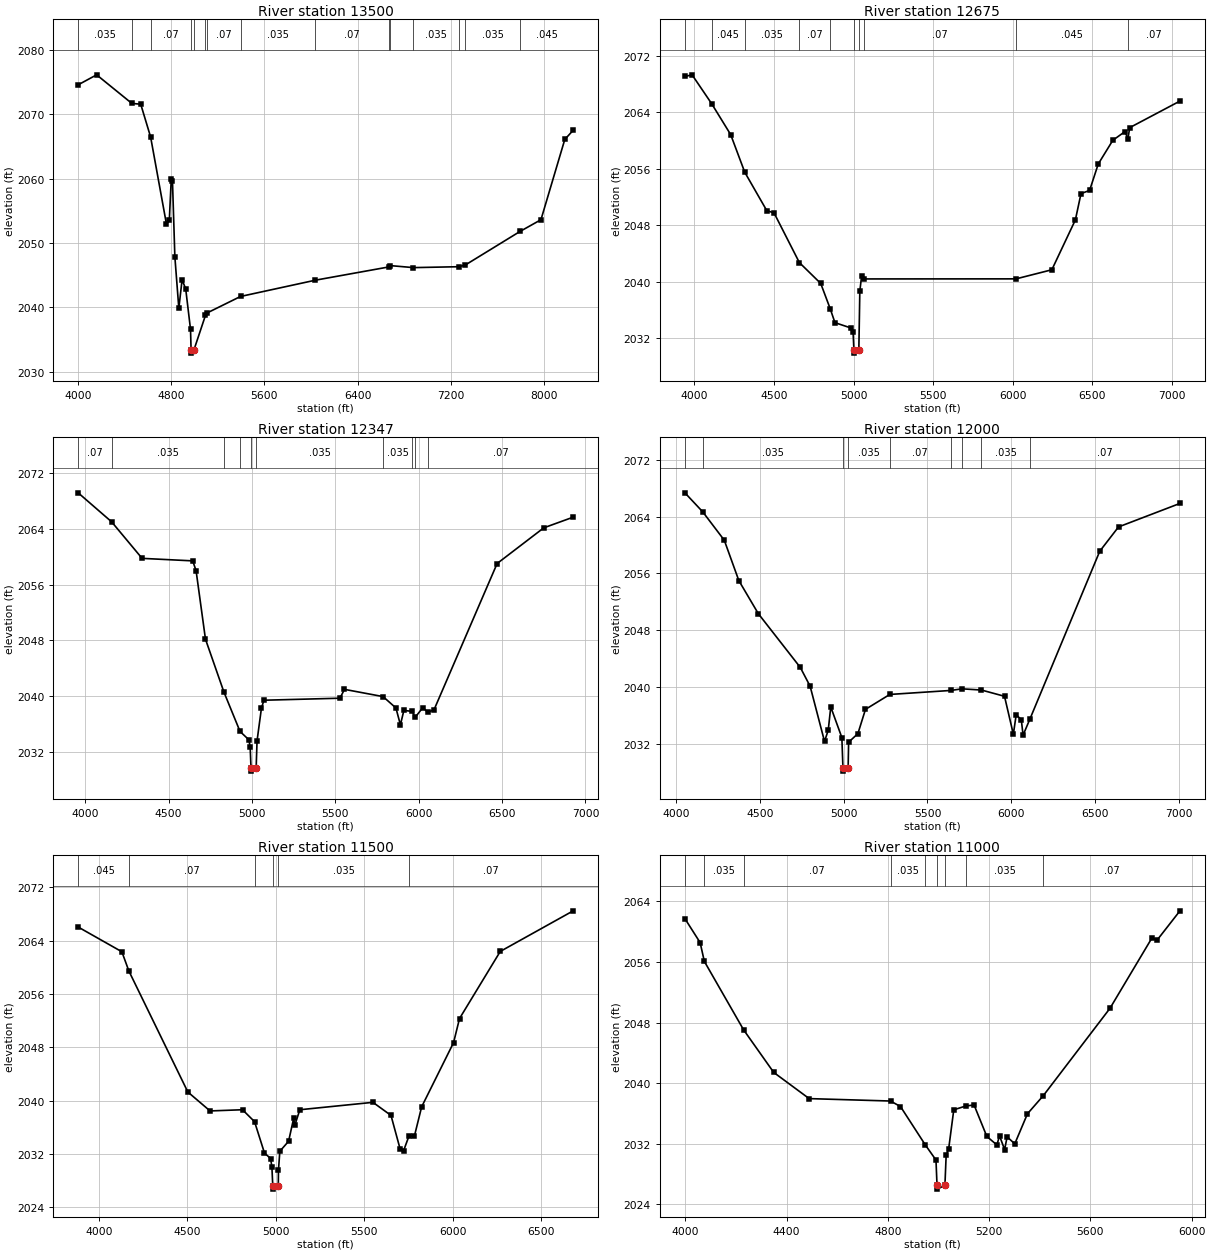
Type RM Length L Ch R = 1,13500,825,825,825
BEGIN DESCRIPTION:
East Cottonwood Creek 26.0
END DESCRIPTION:
XS GIS Cut Line= 5
      1365201.49      6920596.06      1366167.20      6920349.45
      1366439.70      6920294.07      1366812.57      6919971.07
      1366298.67      6917547.44
#Sta/Elev= 30
  4003.3 2074.56  4161.7 2076.11  4463.9 2071.67  4539.8 2071.55  4624.7 2066.45
  4760.4 2052.93  4784.9 2053.49  4801.6 2059.90  4812.0 2059.66  4832.6 2047.84
  4866.6 2039.85  4894.5 2044.28  4925.5 2042.87  4966.8 2036.59  4971.7 2033.39
  4972.2 2032.89  4996.2 2033.39  5095.1 2038.76  5104.6 2039.09  5395.7 2041.69
  6038.4 2044.22  6669.1 2046.28  6681.1 2046.48  6878.6 2046.17  7267.1 2046.31
  7322.2 2046.56  7793.0 2051.79  7972.3 2053.61  8176.8 2066.08  8248.9 2067.50
#Mann=15,-1,0
  4003.3   0.035       0  4463.9   0.045       0  4624.7    0.07       0
  4971.7    0.07       0  4996.2    0.07       0  5095.1   0.035       0
  5104.6    0.07       0  5395.7   0.035       0  6038.4    0.07       0
  6669.1   0.035       0  6681.1    0.07       0  6878.6   0.035       0
  7267.1    0.07       0  7322.2   0.035       0  7793.0   0.045       0
Bank Sta=4971.7,4996.2
Exp/Cntr=0.3,0.1

Type RM Length L Ch R = 1,12675,328,328,328
BEGIN DESCRIPTION:
East Cottonwood Creek 25.0
END DESCRIPTION:
XS GIS Cut Line= 3
      1365840.31      6920714.13      1366882.01      6920568.29
      1368777.82      6921366.89
#Sta/Elev= 30
  3941.2 2069.09  3986.3 2069.32  4109.1 2065.23  4228.7 2060.84  4317.0 2055.51
  4455.0 2050.08  4501.3 2049.73  4660.0 2042.70  4794.1 2039.74  4853.9 2036.14
  4883.4 2034.18  4986.0 2033.41  4997.4 2032.80  5002.5 2030.36  5003.0 2029.86
  5033.5 2030.36  5039.7 2038.66  5050.6 2040.73  5063.0 2040.38  6020.8 2040.39
  6245.6 2041.68  6393.4 2048.75  6428.6 2052.47  6482.9 2052.94  6537.1 2056.68
  6628.7 2060.04  6705.3 2061.28  6723.3 2060.22  6734.5 2061.83  7050.2 2065.60
#Mann=10,-1,0
  3941.2    0.07       0  4109.1   0.045       0  4317.0   0.035       0
  4660.0    0.07       0  4853.9   0.035       0  5002.5   0.035       0
  5033.5   0.035       0  5063.0    0.07       0  6020.8   0.045       0
  6723.3    0.07       0
Bank Sta=5002.5,5033.5
Exp/Cntr=0.3,0.1

Type RM Length L Ch R = 1,12347,347,347,347
BEGIN DESCRIPTION:
East Cottonwood Creek 24.0
END DESCRIPTION:
XS GIS Cut Line= 3
      1365826.45      6920714.12      1366840.34      6920873.84
      1368715.33      6921380.78
#Sta/Elev= 30
  3958.1 2069.15  4158.7 2064.99  4341.4 2059.75  4645.0 2059.39  4665.3 2057.97
  4721.5 2048.16  4832.2 2040.57  4928.8 2034.92  4981.6 2033.73  4989.5 2032.71
  4994.5 2029.73  4995.0 2029.23  5025.5 2029.73  5030.8 2033.57  5057.3 2038.29
  5072.2 2039.40  5528.0 2039.69  5554.9 2040.96  5786.6 2039.92  5863.6 2038.29
  5890.6 2035.87  5911.3 2037.94  5961.4 2037.80  5978.6 2036.93  6025.2 2038.35
  6054.8 2037.66  6092.5 2038.05  6470.5 2059.01  6750.4 2064.13  6926.8 2065.66
#Mann=10,-1,0
  3958.1    0.07       0  4158.7   0.035       0  4832.2    0.07       0
  4928.8   0.035       0  4994.5   0.035       0  5025.5   0.035       0
  5786.6   0.035       0  5961.4   0.045       0  5978.6   0.035       0
  6054.8    0.07       0
Bank Sta=4994.5,5025.5
Exp/Cntr=0.3,0.1

Type RM Length L Ch R = 1,12000,500,500,500
BEGIN DESCRIPTION:
East Cottonwood Creek 23.0
END DESCRIPTION:
XS GIS Cut Line= 4
      1365937.57      6920714.12      1366754.18      6921193.08
      1367069.51      6921089.12      1368715.36      6921394.68
#Sta/Elev= 30
  4053.3 2067.35  4159.7 2064.67  4288.1 2060.68  4374.9 2055.00  4491.3 2050.34
  4741.5 2042.78  4800.1 2040.14  4886.0 2032.37  4908.2 2033.96  4923.2 2037.22
  4989.4 2032.91  4995.8 2028.69  4996.3 2028.19  5026.9 2028.69  5029.7 2032.26
  5085.1 2033.47  5130.2 2036.88  5275.4 2038.98  5637.9 2039.54  5706.5 2039.77
  5822.1 2039.60  5959.5 2038.72  6012.3 2033.38  6029.2 2036.13  6059.7 2035.42
  6070.2 2033.25  6111.1 2035.52  6527.6 2059.13  6639.5 2062.55  7006.0 2065.86
#Mann=9,-1,0
  4053.3    0.07       0  4159.7   0.035       0  4995.8   0.035       0
  5026.9   0.035       0  5275.4    0.07       0  5637.9   0.035       0
  5706.5    0.07       0  5822.1   0.035       0  6111.1    0.07       0
Bank Sta=4995.8,5026.9
Exp/Cntr=0.3,0.1

Type RM Length L Ch R = 1,11500,500,500,500
BEGIN DESCRIPTION:
East Cottonwood Creek 22.0
END DESCRIPTION:
XS GIS Cut Line= 5
      1366152.88      6921637.73      1367072.55      6921464.85
      1367114.71      6921289.12      1367208.40      6921179.40
      1368715.35      6921471.07
#Sta/Elev= 30
  3883.5 2066.04  4130.3 2062.33  4169.7 2059.45  4502.9 2041.29  4628.4 2038.45
  4811.6 2038.63  4879.6 2036.84  4935.6 2032.14  4970.3 2031.31  4977.6 2030.03
  4982.5 2027.22  4983.0 2026.72  5013.6 2027.22  5014.7 2029.59  5022.4 2032.40
  5071.8 2033.90  5100.3 2037.32  5106.9 2036.30  5135.4 2038.63  5548.2 2039.74
  5650.1 2037.78  5701.0 2032.81  5721.4 2032.49  5751.4 2034.67  5782.5 2034.69
  5823.2 2039.06  6003.4 2048.69  6037.1 2052.31  6267.3 2062.38  6679.2 2068.47
#Mann=6,-1,0
  3883.5   0.045       0  4169.7    0.07       0  4879.6   0.035       0
  4982.5   0.035       0  5013.6   0.035       0  5751.4    0.07       0
Bank Sta=4982.5,5013.6
Exp/Cntr=0.3,0.1

Type RM Length L Ch R = 1,11000,500,500,500
BEGIN DESCRIPTION:
East Cottonwood Creek 21.0
END DESCRIPTION:
XS GIS Cut Line= 3
      1366404.96      6921638.00      1367404.93      6921574.30
      1368355.02      6921488.00
#Sta/Elev= 30
  3998.0 2061.73  4058.2 2058.56  4074.7 2056.09  4229.7 2047.06  4348.8 2041.43
  4489.0 2037.97  4810.5 2037.65  4849.8 2036.92  4947.6 2031.87  4990.0 2029.86
  4994.1 2026.52  4994.6 2026.02  5025.3 2026.52  5030.2 2030.47  5040.2 2031.36
  5060.3 2036.49  5109.2 2037.01  5140.6 2037.12  5190.9 2032.98  5230.7 2031.85
  5241.1 2033.06  5261.1 2031.24  5271.2 2032.92  5301.3 2032.00  5351.5 2035.97
  5414.3 2038.37  5677.7 2049.90  5843.5 2059.19  5863.6 2058.89  5954.0 2062.76
#Mann=9,-1,0
  3998.0   0.045       0  4074.7   0.035       0  4229.7    0.07       0
  4810.5   0.035       0  4947.6    0.07       0  4994.1    0.07       0
  5025.3    0.07       0  5109.2   0.035       0  5414.3    0.07       0
Bank Sta=4994.1,5025.3
Exp/Cntr=0.3,0.1

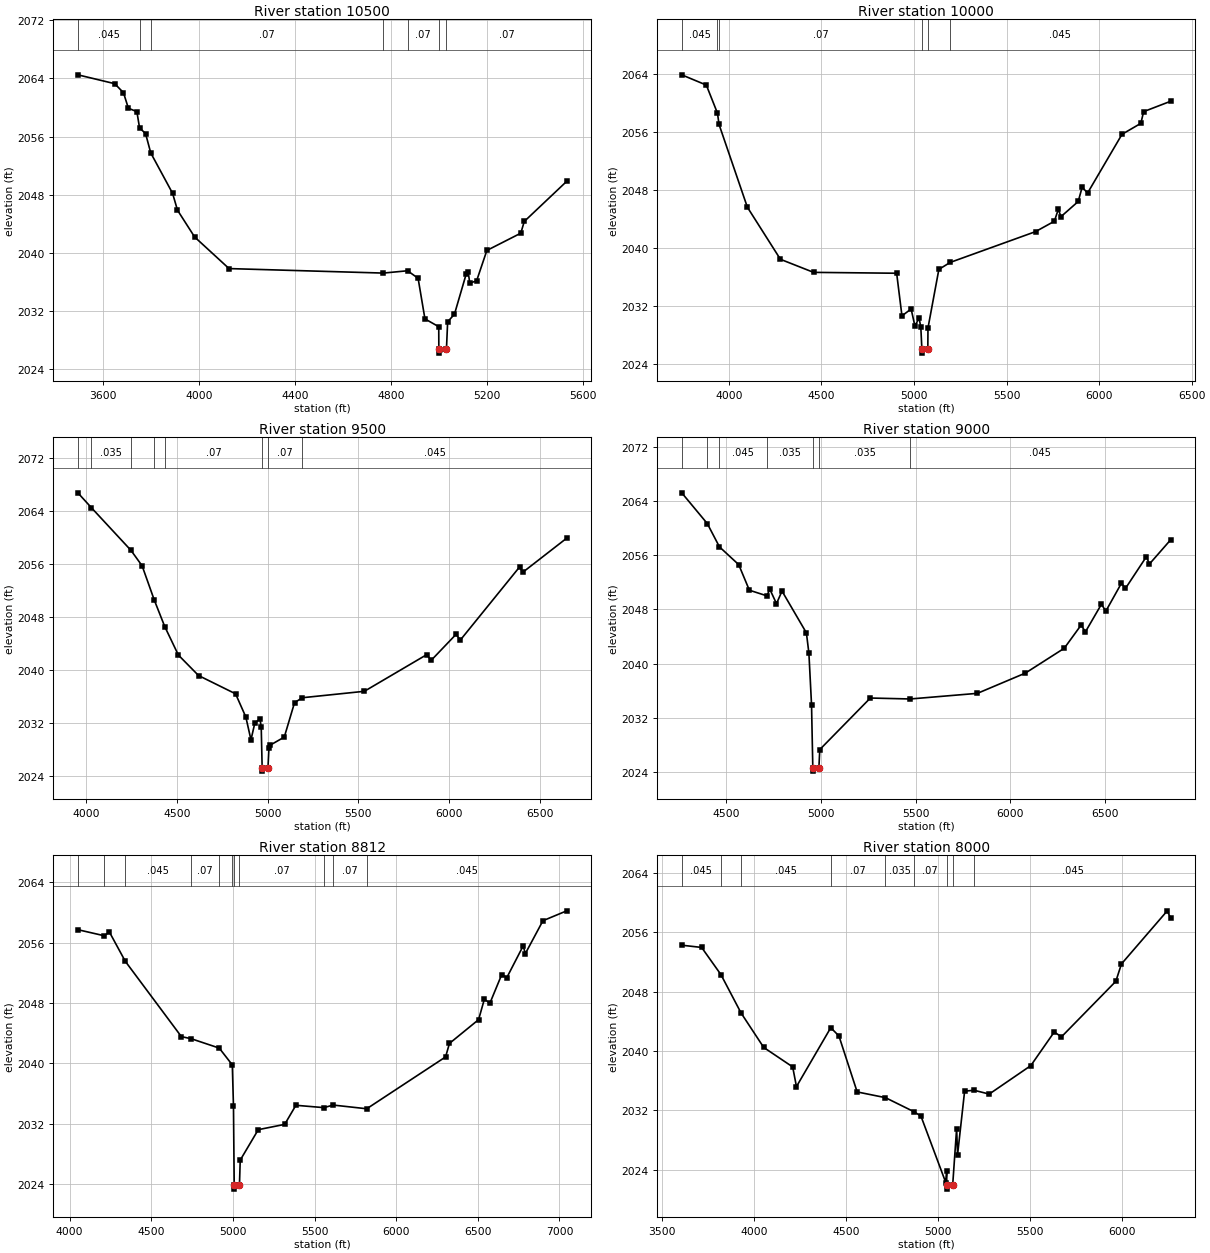
Type RM Length L Ch R = 1,10500,500,500,500
BEGIN DESCRIPTION:
East Cottonwood Creek 20.0
END DESCRIPTION:
XS GIS Cut Line= 3
      1366229.27      6921609.96      1367699.11      6921934.78
      1368105.03      6921587.98
#Sta/Elev= 30
  3494.7 2064.50  3648.4 2063.28  3684.9 2062.04  3705.4 2059.90  3740.9 2059.42
  3752.1 2057.18  3777.1 2056.41  3798.7 2053.74  3889.7 2048.18  3910.2 2045.85
  3981.9 2042.15  4125.3 2037.80  4769.0 2037.18  4870.1 2037.50  4913.9 2036.46
  4942.4 2030.87  5000.0 2029.79  5000.4 2026.65  5000.9 2026.15  5032.1 2026.65
  5037.1 2030.46  5065.6 2031.52  5115.0 2037.11  5122.7 2037.37  5129.3 2035.80
  5157.9 2036.11  5200.7 2040.30  5342.3 2042.68  5356.6 2044.29  5533.9 2049.83
#Mann=7,-1,0
  3494.7   0.045       0  3752.1   0.035       0  3798.7    0.07       0
  4769.0   0.035       0  4870.1    0.07       0  5000.4    0.07       0
  5032.1    0.07       0
Bank Sta=5000.4,5032.1
Exp/Cntr=0.3,0.1

Type RM Length L Ch R = 1,10000,500,500,500
BEGIN DESCRIPTION:
East Cottonwood Creek 19.0
END DESCRIPTION:
XS GIS Cut Line= 5
      1366288.92      6921623.15      1367298.68      6921957.18
      1367420.76      6922103.59      1367484.46      6922257.68
      1368493.16      6922943.31
#Sta/Elev= 30
  3745.8 2063.82  3878.6 2062.41  3938.9 2058.53  3947.1 2057.00  4100.3 2045.59
  4278.8 2038.42  4457.9 2036.62  4906.6 2036.50  4935.2 2030.63  4984.7 2031.58
  5005.1 2029.25  5028.0 2030.32  5037.2 2029.03  5042.9 2026.00  5043.4 2025.50
  5074.9 2026.00  5075.8 2028.96  5134.6 2037.03  5195.7 2037.99  5656.8 2042.23
  5758.5 2043.66  5779.5 2045.28  5794.5 2044.30  5887.3 2046.38  5908.3 2048.33
  5938.2 2047.56  6123.8 2055.63  6225.6 2057.14  6240.5 2058.75  6386.4 2060.18
#Mann=6,-1,0
  3745.8   0.045       0  3938.9   0.035       0  3947.1    0.07       0
  5042.9    0.07       0  5074.9    0.07       0  5195.7   0.045       0
Bank Sta=5042.9,5074.9
Exp/Cntr=0.3,0.1

Type RM Length L Ch R = 1,9500,500,500,500
BEGIN DESCRIPTION:
East Cottonwood Creek 18.0
END DESCRIPTION:
XS GIS Cut Line= 5
      1366116.91      6921650.63      1366825.88      6922011.89
      1367002.88      6922190.55      1367239.54      6922426.05
      1368458.37      6922922.44
#Sta/Elev= 30
  3952.8 2066.72  4027.0 2064.49  4246.0 2058.03  4307.3 2055.70  4374.3 2050.54
  4432.0 2046.54  4507.4 2042.23  4618.6 2039.14  4822.9 2036.38  4879.5 2032.88
  4907.8 2029.43  4929.0 2031.96  4957.2 2032.59  4964.3 2031.44  4969.5 2025.21
  4970.0 2024.71  5001.6 2025.21  5006.8 2028.13  5013.8 2028.63  5091.6 2029.85
  5148.2 2035.05  5191.4 2035.79  5533.3 2036.76  5878.4 2042.31  5901.2 2041.41
  6038.9 2045.35  6063.0 2044.50  6389.4 2055.52  6408.0 2054.74  6649.9 2059.88
#Mann=8,-1,0
  3952.8   0.045       0  4027.0   0.035       0  4246.0    0.07       0
  4374.3   0.035       0  4432.0    0.07       0  4969.5    0.07       0
  5001.6    0.07       0  5191.4   0.045       0
Bank Sta=4969.5,5001.6
Exp/Cntr=0.3,0.1

Type RM Length L Ch R = 1,9000,188,188,188
BEGIN DESCRIPTION:
East Cottonwood Creek 17.0
END DESCRIPTION:
XS GIS Cut Line= 3
      1366097.28      6921714.11      1366543.57      6922299.23
      1368290.89      6922894.39
#Sta/Elev= 30
  4264.1 2065.18  4399.0 2060.65  4463.3 2057.21  4565.0 2054.59  4621.2 2050.82
  4713.6 2049.99  4729.2 2050.96  4764.5 2048.84  4793.6 2050.69  4922.4 2044.53
  4935.6 2041.54  4949.5 2033.96  4956.3 2024.64  4956.8 2024.14  4988.4 2024.64
  4993.1 2027.32  5260.1 2034.92  5470.8 2034.78  5825.5 2035.61  6079.1 2038.60
  6284.2 2042.26  6373.0 2045.67  6396.0 2044.68  6480.5 2048.75  6503.7 2047.73
  6586.1 2051.85  6607.3 2051.08  6717.9 2055.76  6734.0 2054.68  6845.9 2058.25
#Mann=7,-1,0
  4264.1   0.045       0  4399.0   0.035       0  4463.3   0.045       0
  4713.6   0.035       0  4956.3    0.07       0  4988.4   0.035       0
  5470.8   0.045       0
Bank Sta=4956.3,4988.4
Exp/Cntr=0.3,0.1

Type RM Length L Ch R = 1,8812,812,812,812
BEGIN DESCRIPTION:
East Cottonwood Creek 16.0
END DESCRIPTION:
XS GIS Cut Line= 3
      1365486.62      6922218.31      1366423.68      6922436.34
      1368390.19      6922950.06
#Sta/Elev= 30
  4050.2 2057.71  4213.2 2056.90  4242.9 2057.42  4340.8 2053.52  4684.3 2043.54
  4744.7 2043.26  4916.2 2042.02  4996.3 2039.79  5003.4 2034.29  5007.9 2023.83
  5008.4 2023.33  5040.0 2023.83  5044.7 2027.17  5155.3 2031.21  5317.1 2031.91
  5385.7 2034.44  5557.0 2034.13  5614.2 2034.47  5819.7 2033.98  6302.6 2040.85
  6326.3 2042.64  6504.8 2045.79  6540.1 2048.49  6574.3 2047.98  6646.7 2051.77
  6677.7 2051.36  6777.7 2055.55  6791.4 2054.55  6899.0 2058.90  7044.8 2060.21
#Mann=11,-1,0
  4050.2   0.045       0  4213.2   0.035       0  4340.8   0.045       0
  4744.7    0.07       0  4916.2   0.035       0  4996.3    0.07       0
  5007.9    0.07       0  5040.0    0.07       0  5557.0   0.045       0
  5614.2    0.07       0  5819.7   0.045       0
Bank Sta=5007.9,5040
Exp/Cntr=0.3,0.1

Type RM Length L Ch R = 1,8000,500,500,500
BEGIN DESCRIPTION:
East Cottonwood Creek 15.0
END DESCRIPTION:
XS GIS Cut Line= 4
      1365700.18      6922632.37      1366846.04      6922924.05
      1366971.42      6922754.72      1368218.42      6922976.13
#Sta/Elev= 30
  3606.9 2054.24  3715.1 2053.94  3820.1 2050.28  3929.7 2045.11  4052.9 2040.47
  4210.4 2037.85  4231.0 2035.20  4417.6 2043.13  4462.0 2042.02  4561.2 2034.48
  4715.0 2033.71  4868.2 2031.84  4908.1 2031.23  5043.3 2022.27  5048.4 2023.83
  5048.5 2021.89  5049.0 2021.39  5080.7 2021.89  5102.3 2029.55  5107.4 2026.02
  5145.8 2034.59  5198.2 2034.70  5279.6 2034.19  5505.7 2038.02  5633.3 2042.55
  5672.7 2041.90  5968.5 2049.38  5999.0 2051.72  6248.2 2058.87  6266.5 2057.88
#Mann=9,-1,0
  3606.9   0.045       0  3820.1    0.07       0  3929.7   0.045       0
  4417.6    0.07       0  4715.0   0.035       0  4868.2    0.07       0
  5048.5    0.07       0  5080.7    0.07       0  5198.2   0.045       0
Bank Sta=5048.5,5080.7
Exp/Cntr=0.3,0.1

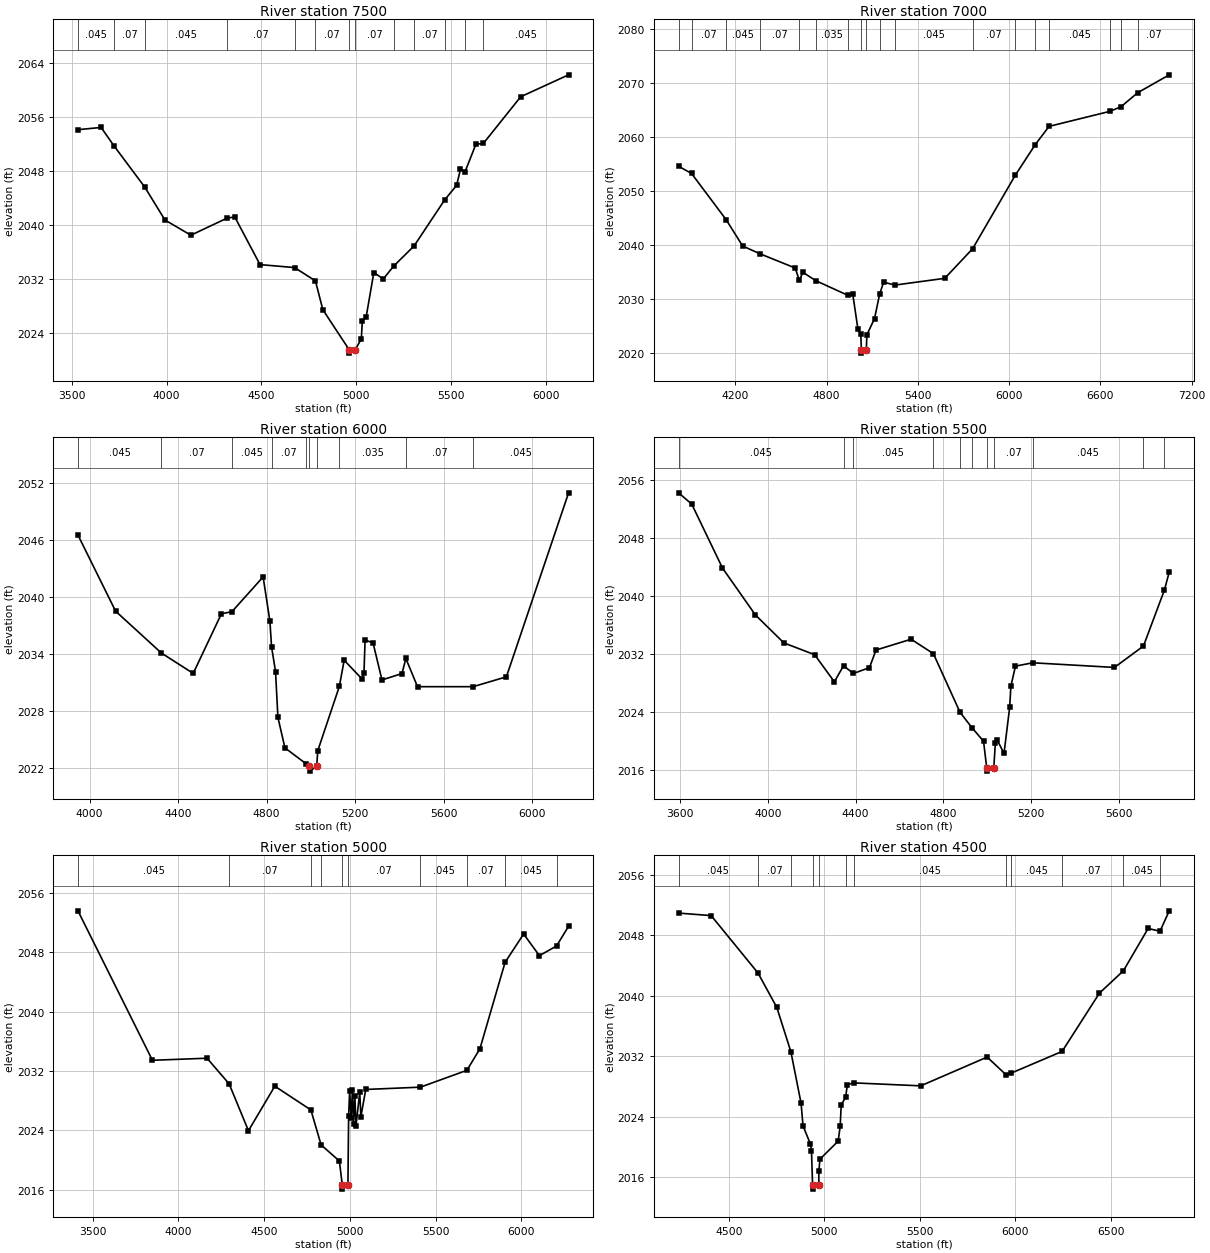
Type RM Length L Ch R = 1,7500,500,500,500
BEGIN DESCRIPTION:
East Cottonwood Creek 14.0
END DESCRIPTION:
XS GIS Cut Line= 3
      1365668.92      6922637.58      1367064.54      6923088.64
      1368166.39      6923275.61
#Sta/Elev= 30
  3533.3 2054.09  3655.3 2054.42  3723.2 2051.69  3885.7 2045.56  3991.6 2040.70
  4128.2 2038.45  4316.4 2040.95  4359.0 2041.17  4492.3 2034.09  4674.3 2033.65
  4784.1 2031.68  4823.1 2027.41  4961.8 2021.47  4962.4 2020.97  4994.0 2021.47
  5025.9 2023.09  5031.0 2025.66  5051.2 2026.32  5091.8 2032.92  5141.5 2031.96
  5195.6 2033.85  5303.8 2036.86  5464.8 2043.68  5527.9 2045.85  5548.2 2048.25
  5571.1 2047.77  5629.3 2051.93  5668.6 2052.05  5865.3 2058.97  6117.6 2062.22
#Mann=13,-1,0
  3533.3   0.045       0  3723.2    0.07       0  3885.7   0.045       0
  4316.4    0.07       0  4674.3   0.035       0  4784.1    0.07       0
  4961.8    0.07       0  4994.0    0.07       0  5195.6   0.045       0
  5303.8    0.07       0  5464.8   0.045       0  5571.1    0.07       0
  5668.6   0.045       0
Bank Sta=4961.8,4994
Exp/Cntr=0.3,0.1

Type RM Length L Ch R = 1,7000,1000,1000,1000
BEGIN DESCRIPTION:
East Cottonwood Creek 13.0
END DESCRIPTION:
XS GIS Cut Line= 4
      1365713.25      6922666.24      1366457.77      6923085.69
      1366680.02      6923312.79      1368725.80      6923476.28
#Sta/Elev= 30
  3827.7 2054.56  3912.7 2053.24  4140.0 2044.69  4248.8 2039.81  4361.0 2038.39
  4594.1 2035.74  4621.0 2033.45  4644.6 2034.93  4731.4 2033.37  4941.3 2030.67
  4971.8 2031.00  5006.4 2024.41  5025.1 2023.46  5029.0 2020.49  5029.5 2019.99
  5061.2 2020.49  5065.2 2023.39  5115.3 2026.38  5149.3 2030.95  5175.5 2033.13
  5248.5 2032.58  5576.8 2033.83  5760.4 2039.32  6041.3 2052.95  6171.2 2058.56
  6262.3 2061.95  6662.1 2064.73  6735.4 2065.59  6845.0 2068.18  7052.3 2071.49
#Mann=18,-1,0
  3827.7   0.045       0  3912.7    0.07       0  4140.0   0.045       0
  4361.0    0.07       0  4621.0   0.033       0  4731.4   0.035       0
  4941.3   0.033       0  5029.0   0.033       0  5061.2   0.033       0
  5149.3   0.035       0  5248.5   0.045       0  5760.4    0.07       0
  6041.3   0.045       0  6171.2    0.07       0  6262.3   0.045       0
  6662.1    0.07       0  6735.4   0.045       0  6845.0    0.07       0
Bank Sta=5029,5061.2
Exp/Cntr=0.3,0.1

Type RM Length L Ch R = 1,6000,500,500,500
BEGIN DESCRIPTION:
East Cottonwood Creek 11.0
END DESCRIPTION:
XS GIS Cut Line= 3
      1365305.04      6923887.99      1366295.38      6923530.47
      1367455.01      6923638.00
#Sta/Elev= 30
  3947.1 2046.55  4117.2 2038.53  4324.1 2034.12  4468.0 2031.97  4595.6 2038.26
  4642.9 2038.47  4784.0 2042.14  4814.7 2037.46  4822.1 2034.78  4840.1 2032.16
  4850.8 2027.34  4882.6 2024.12  4977.3 2022.46  4993.4 2022.17  4993.9 2021.67
  5026.0 2022.17  5031.1 2023.83  5128.5 2030.60  5150.3 2033.36  5230.6 2031.39
  5239.8 2032.04  5244.8 2035.48  5280.8 2035.19  5321.0 2031.28  5411.4 2031.95
  5429.2 2033.54  5481.7 2030.57  5733.0 2030.57  5883.4 2031.61  6164.6 2051.00
#Mann=10,-1,0
  3947.1   0.045       0  4324.1    0.07       0  4642.9   0.045       0
  4822.1    0.07       0  4977.3   0.033       0  4993.4   0.033       0
  5026.0   0.033       0  5128.5   0.035       0  5429.2    0.07       0
  5733.0   0.045       0
Bank Sta=4993.4,5026
Exp/Cntr=0.3,0.1

Type RM Length L Ch R = 1,5500,500,500,500
BEGIN DESCRIPTION:
East Cottonwood Creek 10.0
END DESCRIPTION:
XS GIS Cut Line= 3
      1365155.03      6923888.00      1366561.61      6923933.09
      1367355.01      6923688.00
#Sta/Elev= 30
  3592.7 2054.28  3652.7 2052.72  3792.8 2043.91  3942.9 2037.44  4072.9 2033.58
  4213.0 2031.96  4303.0 2028.22  4344.9 2030.43  4390.0 2029.37  4463.1 2030.17
  4493.1 2032.60  4653.2 2034.09  4754.7 2032.10  4876.1 2024.02  4930.3 2021.90
  4983.4 2020.02  4997.7 2016.40  4998.3 2015.90  5030.3 2016.40  5037.2 2019.74
  5045.4 2020.22  5076.8 2018.34  5102.5 2024.68  5108.2 2027.64  5129.1 2030.38
  5208.3 2030.84  5580.4 2030.20  5712.8 2033.15  5808.5 2040.89  5830.4 2043.37
#Mann=11,-1,0
  3592.7   0.045       0  4344.9    0.07       0  4390.0   0.045       0
  4754.7    0.07       0  4876.1   0.035       0  4930.3    0.07       0
  4997.7    0.07       0  5030.3    0.07       0  5208.3   0.045       0
  5712.8    0.07       0  5808.5   0.045       0
Bank Sta=4997.7,5030.3
Exp/Cntr=0.3,0.1

Type RM Length L Ch R = 1,5000,500,500,500
BEGIN DESCRIPTION:
East Cottonwood Creek 9.0
END DESCRIPTION:
XS GIS Cut Line= 3
      1365205.03      6923988.01      1366751.71      6924335.82
      1367705.03      6923487.97
#Sta/Elev= 30
  3414.7 2053.58  3849.0 2033.44  4167.4 2033.72  4296.2 2030.27  4408.9 2023.95
  4562.6 2029.95  4773.0 2026.75  4832.6 2022.04  4939.2 2019.87  4956.3 2016.58
  4956.9 2016.08  4989.0 2016.58  4993.1 2025.96  4999.1 2029.33  5007.7 2025.61
  5015.2 2029.40  5021.9 2024.88  5029.4 2028.60  5036.1 2024.59  5057.8 2029.14
  5064.5 2025.85  5093.0 2029.51  5411.8 2029.82  5682.7 2032.09  5758.6 2034.99
  5905.4 2046.64  6013.6 2050.46  6105.6 2047.54  6205.7 2048.85  6275.8 2051.51
#Mann=10,-1,0
  3414.7   0.045       0  4296.2    0.07       0  4773.0   0.035       0
  4832.6    0.07       0  4956.3    0.07       0  4989.0    0.07       0
  5411.8   0.045       0  5682.7    0.07       0  5905.4   0.045       0
  6205.7    0.07       0
Bank Sta=4956.3,4989
Exp/Cntr=0.3,0.1

Type RM Length L Ch R = 1,4500,500,500,500
BEGIN DESCRIPTION:
East Cottonwood Creek 8.0
END DESCRIPTION:
XS GIS Cut Line= 5
      1365616.39      6924685.04      1366236.18      6924528.79
      1366345.93      6924585.91      1366590.34      6924664.21
      1367746.54      6923633.01
#Sta/Elev= 30
  4237.1 2050.94  4407.5 2050.61  4652.9 2043.02  4751.3 2038.47  4824.8 2032.63
  4878.4 2025.80  4888.6 2022.81  4927.2 2020.42  4932.8 2019.53  4938.6 2014.96
  4939.1 2014.46  4971.3 2014.96  4971.4 2016.80  4977.0 2018.42  5072.5 2020.80
  5083.0 2022.75  5088.5 2025.63  5111.4 2026.57  5120.7 2028.28  5155.6 2028.50
  5504.8 2028.11  5852.5 2031.91  5951.2 2029.58  5977.2 2029.78  6245.0 2032.66
  6440.3 2040.36  6565.9 2043.32  6695.3 2048.91  6757.3 2048.54  6805.9 2051.24
#Mann=12,-1,0
  4237.1   0.045       0  4652.9    0.07       0  4824.8   0.035       0
  4938.6    0.07       0  4971.3   0.035       0  5111.4   0.035       0
  5155.6   0.045       0  5951.2    0.07       0  5977.2   0.045       0
  6245.0    0.07       0  6565.9   0.045       0  6757.3    0.07       0
Bank Sta=4938.6,4971.3
Exp/Cntr=0.3,0.1

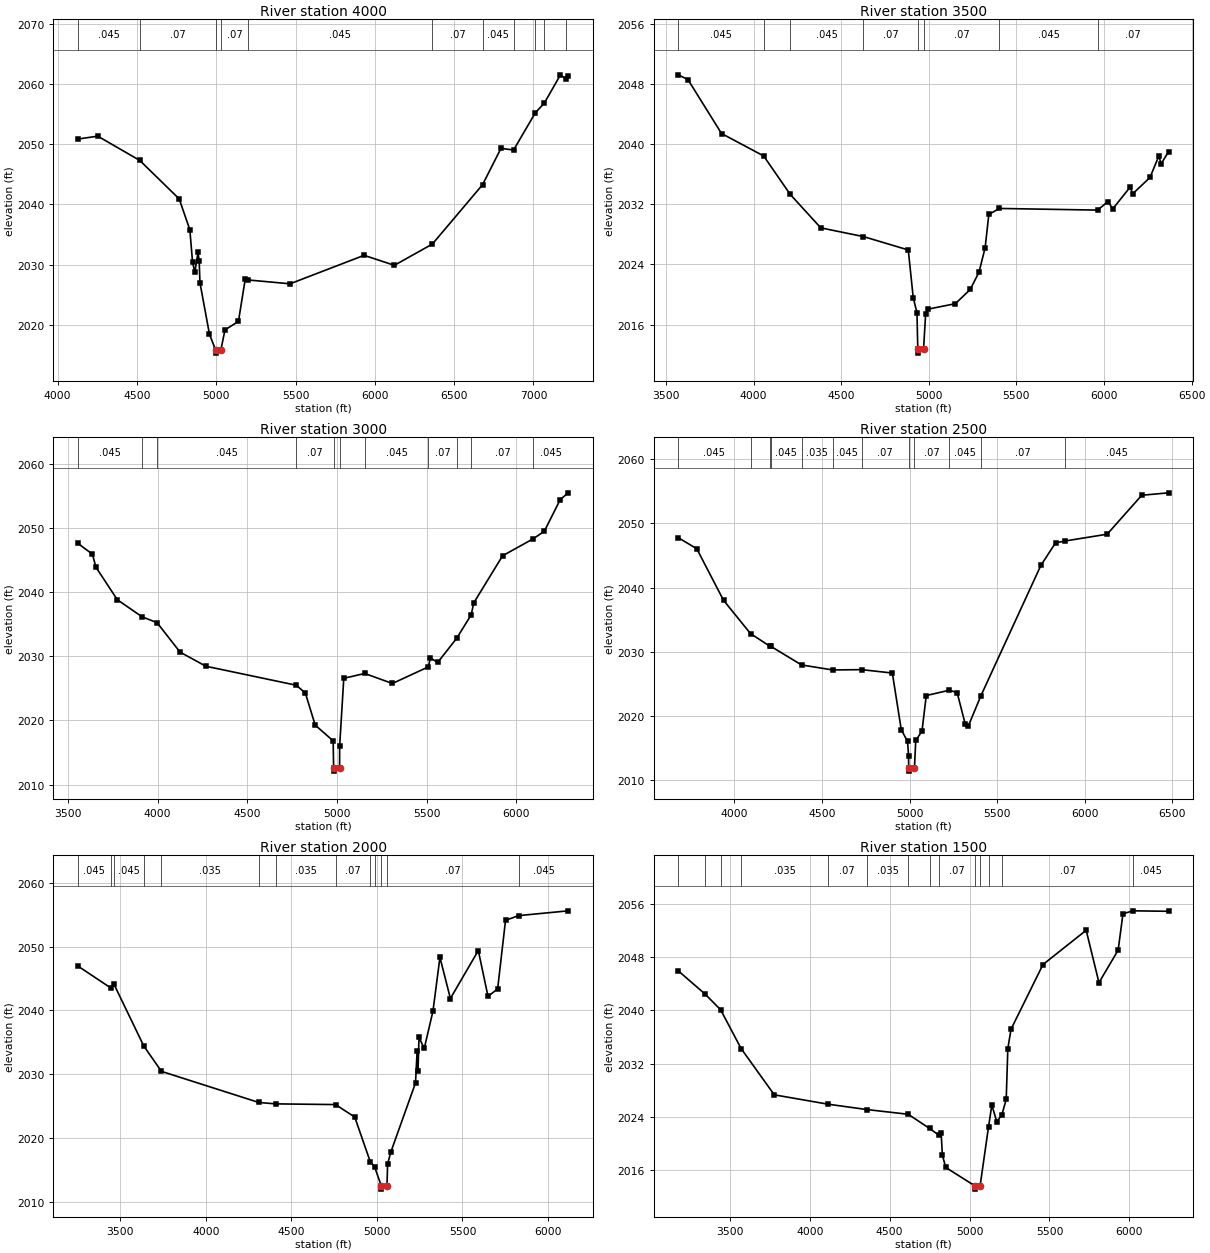
Type RM Length L Ch R = 1,4000,500,500,500
BEGIN DESCRIPTION:
East Cottonwood Creek 7.0
END DESCRIPTION:
XS GIS Cut Line= 3
      1365559.05      6924773.57      1366406.51      6924977.71
      1368004.98      6923438.02
#Sta/Elev= 30
  4128.3 2050.86  4253.3 2051.34  4517.9 2047.31  4766.7 2040.91  4833.9 2035.77
  4850.5 2030.49  4864.7 2028.69  4885.3 2032.01  4892.5 2030.62  4897.6 2026.97
  4957.3 2018.44  4996.4 2015.79  4997.0 2015.29  5029.1 2015.79  5055.2 2019.15
  5140.1 2020.56  5182.6 2027.54  5202.5 2027.44  5465.5 2026.81  5932.2 2031.54
  6123.1 2029.88  6362.5 2033.41  6678.8 2043.27  6795.1 2049.31  6874.6 2049.04
  7011.8 2055.23  7068.3 2056.83  7169.9 2061.53  7204.8 2060.84  7219.4 2061.32
#Mann=11,-1,0
  4128.3   0.045       0  4517.9    0.07       0  4996.4    0.07       0
  5029.1    0.07       0  5202.5   0.045       0  6362.5    0.07       0
  6678.8   0.045       0  6874.6    0.07       0  7011.8   0.045       0
  7068.3    0.07       0  7204.8   0.045       0
Bank Sta=4996.4,5029.1
Exp/Cntr=0.3,0.1

Type RM Length L Ch R = 1,3500,500,500,500
BEGIN DESCRIPTION:
East Cottonwood Creek 6.0
END DESCRIPTION:
XS GIS Cut Line= 4
      1365501.80      6924976.71      1366658.05      6925299.62
      1366820.52      6925137.81      1367754.98      6924138.02
#Sta/Elev= 30
  3570.2 2049.21  3625.4 2048.58  3817.1 2041.41  4057.4 2038.43  4209.1 2033.32
  4383.4 2028.87  4626.9 2027.71  4882.8 2025.93  4911.1 2019.58  4932.3 2017.60
  4937.2 2012.72  4937.7 2012.22  4969.9 2012.72  4981.8 2017.39  4996.0 2018.07
  5151.4 2018.79  5236.4 2020.68  5286.2 2022.97  5321.4 2026.22  5342.4 2030.65
  5402.6 2031.45  5962.9 2031.23  6021.9 2032.35  6050.3 2031.41  6149.4 2034.30
  6163.2 2033.39  6262.3 2035.57  6312.1 2038.40  6326.3 2037.41  6368.5 2039.00
#Mann=8,-1,0
  3570.2   0.045       0  4057.4    0.07       0  4209.1   0.045       0
  4626.9    0.07       0  4937.2    0.07       0  4969.9    0.07       0
  5402.6   0.045       0  5962.9    0.07       0
Bank Sta=4937.2,4969.9
Exp/Cntr=0.3,0.1

Type RM Length L Ch R = 1,3000,500,500,500
BEGIN DESCRIPTION:
East Cottonwood Creek 5.0
END DESCRIPTION:
XS GIS Cut Line= 3
      1365559.07      6925091.29      1366944.01      6925497.93
      1368116.42      6926033.39
#Sta/Elev= 30
  3556.6 2047.58  3637.3 2045.89  3656.6 2043.88  3776.0 2038.80  3914.0 2036.14
  3997.6 2035.22  4125.5 2030.64  4269.4 2028.44  4773.1 2025.48  4823.9 2024.26
  4878.6 2019.27  4978.7 2016.82  4981.3 2012.60  4981.9 2012.10  5014.5 2012.60
  5014.9 2016.00  5037.9 2026.56  5154.8 2027.31  5308.9 2025.75  5508.9 2028.34
  5520.5 2029.73  5561.1 2029.03  5666.7 2032.78  5748.3 2036.47  5761.8 2038.30
  5923.0 2045.65  6094.6 2048.31  6155.4 2049.47  6244.3 2054.41  6288.9 2055.45
#Mann=11,-1,0
  3556.6   0.045       0  3914.0    0.07       0  3997.6   0.045       0
  4773.1    0.07       0  4981.3    0.07       0  5014.5    0.07       0
  5154.8   0.045       0  5508.9    0.07       0  5666.7   0.045       0
  5748.3    0.07       0  6094.6   0.045       0
Bank Sta=4981.3,5014.5
Exp/Cntr=0.3,0.1

Type RM Length L Ch R = 1,2500,500,500,500
BEGIN DESCRIPTION:
East Cottonwood Creek 4.0
END DESCRIPTION:
XS GIS Cut Line= 3
      1365538.24      6925096.49      1366631.77      6925837.59
      1368008.73      6926380.98
#Sta/Elev= 30
  3679.0 2047.77  3784.8 2046.04  3937.5 2038.01  4091.8 2032.82  4201.6 2030.86
  4209.1 2030.81  4383.5 2027.93  4561.1 2027.15  4725.8 2027.20  4902.0 2026.67
  4952.9 2017.85  4988.8 2016.01  4994.8 2013.80  4995.1 2011.88  4995.8 2011.38
  5028.4 2011.88  5035.7 2016.16  5071.3 2017.61  5095.7 2023.16  5227.4 2023.99
  5272.2 2023.62  5317.5 2018.80  5336.5 2018.44  5407.8 2023.12  5750.5 2043.45
  5834.3 2046.96  5890.4 2047.26  6129.3 2048.31  6326.8 2054.38  6480.3 2054.76
#Mann=12,-1,0
  3679.0   0.045       0  4091.8    0.07       0  4201.6   0.035       0
  4209.1   0.045       0  4383.5   0.035       0  4561.1   0.045       0
  4725.8    0.07       0  4995.1    0.07       0  5028.4    0.07       0
  5227.4   0.045       0  5407.8    0.07       0  5890.4   0.045       0
Bank Sta=4995.1,5028.4
Exp/Cntr=0.3,0.1

Type RM Length L Ch R = 1,2000,500,500,500
BEGIN DESCRIPTION:
East Cottonwood Creek 3.0
END DESCRIPTION:
XS GIS Cut Line= 4
      1365507.01      6925138.16      1366533.05      6926169.42
      1366823.67      6926206.46      1367920.97      6926424.19
#Sta/Elev= 30
  3252.3 2046.94  3442.8 2043.54  3463.6 2044.06  3637.3 2034.42  3740.5 2030.45
  4309.5 2025.58  4408.0 2025.36  4758.1 2025.25  4870.3 2023.30  4961.7 2016.25
  4986.2 2015.53  5025.5 2012.51  5026.1 2012.01  5058.8 2012.51  5062.5 2015.96
  5081.4 2017.82  5225.6 2028.64  5234.9 2033.59  5240.0 2030.46  5246.0 2035.77
  5276.6 2034.04  5327.6 2039.88  5368.4 2048.30  5429.5 2041.86  5592.7 2049.37
  5649.4 2042.19  5705.7 2043.37  5751.8 2054.10  5828.4 2054.84  6118.7 2055.59
#Mann=13,-1,0
  3252.3   0.045       0  3442.8    0.07       0  3463.6   0.045       0
  3637.3    0.07       0  3740.5   0.035       0  4309.5    0.07       0
  4408.0   0.035       0  4758.1    0.07       0  4961.7   0.035       0
  4986.2    0.07       0  5025.5    0.07       0  5058.8    0.07       0
  5828.4   0.045       0
Bank Sta=5025.5,5058.8
Exp/Cntr=0.3,0.1

Type RM Length L Ch R = 1,1500,1000,1000,1000
BEGIN DESCRIPTION:
East Cottonwood Creek 2.0
END DESCRIPTION:
XS GIS Cut Line= 3
      1365496.61      6925179.86      1366665.80      6926577.51
      1367910.54      6926543.74
#Sta/Elev= 30
  3177.8 2045.93  3346.0 2042.43  3442.9 2040.08  3570.9 2034.26  3778.5 2027.31
  4113.2 2025.91  4356.9 2025.10  4616.2 2024.39  4749.5 2022.27  4806.1 2021.28
  4822.1 2021.64  4829.9 2018.28  4850.7 2016.41  5032.6 2013.65  5033.2 2013.15
  5065.9 2013.65  5118.8 2022.53  5139.3 2025.78  5170.2 2023.29  5202.2 2024.31
  5229.3 2026.64  5239.3 2034.24  5259.3 2037.16  5459.4 2046.88  5729.5 2052.02
  5809.5 2044.16  5929.5 2049.04  5959.6 2054.50  6022.5 2054.94  6245.2 2054.87
#Mann=14,-1,0
  3177.8   0.045       0  3346.0    0.07       0  3442.9   0.045       0
  3570.9   0.035       0  4113.2    0.07       0  4356.9   0.035       0
  4616.2    0.07       0  4749.5   0.035       0  4806.1    0.07       0
  5032.6    0.07       0  5065.9    0.07       0  5118.8   0.035       0
  5202.2    0.07       0  6022.5   0.045       0
Bank Sta=5032.6,5065.9
Exp/Cntr=0.3,0.1

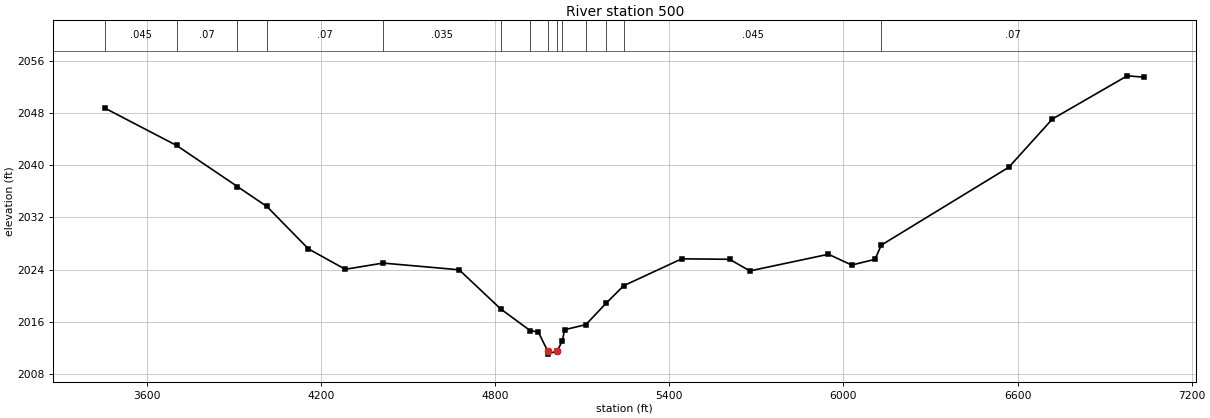
Type RM Length L Ch R = 1,500,0,0,0
BEGIN DESCRIPTION:
East Cottonwood Creek 1.0
END DESCRIPTION:
XS GIS Cut Line= 4
      1365430.61      6925030.50      1365759.32      6926537.98
      1366107.70      6926853.44      1367670.15      6926749.28
#Sta/Elev= 30
  3457.1 2048.70  3702.6 2043.02  3912.3 2036.72  4013.1 2033.69  4157.0 2027.17
  4283.6 2024.05  4414.1 2025.00  4676.1 2023.97  4819.5 2017.96  4920.3 2014.67
  4948.8 2014.43  4980.8 2011.55  4981.4 2011.05  5014.2 2011.55  5031.5 2013.09
  5039.3 2014.79  5112.7 2015.57  5181.9 2018.83  5242.9 2021.53  5442.8 2025.65
  5607.6 2025.58  5677.7 2023.80  5948.3 2026.35  6028.5 2024.70  6108.7 2025.57
  6130.4 2027.75  6569.7 2039.68  6720.1 2047.08  6977.8 2053.69  7035.9 2053.48
#Mann=14,-1,0
  3457.1   0.045       0  3702.6    0.07       0  3912.3   0.035       0
  4013.1    0.07       0  4414.1   0.035       0  4819.5    0.07       0
  4920.3   0.035       0  4980.8   0.035       0  5014.2   0.035       0
  5031.5    0.07       0  5112.7   0.035       0  5181.9    0.07       0
  5242.9   0.045       0  6130.4    0.07       0
Bank Sta=4980.8,5014.2
Exp/Cntr=0.3,0.1

Chan Stop Cuts=-1