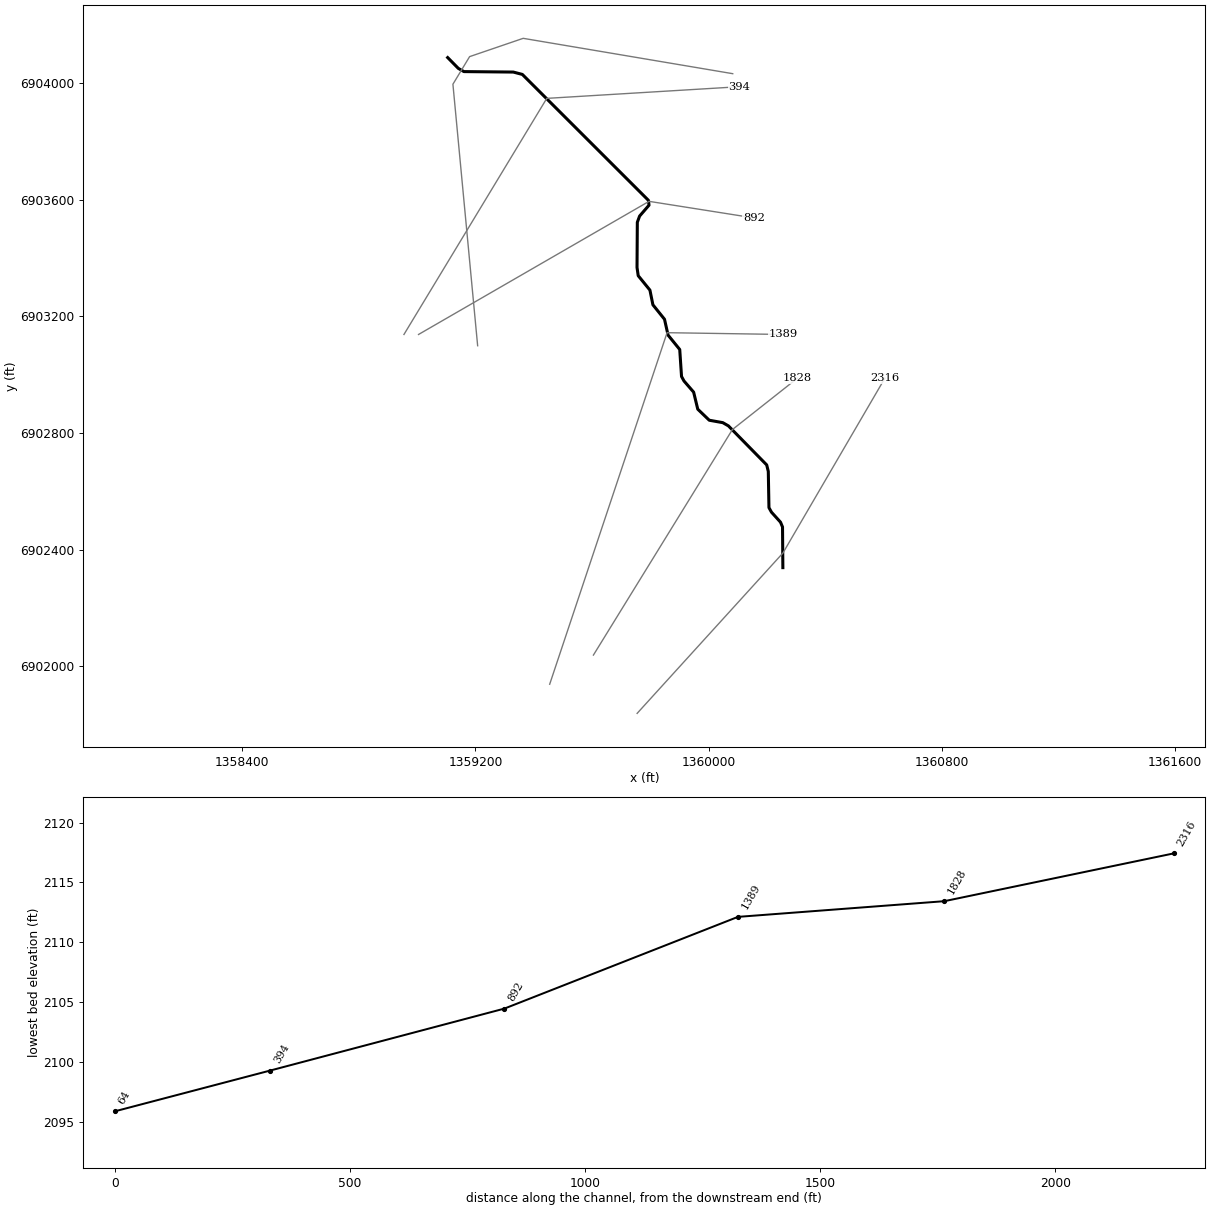
--- East Cottonwood Creek Trib04.prj (project) ---

Proj Title=East Cottonwood Creek Trib04 Base Level Engineering
Current Plan=p01
Default Exp/Contr=0.3,0.1
English Units
Geom File=g01
Flow File=f01
Plan File=p01
BEGIN DESCRIPTION:
East Cottonwood Creek Trib04
END DESCRIPTION:

--- East Cottonwood Creek Trib04.p01 (plan) ---

Plan Title=Multiple Run
Short Identifier=Multiple
Geom File=g01
Flow File=f01
Subcritical Flow
K Sum by GR= 0
Std Step Tol= 0.01
Critical Tol= 0.01
Num of Std Step Trials= 20
Max Error Tol= 0.3
Flow Tol Ratio= 0.001
Split Flow NTrial= 30
Split Flow Tol= 0.02
Split Flow Ratio= 0.02
Log Output Level= 0
Friction Slope Method= 1
Unsteady Friction Slope Method= 2
Unsteady Bridges Friction Slope Method= 1
Parabolic Critical Depth
Global Vel Dist=  1 , 1 , 1
Global Log Level= 0
CheckData=True
Encroach Param= -1, 0, 0, 0
BEGIN DESCRIPTION:
Multiple Run
END DESCRIPTION:

--- East Cottonwood Creek Trib04.f01 (steady flow) ---

Flow Title=Multiple
Number of Profiles=7
Profile Names=10-year,25-year,50-year,1pct_min,100-year,1pct_plu,500-year
River Rch & RM= East Cottonwood ,Reach-1,2316
     318     459     580     364     727    1450    1158
Boundary for River Rch & Prof#=East Cottonwood ,Reach-1,1
Up Type=0
Dn Type=3
Dn Slope=0.005
Boundary for River Rch & Prof#=East Cottonwood ,Reach-1,2
Up Type=0
Dn Type=3
Dn Slope=0.005
Boundary for River Rch & Prof#=East Cottonwood ,Reach-1,3
Up Type=0
Dn Type=3
Dn Slope=0.005
Boundary for River Rch & Prof#=East Cottonwood ,Reach-1,4
Up Type=0
Dn Type=3
Dn Slope=0.005
Boundary for River Rch & Prof#=East Cottonwood ,Reach-1,5
Up Type=0
Dn Type=3
Dn Slope=0.005
Boundary for River Rch & Prof#=East Cottonwood ,Reach-1,6
Up Type=0
Dn Type=3
Dn Slope=0.005
Boundary for River Rch & Prof#=East Cottonwood ,Reach-1,7
Up Type=0
Dn Type=3
Dn Slope=0.005

--- East Cottonwood Creek Trib04.g01 (geometry) ---

Geom Title=Existing Conditions

River Reach=East Cottonwood ,Reach-1
Reach XY= 30
      1360255.00      6902338.00      1360253.83      6902477.52
      1360246.87      6902494.06      1360215.85      6902528.35
      1360207.27      6902543.94      1360205.02      6902668.01
      1360199.53      6902690.45      1360068.20      6902824.36
      1360048.91      6902835.45      1360002.46      6902843.75
      1359963.02      6902881.66      1359948.85      6902940.15
      1359915.83      6902978.34      1359907.33      6902993.96
      1359901.17      6903086.42      1359861.12      6903135.82
      1359848.92      6903190.20      1359809.16      6903239.72
      1359798.88      6903290.18      1359758.75      6903339.55
      1359754.63      6903367.85      1359755.66      6903522.84
      1359763.47      6903544.19      1359795.71      6903581.47
      1359793.90      6903598.06      1359361.19      6904030.19
      1359330.12      6904038.29      1359160.78      6904039.89
      1359141.50      6904050.92      1359105.00      6904088.00

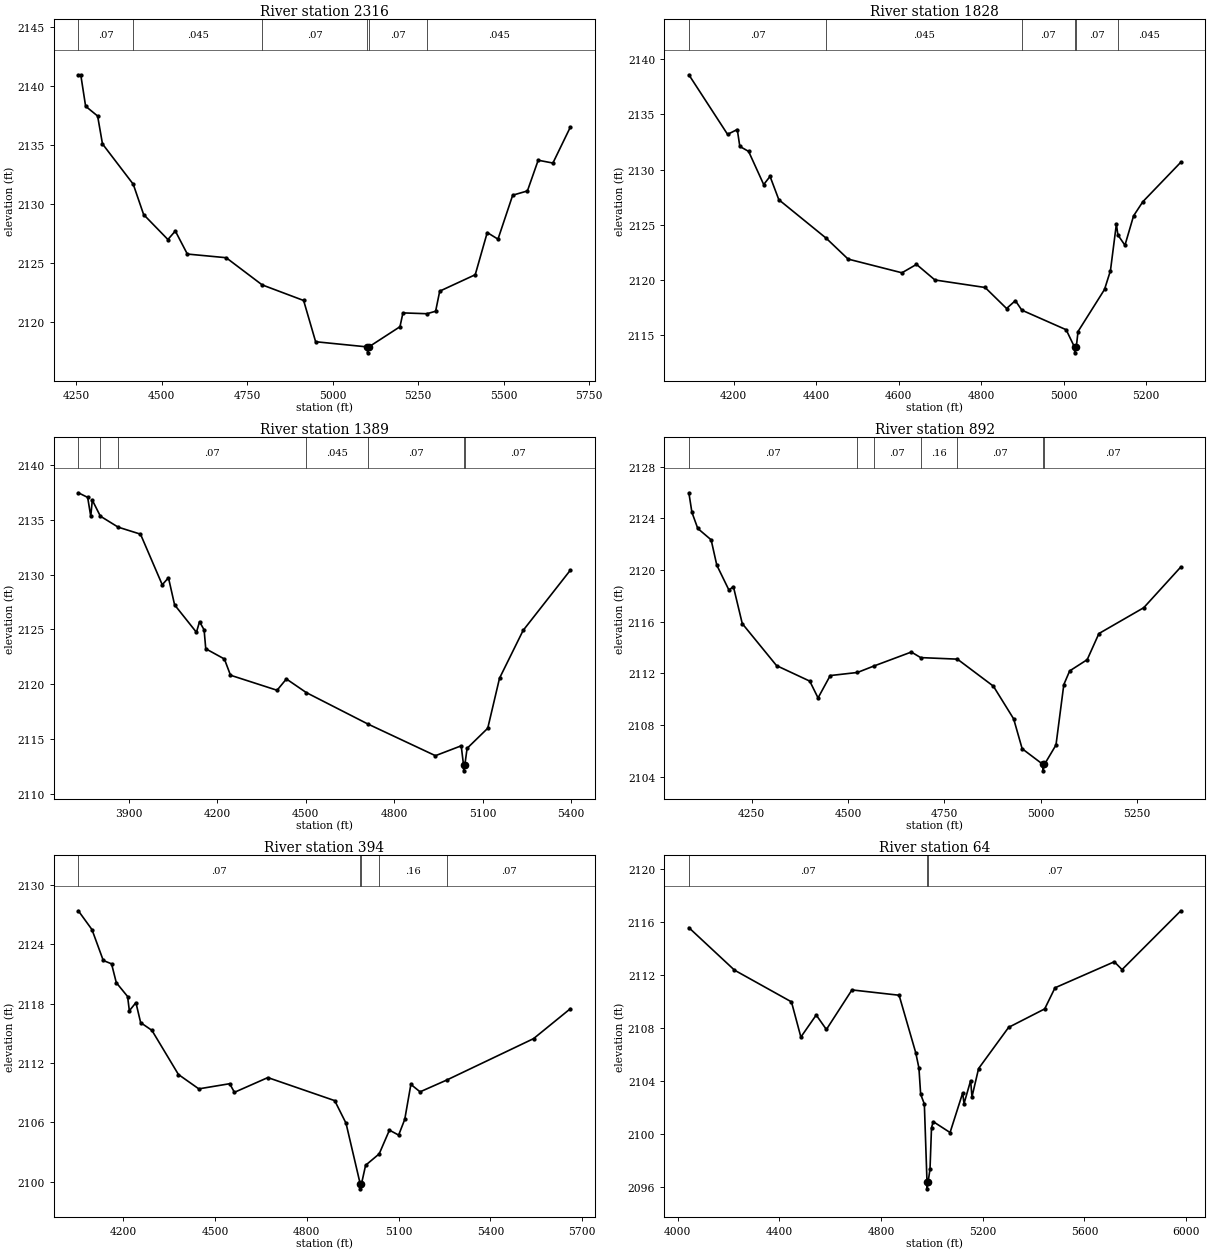
Type RM Length L Ch R = 1,2316,488,488,488
BEGIN DESCRIPTION:
East Cottonwood Creek Trib04 5.0
END DESCRIPTION:
XS GIS Cut Line= 3
      1359755.01      6901838.01      1360255.11      6902388.05
      1360604.99      6902987.98
#Sta/Elev= 30
  4256.6 2140.91  4263.7 2140.95  4277.9 2138.29  4313.0 2137.46  4327.2 2135.10
  4417.1 2131.69  4447.5 2129.12  4518.4 2127.01  4540.1 2127.73  4575.2 2125.78
  4688.7 2125.47  4793.9 2123.17  4915.1 2121.85  4950.2 2118.36  5101.6 2117.92
  5101.9 2117.42  5105.6 2117.92  5196.7 2119.63  5205.4 2120.80  5275.5 2120.73
  5300.9 2120.94  5312.9 2122.64  5416.7 2124.03  5451.8 2127.60  5483.2 2127.04
  5526.2 2130.76  5569.2 2131.12  5600.7 2133.72  5643.7 2133.48  5694.5 2136.51
#Mann=6,-1,0
  4256.6    0.07       0  4417.1   0.045       0  4793.9    0.07       0
  5101.6    0.07       0  5105.6    0.07       0  5275.5   0.045       0
Bank Sta=5101.6,5105.6
Exp/Cntr=0.3,0.1

Type RM Length L Ch R = 1,1828,439,439,439
BEGIN DESCRIPTION:
East Cottonwood Creek Trib04 4.0
END DESCRIPTION:
XS GIS Cut Line= 3
      1359605.02      6902038.03      1360081.82      6902811.70
      1360304.99      6902987.99
#Sta/Elev= 30
  4091.2 2138.58  4185.1 2133.19  4208.6 2133.63  4214.8 2132.10  4236.1 2131.65
  4272.7 2128.65  4288.1 2129.39  4309.4 2127.28  4424.2 2123.80  4477.4 2121.91
  4608.0 2120.67  4643.3 2121.43  4688.0 2120.02  4809.8 2119.34  4861.8 2117.44
  4883.1 2118.15  4898.8 2117.29  5006.3 2115.52  5026.8 2113.93  5027.0 2113.43
  5030.8 2113.93  5035.1 2115.36  5099.3 2119.16  5113.7 2120.86  5128.1 2125.07
  5131.8 2124.09  5148.9 2123.16  5169.8 2125.82  5192.3 2127.10  5284.4 2130.67
#Mann=6,-1,0
  4091.2    0.07       0  4424.2   0.045       0  4898.8    0.07       0
  5026.8    0.07       0  5030.8    0.07       0  5131.8   0.045       0
Bank Sta=5026.8,5030.8
Exp/Cntr=0.3,0.1

Type RM Length L Ch R = 1,1389,497,497,497
BEGIN DESCRIPTION:
East Cottonwood Creek Trib04 3.0
END DESCRIPTION:
XS GIS Cut Line= 3
      1359454.99      6901937.97      1359857.70      6903144.12
      1360254.96      6903138.00
#Sta/Elev= 30
  3728.4 2137.45  3760.1 2137.03  3770.6 2135.30  3775.8 2136.78  3803.1 2135.32
  3863.5 2134.32  3939.3 2133.68  4013.1 2129.07  4034.2 2129.71  4055.0 2127.24
  4129.1 2124.74  4139.6 2125.71  4155.1 2124.96  4160.7 2123.24  4223.9 2122.31
  4244.6 2120.83  4402.6 2119.46  4434.2 2120.49  4501.7 2119.25  4709.6 2116.40
  4939.8 2113.50  5027.3 2114.40  5035.3 2112.62  5035.6 2112.12  5039.4 2112.62
  5047.3 2114.17  5117.3 2116.00  5157.3 2120.56  5237.3 2124.91  5397.3 2130.39
#Mann=7,-1,0
  3728.4    0.07       0  3803.1    0.16       0  3863.5    0.07       0
  4501.7   0.045       0  4709.6    0.07       0  5035.3    0.07       0
  5039.4    0.07       0
Bank Sta=5035.3,5039.4
Exp/Cntr=0.3,0.1

Type RM Length L Ch R = 1,892,498,498,498
BEGIN DESCRIPTION:
East Cottonwood Creek Trib04 2.0
END DESCRIPTION:
XS GIS Cut Line= 3
      1359004.99      6903137.99      1359795.87      6903594.74
      1360155.02      6903538.00
#Sta/Elev= 30
  4086.7 2125.97  4094.6 2124.46  4109.8 2123.21  4144.5 2122.33  4159.2 2120.37
  4190.6 2118.45  4202.3 2118.71  4225.3 2115.85  4314.3 2112.60  4400.5 2111.40
  4422.0 2110.10  4453.6 2111.83  4524.3 2112.07  4566.2 2112.56  4664.1 2113.65
  4688.4 2113.22  4783.7 2113.10  4877.1 2111.01  4929.7 2108.48  4951.8 2106.17
  5005.6 2104.96  5005.9 2104.46  5009.7 2104.96  5039.6 2106.46  5059.9 2111.13
  5075.1 2112.19  5120.6 2113.06  5151.0 2115.08  5267.4 2117.08  5363.6 2120.23
#Mann=7,-1,0
  4086.7    0.07       0  4524.3    0.16       0  4566.2    0.07       0
  4688.4    0.16       0  4783.7    0.07       0  5005.6    0.07       0
  5009.7    0.07       0
Bank Sta=5005.6,5009.7
Exp/Cntr=0.3,0.1

Type RM Length L Ch R = 1,394,330,330,330
BEGIN DESCRIPTION:
East Cottonwood Creek Trib04 1.0
END DESCRIPTION:
XS GIS Cut Line= 3
      1358955.00      6903138.00      1359445.01      6903948.02
      1360105.00      6903988.00
#Sta/Elev= 30
  4053.3 2127.38  4097.9 2125.48  4134.8 2122.36  4161.9 2122.02  4177.4 2120.12
  4214.3 2118.72  4220.1 2117.28  4241.5 2118.10  4257.0 2116.08  4293.8 2115.30
  4380.5 2110.84  4447.1 2109.39  4548.0 2109.91  4563.5 2109.04  4672.7 2110.53
  4891.3 2108.20  4928.2 2105.92  4974.6 2099.79  4974.9 2099.29  4978.8 2099.79
  4992.2 2101.67  5036.6 2102.82  5070.1 2105.22  5100.2 2104.72  5120.2 2106.31
  5140.2 2109.84  5170.3 2109.09  5257.4 2110.28  5541.0 2114.46  5661.2 2117.48
#Mann=5,-1,0
  4053.3    0.07       0  4974.6    0.07       0  4978.8    0.07       0
  5036.6    0.16       0  5257.4    0.07       0
Bank Sta=4974.6,4978.8
Exp/Cntr=0.3,0.1

Type RM Length L Ch R = 1,64,0,0,0
BEGIN DESCRIPTION:
East Cottonwood Creek Trib04 0.5
END DESCRIPTION:
XS GIS Cut Line= 5
      1359207.82      6903099.36      1359122.98      6903996.57
      1359180.25      6904091.25      1359364.07      6904154.01
      1360083.00      6904032.75
#Sta/Elev= 30
  4043.7 2115.56  4223.1 2112.36  4447.3 2109.97  4484.3 2107.32  4544.6 2108.98
  4584.7 2107.89  4685.2 2110.87  4870.7 2110.47  4936.3 2106.13  4948.7 2104.99
  4955.5 2103.01  4970.0 2102.28  4980.5 2096.39  4980.8 2095.89  4984.7 2096.39
  4992.3 2097.38  4998.2 2100.50  5005.0 2100.95  5071.2 2100.13  5120.8 2103.11
  5126.1 2102.31  5152.1 2104.04  5157.4 2102.82  5183.4 2104.95  5301.5 2108.05
  5443.4 2109.44  5484.0 2111.03  5717.3 2112.99  5747.7 2112.40  5978.9 2116.83
#Mann=3,-1,0
  4043.7    0.07       0  4980.5    0.07       0  4984.7    0.07       0
Bank Sta=4980.5,4984.7
Exp/Cntr=0.3,0.1

Chan Stop Cuts=-1