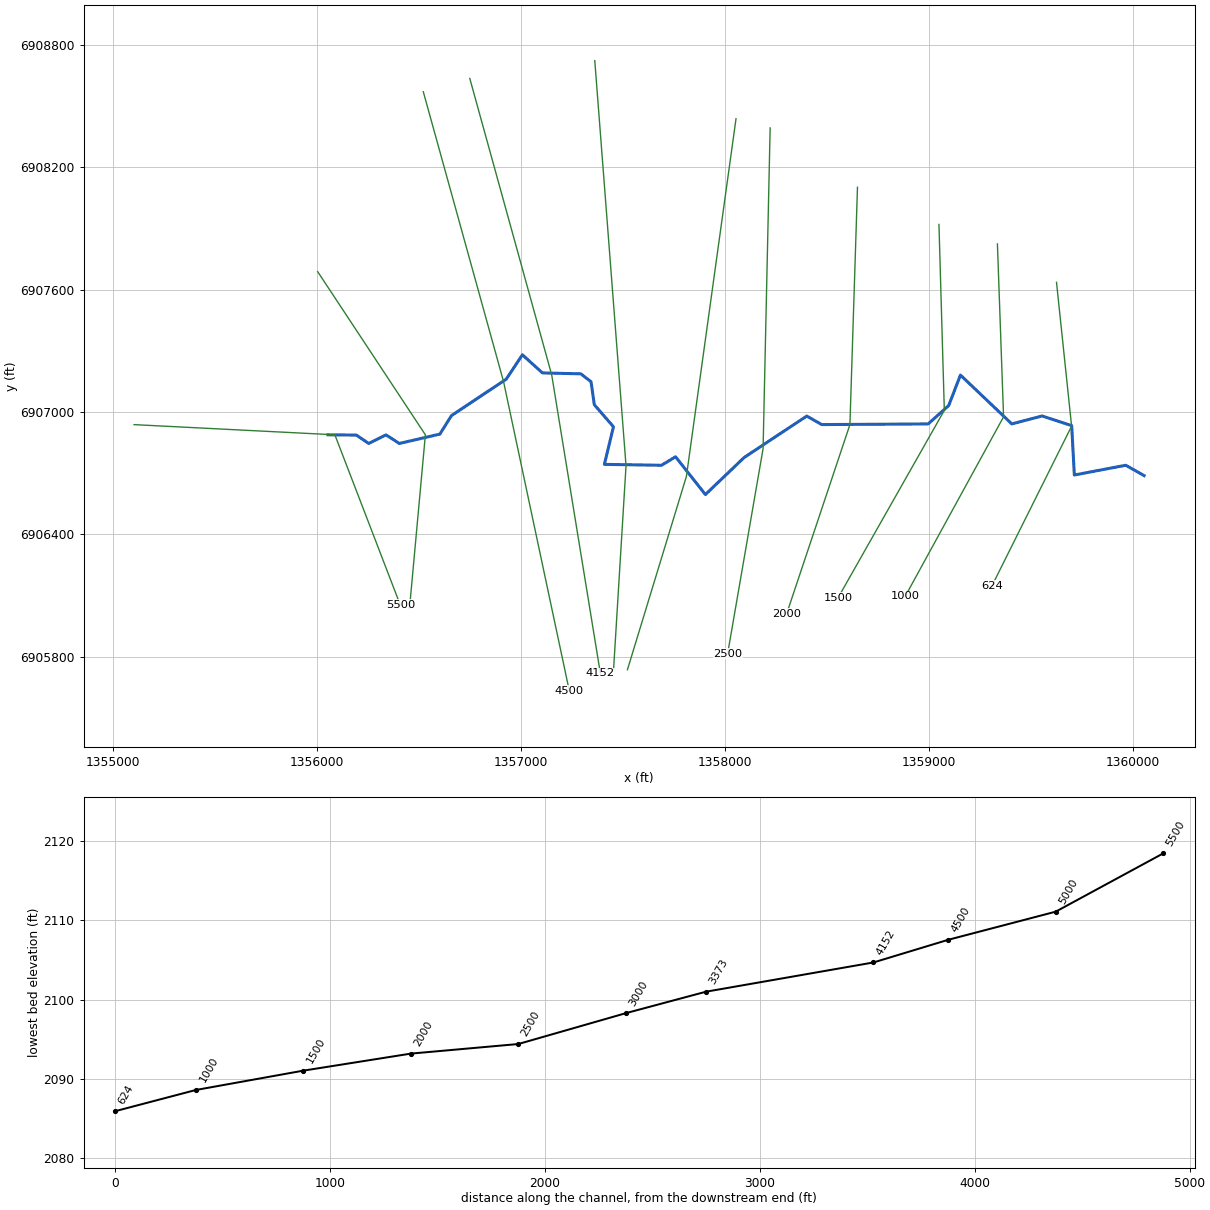
--- East Cottonwood Creek Trib05.prj (project) ---

Proj Title=East Cottonwood Creek Trib05 Base Level Engineering
Current Plan=p01
Default Exp/Contr=0.3,0.1
English Units
Geom File=g01
Flow File=f01
Plan File=p01
BEGIN DESCRIPTION:
East Cottonwood Creek Trib05
END DESCRIPTION:

--- East Cottonwood Creek Trib05.p01 (plan) ---

Plan Title=Multiple Run
Short Identifier=Multiple
Geom File=g01
Flow File=f01
Subcritical Flow
K Sum by GR= 0
Std Step Tol= 0.01
Critical Tol= 0.01
Num of Std Step Trials= 20
Max Error Tol= 0.3
Flow Tol Ratio= 0.001
Split Flow NTrial= 30
Split Flow Tol= 0.02
Split Flow Ratio= 0.02
Log Output Level= 0
Friction Slope Method= 1
Unsteady Friction Slope Method= 2
Unsteady Bridges Friction Slope Method= 1
Parabolic Critical Depth
Global Vel Dist=  1 , 1 , 1
Global Log Level= 0
CheckData=True
Encroach Param= -1, 0, 0, 0
BEGIN DESCRIPTION:
Multiple Run
END DESCRIPTION:

--- East Cottonwood Creek Trib05.f01 (steady flow) ---

Flow Title=Multiple
Number of Profiles=7
Profile Names=10-year,25-year,50-year,1pct_min,100-year,1pct_plu,500-year
River Rch & RM= East Cottonwood ,Reach-1,5500
     330     478     606     382     762    1521    1223
River Rch & RM= East Cottonwood ,Reach-1,4152
     374     544     690     435     869    1733    1395
Boundary for River Rch & Prof#=East Cottonwood ,Reach-1,1
Up Type=0
Dn Type=3
Dn Slope=0.005
Boundary for River Rch & Prof#=East Cottonwood ,Reach-1,2
Up Type=0
Dn Type=3
Dn Slope=0.005
Boundary for River Rch & Prof#=East Cottonwood ,Reach-1,3
Up Type=0
Dn Type=3
Dn Slope=0.005
Boundary for River Rch & Prof#=East Cottonwood ,Reach-1,4
Up Type=0
Dn Type=3
Dn Slope=0.005
Boundary for River Rch & Prof#=East Cottonwood ,Reach-1,5
Up Type=0
Dn Type=3
Dn Slope=0.005
Boundary for River Rch & Prof#=East Cottonwood ,Reach-1,6
Up Type=0
Dn Type=3
Dn Slope=0.005
Boundary for River Rch & Prof#=East Cottonwood ,Reach-1,7
Up Type=0
Dn Type=3
Dn Slope=0.005

--- East Cottonwood Creek Trib05.g01 (geometry) ---

Geom Title=Existing Conditions

River Reach=East Cottonwood ,Reach-1
Reach XY= 30
      1356055.00      6906888.00      1356194.59      6906886.66
      1356255.01      6906845.58      1356339.64      6906887.71
      1356404.99      6906845.59      1356603.73      6906891.48
      1356660.64      6906982.35      1356928.84      6907160.87
      1357008.15      6907280.47      1357106.46      6907191.56
      1357294.73      6907187.02      1357344.64      6907148.16
      1357360.54      6907035.58      1357454.39      6906927.38
      1357409.92      6906743.03      1357689.85      6906738.67
      1357758.67      6906780.31      1357904.99      6906595.07
      1358095.32      6906777.22      1358401.68      6906979.96
      1358474.98      6906938.18      1358996.56      6906941.40
      1359097.21      6907031.56      1359154.76      6907181.03
      1359406.50      6906941.46      1359555.00      6906980.44
      1359699.97      6906932.93      1359712.91      6906690.90
      1359965.02      6906738.78      1360055.00      6906688.00

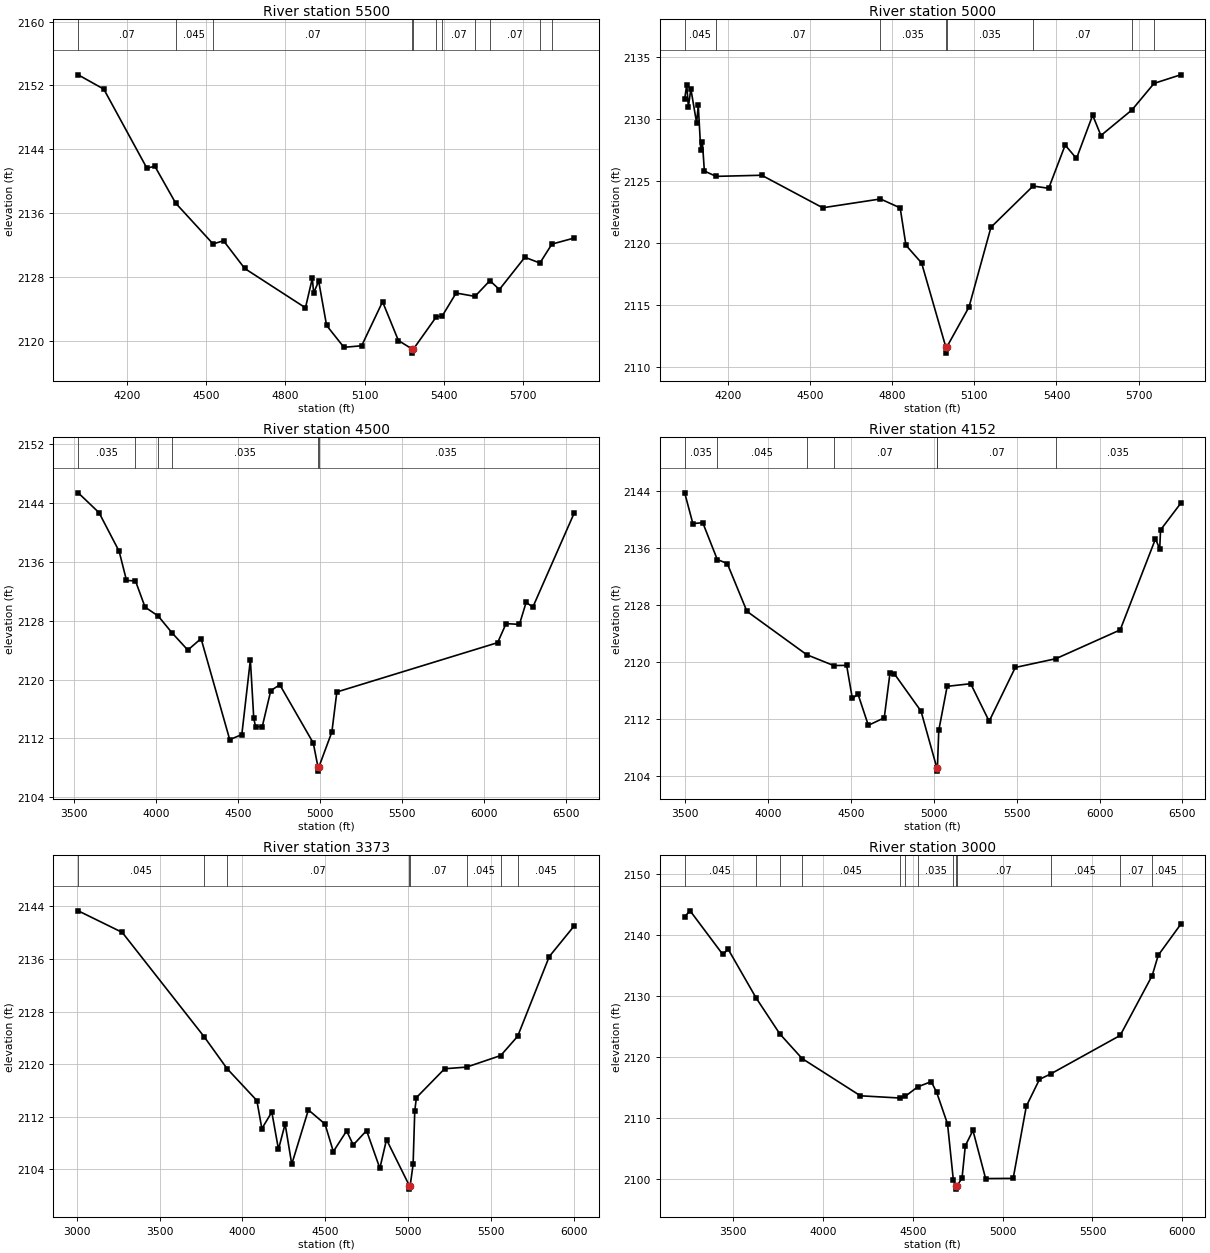
Type RM Length L Ch R = 1,5500,500,500,500
BEGIN DESCRIPTION:
East Cottonwood Creek Trib05 11.0
END DESCRIPTION:
XS GIS Cut Line= 3
      1355105.02      6906938.00      1356089.16      6906888.07
      1356409.70      6906053.62
#Sta/Elev= 30
  4014.6 2153.33  4111.5 2151.54  4274.9 2141.63  4304.9 2141.88  4384.0 2137.25
  4525.6 2132.14  4565.3 2132.54  4645.4 2129.07  4875.7 2124.14  4901.8 2127.84
  4906.8 2125.98  4925.7 2127.50  4955.8 2121.93  5021.5 2119.19  5088.6 2119.38
  5167.9 2124.90  5227.9 2120.04  5280.6 2118.96  5280.8 2118.46  5284.6 2118.96
  5372.2 2123.04  5393.2 2123.07  5446.6 2125.99  5518.0 2125.57  5574.6 2127.54
  5610.6 2126.43  5707.1 2130.47  5764.2 2129.75  5809.5 2132.12  5893.9 2132.88
#Mann=11,-1,0
  4014.6    0.07       0  4384.0   0.045       0  4525.6    0.07       0
  5280.6    0.07       0  5284.6    0.07       0  5372.2   0.035       0
  5393.2    0.07       0  5518.0   0.045       0  5574.6    0.07       0
  5764.2   0.045       0  5809.5    0.07       0
Bank Sta=5280.6,5284.6
Exp/Cntr=0.3,0.1

Type RM Length L Ch R = 1,5000,500,500,500
BEGIN DESCRIPTION:
East Cottonwood Creek Trib05 10.0
END DESCRIPTION:
XS GIS Cut Line= 3
      1356005.01      6907687.98      1356532.73      6906887.95
      1356455.00      6906038.00
#Sta/Elev= 30
  4041.6 2131.57  4049.1 2132.75  4055.1 2130.95  4064.2 2132.40  4085.2 2129.65
  4091.2 2131.07  4100.3 2127.50  4106.3 2128.13  4113.5 2125.78  4156.4 2125.35
  4323.1 2125.44  4545.9 2122.82  4756.9 2123.53  4828.9 2122.81  4850.0 2119.80
  4907.2 2118.37  4995.5 2111.61  4995.8 2111.11  4999.5 2111.61  5080.3 2114.82
  5160.6 2121.25  5314.4 2124.57  5371.5 2124.39  5431.7 2127.87  5473.1 2126.79
  5532.2 2130.28  5562.3 2128.64  5676.0 2130.71  5756.4 2132.84  5853.5 2133.53
#Mann=8,-1,0
  4041.6   0.045       0  4156.4    0.07       0  4756.9   0.035       0
  4995.5   0.035       0  4999.5   0.035       0  5314.4    0.07       0
  5676.0   0.045       0  5756.4    0.07       0
Bank Sta=4995.5,4999.5
Exp/Cntr=0.3,0.1

Type RM Length L Ch R = 1,4500,348,348,348
BEGIN DESCRIPTION:
East Cottonwood Creek Trib05 9.0
END DESCRIPTION:
XS GIS Cut Line= 3
      1356522.46      6908570.54      1356915.74      6907149.25
      1357238.30      6905631.44
#Sta/Elev= 30
  3525.3 2145.40  3652.4 2142.70  3775.2 2137.44  3819.9 2133.49  3874.8 2133.42
  3933.2 2129.86  4013.3 2128.65  4097.5 2126.37  4194.1 2124.02  4275.0 2125.58
  4449.9 2111.84  4523.7 2112.53  4575.9 2122.69  4596.6 2114.73  4607.9 2113.59
  4648.5 2113.62  4700.4 2118.51  4755.5 2119.30  4959.8 2111.38  4988.9 2108.06
  4989.2 2107.56  4992.9 2108.06  5073.3 2112.89  5103.5 2118.32  6084.9 2125.03
  6136.1 2127.62  6217.8 2127.51  6258.7 2130.51  6299.6 2129.86  6551.7 2142.64
#Mann=6,-1,0
  3525.3   0.035       0  3874.8   0.045       0  4013.3    0.07       0
  4097.5   0.035       0  4988.9   0.035       0  4992.9   0.035       0
Bank Sta=4988.9,4992.9
Exp/Cntr=0.3,0.1

Type RM Length L Ch R = 1,4152,779,779,779
BEGIN DESCRIPTION:
East Cottonwood Creek Trib05 8.0
END DESCRIPTION:
XS GIS Cut Line= 3
      1356750.32      6908635.64      1357151.81      6907181.61
      1357390.26      6905718.36
#Sta/Elev= 30
  3497.7 2143.76  3547.1 2139.44  3606.7 2139.57  3694.3 2134.40  3754.5 2133.84
  3873.1 2127.13  4233.8 2121.04  4396.2 2119.52  4474.5 2119.54  4508.8 2114.90
  4543.1 2115.50  4605.3 2111.13  4701.3 2112.18  4735.7 2118.44  4760.9 2118.40
  4923.0 2113.12  5017.9 2105.20  5018.1 2104.70  5022.0 2105.20  5030.1 2110.41
  5080.7 2116.60  5222.6 2116.97  5334.0 2111.70  5491.7 2119.25  5736.5 2120.48
  6124.3 2124.52  6337.1 2137.30  6362.6 2135.88  6367.6 2138.55  6488.7 2142.27
#Mann=7,-1,0
  3497.7   0.035       0  3694.3   0.045       0  4233.8   0.035       0
  4396.2    0.07       0  5017.9    0.07       0  5022.0    0.07       0
  5736.5   0.035       0
Bank Sta=5017.9,5022
Exp/Cntr=0.3,0.1

Type RM Length L Ch R = 1,3373,373,373,373
BEGIN DESCRIPTION:
East Cottonwood Creek Trib05 7.0
END DESCRIPTION:
XS GIS Cut Line= 3
      1357362.89      6908722.82      1357515.96      6906736.15
      1357455.00      6905737.97
#Sta/Elev= 30
  3009.2 2143.34  3274.8 2140.06  3769.4 2124.18  3908.0 2119.32  4087.2 2114.48
  4117.3 2110.21  4177.5 2112.73  4217.6 2107.06  4257.7 2110.92  4297.8 2104.80
  4398.1 2113.06  4498.4 2110.91  4548.6 2106.72  4628.8 2109.86  4668.9 2107.73
  4749.2 2109.91  4829.4 2104.18  4869.5 2108.55  5007.8 2101.51  5008.1 2101.01
  5012.1 2101.51  5030.0 2104.76  5040.0 2112.93  5050.0 2114.93  5220.3 2119.32
  5352.6 2119.57  5558.8 2121.33  5661.0 2124.26  5851.5 2136.38  6001.8 2141.04
#Mann=8,-1,0
  3009.2   0.045       0  3769.4   0.035       0  3908.0    0.07       0
  5007.8    0.07       0  5012.1    0.07       0  5352.6   0.045       0
  5558.8    0.07       0  5661.0   0.045       0
Bank Sta=5007.8,5012.1
Exp/Cntr=0.3,0.1

Type RM Length L Ch R = 1,3000,500,500,500
BEGIN DESCRIPTION:
East Cottonwood Creek Trib05 6.0
END DESCRIPTION:
XS GIS Cut Line= 3
      1358055.00      6908437.98      1357811.89      6906684.04
      1357522.89      6905736.12
#Sta/Elev= 30
  3229.3 2142.96  3259.6 2143.89  3441.3 2136.75  3471.6 2137.59  3627.3 2129.61
  3759.3 2123.72  3883.3 2119.69  4208.0 2113.59  4429.8 2113.22  4458.0 2113.51
  4526.6 2115.05  4602.3 2115.91  4632.6 2114.15  4693.1 2108.97  4725.1 2099.87
  4741.5 2098.80  4741.8 2098.30  4745.8 2098.80  4773.9 2100.15  4792.1 2105.41
  4834.5 2107.92  4905.1 2100.03  5058.6 2100.06  5131.8 2111.89  5205.0 2116.28
  5266.8 2117.16  5654.5 2123.48  5832.8 2133.29  5866.3 2136.61  5991.0 2141.66
#Mann=13,-1,0
  3229.3   0.045       0  3627.3   0.035       0  3759.3    0.07       0
  3883.3   0.045       0  4429.8   0.035       0  4458.0    0.07       0
  4526.6   0.035       0  4725.1    0.07       0  4741.5    0.07       0
  4745.8    0.07       0  5266.8   0.045       0  5654.5    0.07       0
  5832.8   0.045       0
Bank Sta=4741.5,4745.8
Exp/Cntr=0.3,0.1

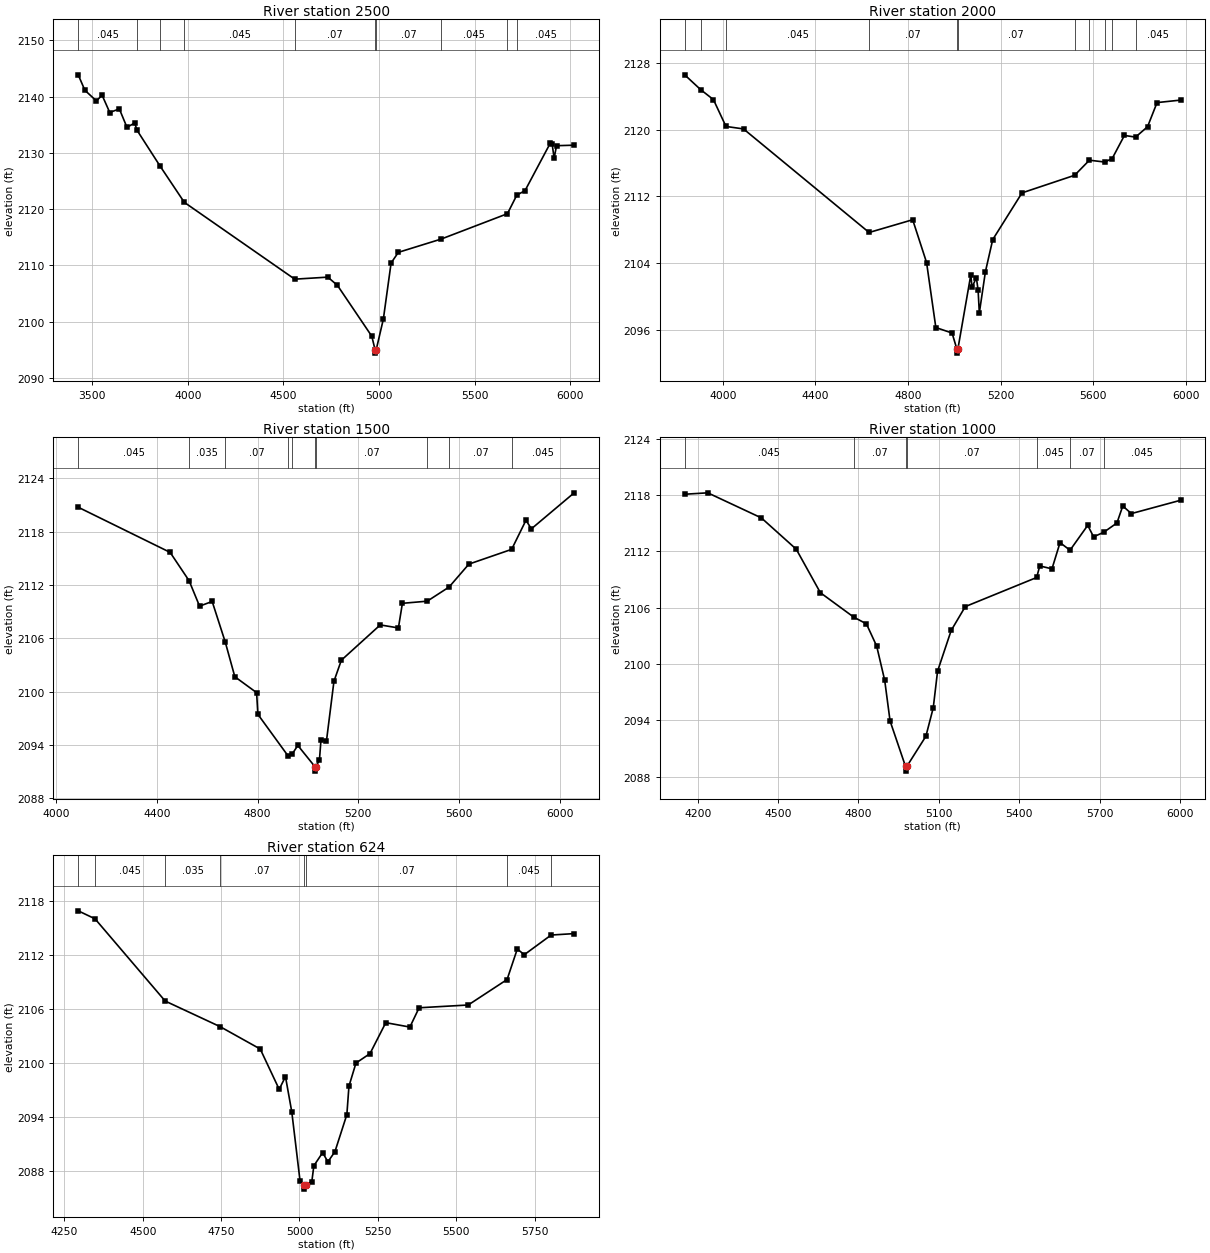
Type RM Length L Ch R = 1,2500,500,500,500
BEGIN DESCRIPTION:
East Cottonwood Creek Trib05 5.0
END DESCRIPTION:
XS GIS Cut Line= 3
      1358222.27      6908392.93      1358187.63      6906820.11
      1358013.93      6905814.81
#Sta/Elev= 30
  3426.8 2143.89  3461.7 2141.14  3521.8 2139.26  3551.8 2140.26  3591.8 2137.19
  3641.8 2137.84  3681.8 2134.55  3721.8 2135.33  3735.0 2134.00  3854.6 2127.68
  3981.6 2121.22  4559.1 2107.56  4732.0 2107.92  4782.1 2106.47  4962.1 2097.41
  4979.8 2094.91  4980.2 2094.41  4984.4 2094.91  5022.4 2100.45  5063.0 2110.44
  5101.0 2112.33  5324.8 2114.69  5671.3 2119.20  5720.3 2122.50  5763.3 2123.30
  5895.2 2131.73  5905.3 2131.54  5915.5 2129.08  5928.2 2131.29  6020.2 2131.38
#Mann=10,-1,0
  3426.8   0.045       0  3735.0   0.035       0  3854.6    0.07       0
  3981.6   0.045       0  4559.1    0.07       0  4979.8    0.07       0
  4984.4    0.07       0  5324.8   0.045       0  5671.3    0.07       0
  5720.3   0.045       0
Bank Sta=4979.8,4984.4
Exp/Cntr=0.3,0.1

Type RM Length L Ch R = 1,2000,500,500,500
BEGIN DESCRIPTION:
East Cottonwood Creek Trib05 4.0
END DESCRIPTION:
XS GIS Cut Line= 3
      1358650.22      6908101.99      1358613.20      6906937.98
      1358303.50      6906011.47
#Sta/Elev= 30
  3835.4 2126.58  3904.5 2124.80  3959.5 2123.61  4013.7 2120.39  4089.5 2120.09
  4631.8 2107.67  4819.9 2109.20  4879.9 2104.07  4919.9 2096.27  4990.0 2095.61
  5010.6 2093.70  5010.9 2093.20  5015.2 2093.70  5070.9 2102.59  5076.1 2101.09
  5094.9 2102.25  5102.4 2100.76  5107.7 2098.02  5134.0 2102.97  5165.6 2106.82
  5292.0 2112.42  5519.2 2114.53  5583.0 2116.34  5649.5 2116.12  5681.4 2116.54
  5734.2 2119.31  5782.4 2119.11  5834.2 2120.36  5875.1 2123.25  5976.9 2123.55
#Mann=11,-1,0
  3835.4   0.035       0  3904.5    0.07       0  4013.7   0.045       0
  4631.8    0.07       0  5010.6    0.07       0  5015.2    0.07       0
  5519.2   0.045       0  5583.0    0.07       0  5649.5   0.045       0
  5681.4    0.07       0  5782.4   0.045       0
Bank Sta=5010.6,5015.2
Exp/Cntr=0.3,0.1

Type RM Length L Ch R = 1,1500,500,500,500
BEGIN DESCRIPTION:
East Cottonwood Creek Trib05 3.0
END DESCRIPTION:
XS GIS Cut Line= 3
      1359049.52      6907919.65      1359075.83      6907008.03
      1358554.73      6906088.07
#Sta/Elev= 30
  4088.0 2120.74  4453.0 2115.66  4528.3 2112.47  4569.9 2109.61  4619.9 2110.14
  4672.1 2105.55  4709.9 2101.67  4796.4 2099.88  4801.4 2097.44  4921.1 2092.77
  4936.7 2092.93  4960.0 2093.94  5028.0 2091.55  5028.4 2091.05  5032.8 2091.55
  5046.0 2092.35  5052.1 2094.60  5073.7 2094.43  5103.5 2101.16  5132.9 2103.53
  5287.4 2107.50  5359.4 2107.16  5375.3 2109.93  5473.9 2110.17  5560.6 2111.76
  5639.3 2114.34  5809.1 2116.00  5865.9 2119.27  5887.5 2118.31  6057.3 2122.36
#Mann=10,-1,0
  4088.0   0.045       0  4528.3   0.035       0  4672.1    0.07       0
  4921.1   0.035       0  4936.7    0.07       0  5028.0    0.07       0
  5032.8    0.07       0  5473.9   0.045       0  5560.6    0.07       0
  5809.1   0.045       0
Bank Sta=5028,5032.8
Exp/Cntr=0.3,0.1

Type RM Length L Ch R = 1,1000,376,376,376
BEGIN DESCRIPTION:
East Cottonwood Creek Trib05 2.0
END DESCRIPTION:
XS GIS Cut Line= 3
      1359335.98      6907824.15      1359366.16      6906976.28
      1358884.61      6906096.79
#Sta/Elev= 30
  4151.6 2118.08  4237.8 2118.23  4437.9 2115.56  4568.0 2112.23  4658.1 2107.60
  4782.1 2105.01  4830.0 2104.28  4868.2 2101.92  4898.2 2098.27  4918.2 2093.95
  4975.9 2089.11  4976.2 2088.61  4980.7 2089.11  5051.9 2092.32  5079.4 2095.35
  5095.5 2099.25  5146.3 2103.58  5198.9 2106.12  5465.4 2109.22  5476.9 2110.45
  5522.5 2110.14  5552.6 2112.93  5589.9 2112.12  5656.0 2114.77  5677.8 2113.55
  5715.0 2114.02  5765.0 2115.02  5786.8 2116.83  5818.9 2116.02  6002.7 2117.44
#Mann=7,-1,0
  4151.6   0.045       0  4782.1    0.07       0  4975.9    0.07       0
  4980.7    0.07       0  5465.4   0.045       0  5589.9    0.07       0
  5715.0   0.045       0
Bank Sta=4975.9,4980.7
Exp/Cntr=0.3,0.1

Type RM Length L Ch R = 1,624,0,0,0
BEGIN DESCRIPTION:
East Cottonwood Creek Trib05 1.0
END DESCRIPTION:
XS GIS Cut Line= 3
      1359625.63      6907635.67      1359699.49      6906930.35
      1359309.98      6906148.92
#Sta/Elev= 30
  4294.0 2116.96  4347.6 2116.07  4571.5 2106.90  4746.5 2104.05  4874.8 2101.55
  4935.2 2097.06  4955.3 2098.47  4975.4 2094.54  5001.8 2086.83  5014.6 2086.43
  5014.9 2085.93  5019.4 2086.43  5039.3 2086.77  5045.9 2088.54  5073.8 2090.00
  5090.6 2088.98  5113.0 2090.10  5151.1 2094.24  5157.8 2097.41  5180.2 2099.99
  5224.9 2101.04  5275.3 2104.49  5352.2 2104.00  5381.6 2106.15  5538.3 2106.46
  5662.3 2109.30  5694.9 2112.70  5717.3 2112.07  5802.8 2114.26  5876.3 2114.42
#Mann=8,-1,0
  4294.0    0.07       0  4347.6   0.045       0  4571.5   0.035       0
  4746.5    0.07       0  5014.6    0.07       0  5019.4    0.07       0
  5662.3   0.045       0  5802.8    0.07       0
Bank Sta=5014.6,5019.4
Exp/Cntr=0.3,0.1

Chan Stop Cuts=-1