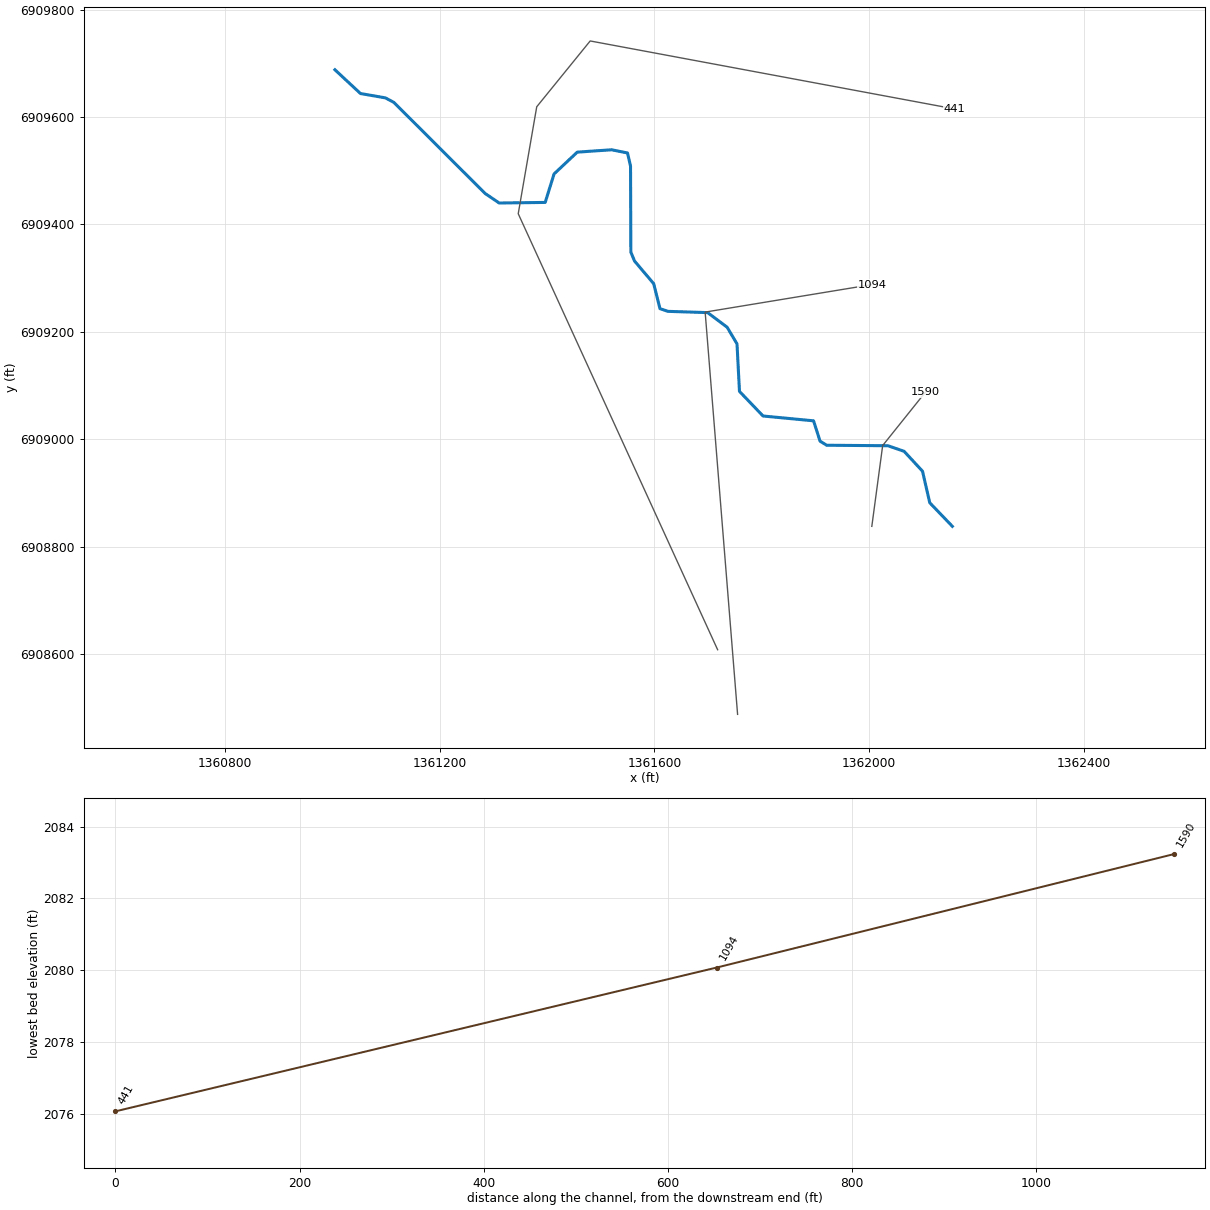
--- East Cottonwood Creek Trib06.prj (project) ---

Proj Title=East Cottonwood Creek Trib06 Base Level Engineering
Current Plan=p01
Default Exp/Contr=0.3,0.1
English Units
Geom File=g01
Flow File=f01
Plan File=p01
BEGIN DESCRIPTION:
East Cottonwood Creek Trib06
END DESCRIPTION:

--- East Cottonwood Creek Trib06.p01 (plan) ---

Plan Title=Multiple Run
Short Identifier=Multiple
Geom File=g01
Flow File=f01
Subcritical Flow
K Sum by GR= 0
Std Step Tol= 0.01
Critical Tol= 0.01
Num of Std Step Trials= 20
Max Error Tol= 0.3
Flow Tol Ratio= 0.001
Split Flow NTrial= 30
Split Flow Tol= 0.02
Split Flow Ratio= 0.02
Log Output Level= 0
Friction Slope Method= 1
Unsteady Friction Slope Method= 2
Unsteady Bridges Friction Slope Method= 1
Parabolic Critical Depth
Global Vel Dist=  1 , 1 , 1
Global Log Level= 0
CheckData=True
Encroach Param= -1, 0, 0, 0
BEGIN DESCRIPTION:
Multiple Run
END DESCRIPTION:

--- East Cottonwood Creek Trib06.f01 (steady flow) ---

Flow Title=Multiple
Number of Profiles=7
Profile Names=10-year,25-year,50-year,1pct_min,100-year,1pct_plu,500-year
River Rch & RM= East Cottonwood ,Reach-1,1590
     273     388     486     302     603    1203     942
Boundary for River Rch & Prof#=East Cottonwood ,Reach-1,1
Up Type=0
Dn Type=3
Dn Slope=0.005
Boundary for River Rch & Prof#=East Cottonwood ,Reach-1,2
Up Type=0
Dn Type=3
Dn Slope=0.005
Boundary for River Rch & Prof#=East Cottonwood ,Reach-1,3
Up Type=0
Dn Type=3
Dn Slope=0.005
Boundary for River Rch & Prof#=East Cottonwood ,Reach-1,4
Up Type=0
Dn Type=3
Dn Slope=0.005
Boundary for River Rch & Prof#=East Cottonwood ,Reach-1,5
Up Type=0
Dn Type=3
Dn Slope=0.005
Boundary for River Rch & Prof#=East Cottonwood ,Reach-1,6
Up Type=0
Dn Type=3
Dn Slope=0.005
Boundary for River Rch & Prof#=East Cottonwood ,Reach-1,7
Up Type=0
Dn Type=3
Dn Slope=0.005

--- East Cottonwood Creek Trib06.g01 (geometry) ---

Geom Title=Existing Conditions

River Reach=East Cottonwood ,Reach-1
Reach XY= 30
      1362155.00      6908838.00      1362112.95      6908881.89
      1362099.41      6908940.65      1362065.12      6908977.67
      1362035.09      6908988.06      1361920.96      6908988.97
      1361908.58      6908996.58      1361896.49      6909034.44
      1361802.35      6909043.42      1361758.52      6909089.26
      1361753.90      6909177.68      1361735.56      6909208.63
      1361699.22      6909235.89      1361625.26      6909238.22
      1361610.44      6909243.25      1361598.70      6909289.78
      1361563.07      6909331.88      1361556.19      6909348.48
      1361555.60      6909508.63      1361549.96      6909533.08
      1361520.56      6909539.00      1361456.38      6909534.63
      1361413.17      6909494.03      1361396.65      6909441.00
      1361310.98      6909439.92      1361284.87      6909457.57
      1361114.71      6909627.30      1361099.03      6909635.66
      1361052.65      6909643.71      1361005.00      6909688.00

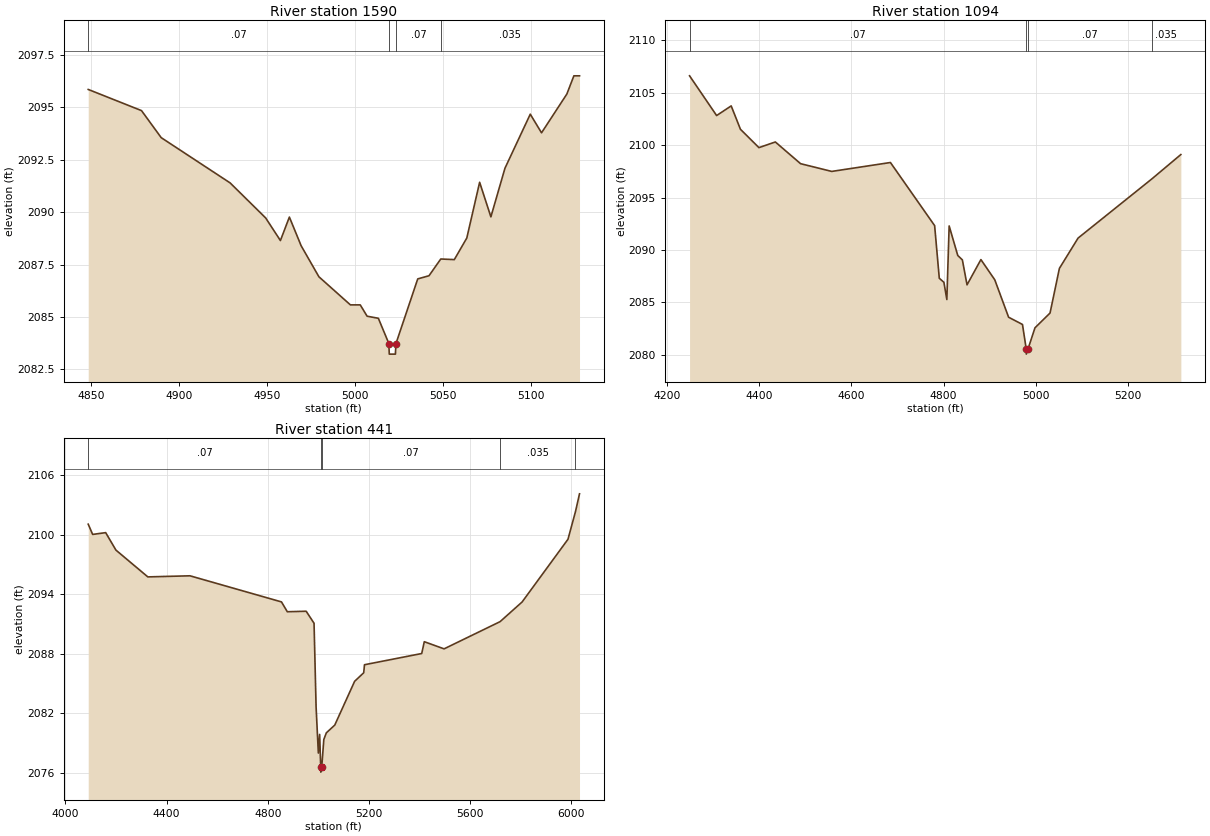
Type RM Length L Ch R = 1,1590,496,496,496
BEGIN DESCRIPTION:
East Cottonwood Creek Trib06 2.0
END DESCRIPTION:
XS GIS Cut Line= 3
      1362005.00      6908837.97      1362025.21      6908988.42
      1362105.00      6909087.99
#Sta/Elev= 30
  4848.2 2095.86  4878.5 2094.85  4889.7 2093.56  4928.9 2091.40  4949.1 2089.73
  4957.5 2088.65  4962.6 2089.77  4969.3 2088.40  4979.4 2086.92  4997.3 2085.58
  5002.9 2085.58  5006.8 2085.04  5013.2 2084.94  5019.2 2083.73  5019.4 2083.23
  5022.9 2083.23  5023.2 2083.73  5035.6 2086.82  5042.0 2086.97  5048.7 2087.77
  5056.4 2087.74  5063.5 2088.77  5070.8 2091.43  5077.2 2089.78  5085.2 2092.10
  5099.6 2094.68  5106.0 2093.79  5120.4 2095.64  5124.4 2096.51  5127.6 2096.51
#Mann=4,-1,0
  4848.2    0.07       0  5019.2    0.07       0  5023.2    0.07       0
  5048.7   0.035       0
Bank Sta=5019.2,5023.2
Exp/Cntr=0.3,0.1

Type RM Length L Ch R = 1,1094,653,653,653
BEGIN DESCRIPTION:
East Cottonwood Creek Trib06 1.0
END DESCRIPTION:
XS GIS Cut Line= 3
      1361755.00      6908487.99      1361694.58      6909236.86
      1362005.00      6909288.00
#Sta/Elev= 30
  4248.7 2106.62  4307.4 2102.83  4339.0 2103.75  4359.1 2101.52  4399.2 2099.77
  4434.8 2100.31  4489.5 2098.24  4557.1 2097.50  4684.5 2098.35  4780.4 2092.33
  4790.5 2087.31  4800.5 2086.92  4806.9 2085.28  4811.9 2092.30  4830.6 2089.48
  4840.6 2089.06  4850.7 2086.68  4880.8 2089.09  4910.9 2087.16  4940.9 2083.59
  4971.0 2082.90  4979.1 2080.57  4979.3 2080.07  4983.1 2080.57  4998.1 2082.58
  5030.8 2083.99  5051.1 2088.25  5091.6 2091.14  5251.8 2096.79  5314.6 2099.11
#Mann=4,-1,0
  4248.7    0.07       0  4979.1    0.07       0  4983.1    0.07       0
  5251.8   0.035       0
Bank Sta=4979.1,4983.1
Exp/Cntr=0.3,0.1

Type RM Length L Ch R = 1,441,0,0,0
BEGIN DESCRIPTION:
East Cottonwood Creek Trib06 0.5
END DESCRIPTION:
XS GIS Cut Line= 5
      1361717.82      6908608.31      1361346.44      6909419.98
      1361380.90      6909619.08      1361480.45      6909741.60
      1362158.15      6909615.25
#Sta/Elev= 30
  4090.1 2101.04  4107.6 2100.01  4159.1 2100.19  4199.6 2098.43  4325.7 2095.73
  4492.3 2095.84  4854.0 2093.21  4877.0 2092.22  4951.6 2092.27  4982.7 2091.06
  4990.8 2082.62  4999.7 2077.98  5004.8 2079.86  5009.1 2076.56  5009.4 2076.06
  5013.1 2076.56  5021.3 2079.35  5031.4 2080.02  5064.6 2080.80  5143.1 2085.21
  5179.0 2086.07  5182.1 2086.88  5408.3 2088.01  5418.5 2089.20  5496.7 2088.48
  5718.0 2091.22  5805.0 2093.20  5986.4 2099.52  6016.0 2102.30  6032.0 2104.10
#Mann=5,-1,0
  4090.1    0.07       0  5009.1    0.07       0  5013.1    0.07       0
  5718.0   0.035       0  6016.0    0.07       0
Bank Sta=5009.1,5013.1
Exp/Cntr=0.3,0.1

Chan Stop Cuts=-1