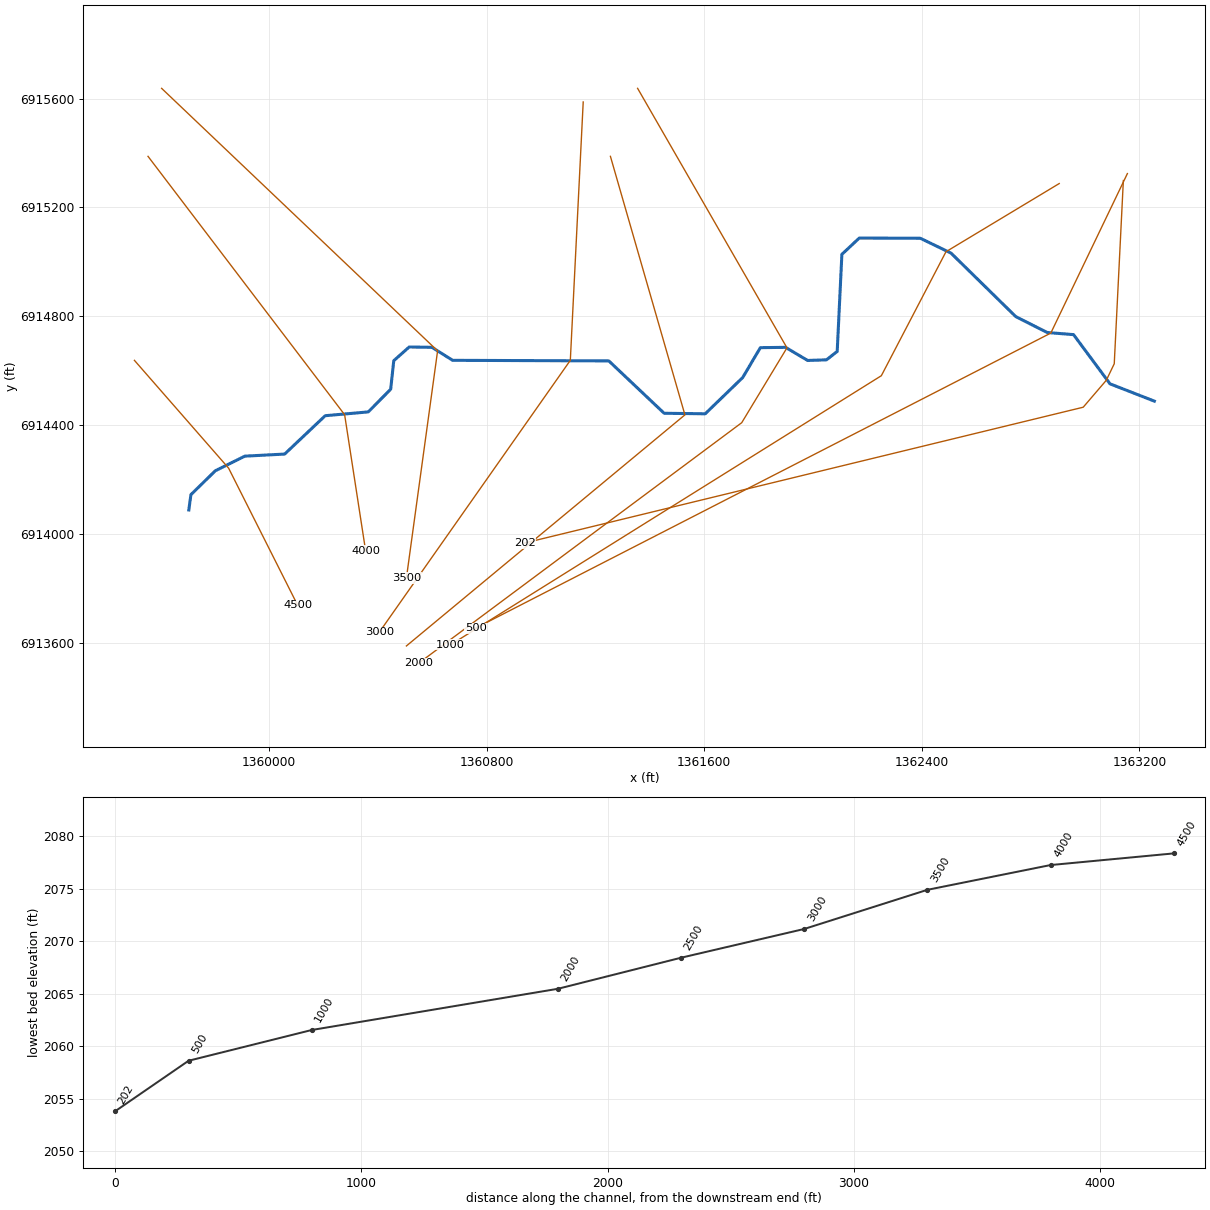
--- East Cottonwood Creek Trib07.prj (project) ---

Proj Title=East Cottonwood Creek Trib07 Base Level Engineering
Current Plan=p01
Default Exp/Contr=0.3,0.1
English Units
Geom File=g01
Flow File=f01
Plan File=p01
BEGIN DESCRIPTION:
East Cottonwood Creek Trib07
END DESCRIPTION:

--- East Cottonwood Creek Trib07.p01 (plan) ---

Plan Title=Multiple Run
Short Identifier=Multiple
Geom File=g01
Flow File=f01
Subcritical Flow
K Sum by GR= 0
Std Step Tol= 0.01
Critical Tol= 0.01
Num of Std Step Trials= 20
Max Error Tol= 0.3
Flow Tol Ratio= 0.001
Split Flow NTrial= 30
Split Flow Tol= 0.02
Split Flow Ratio= 0.02
Log Output Level= 0
Friction Slope Method= 1
Unsteady Friction Slope Method= 2
Unsteady Bridges Friction Slope Method= 1
Parabolic Critical Depth
Global Vel Dist=  1 , 1 , 1
Global Log Level= 0
CheckData=True
Encroach Param= -1, 0, 0, 0
BEGIN DESCRIPTION:
Multiple Run
END DESCRIPTION:

--- East Cottonwood Creek Trib07.f01 (steady flow) ---

Flow Title=Multiple
Number of Profiles=7
Profile Names=10-year,25-year,50-year,1pct_min,100-year,1pct_plu,500-year
River Rch & RM= East Cottonwood ,Reach-1,4500
     268     380     474     294     587    1171     913
River Rch & RM= East Cottonwood ,Reach-1,3500
     282     400     500     310     619    1236     964
Boundary for River Rch & Prof#=East Cottonwood ,Reach-1,1
Up Type=0
Dn Type=3
Dn Slope=0.005
Boundary for River Rch & Prof#=East Cottonwood ,Reach-1,2
Up Type=0
Dn Type=3
Dn Slope=0.005
Boundary for River Rch & Prof#=East Cottonwood ,Reach-1,3
Up Type=0
Dn Type=3
Dn Slope=0.005
Boundary for River Rch & Prof#=East Cottonwood ,Reach-1,4
Up Type=0
Dn Type=3
Dn Slope=0.005
Boundary for River Rch & Prof#=East Cottonwood ,Reach-1,5
Up Type=0
Dn Type=3
Dn Slope=0.005
Boundary for River Rch & Prof#=East Cottonwood ,Reach-1,6
Up Type=0
Dn Type=3
Dn Slope=0.005
Boundary for River Rch & Prof#=East Cottonwood ,Reach-1,7
Up Type=0
Dn Type=3
Dn Slope=0.005

--- East Cottonwood Creek Trib07.g01 (geometry) ---

Geom Title=Existing Conditions

River Reach=East Cottonwood ,Reach-1
Reach XY= 30
      1359705.00      6914088.00      1359712.75      6914144.24
      1359802.69      6914232.18      1359910.93      6914285.75
      1360057.45      6914293.47      1360206.47      6914434.46
      1360364.82      6914448.47      1360447.14      6914531.81
      1360458.51      6914636.75      1360515.31      6914687.14
      1360599.02      6914685.84      1360675.03      6914638.07
      1361249.15      6914635.94      1361452.55      6914443.45
      1361603.53      6914441.53      1361741.36      6914574.80
      1361806.28      6914684.63      1361899.02      6914685.83
      1361980.01      6914637.58      1362049.32      6914639.88
      1362088.76      6914670.76      1362105.98      6915027.74
      1362170.02      6915087.68      1362394.50      6915086.80
      1362507.30      6915032.17      1362745.32      6914798.76
      1362860.97      6914740.34      1362957.67      6914732.58
      1363091.76      6914551.60      1363255.00      6914488.00

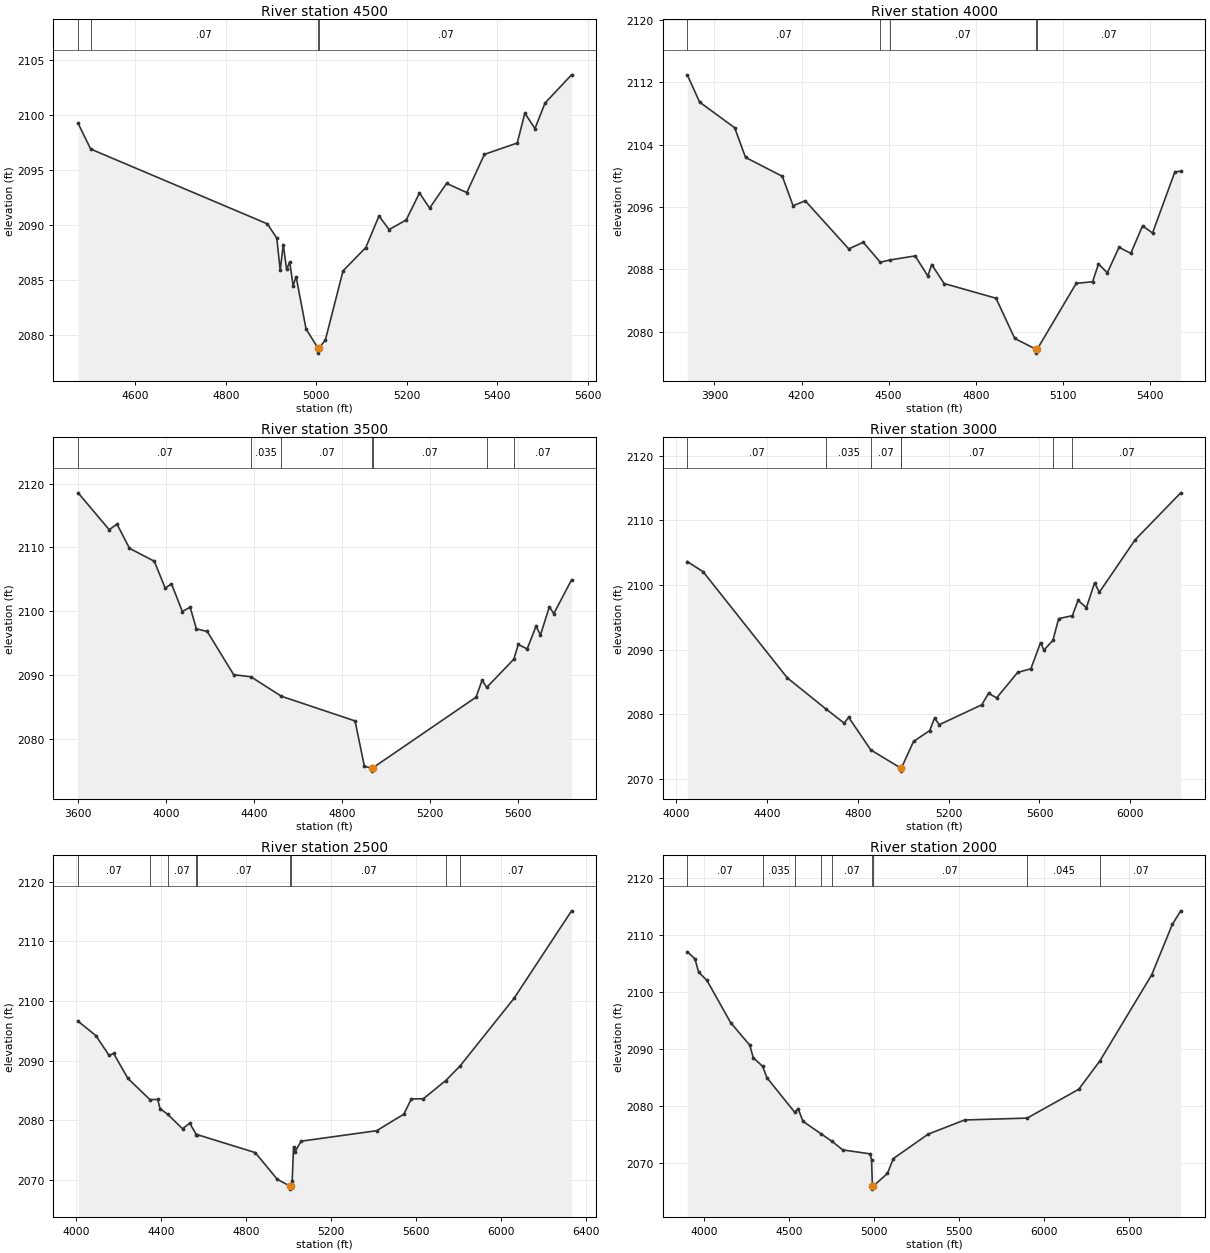
Type RM Length L Ch R = 1,4500,500,500,500
BEGIN DESCRIPTION:
East Cottonwood Creek Trib07 9.0
END DESCRIPTION:
XS GIS Cut Line= 3
      1359505.01      6914637.99      1359851.34      6914241.58
      1360105.02      6913737.96
#Sta/Elev= 30
  4473.6 2099.24  4501.4 2096.90  4891.7 2090.11  4912.6 2088.82  4920.2 2085.88
  4926.8 2088.23  4934.4 2085.97  4941.1 2086.66  4948.7 2084.49  4955.3 2085.32
  4977.2 2080.58  5002.8 2078.87  5003.1 2078.37  5006.8 2078.87  5020.0 2079.57
  5059.0 2085.84  5109.3 2087.96  5138.4 2090.82  5160.8 2089.59  5198.5 2090.46
  5227.9 2092.91  5250.3 2091.54  5287.8 2093.78  5332.4 2092.95  5371.4 2096.42
  5443.9 2097.45  5460.7 2100.16  5483.0 2098.76  5505.3 2101.08  5563.9 2103.64
#Mann=4,-1,0
  4473.6   0.035       0  4501.4    0.07       0  5002.8    0.07       0
  5006.8    0.07       0
Bank Sta=5002.8,5006.8
Exp/Cntr=0.3,0.1

Type RM Length L Ch R = 1,4000,500,500,500
BEGIN DESCRIPTION:
East Cottonwood Creek Trib07 8.0
END DESCRIPTION:
XS GIS Cut Line= 3
      1359555.03      6915387.97      1360277.88      6914438.02
      1360355.00      6913938.03
#Sta/Elev= 30
  3806.3 2112.96  3848.9 2109.46  3969.6 2106.17  4006.9 2102.37  4133.8 2099.94
  4170.7 2096.17  4212.7 2096.80  4362.5 2090.63  4412.4 2091.48  4471.1 2088.92
  4504.2 2089.21  4591.1 2089.73  4634.8 2087.16  4648.2 2088.62  4690.9 2086.19
  4869.7 2084.30  4934.2 2079.14  5007.5 2077.76  5007.7 2077.26  5011.5 2077.76
  5145.9 2086.21  5202.4 2086.42  5222.6 2088.70  5253.0 2087.56  5293.4 2090.84
  5333.9 2090.06  5374.4 2093.60  5408.7 2092.67  5485.7 2100.51  5505.9 2100.60
#Mann=5,-1,0
  3806.3    0.07       0  4471.1   0.035       0  4504.2    0.07       0
  5007.5    0.07       0  5011.5    0.07       0
Bank Sta=5007.5,5011.5
Exp/Cntr=0.3,0.1

Type RM Length L Ch R = 1,3500,500,500,500
BEGIN DESCRIPTION:
East Cottonwood Creek Trib07 7.0
END DESCRIPTION:
XS GIS Cut Line= 3
      1359605.02      6915637.98      1360619.63      6914672.89
      1360505.00      6913838.02
#Sta/Elev= 30
  3599.7 2118.54  3741.1 2112.76  3776.6 2113.63  3833.2 2109.84  3946.1 2107.81
  3995.8 2103.59  4024.2 2104.28  4073.5 2099.93  4109.1 2100.60  4137.4 2097.21
  4186.8 2096.80  4306.9 2090.02  4385.5 2089.69  4523.8 2086.64  4858.6 2082.77
  4901.1 2075.64  4934.6 2075.40  4934.9 2074.90  4938.7 2075.40  5408.7 2086.50
  5436.1 2089.16  5457.1 2088.03  5580.2 2092.45  5600.5 2094.76  5640.8 2094.06
  5681.2 2097.63  5701.4 2096.26  5741.8 2100.67  5762.0 2099.60  5842.7 2104.90
#Mann=7,-1,0
  3599.7    0.07       0  4385.5   0.035       0  4523.8    0.07       0
  4934.6    0.07       0  4938.7    0.07       0  5457.1   0.035       0
  5580.2    0.07       0
Bank Sta=4934.6,4938.7
Exp/Cntr=0.3,0.1

Type RM Length L Ch R = 1,3000,500,500,500
BEGIN DESCRIPTION:
East Cottonwood Creek Trib07 6.0
END DESCRIPTION:
XS GIS Cut Line= 3
      1361155.00      6915587.95      1361107.60      6914638.04
      1360404.99      6913637.98
#Sta/Elev= 30
  4048.9 2103.62  4118.9 2102.04  4489.4 2085.61  4660.9 2080.76  4739.7 2078.61
  4759.7 2079.50  4857.2 2074.45  4988.0 2071.67  4988.2 2071.17  4992.1 2071.67
  5045.4 2075.76  5116.9 2077.46  5137.8 2079.39  5158.9 2078.36  5346.0 2081.44
  5375.7 2083.22  5411.4 2082.51  5503.8 2086.45  5562.2 2087.02  5604.8 2091.07
  5619.6 2089.91  5659.4 2091.43  5684.4 2094.78  5744.9 2095.24  5770.0 2097.61
  5806.7 2096.48  5842.7 2100.32  5863.6 2098.86  6021.3 2106.99  6222.2 2114.26
#Mann=7,-1,0
  4048.9    0.07       0  4660.9   0.035       0  4857.2    0.07       0
  4988.0    0.07       0  4992.1    0.07       0  5659.4   0.035       0
  5744.9    0.07       0
Bank Sta=4988,4992.1
Exp/Cntr=0.3,0.1

Type RM Length L Ch R = 1,2500,500,500,500
BEGIN DESCRIPTION:
East Cottonwood Creek Trib07 5.0
END DESCRIPTION:
XS GIS Cut Line= 3
      1361255.00      6915388.00      1361528.90      6914437.57
      1360504.97      6913587.98
#Sta/Elev= 30
  4010.9 2096.59  4094.2 2094.19  4156.6 2090.86  4178.0 2091.18  4245.3 2086.99
  4348.3 2083.45  4385.2 2083.47  4396.0 2081.93  4431.8 2080.99  4501.8 2078.56
  4535.5 2079.49  4566.9 2077.57  4570.1 2077.58  4843.5 2074.56  4947.5 2070.07
  5007.3 2068.93  5007.6 2068.43  5011.5 2068.93  5017.2 2069.75  5023.7 2075.53
  5031.1 2074.72  5058.8 2076.47  5414.4 2078.23  5542.0 2081.00  5577.1 2083.55
  5634.4 2083.60  5739.3 2086.65  5806.7 2089.10  6060.2 2100.44  6330.5 2115.11
#Mann=9,-1,0
  4010.9    0.07       0  4348.3   0.035       0  4431.8    0.07       0
  4566.9   0.035       0  4570.1    0.07       0  5007.3    0.07       0
  5011.5    0.07       0  5739.3   0.045       0  5806.7    0.07       0
Bank Sta=5007.3,5011.5
Exp/Cntr=0.3,0.1

Type RM Length L Ch R = 1,2000,1000,1000,1000
BEGIN DESCRIPTION:
East Cottonwood Creek Trib07 4.0
END DESCRIPTION:
XS GIS Cut Line= 4
      1361354.99      6915638.02      1361904.09      6914683.95
      1361737.80      6914408.82      1360549.31      6913523.95
#Sta/Elev= 30
  3899.2 2107.09  3944.5 2105.84  3966.0 2103.50  4014.9 2102.06  4154.3 2094.66
  4266.4 2090.72  4287.9 2088.50  4342.6 2086.99  4368.4 2084.98  4531.8 2078.94
  4550.9 2079.60  4580.0 2077.36  4685.1 2075.19  4751.0 2073.85  4813.9 2072.35
  4974.9 2071.65  4983.8 2070.61  4988.6 2065.97  4988.9 2065.47  4992.8 2065.97
  5077.1 2068.22  5112.1 2070.83  5316.9 2075.11  5531.4 2077.59  5899.3 2077.92
  6202.9 2082.97  6328.3 2087.99  6632.6 2103.05  6753.5 2111.87  6803.2 2114.25
#Mann=9,-1,0
  3899.2    0.07       0  4342.6   0.035       0  4531.8    0.07       0
  4685.1   0.035       0  4751.0    0.07       0  4988.6    0.07       0
  4992.8    0.07       0  5899.3   0.045       0  6328.3    0.07       0
Bank Sta=4988.6,4992.8
Exp/Cntr=0.3,0.1

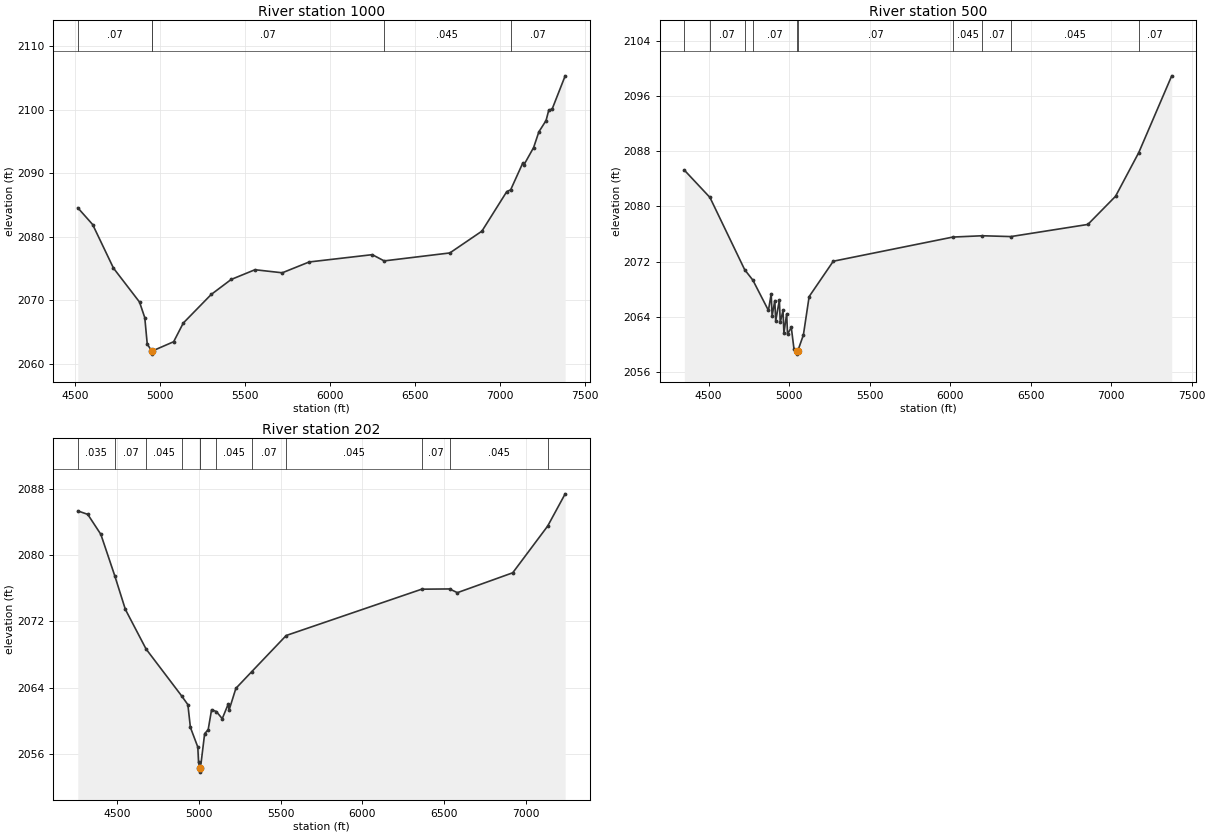
Type RM Length L Ch R = 1,1000,500,500,500
BEGIN DESCRIPTION:
East Cottonwood Creek Trib07 2.0
END DESCRIPTION:
XS GIS Cut Line= 4
      1362905.01      6915288.00      1362488.67      6915037.29
      1362251.11      6914581.56      1360666.92      6913591.98
#Sta/Elev= 30
  4514.0 2084.55  4601.4 2081.92  4724.1 2075.06  4877.2 2069.73  4908.2 2067.27
  4922.6 2063.13  4948.8 2062.04  4949.1 2061.54  4953.1 2062.04  5078.1 2063.49
  5134.5 2066.42  5299.0 2070.92  5416.5 2073.28  5556.5 2074.81  5717.3 2074.33
  5875.3 2076.03  6246.8 2077.18  6316.7 2076.20  6703.2 2077.45  6891.9 2080.88
  7038.2 2087.10  7061.0 2087.38  7132.5 2091.60  7138.4 2091.27  7196.2 2094.03
  7226.9 2096.49  7269.3 2098.27  7284.7 2099.85  7305.9 2100.13  7381.8 2105.30
#Mann=5,-1,0
  4514.0    0.07       0  4948.8    0.07       0  4953.1    0.07       0
  6316.7   0.045       0  7061.0    0.07       0
Bank Sta=4948.8,4953.1
Exp/Cntr=0.3,0.1

Type RM Length L Ch R = 1,500,298,298,298
BEGIN DESCRIPTION:
East Cottonwood Creek Trib07 1.0
END DESCRIPTION:
XS GIS Cut Line= 3
      1363155.64      6915324.64      1362874.13      6914738.32
      1360759.93      6913653.68
#Sta/Elev= 30
  4349.6 2085.27  4508.6 2081.31  4724.4 2070.84  4775.2 2069.33  4871.9 2064.94
  4889.0 2067.35  4894.5 2064.12  4911.6 2066.37  4917.1 2063.43  4939.8 2066.46
  4945.3 2063.21  4962.4 2064.94  4968.0 2061.68  4985.1 2064.44  4990.6 2061.51
  5013.8 2062.48  5030.3 2059.41  5050.3 2059.11  5050.6 2058.61  5054.7 2059.11
  5088.9 2061.38  5124.7 2066.95  5274.5 2072.07  6017.0 2075.57  6199.8 2075.76
  6377.2 2075.64  6855.5 2077.40  7027.4 2081.48  7171.7 2087.82  7376.2 2098.93
#Mann=10,-1,0
  4349.6   0.035       0  4508.6    0.07       0  4724.4   0.045       0
  4775.2    0.07       0  5050.3    0.07       0  5054.7    0.07       0
  6017.0   0.045       0  6199.8    0.07       0  6377.2   0.045       0
  7171.7    0.07       0
Bank Sta=5050.3,5054.7
Exp/Cntr=0.3,0.1

Type RM Length L Ch R = 1,202,0,0,0
BEGIN DESCRIPTION:
East Cottonwood Creek Trib07 0.5
END DESCRIPTION:
XS GIS Cut Line= 5
      1363140.80      6915299.01      1363107.33      6914625.53
      1363078.13      6914564.71      1362993.24      6914465.70
      1360940.24      6913966.56
#Sta/Elev= 30
  4257.9 2085.33  4319.0 2084.91  4399.1 2082.50  4484.0 2077.52  4549.3 2073.44
  4676.1 2068.66  4893.9 2063.00  4932.2 2061.94  4947.6 2059.20  4992.9 2056.83
  4997.5 2055.00  5004.8 2054.30  5005.1 2053.80  5009.2 2054.30  5034.9 2058.45
  5056.4 2058.91  5077.3 2061.34  5106.7 2061.11  5142.6 2060.25  5179.2 2062.01
  5184.4 2061.28  5226.1 2063.91  5322.9 2065.92  5534.3 2070.29  6364.2 2075.88
  6535.0 2075.91  6582.6 2075.46  6921.7 2077.86  7135.7 2083.50  7242.9 2087.39
#Mann=12,-1,0
  4257.9   0.035       0  4484.0    0.07       0  4676.1   0.045       0
  4893.9    0.07       0  5004.8    0.07       0  5009.2    0.07       0
  5106.7   0.045       0  5322.9    0.07       0  5534.3   0.045       0
  6364.2    0.07       0  6535.0   0.045       0  7135.7    0.07       0
Bank Sta=5004.8,5009.2
Exp/Cntr=0.3,0.1

Chan Stop Cuts=-1