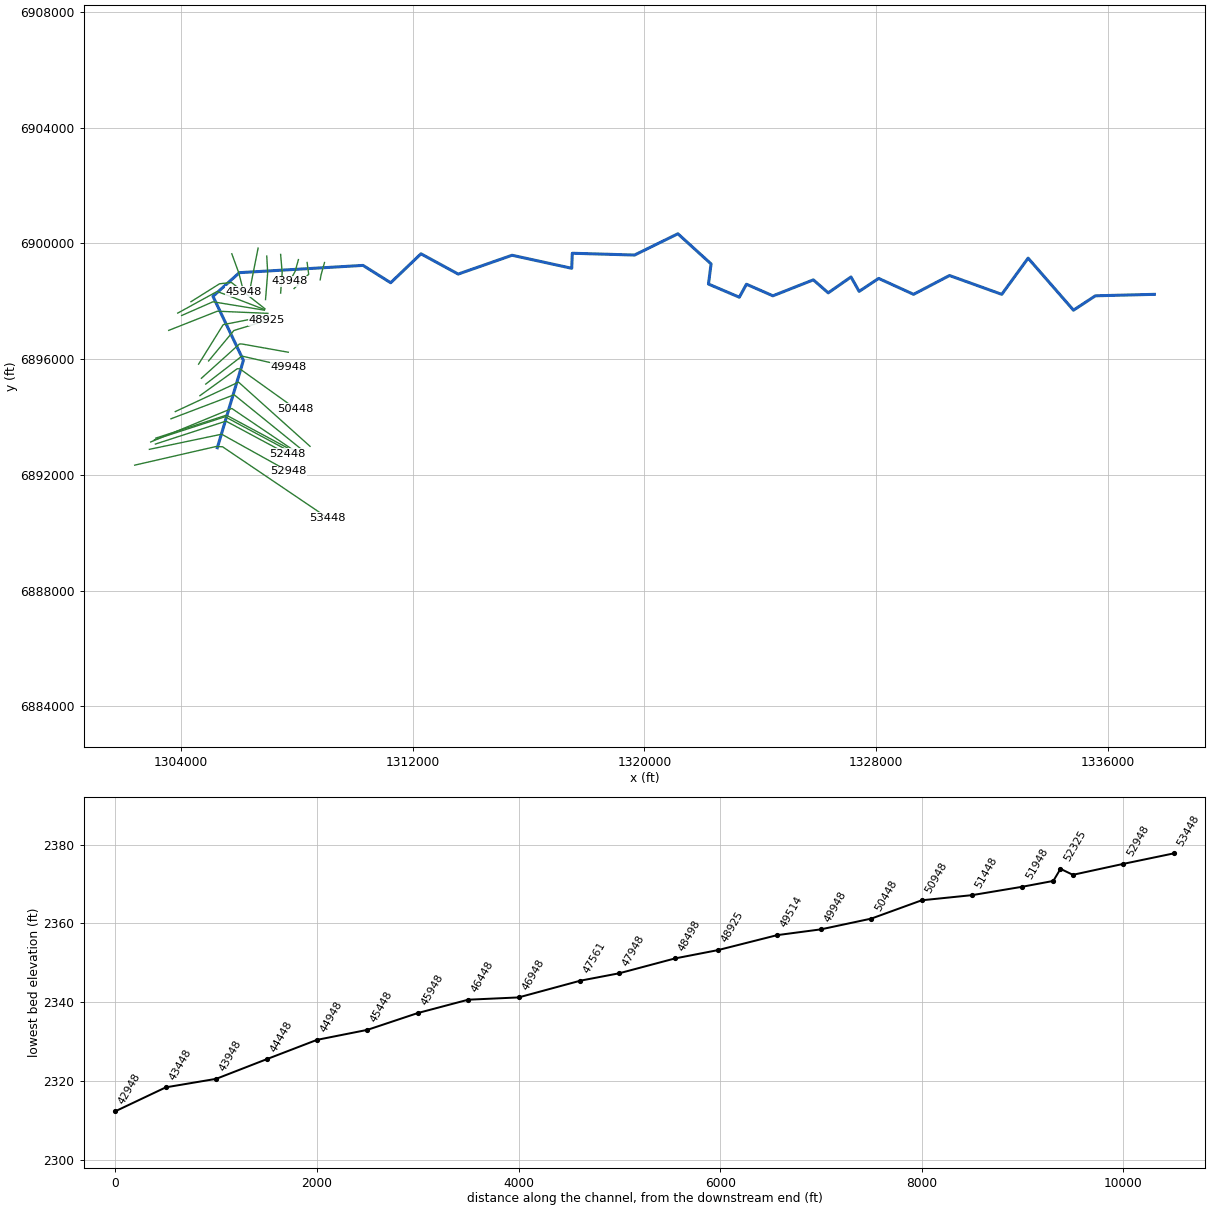
--- Linn Creek.prj (project) ---

Proj Title=Linn Creek Base Level Engineering
Current Plan=p01
Default Exp/Contr=0.3,0.1
English Units
Geom File=g01
Flow File=f01
Plan File=p01
BEGIN DESCRIPTION:
Linn Creek
END DESCRIPTION:

--- Linn Creek.p01 (plan) ---

Plan Title=Multiple Run
Short Identifier=Multiple
Geom File=g01
Flow File=f01
Subcritical Flow
K Sum by GR= 0
Std Step Tol= 0.01
Critical Tol= 0.01
Num of Std Step Trials= 20
Max Error Tol= 0.3
Flow Tol Ratio= 0.001
Split Flow NTrial= 30
Split Flow Tol= 0.02
Split Flow Ratio= 0.02
Log Output Level= 0
Friction Slope Method= 1
Unsteady Friction Slope Method= 2
Unsteady Bridges Friction Slope Method= 1
Parabolic Critical Depth
Global Vel Dist=  1 , 1 , 1
Global Log Level= 0
CheckData=True
Encroach Param= -1, 0, 0, 0
BEGIN DESCRIPTION:
Multiple Run
END DESCRIPTION:

--- Linn Creek.f01 (steady flow) ---

Flow Title=Multiple
Number of Profiles=7
Profile Names=10-year,25-year,50-year,1pct_min,100-year,1pct_plu,500-year
River Rch & RM= Linn Creek,Reach-1,53448
     145     192     229     136     271     541     384
River Rch & RM= Linn Creek,Reach-1,52448
     253     349     426     259     516    1029     766
River Rch & RM= Linn Creek,Reach-1,49948
     371     524     650     400     799    1593    1222
River Rch & RM= Linn Creek,Reach-1,47561
     412     586     732     453     904    1803    1397
River Rch & RM= Linn Creek,Reach-1,43948
    1019    1513    1944    1236    2466    4920    4024
River Rch & RM= Linn Creek,Reach-1,39948
    1132    1694    2190    1400    2794    5575    4614
River Rch & RM= Linn Creek,Reach-1,37948
    1233    1854    2404    1542    3077    6140    5113
River Rch & RM= Linn Creek,Reach-1,35448
    1359    2051    2667    1715    3421    6827    5714
River Rch & RM= Linn Creek,Reach-1,29810
    1468    2219    2889    1859    3710    7402    6205
River Rch & RM= Linn Creek,Reach-1,25000
    1566    2370    3088    1989    3969    7919    6648
River Rch & RM= Linn Creek,Reach-1,21360
    1612    2442    3183    2051    4092    8165    6858
River Rch & RM= Linn Creek,Reach-1,19000
    1635    2474    3223    2075    4140    8261    6928
River Rch & RM= Linn Creek,Reach-1,9500
    1831    2780    3629    2340    4670    9317    7842
River Rch & RM= Linn Creek,Reach-1,4500
    1899    2886    3770    2433    4855    9688    8165
River Rch & RM= Linn Creek,Reach-1,3629
    2553    3915    5147    3341    6667   13302   11340
Boundary for River Rch & Prof#=Linn Creek,Reach-1,1
Up Type=0
Dn Type=3
Dn Slope=0.005
Boundary for River Rch & Prof#=Linn Creek,Reach-1,2
Up Type=0
Dn Type=3
Dn Slope=0.005
Boundary for River Rch & Prof#=Linn Creek,Reach-1,3
Up Type=0
Dn Type=3
Dn Slope=0.005
Boundary for River Rch & Prof#=Linn Creek,Reach-1,4
Up Type=0
Dn Type=3
Dn Slope=0.005
Boundary for River Rch & Prof#=Linn Creek,Reach-1,5
Up Type=0
Dn Type=3
Dn Slope=0.005
Boundary for River Rch & Prof#=Linn Creek,Reach-1,6
Up Type=0
Dn Type=3
Dn Slope=0.005
Boundary for River Rch & Prof#=Linn Creek,Reach-1,7
Up Type=0
Dn Type=3
Dn Slope=0.005

--- Linn Creek.g01 (geometry) ---

Geom Title=Existing Conditions

River Reach=Linn Creek,Reach-1
Reach XY= 30
      1305255.00      6892938.00      1306155.39      6895958.13
      1305104.94      6898168.06      1306015.50      6898986.78
      1310285.02      6899238.04      1311239.84      6898638.38
      1312284.82      6899638.43      1313570.21      6898938.51
      1315429.89      6899588.32      1317489.24      6899137.87
      1317508.83      6899657.87      1319658.06      6899595.73
      1321155.01      6900330.47      1322299.54      6899290.45
      1322210.41      6898593.16      1323275.30      6898138.29
      1323520.82      6898587.35      1324434.75      6898187.50
      1325829.97      6898738.50      1326344.53      6898288.93
      1327130.00      6898838.41      1327410.84      6898340.05
      1328084.87      6898788.41      1329289.79      6898238.24
      1330530.00      6898888.59      1332334.82      6898238.04
      1333244.31      6899488.76      1334810.94      6897690.26
      1335565.61      6898187.41      1337605.00      6898238.00

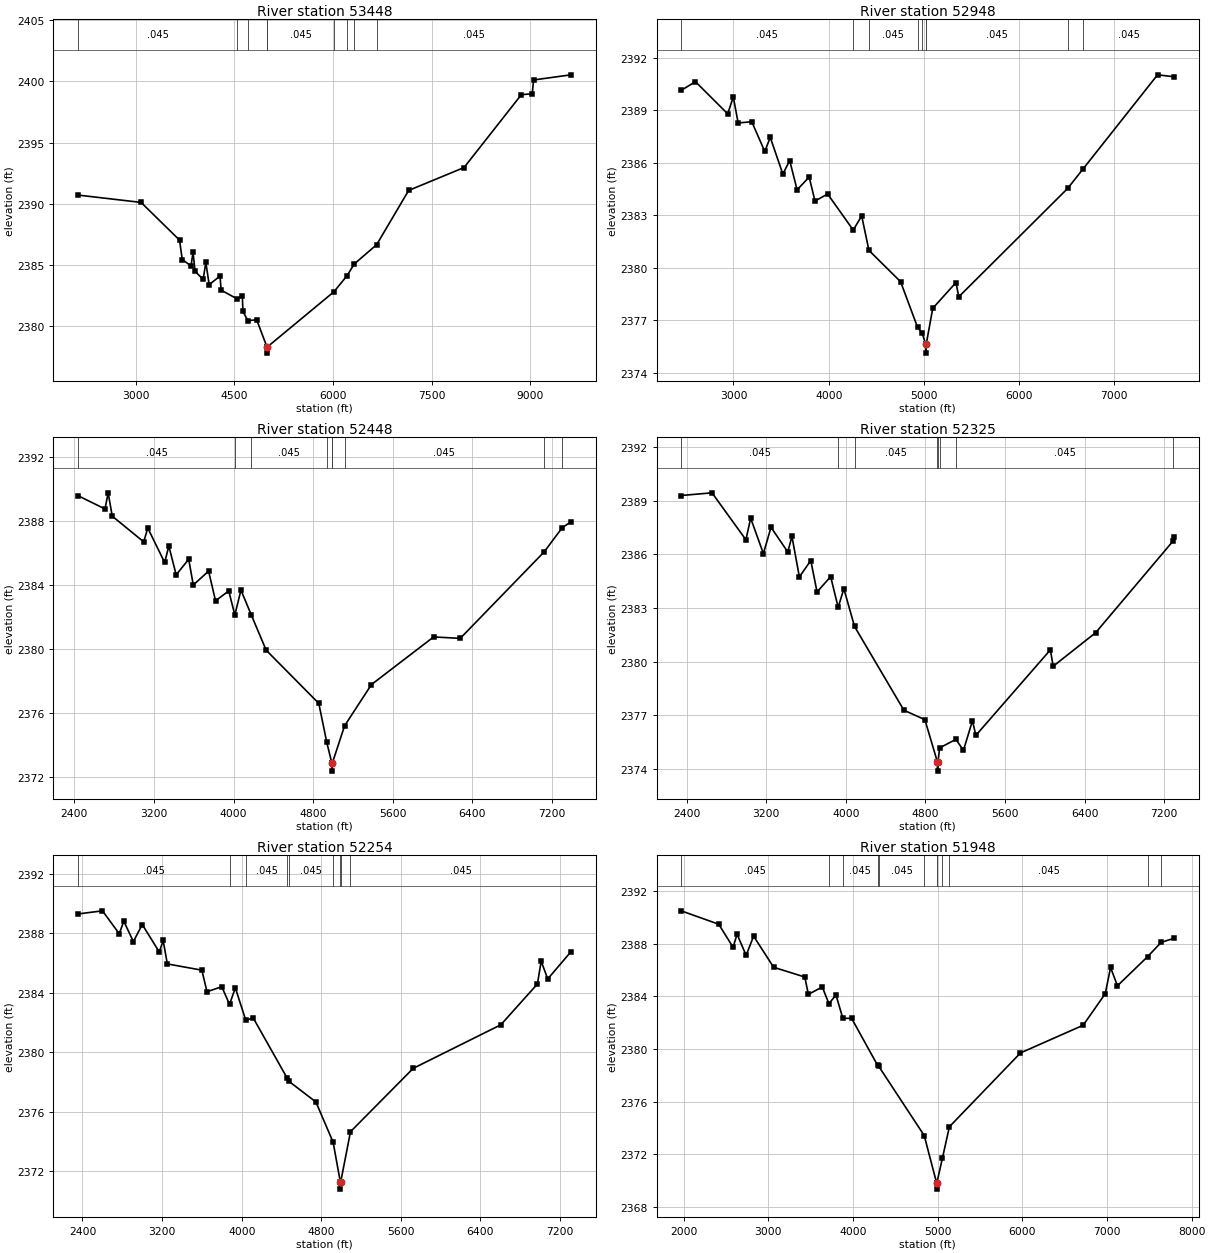
Type RM Length L Ch R = 1,53448,500,500,500
BEGIN DESCRIPTION:
Linn Creek 105.0
END DESCRIPTION:
XS GIS Cut Line= 4
      1302401.28      6892336.28      1305205.99      6892979.87
      1305435.50      6892971.86      1309067.97      6890513.35
#Sta/Elev= 30
  2122.4 2390.71  3080.4 2390.11  3665.2 2387.03  3706.2 2385.44  3839.6 2384.92
  3870.4 2386.03  3901.3 2384.47  4024.3 2383.82  4065.3 2385.20  4115.6 2383.39
  4280.8 2384.09  4297.4 2382.94  4542.6 2382.22  4619.4 2382.46  4629.6 2381.21
  4703.1 2380.44  4837.6 2380.52  4994.9 2378.29  4995.2 2377.79  4998.9 2378.29
  6011.3 2382.80  6210.8 2384.11  6321.6 2385.08  6661.3 2386.65  7148.7 2391.09
  7990.6 2392.96  8862.4 2398.92  9027.2 2398.99  9048.2 2400.12  9615.9 2400.54
#Mann=9,-1,0
  2122.4   0.045       0  4542.6   0.035       0  4703.1   0.045       0
  4994.9   0.045       0  4998.9   0.045       0  6011.3   0.035       0
  6210.8   0.045       0  6321.6    0.07       0  6661.3   0.045       0
Bank Sta=4994.9,4998.9
Exp/Cntr=0.3,0.1

Type RM Length L Ch R = 1,52948,500,500,500
BEGIN DESCRIPTION:
Linn Creek 104.0
END DESCRIPTION:
XS GIS Cut Line= 3
      1302909.09      6892883.16      1305404.64      6893405.86
      1307700.34      6892128.18
#Sta/Elev= 30
  2450.3 2390.14  2600.2 2390.64  2939.5 2388.80  2997.8 2389.77  3048.9 2388.28
  3192.0 2388.35  3328.7 2386.65  3386.1 2387.46  3518.2 2385.36  3590.4 2386.13
  3668.0 2384.46  3794.8 2385.19  3856.1 2383.82  3988.9 2384.22  4257.7 2382.16
  4346.5 2382.97  4422.6 2381.00  4755.2 2379.21  4933.1 2376.61  4980.6 2376.29
  5020.0 2375.63  5020.3 2375.13  5024.0 2375.63  5092.9 2377.69  5336.5 2379.16
  5366.6 2378.35  6510.0 2384.54  6671.3 2385.65  7454.1 2391.03  7627.3 2390.92
#Mann=9,-1,0
  2450.3   0.045       0  4257.7   0.035       0  4422.6   0.045       0
  4933.1   0.035       0  4980.6   0.045       0  5020.0   0.045       0
  5024.0   0.045       0  6510.0   0.035       0  6671.3   0.045       0
Bank Sta=5020,5024
Exp/Cntr=0.3,0.1

Type RM Length L Ch R = 1,52448,123,123,123
BEGIN DESCRIPTION:
Linn Creek 103.0
END DESCRIPTION:
XS GIS Cut Line= 3
      1303117.39      6893065.44      1305554.49      6893857.90
      1307660.87      6892727.35
#Sta/Elev= 30
  2437.3 2389.59  2708.2 2388.76  2739.7 2389.77  2780.8 2388.31  3097.3 2386.70
  3137.5 2387.57  3307.7 2385.41  3349.6 2386.44  3423.2 2384.64  3549.4 2385.61
  3595.2 2384.00  3749.2 2384.87  3818.8 2383.01  3951.8 2383.63  4012.9 2382.12
  4074.3 2383.68  4179.5 2382.11  4327.6 2379.92  4856.7 2376.59  4936.8 2374.15
  4987.6 2372.85  4987.9 2372.35  4992.5 2372.85  5116.1 2375.19  5385.9 2377.77
  6010.7 2380.75  6278.2 2380.66  7121.0 2386.07  7302.1 2387.58  7390.6 2387.96
#Mann=9,-1,0
  2437.3   0.045       0  4012.9   0.035       0  4179.5   0.045       0
  4936.8   0.035       0  4987.6   0.035       0  4992.5   0.035       0
  5116.1   0.045       0  7121.0   0.035       0  7302.1   0.045       0
Bank Sta=4987.6,4992.5
Exp/Cntr=0.3,0.1

Type RM Length L Ch R = 1,52325,71,71,71
BEGIN DESCRIPTION:
Linn Creek 102.6
END DESCRIPTION:
XS GIS Cut Line= 3
      1303086.00      6893216.82      1305523.07      6894009.27
      1307630.18      6892878.33
#Sta/Elev= 30
  2344.1 2389.30  2654.2 2389.45  2995.0 2386.82  3042.8 2388.03  3170.5 2386.05
  3247.4 2387.52  3415.6 2386.14  3457.7 2387.01  3532.4 2384.74  3647.0 2385.66
  3710.0 2383.90  3846.6 2384.76  3922.1 2383.04  3979.6 2384.08  4086.5 2381.97
  4582.8 2377.28  4793.9 2376.75  4920.5 2374.37  4920.9 2373.87  4925.5 2374.37
  4941.8 2375.17  5106.0 2375.65  5181.3 2375.03  5272.1 2376.69  5306.3 2375.87
  6055.2 2380.66  6083.3 2379.74  6510.4 2381.62  7292.7 2386.78  7298.2 2386.98
#Mann=8,-1,0
  2344.1   0.045       0  3922.1   0.035       0  4086.5   0.045       0
  4920.5   0.035       0  4925.5   0.045       0  4941.8   0.035       0
  5106.0   0.045       0  7292.7   0.035       0
Bank Sta=4920.5,4925.5
Exp/Cntr=0.3,0.1

Type RM Length L Ch R = 1,52254,306,306,306
BEGIN DESCRIPTION:
Linn Creek 102.5
END DESCRIPTION:
XS GIS Cut Line= 3
      1303131.66      6893271.07      1305568.77      6894063.53
      1307675.58      6892932.76
#Sta/Elev= 30
  2355.4 2389.30  2600.8 2389.51  2769.0 2387.97  2815.4 2388.81  2911.2 2387.44
  3000.4 2388.59  3172.0 2386.74  3210.7 2387.52  3252.7 2385.94  3599.7 2385.52
  3651.1 2384.07  3799.5 2384.41  3877.9 2383.22  3936.2 2384.33  4041.8 2382.14
  4115.0 2382.32  4459.0 2378.24  4472.1 2378.06  4745.9 2376.66  4919.2 2373.95
  4990.8 2371.30  4991.1 2370.80  4995.8 2371.30  5093.4 2374.66  5724.0 2378.92
  6604.9 2381.85  6972.0 2384.59  7010.2 2386.12  7076.0 2384.93  7309.2 2386.76
#Mann=9,-1,0
  2355.4   0.045       0  3877.9   0.035       0  4041.8   0.045       0
  4459.0   0.035       0  4472.1   0.045       0  4919.2   0.035       0
  4990.8   0.035       0  4995.8   0.035       0  5093.4   0.045       0
Bank Sta=4990.8,4995.8
Exp/Cntr=0.3,0.1

Type RM Length L Ch R = 1,51948,500,500,500
BEGIN DESCRIPTION:
Linn Creek 102.0
END DESCRIPTION:
XS GIS Cut Line= 3
      1302954.97      6893137.99      1305754.93      6894295.28
      1308067.04      6892730.40
#Sta/Elev= 30
  1970.3 2390.52  2414.0 2389.50  2583.6 2387.74  2630.4 2388.74  2737.9 2387.13
  2825.9 2388.59  3063.2 2386.22  3431.1 2385.48  3472.3 2384.16  3637.4 2384.72
  3715.3 2383.45  3799.0 2384.11  3880.1 2382.33  3982.9 2382.34  4291.0 2378.75
  4304.1 2378.68  4841.2 2373.41  4986.4 2369.83  4986.8 2369.33  4991.5 2369.83
  5056.9 2371.71  5138.7 2374.08  5978.2 2379.70  6718.8 2381.81  6979.4 2384.21
  7042.4 2386.21  7123.2 2384.81  7480.9 2387.04  7640.1 2388.12  7791.9 2388.43
#Mann=12,-1,0
  1970.3   0.045       0  3715.3   0.035       0  3880.1   0.045       0
  4291.0   0.035       0  4304.1   0.045       0  4841.2   0.035       0
  4986.4   0.035       0  4991.5   0.035       0  5056.9    0.07       0
  5138.7   0.045       0  7480.9   0.035       0  7640.1   0.045       0
Bank Sta=4986.4,4991.5
Exp/Cntr=0.3,0.1

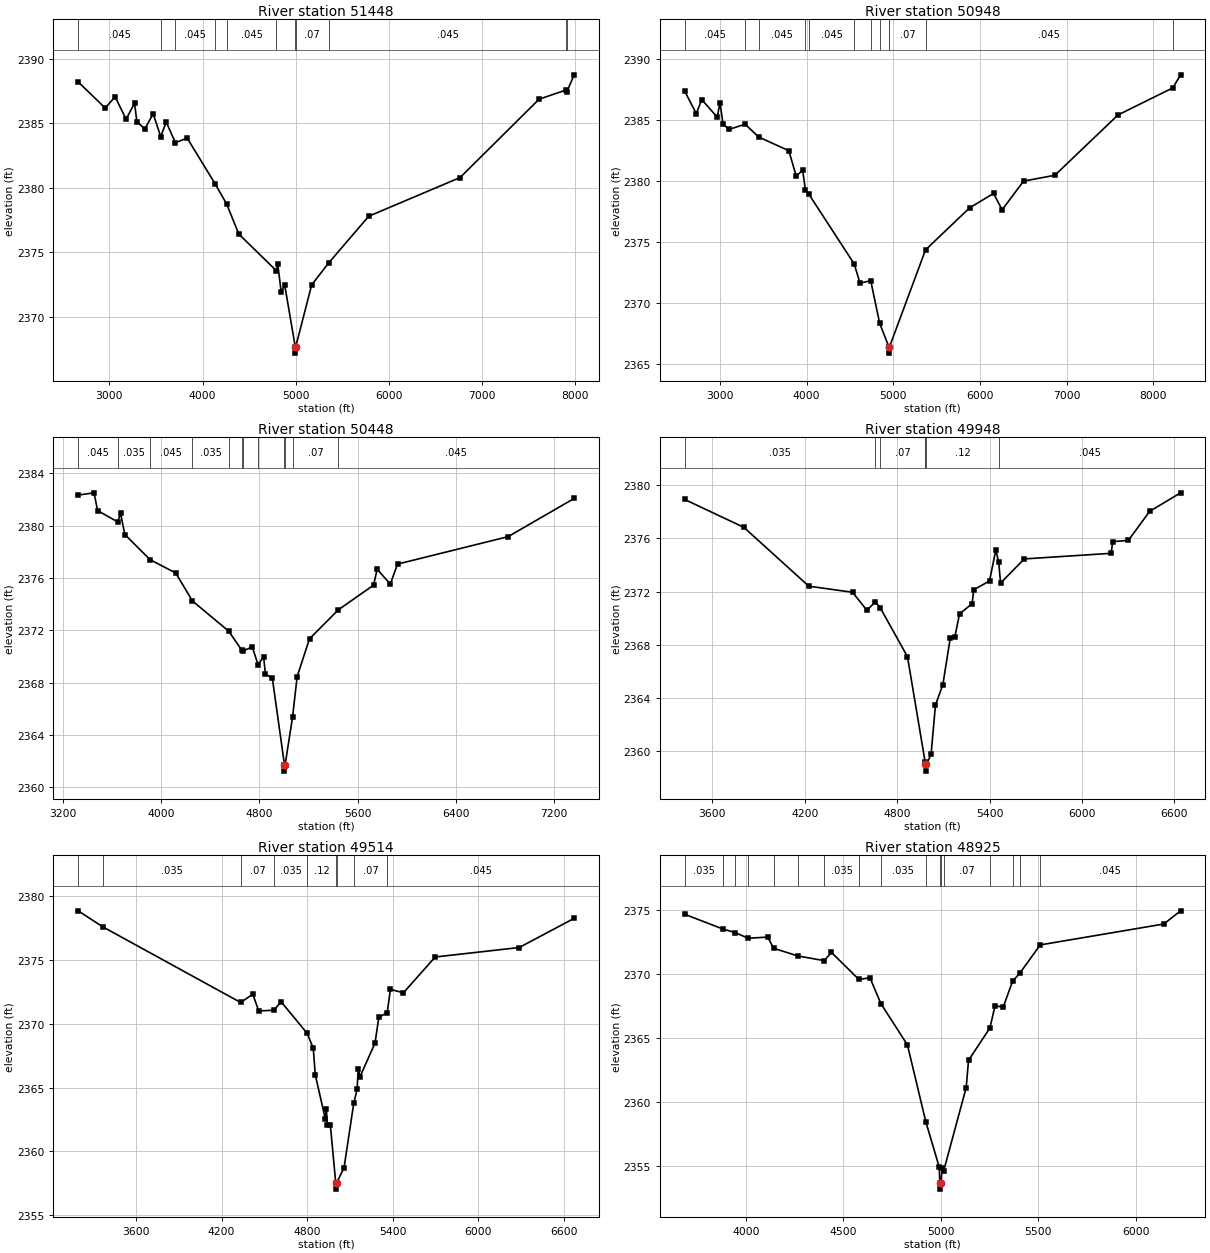
Type RM Length L Ch R = 1,51448,500,500,500
BEGIN DESCRIPTION:
Linn Creek 101.0
END DESCRIPTION:
XS GIS Cut Line= 3
      1303654.97      6893937.99      1305835.65      6894768.86
      1308154.97      6892888.03
#Sta/Elev= 30
  2666.4 2388.21  2955.4 2386.19  3062.4 2387.06  3180.1 2385.32  3270.7 2386.56
  3295.4 2385.14  3380.3 2384.56  3470.6 2385.74  3551.4 2383.97  3610.4 2385.10
  3708.7 2383.50  3835.1 2383.86  4133.3 2380.33  4258.5 2378.75  4388.9 2376.42
  4792.8 2373.57  4806.7 2374.10  4843.6 2371.92  4881.6 2372.46  4994.2 2367.69
  4994.6 2367.19  4999.8 2367.69  5170.5 2372.48  5351.8 2374.17  5782.7 2377.80
  6763.0 2380.80  7609.7 2386.87  7902.1 2387.59  7908.5 2387.46  7986.1 2388.76
#Mann=11,-1,0
  2666.4   0.045       0  3551.4   0.035       0  3708.7   0.045       0
  4133.3   0.035       0  4258.5   0.045       0  4792.8    0.07       0
  4994.2    0.07       0  4999.8    0.07       0  5351.8   0.045       0
  7902.1   0.035       0  7908.5   0.045       0
Bank Sta=4994.2,4999.8
Exp/Cntr=0.3,0.1

Type RM Length L Ch R = 1,50948,500,500,500
BEGIN DESCRIPTION:
Linn Creek 100.0
END DESCRIPTION:
XS GIS Cut Line= 3
      1303805.00      6894188.00      1305987.48      6895205.24
      1308455.03      6892987.97
#Sta/Elev= 30
  2592.1 2387.37  2726.1 2385.53  2789.2 2386.68  2967.2 2385.24  3000.3 2386.41
  3034.5 2384.68  3103.1 2384.23  3289.7 2384.66  3446.6 2383.61  3794.7 2382.48
  3879.8 2380.40  3953.9 2380.89  3986.6 2379.25  4025.3 2378.92  4548.9 2373.20
  4616.3 2371.62  4739.9 2371.82  4843.0 2368.33  4950.3 2366.38  4950.8 2365.88
  4955.9 2366.38  5372.5 2374.35  5881.7 2377.80  6157.5 2378.98  6256.9 2377.64
  6504.3 2379.99  6865.4 2380.47  7594.9 2385.42  8227.5 2387.64  8317.4 2388.71
#Mann=12,-1,0
  2592.1   0.045       0  3289.7   0.035       0  3446.6   0.045       0
  3986.6   0.035       0  4025.3   0.045       0  4548.9    0.07       0
  4739.9   0.035       0  4843.0    0.07       0  4950.3    0.07       0
  4955.9    0.07       0  5372.5   0.045       0  8227.5   0.035       0
Bank Sta=4950.3,4955.9
Exp/Cntr=0.3,0.1

Type RM Length L Ch R = 1,50448,500,500,500
BEGIN DESCRIPTION:
Linn Creek 99.0
END DESCRIPTION:
XS GIS Cut Line= 4
      1304654.98      6894737.98      1305942.08      6895667.88
      1306031.54      6895664.52      1307955.03      6894287.98
#Sta/Elev= 30
  3322.6 2382.34  3451.4 2382.51  3480.8 2381.15  3644.3 2380.29  3667.3 2380.95
  3702.9 2379.32  3908.1 2377.40  4117.5 2376.38  4253.9 2374.24  4549.8 2371.93
  4657.1 2370.46  4669.4 2370.43  4741.4 2370.73  4789.1 2369.36  4833.9 2369.99
  4848.6 2368.65  4905.0 2368.34  5003.6 2361.73  5004.1 2361.23  5009.4 2361.73
  5069.6 2365.34  5107.2 2368.46  5208.0 2371.35  5442.4 2373.56  5730.1 2375.45
  5759.6 2376.67  5866.5 2375.53  5925.4 2377.06  6827.2 2379.16  7365.3 2382.08
#Mann=12,-1,0
  3322.6   0.045       0  3644.3   0.035       0  3908.1   0.045       0
  4253.9   0.035       0  4549.8    0.07       0  4657.1   0.035       0
  4669.4    0.07       0  4789.1    0.16       0  5003.6    0.07       0
  5009.4    0.16       0  5069.6    0.07       0  5442.4   0.045       0
Bank Sta=5003.6,5009.4
Exp/Cntr=0.3,0.1

Type RM Length L Ch R = 1,49948,434,434,434
BEGIN DESCRIPTION:
Linn Creek 98.0
END DESCRIPTION:
XS GIS Cut Line= 3
      1304855.00      6895138.00      1306105.13      6896104.55
      1307704.98      6895738.01
#Sta/Elev= 30
  3419.8 2378.93  3804.7 2376.83  4225.8 2372.41  4510.1 2371.95  4603.4 2370.60
  4658.5 2371.23  4689.4 2370.80  4866.9 2367.11  4981.7 2359.19  4984.0 2359.00
  4984.5 2358.50  4990.6 2359.00  5020.4 2359.78  5048.9 2363.47  5096.9 2365.01
  5144.9 2368.50  5174.3 2368.58  5205.1 2370.32  5287.1 2371.10  5297.4 2372.14
  5400.0 2372.80  5441.0 2375.14  5459.6 2374.21  5471.8 2372.64  5625.7 2374.46
  6189.9 2374.88  6200.2 2375.76  6301.6 2375.85  6440.5 2378.04  6641.3 2379.43
#Mann=7,-1,0
  3419.8   0.035       0  4658.5    0.16       0  4689.4    0.07       0
  4981.7    0.12       0  4984.0    0.07       0  4990.6    0.12       0
  5459.6   0.045       0
Bank Sta=4984,4990.6
Exp/Cntr=0.3,0.1

Type RM Length L Ch R = 1,49514,589,589,589
BEGIN DESCRIPTION:
Linn Creek 97.0
END DESCRIPTION:
XS GIS Cut Line= 4
      1304705.03      6895338.03      1306019.33      6896523.78
      1306108.74      6896522.05      1307705.00      6896238.00
#Sta/Elev= 30
  3193.6 2378.86  3365.3 2377.61  4333.7 2371.67  4418.8 2372.32  4460.7 2371.01
  4567.9 2371.06  4616.8 2371.74  4800.8 2369.25  4843.3 2368.08  4857.5 2366.00
  4928.5 2362.51  4935.2 2363.31  4942.7 2362.09  4963.2 2362.06  5001.0 2357.53
  5001.5 2357.03  5007.6 2357.53  5059.5 2358.71  5127.3 2363.75  5150.9 2364.85
  5159.0 2366.48  5171.3 2365.85  5277.0 2368.49  5303.3 2370.50  5362.6 2370.88
  5384.6 2372.70  5476.0 2372.43  5699.4 2375.24  6288.5 2375.98  6674.5 2378.27
#Mann=9,-1,0
  3193.6    0.07       0  3365.3   0.035       0  4333.7    0.07       0
  4567.9   0.035       0  4800.8    0.12       0  5001.0    0.07       0
  5007.6    0.12       0  5127.3    0.07       0  5362.6   0.045       0
Bank Sta=5001,5007.6
Exp/Cntr=0.3,0.1

Type RM Length L Ch R = 1,48925,427,427,427
BEGIN DESCRIPTION:
Linn Creek 96.0
END DESCRIPTION:
XS GIS Cut Line= 3
      1304954.98      6895937.98      1305826.45      6896987.93
      1306955.01      6897338.00
#Sta/Elev= 30
  3685.5 2374.67  3881.7 2373.52  3944.9 2373.24  4011.5 2372.80  4112.0 2372.89
  4141.7 2372.02  4266.0 2371.42  4402.2 2371.05  4438.8 2371.70  4579.4 2369.59
  4636.8 2369.71  4692.8 2367.70  4829.2 2364.47  4923.2 2358.49  4992.3 2354.94
  4995.4 2353.72  4995.9 2353.22  5002.2 2353.72  5006.6 2354.86  5014.9 2354.63
  5130.8 2361.15  5142.7 2363.27  5252.5 2365.80  5278.8 2367.53  5320.7 2367.42
  5369.0 2369.45  5405.1 2370.05  5510.6 2372.28  6144.9 2373.91  6231.6 2374.94
#Mann=17,-1,0
  3685.5   0.035       0  3881.7    0.07       0  3944.9   0.035       0
  4011.5    0.07       0  4141.7   0.035       0  4266.0    0.07       0
  4402.2   0.035       0  4579.4    0.07       0  4692.8   0.035       0
  4923.2    0.12       0  4995.4    0.07       0  5002.2    0.12       0
  5014.9    0.07       0  5252.5   0.035       0  5369.0    0.07       0
  5405.1   0.035       0  5510.6   0.045       0
Bank Sta=4995.4,5002.2
Exp/Cntr=0.3,0.1

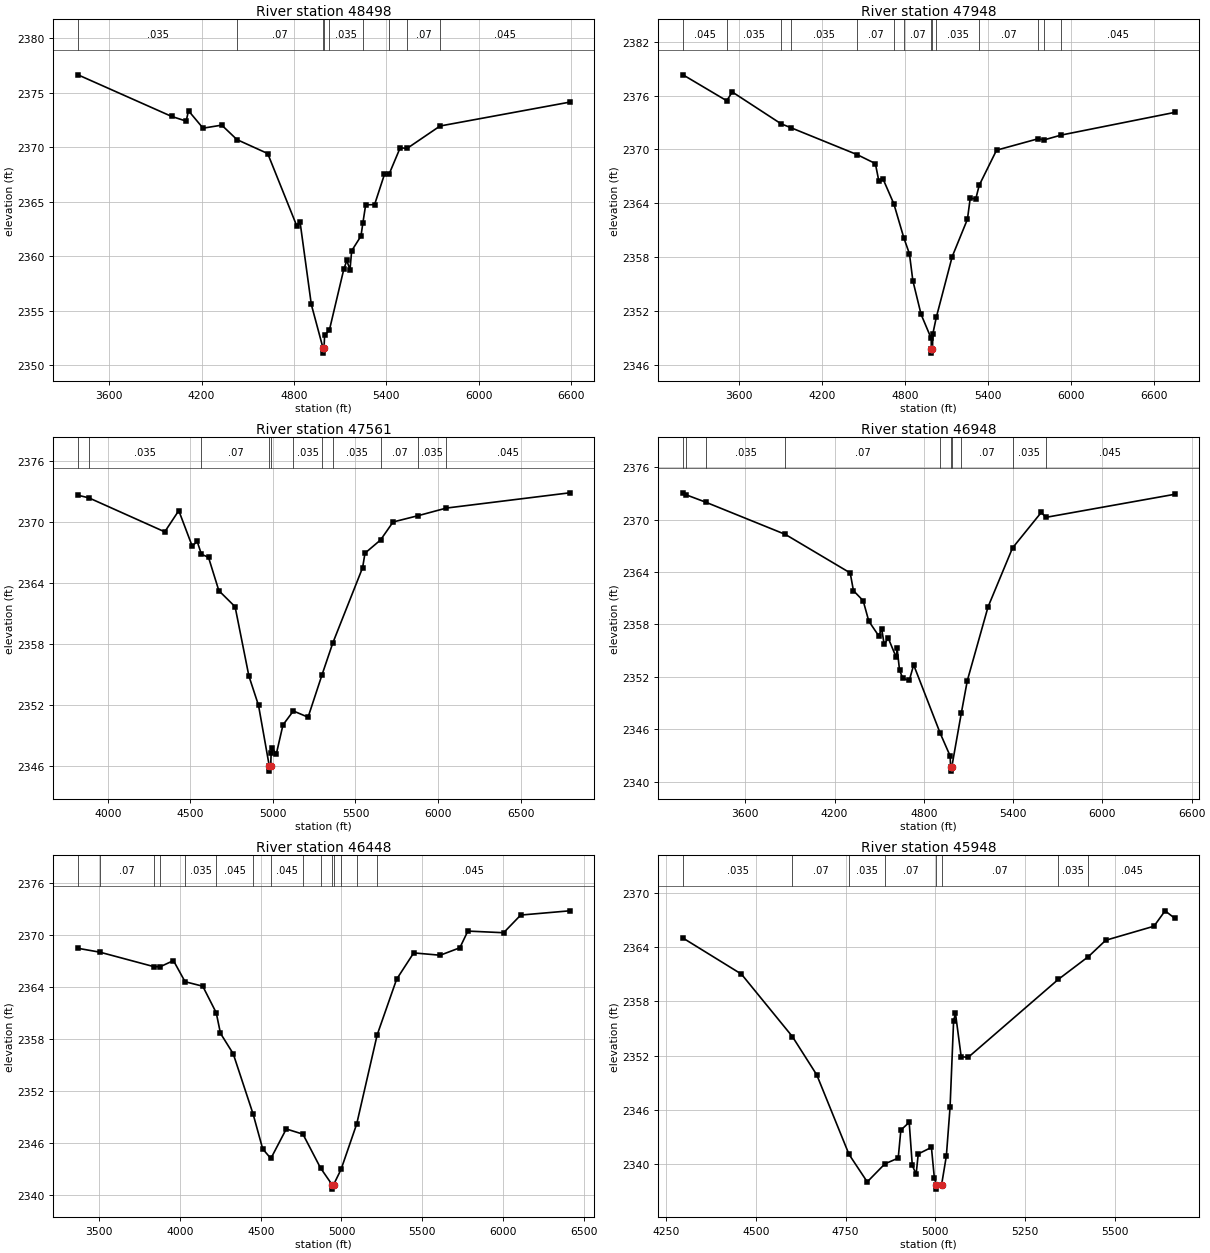
Type RM Length L Ch R = 1,48498,550,550,550
BEGIN DESCRIPTION:
Linn Creek 95.0
END DESCRIPTION:
XS GIS Cut Line= 3
      1304608.87      6895826.08      1305457.83      6897190.67
      1307015.08      6897497.95
#Sta/Elev= 30
  3397.1 2376.66  4005.5 2372.84  4099.9 2372.41  4115.2 2373.36  4209.7 2371.76
  4331.2 2372.04  4430.1 2370.71  4629.9 2369.43  4818.8 2362.78  4840.0 2363.15
  4913.2 2355.57  4988.6 2351.60  4989.1 2351.10  4995.9 2351.60  4999.7 2352.77
  5030.2 2353.19  5124.2 2358.80  5144.0 2359.61  5164.4 2358.74  5175.5 2360.50
  5235.8 2361.85  5248.0 2363.03  5266.4 2364.72  5324.3 2364.74  5388.7 2367.53
  5419.3 2367.56  5490.6 2369.96  5535.4 2369.90  5749.8 2371.96  6591.5 2374.15
#Mann=9,-1,0
  3397.1   0.035       0  4430.1    0.07       0  4988.6    0.07       0
  4995.9    0.07       0  5030.2   0.035       0  5248.0    0.07       0
  5419.3   0.035       0  5535.4    0.07       0  5749.8   0.045       0
Bank Sta=4988.6,4995.9
Exp/Cntr=0.3,0.1

Type RM Length L Ch R = 1,47948,387,387,387
BEGIN DESCRIPTION:
Linn Creek 94.0
END DESCRIPTION:
XS GIS Cut Line= 3
      1303577.63      6896992.75      1305255.38      6897655.75
      1306999.49      6897581.29
#Sta/Elev= 30
  3196.0 2378.30  3511.4 2375.42  3551.9 2376.39  3903.4 2372.86  3978.2 2372.40
  4454.2 2369.42  4585.0 2368.43  4609.4 2366.54  4639.1 2366.76  4718.5 2363.95
  4790.5 2360.17  4831.1 2358.39  4855.5 2355.42  4914.9 2351.67  4988.0 2348.99
  4989.3 2347.85  4989.8 2347.35  4997.5 2347.85  5000.0 2349.50  5024.8 2351.32
  5139.7 2358.08  5249.8 2362.24  5269.9 2364.58  5309.9 2364.50  5334.9 2366.02
  5460.0 2369.92  5760.3 2371.19  5802.6 2371.06  5926.6 2371.60  6745.7 2374.12
#Mann=14,-1,0
  3196.0   0.045       0  3511.4   0.035       0  3903.4    0.07       0
  3978.2   0.035       0  4454.2    0.07       0  4718.5   0.035       0
  4790.5    0.07       0  4989.3    0.07       0  4997.5    0.07       0
  5024.8   0.035       0  5334.9    0.07       0  5760.3   0.035       0
  5802.6    0.07       0  5926.6   0.045       0
Bank Sta=4989.3,4997.5
Exp/Cntr=0.3,0.1

Type RM Length L Ch R = 1,47561,613,613,613
BEGIN DESCRIPTION:
Linn Creek 93.0
END DESCRIPTION:
XS GIS Cut Line= 3
      1304023.84      6897506.65      1305104.53      6897980.60
      1306877.97      6897691.53
#Sta/Elev= 30
  3819.6 2372.61  3884.8 2372.36  4345.0 2369.01  4429.9 2371.10  4511.0 2367.61
  4541.6 2368.06  4566.8 2366.81  4609.9 2366.50  4672.6 2363.22  4770.9 2361.64
  4854.5 2354.82  4912.8 2351.93  4978.0 2345.96  4978.5 2345.46  4986.6 2345.96
  4989.2 2347.23  4997.2 2347.70  5020.4 2347.14  5060.9 2350.01  5123.6 2351.38
  5212.9 2350.77  5297.7 2354.96  5362.3 2358.06  5543.2 2365.49  5557.4 2366.91
  5651.6 2368.21  5727.6 2369.98  5881.3 2370.61  6050.3 2371.35  6796.5 2372.85
#Mann=11,-1,0
  3819.6    0.07       0  3884.8   0.035       0  4566.8    0.07       0
  4978.0    0.07       0  4986.6    0.07       0  5123.6   0.035       0
  5297.7    0.07       0  5362.3   0.035       0  5651.6    0.07       0
  5881.3   0.035       0  6050.3   0.045       0
Bank Sta=4978,4986.6
Exp/Cntr=0.3,0.1

Type RM Length L Ch R = 1,46948,500,500,500
BEGIN DESCRIPTION:
Linn Creek 92.0
END DESCRIPTION:
XS GIS Cut Line= 4
      1303888.37      6897589.96      1305244.61      6898335.35
      1305500.25      6898244.74      1306886.68      6897711.33
#Sta/Elev= 30
  3181.2 2373.07  3199.4 2372.86  3333.8 2372.00  3869.1 2368.31  4305.0 2363.90
  4326.8 2361.87  4392.1 2360.72  4430.0 2358.38  4495.4 2356.73  4517.2 2357.43
  4533.3 2355.72  4560.8 2356.43  4614.7 2354.22  4620.4 2355.26  4636.5 2352.78
  4658.3 2351.84  4701.9 2351.59  4731.6 2353.37  4910.6 2345.52  4976.9 2342.94
  4979.5 2341.71  4980.0 2341.21  4988.1 2341.71  5052.0 2347.87  5092.3 2351.58
  5231.5 2360.01  5396.1 2366.76  5589.3 2370.83  5619.7 2370.26  6485.5 2372.90
#Mann=10,-1,0
  3181.2   0.035       0  3199.4    0.07       0  3333.8   0.035       0
  3869.1    0.07       0  4910.6   0.035       0  4979.5   0.035       0
  4988.1   0.035       0  5052.0    0.07       0  5396.1   0.035       0
  5619.7   0.045       0
Bank Sta=4979.5,4988.1
Exp/Cntr=0.3,0.1

Type RM Length L Ch R = 1,46448,500,500,500
BEGIN DESCRIPTION:
Linn Creek 91.0
END DESCRIPTION:
XS GIS Cut Line= 5
      1304344.31      6897983.04      1305332.14      6898602.82
      1305743.60      6898647.96      1305784.16      6898616.04
      1306895.36      6897743.88
#Sta/Elev= 30
  3368.3 2368.45  3504.6 2368.00  3838.6 2366.33  3878.4 2366.33  3959.4 2367.03
  4031.4 2364.59  4141.0 2364.07  4224.2 2361.01  4250.6 2358.63  4329.5 2356.27
  4452.4 2349.32  4512.2 2345.27  4562.7 2344.17  4658.1 2347.58  4761.3 2346.98
  4870.4 2343.07  4942.2 2341.13  4942.7 2340.63  4950.9 2341.13  4997.8 2342.93
  5094.3 2348.16  5221.0 2358.45  5341.5 2364.88  5447.3 2367.92  5611.3 2367.65
  5732.9 2368.51  5782.6 2370.44  6004.1 2370.25  6109.8 2372.29  6412.6 2372.78
#Mann=15,-1,0
  3368.3   0.035       0  3504.6    0.07       0  3838.6   0.035       0
  3878.4    0.07       0  4031.4   0.035       0  4224.2   0.045       0
  4452.4   0.035       0  4562.7   0.045       0  4761.3   0.035       0
  4870.4    0.07       0  4942.2   0.035       0  4950.9    0.07       0
  4997.8   0.035       0  5094.3    0.07       0  5221.0   0.045       0
Bank Sta=4942.2,4950.9
Exp/Cntr=0.3,0.1

Type RM Length L Ch R = 1,45948,500,500,500
BEGIN DESCRIPTION:
Linn Creek 90.0
END DESCRIPTION:
XS GIS Cut Line= 3
      1305755.00      6899637.99      1305996.13      6898977.74
      1306162.39      6898332.31
#Sta/Elev= 30
  4297.1 2364.97  4459.8 2360.99  4601.8 2354.09  4669.7 2349.86  4759.5 2341.08
  4810.3 2338.04  4859.4 2340.03  4896.6 2340.67  4903.9 2343.76  4927.2 2344.62
  4935.8 2339.86  4946.5 2338.89  4952.4 2341.13  4989.1 2341.85  4997.2 2338.49
  5002.7 2337.74  5003.2 2337.24  5017.5 2337.74  5030.7 2340.91  5041.0 2346.28
  5050.9 2355.85  5056.1 2356.65  5072.0 2351.86  5091.6 2351.80  5342.3 2360.40
  5426.6 2362.93  5474.7 2364.73  5609.0 2366.28  5640.0 2367.98  5666.5 2367.17
#Mann=8,-1,0
  4297.1   0.035       0  4601.8    0.07       0  4759.5   0.035       0
  4859.4    0.07       0  5002.7    0.07       0  5017.5    0.07       0
  5342.3   0.035       0  5426.6   0.045       0
Bank Sta=5002.7,5017.5
Exp/Cntr=0.3,0.1

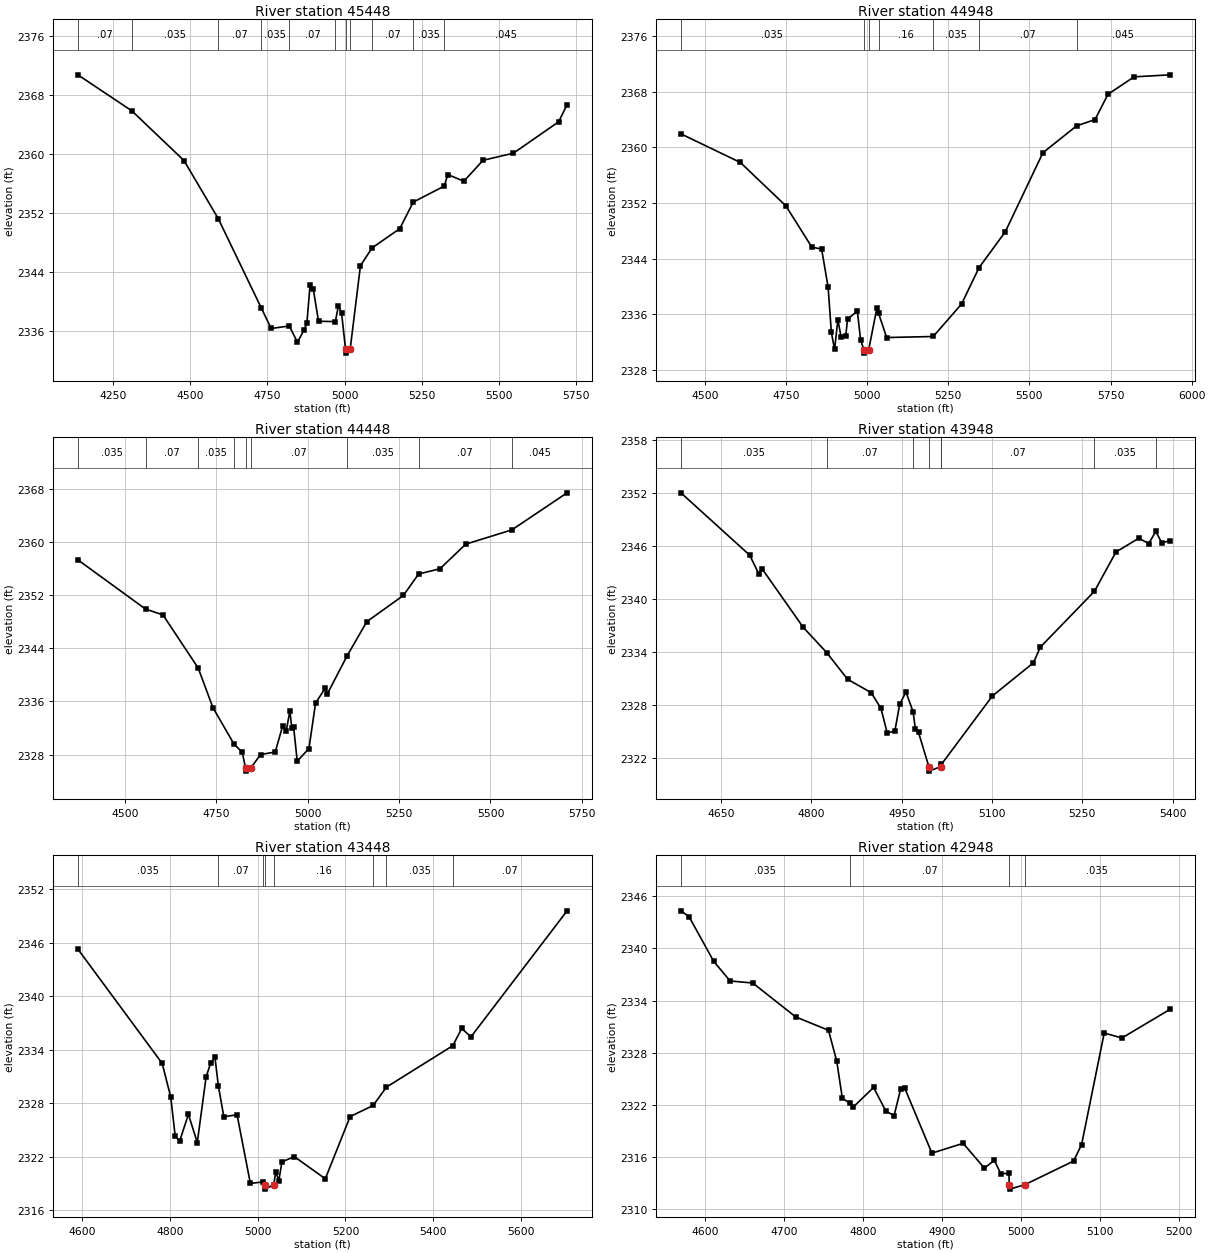
Type RM Length L Ch R = 1,45448,500,500,500
BEGIN DESCRIPTION:
Linn Creek 89.0
END DESCRIPTION:
XS GIS Cut Line= 3
      1306662.58      6899835.05      1306493.79      6898988.00
      1306357.36      6898281.25
#Sta/Elev= 30
  4136.3 2370.69  4311.2 2365.80  4480.0 2359.06  4590.9 2351.18  4729.5 2339.13
  4762.0 2336.31  4820.6 2336.65  4847.1 2334.44  4869.2 2336.17  4877.6 2337.04
  4887.8 2342.18  4898.0 2341.72  4915.2 2337.29  4969.7 2337.24  4979.6 2339.38
  4989.8 2338.45  5002.7 2333.47  5003.2 2332.97  5017.6 2333.47  5050.9 2344.81
  5088.3 2347.22  5178.2 2349.84  5221.8 2353.44  5322.1 2355.61  5333.8 2357.17
  5385.6 2356.27  5448.1 2359.11  5546.2 2360.07  5692.6 2364.33  5719.8 2366.65
#Mann=11,-1,0
  4136.3    0.07       0  4311.2   0.035       0  4590.9    0.07       0
  4729.5   0.035       0  4820.6    0.07       0  4969.7   0.035       0
  5002.7   0.035       0  5017.6   0.035       0  5088.3    0.07       0
  5221.8   0.035       0  5322.1   0.045       0
Bank Sta=5002.7,5017.6
Exp/Cntr=0.3,0.1

Type RM Length L Ch R = 1,44948,500,500,500
BEGIN DESCRIPTION:
Linn Creek 88.0
END DESCRIPTION:
XS GIS Cut Line= 3
      1306961.19      6899560.77      1306993.79      6898988.00
      1306919.52      6898057.25
#Sta/Elev= 30
  4426.3 2361.93  4609.4 2357.82  4749.6 2351.59  4829.7 2345.65  4859.8 2345.38
  4879.8 2339.91  4889.8 2333.41  4899.8 2330.96  4909.8 2335.25  4919.9 2332.73
  4934.1 2332.96  4939.9 2335.34  4969.9 2336.47  4980.0 2332.30  4990.0 2330.93
  4990.5 2330.43  5004.9 2330.93  5030.1 2336.90  5035.3 2336.15  5060.2 2332.67
  5203.7 2332.82  5290.9 2337.48  5345.0 2342.72  5425.6 2347.85  5541.7 2359.22
  5645.5 2363.08  5702.2 2363.98  5742.3 2367.62  5822.6 2370.12  5933.7 2370.41
#Mann=7,-1,0
  4426.3   0.035       0  4990.0   0.035       0  5004.9   0.035       0
  5035.3    0.16       0  5203.7   0.035       0  5345.0    0.07       0
  5645.5   0.045       0
Bank Sta=4990,5004.9
Exp/Cntr=0.3,0.1

Type RM Length L Ch R = 1,44448,500,500,500
BEGIN DESCRIPTION:
Linn Creek 87.0
END DESCRIPTION:
XS GIS Cut Line= 3
      1307440.35      6899616.34      1307493.71      6898989.10
      1307440.49      6898281.30
#Sta/Elev= 30
  4370.5 2357.28  4555.7 2349.88  4603.5 2349.00  4699.9 2341.01  4740.2 2335.06
  4797.9 2329.58  4820.5 2328.35  4829.4 2326.01  4829.9 2325.51  4844.4 2326.01
  4870.6 2328.01  4910.8 2328.38  4930.9 2332.27  4940.9 2331.54  4950.9 2334.57
  4956.1 2332.02  4961.1 2332.17  4971.0 2327.01  5003.1 2328.90  5021.2 2335.74
  5047.9 2338.01  5052.9 2337.07  5107.7 2342.86  5161.6 2347.99  5261.8 2351.94
  5303.3 2355.15  5362.1 2355.95  5432.3 2359.64  5558.7 2361.79  5709.8 2367.36
#Mann=9,-1,0
  4370.5   0.035       0  4555.7    0.07       0  4699.9   0.035       0
  4797.9    0.07       0  4829.4    0.07       0  4844.4    0.07       0
  5107.7   0.035       0  5303.3    0.07       0  5558.7   0.045       0
Bank Sta=4829.4,4844.4
Exp/Cntr=0.3,0.1

Type RM Length L Ch R = 1,43948,500,500,500
BEGIN DESCRIPTION:
Linn Creek 86.0
END DESCRIPTION:
XS GIS Cut Line= 3
      1308055.00      6899437.98      1307942.70      6899036.60
      1307755.01      6898688.02
#Sta/Elev= 30
  4583.2 2352.00  4697.4 2344.95  4713.0 2342.78  4718.2 2343.39  4786.5 2336.78
  4825.4 2333.93  4860.0 2330.92  4899.3 2329.40  4915.5 2327.62  4925.9 2324.84
  4938.6 2325.07  4946.6 2328.08  4957.0 2329.48  4968.8 2327.26  4972.7 2325.27
  4977.9 2324.90  4995.1 2321.03  4995.6 2320.53  5014.6 2321.03  5016.0 2321.30
  5100.6 2329.03  5168.8 2332.78  5180.1 2334.54  5270.2 2340.87  5305.9 2345.31
  5344.0 2346.87  5360.2 2346.26  5372.1 2347.64  5382.1 2346.33  5395.9 2346.60
#Mann=8,-1,0
  4583.2   0.035       0  4825.4    0.07       0  4968.8    0.16       0
  4995.1    0.07       0  5014.6    0.16       0  5016.0    0.07       0
  5270.2   0.035       0  5372.1    0.07       0
Bank Sta=4995.1,5014.6
Exp/Cntr=0.3,0.1

Type RM Length L Ch R = 1,43448,500,500,500
BEGIN DESCRIPTION:
Linn Creek 85.0
END DESCRIPTION:
XS GIS Cut Line= 3
      1308355.00      6899338.00      1308409.63      6898931.15
      1307904.99      6898437.99
#Sta/Elev= 30
  4589.5 2345.26  4781.8 2332.46  4801.4 2328.68  4811.5 2324.32  4821.6 2323.74
  4841.7 2326.75  4861.9 2323.59  4882.1 2330.95  4892.2 2332.45  4902.3 2333.12
  4910.0 2329.93  4922.5 2326.48  4952.7 2326.70  4983.0 2319.01  5012.3 2319.18
  5016.9 2318.87  5017.4 2318.37  5036.5 2318.87  5040.9 2320.29  5048.0 2319.33
  5055.0 2321.43  5083.3 2322.01  5154.0 2319.53  5210.6 2326.50  5263.1 2327.74
  5293.5 2329.80  5444.9 2334.44  5465.2 2336.37  5486.3 2335.43  5705.6 2349.55
#Mann=8,-1,0
  4589.5   0.035       0  4910.0    0.07       0  5012.3    0.16       0
  5016.9    0.07       0  5036.5    0.16       0  5263.1    0.07       0
  5293.5   0.035       0  5444.9    0.07       0
Bank Sta=5016.9,5036.5
Exp/Cntr=0.3,0.1

Type RM Length L Ch R = 1,42948,500,500,500
BEGIN DESCRIPTION:
Linn Creek 84.0
END DESCRIPTION:
XS GIS Cut Line= 3
      1308954.99      6899337.96      1308840.28      6898923.44
      1308804.99      6898737.97
#Sta/Elev= 30
  4569.9 2344.33  4580.2 2343.65  4611.4 2338.51  4632.1 2336.26  4660.8 2336.02
  4715.1 2332.12  4756.6 2330.58  4767.0 2327.03  4774.1 2322.76  4783.4 2322.20
  4787.8 2321.74  4813.6 2324.00  4829.3 2321.26  4839.6 2320.77  4847.9 2323.84
  4853.1 2323.91  4887.4 2316.44  4926.9 2317.57  4953.8 2314.72  4966.4 2315.61
  4974.5 2314.09  4984.9 2314.11  4985.2 2312.80  4985.7 2312.30  5004.8 2312.80
  5066.6 2315.53  5076.8 2317.43  5105.4 2330.27  5127.7 2329.69  5188.8 2333.00
#Mann=4,-1,0
  4569.9   0.035       0  4783.4    0.07       0  4985.2   0.035       0
  5004.8   0.035       0
Bank Sta=4985.2,5004.8
Exp/Cntr=0.3,0.1