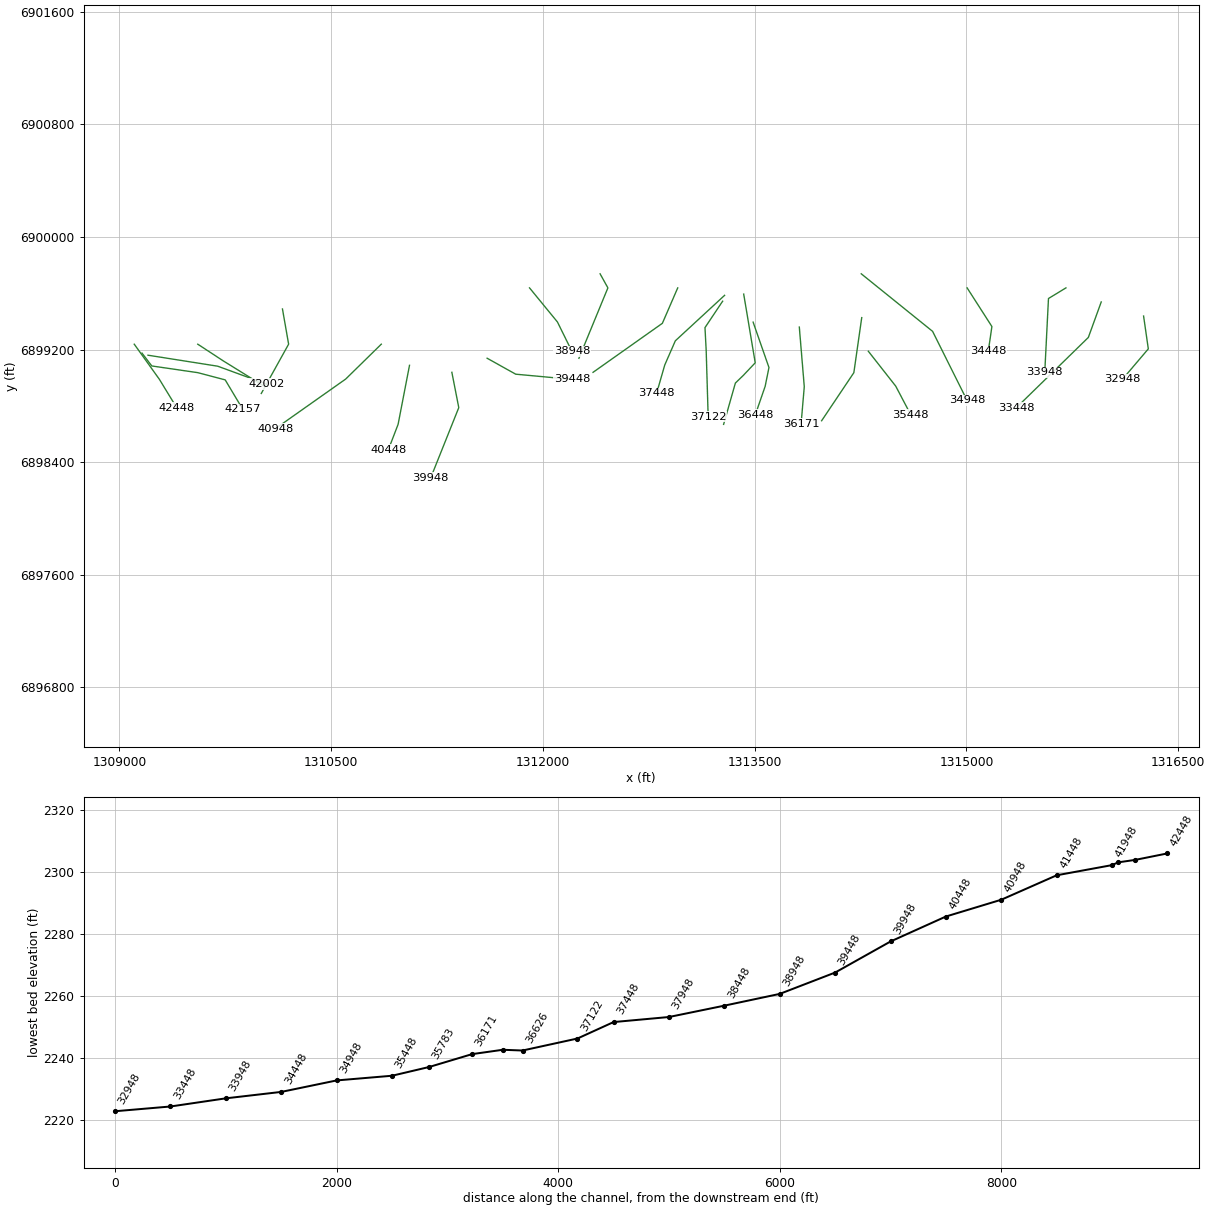
HEC-RAS study Linn Creek.prj: Linn Creek Base Level Engineering

--- Linn Creek.g01 (geometry) --- (continued)

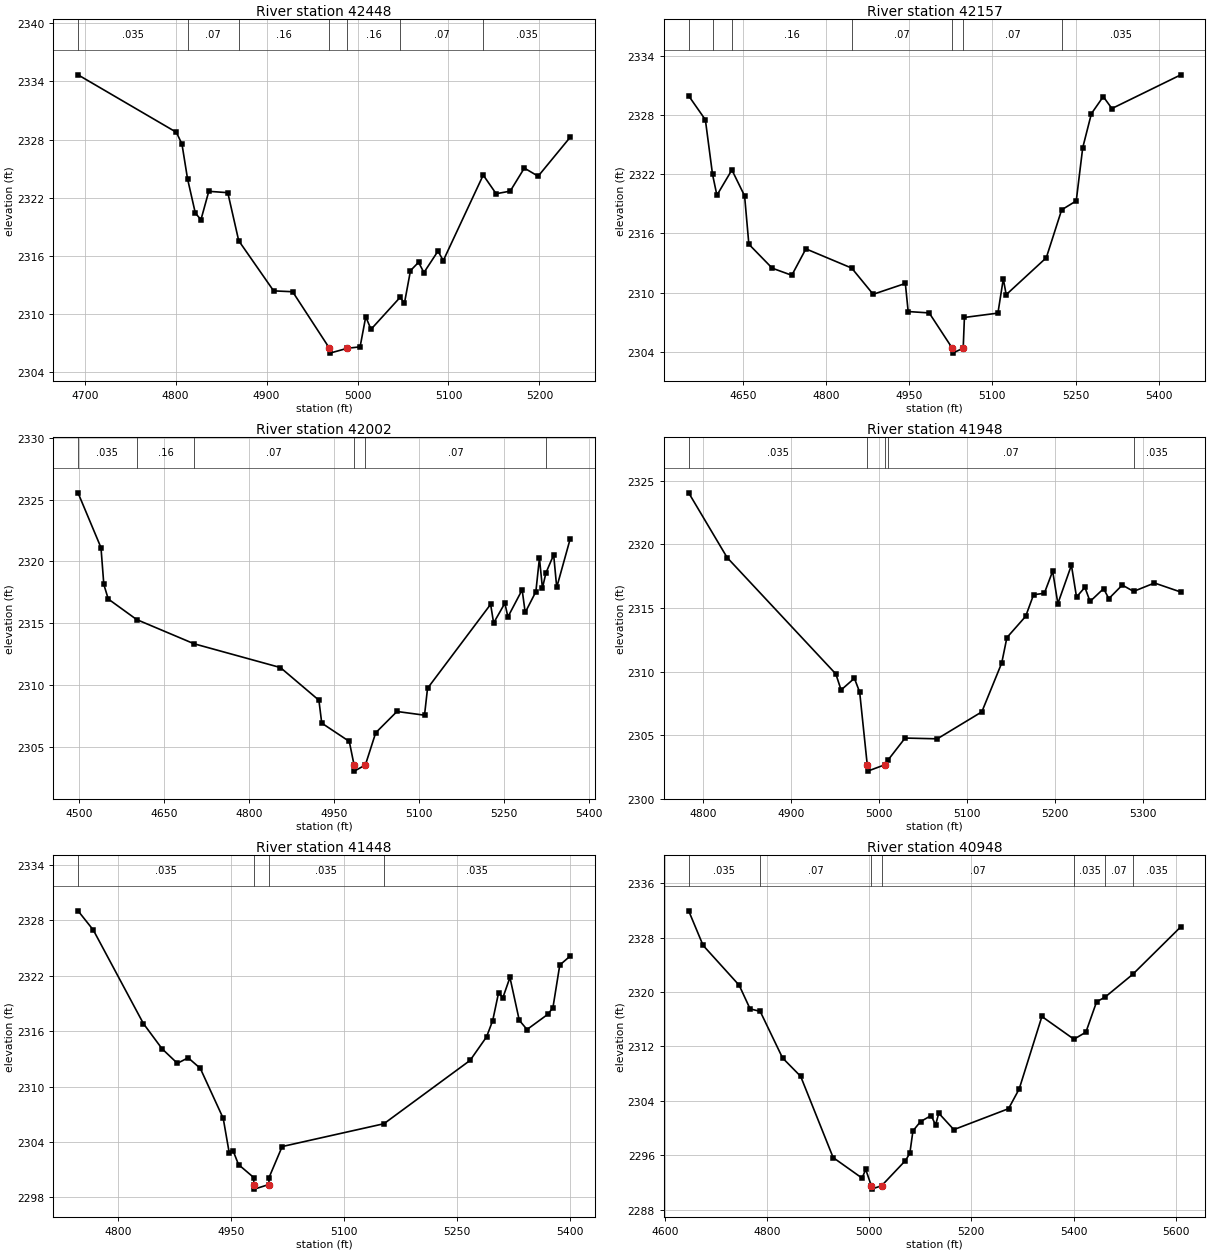
Type RM Length L Ch R = 1,42448,291,291,291
BEGIN DESCRIPTION:
Linn Creek 83.0
END DESCRIPTION:
XS GIS Cut Line= 3
      1309105.02      6899237.98      1309283.52      6898987.72
      1309405.02      6898787.97
#Sta/Elev= 30
  4692.6 2334.68  4800.7 2328.75  4806.9 2327.53  4813.0 2323.96  4821.6 2320.40
  4827.8 2319.72  4836.4 2322.65  4857.3 2322.51  4869.3 2317.55  4907.7 2312.37
  4928.6 2312.28  4969.1 2306.44  4969.6 2305.94  4988.8 2306.44  5002.8 2306.59
  5009.0 2309.69  5014.8 2308.40  5046.7 2311.69  5051.6 2311.12  5058.2 2314.46
  5067.1 2315.32  5073.0 2314.26  5088.4 2316.47  5094.3 2315.50  5138.2 2324.33
  5152.4 2322.40  5167.9 2322.67  5183.4 2325.05  5198.6 2324.21  5233.8 2328.23
#Mann=7,-1,0
  4692.6   0.035       0  4813.0    0.07       0  4869.3    0.16       0
  4969.1    0.07       0  4988.8    0.16       0  5046.7    0.07       0
  5138.2   0.035       0
Bank Sta=4969.1,4988.8
Exp/Cntr=0.3,0.1

Type RM Length L Ch R = 1,42157,155,155,155
BEGIN DESCRIPTION:
Linn Creek 82.6
END DESCRIPTION:
XS GIS Cut Line= 5
      1309159.88      6899174.47      1309229.34      6899083.31
      1309555.73      6899035.57      1309749.30      6898984.35
      1309873.43      6898776.03
#Sta/Elev= 30
  4552.6 2329.96  4582.7 2327.53  4595.6 2321.99  4603.5 2319.87  4630.5 2322.44
  4653.4 2319.81  4661.1 2314.90  4703.2 2312.47  4738.5 2311.75  4763.9 2314.43
  4846.5 2312.48  4885.2 2309.82  4943.2 2310.92  4948.3 2308.07  4986.2 2307.93
  5027.8 2304.35  5028.3 2303.85  5047.5 2304.35  5049.7 2307.47  5110.1 2307.91
  5119.8 2311.39  5125.0 2309.78  5197.3 2313.53  5225.0 2318.39  5251.3 2319.30
  5263.0 2324.70  5278.6 2328.15  5300.0 2329.88  5315.6 2328.67  5439.8 2332.09
#Mann=7,-1,0
  4552.6   0.035       0  4595.6    0.07       0  4630.5    0.16       0
  4846.5    0.07       0  5027.8    0.07       0  5047.5    0.07       0
  5225.0   0.035       0
Bank Sta=5027.8,5047.5
Exp/Cntr=0.3,0.1

Type RM Length L Ch R = 1,42002,54,54,54
BEGIN DESCRIPTION:
Linn Creek 82.5
END DESCRIPTION:
XS GIS Cut Line= 3
      1309202.39      6899159.70      1309696.35      6899081.57
      1310041.77      6898954.63
#Sta/Elev= 30
  4498.0 2325.54  4538.5 2321.11  4543.5 2318.14  4551.3 2316.96  4601.4 2315.30
  4702.8 2313.34  4855.0 2311.42  4922.9 2308.78  4927.9 2306.93  4976.5 2305.45
  4984.9 2303.55  4985.4 2303.05  5004.9 2303.55  5023.1 2306.15  5060.6 2307.87
  5109.2 2307.57  5114.5 2309.74  5225.8 2316.53  5231.1 2315.02  5250.9 2316.62
  5256.3 2315.51  5281.4 2317.70  5286.8 2315.87  5305.6 2317.55  5311.9 2320.26
  5317.2 2317.84  5323.3 2319.06  5337.0 2320.53  5342.4 2317.90  5366.1 2321.81
#Mann=6,-1,0
  4498.0   0.035       0  4601.4    0.16       0  4702.8    0.07       0
  4984.9    0.07       0  5004.9    0.07       0  5323.3   0.035       0
Bank Sta=4984.9,5004.9
Exp/Cntr=0.3,0.1

Type RM Length L Ch R = 1,41948,500,500,500
BEGIN DESCRIPTION:
Linn Creek 82.0
END DESCRIPTION:
XS GIS Cut Line= 3
      1309555.03      6899237.98      1309735.97      6899119.10
      1310027.12      6898938.32
#Sta/Elev= 30
  4783.5 2324.05  4827.2 2318.96  4950.7 2309.81  4956.7 2308.55  4971.8 2309.47
  4977.8 2308.38  4986.4 2302.67  4986.9 2302.17  5006.4 2302.67  5009.9 2303.03
  5029.4 2304.77  5066.0 2304.71  5116.6 2306.83  5139.2 2310.67  5145.1 2312.67
  5166.4 2314.34  5175.4 2316.04  5187.6 2316.15  5197.1 2317.89  5203.0 2315.34
  5218.4 2318.36  5224.2 2315.86  5233.7 2316.62  5239.6 2315.51  5255.0 2316.52
  5260.9 2315.73  5276.2 2316.80  5289.0 2316.30  5312.8 2316.96  5342.7 2316.25
#Mann=5,-1,0
  4783.5   0.035       0  4986.4   0.035       0  5006.4   0.035       0
  5009.9    0.07       0  5289.0   0.035       0
Bank Sta=4986.4,5006.4
Exp/Cntr=0.3,0.1

Type RM Length L Ch R = 1,41448,500,500,500
BEGIN DESCRIPTION:
Linn Creek 81.0
END DESCRIPTION:
XS GIS Cut Line= 3
      1310155.00      6899488.01      1310198.60      6899238.09
      1310004.98      6898887.96
#Sta/Elev= 30
  4746.3 2329.02  4766.6 2326.94  4833.1 2316.82  4858.0 2314.08  4878.3 2312.51
  4892.6 2313.11  4908.7 2311.97  4939.2 2306.55  4947.1 2302.85  4952.2 2303.07
  4959.5 2301.55  4979.8 2300.14  4979.9 2299.39  4980.4 2298.89  4999.9 2299.39
  5000.0 2300.13  5017.5 2303.50  5152.7 2305.97  5267.2 2312.83  5289.0 2315.37
  5297.2 2317.14  5305.0 2320.15  5310.7 2319.61  5320.1 2321.81  5332.5 2317.17
  5342.8 2316.17  5370.3 2317.81  5377.2 2318.53  5386.3 2323.15  5400.1 2324.12
#Mann=4,-1,0
  4746.3   0.035       0  4979.9    0.07       0  4999.9   0.035       0
  5152.7   0.035       0
Bank Sta=4979.9,4999.9
Exp/Cntr=0.3,0.1

Type RM Length L Ch R = 1,40948,500,500,500
BEGIN DESCRIPTION:
Linn Creek 80.0
END DESCRIPTION:
XS GIS Cut Line= 3
      1310854.98      6899237.98      1310603.00      6898990.35
      1310105.03      6898638.02
#Sta/Elev= 30
  4646.7 2331.94  4674.9 2326.86  4745.6 2320.99  4766.9 2317.52  4786.7 2317.15
  4830.5 2310.30  4865.9 2307.60  4929.5 2295.65  4986.1 2292.63  4993.2 2293.91
  5004.2 2291.51  5004.7 2291.01  5024.4 2291.51  5071.0 2295.21  5079.6 2296.28
  5085.7 2299.58  5100.5 2300.94  5121.4 2301.83  5130.0 2300.44  5136.2 2302.18
  5165.7 2299.76  5272.8 2302.84  5293.7 2305.75  5338.1 2316.40  5400.8 2313.06
  5424.2 2314.09  5445.1 2318.55  5462.1 2319.27  5515.9 2322.60  5610.0 2329.59
#Mann=7,-1,0
  4646.7   0.035       0  4786.7    0.07       0  5004.2    0.07       0
  5024.4    0.07       0  5400.8   0.035       0  5462.1    0.07       0
  5515.9   0.035       0
Bank Sta=5004.2,5024.4
Exp/Cntr=0.3,0.1

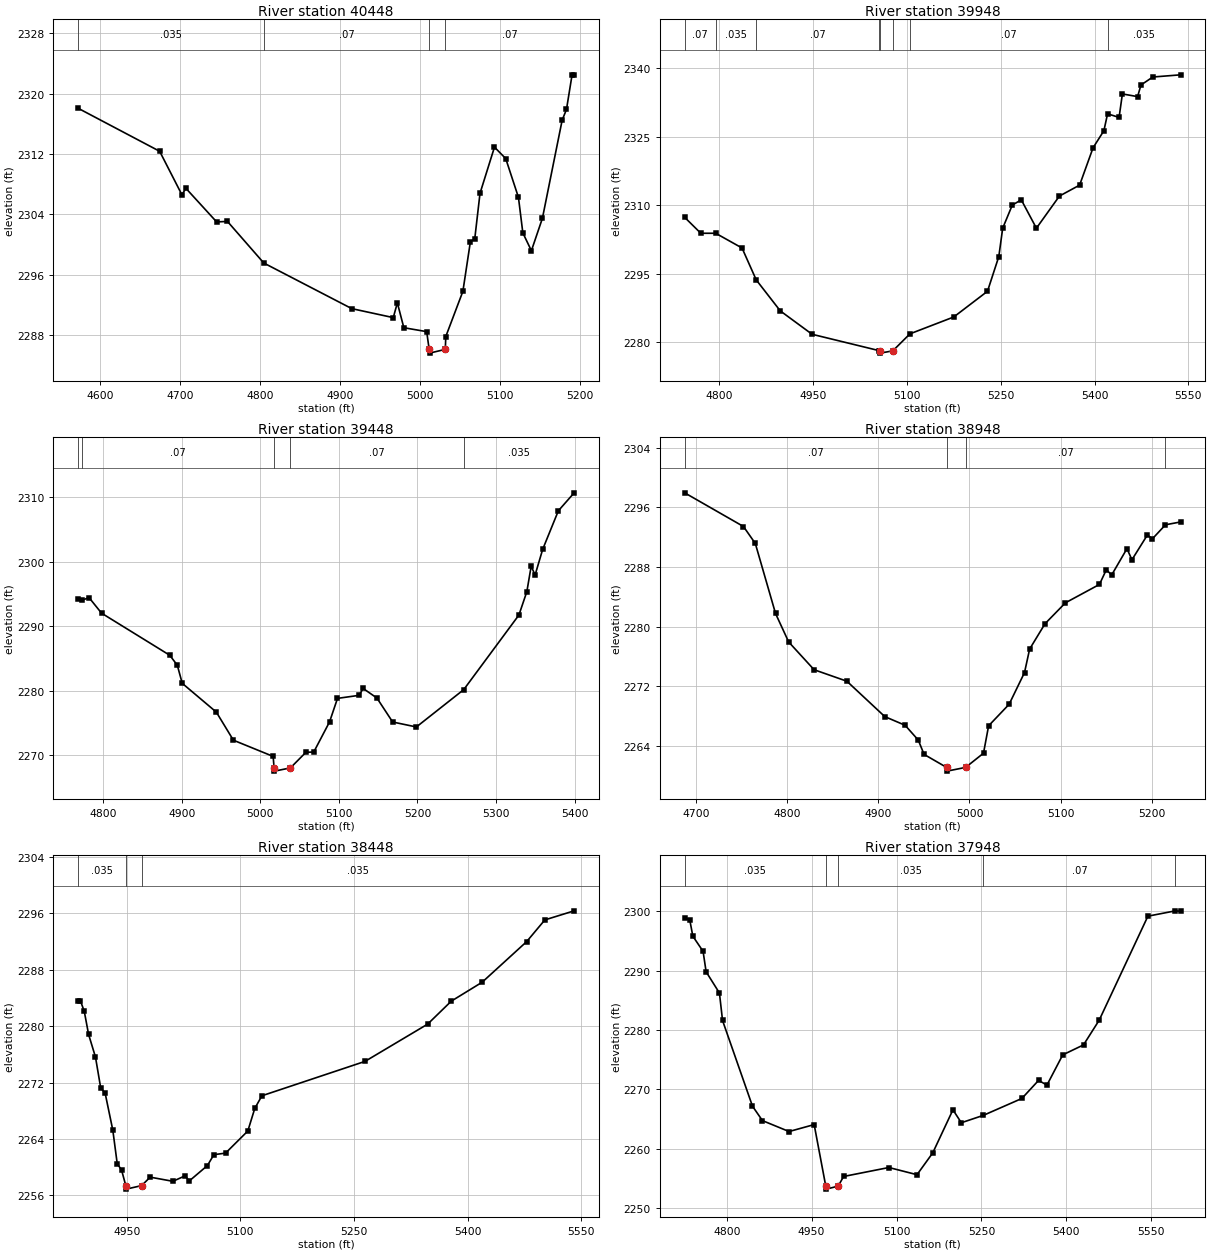
Type RM Length L Ch R = 1,40448,500,500,500
BEGIN DESCRIPTION:
Linn Creek 79.0
END DESCRIPTION:
XS GIS Cut Line= 3
      1311055.01      6899088.03      1310974.09      6898668.26
      1310905.02      6898488.04
#Sta/Elev= 30
  4572.5 2318.07  4674.4 2312.37  4702.2 2306.61  4707.3 2307.45  4745.7 2303.00
  4759.2 2303.07  4804.7 2297.55  4914.8 2291.50  4966.7 2290.31  4971.8 2292.27
  4979.9 2288.97  5008.5 2288.45  5011.6 2286.10  5012.1 2285.60  5031.8 2286.10
  5032.4 2287.80  5053.8 2293.80  5063.2 2300.40  5068.6 2300.72  5075.2 2306.79
  5093.3 2312.92  5107.4 2311.40  5123.3 2306.26  5128.8 2301.55  5139.5 2299.18
  5153.3 2303.49  5178.0 2316.50  5183.4 2317.92  5190.4 2322.51  5193.0 2322.51
#Mann=4,-1,0
  4572.5   0.035       0  4804.7    0.07       0  5011.6    0.07       0
  5031.8    0.07       0
Bank Sta=5011.6,5031.8
Exp/Cntr=0.3,0.1

Type RM Length L Ch R = 1,39948,500,500,500
BEGIN DESCRIPTION:
Linn Creek 78.0
END DESCRIPTION:
XS GIS Cut Line= 3
      1311354.99      6899038.04      1311403.97      6898787.28
      1311204.99      6898287.97
#Sta/Elev= 30
  4744.5 2307.33  4770.3 2303.84  4794.1 2303.84  4836.2 2300.61  4858.9 2293.61
  4897.4 2286.81  4948.3 2281.68  5055.0 2278.11  5056.6 2278.05  5057.1 2277.55
  5077.3 2278.05  5104.7 2281.78  5174.8 2285.48  5228.7 2291.12  5246.8 2298.74
  5253.0 2304.95  5268.3 2310.01  5282.7 2311.18  5306.9 2304.95  5343.7 2312.00
  5376.0 2314.40  5397.5 2322.59  5414.8 2326.33  5420.7 2330.04  5439.1 2329.25
  5444.4 2334.40  5468.7 2333.81  5474.1 2336.36  5493.0 2338.11  5537.5 2338.59
#Mann=8,-1,0
  4744.5    0.07       0  4794.1   0.035       0  4858.9    0.07       0
  5055.0   0.035       0  5056.6    0.07       0  5077.3   0.035       0
  5104.7    0.07       0  5420.7   0.035       0
Bank Sta=5056.6,5077.3
Exp/Cntr=0.3,0.1

Type RM Length L Ch R = 1,39448,500,500,500
BEGIN DESCRIPTION:
Linn Creek 77.0
END DESCRIPTION:
XS GIS Cut Line= 3
      1311604.99      6899138.01      1311807.17      6899024.83
      1312204.97      6898988.00
#Sta/Elev= 30
  4768.3 2294.21  4773.0 2293.99  4782.0 2294.43  4798.0 2292.01  4884.8 2285.49
  4894.4 2283.95  4900.7 2281.14  4944.1 2276.68  4965.8 2272.33  5016.4 2269.82
  5017.6 2268.04  5018.1 2267.54  5038.4 2268.04  5058.1 2270.46  5068.1 2270.50
  5088.2 2275.17  5098.3 2278.81  5125.8 2279.28  5130.9 2280.35  5148.5 2278.86
  5168.5 2275.15  5198.7 2274.38  5259.0 2280.17  5329.2 2291.72  5339.3 2295.35
  5344.8 2299.28  5349.8 2297.92  5359.4 2301.88  5379.4 2307.87  5399.5 2310.65
#Mann=5,-1,0
  4768.3   0.035       0  4773.0    0.07       0  5017.6    0.07       0
  5038.4    0.07       0  5259.0   0.035       0
Bank Sta=5017.6,5038.4
Exp/Cntr=0.3,0.1

Type RM Length L Ch R = 1,38948,500,500,500
BEGIN DESCRIPTION:
Linn Creek 76.0
END DESCRIPTION:
XS GIS Cut Line= 3
      1311905.03      6899637.96      1312102.73      6899395.95
      1312204.98      6899188.03
#Sta/Elev= 30
  4687.5 2297.93  4752.0 2293.42  4765.0 2291.15  4787.2 2281.77  4801.6 2277.96
  4829.5 2274.24  4865.5 2272.70  4907.1 2267.96  4929.4 2266.80  4943.8 2264.82
  4950.2 2262.90  4974.9 2261.16  4975.4 2260.66  4995.8 2261.16  5015.4 2263.06
  5021.0 2266.73  5043.5 2269.61  5060.4 2273.86  5066.0 2277.00  5082.9 2280.40
  5105.3 2283.20  5142.6 2285.66  5150.3 2287.66  5155.9 2286.90  5172.8 2290.45
  5178.3 2288.97  5195.2 2292.28  5200.8 2291.78  5215.1 2293.65  5231.7 2294.03
#Mann=4,-1,0
  4687.5    0.07       0  4974.9    0.07       0  4995.8    0.07       0
  5215.1   0.035       0
Bank Sta=4974.9,4995.8
Exp/Cntr=0.3,0.1

Type RM Length L Ch R = 1,38448,500,500,500
BEGIN DESCRIPTION:
Linn Creek 75.0
END DESCRIPTION:
XS GIS Cut Line= 3
      1312405.02      6899737.97      1312460.22      6899638.11
      1312254.99      6899137.98
#Sta/Elev= 30
  4885.9 2283.63  4888.7 2283.63  4893.9 2282.10  4899.6 2278.83  4908.7 2275.61
  4915.6 2271.23  4921.4 2270.51  4931.6 2265.22  4937.4 2260.48  4943.1 2259.59
  4948.7 2257.37  4949.2 2256.87  4969.6 2257.37  4980.9 2258.57  5010.9 2257.98
  5027.0 2258.76  5032.5 2258.03  5056.4 2260.21  5065.0 2261.76  5080.4 2261.98
  5109.8 2265.12  5119.0 2268.33  5128.4 2270.12  5264.5 2275.00  5347.2 2280.29
  5378.4 2283.55  5419.2 2286.24  5477.9 2292.00  5501.9 2295.08  5540.6 2296.37
#Mann=3,-1,0
  4885.9   0.035       0  4948.7   0.035       0  4969.6   0.035       0
Bank Sta=4948.7,4969.6
Exp/Cntr=0.3,0.1

Type RM Length L Ch R = 1,37948,500,500,500
BEGIN DESCRIPTION:
Linn Creek 74.0
END DESCRIPTION:
XS GIS Cut Line= 3
      1312954.99      6899637.98      1312846.13      6899386.20
      1312355.04      6899038.03
#Sta/Elev= 30
  4725.7 2298.90  4734.7 2298.55  4740.1 2295.81  4758.2 2293.26  4763.6 2289.81
  4787.1 2286.24  4792.6 2281.61  4845.5 2267.18  4863.1 2264.75  4910.1 2262.91
  4954.5 2264.08  4975.0 2253.71  4975.5 2253.21  4996.9 2253.71  5006.5 2255.34
  5086.5 2256.85  5136.2 2255.64  5164.0 2259.31  5199.7 2266.57  5214.5 2264.39
  5253.3 2265.63  5321.5 2268.48  5351.0 2271.52  5365.8 2270.73  5393.7 2275.82
  5430.4 2277.50  5458.1 2281.66  5544.2 2299.18  5592.9 2300.08  5602.0 2300.00
#Mann=5,-1,0
  4725.7   0.035       0  4975.0   0.035       0  4996.9   0.035       0
  5253.3    0.07       0  5592.9   0.035       0
Bank Sta=4975,4996.9
Exp/Cntr=0.3,0.1

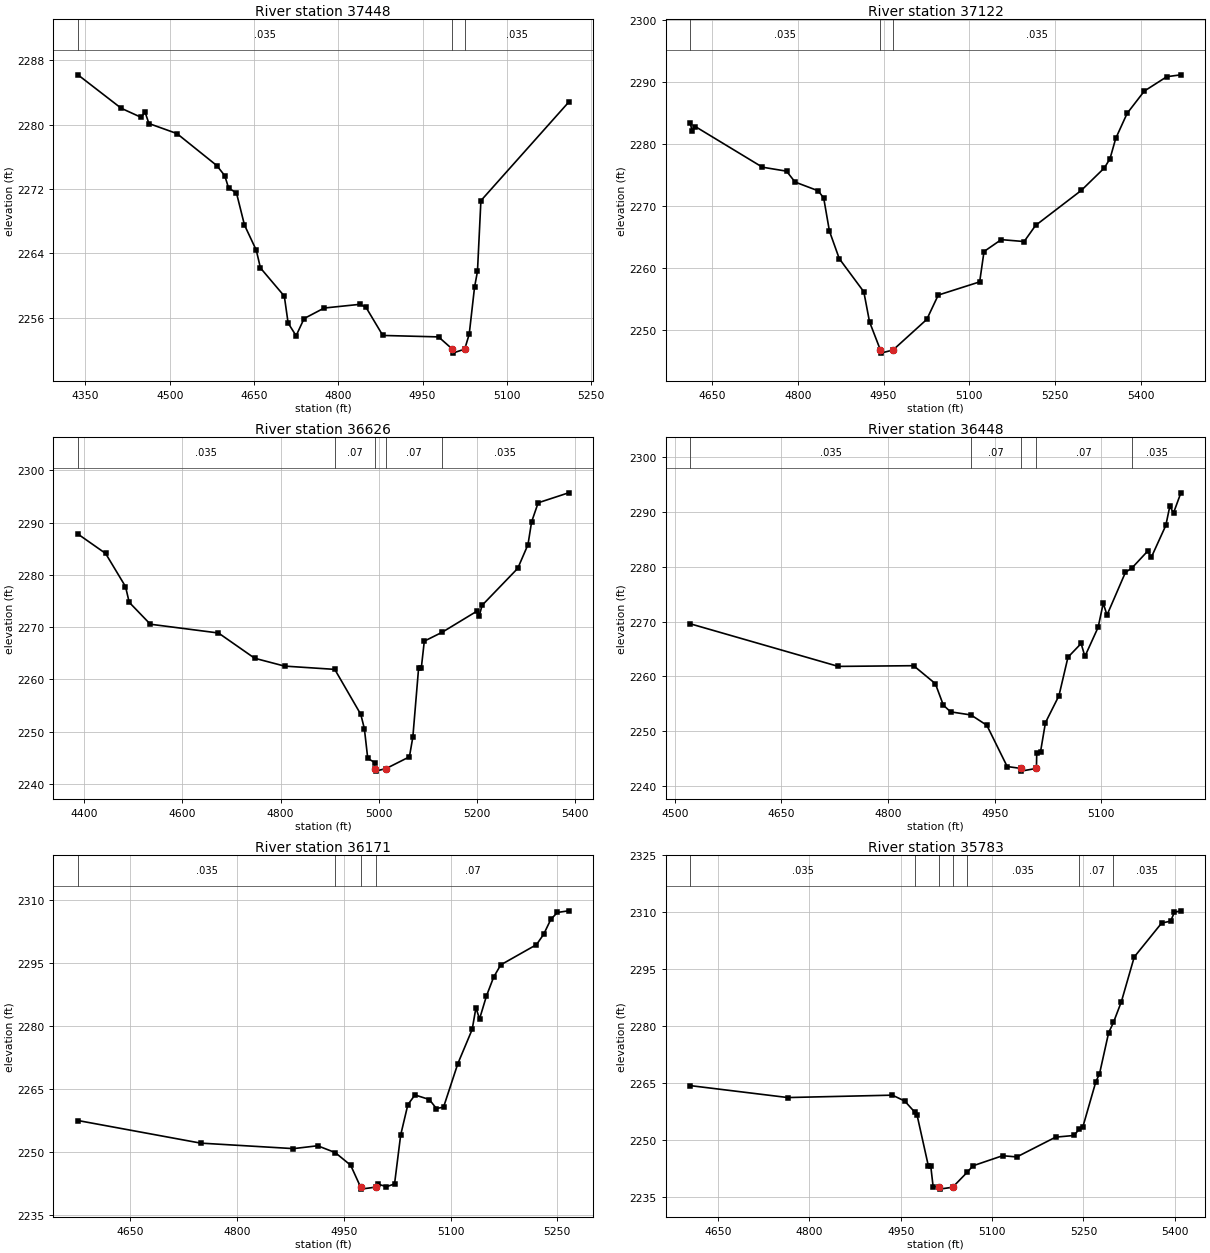
Type RM Length L Ch R = 1,37448,326,326,326
BEGIN DESCRIPTION:
Linn Creek 73.0
END DESCRIPTION:
XS GIS Cut Line= 4
      1313286.91      6899584.93      1312937.97      6899262.03
      1312862.93      6899089.67      1312805.01      6898888.03
#Sta/Elev= 30
  4336.6 2286.21  4413.6 2282.05  4448.8 2280.93  4456.1 2281.56  4462.9 2280.15
  4512.8 2278.90  4583.7 2274.92  4597.9 2273.66  4604.7 2272.13  4618.8 2271.50
  4633.0 2267.52  4654.0 2264.39  4661.4 2262.18  4703.9 2258.67  4710.7 2255.32
  4724.9 2253.74  4739.1 2255.88  4774.8 2257.19  4838.2 2257.65  4849.1 2257.30
  4879.2 2253.78  4978.4 2253.60  5003.0 2252.08  5003.5 2251.58  5025.0 2252.08
  5033.0 2253.94  5042.5 2259.79  5047.7 2261.76  5053.8 2270.55  5209.8 2282.79
#Mann=3,-1,0
  4336.6   0.035       0  5003.0   0.035       0  5025.0   0.035       0
Bank Sta=5003,5025
Exp/Cntr=0.3,0.1

Type RM Length L Ch R = 1,37122,496,496,496
BEGIN DESCRIPTION:
Linn Creek 72.0
END DESCRIPTION:
XS GIS Cut Line= 4
      1313273.06      6899543.31      1313148.04      6899355.78
      1313156.50      6899194.97      1313170.61      6898724.10
#Sta/Elev= 30
  4612.1 2283.36  4615.1 2282.21  4621.1 2282.84  4738.2 2276.29  4780.3 2275.65
  4795.3 2273.89  4835.7 2272.48  4845.3 2271.31  4855.3 2265.98  4872.5 2261.53
  4915.4 2256.18  4925.4 2251.33  4944.4 2246.78  4944.9 2246.28  4966.4 2246.78
  5025.5 2251.73  5045.5 2255.65  5117.9 2257.78  5125.5 2262.68  5155.6 2264.60
  5195.6 2264.29  5215.6 2266.89  5295.6 2272.55  5335.6 2276.15  5345.6 2277.63
  5355.7 2280.93  5375.7 2284.99  5405.7 2288.58  5445.0 2290.90  5469.6 2291.20
#Mann=3,-1,0
  4612.1   0.035       0  4944.4   0.035       0  4966.4   0.035       0
Bank Sta=4944.4,4966.4
Exp/Cntr=0.3,0.1

Type RM Length L Ch R = 1,36626,178,178,178
BEGIN DESCRIPTION:
Linn Creek 71.5
END DESCRIPTION:
XS GIS Cut Line= 5
      1313422.34      6899593.68      1313503.94      6899105.78
      1313418.87      6899015.50      1313363.32      6898961.68
      1313280.01      6898668.35
#Sta/Elev= 30
  4386.7 2287.82  4443.1 2284.11  4483.7 2277.77  4491.3 2274.75  4534.4 2270.55
  4673.4 2268.87  4747.3 2264.03  4808.2 2262.53  4910.7 2261.90  4963.8 2253.28
  4971.1 2250.55  4978.0 2244.85  4992.2 2244.06  4993.6 2242.91  4994.1 2242.41
  5015.6 2242.91  5063.0 2245.15  5070.0 2248.92  5081.8 2262.19  5087.3 2262.19
  5093.4 2267.31  5129.8 2269.01  5200.2 2273.02  5205.4 2272.11  5211.3 2274.17
  5284.1 2281.26  5304.9 2285.79  5312.3 2290.15  5325.7 2293.81  5387.7 2295.72
#Mann=5,-1,0
  4386.7   0.035       0  4910.7    0.07       0  4993.6    0.07       0
  5015.6    0.07       0  5129.8   0.035       0
Bank Sta=4993.6,5015.6
Exp/Cntr=0.3,0.1

Type RM Length L Ch R = 1,36448,277,277,277
BEGIN DESCRIPTION:
Linn Creek 71.0
END DESCRIPTION:
XS GIS Cut Line= 4
      1313489.03      6899394.66      1313601.26      6899072.12
      1313574.18      6898938.14      1313504.99      6898737.96
#Sta/Elev= 30
  4521.8 2269.59  4730.0 2261.80  4835.9 2261.93  4866.5 2258.64  4877.7 2254.72
  4887.9 2253.49  4916.6 2252.92  4938.9 2251.03  4967.5 2243.49  4986.5 2243.15
  4987.0 2242.65  5008.6 2243.15  5009.1 2246.03  5014.4 2246.19  5021.3 2251.51
  5040.3 2256.44  5053.0 2263.48  5071.5 2265.99  5076.8 2263.62  5095.4 2268.95
  5102.6 2273.34  5107.9 2271.19  5133.8 2278.99  5143.2 2279.83  5165.0 2282.87
  5170.3 2281.77  5190.6 2287.58  5196.2 2291.07  5201.5 2289.88  5211.8 2293.54
#Mann=5,-1,0
  4521.8   0.035       0  4916.6    0.07       0  4986.5    0.07       0
  5008.6    0.07       0  5143.2   0.035       0
Bank Sta=4986.5,5008.6
Exp/Cntr=0.3,0.1

Type RM Length L Ch R = 1,36171,388,388,388
BEGIN DESCRIPTION:
Linn Creek 70.5
END DESCRIPTION:
XS GIS Cut Line= 4
      1313816.26      6899359.57      1313844.10      6899024.26
      1313851.38      6898936.54      1313829.03      6898673.18
#Sta/Elev= 30
  4576.9 2257.56  4749.1 2252.19  4879.5 2250.88  4913.4 2251.56  4938.1 2249.94
  4959.8 2246.93  4973.7 2241.75  4974.2 2241.25  4995.8 2241.75  4998.2 2242.44
  5010.0 2241.83  5021.4 2242.48  5030.0 2254.11  5040.1 2261.34  5050.1 2263.64
  5070.2 2262.56  5080.2 2260.41  5090.2 2260.75  5110.3 2271.10  5130.4 2279.22
  5135.7 2284.40  5140.7 2281.69  5150.5 2287.20  5160.5 2291.64  5170.5 2294.57
  5220.7 2299.38  5230.8 2301.85  5240.8 2305.38  5250.0 2307.03  5265.7 2307.42
#Mann=4,-1,0
  4576.9   0.035       0  4938.1    0.07       0  4973.7    0.07       0
  4995.8    0.07       0
Bank Sta=4973.7,4995.8
Exp/Cntr=0.3,0.1

Type RM Length L Ch R = 1,35783,335,335,335
BEGIN DESCRIPTION:
Linn Creek 70.0
END DESCRIPTION:
XS GIS Cut Line= 3
      1314258.43      6899426.63      1314202.56      6899035.50
      1313974.32      6898693.94
#Sta/Elev= 30
  4604.2 2264.36  4764.4 2261.22  4936.2 2261.85  4956.4 2260.31  4973.3 2257.31
  4976.6 2256.69  4995.5 2243.06  4999.3 2243.06  5003.1 2237.76  5013.1 2237.60
  5013.6 2237.10  5035.2 2237.60  5059.3 2241.58  5068.5 2243.24  5117.2 2245.90
  5140.6 2245.58  5204.3 2250.79  5234.4 2251.23  5243.4 2252.95  5248.9 2253.40
  5270.4 2265.39  5276.4 2267.45  5291.4 2278.29  5299.3 2280.99  5312.4 2286.50
  5333.5 2298.25  5378.5 2307.18  5393.2 2307.68  5399.5 2310.04  5410.1 2310.40
#Mann=7,-1,0
  4604.2   0.035       0  4973.3    0.07       0  5013.1    0.07       0
  5035.2    0.07       0  5059.3   0.035       0  5243.4    0.07       0
  5299.3   0.035       0
Bank Sta=5013.1,5035.2
Exp/Cntr=0.3,0.1

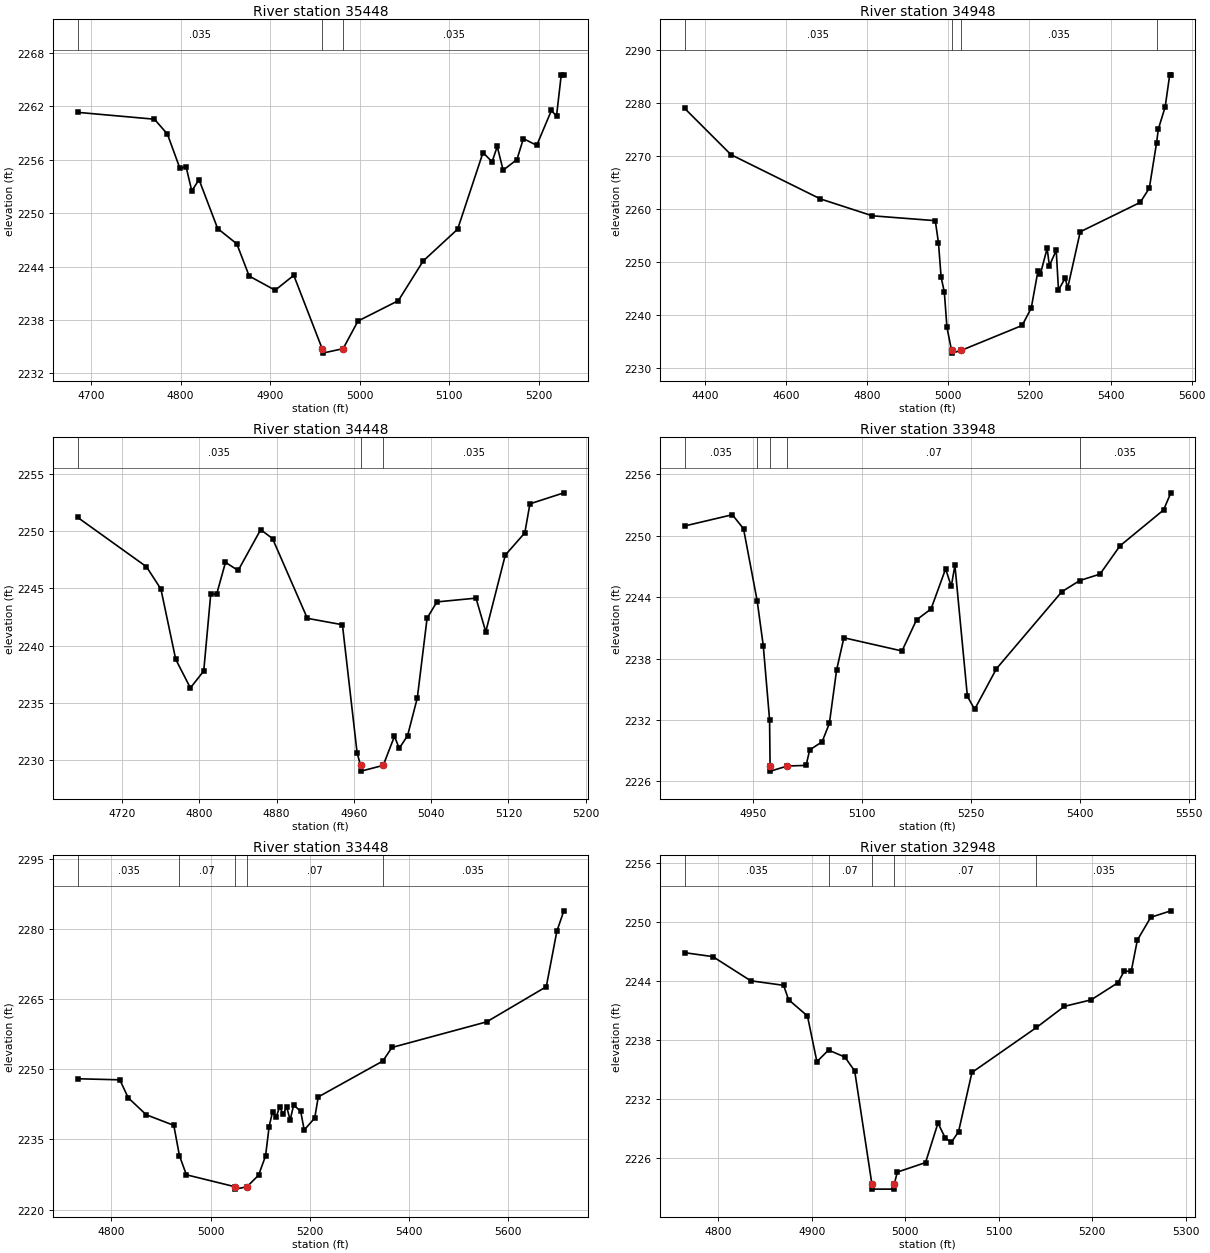
Type RM Length L Ch R = 1,35448,500,500,500
BEGIN DESCRIPTION:
Linn Creek 69.0
END DESCRIPTION:
XS GIS Cut Line= 3
      1314305.03      6899187.96      1314499.30      6898939.88
      1314605.01      6898737.98
#Sta/Elev= 30
  4684.9 2261.30  4770.7 2260.53  4785.2 2258.86  4799.2 2255.00  4806.0 2255.21
  4812.4 2252.48  4820.5 2253.75  4841.3 2248.26  4862.7 2246.54  4876.5 2242.93
  4905.5 2241.34  4926.3 2243.01  4958.0 2234.78  4958.5 2234.28  4981.4 2234.78
  4998.0 2237.88  5043.1 2240.17  5070.8 2244.62  5109.3 2248.19  5137.6 2256.78
  5147.8 2255.75  5153.5 2257.47  5160.1 2254.81  5175.5 2256.00  5182.7 2258.35
  5197.6 2257.60  5214.0 2261.51  5219.7 2260.88  5225.0 2265.51  5227.9 2265.51
#Mann=3,-1,0
  4684.9   0.035       0  4958.0   0.035       0  4981.4   0.035       0
Bank Sta=4958,4981.4
Exp/Cntr=0.3,0.1

Type RM Length L Ch R = 1,34948,500,500,500
BEGIN DESCRIPTION:
Linn Creek 68.0
END DESCRIPTION:
XS GIS Cut Line= 3
      1314255.02      6899737.98      1314760.39      6899329.20
      1315004.98      6898838.03
#Sta/Elev= 30
  4350.0 2279.01  4464.3 2270.26  4684.4 2261.91  4812.8 2258.71  4968.0 2257.79
  4975.9 2253.56  4982.3 2247.14  4990.3 2244.30  4996.7 2237.64  5008.1 2233.27
  5008.6 2232.77  5031.5 2233.27  5182.1 2238.00  5204.5 2241.27  5221.3 2248.37
  5226.9 2247.65  5243.7 2252.56  5249.3 2249.28  5266.1 2252.19  5271.7 2244.70
  5288.5 2246.96  5294.1 2244.98  5325.3 2255.69  5473.2 2261.24  5495.6 2263.93
  5513.5 2272.49  5517.9 2275.11  5534.7 2279.28  5545.9 2285.34  5548.7 2285.34
#Mann=4,-1,0
  4350.0   0.035       0  5008.1   0.035       0  5031.5   0.035       0
  5513.5    0.07       0
Bank Sta=5008.1,5031.5
Exp/Cntr=0.3,0.1

Type RM Length L Ch R = 1,34448,500,500,500
BEGIN DESCRIPTION:
Linn Creek 67.0
END DESCRIPTION:
XS GIS Cut Line= 3
      1315005.02      6899637.97      1315180.50      6899363.46
      1315155.00      6899188.01
#Sta/Elev= 30
  4674.2 2251.19  4745.4 2246.89  4760.4 2244.94  4775.7 2238.82  4790.9 2236.32
  4804.7 2237.80  4812.0 2244.54  4818.0 2244.47  4827.2 2247.27  4840.3 2246.56
  4863.6 2250.12  4875.9 2249.34  4911.9 2242.39  4948.2 2241.83  4963.4 2230.65
  4967.0 2229.57  4967.5 2229.07  4990.4 2229.57  5002.0 2232.10  5007.0 2231.06
  5015.6 2232.16  5025.7 2235.46  5035.8 2242.40  5045.9 2243.82  5086.4 2244.15
  5096.5 2241.22  5116.7 2247.90  5136.9 2249.84  5142.2 2252.37  5177.3 2253.33
#Mann=3,-1,0
  4674.2   0.035       0  4967.0   0.035       0  4990.4   0.035       0
Bank Sta=4967,4990.4
Exp/Cntr=0.3,0.1

Type RM Length L Ch R = 1,33948,500,500,500
BEGIN DESCRIPTION:
Linn Creek 66.0
END DESCRIPTION:
XS GIS Cut Line= 3
      1315704.97      6899637.98      1315581.28      6899562.50
      1315555.00      6899037.96
#Sta/Elev= 30
  4855.1 2250.95  4920.9 2252.05  4936.3 2250.68  4955.1 2243.64  4963.5 2239.26
  4972.2 2232.02  4972.9 2227.50  4973.4 2227.00  4996.7 2227.50  5022.5 2227.56
  5027.5 2229.07  5044.6 2229.87  5054.6 2231.66  5064.6 2236.89  5074.6 2240.03
  5154.7 2238.74  5174.7 2241.78  5194.7 2242.84  5214.8 2246.76  5222.6 2245.05
  5227.6 2247.11  5244.8 2234.31  5254.8 2233.04  5284.9 2237.01  5375.0 2244.53
  5399.7 2245.62  5427.6 2246.25  5455.1 2249.01  5515.1 2252.51  5525.2 2254.19
#Mann=5,-1,0
  4855.1   0.035       0  4955.1    0.07       0  4972.9    0.07       0
  4996.7    0.07       0  5399.7   0.035       0
Bank Sta=4972.9,4996.7
Exp/Cntr=0.3,0.1

Type RM Length L Ch R = 1,33448,500,500,500
BEGIN DESCRIPTION:
Linn Creek 65.0
END DESCRIPTION:
XS GIS Cut Line= 3
      1315955.01      6899538.04      1315863.71      6899285.86
      1315355.00      6898788.00
#Sta/Elev= 30
  4731.8 2247.98  4816.9 2247.75  4833.8 2243.91  4870.1 2240.28  4925.7 2238.01
  4937.0 2231.54  4951.0 2227.44  5049.3 2224.87  5049.8 2224.37  5073.1 2224.87
  5096.5 2227.35  5110.6 2231.46  5117.8 2237.75  5124.8 2240.97  5131.9 2239.72
  5138.9 2241.98  5146.1 2240.38  5153.1 2242.01  5160.2 2239.13  5167.2 2242.37
  5181.4 2241.01  5188.5 2237.02  5209.7 2239.58  5216.8 2244.09  5347.0 2251.77
  5365.3 2254.67  5556.3 2260.15  5676.4 2267.67  5697.7 2279.53  5711.8 2283.90
#Mann=5,-1,0
  4731.8   0.035       0  4937.0    0.07       0  5049.3    0.07       0
  5073.1    0.07       0  5347.0   0.035       0
Bank Sta=5049.3,5073.1
Exp/Cntr=0.3,0.1

Type RM Length L Ch R = 1,32948,500,500,500
BEGIN DESCRIPTION:
Linn Creek 64.0
END DESCRIPTION:
XS GIS Cut Line= 3
      1316255.00      6899437.98      1316288.51      6899204.57
      1316104.98      6898987.97
#Sta/Elev= 30
  4764.2 2246.90  4794.4 2246.50  4834.9 2244.04  4870.0 2243.58  4875.3 2242.12
  4895.5 2240.46  4905.6 2235.81  4918.0 2236.99  4935.5 2236.28  4946.0 2234.86
  4964.4 2223.34  4964.9 2222.84  4987.8 2222.84  4988.3 2223.34  4991.5 2224.57
  5021.7 2225.54  5035.0 2229.56  5042.7 2228.06  5049.3 2227.60  5057.0 2228.69
  5071.3 2234.71  5140.3 2239.29  5170.1 2241.44  5198.7 2242.10  5227.3 2243.84
  5233.9 2245.00  5241.6 2245.03  5248.1 2248.18  5262.4 2250.50  5283.9 2251.16
#Mann=5,-1,0
  4764.2   0.035       0  4918.0    0.07       0  4964.4    0.07       0
  4988.3    0.07       0  5140.3   0.035       0
Bank Sta=4964.4,4988.3
Exp/Cntr=0.3,0.1