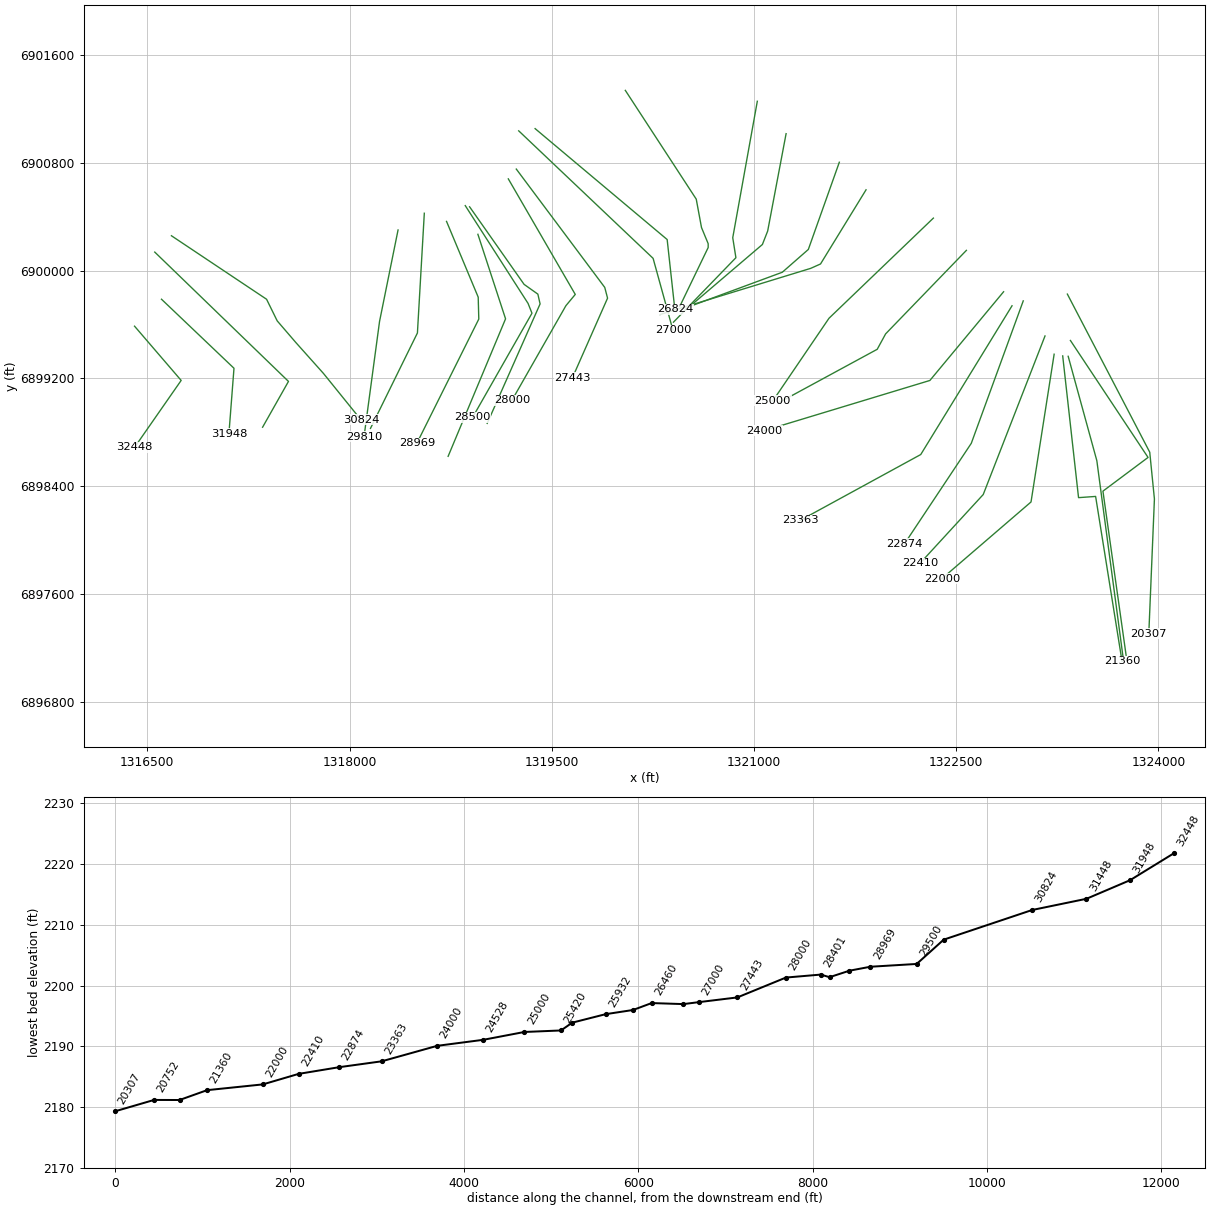
HEC-RAS study Linn Creek.prj: Linn Creek Base Level Engineering

--- Linn Creek.g01 (geometry) --- (continued)

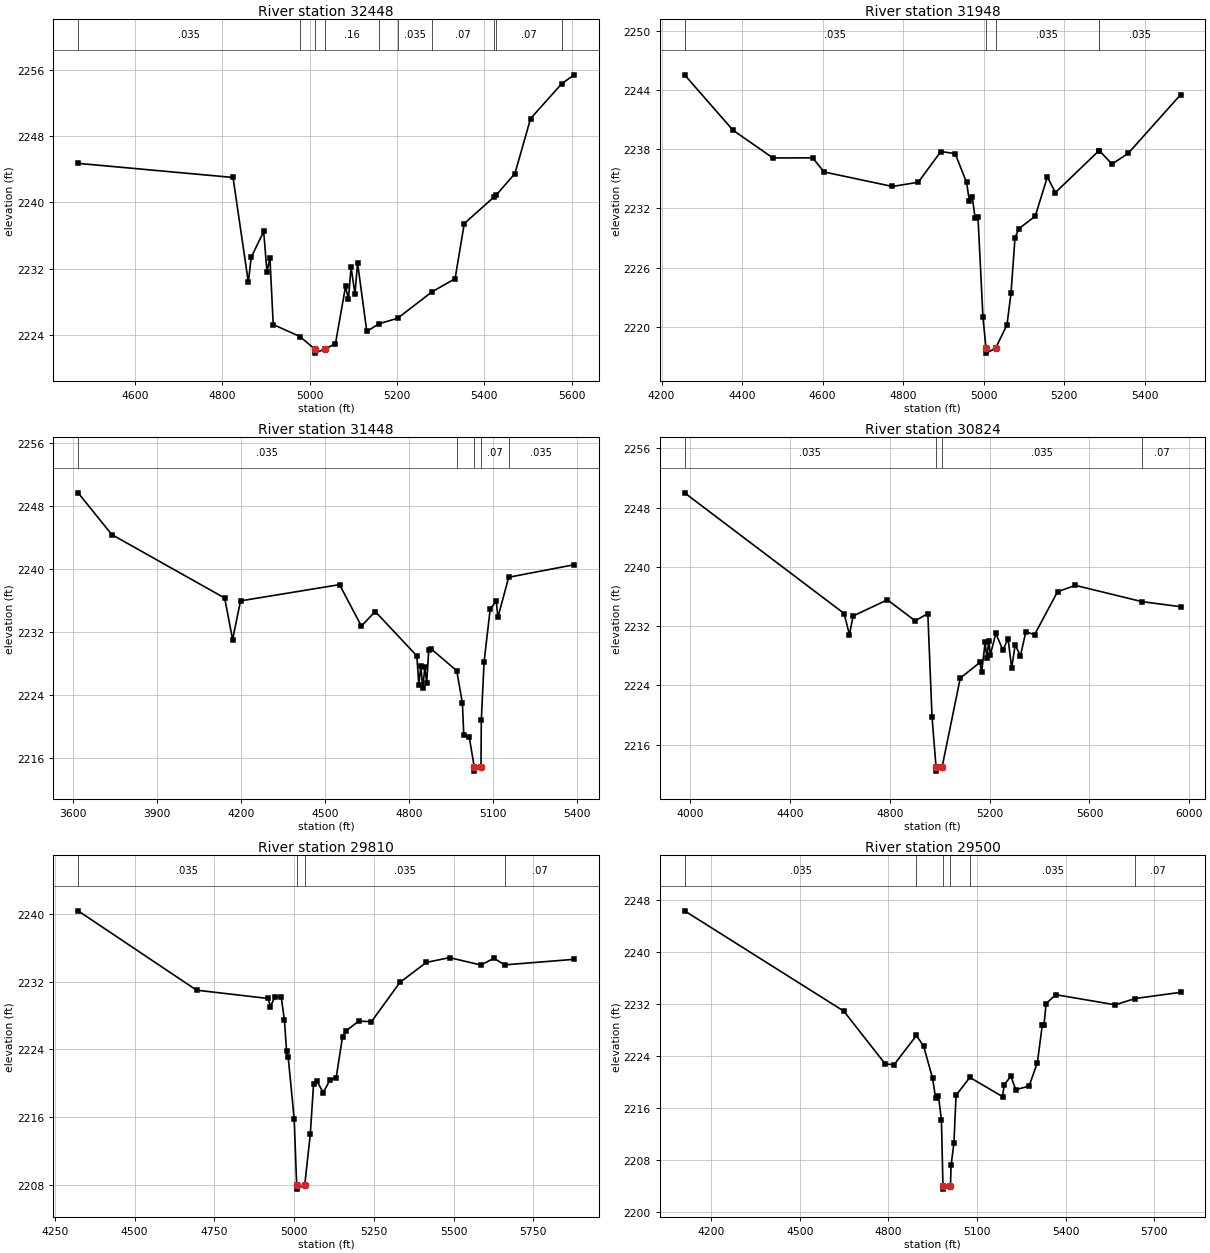
Type RM Length L Ch R = 1,32448,500,500,500
BEGIN DESCRIPTION:
Linn Creek 63.0
END DESCRIPTION:
XS GIS Cut Line= 3
      1316405.02      6899587.97      1316750.90      6899185.33
      1316405.00      6898687.99
#Sta/Elev= 30
  4469.2 2244.74  4824.2 2243.03  4859.3 2230.35  4865.9 2233.37  4894.4 2236.49
  4902.1 2231.55  4908.7 2233.33  4916.3 2225.22  4977.5 2223.77  5011.2 2222.26
  5011.7 2221.76  5035.1 2222.26  5058.9 2222.91  5082.0 2229.83  5088.6 2228.29
  5094.7 2232.16  5103.5 2228.94  5109.6 2232.67  5130.7 2224.39  5158.6 2225.31
  5201.5 2225.99  5280.3 2229.19  5333.0 2230.77  5354.0 2237.45  5422.7 2240.69
  5427.0 2240.89  5470.1 2243.50  5505.9 2250.16  5577.3 2254.38  5605.8 2255.46
#Mann=10,-1,0
  4469.2   0.035       0  4977.5    0.16       0  5011.2    0.07       0
  5035.1    0.16       0  5158.6    0.07       0  5201.5   0.035       0
  5280.3    0.07       0  5422.7   0.035       0  5427.0    0.07       0
  5577.3   0.035       0
Bank Sta=5011.2,5035.1
Exp/Cntr=0.3,0.1

Type RM Length L Ch R = 1,31948,500,500,500
BEGIN DESCRIPTION:
Linn Creek 62.0
END DESCRIPTION:
XS GIS Cut Line= 3
      1316604.98      6899788.02      1317142.76      6899275.49
      1317105.00      6898788.05
#Sta/Elev= 30
  4257.1 2245.54  4377.4 2239.93  4476.5 2237.12  4575.3 2237.13  4603.6 2235.70
  4773.4 2234.23  4837.3 2234.66  4893.6 2237.77  4929.1 2237.56  4957.4 2234.64
  4964.3 2232.78  4971.6 2233.14  4978.5 2231.07  4985.7 2231.16  4998.1 2220.97
  5005.6 2217.85  5006.1 2217.35  5029.5 2217.85  5057.7 2220.21  5067.7 2223.40
  5077.7 2229.05  5087.7 2229.97  5127.9 2231.22  5158.0 2235.19  5178.0 2233.62
  5286.6 2237.87  5287.0 2237.87  5318.4 2236.50  5358.6 2237.58  5488.9 2243.53
#Mann=5,-1,0
  4257.1   0.035       0  5005.6   0.035       0  5029.5   0.035       0
  5286.6    0.07       0  5287.0   0.035       0
Bank Sta=5005.6,5029.5
Exp/Cntr=0.3,0.1

Type RM Length L Ch R = 1,31448,624,624,624
BEGIN DESCRIPTION:
Linn Creek 61.0
END DESCRIPTION:
XS GIS Cut Line= 3
      1316555.01      6900137.99      1317546.99      6899177.92
      1317355.00      6898837.99
#Sta/Elev= 30
  3619.5 2249.63  3739.7 2244.33  4142.8 2236.27  4171.1 2231.00  4199.4 2235.91
  4552.9 2237.97  4630.8 2232.71  4680.2 2234.56  4828.9 2228.92  4835.9 2225.25
  4843.0 2227.63  4850.0 2224.79  4857.2 2227.48  4864.1 2225.52  4871.3 2229.69
  4878.3 2229.86  4971.2 2227.04  4991.5 2222.92  4996.3 2218.88  5015.7 2218.67
  5033.9 2214.79  5034.4 2214.29  5057.8 2214.79  5059.0 2220.76  5068.8 2228.14
  5090.8 2234.91  5112.4 2235.86  5118.2 2233.82  5156.8 2238.91  5390.4 2240.50
#Mann=5,-1,0
  3619.5   0.035       0  4971.2    0.07       0  5033.9    0.07       0
  5057.8    0.07       0  5156.8   0.035       0
Bank Sta=5033.9,5057.8
Exp/Cntr=0.3,0.1

Type RM Length L Ch R = 1,30824,1014,1014,1014
BEGIN DESCRIPTION:
Linn Creek 60.0
END DESCRIPTION:
XS GIS Cut Line= 6
      1316678.74      6900259.22      1317384.48      6899787.86
      1317463.25      6899627.49      1317602.19      6899465.99
      1317806.70      6899236.93      1318084.47      6898893.19
#Sta/Elev= 30
  3976.2 2250.00  4616.3 2233.71  4637.3 2230.85  4652.4 2233.38  4789.4 2235.56
  4901.3 2232.72  4951.8 2233.71  4968.7 2219.74  4984.8 2212.94  4985.3 2212.44
  5008.7 2212.94  5082.0 2225.00  5160.9 2227.11  5167.5 2225.79  5181.8 2229.85
  5188.4 2227.66  5196.0 2229.99  5202.6 2228.14  5224.5 2231.02  5252.9 2228.77
  5273.8 2230.31  5288.0 2226.34  5302.2 2229.49  5323.1 2227.99  5344.8 2231.24
  5380.0 2230.86  5471.9 2236.65  5543.2 2237.51  5811.4 2235.31  5965.6 2234.63
#Mann=4,-1,0
  3976.2   0.035       0  4984.8   0.035       0  5008.7   0.035       0
  5811.4    0.07       0
Bank Sta=4984.8,5008.7
Exp/Cntr=0.3,0.1

Type RM Length L Ch R = 1,29810,310,310,310
BEGIN DESCRIPTION:
Linn Creek 59.0
END DESCRIPTION:
XS GIS Cut Line= 3
      1318359.86      6900302.08      1318222.62      6899623.45
      1318107.61      6898768.42
#Sta/Elev= 30
  4323.0 2240.32  4694.4 2230.98  4918.9 2230.00  4925.9 2229.05  4939.3 2230.13
  4959.7 2230.21  4969.9 2227.44  4976.6 2223.77  4981.7 2223.09  5000.5 2215.78
  5008.2 2208.06  5008.7 2207.56  5033.6 2208.06  5051.1 2214.09  5061.2 2219.94
  5071.3 2220.30  5091.5 2218.93  5113.4 2220.46  5131.9 2220.64  5152.0 2225.51
  5162.1 2226.16  5202.5 2227.33  5242.8 2227.28  5331.8 2231.89  5414.8 2234.25
  5487.6 2234.81  5585.9 2233.94  5626.3 2234.73  5660.6 2233.96  5878.1 2234.61
#Mann=4,-1,0
  4323.0   0.035       0  5008.2   0.035       0  5033.6   0.035       0
  5660.6    0.07       0
Bank Sta=5008.2,5033.6
Exp/Cntr=0.3,0.1

Type RM Length L Ch R = 1,29500,531,531,531
BEGIN DESCRIPTION:
Linn Creek 58.0
END DESCRIPTION:
XS GIS Cut Line= 3
      1318554.66      6900426.41      1318503.53      6899537.58
      1318155.37      6898829.22
#Sta/Elev= 30
  4109.7 2246.38  4649.0 2230.94  4789.2 2222.81  4819.3 2222.72  4894.9 2227.20
  4919.5 2225.52  4949.5 2220.60  4959.5 2217.63  4969.5 2217.92  4979.5 2214.12
  4984.6 2204.06  4985.1 2203.56  5010.0 2204.06  5012.1 2207.21  5021.8 2210.69
  5029.0 2218.00  5075.7 2220.75  5186.4 2217.79  5192.0 2219.59  5214.4 2220.94
  5231.3 2218.85  5276.3 2219.42  5304.3 2223.03  5321.2 2228.88  5326.8 2228.84
  5333.8 2232.09  5366.2 2233.48  5567.8 2231.92  5635.7 2232.89  5789.3 2233.84
#Mann=6,-1,0
  4109.7   0.035       0  4894.9    0.07       0  4984.6    0.07       0
  5010.0    0.07       0  5075.7   0.035       0  5635.7    0.07       0
Bank Sta=4984.6,5010
Exp/Cntr=0.3,0.1

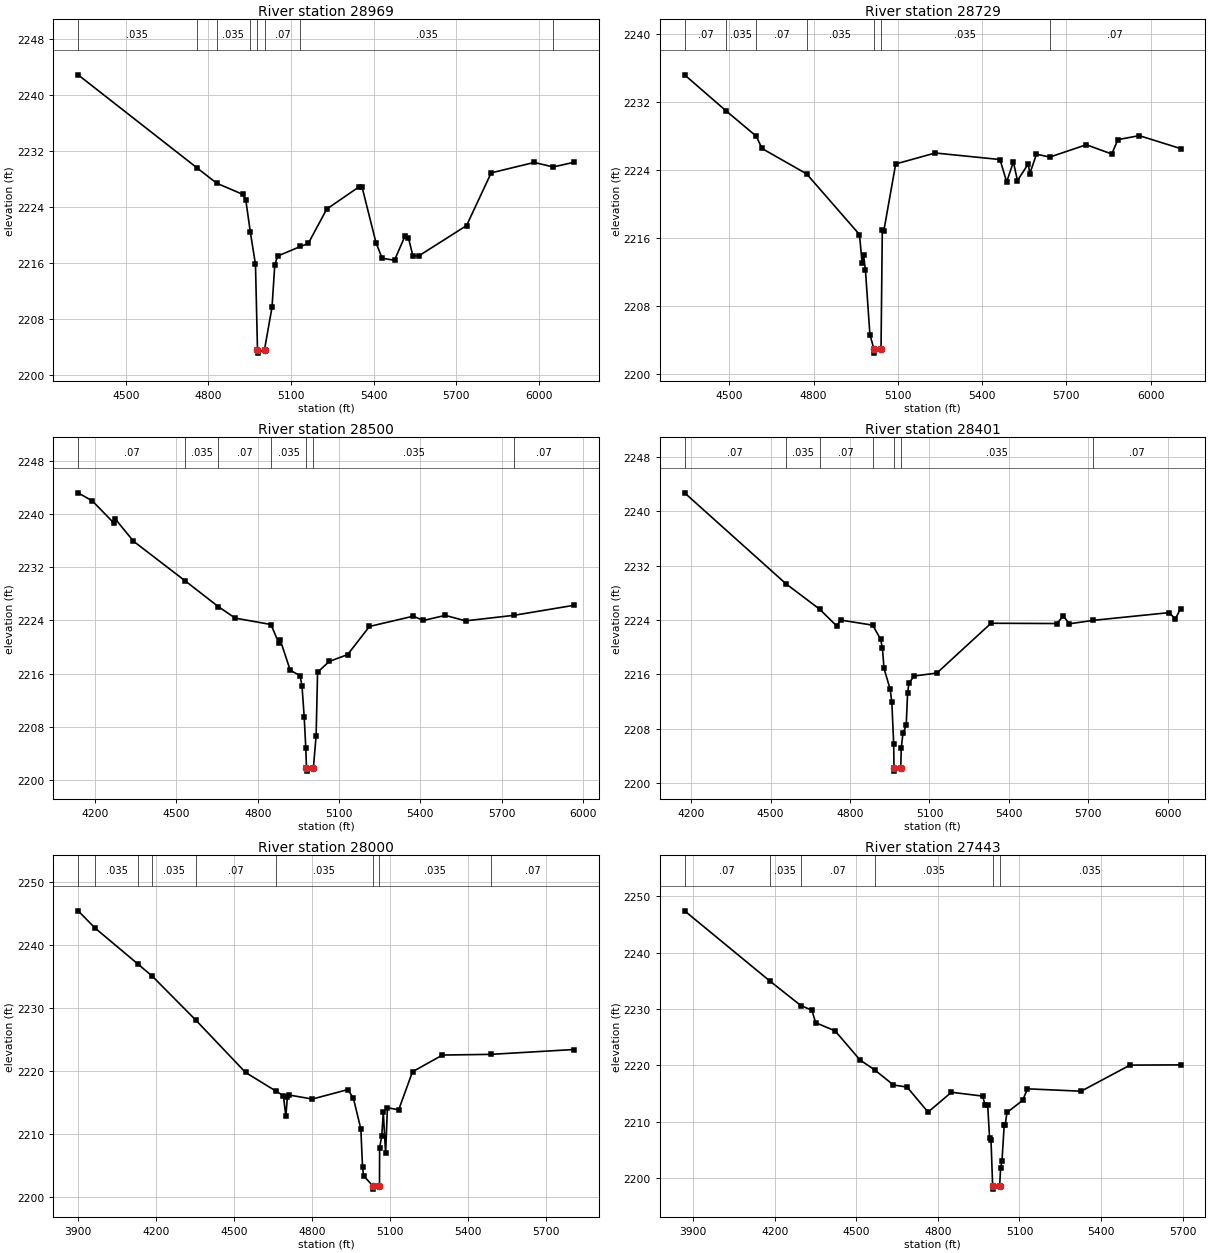
Type RM Length L Ch R = 1,28969,240,240,240
BEGIN DESCRIPTION:
Linn Creek 57.0
END DESCRIPTION:
XS GIS Cut Line= 4
      1318719.58      6900365.64      1318954.47      6899803.38
      1318958.81      6899640.62      1318499.11      6898718.09
#Sta/Elev= 30
  4326.1 2242.94  4757.1 2229.66  4829.5 2227.43  4924.4 2225.83  4935.5 2225.06
  4951.8 2220.50  4970.8 2215.80  4978.1 2203.60  4978.6 2203.10  5003.6 2203.60
  5030.9 2209.66  5040.9 2215.69  5050.9 2216.99  5134.4 2218.37  5162.8 2218.81
  5229.9 2223.72  5347.4 2226.91  5358.2 2226.87  5409.0 2218.88  5431.4 2216.67
  5476.1 2216.40  5514.6 2219.89  5526.5 2219.63  5543.3 2216.96  5565.7 2217.05
  5738.0 2221.36  5827.4 2228.90  5983.9 2230.40  6052.5 2229.75  6129.0 2230.42
#Mann=8,-1,0
  4326.1   0.035       0  4757.1    0.07       0  4829.5   0.035       0
  4951.8    0.07       0  4978.1    0.07       0  5003.6    0.07       0
  5134.4   0.035       0  6052.5    0.07       0
Bank Sta=4978.1,5003.6
Exp/Cntr=0.3,0.1

Type RM Length L Ch R = 1,28729,229,229,229
BEGIN DESCRIPTION:
Linn Creek 56.5
END DESCRIPTION:
XS GIS Cut Line= 3
      1318952.19      6900269.96      1319157.39      6899642.51
      1318731.33      6898621.82
#Sta/Elev= 30
  4340.7 2235.17  4489.0 2230.92  4596.2 2227.95  4616.3 2226.51  4775.1 2223.53
  4963.5 2216.39  4972.9 2213.03  4978.2 2213.94  4984.6 2212.25  5000.6 2204.64
  5014.7 2202.95  5015.2 2202.45  5040.2 2202.95  5044.8 2216.95  5050.3 2216.85
  5092.4 2224.69  5233.3 2225.98  5463.8 2225.21  5487.6 2222.58  5511.5 2224.93
  5525.9 2222.74  5564.5 2224.70  5569.9 2223.54  5593.7 2225.84  5641.1 2225.50
  5771.3 2226.95  5861.8 2225.86  5883.5 2227.55  5959.7 2228.02  6106.9 2226.50
#Mann=7,-1,0
  4340.7    0.07       0  4489.0   0.035       0  4596.2    0.07       0
  4775.1   0.035       0  5014.7   0.035       0  5040.2   0.035       0
  5641.1    0.07       0
Bank Sta=5014.7,5040.2
Exp/Cntr=0.3,0.1

Type RM Length L Ch R = 1,28500,99,99,99
BEGIN DESCRIPTION:
Linn Creek 56.0
END DESCRIPTION:
XS GIS Cut Line= 4
      1318858.47      6900482.83      1319324.22      6899757.13
      1319353.27      6899684.21      1318913.66      6898912.19
#Sta/Elev= 30
  4137.7 2243.16  4190.6 2241.93  4269.2 2238.64  4275.1 2239.22  4341.8 2235.90
  4533.2 2229.92  4654.4 2226.09  4717.1 2224.35  4849.0 2223.39  4877.7 2220.60
  4883.6 2221.01  4919.9 2216.53  4956.3 2215.71  4963.3 2214.18  4971.5 2209.50
  4977.4 2204.79  4979.9 2201.88  4980.4 2201.38  5005.4 2201.88  5015.4 2206.69
  5020.8 2216.22  5063.6 2217.84  5131.7 2218.88  5212.2 2223.10  5373.6 2224.64
  5411.0 2224.00  5491.7 2224.76  5566.7 2223.94  5744.7 2224.77  5966.9 2226.28
#Mann=7,-1,0
  4137.7    0.07       0  4533.2   0.035       0  4654.4    0.07       0
  4849.0   0.035       0  4979.9   0.035       0  5005.4   0.035       0
  5744.7    0.07       0
Bank Sta=4979.9,5005.4
Exp/Cntr=0.3,0.1

Type RM Length L Ch R = 1,28401,401,401,401
BEGIN DESCRIPTION:
Linn Creek 55.5
END DESCRIPTION:
XS GIS Cut Line= 5
      1318890.59      6900474.11      1319294.76      6899898.38
      1319397.04      6899825.79      1319413.54      6899753.20
      1319021.18      6898866.43
#Sta/Elev= 30
  4175.2 2242.67  4557.9 2229.32  4684.8 2225.60  4749.7 2223.12  4764.5 2223.99
  4885.6 2223.24  4915.7 2221.15  4922.2 2219.87  4928.3 2216.88  4951.7 2213.82
  4957.8 2211.89  4964.8 2205.86  4966.0 2202.31  4966.5 2201.81  4991.5 2202.31
  4993.5 2205.24  4999.7 2207.34  5012.1 2208.53  5017.3 2213.26  5022.4 2214.76
  5042.8 2215.78  5127.9 2216.21  5332.3 2223.52  5581.6 2223.48  5604.9 2224.61
  5628.2 2223.44  5719.1 2223.95  6004.9 2225.08  6028.2 2224.15  6048.2 2225.68
#Mann=7,-1,0
  4175.2    0.07       0  4557.9   0.035       0  4684.8    0.07       0
  4885.6   0.035       0  4966.0   0.035       0  4991.5   0.035       0
  5719.1    0.07       0
Bank Sta=4966,4991.5
Exp/Cntr=0.3,0.1

Type RM Length L Ch R = 1,28000,557,557,557
BEGIN DESCRIPTION:
Linn Creek 55.0
END DESCRIPTION:
XS GIS Cut Line= 4
      1319177.90      6900681.35      1319674.45      6899823.68
      1319605.02      6899739.96      1319205.02      6899038.03
#Sta/Elev= 30
  3900.2 2245.47  3966.7 2242.69  4129.4 2237.06  4186.2 2235.07  4351.8 2228.18
  4544.2 2219.83  4661.4 2216.86  4689.8 2216.15  4699.2 2212.85  4704.9 2215.89
  4712.9 2216.24  4801.1 2215.61  4937.6 2217.11  4959.0 2215.73  4987.6 2210.86
  4994.1 2204.81  4998.0 2203.46  5033.7 2201.82  5034.2 2201.32  5059.3 2201.82
  5059.8 2207.92  5068.1 2209.75  5073.9 2213.59  5082.8 2207.00  5089.8 2214.24
  5133.0 2213.90  5186.3 2219.94  5301.5 2222.59  5487.7 2222.70  5807.9 2223.47
#Mann=9,-1,0
  3900.2    0.07       0  3966.7   0.035       0  4129.4    0.07       0
  4186.2   0.035       0  4351.8    0.07       0  4661.4   0.035       0
  5033.7   0.035       0  5059.3   0.035       0  5487.7    0.07       0
Bank Sta=5033.7,5059.3
Exp/Cntr=0.3,0.1

Type RM Length L Ch R = 1,27443,443,443,443
BEGIN DESCRIPTION:
Linn Creek 54.0
END DESCRIPTION:
XS GIS Cut Line= 4
      1319236.97      6900754.20      1319893.20      6899875.76
      1319914.03      6899795.90      1319653.61      6899205.61
#Sta/Elev= 30
  3868.4 2247.44  4182.2 2234.98  4296.4 2230.61  4336.5 2229.81  4350.5 2227.59
  4422.0 2226.13  4513.7 2220.97  4567.3 2219.22  4636.7 2216.53  4686.7 2216.16
  4763.8 2211.72  4849.8 2215.24  4964.9 2214.56  4972.9 2213.02  4983.2 2212.90
  4990.1 2207.08  4995.3 2206.82  5001.4 2198.55  5001.9 2198.05  5027.0 2198.55
  5030.6 2201.77  5035.8 2203.10  5043.8 2209.39  5047.4 2209.39  5054.0 2211.65
  5111.6 2213.79  5129.4 2215.85  5326.9 2215.43  5506.5 2220.06  5692.6 2220.10
#Mann=6,-1,0
  3868.4    0.07       0  4182.2   0.035       0  4296.4    0.07       0
  4567.3   0.035       0  5001.4   0.035       0  5027.0   0.035       0
Bank Sta=5001.4,5027
Exp/Cntr=0.3,0.1

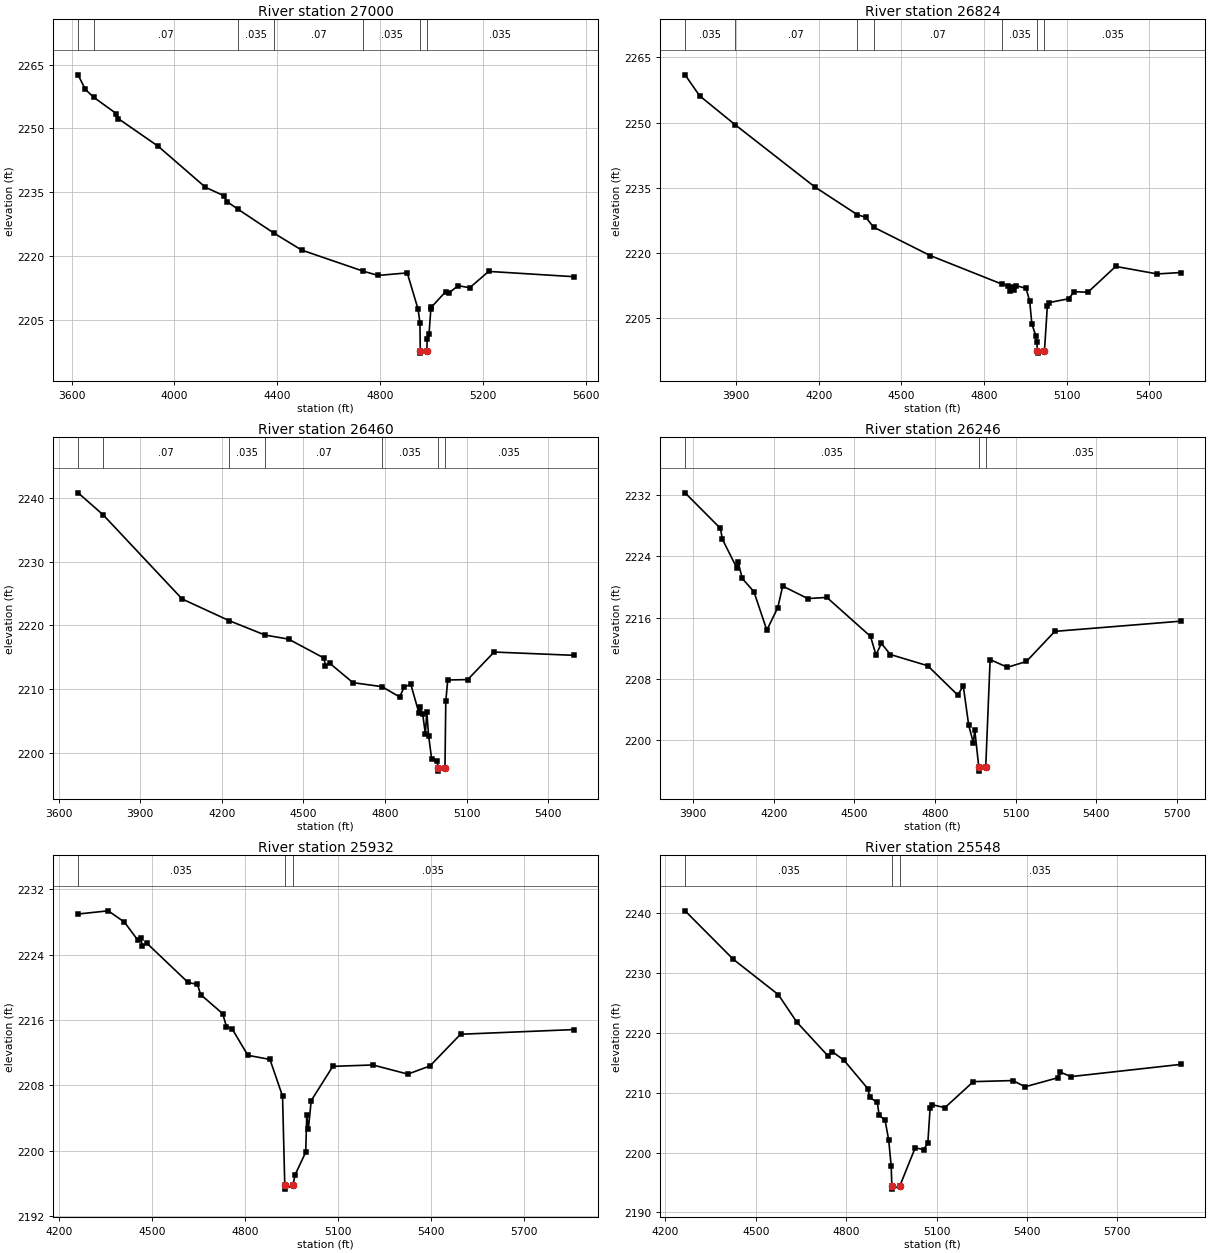
Type RM Length L Ch R = 1,27000,176,176,176
BEGIN DESCRIPTION:
Linn Creek 53.0
END DESCRIPTION:
XS GIS Cut Line= 3
      1319254.97      6901038.03      1320251.89      6900091.49
      1320399.06      6899558.33
#Sta/Elev= 30
  3625.3 2262.58  3653.5 2259.16  3686.3 2257.31  3774.0 2253.48  3780.9 2252.33
  3936.6 2245.83  4120.6 2236.20  4191.1 2234.25  4205.2 2232.80  4249.0 2230.98
  4387.2 2225.43  4495.2 2221.45  4735.1 2216.49  4792.5 2215.50  4905.8 2216.10
  4948.2 2207.52  4955.1 2204.38  4956.5 2197.77  4957.0 2197.27  4982.1 2197.77
  4983.4 2200.69  4990.5 2201.76  4997.6 2207.58  5000.0 2208.07  5055.5 2211.71
  5069.6 2211.48  5103.9 2213.10  5148.9 2212.61  5222.5 2216.45  5553.1 2215.21
#Mann=7,-1,0
  3625.3   0.035       0  3686.3    0.07       0  4249.0   0.035       0
  4387.2    0.07       0  4735.1   0.035       0  4956.5   0.035       0
  4982.1   0.035       0
Bank Sta=4956.5,4982.1
Exp/Cntr=0.3,0.1

Type RM Length L Ch R = 1,26824,364,364,364
BEGIN DESCRIPTION:
Linn Creek 52.6
END DESCRIPTION:
XS GIS Cut Line= 3
      1319376.61      6901054.50      1320356.17      6900231.16
      1320413.03      6899713.39
#Sta/Elev= 30
  3714.1 2260.98  3766.9 2256.16  3896.0 2249.50  4185.7 2235.18  4340.4 2228.78
  4370.4 2228.21  4398.8 2225.94  4604.6 2219.40  4866.4 2212.80  4888.1 2212.49
  4895.9 2211.33  4902.4 2212.19  4910.2 2211.45  4916.7 2212.47  4953.0 2211.86
  4966.2 2208.91  4974.0 2203.69  4988.3 2200.93  4992.3 2199.45  4994.2 2197.45
  4994.7 2196.95  5019.8 2197.45  5030.4 2207.85  5037.1 2208.59  5107.6 2209.45
  5127.7 2211.07  5178.0 2210.97  5278.6 2216.90  5429.5 2215.17  5514.6 2215.49
#Mann=7,-1,0
  3714.1   0.035       0  3896.0    0.07       0  4340.4   0.035       0
  4398.8    0.07       0  4866.4   0.035       0  4994.2   0.035       0
  5019.8   0.035       0
Bank Sta=4994.2,5019.8
Exp/Cntr=0.3,0.1

Type RM Length L Ch R = 1,26460,214,214,214
BEGIN DESCRIPTION:
Linn Creek 52.5
END DESCRIPTION:
XS GIS Cut Line= 6
      1320045.86      6901338.35      1320571.89      6900531.09
      1320610.95      6900320.15      1320660.43      6900200.36
      1320660.43      6900171.71      1320449.75      6899734.75
#Sta/Elev= 30
  3671.8 2240.78  3763.7 2237.34  4054.2 2224.13  4226.4 2220.74  4358.8 2218.47
  4445.4 2217.83  4575.1 2214.87  4581.1 2213.68  4596.2 2214.06  4682.1 2211.00
  4788.8 2210.37  4853.7 2208.76  4871.0 2210.35  4894.9 2210.72  4924.2 2206.30
  4929.6 2207.13  4938.7 2206.02  4948.1 2202.96  4953.5 2206.32  4960.4 2202.61
  4971.2 2199.06  4991.8 2198.67  4994.6 2197.62  4995.1 2197.12  5020.3 2197.62
  5023.3 2208.07  5030.5 2211.42  5103.9 2211.48  5200.9 2215.80  5493.2 2215.29
#Mann=7,-1,0
  3671.8   0.035       0  3763.7    0.07       0  4226.4   0.035       0
  4358.8    0.07       0  4788.8   0.035       0  4994.6   0.035       0
  5020.3   0.035       0
Bank Sta=4994.6,5020.3
Exp/Cntr=0.3,0.1

Type RM Length L Ch R = 1,26246,314,314,314
BEGIN DESCRIPTION:
Linn Creek 52.0
END DESCRIPTION:
XS GIS Cut Line= 4
      1321025.01      6901257.65      1320842.72      6900244.63
      1320866.16      6900096.19      1320402.96      6899617.61
#Sta/Elev= 30
  3869.3 2232.30  4001.0 2227.66  4008.3 2226.24  4062.0 2222.50  4067.0 2223.25
  4082.3 2221.12  4125.7 2219.40  4173.8 2214.38  4214.4 2217.30  4233.0 2220.13
  4326.2 2218.50  4397.3 2218.65  4559.9 2213.57  4580.2 2211.16  4600.5 2212.65
  4633.8 2211.20  4773.2 2209.73  4885.0 2205.90  4905.3 2207.12  4925.6 2201.97
  4943.0 2199.67  4948.1 2201.37  4963.3 2196.48  4963.8 2195.98  4989.0 2196.48
  5005.4 2210.54  5069.7 2209.53  5140.4 2210.29  5246.4 2214.22  5714.9 2215.55
#Mann=3,-1,0
  3869.3   0.035       0  4963.3   0.035       0  4989.0   0.035       0
Bank Sta=4963.3,4989
Exp/Cntr=0.3,0.1

Type RM Length L Ch R = 1,25932,384,384,384
BEGIN DESCRIPTION:
Linn Creek 51.5
END DESCRIPTION:
XS GIS Cut Line= 4
      1321238.49      6901016.90      1321101.89      6900294.44
      1321062.70      6900194.39      1320486.20      6899702.41
#Sta/Elev= 30
  4261.2 2228.97  4358.7 2229.36  4411.1 2227.97  4453.4 2225.81  4463.5 2226.04
  4468.5 2225.09  4484.0 2225.37  4616.3 2220.60  4646.8 2220.35  4657.0 2219.11
  4728.2 2216.77  4740.5 2215.19  4758.8 2214.91  4809.6 2211.67  4880.9 2211.17
  4921.6 2206.68  4928.8 2195.79  4929.3 2195.29  4955.1 2195.79  4962.3 2197.06
  4996.5 2199.81  4999.8 2204.41  5005.2 2202.68  5014.1 2206.12  5083.9 2210.32
  5213.3 2210.49  5326.3 2209.37  5397.7 2210.37  5496.5 2214.25  5861.8 2214.82
#Mann=3,-1,0
  4261.2   0.035       0  4928.8   0.035       0  4955.1   0.035       0
Bank Sta=4928.8,4955.1
Exp/Cntr=0.3,0.1

Type RM Length L Ch R = 1,25548,128,128,128
BEGIN DESCRIPTION:
Linn Creek 50.5
END DESCRIPTION:
XS GIS Cut Line= 4
      1321633.35      6900804.96      1321403.42      6900157.50
      1321210.27      6899988.23      1320552.75      6899745.19
#Sta/Elev= 30
  4265.3 2240.39  4425.6 2232.28  4574.6 2226.40  4636.3 2221.79  4739.6 2216.15
  4754.5 2216.84  4792.7 2215.43  4872.6 2210.63  4877.9 2209.21  4903.5 2208.40
  4909.4 2206.23  4929.0 2205.44  4941.2 2202.09  4949.5 2197.74  4951.6 2194.39
  4952.1 2193.89  4977.9 2194.39  5029.2 2200.80  5056.8 2200.49  5071.0 2201.54
  5078.6 2207.42  5085.2 2207.99  5127.9 2207.51  5222.2 2211.85  5353.4 2212.03
  5394.0 2210.99  5502.7 2212.50  5510.4 2213.45  5546.1 2212.69  5910.2 2214.73
#Mann=3,-1,0
  4265.3   0.035       0  4951.6   0.035       0  4977.9   0.035       0
Bank Sta=4951.6,4977.9
Exp/Cntr=0.3,0.1

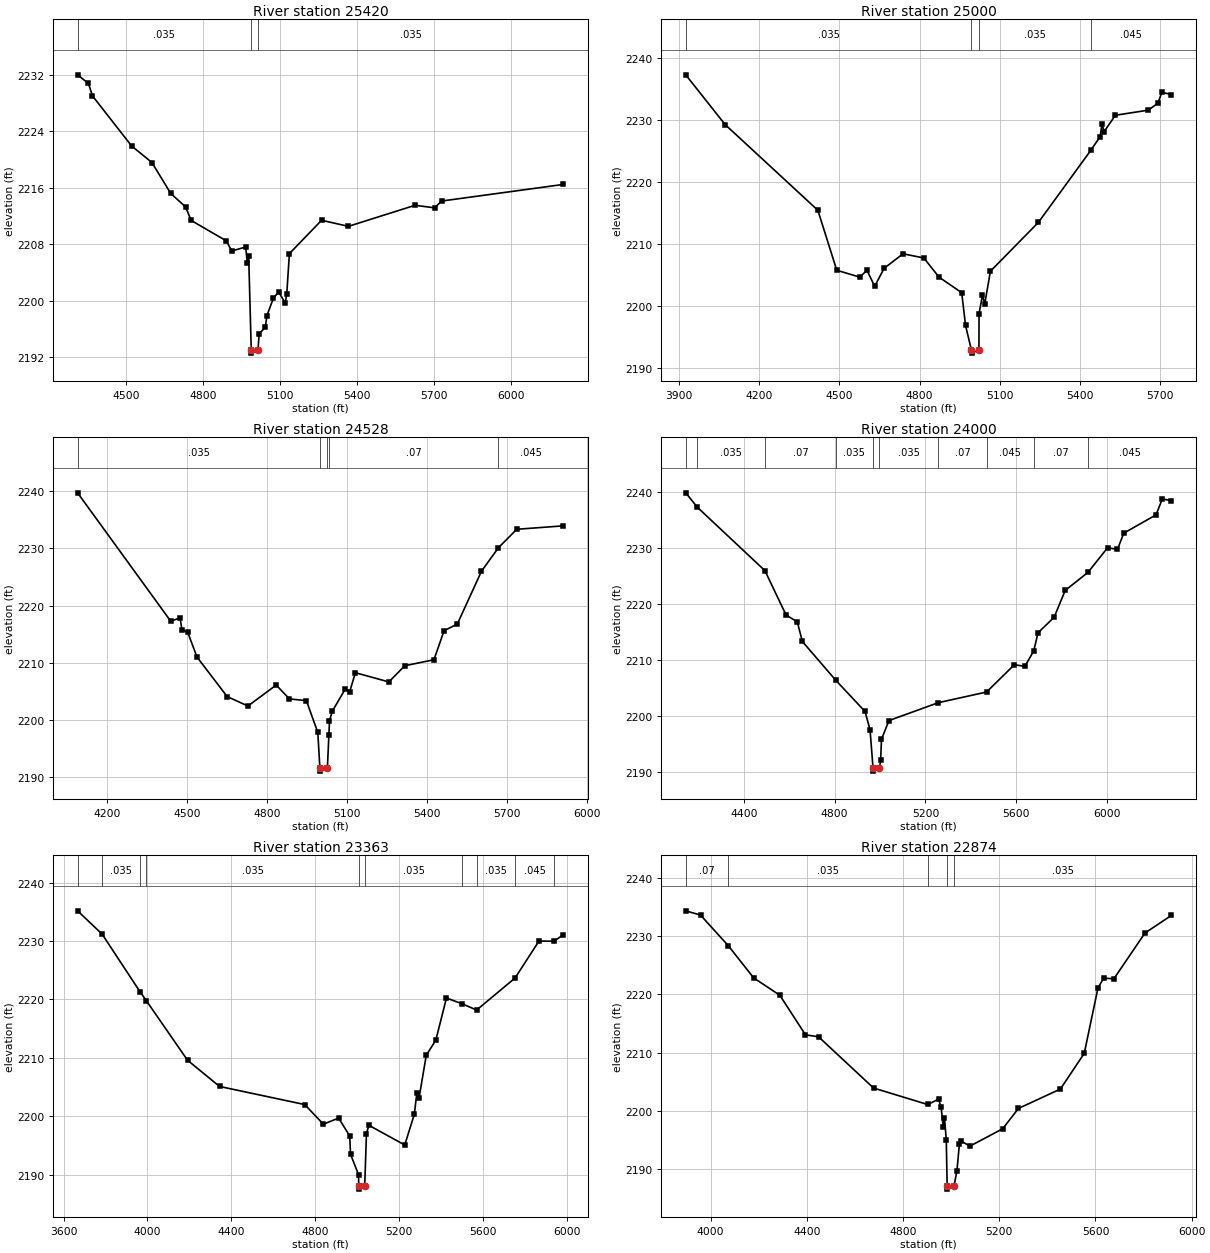
Type RM Length L Ch R = 1,25420,420,420,420
BEGIN DESCRIPTION:
Linn Creek 50.0
END DESCRIPTION:
XS GIS Cut Line= 4
      1321831.53      6900600.26      1321493.85      6900049.73
      1321420.93      6900017.18      1320303.77      6899674.61
#Sta/Elev= 30
  4309.5 2231.99  4351.9 2230.77  4367.4 2229.02  4520.1 2221.93  4599.4 2219.58
  4672.9 2215.20  4730.9 2213.29  4752.2 2211.39  4889.5 2208.50  4910.8 2207.06
  4965.0 2207.63  4971.2 2205.39  4976.7 2206.39  4986.7 2193.11  4987.2 2192.61
  5013.0 2193.11  5017.6 2195.33  5041.4 2196.27  5048.0 2197.93  5072.8 2200.36
  5093.7 2201.29  5118.8 2199.70  5125.1 2200.91  5135.5 2206.69  5261.1 2211.41
  5365.6 2210.55  5625.6 2213.53  5701.6 2213.17  5729.1 2214.13  6203.7 2216.48
#Mann=3,-1,0
  4309.5   0.035       0  4986.7   0.035       0  5013.0   0.035       0
Bank Sta=4986.7,5013
Exp/Cntr=0.3,0.1

Type RM Length L Ch R = 1,25000,472,472,472
BEGIN DESCRIPTION:
Linn Creek 49.0
END DESCRIPTION:
XS GIS Cut Line= 3
      1322331.08      6900390.30      1321556.62      6899646.63
      1321139.91      6899033.18
#Sta/Elev= 30
  3926.3 2237.32  4073.5 2229.29  4420.1 2215.44  4490.8 2205.75  4575.8 2204.65
  4604.1 2205.72  4632.4 2203.15  4667.9 2206.07  4738.6 2208.41  4816.3 2207.73
  4872.9 2204.64  4957.8 2202.12  4972.0 2196.85  4994.0 2192.86  4994.5 2192.36
  5022.1 2192.86  5022.5 2198.73  5035.1 2201.68  5044.0 2200.35  5065.0 2205.59
  5244.7 2213.50  5440.0 2225.11  5475.2 2227.34  5481.9 2229.38  5490.1 2228.16
  5532.1 2230.79  5654.8 2231.61  5690.8 2232.73  5705.7 2234.49  5741.6 2234.14
#Mann=4,-1,0
  3926.3   0.035       0  4994.0   0.035       0  5022.1   0.035       0
  5440.0   0.045       0
Bank Sta=4994,5022.1
Exp/Cntr=0.3,0.1

Type RM Length L Ch R = 1,24528,528,528,528
BEGIN DESCRIPTION:
Linn Creek 48.0
END DESCRIPTION:
XS GIS Cut Line= 4
      1322575.91      6900150.75      1321976.92      6899530.93
      1321914.42      6899416.35      1321185.21      6899020.49
#Sta/Elev= 30
  4089.5 2239.71  4438.7 2217.29  4474.0 2217.83  4481.1 2215.76  4502.2 2215.38
  4537.7 2210.99  4650.7 2204.10  4728.6 2202.45  4834.6 2206.11  4884.3 2203.69
  4947.8 2203.39  4990.7 2197.83  4998.5 2191.57  4999.0 2191.07  5026.6 2191.57
  5032.3 2197.45  5034.5 2199.84  5044.8 2201.52  5093.7 2205.42  5109.9 2204.90
  5131.7 2208.27  5257.2 2206.66  5317.1 2209.49  5426.4 2210.54  5464.4 2215.62
  5513.8 2216.76  5604.7 2226.01  5668.5 2230.13  5737.2 2233.34  5911.7 2233.94
#Mann=5,-1,0
  4089.5   0.035       0  4998.5   0.035       0  5026.6   0.035       0
  5032.3    0.07       0  5668.5   0.045       0
Bank Sta=4998.5,5026.6
Exp/Cntr=0.3,0.1

Type RM Length L Ch R = 1,24000,637,637,637
BEGIN DESCRIPTION:
Linn Creek 47.0
END DESCRIPTION:
XS GIS Cut Line= 3
      1322851.95      6899843.47      1322305.17      6899185.00
      1321077.20      6898812.58
#Sta/Elev= 30
  4144.1 2239.79  4195.4 2237.21  4492.9 2225.89  4586.1 2217.96  4635.5 2216.75
  4657.7 2213.24  4805.1 2206.30  4933.7 2200.74  4955.9 2197.46  4969.1 2190.58
  4969.6 2190.08  4997.3 2190.58  5002.7 2192.07  5006.1 2195.75  5039.0 2199.11
  5256.7 2202.31  5469.0 2204.21  5591.6 2209.09  5637.6 2208.79  5676.8 2211.56
  5695.5 2214.78  5766.6 2217.57  5815.3 2222.36  5915.8 2225.59  6002.1 2229.99
  6045.5 2229.68  6073.2 2232.59  6215.2 2235.85  6242.9 2238.69  6283.2 2238.39
#Mann=10,-1,0
  4144.1    0.07       0  4195.4   0.035       0  4492.9    0.07       0
  4805.1   0.035       0  4969.1   0.035       0  4997.3   0.035       0
  5256.7    0.07       0  5469.0   0.045       0  5676.8    0.07       0
  5915.8   0.045       0
Bank Sta=4969.1,4997.3
Exp/Cntr=0.3,0.1

Type RM Length L Ch R = 1,23363,489,489,489
BEGIN DESCRIPTION:
Linn Creek 46.0
END DESCRIPTION:
XS GIS Cut Line= 3
      1322914.44      6899739.30      1322237.34      6898635.10
      1321341.46      6898145.49
#Sta/Elev= 30
  3667.1 2235.18  3784.4 2231.18  3964.9 2221.32  3994.6 2219.81  4191.4 2209.60
  4344.1 2205.11  4750.3 2202.01  4839.1 2198.65  4912.0 2199.69  4964.6 2196.64
  4968.7 2193.51  5006.7 2190.01  5007.9 2188.03  5008.4 2187.53  5036.2 2188.03
  5044.6 2197.04  5056.2 2198.46  5227.1 2195.09  5272.7 2200.32  5284.7 2203.95
  5295.1 2203.07  5329.7 2210.44  5375.3 2213.04  5426.0 2220.25  5502.4 2219.24
  5569.8 2218.19  5753.1 2223.67  5867.2 2230.01  5938.5 2229.97  5983.3 2231.09
#Mann=10,-1,0
  3667.1    0.07       0  3784.4   0.035       0  3964.9    0.07       0
  3994.6   0.035       0  5007.9   0.035       0  5036.2   0.035       0
  5502.4    0.07       0  5569.8   0.035       0  5753.1   0.045       0
  5938.5   0.035       0
Bank Sta=5007.9,5036.2
Exp/Cntr=0.3,0.1

Type RM Length L Ch R = 1,22874,464,464,464
BEGIN DESCRIPTION:
Linn Creek 45.0
END DESCRIPTION:
XS GIS Cut Line= 3
      1322997.76      6899775.75      1322612.34      6898718.43
      1322117.57      6897973.67
#Sta/Elev= 30
  3896.5 2234.37  3958.0 2233.64  4073.1 2228.40  4179.1 2222.85  4287.9 2219.86
  4394.4 2213.07  4448.8 2212.73  4677.4 2203.93  4902.2 2201.10  4947.8 2202.00
  4958.5 2200.62  4967.0 2197.31  4972.4 2198.86  4979.8 2194.98  4983.5 2187.06
  4984.0 2186.56  5011.8 2187.06  5024.0 2189.67  5034.4 2194.31  5042.3 2194.79
  5078.4 2193.95  5214.5 2196.94  5279.8 2200.42  5454.2 2203.75  5553.4 2209.88
  5610.7 2221.16  5634.6 2222.80  5676.7 2222.70  5806.0 2230.56  5916.0 2233.59
#Mann=5,-1,0
  3896.5    0.07       0  4073.1   0.035       0  4902.2    0.07       0
  4983.5   0.035       0  5011.8   0.035       0
Bank Sta=4983.5,5011.8
Exp/Cntr=0.3,0.1

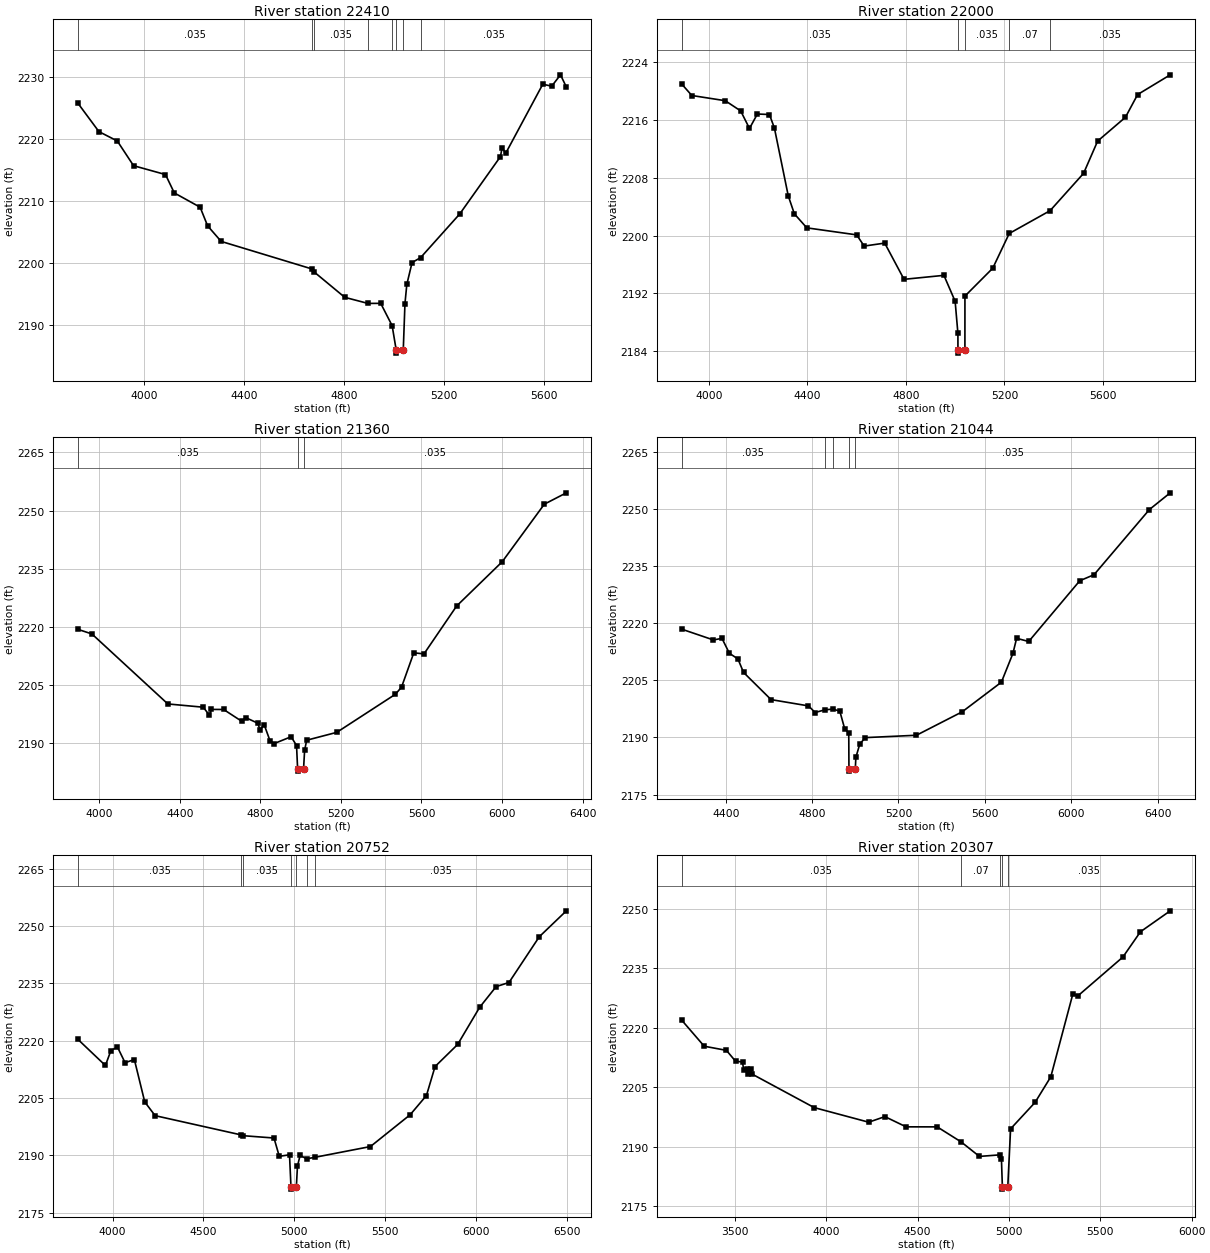
Type RM Length L Ch R = 1,22410,410,410,410
BEGIN DESCRIPTION:
Linn Creek 44.0
END DESCRIPTION:
XS GIS Cut Line= 3
      1323159.22      6899515.33      1322700.88      6898338.23
      1322232.13      6897827.81
#Sta/Elev= 30
  3735.1 2225.74  3819.5 2221.15  3893.1 2219.64  3958.2 2215.66  4086.1 2214.23
  4121.4 2211.27  4224.8 2208.97  4254.7 2205.97  4309.0 2203.46  4671.1 2199.04
  4682.5 2198.50  4803.9 2194.45  4896.7 2193.47  4947.9 2193.48  4993.7 2189.88
  5009.9 2185.96  5010.4 2185.46  5038.2 2185.96  5045.0 2193.45  5052.4 2196.52
  5073.4 2200.05  5107.7 2200.85  5264.5 2207.89  5427.3 2217.12  5434.1 2218.58
  5448.3 2217.65  5596.9 2228.79  5632.6 2228.47  5667.8 2230.30  5691.3 2228.33
#Mann=8,-1,0
  3735.1   0.035       0  4671.1    0.07       0  4682.5   0.035       0
  4896.7    0.07       0  4993.7   0.035       0  5009.9   0.035       0
  5038.2   0.035       0  5107.7   0.035       0
Bank Sta=5009.9,5038.2
Exp/Cntr=0.3,0.1

Type RM Length L Ch R = 1,22000,640,640,640
BEGIN DESCRIPTION:
Linn Creek 43.0
END DESCRIPTION:
XS GIS Cut Line= 3
      1323226.92      6899379.88      1323055.45      6898283.01
      1322393.62      6897713.25
#Sta/Elev= 30
  3889.8 2220.96  3930.9 2219.37  4066.5 2218.65  4129.2 2217.24  4165.0 2214.81
  4197.0 2216.81  4246.0 2216.74  4266.2 2214.87  4322.5 2205.48  4347.2 2203.00
  4397.8 2201.06  4600.2 2200.09  4630.6 2198.54  4714.1 2198.95  4792.5 2193.94
  4954.5 2194.49  5000.0 2190.90  5011.3 2186.45  5011.4 2184.23  5011.9 2183.73
  5039.7 2184.23  5039.8 2191.62  5152.8 2195.48  5219.6 2200.28  5385.6 2203.44
  5521.5 2208.60  5578.5 2213.06  5691.5 2216.36  5740.9 2219.50  5873.3 2222.23
#Mann=5,-1,0
  3889.8   0.035       0  5011.4   0.035       0  5039.7   0.035       0
  5219.6    0.07       0  5385.6   0.035       0
Bank Sta=5011.4,5039.7
Exp/Cntr=0.3,0.1

Type RM Length L Ch R = 1,21360,316,316,316
BEGIN DESCRIPTION:
Linn Creek 41.5
END DESCRIPTION:
XS GIS Cut Line= 4
      1323290.41      6899367.28      1323407.99      6898315.06
      1323534.63      6898324.11      1323730.60      6897100.01
#Sta/Elev= 30
  3894.1 2219.36  3963.8 2218.17  4340.9 2200.11  4516.5 2199.27  4547.4 2197.21
  4557.5 2198.70  4617.9 2198.68  4708.4 2195.62  4728.5 2196.56  4787.4 2195.15
  4799.0 2193.40  4819.1 2194.77  4849.3 2190.45  4869.4 2189.90  4952.9 2191.65
  4979.9 2189.39  4985.3 2183.28  4985.8 2182.78  5014.6 2183.28  5020.0 2188.14
  5030.1 2190.75  5179.6 2192.78  5470.8 2202.61  5501.2 2204.45  5562.0 2213.30
  5612.6 2213.02  5774.7 2225.37  6001.0 2236.79  6210.1 2251.64  6319.5 2254.57
#Mann=3,-1,0
  3894.1   0.035       0  4985.3   0.035       0  5014.6   0.035       0
Bank Sta=4985.3,5014.6
Exp/Cntr=0.3,0.1

Type RM Length L Ch R = 1,21044,292,292,292
BEGIN DESCRIPTION:
Linn Creek 41.0
END DESCRIPTION:
XS GIS Cut Line= 3
      1323331.08      6899364.31      1323543.67      6898589.43
      1323736.58      6897142.65
#Sta/Elev= 30
  4195.7 2218.44  4342.5 2215.61  4382.2 2216.02  4416.6 2212.11  4456.2 2210.61
  4482.2 2207.08  4609.6 2199.94  4782.9 2198.29  4814.0 2196.55  4859.4 2197.27
  4896.1 2197.44  4928.1 2196.92  4950.8 2192.27  4969.6 2191.25  4970.5 2181.66
  4971.0 2181.16  4999.9 2181.66  5002.5 2184.77  5020.8 2188.29  5046.6 2189.96
  5283.1 2190.58  5495.0 2196.73  5676.6 2204.51  5730.1 2212.07  5747.2 2216.04
  5803.2 2215.20  6039.8 2231.15  6105.9 2232.74  6362.6 2249.86  6458.8 2254.24
#Mann=5,-1,0
  4195.7   0.035       0  4859.4    0.07       0  4896.1   0.035       0
  4970.5   0.035       0  4999.9   0.035       0
Bank Sta=4970.5,4999.9
Exp/Cntr=0.3,0.1

Type RM Length L Ch R = 1,20752,445,445,445
BEGIN DESCRIPTION:
Linn Creek 40.5
END DESCRIPTION:
XS GIS Cut Line= 4
      1323347.69      6899481.88      1323923.57      6898613.55
      1323588.90      6898363.30      1323760.76      6897145.19
#Sta/Elev= 30
  3808.7 2220.36  3960.5 2213.51  3990.6 2217.39  4026.7 2218.35  4068.8 2214.24
  4119.9 2215.07  4177.0 2203.99  4234.2 2200.39  4707.3 2195.36  4718.6 2195.15
  4888.8 2194.54  4917.9 2189.75  4974.2 2190.15  4982.4 2181.67  4982.9 2181.17
  5011.8 2181.67  5018.0 2187.17  5032.6 2190.00  5068.8 2189.10  5113.4 2189.49
  5419.9 2192.31  5638.4 2200.62  5728.3 2205.66  5775.6 2213.23  5900.0 2219.01
  6021.2 2228.73  6112.1 2234.15  6182.8 2235.22  6349.8 2247.20  6498.7 2253.97
#Mann=7,-1,0
  3808.7   0.035       0  4707.3    0.07       0  4718.6   0.035       0
  4982.4   0.035       0  5011.8   0.035       0  5068.8    0.07       0
  5113.4   0.035       0
Bank Sta=4982.4,5011.8
Exp/Cntr=0.3,0.1

Type RM Length L Ch R = 1,20307,307,307,307
BEGIN DESCRIPTION:
Linn Creek 40.0
END DESCRIPTION:
XS GIS Cut Line= 4
      1323325.03      6899826.04      1323936.12      6898652.46
      1323970.85      6898305.24      1323929.18      6897305.21
#Sta/Elev= 30
  3209.7 2221.93  3332.9 2215.35  3454.3 2214.31  3504.1 2211.58  3542.7 2211.37
  3548.3 2209.43  3564.8 2209.70  3570.4 2208.32  3586.9 2209.69  3592.5 2208.38
  3934.8 2199.87  4233.0 2196.19  4321.4 2197.60  4437.5 2195.02  4607.7 2195.01
  4738.6 2191.22  4838.8 2187.56  4952.3 2187.96  4959.1 2186.95  4964.4 2179.81
  4964.9 2179.31  4993.8 2179.81  5009.2 2194.51  5143.3 2201.19  5229.3 2207.64
  5349.5 2228.46  5378.5 2228.09  5623.7 2237.84  5719.8 2244.22  5882.7 2249.50
#Mann=5,-1,0
  3209.7   0.035       0  4738.6    0.07       0  4952.3   0.035       0
  4964.4   0.035       0  4993.8   0.035       0
Bank Sta=4964.4,4993.8
Exp/Cntr=0.3,0.1