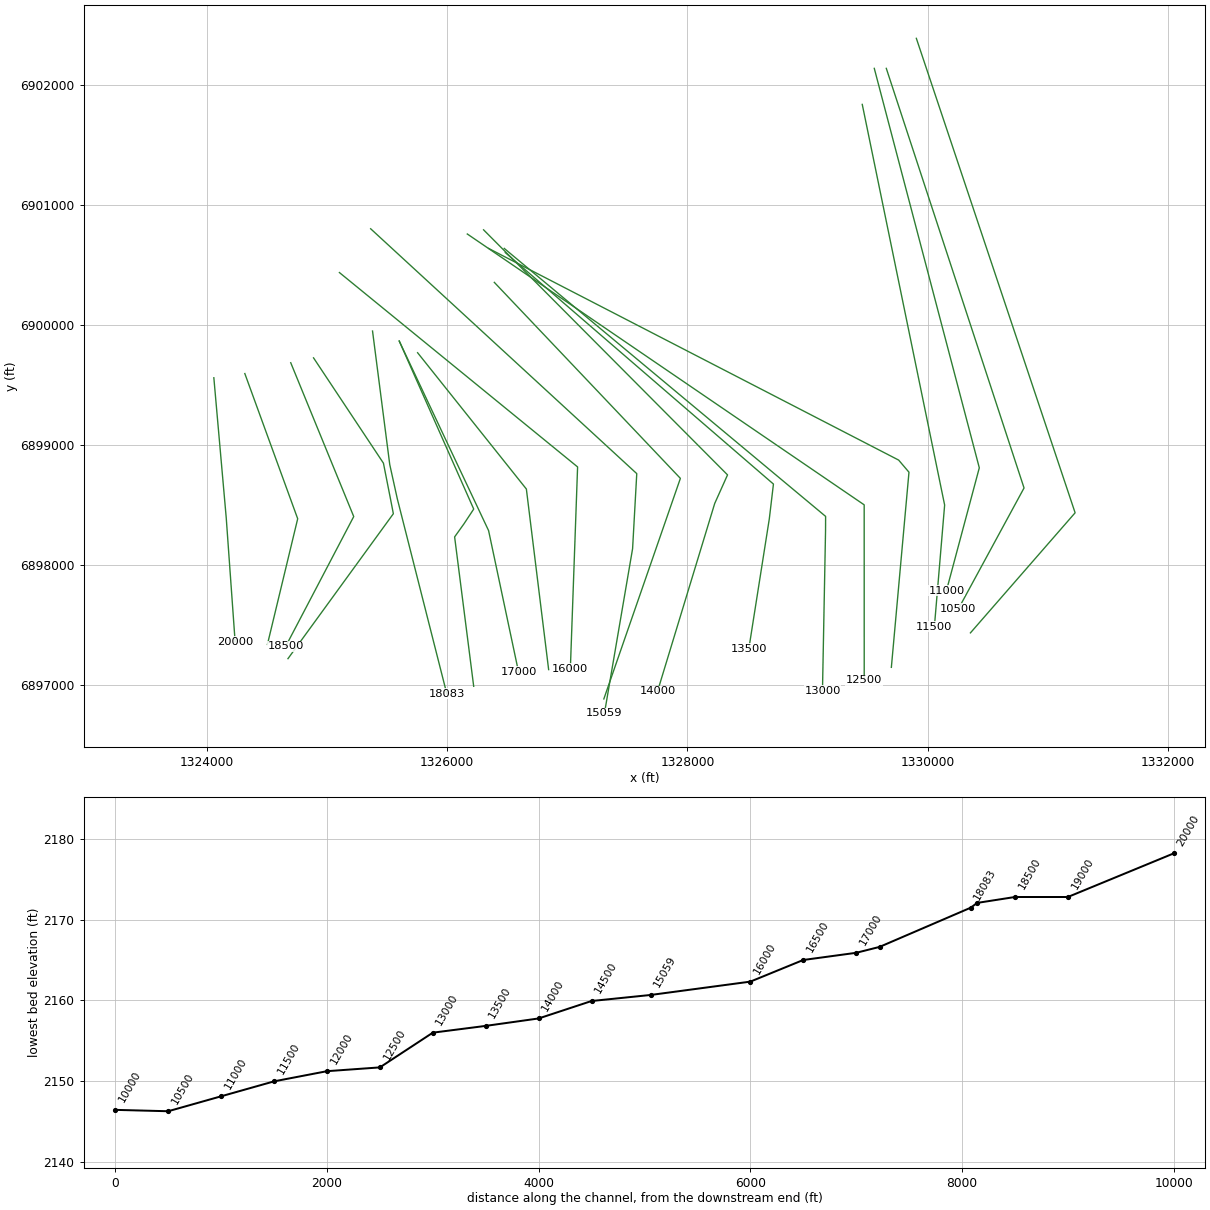
HEC-RAS study Linn Creek.prj: Linn Creek Base Level Engineering

--- Linn Creek.g01 (geometry) --- (continued)

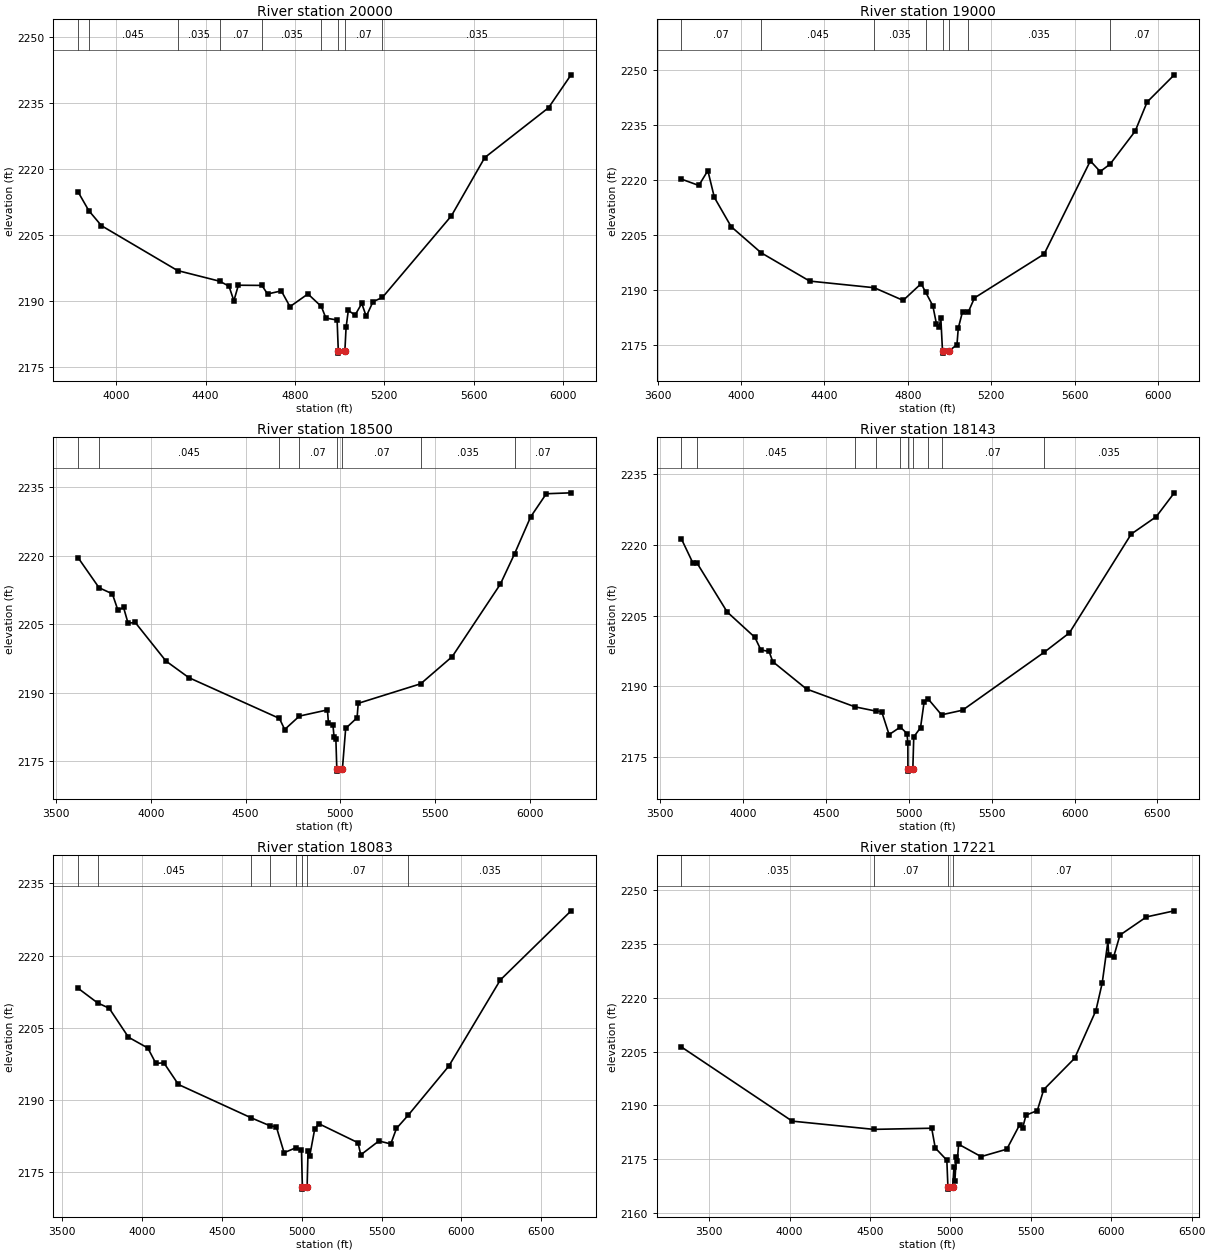
Type RM Length L Ch R = 1,20000,1000,1000,1000
BEGIN DESCRIPTION:
Linn Creek 39.0
END DESCRIPTION:
XS GIS Cut Line= 3
      1324060.26      6899562.17      1324163.30      6898396.72
      1324237.34      6897364.27
#Sta/Elev= 30
  3830.0 2214.86  3877.8 2210.61  3934.6 2207.17  4274.8 2196.97  4463.6 2194.54
  4505.1 2193.41  4526.9 2190.09  4547.0 2193.63  4652.3 2193.59  4677.5 2191.64
  4739.1 2192.34  4777.9 2188.76  4858.2 2191.65  4918.1 2188.80  4938.5 2186.16
  4988.7 2185.72  4994.0 2178.69  4994.5 2178.19  5023.4 2178.69  5028.8 2184.03
  5038.8 2187.90  5068.9 2186.83  5099.0 2189.49  5119.0 2186.54  5149.1 2189.87
  5191.6 2190.87  5500.0 2209.42  5649.1 2222.66  5934.3 2233.99  6035.1 2241.48
#Mann=9,-1,0
  3830.0   0.035       0  3877.8   0.045       0  4274.8   0.035       0
  4463.6    0.07       0  4652.3   0.035       0  4918.1    0.07       0
  4994.0    0.07       0  5023.4    0.07       0  5191.6   0.035       0
Bank Sta=4994,5023.4
Exp/Cntr=0.3,0.1

Type RM Length L Ch R = 1,19000,500,500,500
BEGIN DESCRIPTION:
Linn Creek 38.0
END DESCRIPTION:
XS GIS Cut Line= 3
      1324318.05      6899596.95      1324757.91      6898388.30
      1324505.94      6897341.50
#Sta/Elev= 30
  3713.8 2220.27  3797.8 2218.52  3841.1 2222.58  3872.3 2215.26  3952.8 2207.29
  4096.3 2200.17  4329.1 2192.44  4638.7 2190.63  4777.2 2187.17  4863.6 2191.75
  4884.8 2189.43  4919.4 2185.71  4936.5 2180.85  4950.0 2179.88  4957.7 2182.45
  4965.8 2173.29  4966.3 2172.79  4995.4 2173.29  5035.1 2175.11  5041.4 2179.61
  5062.0 2184.14  5089.5 2184.01  5118.9 2187.85  5452.9 2199.81  5674.4 2225.22
  5721.5 2222.31  5769.4 2224.36  5889.2 2233.33  5946.6 2241.29  6076.7 2248.70
#Mann=8,-1,0
  3713.8    0.07       0  4096.3   0.045       0  4638.7   0.035       0
  4884.8    0.16       0  4965.8    0.07       0  4995.4    0.16       0
  5089.5   0.035       0  5769.4    0.07       0
Bank Sta=4965.8,4995.4
Exp/Cntr=0.3,0.1

Type RM Length L Ch R = 1,18500,357,357,357
BEGIN DESCRIPTION:
Linn Creek 37.0
END DESCRIPTION:
XS GIS Cut Line= 3
      1324700.03      6899687.15      1325224.15      6898406.55
      1324659.16      6897327.63
#Sta/Elev= 30
  3616.3 2219.61  3727.1 2213.01  3797.3 2211.68  3826.8 2208.06  3856.2 2208.71
  3880.2 2205.23  3917.9 2205.40  4080.0 2196.94  4200.6 2193.30  4678.9 2184.35
  4706.7 2181.92  4784.2 2184.86  4932.2 2186.22  4937.6 2183.34  4961.6 2182.83
  4967.0 2180.34  4976.8 2179.85  4981.7 2173.29  4982.2 2172.79  5011.3 2173.29
  5028.5 2182.16  5088.7 2184.50  5094.7 2187.66  5424.5 2191.95  5591.0 2197.92
  5844.5 2213.78  5919.5 2220.43  6004.6 2228.55  6087.2 2233.63  6217.9 2233.83
#Mann=8,-1,0
  3616.3    0.07       0  3727.1   0.045       0  4678.9   0.035       0
  4784.2    0.07       0  4981.7    0.07       0  5011.3    0.07       0
  5424.5   0.035       0  5919.5    0.07       0
Bank Sta=4981.7,5011.3
Exp/Cntr=0.3,0.1

Type RM Length L Ch R = 1,18143,60,60,60
BEGIN DESCRIPTION:
Linn Creek 36.5
END DESCRIPTION:
XS GIS Cut Line= 5
      1324889.72      6899727.76      1325471.30      6898851.05
      1325532.06      6898542.89      1325553.76      6898430.04
      1324677.01      6897223.42
#Sta/Elev= 30
  3628.9 2221.32  3698.2 2216.21  3722.2 2216.24  3905.7 2205.78  4072.6 2200.41
  4108.6 2197.75  4158.3 2197.41  4180.6 2195.25  4383.9 2189.46  4676.4 2185.68
  4800.8 2184.79  4837.0 2184.68  4881.9 2179.80  4949.9 2181.40  4989.9 2180.01
  4995.0 2177.98  4995.4 2172.56  4995.9 2172.06  5025.1 2172.56  5030.6 2179.31
  5071.3 2181.26  5093.4 2186.80  5115.3 2187.44  5198.1 2183.99  5324.7 2184.97
  5817.9 2197.27  5969.3 2201.36  6341.8 2222.29  6492.6 2225.97  6601.5 2231.03
#Mann=10,-1,0
  3628.9    0.07       0  3722.2   0.045       0  4676.4   0.035       0
  4800.8    0.16       0  4949.9    0.07       0  4995.4    0.07       0
  5025.1    0.07       0  5115.3    0.16       0  5198.1    0.07       0
  5817.9   0.035       0
Bank Sta=4995.4,5025.1
Exp/Cntr=0.3,0.1

Type RM Length L Ch R = 1,18083,862,862,862
BEGIN DESCRIPTION:
Linn Creek 36.0
END DESCRIPTION:
XS GIS Cut Line= 4
      1325380.56      6899951.12      1325523.87      6898839.24
      1325586.80      6898553.94      1325998.27      6896931.64
#Sta/Elev= 30
  3599.6 2213.22  3721.5 2210.18  3794.3 2209.07  3915.3 2203.04  4036.3 2200.80
  4086.7 2197.61  4137.1 2197.71  4227.9 2193.22  4684.0 2186.28  4803.9 2184.60
  4840.8 2184.45  4889.7 2179.04  4965.2 2180.09  4998.4 2179.57  5004.1 2171.97
  5004.6 2171.47  5033.8 2171.97  5039.6 2179.38  5049.9 2178.31  5080.9 2183.89
  5106.9 2185.07  5352.7 2181.11  5369.7 2178.59  5483.2 2181.48  5557.6 2180.86
  5593.4 2184.09  5666.9 2186.84  5921.2 2197.05  6243.8 2214.95  6686.5 2229.31
#Mann=8,-1,0
  3599.6   0.035       0  3721.5   0.045       0  4684.0   0.035       0
  4803.9    0.16       0  4965.2    0.07       0  5004.1    0.07       0
  5033.8    0.07       0  5666.9   0.035       0
Bank Sta=5004.1,5033.8
Exp/Cntr=0.3,0.1

Type RM Length L Ch R = 1,17221,221,221,221
BEGIN DESCRIPTION:
Linn Creek 34.5
END DESCRIPTION:
XS GIS Cut Line= 5
      1325602.78      6899867.76      1326222.38      6898468.89
      1326141.65      6898346.49      1326063.53      6898237.12
      1326222.17      6896993.38
#Sta/Elev= 30
  3327.2 2206.29  4016.6 2185.58  4523.5 2183.28  4883.9 2183.60  4906.1 2178.09
  4978.0 2174.69  4984.9 2167.11  4985.4 2166.61  5014.9 2167.11  5022.1 2172.71
  5028.2 2168.94  5036.8 2175.52  5043.0 2174.38  5051.1 2179.14  5191.0 2175.68
  5350.7 2177.75  5430.6 2184.55  5449.8 2183.76  5470.0 2187.24  5540.5 2188.53
  5580.2 2194.37  5772.4 2203.11  5904.6 2216.41  5943.8 2224.08  5979.4 2235.74
  5984.4 2231.81  6014.3 2231.29  6054.2 2237.48  6218.9 2242.55  6392.0 2244.25
#Mann=4,-1,0
  3327.2   0.035       0  4523.5    0.07       0  4984.9    0.07       0
  5014.9    0.07       0
Bank Sta=4984.9,5014.9
Exp/Cntr=0.3,0.1

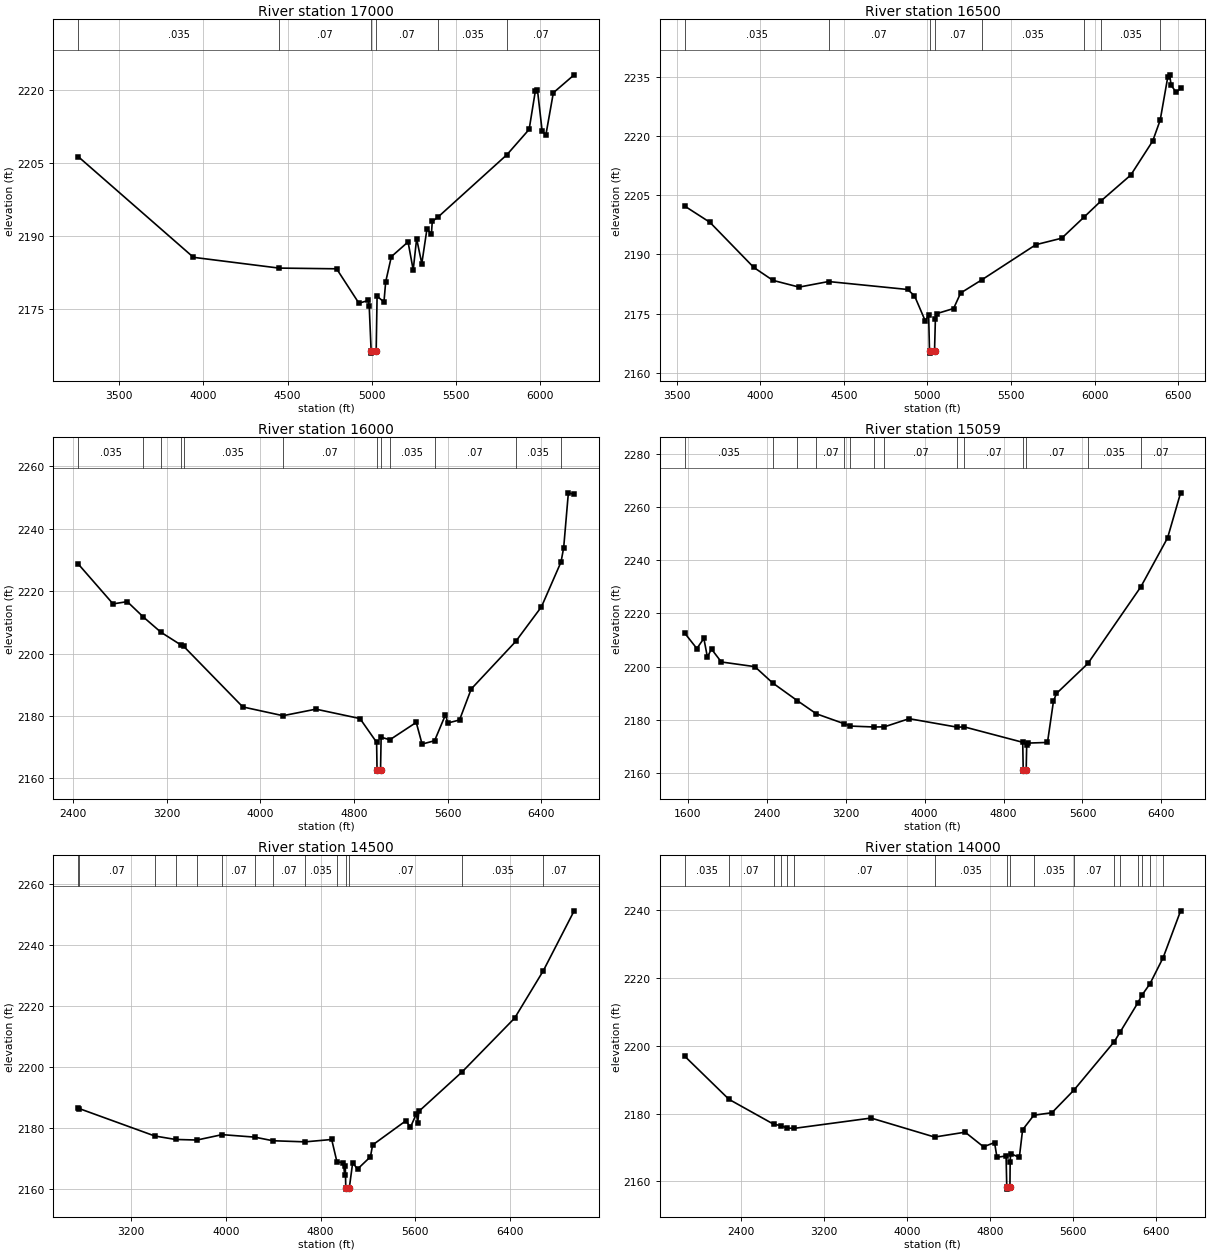
Type RM Length L Ch R = 1,17000,500,500,500
BEGIN DESCRIPTION:
Linn Creek 34.0
END DESCRIPTION:
XS GIS Cut Line= 3
      1325602.81      6899867.70      1326346.22      6898289.31
      1326595.61      6897111.93
#Sta/Elev= 30
  3255.3 2206.29  3940.3 2185.58  4447.9 2183.37  4791.4 2183.22  4924.1 2176.14
  4979.3 2176.71  4985.1 2175.62  4996.6 2166.38  4997.1 2165.88  5026.6 2166.38
  5032.0 2177.58  5072.9 2176.40  5083.1 2180.54  5116.8 2185.72  5216.2 2188.75
  5246.7 2182.98  5267.1 2189.41  5297.8 2184.29  5328.4 2191.39  5355.0 2190.38
  5360.1 2192.96  5394.9 2193.88  5804.3 2206.70  5935.9 2211.89  5972.4 2219.70
  5985.6 2219.93  6013.3 2211.55  6035.3 2210.73  6079.8 2219.42  6203.5 2223.11
#Mann=6,-1,0
  3255.3   0.035       0  4447.9    0.07       0  4996.6    0.07       0
  5026.6    0.07       0  5394.9   0.035       0  5804.3    0.07       0
Bank Sta=4996.6,5026.6
Exp/Cntr=0.3,0.1

Type RM Length L Ch R = 1,16500,500,500,500
BEGIN DESCRIPTION:
Linn Creek 33.0
END DESCRIPTION:
XS GIS Cut Line= 3
      1325755.57      6899770.51      1326660.43      6898635.70
      1326845.77      6897132.28
#Sta/Elev= 30
  3548.6 2202.21  3699.5 2198.10  3962.1 2186.67  4076.2 2183.41  4232.7 2181.70
  4409.0 2183.11  4881.3 2181.10  4922.9 2179.53  4987.0 2173.20  5007.8 2174.53
  5012.9 2165.49  5013.4 2164.99  5042.9 2165.49  5048.1 2173.61  5058.1 2175.01
  5156.9 2176.28  5199.2 2180.21  5324.5 2183.51  5649.0 2192.44  5803.7 2194.08
  5938.7 2199.48  6041.5 2203.62  6216.8 2210.07  6347.8 2218.67  6392.6 2223.96
  6438.5 2235.00  6448.6 2235.43  6458.7 2232.76  6488.9 2230.96  6514.8 2232.09
#Mann=8,-1,0
  3548.6   0.035       0  4409.0    0.07       0  5012.9    0.07       0
  5042.9    0.07       0  5324.5   0.035       0  5938.7    0.07       0
  6041.5   0.035       0  6392.6    0.07       0
Bank Sta=5012.9,5042.9
Exp/Cntr=0.3,0.1

Type RM Length L Ch R = 1,16000,941,941,941
BEGIN DESCRIPTION:
Linn Creek 32.0
END DESCRIPTION:
XS GIS Cut Line= 3
      1325105.00      6900438.00      1327086.64      6898819.67
      1327026.40      6897138.55
#Sta/Elev= 30
  2441.5 2228.72  2739.4 2215.92  2860.8 2216.65  2998.4 2211.72  3148.1 2206.86
  3319.0 2202.78  3344.5 2202.28  3848.8 2182.89  4192.6 2180.08  4474.0 2182.18
  4850.9 2179.16  4993.1 2171.55  4996.7 2162.81  4997.2 2162.31  5026.7 2162.81
  5031.7 2173.19  5106.1 2172.36  5331.9 2177.93  5381.9 2170.98  5488.7 2172.05
  5582.0 2180.38  5602.1 2177.74  5702.1 2178.71  5802.2 2188.65  6182.9 2203.90
  6402.6 2214.99  6569.9 2229.36  6592.7 2233.96  6632.7 2251.53  6682.2 2251.04
#Mann=12,-1,0
  2441.5   0.035       0  2998.4    0.07       0  3148.1   0.035       0
  3319.0    0.07       0  3344.5   0.035       0  4192.6    0.07       0
  4996.7    0.07       0  5026.7    0.07       0  5106.1   0.035       0
  5488.7    0.07       0  6182.9   0.035       0  6569.9    0.07       0
Bank Sta=4996.7,5026.7
Exp/Cntr=0.3,0.1

Type RM Length L Ch R = 1,15059,559,559,559
BEGIN DESCRIPTION:
Linn Creek 31.0
END DESCRIPTION:
XS GIS Cut Line= 4
      1325364.96      6900802.62      1327578.93      6898763.90
      1327544.21      6898138.90      1327309.92      6896767.89
#Sta/Elev= 30
  1568.3 2212.62  1691.7 2206.80  1762.6 2210.62  1798.3 2203.63  1840.2 2206.60
  1939.5 2201.75  2279.2 2199.99  2459.1 2193.88  2710.2 2187.18  2902.8 2182.24
  3187.5 2178.47  3248.3 2177.62  3491.8 2177.27  3592.7 2177.34  3843.2 2180.40
  4333.4 2177.19  4401.2 2177.32  4994.5 2171.51  4999.5 2161.16  5000.0 2160.66
  5029.6 2161.16  5034.6 2170.52  5044.6 2171.21  5245.4 2171.46  5306.3 2187.02
  5336.7 2189.90  5655.2 2201.18  6191.6 2230.03  6462.8 2248.47  6594.8 2265.42
#Mann=14,-1,0
  1568.3   0.035       0  2459.1    0.07       0  2710.2   0.035       0
  2902.8    0.07       0  3187.5   0.035       0  3248.3    0.07       0
  3491.8   0.035       0  3592.7    0.07       0  4333.4   0.035       0
  4401.2    0.07       0  4999.5    0.07       0  5029.6    0.07       0
  5655.2   0.035       0  6191.6    0.07       0
Bank Sta=4999.5,5029.6
Exp/Cntr=0.3,0.1

Type RM Length L Ch R = 1,14500,500,500,500
BEGIN DESCRIPTION:
Linn Creek 29.0
END DESCRIPTION:
XS GIS Cut Line= 3
      1326393.87      6900356.21      1327941.84      6898724.43
      1327305.00      6896888.01
#Sta/Elev= 30
  2750.8 2186.45  2760.7 2186.34  3397.8 2177.36  3573.4 2176.22  3754.5 2176.03
  3967.6 2177.80  4244.2 2176.98  4395.8 2175.80  4669.5 2175.43  4893.7 2176.21
  4938.0 2168.91  4992.8 2168.55  5003.6 2164.47  5008.9 2167.39  5012.9 2160.41
  5013.4 2159.91  5043.1 2160.41  5071.1 2168.55  5112.6 2166.50  5221.5 2170.53
  5239.7 2174.41  5522.3 2182.39  5558.7 2180.15  5610.1 2184.65  5621.0 2181.72
  5631.3 2185.47  5997.4 2198.44  6440.5 2216.06  6683.2 2231.63  6943.7 2251.29
#Mann=14,-1,0
  2750.8   0.035       0  2760.7    0.07       0  3397.8   0.035       0
  3573.4    0.07       0  3754.5   0.035       0  3967.6    0.07       0
  4244.2   0.035       0  4395.8    0.07       0  4669.5   0.035       0
  4938.0    0.07       0  5012.9    0.07       0  5043.1    0.07       0
  5997.4   0.035       0  6683.2    0.07       0
Bank Sta=5012.9,5043.1
Exp/Cntr=0.3,0.1

Type RM Length L Ch R = 1,14000,500,500,500
BEGIN DESCRIPTION:
Linn Creek 28.0
END DESCRIPTION:
XS GIS Cut Line= 4
      1326304.45      6900793.72      1328334.14      6898753.49
      1328227.26      6898515.03      1327752.37      6896953.44
#Sta/Elev= 30
  1860.8 2196.88  2286.9 2184.18  2716.4 2176.86  2787.0 2176.43  2848.8 2175.71
  2913.9 2175.63  3654.2 2178.67  4265.0 2173.08  4559.3 2174.51  4735.8 2170.21
  4842.2 2171.46  4865.2 2167.11  4952.9 2167.52  4959.7 2158.25  4960.2 2157.75
  4989.9 2158.25  4992.3 2165.66  4996.6 2168.22  5080.5 2167.08  5111.9 2175.21
  5220.1 2179.51  5394.1 2180.24  5605.4 2186.88  5993.9 2201.16  6051.6 2204.04
  6218.2 2212.45  6258.0 2214.74  6336.9 2218.17  6464.4 2225.90  6632.2 2239.66
#Mann=17,-1,0
  1860.8   0.035       0  2286.9    0.07       0  2716.4   0.035       0
  2787.0    0.07       0  2848.8   0.035       0  2913.9    0.07       0
  4265.0   0.035       0  4959.7    0.07       0  4989.9   0.035       0
  5220.1   0.035       0  5605.4    0.07       0  5993.9    0.16       0
  6051.6    0.07       0  6218.2    0.16       0  6258.0    0.07       0
  6336.9    0.16       0  6464.4    0.07       0
Bank Sta=4959.7,4989.9
Exp/Cntr=0.3,0.1

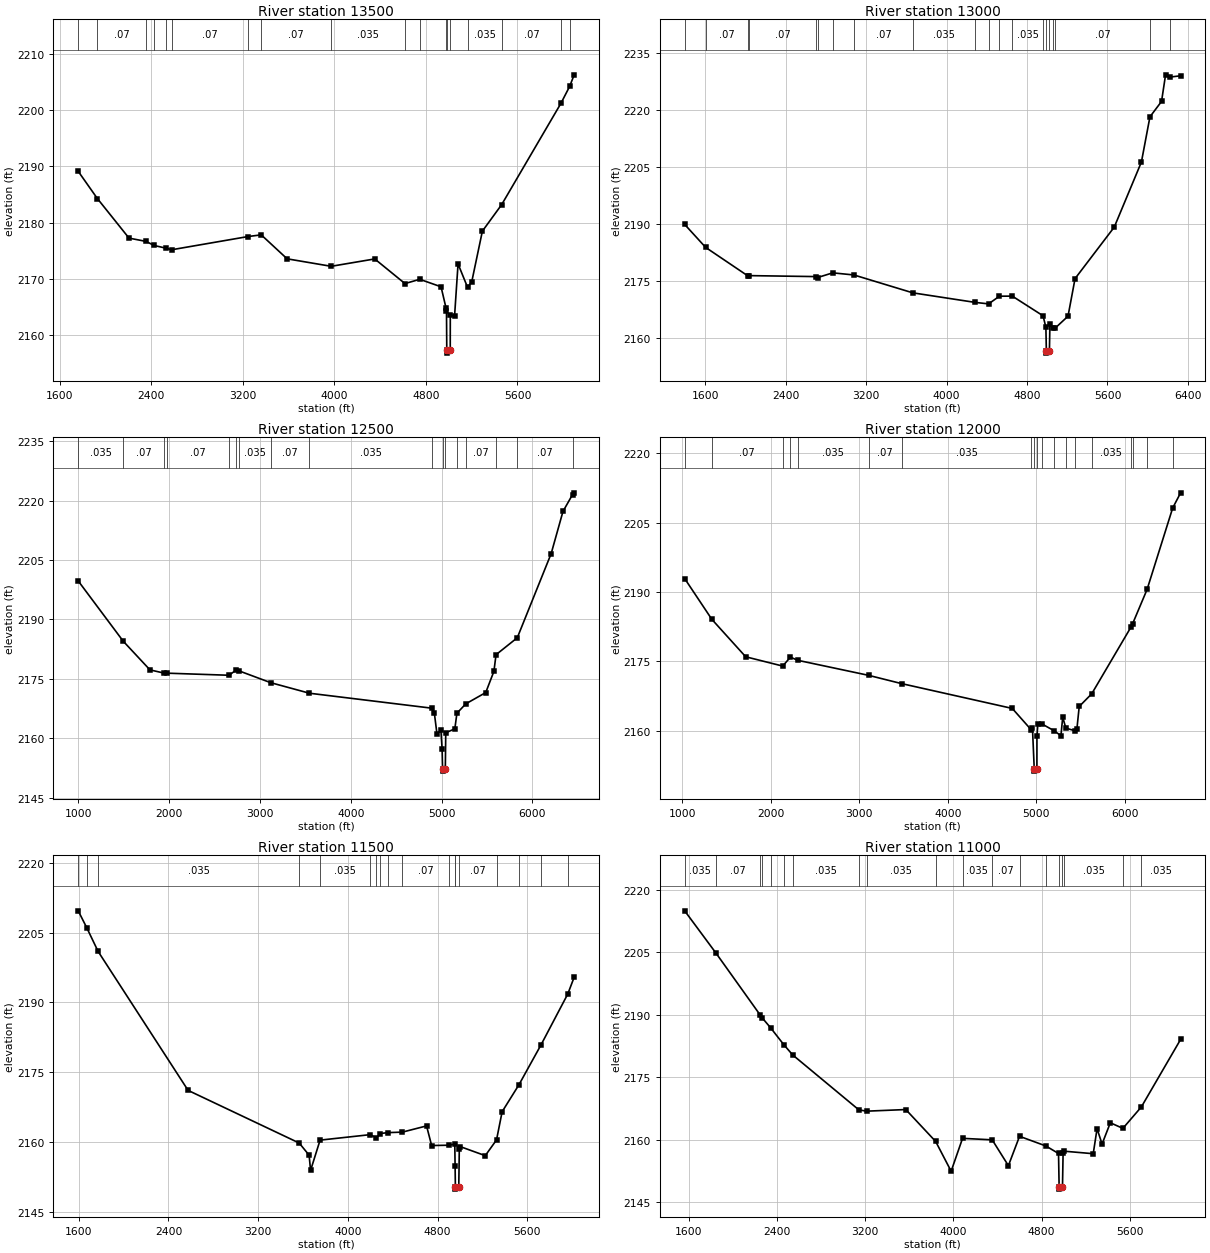
Type RM Length L Ch R = 1,13500,500,500,500
BEGIN DESCRIPTION:
Linn Creek 27.0
END DESCRIPTION:
XS GIS Cut Line= 4
      1326485.16      6900604.19      1328716.08      6898677.10
      1328681.75      6898387.83      1328511.22      6897305.58
#Sta/Elev= 30
  1760.7 2189.14  1928.2 2184.30  2204.7 2177.27  2355.2 2176.68  2422.7 2175.97
  2526.1 2175.49  2577.1 2175.20  3245.3 2177.55  3360.4 2177.85  3586.8 2173.59
  3972.0 2172.26  4352.5 2173.57  4616.9 2169.19  4746.0 2169.95  4932.2 2168.62
  4975.1 2164.90  4979.7 2164.34  4982.3 2157.33  4982.8 2156.83  5012.5 2157.33
  5013.1 2163.55  5050.4 2163.45  5080.8 2172.69  5164.1 2168.51  5200.6 2169.52
  5293.4 2178.51  5461.9 2183.22  5980.4 2201.24  6057.1 2204.27  6095.6 2206.29
#Mann=18,-1,0
  1760.7   0.035       0  1928.2    0.07       0  2355.2   0.035       0
  2422.7    0.07       0  2526.1   0.035       0  2577.1    0.07       0
  3245.3   0.035       0  3360.4    0.07       0  3972.0   0.035       0
  4616.9    0.07       0  4746.0   0.035       0  4975.1    0.07       0
  4982.3    0.07       0  5012.5    0.07       0  5164.1   0.035       0
  5461.9    0.07       0  5980.4    0.16       0  6057.1    0.07       0
Bank Sta=4982.3,5012.5
Exp/Cntr=0.3,0.1

Type RM Length L Ch R = 1,13000,500,500,500
BEGIN DESCRIPTION:
Linn Creek 26.0
END DESCRIPTION:
XS GIS Cut Line= 4
      1326476.46      6900638.93      1329150.11      6898408.00
      1329149.53      6898285.56      1329124.07      6896958.31
#Sta/Elev= 30
  1395.4 2189.88  1603.8 2183.83  2020.8 2176.38  2035.7 2176.40  2705.7 2176.14
  2717.1 2175.89  2867.7 2177.13  3078.6 2176.57  3664.7 2171.86  4286.1 2169.34
  4417.8 2168.96  4525.6 2170.98  4653.6 2171.00  4959.3 2165.82  4987.6 2162.79
  4992.4 2156.49  4992.9 2155.99  5022.7 2156.49  5027.6 2163.59  5057.2 2162.52
  5077.9 2162.53  5207.6 2165.71  5277.6 2175.61  5667.7 2189.18  5937.7 2206.32
  6022.4 2218.21  6137.8 2222.27  6177.8 2229.27  6226.7 2228.69  6327.5 2229.02
#Mann=20,-1,0
  1395.4   0.035       0  1603.8    0.07       0  2020.8   0.035       0
  2035.7    0.07       0  2705.7   0.035       0  2717.1    0.07       0
  2867.7   0.035       0  3078.6    0.07       0  3664.7   0.035       0
  4286.1    0.07       0  4417.8   0.035       0  4525.6    0.07       0
  4653.6   0.035       0  4959.3    0.07       0  4992.4    0.07       0
  5022.7    0.07       0  5057.2    0.16       0  5077.9    0.07       0
  6022.4   0.035       0  6226.7    0.07       0
Bank Sta=4992.4,5022.7
Exp/Cntr=0.3,0.1

Type RM Length L Ch R = 1,12500,500,500,500
BEGIN DESCRIPTION:
Linn Creek 25.0
END DESCRIPTION:
XS GIS Cut Line= 3
      1326169.07      6900758.97      1329471.02      6898504.12
      1329471.29      6897045.12
#Sta/Elev= 30
  1001.6 2199.74  1496.7 2184.52  1791.1 2177.27  1943.3 2176.47  1976.6 2176.44
  2660.9 2175.91  2739.8 2177.23  2769.8 2177.03  3119.3 2174.04  3546.2 2171.37
  4893.4 2167.59  4920.1 2166.44  4949.6 2161.05  4992.7 2161.99  5006.1 2157.25
  5011.0 2152.19  5011.5 2151.69  5041.3 2152.19  5046.1 2161.37  5146.1 2162.39
  5168.9 2166.32  5266.8 2168.69  5486.1 2171.54  5576.1 2176.91  5599.3 2181.10
  5833.3 2185.39  6206.1 2206.65  6336.1 2217.31  6441.6 2221.57  6459.0 2222.00
#Mann=17,-1,0
  1001.6   0.035       0  1496.7    0.07       0  1943.3   0.035       0
  1976.6    0.07       0  2660.9   0.035       0  2739.8    0.07       0
  2769.8   0.035       0  3119.3    0.07       0  3546.2   0.035       0
  4893.4    0.07       0  5011.0    0.07       0  5041.3    0.07       0
  5168.9    0.16       0  5266.8    0.07       0  5599.3   0.035       0
  5833.3    0.07       0  6441.6   0.035       0
Bank Sta=5011,5041.3
Exp/Cntr=0.3,0.1

Type RM Length L Ch R = 1,12000,500,500,500
BEGIN DESCRIPTION:
Linn Creek 24.0
END DESCRIPTION:
XS GIS Cut Line= 4
      1326346.29      6900638.90      1329757.75      6898876.75
      1329843.71      6898775.78      1329697.15      6897151.17
#Sta/Elev= 30
  1027.7 2192.90  1334.9 2184.07  1717.2 2175.97  2135.3 2173.96  2222.7 2175.90
  2302.5 2175.22  3106.5 2171.95  3479.2 2170.16  4729.2 2164.79  4943.3 2160.16
  4957.3 2160.53  4977.2 2151.72  4977.7 2151.22  5007.5 2151.72  5007.8 2158.73
  5017.8 2161.33  5070.1 2161.37  5199.0 2159.99  5278.9 2158.89  5299.0 2162.89
  5334.4 2160.53  5433.0 2159.98  5459.6 2160.40  5485.6 2165.22  5626.6 2167.95
  6071.2 2182.43  6087.7 2183.07  6252.5 2190.56  6541.4 2208.17  6631.2 2211.46
#Mann=19,-1,0
  1027.7   0.035       0  1334.9    0.07       0  2135.3   0.035       0
  2222.7    0.07       0  2302.5   0.035       0  3106.5    0.07       0
  3479.2   0.035       0  4943.3    0.07       0  4977.2    0.07       0
  5007.5    0.07       0  5070.1   0.035       0  5199.0    0.07       0
  5334.4    0.16       0  5433.0    0.07       0  5626.6   0.035       0
  6071.2    0.07       0  6087.7   0.035       0  6252.5    0.07       0
  6541.4   0.035       0
Bank Sta=4977.2,5007.5
Exp/Cntr=0.3,0.1

Type RM Length L Ch R = 1,11500,500,500,500
BEGIN DESCRIPTION:
Linn Creek 23.0
END DESCRIPTION:
XS GIS Cut Line= 3
      1329455.00      6901838.00      1330140.38      6898502.48
      1330055.00      6897487.97
#Sta/Elev= 30
  1594.8 2209.66  1672.7 2205.95  1772.0 2200.96  2574.9 2171.14  3565.7 2159.85
  3654.3 2157.24  3667.2 2153.97  3752.0 2160.47  4200.6 2161.65  4254.7 2160.93
  4290.9 2161.89  4355.8 2162.08  4486.3 2162.19  4701.7 2163.52  4747.0 2159.31
  4900.8 2159.38  4953.5 2159.62  4956.2 2154.95  4958.8 2150.46  4959.3 2149.96
  4989.1 2150.46  4993.7 2158.54  5002.2 2159.08  5225.3 2157.14  5325.8 2160.52
  5375.8 2166.57  5525.0 2172.32  5724.2 2180.98  5961.2 2191.82  6018.1 2195.41
#Mann=18,-1,0
  1594.8   0.035       0  1672.7    0.07       0  1772.0   0.035       0
  3565.7    0.07       0  3752.0   0.035       0  4200.6    0.07       0
  4254.7   0.035       0  4290.9    0.07       0  4355.8   0.035       0
  4486.3    0.07       0  4900.8   0.035       0  4956.2    0.07       0
  4958.8    0.07       0  4989.1    0.07       0  5325.8   0.035       0
  5525.0    0.07       0  5724.2   0.035       0  5961.2    0.07       0
Bank Sta=4958.8,4989.1
Exp/Cntr=0.3,0.1

Type RM Length L Ch R = 1,11000,500,500,500
BEGIN DESCRIPTION:
Linn Creek 22.0
END DESCRIPTION:
XS GIS Cut Line= 3
      1329555.00      6902137.98      1330428.85      6898812.37
      1330155.01      6897788.04
#Sta/Elev= 30
  1561.5 2214.97  1846.9 2204.76  2246.7 2189.93  2266.8 2189.19  2340.6 2186.88
  2460.2 2182.83  2541.6 2180.34  3141.7 2167.15  3212.8 2166.84  3567.3 2167.23
  3838.3 2159.56  3978.6 2152.41  4082.1 2160.31  4351.1 2159.95  4498.0 2153.75
  4599.1 2160.80  4837.9 2158.48  4952.8 2156.67  4958.3 2148.61  4958.8 2148.11
  4988.7 2148.61  4994.2 2156.73  5005.1 2157.22  5267.5 2156.62  5302.4 2162.63
  5347.7 2158.94  5422.6 2164.05  5536.6 2162.71  5704.5 2167.87  6060.3 2184.08
#Mann=19,-1,0
  1561.5   0.035       0  1846.9    0.07       0  2246.7   0.035       0
  2266.8    0.07       0  2340.6   0.035       0  2460.2    0.07       0
  2541.6   0.035       0  3141.7    0.07       0  3212.8   0.035       0
  3838.3    0.07       0  4082.1   0.035       0  4351.1    0.07       0
  4599.1   0.035       0  4837.9    0.07       0  4958.3    0.07       0
  4988.7    0.07       0  5005.1   0.035       0  5536.6    0.07       0
  5704.5   0.035       0
Bank Sta=4958.3,4988.7
Exp/Cntr=0.3,0.1

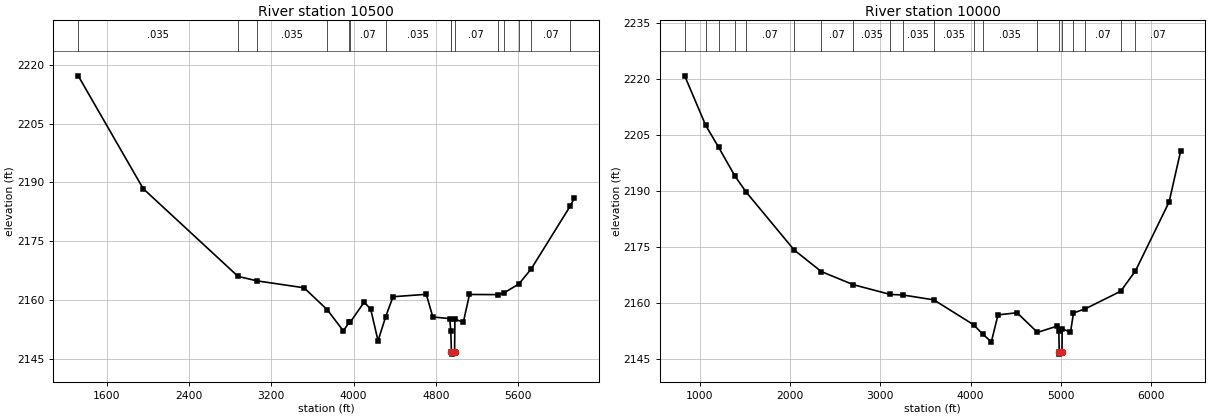
Type RM Length L Ch R = 1,10500,500,500,500
BEGIN DESCRIPTION:
Linn Creek 21.0
END DESCRIPTION:
XS GIS Cut Line= 3
      1329655.00      6902138.00      1330801.05      6898644.48
      1330254.98      6897637.97
#Sta/Elev= 30
  1323.3 2217.17  1954.8 2188.43  2877.5 2166.06  3064.0 2164.92  3519.3 2163.16
  3744.5 2157.57  3901.2 2152.18  3958.2 2154.40  3965.8 2154.32  4102.7 2159.48
  4166.3 2157.79  4238.5 2149.66  4312.9 2155.81  4383.9 2160.88  4707.4 2161.50
  4771.0 2155.73  4935.4 2155.31  4945.5 2152.24  4952.1 2146.76  4952.6 2146.26
  4982.5 2146.76  4985.8 2155.19  5067.5 2154.36  5127.4 2161.46  5404.1 2161.42
  5462.6 2161.86  5607.6 2164.13  5726.2 2167.92  6106.0 2183.94  6145.1 2185.95
#Mann=15,-1,0
  1323.3   0.035       0  2877.5    0.07       0  3064.0   0.035       0
  3744.5    0.07       0  3958.2   0.035       0  3965.8    0.07       0
  4312.9   0.035       0  4945.5    0.07       0  4952.1    0.07       0
  4982.5    0.07       0  5404.1   0.035       0  5462.6    0.07       0
  5607.6   0.035       0  5726.2    0.07       0  6106.0   0.035       0
Bank Sta=4952.1,4982.5
Exp/Cntr=0.3,0.1

Type RM Length L Ch R = 1,10000,500,500,500
BEGIN DESCRIPTION:
Linn Creek 20.0
END DESCRIPTION:
XS GIS Cut Line= 3
      1329904.99      6902388.02      1331225.98      6898437.84
      1330355.00      6897438.00
#Sta/Elev= 30
   834.8 2220.81  1067.3 2207.59  1209.3 2201.76  1389.8 2194.09  1510.8 2189.88
  2047.2 2174.26  2347.3 2168.50  2700.8 2165.00  3112.9 2162.37  3247.5 2162.25
  3593.5 2160.93  4033.3 2154.29  4135.6 2151.75  4230.1 2149.71  4303.9 2156.92
  4514.8 2157.49  4741.1 2152.24  4957.7 2153.91  4977.3 2152.68  4982.1 2146.93
  4982.6 2146.43  5012.5 2146.93  5014.4 2153.24  5106.5 2152.27  5139.9 2157.43
  5271.4 2158.55  5662.0 2163.23  5825.9 2168.67  6198.3 2187.09  6326.0 2200.68
#Mann=20,-1,0
   834.8   0.035       0  1067.3   0.035       0  1209.3    0.07       0
  1389.8   0.035       0  1510.8    0.07       0  2047.2   0.035       0
  2347.3    0.07       0  2700.8   0.035       0  3112.9    0.07       0
  3247.5   0.035       0  3593.5   0.035       0  4033.3    0.07       0
  4135.6   0.035       0  4741.1    0.07       0  4982.1    0.07       0
  5012.5    0.07       0  5139.9   0.035       0  5271.4    0.07       0
  5662.0   0.035       0  5825.9    0.07       0
Bank Sta=4982.1,5012.5
Exp/Cntr=0.3,0.1