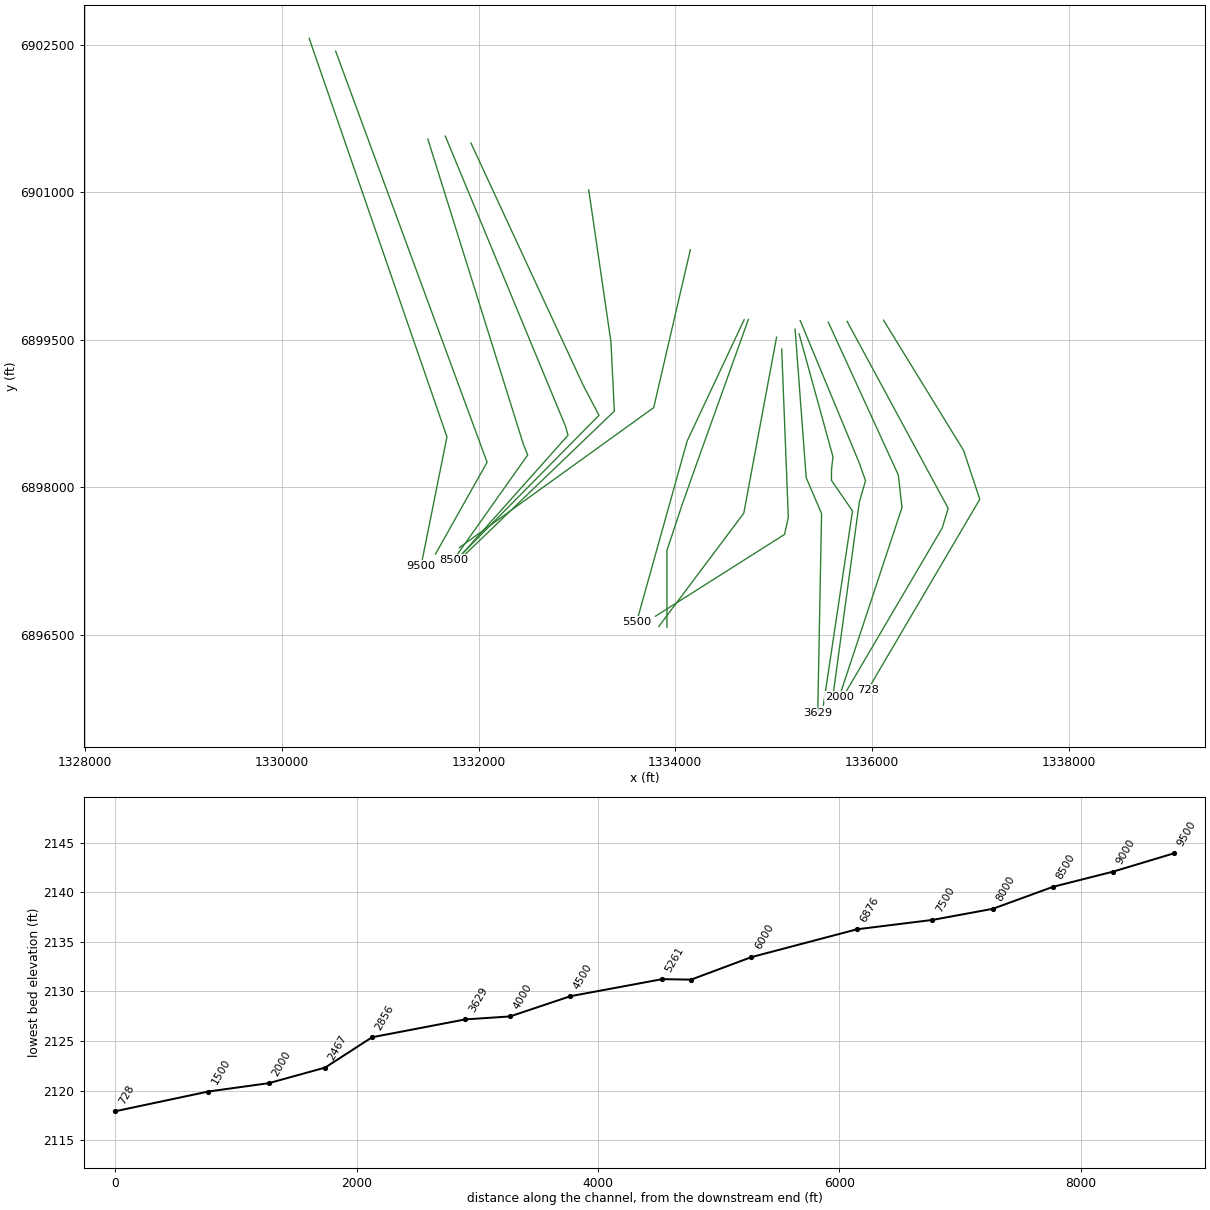
HEC-RAS study Linn Creek.prj: Linn Creek Base Level Engineering

--- Linn Creek.g01 (geometry) --- (continued)

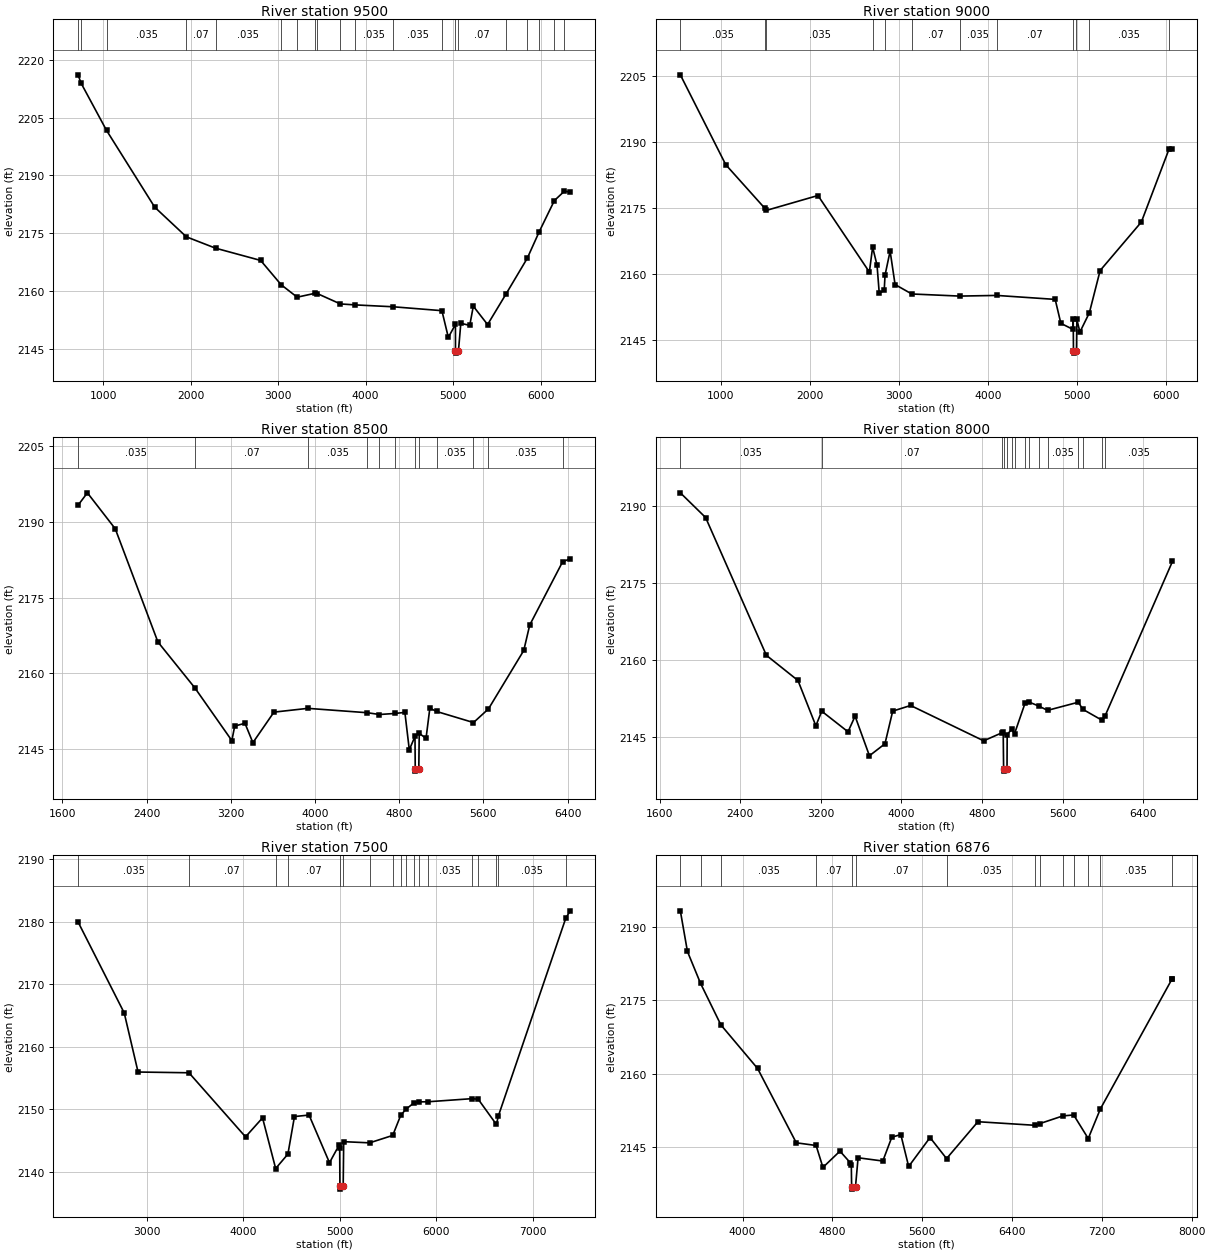
Type RM Length L Ch R = 1,9500,500,500,500
BEGIN DESCRIPTION:
Linn Creek 19.0
END DESCRIPTION:
XS GIS Cut Line= 3
      1330278.17      6902566.30      1331678.94      6898514.18
      1331415.43      6897202.39
#Sta/Elev= 30
   712.6 2216.10   748.4 2213.90  1038.2 2201.70  1589.0 2181.78  1951.1 2174.08
  2284.4 2171.14  2800.0 2167.96  3034.7 2161.65  3217.3 2158.43  3424.0 2159.45
  3446.9 2159.37  3711.1 2156.68  3879.3 2156.43  4315.6 2155.94  4871.6 2154.93
  4945.2 2148.00  5026.7 2151.37  5026.8 2144.42  5027.4 2143.92  5060.6 2144.42
  5087.9 2151.66  5189.9 2151.11  5230.7 2156.09  5393.9 2151.33  5604.0 2159.23
  5847.6 2168.53  5984.7 2175.44  6157.5 2183.49  6273.0 2185.95  6338.0 2185.65
#Mann=20,-1,0
   712.6   0.035       0   748.4    0.07       0  1038.2   0.035       0
  1951.1    0.07       0  2284.4   0.035       0  3034.7    0.07       0
  3217.3   0.035       0  3424.0    0.07       0  3446.9   0.035       0
  3711.1    0.07       0  3879.3   0.035       0  4315.6   0.035       0
  4871.6    0.07       0  5026.8    0.07       0  5060.6    0.07       0
  5604.0   0.035       0  5847.6    0.07       0  5984.7   0.035       0
  6157.5    0.07       0  6273.0   0.035       0
Bank Sta=5026.8,5060.6
Exp/Cntr=0.3,0.1

Type RM Length L Ch R = 1,9000,500,500,500
BEGIN DESCRIPTION:
Linn Creek 18.0
END DESCRIPTION:
XS GIS Cut Line= 3
      1330547.25      6902436.15      1332087.09      6898256.04
      1331562.86      6897323.26
#Sta/Elev= 30
   545.3 2205.23  1054.9 2184.85  1494.5 2174.93  1512.4 2174.48  2090.2 2177.85
  2667.2 2160.49  2703.9 2166.13  2753.3 2162.05  2778.4 2155.63  2834.0 2156.38
  2843.2 2159.78  2900.2 2165.24  2955.8 2157.65  3143.4 2155.51  3680.5 2155.03
  4097.9 2155.18  4753.1 2154.28  4816.7 2148.85  4950.3 2147.50  4955.6 2149.79
  4958.4 2142.59  4959.1 2142.09  4992.3 2142.59  4996.3 2149.75  5030.7 2146.87
  5136.6 2151.23  5257.6 2160.83  5720.4 2171.83  6031.1 2188.37  6070.0 2188.49
#Mann=12,-1,0
   545.3   0.035       0  1494.5    0.07       0  1512.4   0.035       0
  2703.9    0.07       0  2843.2   0.035       0  3143.4    0.07       0
  3680.5   0.035       0  4097.9    0.07       0  4958.4    0.07       0
  4992.3    0.07       0  5136.6   0.035       0  6031.1    0.07       0
Bank Sta=4958.4,4992.3
Exp/Cntr=0.3,0.1

Type RM Length L Ch R = 1,8500,500,500,500
BEGIN DESCRIPTION:
Linn Creek 17.0
END DESCRIPTION:
XS GIS Cut Line= 4
      1331484.75      6901542.07      1332455.87      6898439.19
      1332500.38      6898330.24      1331745.34      6897262.77
#Sta/Elev= 30
  1748.7 2193.32  1837.6 2195.79  2102.5 2188.65  2507.7 2166.19  2858.6 2157.08
  3210.3 2146.61  3237.5 2149.49  3334.9 2150.05  3410.3 2146.20  3610.3 2152.26
  3932.5 2153.01  4498.7 2152.14  4612.9 2151.79  4761.5 2152.00  4854.5 2152.21
  4896.5 2144.79  4950.5 2147.44  4952.9 2141.05  4953.5 2140.55  4986.8 2141.05
  4990.8 2148.07  5055.3 2147.03  5091.7 2153.04  5156.3 2152.39  5506.4 2150.19
  5648.6 2152.90  5984.1 2164.50  6040.7 2169.55  6352.3 2182.07  6425.2 2182.73
#Mann=12,-1,0
  1748.7   0.035       0  2858.6    0.07       0  3932.5   0.035       0
  4498.7    0.07       0  4612.9   0.035       0  4761.5    0.07       0
  4952.9    0.07       0  4986.8    0.07       0  5156.3   0.035       0
  5506.4    0.07       0  5648.6   0.035       0  6352.3    0.07       0
Bank Sta=4952.9,4986.8
Exp/Cntr=0.3,0.1

Type RM Length L Ch R = 1,8000,500,500,500
BEGIN DESCRIPTION:
Linn Creek 16.0
END DESCRIPTION:
XS GIS Cut Line= 4
      1331662.40      6901571.64      1332885.84      6898618.64
      1332910.14      6898530.47      1331844.68      6897335.57
#Sta/Elev= 30
  1803.6 2192.59  2054.8 2187.77  2658.4 2160.91  2972.1 2156.00  3149.7 2147.17
  3208.4 2150.01  3469.2 2146.00  3539.4 2149.04  3682.0 2141.33  3836.1 2143.66
  3913.2 2150.03  4091.2 2151.13  4816.7 2144.24  4999.9 2145.82  5010.8 2145.88
  5014.8 2138.83  5015.5 2138.33  5048.7 2138.83  5050.3 2145.46  5093.6 2146.46
  5123.2 2145.62  5228.1 2151.60  5267.3 2151.80  5362.6 2151.03  5451.6 2150.18
  5757.7 2151.77  5799.9 2150.40  5995.3 2148.22  6021.6 2149.05  6692.4 2179.23
#Mann=15,-1,0
  1803.6   0.035       0  3208.4    0.07       0  4999.9    0.16       0
  5014.8    0.07       0  5048.7    0.16       0  5093.6    0.07       0
  5123.2    0.16       0  5228.1    0.07       0  5267.3    0.16       0
  5362.6    0.07       0  5451.6   0.035       0  5757.7    0.07       0
  5799.9   0.035       0  5995.3    0.07       0  6021.6   0.035       0
Bank Sta=5014.8,5048.7
Exp/Cntr=0.3,0.1

Type RM Length L Ch R = 1,7500,624,624,624
BEGIN DESCRIPTION:
Linn Creek 15.0
END DESCRIPTION:
XS GIS Cut Line= 4
      1331922.80      6901502.24      1333062.45      6899042.97
      1333224.89      6898733.14      1331792.60      6897283.49
#Sta/Elev= 30
  2289.5 2180.00  2768.1 2165.42  2911.4 2155.96  3438.7 2155.84  4024.6 2145.58
  4200.9 2148.62  4336.7 2140.51  4463.6 2142.82  4531.5 2148.83  4682.7 2149.07
  4894.4 2141.44  4997.1 2144.34  5000.0 2143.77  5002.4 2137.71  5003.1 2137.21
  5036.3 2137.71  5041.5 2144.81  5309.8 2144.62  5549.4 2145.81  5632.3 2149.03
  5686.3 2150.00  5773.9 2151.08  5823.1 2151.18  5915.4 2151.20  6365.8 2151.69
  6434.3 2151.62  6623.0 2147.57  6644.3 2148.95  7342.0 2180.59  7387.7 2181.77
#Mann=18,-1,0
  2289.5   0.035       0  3438.7    0.07       0  4336.7    0.16       0
  4463.6    0.07       0  5002.4    0.07       0  5036.3    0.07       0
  5309.8   0.035       0  5549.4    0.07       0  5632.3   0.035       0
  5686.3    0.07       0  5773.9   0.035       0  5823.1    0.07       0
  5915.4   0.035       0  6365.8    0.07       0  6434.3   0.035       0
  6623.0    0.07       0  6644.3   0.035       0  7342.0    0.07       0
Bank Sta=5002.4,5036.3
Exp/Cntr=0.3,0.1

Type RM Length L Ch R = 1,6876,876,876,876
BEGIN DESCRIPTION:
Linn Creek 14.0
END DESCRIPTION:
XS GIS Cut Line= 4
      1333120.72      6901024.77      1333346.41      6899479.66
      1333381.14      6898776.54      1331853.33      6897309.49
#Sta/Elev= 30
  3445.7 2193.41  3509.0 2185.06  3625.6 2178.52  3806.9 2169.99  4133.6 2161.05
  4478.4 2145.78  4655.0 2145.23  4715.8 2140.73  4867.4 2144.07  4958.1 2141.72
  4968.5 2141.29  4971.4 2136.77  4972.2 2136.27  5005.9 2136.77  5028.9 2142.71
  5249.2 2142.04  5329.3 2146.93  5409.4 2147.47  5479.4 2140.92  5669.7 2146.86
  5817.0 2142.54  6096.3 2150.11  6607.4 2149.37  6647.2 2149.72  6852.4 2151.30
  6949.0 2151.50  7078.8 2146.66  7186.9 2152.74  7827.3 2179.50  7829.3 2179.50
#Mann=14,-1,0
  3445.7   0.035       0  3625.6    0.07       0  3806.9   0.035       0
  4655.0    0.07       0  4971.4    0.07       0  5005.9    0.07       0
  5817.0   0.035       0  6607.4    0.07       0  6647.2   0.035       0
  6852.4    0.07       0  6949.0   0.035       0  7078.8    0.07       0
  7186.9   0.035       0  7827.3    0.07       0
Bank Sta=4971.4,5005.9
Exp/Cntr=0.3,0.1

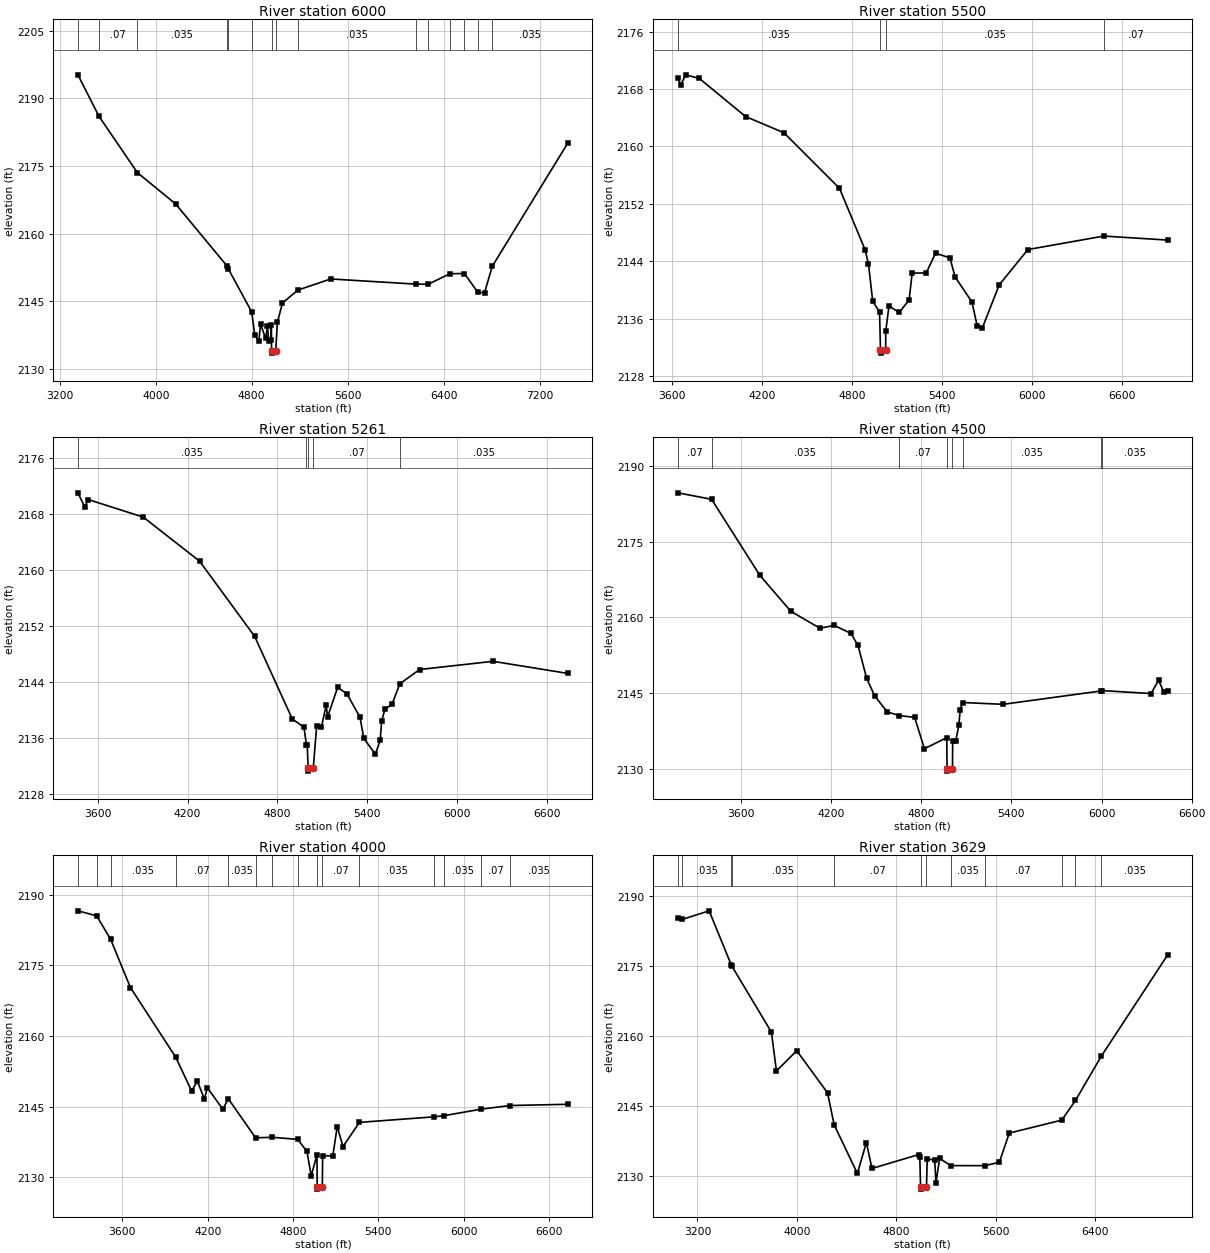
Type RM Length L Ch R = 1,6000,500,500,500
BEGIN DESCRIPTION:
Linn Creek 12.0
END DESCRIPTION:
XS GIS Cut Line= 3
      1334153.70      6900417.14      1333781.12      6898811.50
      1331805.04      6897388.03
#Sta/Elev= 30
  3351.7 2195.22  3526.1 2186.07  3847.5 2173.51  4165.7 2166.58  4591.4 2152.90
  4603.9 2152.23  4800.3 2142.60  4826.0 2137.47  4859.9 2136.06  4873.8 2139.91
  4916.4 2136.72  4931.7 2139.41  4942.0 2136.14  4959.1 2136.40  4964.2 2139.66
  4965.8 2133.96  4966.5 2133.46  5000.4 2133.96  5014.1 2140.28  5056.8 2144.59
  5185.2 2147.45  5458.4 2149.92  6165.6 2148.78  6272.2 2148.75  6451.9 2151.08
  6573.1 2151.13  6685.3 2146.95  6740.8 2146.85  6804.9 2152.70  7435.4 2180.11
#Mann=15,-1,0
  3351.7   0.035       0  3526.1    0.07       0  3847.5   0.035       0
  4591.4    0.07       0  4603.9   0.035       0  4800.3    0.07       0
  4965.8    0.07       0  5000.4    0.07       0  5185.2   0.035       0
  6165.6    0.07       0  6272.2   0.035       0  6451.9    0.07       0
  6573.1   0.035       0  6685.3    0.07       0  6804.9   0.035       0
Bank Sta=4965.8,5000.4
Exp/Cntr=0.3,0.1

Type RM Length L Ch R = 1,5500,239,239,239
BEGIN DESCRIPTION:
Linn Creek 11.0
END DESCRIPTION:
XS GIS Cut Line= 3
      1334700.59      6899705.38      1334121.37      6898472.23
      1333608.56      6896635.89
#Sta/Elev= 30
  3637.6 2169.56  3656.8 2168.56  3690.7 2169.99  3782.0 2169.48  4089.5 2164.18
  4346.0 2161.91  4716.4 2154.17  4887.1 2145.62  4910.0 2143.63  4938.4 2138.40
  4983.9 2136.93  4990.0 2131.69  4990.8 2131.19  5024.6 2131.69  5025.2 2134.26
  5046.7 2137.75  5115.0 2136.86  5180.9 2138.59  5201.7 2142.35  5295.1 2142.37
  5357.4 2145.12  5453.6 2144.47  5487.8 2141.81  5600.7 2138.30  5634.8 2135.04
  5668.9 2134.66  5781.9 2140.69  5973.5 2145.63  6479.7 2147.51  6906.6 2146.95
#Mann=4,-1,0
  3637.6   0.035       0  4990.0   0.035       0  5024.6   0.035       0
  6479.7    0.07       0
Bank Sta=4990,5024.6
Exp/Cntr=0.3,0.1

Type RM Length L Ch R = 1,5261,761,761,761
BEGIN DESCRIPTION:
Linn Creek 10.0
END DESCRIPTION:
XS GIS Cut Line= 5
      1334743.99      6899708.84      1334228.36      6898271.33
      1334069.87      6897823.85      1333915.86      6897359.87
      1333915.86      6896578.65
#Sta/Elev= 30
  3467.7 2170.98  3512.8 2168.99  3538.2 2170.01  3904.2 2167.51  4280.3 2161.22
  4647.8 2150.49  4899.3 2138.69  4977.2 2137.51  4994.2 2134.94  4999.3 2134.94
  5005.1 2131.74  5005.9 2131.24  5039.7 2131.74  5062.1 2137.66  5093.9 2137.53
  5125.7 2140.65  5135.4 2139.00  5202.5 2143.20  5264.2 2142.28  5351.6 2138.92
  5377.2 2135.90  5454.6 2133.65  5486.3 2135.66  5496.3 2138.39  5517.9 2140.08
  5564.9 2140.77  5617.4 2143.71  5749.7 2145.75  6240.3 2146.92  6739.7 2145.19
#Mann=5,-1,0
  3467.7   0.035       0  4994.2    0.07       0  5005.1    0.07       0
  5039.7    0.07       0  5617.4   0.035       0
Bank Sta=5005.1,5039.7
Exp/Cntr=0.3,0.1

Type RM Length L Ch R = 1,4500,500,500,500
BEGIN DESCRIPTION:
Linn Creek 9.0
END DESCRIPTION:
XS GIS Cut Line= 3
      1335030.43      6899528.24      1334697.03      6897737.92
      1333832.51      6896585.55
#Sta/Elev= 30
  3178.9 2184.72  3404.0 2183.44  3725.4 2168.35  3931.9 2161.21  4125.1 2157.87
  4220.4 2158.42  4331.0 2156.85  4378.6 2154.47  4436.5 2147.90  4489.2 2144.48
  4572.7 2141.27  4653.2 2140.55  4755.8 2140.17  4820.9 2133.97  4969.4 2136.16
  4971.7 2130.02  4972.6 2129.52  5007.7 2130.02  5008.9 2135.59  5029.8 2135.58
  5050.6 2138.72  5058.9 2141.71  5074.4 2143.13  5344.3 2142.77  5998.7 2145.43
  6006.2 2145.49  6329.7 2144.91  6379.7 2147.55  6415.1 2145.17  6440.6 2145.46
#Mann=8,-1,0
  3178.9    0.07       0  3404.0   0.035       0  4653.2    0.07       0
  4971.7    0.07       0  5007.7    0.07       0  5074.4   0.035       0
  5998.7    0.07       0  6006.2   0.035       0
Bank Sta=4971.7,5007.7
Exp/Cntr=0.3,0.1

Type RM Length L Ch R = 1,4000,371,371,371
BEGIN DESCRIPTION:
Linn Creek 8.0
END DESCRIPTION:
XS GIS Cut Line= 4
      1335082.52      6899406.77      1335149.80      6897695.69
      1335111.55      6897522.41      1333798.87      6896690.41
#Sta/Elev= 30
  3287.6 2186.56  3419.6 2185.49  3517.5 2180.51  3656.7 2170.28  3975.7 2155.46
  4087.0 2148.30  4127.0 2150.41  4177.1 2146.60  4197.1 2149.02  4307.2 2144.40
  4343.9 2146.70  4536.6 2138.38  4654.8 2138.48  4832.7 2138.04  4897.6 2135.48
  4927.6 2130.31  4967.7 2134.70  4969.7 2127.98  4970.5 2127.48  5005.7 2127.98
  5007.9 2134.58  5079.6 2134.53  5110.3 2140.75  5151.2 2136.52  5266.5 2141.65
  5788.7 2142.82  5860.8 2143.07  6124.1 2144.47  6327.0 2145.23  6731.6 2145.49
#Mann=15,-1,0
  3287.6   0.035       0  3419.6    0.07       0  3517.5   0.035       0
  3975.7    0.07       0  4343.9   0.035       0  4536.6    0.07       0
  4654.8   0.035       0  4832.7    0.07       0  4969.7    0.07       0
  5005.7    0.07       0  5266.5   0.035       0  5788.7    0.07       0
  5860.8   0.035       0  6124.1    0.07       0  6327.0   0.035       0
Bank Sta=4969.7,5005.7
Exp/Cntr=0.3,0.1

Type RM Length L Ch R = 1,3629,773,773,773
BEGIN DESCRIPTION:
Linn Creek 7.0
END DESCRIPTION:
XS GIS Cut Line= 4
      1335218.77      6899609.70      1335331.62      6898099.31
      1335487.87      6897734.73      1335449.03      6895702.86
#Sta/Elev= 30
  3041.6 2185.24  3079.1 2185.04  3294.0 2186.87  3471.0 2175.34  3477.4 2174.99
  3795.4 2160.85  3835.5 2152.52  3999.3 2156.87  4246.7 2147.83  4300.6 2140.95
  4487.3 2130.54  4559.6 2137.18  4604.7 2131.61  4979.6 2134.58  4989.6 2134.06
  4995.7 2127.68  4996.7 2127.18  5043.4 2127.68  5049.6 2133.72  5109.6 2133.36
  5119.6 2128.60  5149.6 2133.77  5237.6 2132.23  5511.9 2132.21  5629.7 2132.93
  5709.7 2139.20  6132.3 2141.98  6242.3 2146.19  6450.7 2155.69  6985.1 2177.44
#Mann=12,-1,0
  3041.6    0.07       0  3079.1   0.035       0  3471.0    0.07       0
  3477.4   0.035       0  4300.6    0.07       0  4995.7    0.07       0
  5043.4    0.07       0  5237.6   0.035       0  5511.9    0.07       0
  6132.3   0.035       0  6242.3    0.07       0  6450.7   0.035       0
Bank Sta=4995.7,5043.4
Exp/Cntr=0.3,0.1

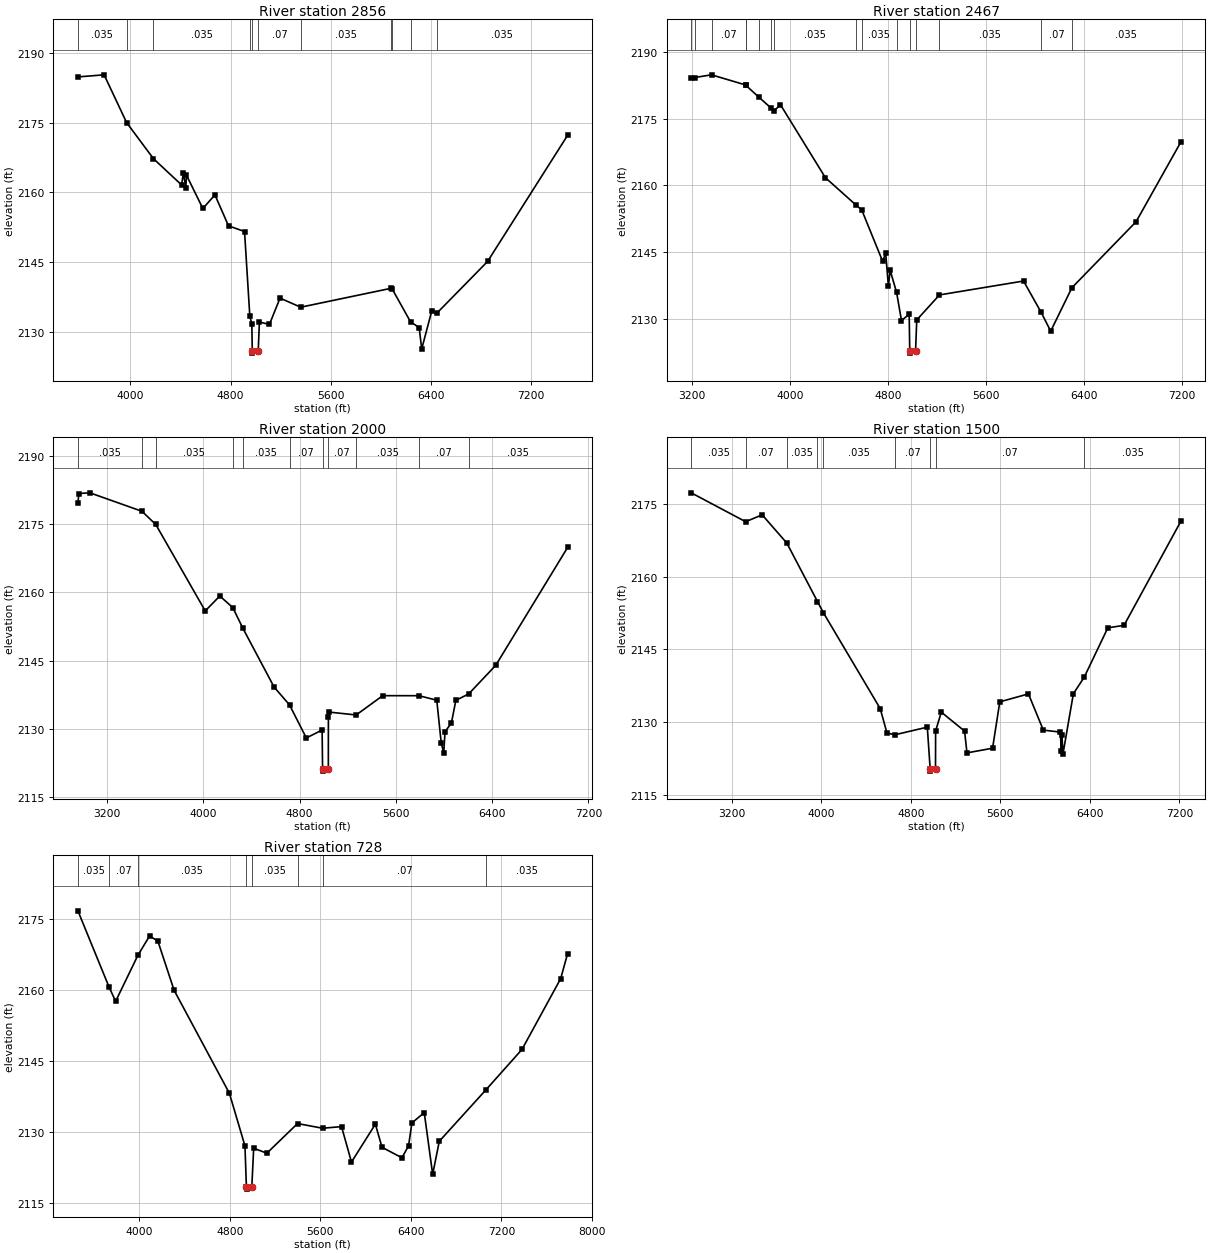
Type RM Length L Ch R = 1,2856,389,389,389
BEGIN DESCRIPTION:
Linn Creek 6.0
END DESCRIPTION:
XS GIS Cut Line= 6
      1335260.01      6899559.79      1335603.68      6898312.27
      1335588.93      6898179.46      1335588.06      6898072.69
      1335802.54      6897760.77      1335506.32      6895786.10
#Sta/Elev= 30
  3580.9 2184.87  3790.2 2185.32  3970.0 2175.02  4184.2 2167.26  4408.3 2161.61
  4422.9 2164.10  4442.7 2161.01  4447.9 2163.70  4578.5 2156.53  4674.9 2159.46
  4783.3 2152.80  4911.3 2151.57  4953.4 2133.41  4969.7 2131.59  4973.0 2125.88
  4974.0 2125.38  5020.7 2125.88  5030.0 2132.08  5110.0 2131.56  5194.6 2137.23
  5359.6 2135.27  6082.8 2139.35  6091.4 2139.14  6236.5 2132.12  6305.6 2130.88
  6325.8 2126.27  6406.7 2134.54  6448.9 2134.04  6851.6 2145.12  7490.6 2172.29
#Mann=11,-1,0
  3580.9   0.035       0  3970.0    0.07       0  4184.2   0.035       0
  4953.4    0.07       0  4973.0    0.07       0  5020.7    0.07       0
  5359.6   0.035       0  6082.8    0.07       0  6091.4   0.035       0
  6236.5    0.07       0  6448.9   0.035       0
Bank Sta=4973,5020.7
Exp/Cntr=0.3,0.1

Type RM Length L Ch R = 1,2467,467,467,467
BEGIN DESCRIPTION:
Linn Creek 5.0
END DESCRIPTION:
XS GIS Cut Line= 5
      1335270.84      6899696.57      1335871.98      6898246.88
      1335934.92      6898068.93      1335871.98      6897851.91
      1335600.07      6895853.83
#Sta/Elev= 30
  3192.3 2184.18  3219.1 2184.24  3358.3 2184.85  3636.7 2182.57  3638.2 2182.50
  3742.9 2179.88  3847.7 2177.31  3868.9 2176.76  3921.3 2178.13  4288.1 2161.75
  4542.3 2155.49  4585.2 2154.50  4755.8 2142.96  4781.1 2144.73  4802.9 2137.39
  4817.3 2140.94  4869.7 2135.99  4910.0 2129.64  4972.8 2131.05  4977.3 2122.82
  4978.3 2122.32  5025.0 2122.82  5034.7 2129.78  5220.3 2135.40  5907.0 2138.52
  6051.0 2131.48  6129.0 2127.26  6302.3 2137.02  6826.5 2151.84  7192.9 2169.79
#Mann=16,-1,0
  3192.3    0.07       0  3219.1   0.035       0  3358.3    0.07       0
  3636.7   0.035       0  3638.2    0.07       0  3742.9   0.035       0
  3847.7    0.07       0  3868.9   0.035       0  4542.3    0.07       0
  4585.2   0.035       0  4869.7    0.07       0  4977.3    0.07       0
  5025.0    0.07       0  5220.3   0.035       0  6051.0    0.07       0
  6302.3   0.035       0
Bank Sta=4977.3,5025
Exp/Cntr=0.3,0.1

Type RM Length L Ch R = 1,2000,500,500,500
BEGIN DESCRIPTION:
Linn Creek 4.0
END DESCRIPTION:
XS GIS Cut Line= 4
      1335556.65      6899679.79      1336268.47      6898125.93
      1336305.51      6897795.64      1335668.35      6895871.17
#Sta/Elev= 30
  2958.5 2179.55  2966.3 2181.71  3058.3 2181.86  3490.4 2177.81  3605.5 2174.91
  4016.4 2155.93  4137.4 2159.20  4245.3 2156.67  4328.2 2152.17  4588.4 2139.22
  4717.1 2135.28  4856.3 2128.03  4987.6 2129.78  4991.5 2121.25  4992.5 2120.75
  5039.3 2121.25  5039.7 2132.64  5047.1 2133.71  5270.6 2133.08  5491.1 2137.32
  5792.8 2137.31  5940.2 2136.32  5977.2 2126.94  5998.2 2124.79  6008.9 2129.43
  6061.4 2131.27  6098.8 2136.29  6205.3 2137.70  6430.1 2143.98  7027.2 2169.86
#Mann=11,-1,0
  2958.5   0.035       0  3490.4    0.07       0  3605.5   0.035       0
  4245.3    0.07       0  4328.2   0.035       0  4717.1    0.07       0
  4991.5    0.07       0  5039.3    0.07       0  5270.6   0.035       0
  5792.8    0.07       0  6205.3   0.035       0
Bank Sta=4991.5,5039.3
Exp/Cntr=0.3,0.1

Type RM Length L Ch R = 1,1500,772,772,772
BEGIN DESCRIPTION:
Linn Creek 3.0
END DESCRIPTION:
XS GIS Cut Line= 4
      1335747.63      6899688.45      1336775.23      6897787.64
      1336714.65      6897588.17      1335699.50      6895859.81
#Sta/Elev= 30
  2839.2 2177.24  3325.3 2171.29  3472.8 2172.71  3693.1 2166.88  3966.9 2154.84
  4019.5 2152.54  4527.1 2132.79  4587.1 2127.78  4656.5 2127.39  4947.7 2128.97
  4973.1 2120.41  4974.1 2119.91  5020.9 2120.41  5021.9 2128.20  5072.8 2132.06
  5280.5 2128.16  5301.9 2123.67  5530.6 2124.63  5595.0 2134.18  5850.9 2135.82
  5983.8 2128.36  6136.4 2127.95  6144.0 2124.02  6149.8 2127.35  6159.6 2123.48
  6252.4 2135.87  6349.4 2139.27  6560.0 2149.43  6704.7 2149.94  7212.9 2171.41
#Mann=9,-1,0
  2839.2   0.035       0  3325.3    0.07       0  3693.1   0.035       0
  3966.9    0.07       0  4019.5   0.035       0  4656.5    0.07       0
  4973.1    0.07       0  5020.9    0.07       0  6349.4   0.035       0
Bank Sta=4973.1,5020.9
Exp/Cntr=0.3,0.1

Type RM Length L Ch R = 1,728,0,0,0
BEGIN DESCRIPTION:
Linn Creek 2.0
END DESCRIPTION:
XS GIS Cut Line= 4
      1336117.85      6899700.60      1336931.66      6898376.80
      1337096.59      6897879.84      1335957.90      6895942.68
#Sta/Elev= 30
  3459.3 2176.74  3734.6 2160.62  3792.5 2157.62  3988.6 2167.31  4091.9 2171.42
  4165.3 2170.36  4308.5 2159.97  4797.3 2138.17  4934.6 2127.05  4947.4 2118.42
  4948.4 2117.92  4995.2 2118.42  5011.7 2126.57  5127.9 2125.51  5399.0 2131.78
  5620.2 2130.79  5787.5 2131.13  5875.4 2123.64  6086.3 2131.65  6144.9 2126.76
  6320.7 2124.55  6379.3 2127.06  6409.0 2131.91  6518.0 2134.09  6592.3 2121.05
  6650.9 2128.04  7064.7 2138.96  7381.3 2147.45  7723.0 2162.42  7783.9 2167.71
#Mann=8,-1,0
  3459.3   0.035       0  3734.6    0.07       0  3988.6   0.035       0
  4947.4    0.07       0  4995.2   0.035       0  5399.0   0.035       0
  5620.2    0.07       0  7064.7   0.035       0
Bank Sta=4947.4,4995.2
Exp/Cntr=0.3,0.1

Chan Stop Cuts=-1