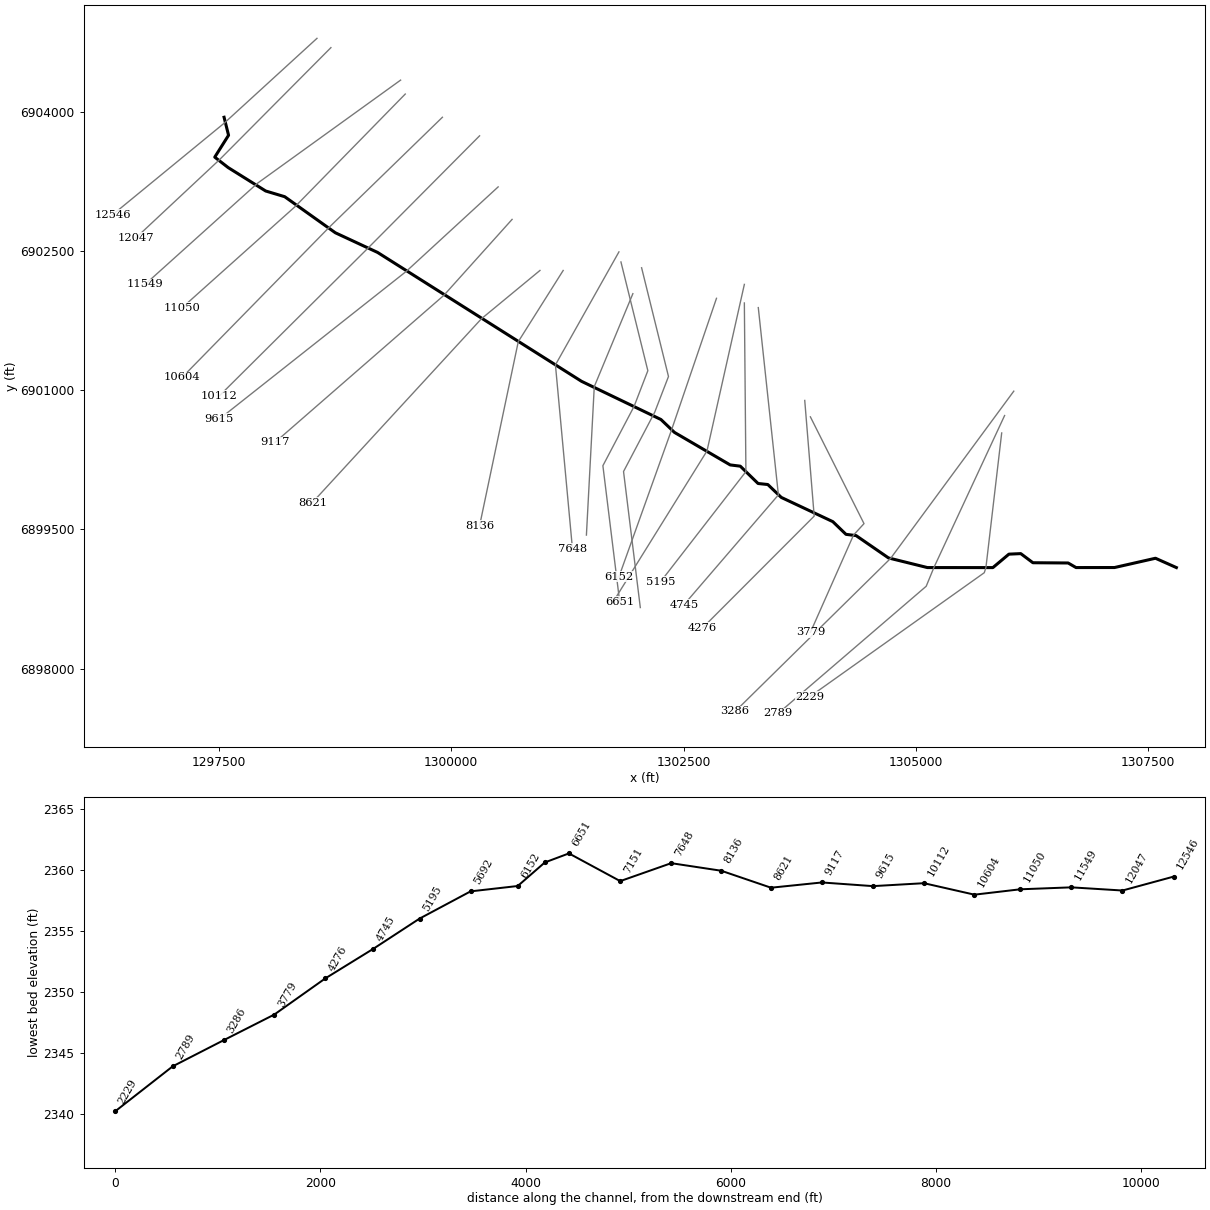
--- Linn Creek Trib052.prj (project) ---

Proj Title=Linn Creek Trib052 Base Level Engineering
Current Plan=p01
Default Exp/Contr=0.3,0.1
English Units
Geom File=g01
Flow File=f01
Plan File=p01
BEGIN DESCRIPTION:
Linn Creek Trib052
END DESCRIPTION:

--- Linn Creek Trib052.p01 (plan) ---

Plan Title=Multiple Run
Short Identifier=Multiple
Geom File=g01
Flow File=f01
Subcritical Flow
K Sum by GR= 0
Std Step Tol= 0.01
Critical Tol= 0.01
Num of Std Step Trials= 20
Max Error Tol= 0.3
Flow Tol Ratio= 0.001
Split Flow NTrial= 30
Split Flow Tol= 0.02
Split Flow Ratio= 0.02
Log Output Level= 0
Friction Slope Method= 1
Unsteady Friction Slope Method= 2
Unsteady Bridges Friction Slope Method= 1
Parabolic Critical Depth
Global Vel Dist=  1 , 1 , 1
Global Log Level= 0
CheckData=True
Encroach Param= -1, 0, 0, 0
BEGIN DESCRIPTION:
Multiple Run
END DESCRIPTION:

--- Linn Creek Trib052.f01 (steady flow) ---

Flow Title=Multiple
Number of Profiles=7
Profile Names=10-year,25-year,50-year,1pct_min,100-year,1pct_plu,500-year
River Rch & RM= Linn Creek Trib0,Reach-1,12546
     190     260     316     191     382     762     563
River Rch & RM= Linn Creek Trib0,Reach-1,11549
     296     414     511     313     624    1245     946
River Rch & RM= Linn Creek Trib0,Reach-1,9615
     330     463     573     351     701    1399    1066
River Rch & RM= Linn Creek Trib0,Reach-1,8621
     417     587     728     447     892    1780    1358
River Rch & RM= Linn Creek Trib0,Reach-1,3286
     650     940    1187     742    1481    2954    2336
Boundary for River Rch & Prof#=Linn Creek Trib0,Reach-1,1
Up Type=0
Dn Type=3
Dn Slope=0.005
Boundary for River Rch & Prof#=Linn Creek Trib0,Reach-1,2
Up Type=0
Dn Type=3
Dn Slope=0.005
Boundary for River Rch & Prof#=Linn Creek Trib0,Reach-1,3
Up Type=0
Dn Type=3
Dn Slope=0.005
Boundary for River Rch & Prof#=Linn Creek Trib0,Reach-1,4
Up Type=0
Dn Type=3
Dn Slope=0.005
Boundary for River Rch & Prof#=Linn Creek Trib0,Reach-1,5
Up Type=0
Dn Type=3
Dn Slope=0.005
Boundary for River Rch & Prof#=Linn Creek Trib0,Reach-1,6
Up Type=0
Dn Type=3
Dn Slope=0.005
Boundary for River Rch & Prof#=Linn Creek Trib0,Reach-1,7
Up Type=0
Dn Type=3
Dn Slope=0.005

--- Linn Creek Trib052.g01 (geometry) ---

Geom Title=Existing Conditions

River Reach=Linn Creek Trib0,Reach-1
Reach XY= 30
      1297555.00      6903938.00      1297603.21      6903744.11
      1297454.61      6903508.37      1297598.95      6903396.16
      1298002.71      6903143.84      1298207.43      6903082.48
      1298752.71      6902693.85      1299207.29      6902482.15
      1301402.71      6901093.85      1302257.43      6900682.48
      1302402.70      6900543.83      1303002.58      6900193.54
      1303111.17      6900180.14      1303302.57      6899993.52
      1303407.43      6899982.48      1303552.57      6899843.52
      1304107.43      6899582.48      1304248.83      6899445.86
      1304357.43      6899432.48      1304706.55      6899191.75
      1305125.03      6899088.07      1305830.12      6899087.70
      1306002.55      6899232.55      1306130.11      6899238.32
      1306260.86      6899140.07      1306639.78      6899137.48
      1306725.03      6899088.07      1307139.78      6899088.52
      1307580.00      6899188.40      1307805.00      6899088.00

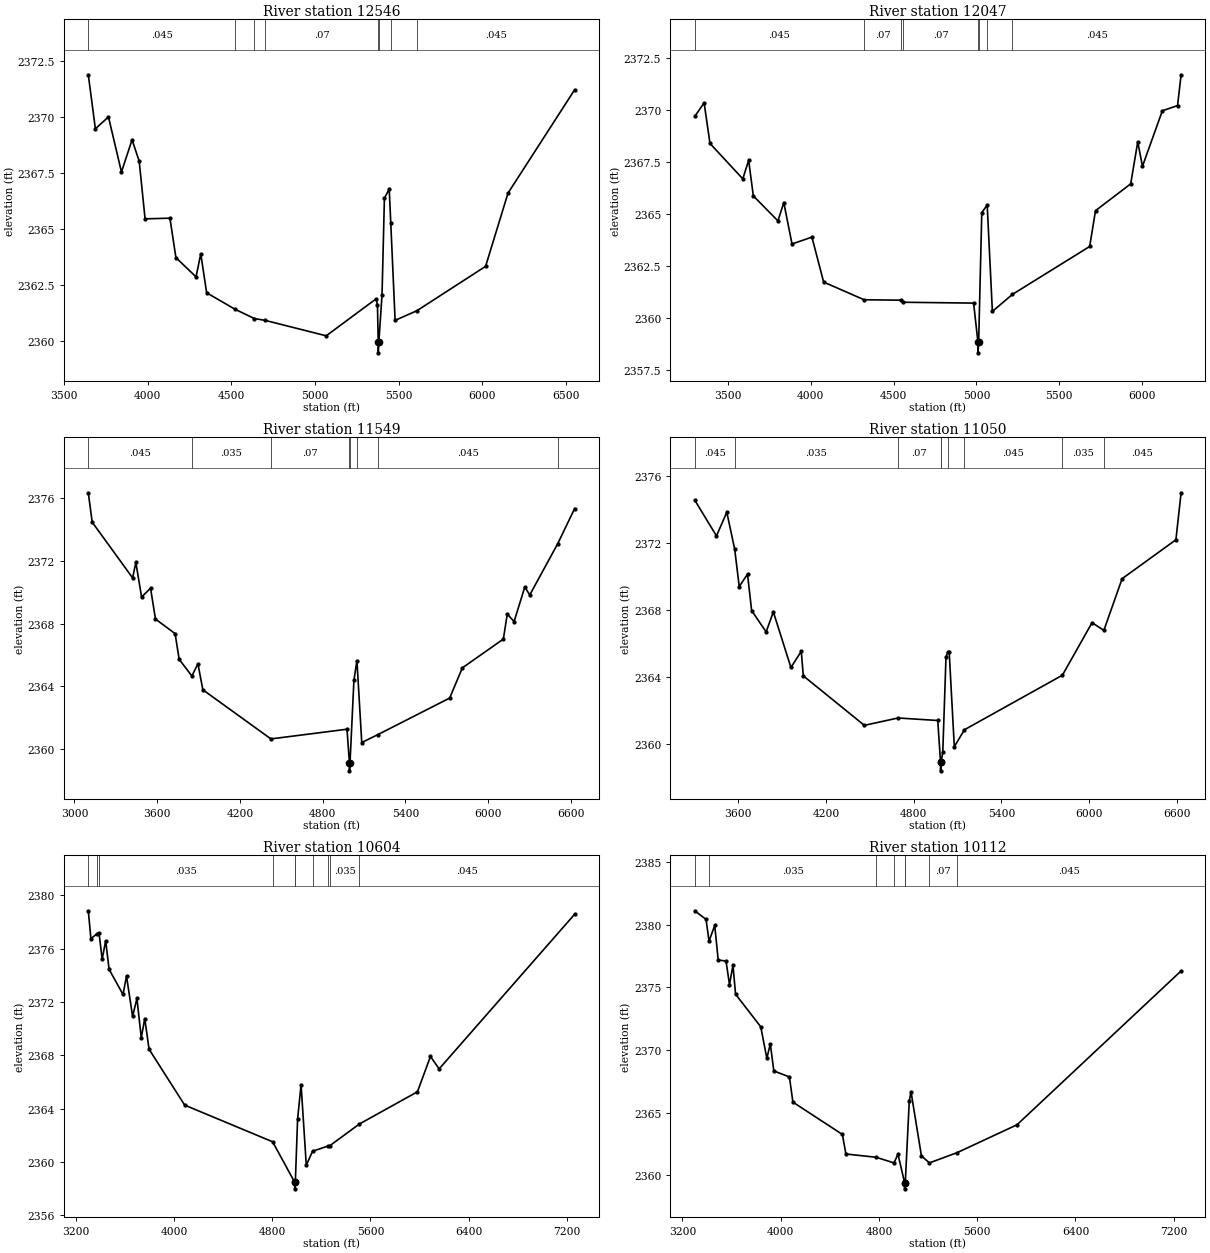
Type RM Length L Ch R = 1,12546,499,499,499
BEGIN DESCRIPTION:
Linn Creek Trib052 22.0
END DESCRIPTION:
XS GIS Cut Line= 3
      1298555.03      6904788.03      1297554.30      6903872.70
      1296354.97      6902887.97
#Sta/Elev= 30
  3643.8 2371.88  3686.1 2369.47  3764.4 2370.00  3842.1 2367.54  3905.6 2368.98
  3948.2 2368.02  3983.3 2365.45  4131.9 2365.48  4167.7 2363.72  4288.0 2362.86
  4316.3 2363.89  4351.5 2362.15  4519.9 2361.42  4636.8 2361.00  4700.6 2360.92
  5066.4 2360.23  5364.9 2361.88  5372.8 2361.62  5377.3 2359.97  5377.5 2359.47
  5381.3 2359.97  5400.2 2362.07  5414.4 2366.37  5443.1 2366.78  5452.4 2365.27
  5478.3 2360.92  5608.8 2361.35  6019.3 2363.33  6153.5 2366.60  6551.8 2371.21
#Mann=8,-1,0
  3643.8   0.045       0  4519.9    0.07       0  4636.8   0.045       0
  4700.6    0.07       0  5377.3    0.07       0  5381.3    0.07       0
  5452.4   0.035       0  5608.8   0.045       0
Bank Sta=5377.3,5381.3
Exp/Cntr=0.3,0.1

Type RM Length L Ch R = 1,12047,498,498,498
BEGIN DESCRIPTION:
Linn Creek Trib052 21.0
END DESCRIPTION:
XS GIS Cut Line= 3
      1298704.98      6904687.98      1297506.82      6903481.99
      1296604.97      6902637.97
#Sta/Elev= 30
  3300.0 2369.69  3356.5 2370.34  3391.9 2368.39  3589.9 2366.69  3625.2 2367.58
  3653.5 2365.87  3802.0 2364.67  3837.4 2365.55  3886.9 2363.56  4007.1 2363.89
  4077.8 2361.73  4322.1 2360.88  4546.4 2360.86  4559.6 2360.76  4982.9 2360.72
  5009.3 2358.83  5009.5 2358.33  5013.3 2358.83  5032.3 2365.07  5064.9 2365.43
  5096.2 2360.32  5217.5 2361.14  5683.4 2363.44  5718.6 2365.16  5931.1 2366.45
  5973.6 2368.47  6001.9 2367.29  6122.1 2369.96  6213.9 2370.21  6235.2 2371.69
#Mann=8,-1,0
  3300.0   0.045       0  4322.1    0.07       0  4546.4   0.045       0
  4559.6    0.07       0  5009.3    0.07       0  5013.3    0.07       0
  5064.9   0.035       0  5217.5   0.045       0
Bank Sta=5009.3,5013.3
Exp/Cntr=0.3,0.1

Type RM Length L Ch R = 1,11549,499,499,499
BEGIN DESCRIPTION:
Linn Creek Trib052 20.0
END DESCRIPTION:
XS GIS Cut Line= 3
      1299455.02      6904338.01      1297914.67      6903227.20
      1296704.98      6902137.98
#Sta/Elev= 30
  3100.9 2376.36  3129.2 2374.48  3422.4 2370.92  3445.7 2371.91  3487.4 2369.70
  3552.5 2370.26  3588.0 2368.29  3730.4 2367.36  3759.8 2365.72  3852.2 2364.65
  3896.0 2365.43  3931.6 2363.77  4425.2 2360.63  4977.0 2361.25  4994.7 2359.09
  4994.9 2358.59  4998.8 2359.09  5027.2 2364.38  5049.1 2365.63  5084.0 2360.40
  5202.0 2360.91  5721.5 2363.24  5813.5 2365.17  6110.9 2367.01  6139.3 2368.61
  6188.7 2368.13  6266.4 2370.34  6302.3 2369.83  6504.2 2373.09  6627.8 2375.35
#Mann=8,-1,0
  3100.9   0.045       0  3852.2   0.035       0  4425.2    0.07       0
  4994.7    0.07       0  4998.8    0.07       0  5049.1   0.035       0
  5202.0   0.045       0  6504.2   0.035       0
Bank Sta=4994.7,4998.8
Exp/Cntr=0.3,0.1

Type RM Length L Ch R = 1,11050,446,446,446
BEGIN DESCRIPTION:
Linn Creek Trib052 19.0
END DESCRIPTION:
XS GIS Cut Line= 3
      1299504.99      6904187.99      1298318.19      6902974.32
      1297104.98      6901887.98
#Sta/Elev= 30
  3302.5 2374.56  3451.0 2372.43  3521.7 2373.84  3575.9 2371.62  3606.6 2369.41
  3663.2 2370.15  3691.5 2367.98  3790.5 2366.71  3839.9 2367.90  3960.1 2364.59
  4030.8 2365.55  4044.9 2364.09  4462.3 2361.14  4692.7 2361.58  4964.3 2361.43
  4983.4 2358.93  4983.6 2358.43  4987.6 2358.93  4998.7 2359.56  5020.7 2365.22
  5032.3 2365.49  5042.4 2365.53  5077.5 2359.87  5147.0 2360.88  5816.9 2364.13
  6019.5 2367.26  6100.3 2366.80  6225.1 2369.88  6593.0 2372.20  6628.5 2375.00
#Mann=9,-1,0
  3302.5   0.045       0  3575.9   0.035       0  4692.7    0.07       0
  4983.4    0.07       0  4987.6    0.07       0  5032.3   0.035       0
  5147.0   0.045       0  5816.9   0.035       0  6100.3   0.045       0
Bank Sta=4983.4,4987.6
Exp/Cntr=0.3,0.1

Type RM Length L Ch R = 1,10604,492,492,492
BEGIN DESCRIPTION:
Linn Creek Trib052 18.0
END DESCRIPTION:
XS GIS Cut Line= 3
      1299904.98      6903937.98      1298688.45      6902754.95
      1297104.97      6901137.97
#Sta/Elev= 30
  3303.1 2378.85  3324.3 2376.76  3372.6 2377.11  3390.3 2377.19  3416.1 2375.21
  3444.4 2376.60  3472.7 2374.45  3585.9 2372.57  3614.2 2373.95  3663.8 2370.93
  3699.1 2372.27  3734.5 2369.32  3762.8 2370.76  3798.1 2368.46  4088.0 2364.27
  4804.1 2361.52  4983.5 2358.49  4983.9 2357.99  4988.9 2358.49  5007.4 2363.22
  5035.7 2365.81  5078.1 2359.76  5129.2 2360.81  5252.2 2361.19  5271.9 2361.24
  5509.9 2362.85  5983.2 2365.27  6089.2 2367.92  6160.0 2366.99  7263.2 2378.59
#Mann=10,-1,0
  3303.1   0.035       0  3372.6    0.07       0  3390.3   0.035       0
  4804.1    0.07       0  4983.5    0.07       0  4988.9    0.07       0
  5129.2   0.035       0  5252.2   0.045       0  5271.9   0.035       0
  5509.9   0.045       0
Bank Sta=4983.5,4988.9
Exp/Cntr=0.3,0.1

Type RM Length L Ch R = 1,10112,497,497,497
BEGIN DESCRIPTION:
Linn Creek Trib052 17.0
END DESCRIPTION:
XS GIS Cut Line= 3
      1300304.99      6903737.99      1299107.20      6902531.92
      1297505.00      6900938.00
#Sta/Elev= 30
  3300.2 2381.12  3392.1 2380.43  3416.5 2378.70  3462.8 2379.95  3491.1 2377.19
  3554.7 2377.11  3583.0 2375.23  3611.3 2376.77  3632.5 2374.46  3837.6 2371.86
  3887.1 2369.35  3915.4 2370.50  3943.7 2368.34  4070.9 2367.86  4099.2 2365.85
  4502.3 2363.27  4530.6 2361.71  4776.6 2361.45  4922.2 2361.00  4954.8 2361.69
  5008.4 2359.43  5008.9 2358.93  5014.4 2359.43  5046.7 2365.93  5060.9 2366.68
  5145.7 2361.56  5210.7 2361.00  5436.8 2361.82  5923.6 2364.04  7260.0 2376.32
#Mann=8,-1,0
  3300.2    0.07       0  3416.5   0.035       0  4776.6    0.07       0
  4922.2   0.094       0  5008.4    0.07       0  5014.4   0.094       0
  5210.7    0.07       0  5436.8   0.045       0
Bank Sta=5008.4,5014.4
Exp/Cntr=0.3,0.1

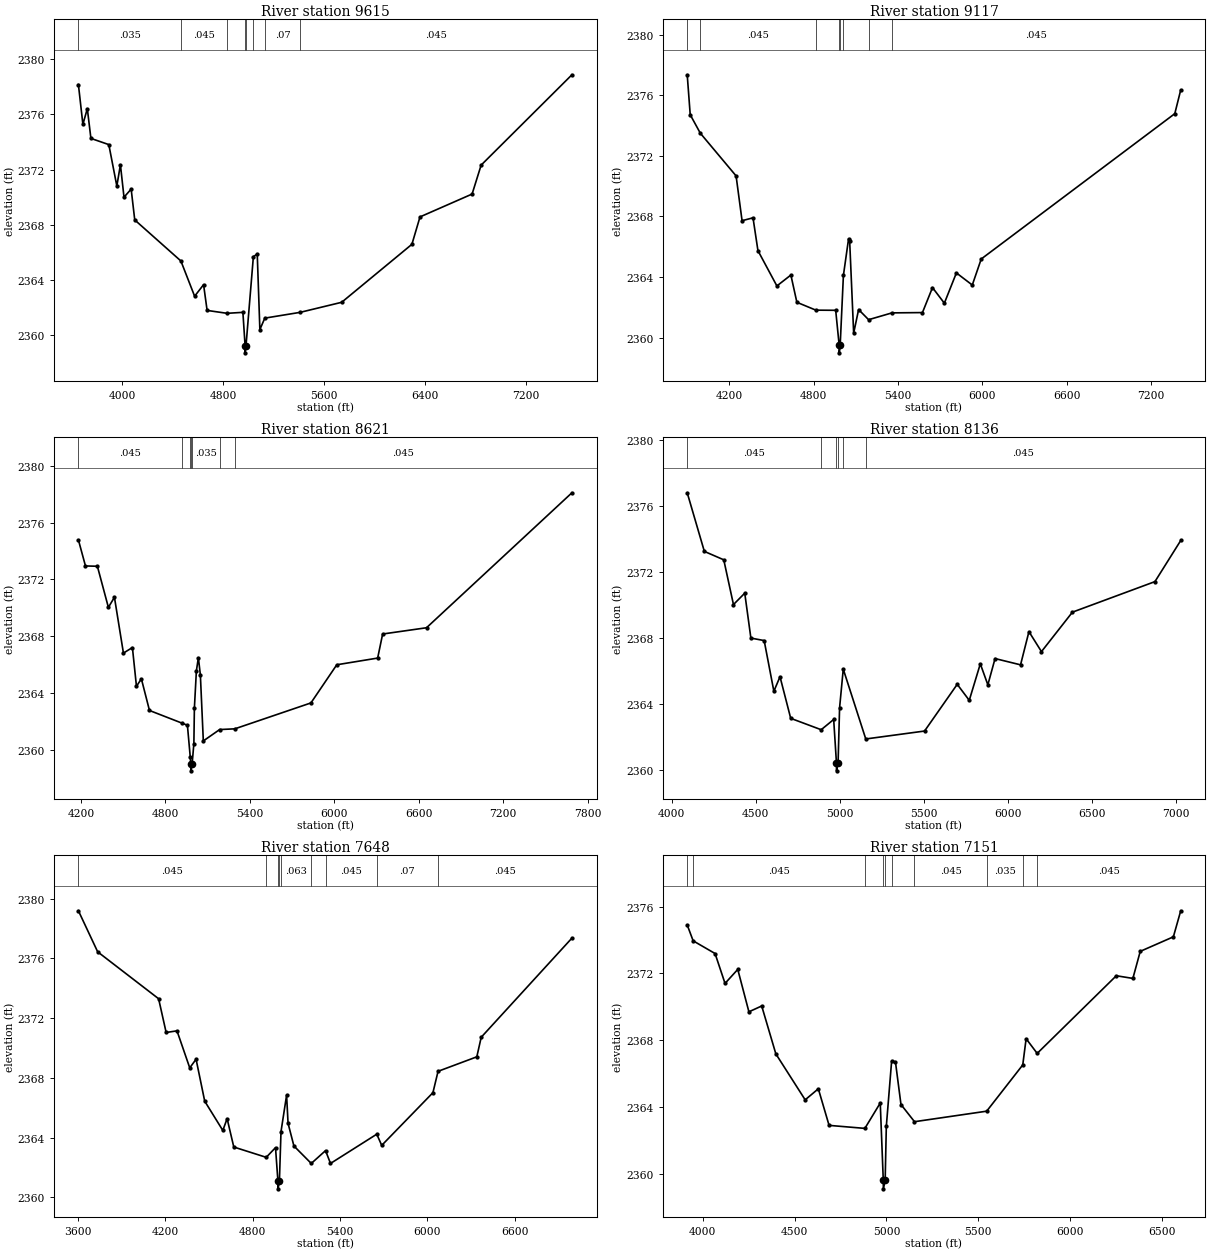
Type RM Length L Ch R = 1,9615,498,498,498
BEGIN DESCRIPTION:
Linn Creek Trib052 16.0
END DESCRIPTION:
XS GIS Cut Line= 3
      1300505.02      6903188.02      1299514.55      6902276.90
      1297505.01      6900688.01
#Sta/Elev= 30
  3654.2 2378.17  3689.7 2375.28  3724.8 2376.42  3753.2 2374.26  3895.0 2373.81
  3958.5 2370.80  3986.8 2372.35  4015.2 2369.99  4071.9 2370.58  4100.3 2368.34
  4465.7 2365.36  4574.4 2362.80  4645.3 2363.64  4673.3 2361.77  4831.2 2361.56
  4956.6 2361.63  4974.1 2359.19  4974.6 2358.69  4981.1 2359.19  5039.5 2365.67
  5070.2 2365.87  5091.0 2360.38  5130.0 2361.21  5409.9 2361.63  5738.8 2362.36
  6294.8 2366.57  6358.9 2368.56  6771.4 2370.22  6842.9 2372.32  7561.8 2378.88
#Mann=8,-1,0
  3654.2   0.035       0  4465.7   0.045       0  4831.2    0.07       0
  4974.1    0.07       0  4981.1    0.07       0  5039.5   0.094       0
  5130.0    0.07       0  5409.9   0.045       0
Bank Sta=4974.1,4981.1
Exp/Cntr=0.3,0.1

Type RM Length L Ch R = 1,9117,496,496,496
BEGIN DESCRIPTION:
Linn Creek Trib052 15.0
END DESCRIPTION:
XS GIS Cut Line= 3
      1300655.02      6902838.03      1299921.52      6902020.97
      1298104.98      6900437.98
#Sta/Elev= 30
  3902.0 2377.36  3923.3 2374.72  3995.1 2373.50  4249.3 2370.68  4291.8 2367.72
  4369.6 2367.91  4404.7 2365.74  4539.3 2363.41  4638.7 2364.13  4681.3 2362.33
  4816.3 2361.81  4957.2 2361.80  4982.0 2359.49  4982.5 2358.99  4989.1 2359.49
  5012.0 2364.10  5048.8 2366.53  5056.4 2366.40  5084.9 2360.29  5120.0 2361.85
  5191.1 2361.18  5357.3 2361.63  5573.8 2361.65  5645.1 2363.30  5729.5 2362.27
  5815.0 2364.27  5928.0 2363.47  5991.6 2365.19  7367.2 2374.79  7409.5 2376.36
#Mann=8,-1,0
  3902.0   0.035       0  3995.1   0.045       0  4816.3    0.07       0
  4982.0    0.07       0  4989.1    0.07       0  5012.0   0.035       0
  5191.1    0.07       0  5357.3   0.045       0
Bank Sta=4982,4989.1
Exp/Cntr=0.3,0.1

Type RM Length L Ch R = 1,8621,485,485,485
BEGIN DESCRIPTION:
Linn Creek Trib052 14.0
END DESCRIPTION:
XS GIS Cut Line= 3
      1300955.01      6902288.01      1300324.87      6901767.69
      1298504.98      6899787.98
#Sta/Elev= 30
  4182.8 2374.78  4233.0 2372.95  4317.6 2372.93  4395.8 2370.04  4438.8 2370.75
  4502.7 2366.83  4566.5 2367.22  4595.2 2364.50  4630.3 2365.02  4687.7 2362.80
  4921.5 2361.90  4957.3 2361.76  4977.7 2359.50  4981.1 2359.06  4981.6 2358.56
  4990.9 2359.06  5003.2 2360.48  5006.8 2362.96  5021.0 2365.58  5035.1 2366.51
  5049.3 2365.30  5070.3 2360.66  5186.4 2361.46  5293.9 2361.51  5834.8 2363.33
  6018.5 2366.01  6308.9 2366.48  6344.3 2368.17  6656.0 2368.61  7689.1 2378.09
#Mann=7,-1,0
  4182.8   0.045       0  4921.5    0.07       0  4977.7   0.035       0
  4981.1   0.035       0  4990.9   0.035       0  5186.4    0.07       0
  5293.9   0.045       0
Bank Sta=4981.1,4990.9
Exp/Cntr=0.3,0.1

Type RM Length L Ch R = 1,8136,488,488,488
BEGIN DESCRIPTION:
Linn Creek Trib052 13.0
END DESCRIPTION:
XS GIS Cut Line= 3
      1301204.99      6902287.99      1300721.55      6901521.04
      1300305.00      6899538.02
#Sta/Elev= 30
  4093.4 2376.79  4195.2 2373.24  4310.6 2372.73  4368.2 2370.02  4435.3 2370.71
  4471.7 2367.99  4550.7 2367.84  4608.3 2364.77  4644.8 2365.65  4708.4 2363.13
  4889.5 2362.44  4963.8 2363.06  4980.1 2360.45  4980.6 2359.95  4990.0 2360.45
  4998.8 2363.76  5020.7 2366.11  5154.5 2361.88  5503.8 2362.36  5698.0 2365.19
  5769.5 2364.22  5835.2 2366.43  5880.0 2365.16  5922.8 2366.75  6074.3 2366.37
  6124.2 2368.38  6198.6 2367.17  6382.6 2369.56  6873.0 2371.41  7026.3 2373.90
#Mann=6,-1,0
  4093.4   0.045       0  4889.5    0.07       0  4980.1    0.07       0
  4990.0    0.07       0  5020.7   0.035       0  5154.5   0.045       0
Bank Sta=4980.1,4990
Exp/Cntr=0.3,0.1

Type RM Length L Ch R = 1,7648,497,497,497
BEGIN DESCRIPTION:
Linn Creek Trib052 12.0
END DESCRIPTION:
XS GIS Cut Line= 3
      1301804.98      6902487.97      1301121.55      6901271.04
      1301305.00      6899288.01
#Sta/Elev= 30
  3604.3 2379.19  3736.6 2376.44  4154.8 2373.30  4206.5 2371.04  4280.9 2371.15
  4368.5 2368.67  4411.9 2369.25  4471.2 2366.44  4595.5 2364.48  4625.0 2365.27
  4670.8 2363.37  4893.4 2362.68  4957.1 2363.33  4973.8 2361.07  4974.3 2360.57
  4983.8 2361.07  4994.8 2364.40  5033.2 2366.84  5043.2 2364.96  5083.4 2363.44
  5202.5 2362.27  5300.6 2363.13  5334.5 2362.27  5652.1 2364.23  5686.0 2363.48
  6037.5 2367.01  6072.7 2368.44  6338.7 2369.41  6368.9 2370.72  6991.5 2377.36
#Mann=9,-1,0
  3604.3   0.045       0  4893.4    0.07       0  4973.8   0.063       0
  4983.8    0.07       0  4994.8   0.063       0  5202.5    0.07       0
  5300.6   0.045       0  5652.1    0.07       0  6072.7   0.045       0
Bank Sta=4973.8,4983.8
Exp/Cntr=0.3,0.1

Type RM Length L Ch R = 1,7151,500,500,500
BEGIN DESCRIPTION:
Linn Creek Trib052 11.0
END DESCRIPTION:
XS GIS Cut Line= 3
      1301954.99      6902037.97      1301539.60      6901037.04
      1301455.00      6899437.98
#Sta/Elev= 30
  3916.3 2374.90  3948.6 2373.95  4067.8 2373.19  4122.0 2371.40  4191.3 2372.24
  4251.9 2369.70  4321.5 2370.05  4398.5 2367.18  4558.0 2364.43  4629.6 2365.09
  4688.1 2362.90  4882.8 2362.72  4966.5 2364.24  4983.0 2359.60  4983.5 2359.10
  4993.2 2359.60  4999.5 2362.84  5028.3 2366.74  5049.1 2366.71  5079.2 2364.15
  5152.8 2363.12  5545.5 2363.75  5741.8 2366.52  5760.1 2368.09  5820.3 2367.21
  6250.8 2371.86  6340.9 2371.70  6381.0 2373.32  6561.2 2374.19  6601.3 2375.75
#Mann=10,-1,0
  3916.3   0.035       0  3948.6   0.045       0  4882.8    0.07       0
  4983.0    0.07       0  4993.2    0.07       0  5028.3   0.063       0
  5152.8   0.045       0  5545.5   0.035       0  5741.8    0.07       0
  5820.3   0.045       0
Bank Sta=4983,4993.2
Exp/Cntr=0.3,0.1

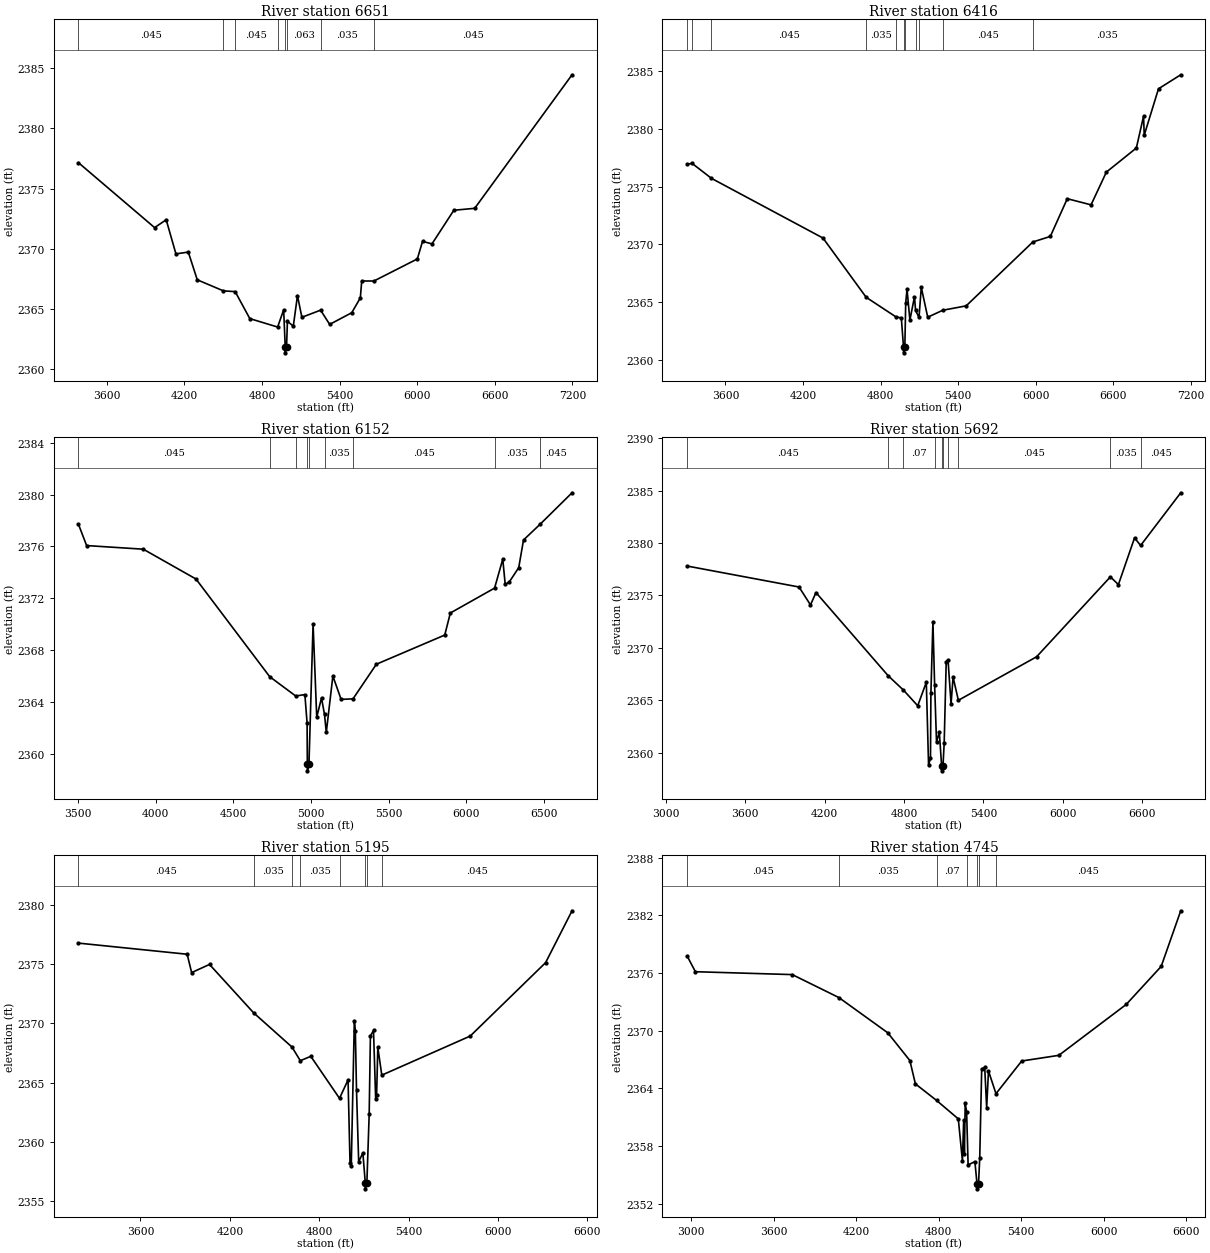
Type RM Length L Ch R = 1,6651,235,235,235
BEGIN DESCRIPTION:
Linn Creek Trib052 10.0
END DESCRIPTION:
XS GIS Cut Line= 5
      1301826.76      6902379.59      1302116.16      6901208.41
      1301968.23      6900824.42      1301632.33      6900185.11
      1301812.69      6898721.37
#Sta/Elev= 30
  3382.1 2377.15  3970.9 2371.76  4060.5 2372.41  4135.7 2369.58  4231.4 2369.73
  4300.5 2367.43  4503.1 2366.51  4593.5 2366.45  4706.8 2364.21  4921.7 2363.51
  4968.3 2364.94  4980.4 2361.87  4980.9 2361.37  4990.6 2361.87  4997.5 2363.98
  5043.0 2363.59  5075.0 2366.12  5109.1 2364.32  5253.8 2364.91  5323.9 2363.73
  5494.7 2364.70  5560.8 2365.93  5571.6 2367.33  5665.9 2367.33  6001.4 2369.16
  6041.7 2370.62  6114.6 2370.41  6283.5 2373.20  6444.7 2373.36  7197.0 2384.44
#Mann=8,-1,0
  3382.1   0.045       0  4503.1   0.035       0  4593.5   0.045       0
  4921.7   0.063       0  4980.4   0.063       0  4990.6   0.063       0
  5253.8   0.035       0  5665.9   0.045       0
Bank Sta=4980.4,4990.6
Exp/Cntr=0.3,0.1

Type RM Length L Ch R = 1,6416,264,264,264
BEGIN DESCRIPTION:
Linn Creek Trib052 9.5
END DESCRIPTION:
XS GIS Cut Line= 5
      1302048.98      6902317.09      1302338.38      6901145.91
      1302190.46      6900761.92      1301854.55      6900122.61
      1302035.10      6898657.38
#Sta/Elev= 30
  3304.0 2376.92  3341.8 2377.01  3492.2 2375.71  4354.7 2370.55  4688.5 2365.43
  4919.5 2363.73  4960.2 2363.65  4977.1 2361.13  4977.6 2360.63  4987.4 2361.13
  4994.1 2364.94  5004.3 2366.13  5026.4 2363.46  5061.9 2365.47  5070.5 2364.29
  5097.0 2363.69  5114.5 2366.29  5164.3 2363.71  5280.6 2364.31  5461.6 2364.69
  5976.8 2370.21  6112.2 2370.69  6243.2 2373.95  6427.1 2373.42  6545.5 2376.25
  6777.2 2378.33  6833.0 2381.08  6838.1 2379.44  6948.5 2383.45  7120.4 2384.66
#Mann=11,-1,0
  3304.0   0.045       0  3341.8   0.035       0  3492.2   0.045       0
  4688.5   0.035       0  4919.5    0.07       0  4977.1    0.07       0
  4987.4    0.07       0  5070.5   0.063       0  5097.0   0.035       0
  5280.6   0.045       0  5976.8   0.035       0
Bank Sta=4977.1,4987.4
Exp/Cntr=0.3,0.1

Type RM Length L Ch R = 1,6152,460,460,460
BEGIN DESCRIPTION:
Linn Creek Trib052 9.0
END DESCRIPTION:
XS GIS Cut Line= 3
      1302855.02      6901988.04      1302371.51      6900570.96
      1301804.99      6898987.98
#Sta/Elev= 30
  3502.7 2377.72  3555.6 2376.07  3920.5 2375.79  4259.8 2373.49  4734.5 2365.96
  4902.0 2364.47  4960.9 2364.58  4975.2 2362.39  4976.8 2359.20  4977.3 2358.70
  4987.2 2359.20  5013.8 2370.04  5037.2 2362.83  5068.0 2364.32  5087.4 2363.05
  5098.8 2361.66  5141.2 2366.01  5194.3 2364.21  5270.8 2364.25  5421.3 2366.92
  5861.6 2369.17  5897.7 2370.87  6182.5 2372.79  6235.2 2375.02  6251.0 2373.08
  6276.5 2373.25  6338.0 2374.37  6368.8 2376.50  6475.4 2377.71  6681.3 2380.14
#Mann=9,-1,0
  3502.7   0.045       0  4734.5   0.035       0  4902.0    0.07       0
  4976.8    0.07       0  4987.2    0.07       0  5087.4   0.035       0
  5270.8   0.045       0  6182.5   0.035       0  6475.4   0.045       0
Bank Sta=4976.8,4987.2
Exp/Cntr=0.3,0.1

Type RM Length L Ch R = 1,5692,497,497,497
BEGIN DESCRIPTION:
Linn Creek Trib052 8.0
END DESCRIPTION:
XS GIS Cut Line= 3
      1303155.00      6902138.00      1302752.71      6900343.85
      1301755.02      6898738.04
#Sta/Elev= 30
  3161.3 2377.80  4006.8 2375.80  4093.5 2374.09  4134.9 2375.27  4680.5 2367.33
  4796.0 2365.96  4903.5 2364.47  4968.4 2366.71  4985.5 2358.81  5000.0 2359.47
  5003.1 2365.66  5018.4 2372.50  5031.3 2366.42  5045.6 2361.01  5066.8 2361.94
  5084.0 2358.76  5084.5 2358.26  5094.5 2358.76  5103.4 2360.89  5118.8 2368.67
  5132.4 2368.85  5155.4 2364.65  5170.7 2367.20  5210.6 2364.99  5801.3 2369.14
  6359.2 2376.77  6419.6 2376.03  6541.6 2380.49  6587.3 2379.76  6890.5 2384.79
#Mann=10,-1,0
  3161.3   0.045       0  4680.5   0.035       0  4796.0    0.07       0
  5031.3   0.063       0  5084.0    0.07       0  5094.5   0.063       0
  5132.4   0.035       0  5210.6   0.045       0  6359.2   0.035       0
  6587.3   0.045       0
Bank Sta=5084,5094.5
Exp/Cntr=0.3,0.1

Type RM Length L Ch R = 1,5195,450,450,450
BEGIN DESCRIPTION:
Linn Creek Trib052 7.0
END DESCRIPTION:
XS GIS Cut Line= 3
      1303155.00      6901937.95      1303171.71      6900121.43
      1302254.97      6898937.96
#Sta/Elev= 30
  3183.4 2376.78  3913.4 2375.84  3943.4 2374.29  4063.4 2374.98  4359.0 2370.90
  4617.3 2368.00  4672.9 2366.85  4743.4 2367.22  4936.1 2363.67  4993.4 2365.23
  5006.7 2358.17  5014.9 2357.98  5035.7 2370.23  5042.3 2369.40  5050.2 2364.35
  5064.7 2358.32  5092.9 2359.06  5109.1 2356.53  5109.6 2356.03  5119.8 2356.53
  5135.3 2362.36  5143.5 2368.94  5164.3 2369.41  5178.8 2363.63  5185.1 2363.92
  5193.2 2367.98  5219.9 2365.63  5813.4 2368.93  6319.5 2375.13  6497.0 2379.51
#Mann=8,-1,0
  3183.4   0.045       0  4359.0   0.035       0  4617.3    0.07       0
  4672.9   0.035       0  4936.1    0.07       0  5109.1    0.07       0
  5119.8    0.07       0  5219.9   0.045       0
Bank Sta=5109.1,5119.8
Exp/Cntr=0.3,0.1

Type RM Length L Ch R = 1,4745,469,469,469
BEGIN DESCRIPTION:
Linn Creek Trib052 6.0
END DESCRIPTION:
XS GIS Cut Line= 3
      1303305.00      6901888.00      1303521.48      6899870.88
      1302505.02      6898688.02
#Sta/Elev= 30
  2971.3 2377.79  3031.6 2376.15  3735.7 2375.85  4074.7 2373.46  4429.6 2369.80
  4590.5 2366.91  4630.8 2364.48  4784.5 2362.76  4942.6 2360.84  4972.7 2356.48
  4981.9 2360.73  4987.0 2357.17  4992.8 2362.44  5003.1 2361.60  5014.0 2356.05
  5063.4 2356.39  5078.8 2354.06  5079.3 2353.56  5089.6 2354.06  5098.5 2356.78
  5112.8 2366.03  5134.7 2366.20  5148.8 2362.01  5162.2 2365.82  5216.6 2363.46
  5403.6 2366.86  5673.5 2367.45  6162.9 2372.74  6417.5 2376.70  6559.6 2382.49
#Mann=7,-1,0
  2971.3   0.045       0  4074.7   0.035       0  4784.5    0.07       0
  5003.1   0.035       0  5078.8    0.07       0  5089.6   0.035       0
  5216.6   0.045       0
Bank Sta=5078.8,5089.6
Exp/Cntr=0.3,0.1

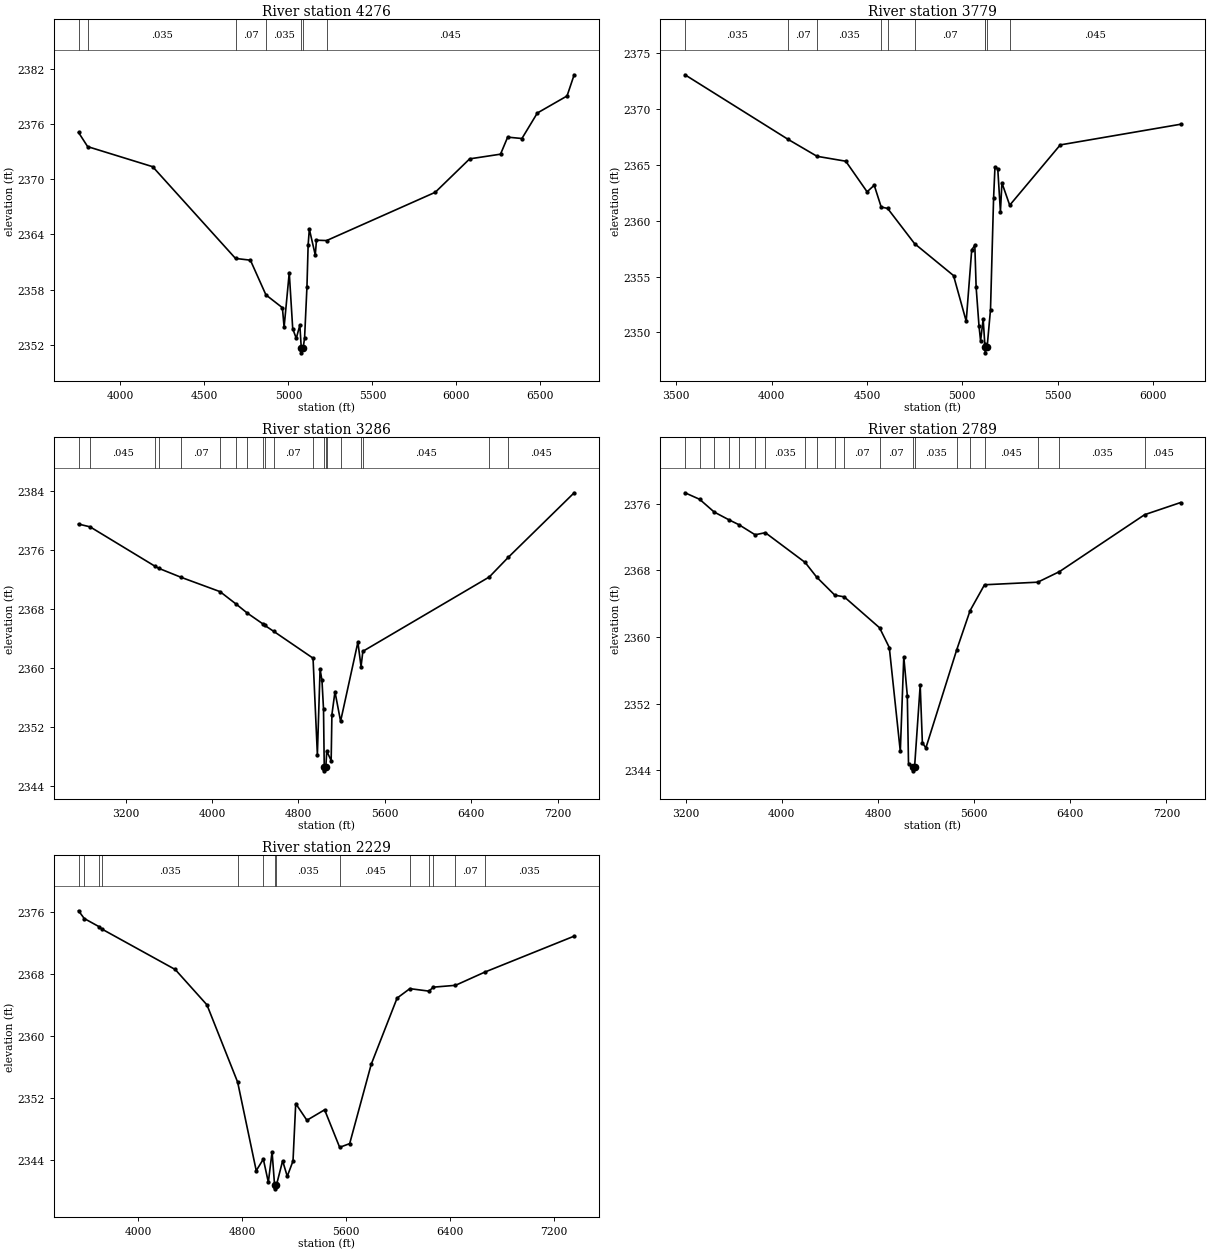
Type RM Length L Ch R = 1,4276,497,497,497
BEGIN DESCRIPTION:
Linn Creek Trib052 5.0
END DESCRIPTION:
XS GIS Cut Line= 3
      1303805.00      6900888.01      1303906.72      6899642.16
      1302705.01      6898438.01
#Sta/Elev= 30
  3750.0 2375.06  3804.4 2373.52  4191.5 2371.34  4684.8 2361.38  4773.4 2361.19
  4866.0 2357.42  4964.0 2356.03  4974.1 2353.91  5004.8 2359.84  5025.4 2353.75
  5046.6 2352.70  5067.8 2354.13  5076.5 2351.63  5077.0 2351.13  5087.4 2351.63
  5096.1 2352.76  5110.2 2358.31  5117.3 2362.87  5124.4 2364.56  5159.7 2361.75
  5166.8 2363.36  5227.3 2363.32  5873.9 2368.56  6079.0 2372.19  6262.8 2372.70
  6305.2 2374.55  6390.1 2374.40  6482.0 2377.17  6658.8 2379.02  6701.2 2381.32
#Mann=7,-1,0
  3750.0   0.045       0  3804.4   0.035       0  4684.8    0.07       0
  4866.0   0.035       0  5076.5   0.035       0  5087.4   0.035       0
  5227.3   0.045       0
Bank Sta=5076.5,5087.4
Exp/Cntr=0.3,0.1

Type RM Length L Ch R = 1,3779,493,493,493
BEGIN DESCRIPTION:
Linn Creek Trib052 4.0
END DESCRIPTION:
XS GIS Cut Line= 4
      1303865.66      6900711.48      1304442.91      6899561.33
      1304330.04      6899438.08      1303866.44      6898391.24
#Sta/Elev= 30
  3546.0 2373.07  4087.3 2367.28  4238.4 2365.77  4389.1 2365.33  4500.9 2362.59
  4538.3 2363.18  4574.8 2361.23  4608.6 2361.10  4749.8 2357.95  4954.1 2355.09
  5020.6 2351.00  5049.4 2357.38  5065.7 2357.81  5072.7 2354.03  5087.6 2350.59
  5096.0 2349.24  5109.5 2351.19  5118.1 2348.96  5119.2 2348.67  5119.7 2348.17
  5130.2 2348.67  5148.0 2352.05  5164.1 2362.00  5171.3 2364.78  5186.0 2364.66
  5200.0 2360.82  5207.9 2363.39  5248.7 2361.39  5513.7 2366.79  6144.9 2368.64
#Mann=10,-1,0
  3546.0   0.035       0  4087.3    0.07       0  4238.4   0.035       0
  4574.8    0.07       0  4608.6   0.035       0  4749.8    0.07       0
  5118.1   0.035       0  5119.2    0.07       0  5130.2   0.035       0
  5248.7   0.045       0
Bank Sta=5119.2,5130.2
Exp/Cntr=0.3,0.1

Type RM Length L Ch R = 1,3286,497,497,497
BEGIN DESCRIPTION:
Linn Creek Trib052 3.0
END DESCRIPTION:
XS GIS Cut Line= 3
      1306055.01      6900988.01      1304729.92      6899187.81
      1303055.01      6897538.01
#Sta/Elev= 30
  2764.7 2379.52  2871.9 2379.14  3472.8 2373.80  3507.2 2373.52  3712.4 2372.31
  4074.1 2370.36  4225.1 2368.65  4325.8 2367.46  4473.3 2365.96  4486.5 2365.80
  4571.8 2364.97  4934.8 2361.34  4974.9 2348.28  4999.9 2359.85  5017.5 2358.32
  5031.7 2354.46  5038.5 2346.57  5039.0 2346.07  5053.2 2346.57  5061.7 2348.74
  5102.4 2347.46  5109.4 2353.70  5137.7 2356.79  5189.7 2352.79  5349.8 2363.51
  5379.0 2360.20  5395.8 2362.27  6565.9 2372.35  6740.5 2375.00  7351.0 2383.76
#Mann=20,-1,0
  2764.7   0.035       0  2871.9   0.045       0  3472.8    0.07       0
  3507.2   0.045       0  3712.4    0.07       0  4074.1   0.035       0
  4225.1    0.07       0  4325.8   0.035       0  4473.3    0.07       0
  4486.5   0.035       0  4571.8    0.07       0  4934.8    0.16       0
  5038.5    0.07       0  5053.2    0.16       0  5061.7   0.035       0
  5189.7    0.16       0  5379.0    0.07       0  5395.8   0.045       0
  6565.9   0.035       0  6740.5   0.045       0
Bank Sta=5038.5,5053.2
Exp/Cntr=0.3,0.1

Type RM Length L Ch R = 1,2789,560,560,560
BEGIN DESCRIPTION:
Linn Creek Trib052 2.0
END DESCRIPTION:
XS GIS Cut Line= 4
      1305956.12      6900725.43      1305194.95      6899087.89
      1305112.35      6898886.85      1303519.33      6897517.68
#Sta/Elev= 30
  3194.2 2377.30  3315.9 2376.52  3437.2 2374.99  3556.7 2374.08  3644.1 2373.46
  3777.8 2372.26  3862.8 2372.51  4193.9 2368.94  4289.7 2367.18  4441.1 2365.01
  4519.1 2364.81  4813.0 2361.10  4894.1 2358.73  4985.7 2346.26  5014.6 2357.61
  5043.9 2352.97  5053.9 2344.78  5089.9 2344.43  5090.4 2343.93  5104.6 2344.43
  5151.2 2354.20  5169.2 2347.30  5198.5 2346.68  5455.6 2358.48  5566.3 2363.16
  5686.2 2366.26  6129.0 2366.57  6310.1 2367.84  7018.3 2374.67  7317.9 2376.13
#Mann=20,-1,0
  3194.2   0.045       0  3315.9    0.07       0  3437.2   0.035       0
  3556.7   0.045       0  3644.1    0.07       0  3777.8    0.07       0
  3862.8   0.035       0  4193.9    0.07       0  4289.7   0.035       0
  4441.1   0.035       0  4519.1    0.07       0  4813.0    0.07       0
  5089.9    0.07       0  5104.6   0.035       0  5455.6   0.045       0
  5566.3   0.035       0  5686.2   0.045       0  6129.0   0.035       0
  6310.1   0.035       0  7018.3   0.045       0
Bank Sta=5089.9,5104.6
Exp/Cntr=0.3,0.1

Type RM Length L Ch R = 1,2229,0,0,0
BEGIN DESCRIPTION:
Linn Creek Trib052 1.0
END DESCRIPTION:
XS GIS Cut Line= 4
      1305924.85      6900537.91      1305755.03      6899087.92
      1305737.35      6899032.68      1303862.38      6897699.37
#Sta/Elev= 30
  3540.1 2376.10  3584.5 2375.10  3699.4 2374.04  3719.5 2373.75  4285.1 2368.53
  4529.6 2363.97  4766.2 2354.00  4909.3 2342.59  4964.0 2344.08  5002.6 2341.10
  5031.4 2345.03  5050.5 2340.75  5051.0 2340.25  5065.2 2340.75  5112.7 2343.86
  5148.3 2341.86  5192.6 2343.84  5213.5 2351.24  5299.6 2349.09  5436.1 2350.44
  5552.1 2345.60  5629.2 2346.08  5795.2 2356.31  5994.4 2364.84  6092.8 2366.06
  6240.5 2365.74  6272.6 2366.25  6444.4 2366.49  6669.8 2368.19  7358.7 2372.83
#Mann=14,-1,0
  3540.1    0.07       0  3584.5   0.035       0  3699.4    0.07       0
  3719.5   0.035       0  4766.2    0.07       0  4964.0   0.035       0
  5050.5   0.035       0  5065.2   0.035       0  5552.1   0.045       0
  6092.8   0.035       0  6240.5   0.045       0  6272.6   0.035       0
  6444.4    0.07       0  6669.8   0.035       0
Bank Sta=5050.5,5065.2
Exp/Cntr=0.3,0.1

Chan Stop Cuts=-1