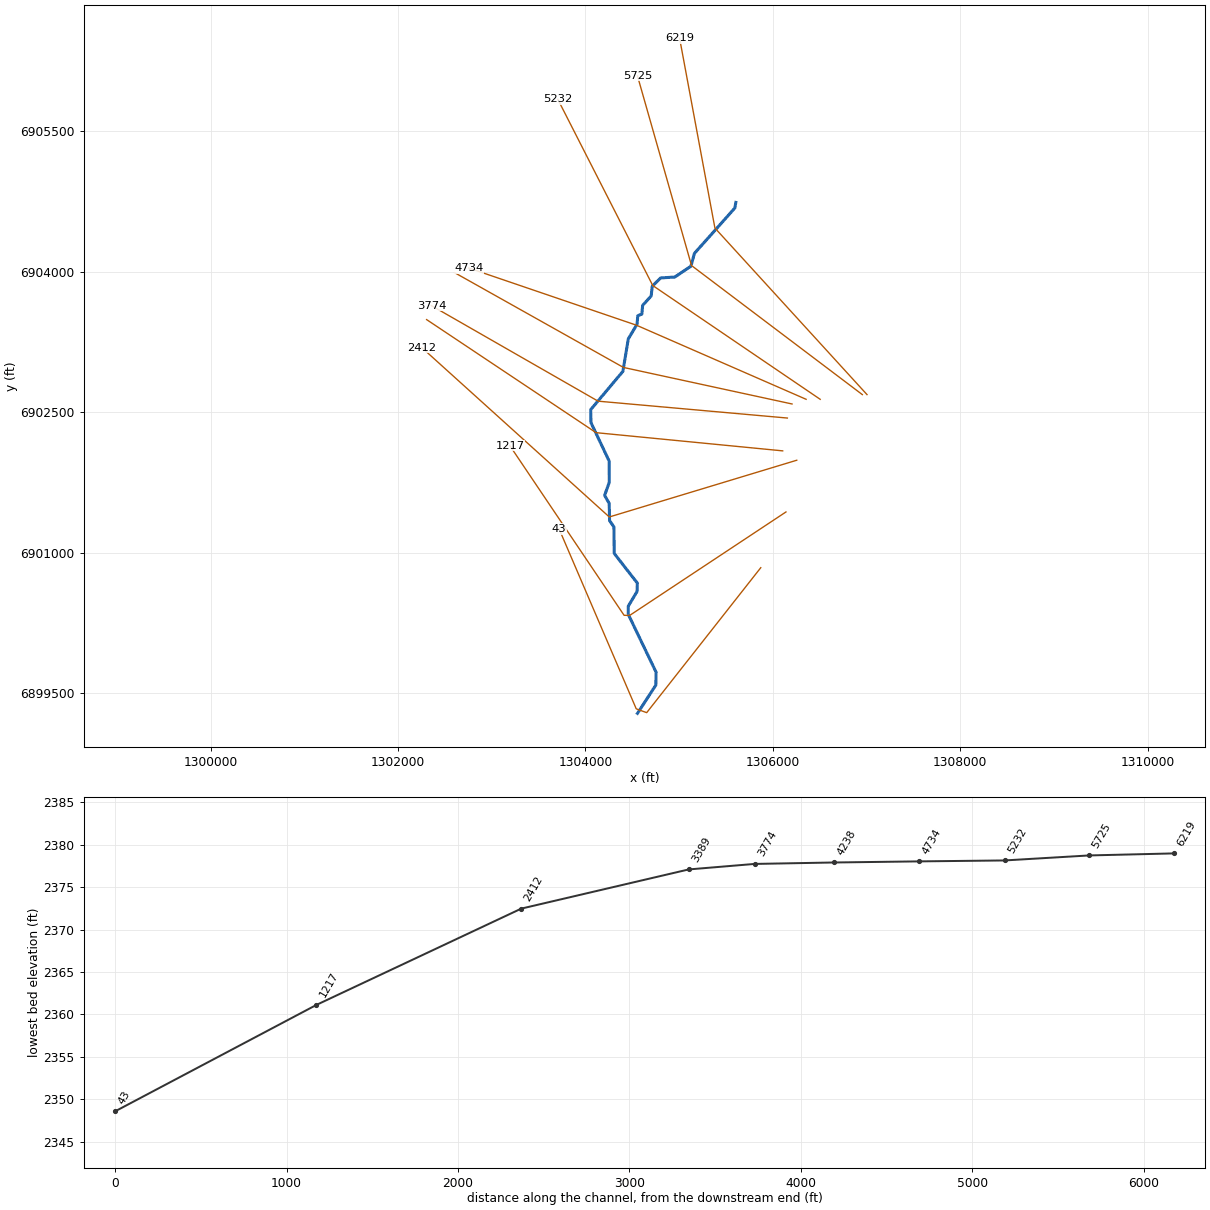
--- Linn Creek Trib052_3.prj (project) ---

Proj Title=Linn Creek Trib052_3 Base Level Engineering
Current Plan=p01
Default Exp/Contr=0.3,0.1
English Units
Geom File=g01
Flow File=f01
Plan File=p01
BEGIN DESCRIPTION:
Linn Creek Trib052_3
END DESCRIPTION:

--- Linn Creek Trib052_3.p01 (plan) ---

Plan Title=Multiple Run
Short Identifier=Multiple
Geom File=g01
Flow File=f01
Subcritical Flow
K Sum by GR= 0
Std Step Tol= 0.01
Critical Tol= 0.01
Num of Std Step Trials= 20
Max Error Tol= 0.3
Flow Tol Ratio= 0.001
Split Flow NTrial= 30
Split Flow Tol= 0.02
Split Flow Ratio= 0.02
Log Output Level= 0
Friction Slope Method= 1
Unsteady Friction Slope Method= 2
Unsteady Bridges Friction Slope Method= 1
Parabolic Critical Depth
Global Vel Dist=  1 , 1 , 1
Global Log Level= 0
CheckData=True
Encroach Param= -1, 0, 0, 0
BEGIN DESCRIPTION:
Multiple Run
END DESCRIPTION:

--- Linn Creek Trib052_3.f01 (steady flow) ---

Flow Title=Multiple
Number of Profiles=7
Profile Names=10-year,25-year,50-year,1pct_min,100-year,1pct_plu,500-year
River Rch & RM= Linn Creek Trib0,Reach-1,6219
     286     399     492     301     601    1199     908
Boundary for River Rch & Prof#=Linn Creek Trib0,Reach-1,1
Up Type=0
Dn Type=3
Dn Slope=0.005
Boundary for River Rch & Prof#=Linn Creek Trib0,Reach-1,2
Up Type=0
Dn Type=3
Dn Slope=0.005
Boundary for River Rch & Prof#=Linn Creek Trib0,Reach-1,3
Up Type=0
Dn Type=3
Dn Slope=0.005
Boundary for River Rch & Prof#=Linn Creek Trib0,Reach-1,4
Up Type=0
Dn Type=3
Dn Slope=0.005
Boundary for River Rch & Prof#=Linn Creek Trib0,Reach-1,5
Up Type=0
Dn Type=3
Dn Slope=0.005
Boundary for River Rch & Prof#=Linn Creek Trib0,Reach-1,6
Up Type=0
Dn Type=3
Dn Slope=0.005
Boundary for River Rch & Prof#=Linn Creek Trib0,Reach-1,7
Up Type=0
Dn Type=3
Dn Slope=0.005

--- Linn Creek Trib052_3.g01 (geometry) ---

Geom Title=Existing Conditions

River Reach=Linn Creek Trib0,Reach-1
Reach XY= 30
      1305605.00      6904738.00      1305594.49      6904678.21
      1305162.86      6904194.17      1305125.51      6904057.73
      1304953.44      6903941.76      1304802.54      6903932.54
      1304712.86      6903844.19      1304701.37      6903739.50
      1304610.56      6903640.36      1304601.45      6903546.50
      1304558.55      6903529.50      1304551.15      6903439.65
      1304457.25      6903282.07      1304399.52      6902935.56
      1304056.04      6902527.56      1304058.74      6902389.56
      1304253.78      6901977.50      1304254.48      6901753.22
      1304204.60      6901613.00      1304253.78      6901527.50
      1304257.26      6901343.94      1304303.78      6901277.50
      1304307.06      6900993.85      1304554.06      6900677.52
      1304551.33      6900589.59      1304457.14      6900432.03
      1304457.17      6900343.97      1304753.81      6899727.50
      1304751.26      6899589.56      1304555.00      6899288.00

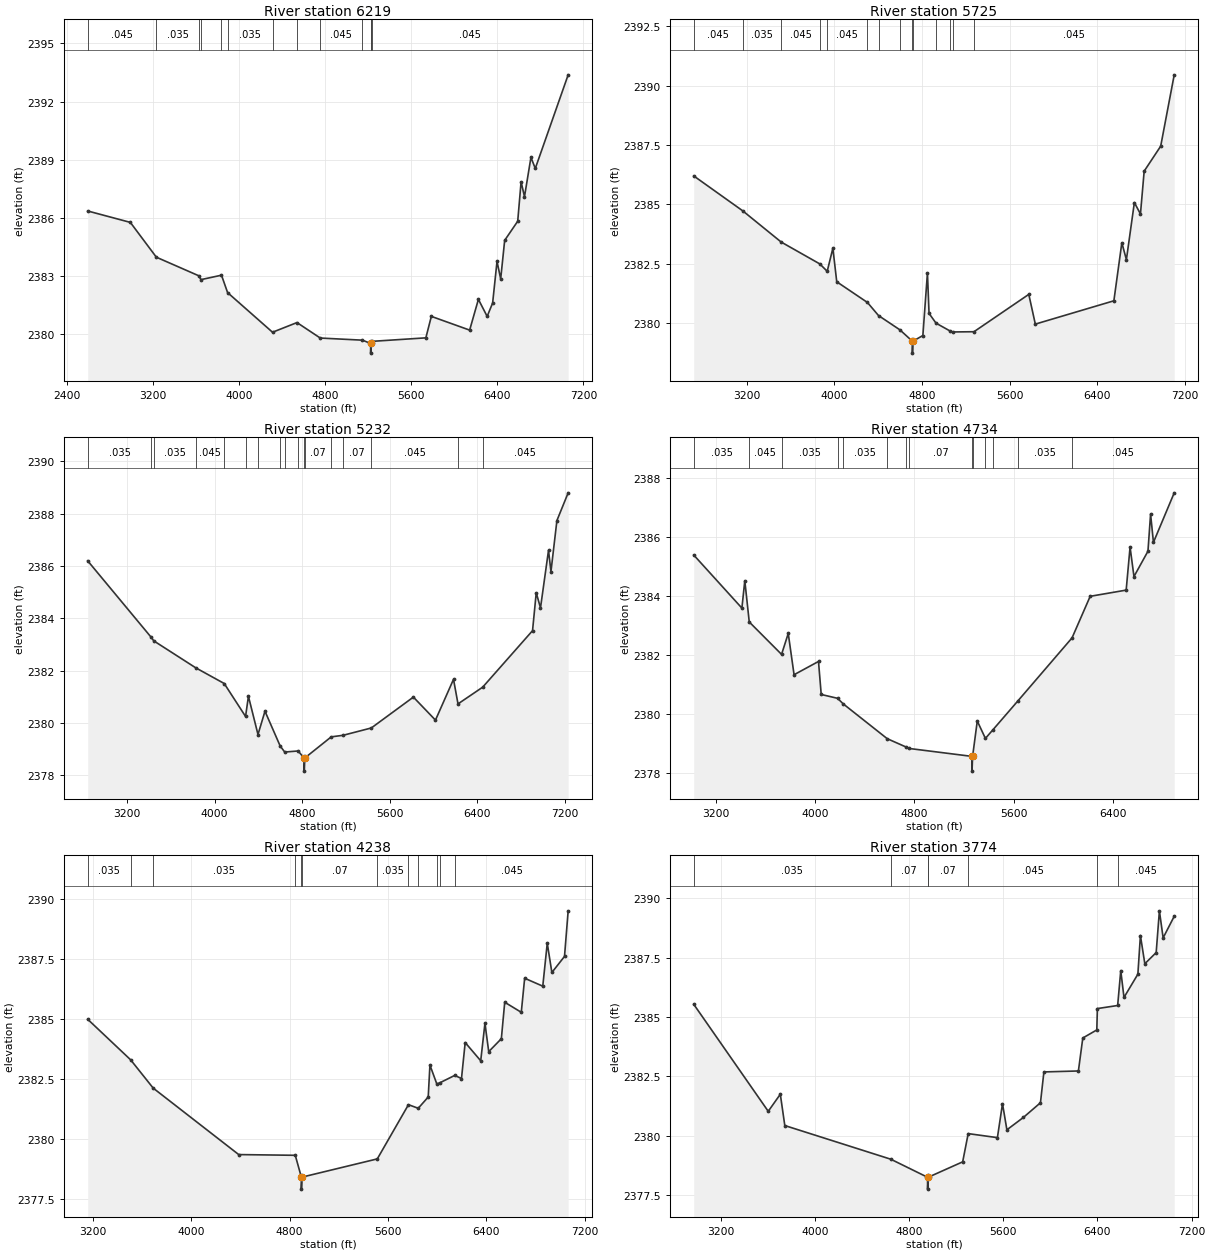
Type RM Length L Ch R = 1,6219,494,494,494
BEGIN DESCRIPTION:
Linn Creek Trib052_3 8.0
END DESCRIPTION:
XS GIS Cut Line= 3
      1307005.03      6902687.97      1305381.62      6904464.69
      1305004.99      6906488.03
#Sta/Elev= 30
  2593.3 2386.34  2989.6 2385.75  3231.4 2383.95  3625.5 2382.99  3645.9 2382.79
  3836.7 2383.02  3893.3 2382.12  4310.9 2380.07  4538.2 2380.57  4754.5 2379.77
  5146.5 2379.66  5222.6 2379.49  5222.9 2378.99  5226.8 2379.49  5238.3 2379.60
  5735.7 2379.78  5786.6 2380.89  6142.6 2380.18  6224.0 2381.77  6305.4 2380.89
  6356.2 2381.58  6396.9 2383.73  6431.1 2382.83  6468.1 2384.82  6589.3 2385.81
  6620.7 2387.85  6652.3 2387.08  6712.2 2389.11  6752.7 2388.54  7058.1 2393.38
#Mann=13,-1,0
  2593.3   0.045       0  3231.4   0.035       0  3625.5   0.045       0
  3645.9   0.035       0  3836.7   0.045       0  3893.3   0.035       0
  4310.9   0.045       0  4538.2   0.035       0  4754.5   0.045       0
  5146.5    0.07       0  5222.6   0.045       0  5226.8    0.07       0
  5238.3   0.045       0
Bank Sta=5222.6,5226.8
Exp/Cntr=0.3,0.1

Type RM Length L Ch R = 1,5725,493,493,493
BEGIN DESCRIPTION:
Linn Creek Trib052_3 7.0
END DESCRIPTION:
XS GIS Cut Line= 3
      1306955.04      6902687.97      1305132.14      6904064.43
      1304554.99      6906088.03
#Sta/Elev= 30
  2715.8 2386.20  3163.8 2384.73  3514.4 2383.42  3867.4 2382.50  3934.8 2382.19
  3986.5 2383.16  4021.9 2381.75  4302.1 2380.88  4403.4 2380.33  4598.5 2379.73
  4712.9 2379.25  4713.2 2378.75  4717.1 2379.25  4808.5 2379.49  4850.3 2382.12
  4864.9 2380.42  4928.8 2380.01  5057.0 2379.68  5080.1 2379.64  5275.4 2379.65
  5776.0 2381.22  5835.6 2379.97  6553.1 2380.95  6625.9 2383.39  6667.5 2382.68
  6740.3 2385.08  6795.9 2384.60  6829.8 2386.40  6980.7 2387.45  7104.3 2390.45
#Mann=14,-1,0
  2715.8   0.045       0  3163.8   0.035       0  3514.4   0.045       0
  3867.4   0.035       0  3934.8   0.045       0  4302.1   0.035       0
  4403.4   0.045       0  4598.5    0.07       0  4712.9   0.035       0
  4717.1    0.07       0  4928.8   0.035       0  5057.0   0.045       0
  5080.1    0.07       0  5275.4   0.045       0
Bank Sta=4712.9,4717.1
Exp/Cntr=0.3,0.1

Type RM Length L Ch R = 1,5232,498,498,498
BEGIN DESCRIPTION:
Linn Creek Trib052_3 6.0
END DESCRIPTION:
XS GIS Cut Line= 3
      1306505.03      6902637.98      1304718.39      6903851.33
      1303705.00      6905838.00
#Sta/Elev= 30
  2840.3 2386.20  3421.8 2383.27  3444.2 2383.14  3827.5 2382.11  4087.7 2381.51
  4282.7 2380.25  4308.9 2381.02  4396.3 2379.56  4460.1 2380.45  4599.0 2379.12
  4640.5 2378.89  4762.6 2378.93  4818.4 2378.66  4818.8 2378.16  4823.3 2378.66
  5065.5 2379.47  5173.8 2379.53  5431.7 2379.81  5816.0 2380.99  6017.8 2380.11
  6182.7 2381.67  6223.7 2380.73  6449.2 2381.37  6904.7 2383.53  6938.5 2384.98
  6977.4 2384.40  7050.6 2386.60  7073.0 2385.79  7127.4 2387.74  7230.2 2388.80
#Mann=17,-1,0
  2840.3   0.035       0  3421.8   0.045       0  3444.2   0.035       0
  3827.5   0.045       0  4087.7   0.035       0  4282.7    0.07       0
  4396.3   0.035       0  4599.0    0.07       0  4640.5   0.035       0
  4762.6    0.07       0  4818.4    0.07       0  4823.3    0.07       0
  5065.5   0.035       0  5173.8    0.07       0  5431.7   0.045       0
  6223.7    0.07       0  6449.2   0.045       0
Bank Sta=4818.4,4823.3
Exp/Cntr=0.3,0.1

Type RM Length L Ch R = 1,4734,496,496,496
BEGIN DESCRIPTION:
Linn Creek Trib052_3 5.0
END DESCRIPTION:
XS GIS Cut Line= 3
      1306354.98      6902638.01      1304544.15      6903428.38
      1302754.96      6904038.01
#Sta/Elev= 30
  3024.2 2385.38  3411.6 2383.58  3435.0 2384.51  3470.8 2383.11  3730.8 2382.01
  3784.6 2382.72  3831.4 2381.32  4028.0 2381.77  4049.8 2380.65  4181.4 2380.52
  4227.2 2380.33  4581.1 2379.15  4731.5 2378.87  4754.7 2378.82  5263.0 2378.55
  5263.3 2378.05  5267.9 2378.55  5305.5 2379.75  5370.9 2379.16  5431.0 2379.45
  5634.0 2380.44  6068.1 2382.57  6214.0 2383.98  6503.6 2384.19  6534.9 2385.65
  6566.3 2384.65  6678.9 2385.51  6700.0 2386.77  6723.0 2385.81  6890.2 2387.49
#Mann=14,-1,0
  3024.2   0.035       0  3470.8   0.045       0  3730.8   0.035       0
  4181.4    0.07       0  4227.2   0.035       0  4581.1    0.07       0
  4731.5   0.035       0  4754.7    0.07       0  5263.0    0.07       0
  5267.9    0.07       0  5370.9   0.035       0  5431.0    0.07       0
  5634.0   0.035       0  6068.1   0.045       0
Bank Sta=5263,5267.9
Exp/Cntr=0.3,0.1

Type RM Length L Ch R = 1,4238,464,464,464
BEGIN DESCRIPTION:
Linn Creek Trib052_3 4.0
END DESCRIPTION:
XS GIS Cut Line= 3
      1306205.01      6902588.00      1304405.45      6902977.81
      1302604.99      6903988.01
#Sta/Elev= 30
  3158.7 2385.00  3507.8 2383.31  3691.3 2382.13  4386.5 2379.36  4846.1 2379.33
  4895.6 2378.42  4896.0 2377.92  4900.7 2378.42  5512.9 2379.18  5766.3 2381.44
  5845.7 2381.29  5926.9 2381.76  5940.8 2383.09  5997.1 2382.30  6024.4 2382.36
  6142.5 2382.66  6197.3 2382.53  6227.4 2384.03  6353.6 2383.27  6388.0 2384.83
  6418.7 2383.65  6521.4 2384.19  6548.8 2385.71  6683.4 2385.29  6710.8 2386.71
  6858.1 2386.38  6894.5 2388.17  6932.1 2386.95  7034.8 2387.62  7064.5 2389.52
#Mann=12,-1,0
  3158.7   0.035       0  3507.8   0.045       0  3691.3   0.035       0
  4846.1    0.07       0  4895.6    0.07       0  4900.7    0.07       0
  5512.9   0.035       0  5766.3   0.045       0  5845.7   0.035       0
  5997.1   0.045       0  6024.4   0.035       0  6142.5   0.045       0
Bank Sta=4895.6,4900.7
Exp/Cntr=0.3,0.1

Type RM Length L Ch R = 1,3774,385,385,385
BEGIN DESCRIPTION:
Linn Creek Trib052_3 3.0
END DESCRIPTION:
XS GIS Cut Line= 3
      1306155.05      6902438.00      1304134.96      6902618.02
      1302354.99      6903638.01
#Sta/Elev= 30
  2971.9 2385.54  3604.4 2381.03  3707.0 2381.75  3745.0 2380.43  4645.4 2379.01
  4957.1 2378.25  4957.5 2377.75  4962.5 2378.25  5255.3 2378.90  5302.2 2380.09
  5550.2 2379.92  5593.4 2381.35  5630.8 2380.25  5770.4 2380.77  5915.7 2381.39
  5945.0 2382.69  6237.9 2382.73  6275.3 2384.12  6394.2 2384.46  6399.1 2385.36
  6571.2 2385.49  6597.6 2386.96  6625.0 2385.83  6742.9 2386.81  6764.5 2388.44
  6801.9 2387.25  6898.3 2387.72  6925.6 2389.48  6957.3 2388.34  7051.5 2389.25
#Mann=7,-1,0
  2971.9   0.035       0  4645.4    0.07       0  4957.1    0.07       0
  4962.5    0.07       0  5302.2   0.045       0  6394.2   0.035       0
  6571.2   0.045       0
Bank Sta=4957.1,4962.5
Exp/Cntr=0.3,0.1

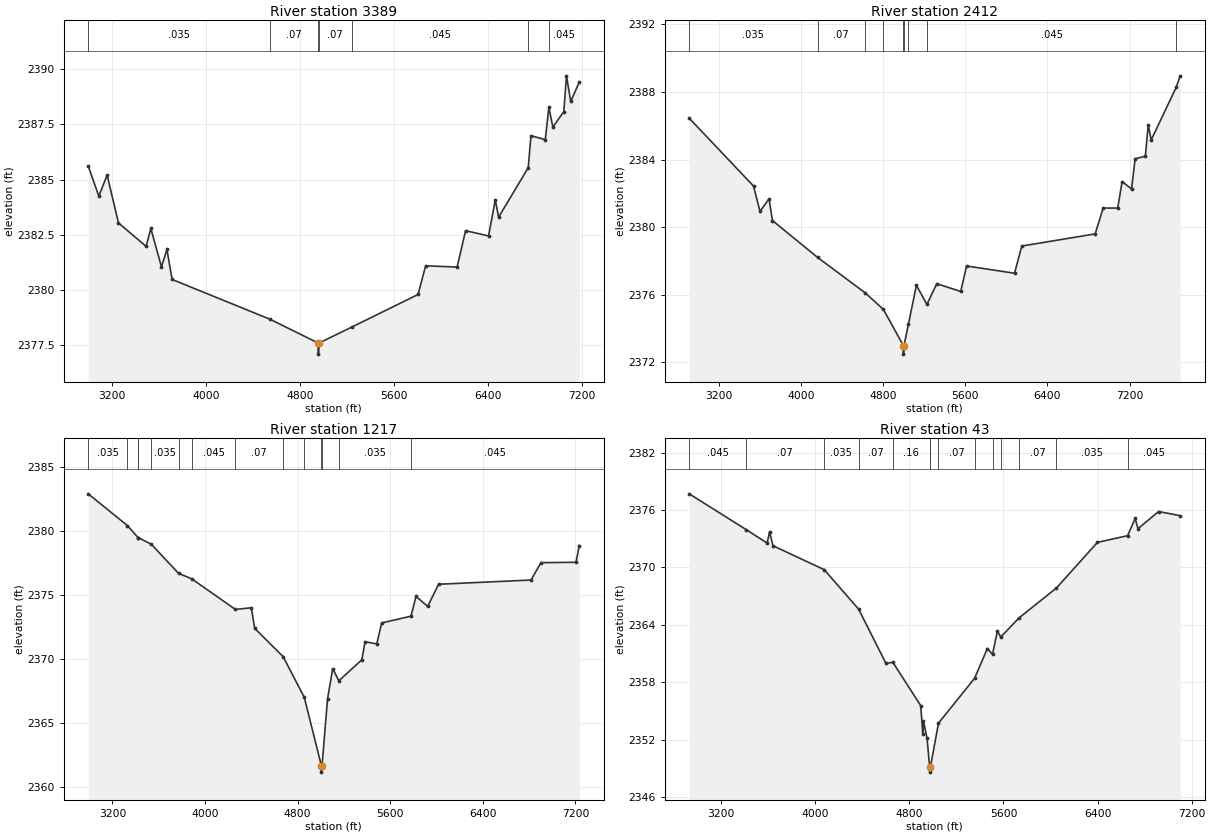
Type RM Length L Ch R = 1,3389,977,977,977
BEGIN DESCRIPTION:
Linn Creek Trib052_3 2.0
END DESCRIPTION:
XS GIS Cut Line= 3
      1306104.99      6902088.00      1304113.42      6902282.06
      1302305.03      6903487.98
#Sta/Elev= 30
  2999.0 2385.62  3089.4 2384.25  3159.7 2385.21  3256.0 2383.04  3491.3 2381.98
  3531.5 2382.79  3621.9 2381.05  3668.2 2381.84  3712.4 2380.48  4544.4 2378.68
  4955.5 2377.60  4956.0 2377.10  4960.9 2377.60  5237.9 2378.32  5803.4 2379.80
  5868.2 2381.10  6135.6 2381.04  6207.7 2382.69  6403.0 2382.45  6460.1 2384.08
  6488.5 2383.30  6740.2 2385.54  6763.5 2386.99  6885.2 2386.81  6915.6 2388.27
  6949.8 2387.38  7042.9 2388.08  7065.5 2389.70  7101.5 2388.54  7173.6 2389.41
#Mann=7,-1,0
  2999.0   0.035       0  4544.4    0.07       0  4955.5    0.07       0
  4960.9    0.07       0  5237.9   0.045       0  6740.2   0.035       0
  6915.6   0.045       0
Bank Sta=4955.5,4960.9
Exp/Cntr=0.3,0.1

Type RM Length L Ch R = 1,2412,1195,1195,1195
BEGIN DESCRIPTION:
Linn Creek Trib052_3 1.0
END DESCRIPTION:
XS GIS Cut Line= 3
      1306255.03      6901988.01      1304254.57      6901382.82
      1302254.98      6903188.02
#Sta/Elev= 30
  2910.0 2386.45  3536.9 2382.43  3599.6 2380.93  3687.7 2381.68  3720.7 2380.39
  4160.1 2378.21  4621.9 2376.12  4801.8 2375.13  4997.0 2372.98  4997.4 2372.48
  5002.4 2372.98  5045.5 2374.24  5123.5 2376.56  5225.7 2375.42  5322.3 2376.65
  5555.5 2376.19  5612.3 2377.70  6079.3 2377.27  6150.3 2378.88  6865.5 2379.60
  6943.2 2381.13  7085.2 2381.13  7127.8 2382.70  7219.7 2382.26  7254.8 2384.05
  7354.2 2384.20  7382.6 2386.05  7411.0 2385.16  7655.0 2388.28  7693.9 2388.96
#Mann=9,-1,0
  2910.0   0.035       0  4160.1    0.07       0  4621.9   0.035       0
  4801.8    0.07       0  4997.0    0.07       0  5002.4    0.07       0
  5045.5   0.035       0  5225.7   0.045       0  7655.0   0.035       0
Bank Sta=4997,5002.4
Exp/Cntr=0.3,0.1

Type RM Length L Ch R = 1,1217,1174,1174,1174
BEGIN DESCRIPTION:
Linn Creek Trib052_3 0.6
END DESCRIPTION:
XS GIS Cut Line= 4
      1306139.99      6901436.35      1304471.58      6900332.47
      1304412.53      6900333.90      1303193.18      6902143.40
#Sta/Elev= 30
  2990.5 2382.92  3328.3 2380.44  3420.7 2379.50  3422.1 2379.50  3535.5 2378.97
  3771.5 2376.69  3883.8 2376.27  4261.8 2373.87  4399.4 2374.00  4428.8 2372.39
  4674.7 2370.17  4857.3 2366.98  5004.8 2361.63  5005.2 2361.13  5010.5 2361.63
  5057.9 2366.85  5102.8 2369.24  5155.5 2368.28  5354.7 2369.93  5381.7 2371.34
  5483.6 2371.17  5525.6 2372.81  5778.8 2373.34  5822.4 2374.89  5923.3 2374.11
  6017.3 2375.84  6815.6 2376.17  6901.9 2377.53  7204.8 2377.56  7232.1 2378.87
#Mann=14,-1,0
  2990.5   0.035       0  3328.3    0.07       0  3420.7   0.035       0
  3422.1    0.07       0  3535.5   0.035       0  3771.5    0.07       0
  3883.8   0.045       0  4261.8    0.07       0  4674.7   0.035       0
  4857.3    0.07       0  5004.8    0.07       0  5010.5    0.07       0
  5155.5   0.035       0  5778.8   0.045       0
Bank Sta=5004.8,5010.5
Exp/Cntr=0.3,0.1

Type RM Length L Ch R = 1,43,0,0,0
BEGIN DESCRIPTION:
Linn Creek Trib052_3 0.5
END DESCRIPTION:
XS GIS Cut Line= 5
      1305870.85      6900841.69      1304653.69      6899295.73
      1304559.94      6899329.58      1304541.71      6899337.39
      1303719.04      6901254.63
#Sta/Elev= 30
  2929.0 2377.70  3413.9 2373.95  3591.2 2372.55  3612.0 2373.73  3640.9 2372.27
  4076.0 2369.77  4368.5 2365.64  4601.4 2359.96  4659.6 2360.08  4896.6 2355.55
  4914.6 2352.57  4919.9 2353.95  4950.6 2352.13  4973.0 2349.09  4973.5 2348.59
  4978.9 2349.09  5047.6 2353.71  5354.9 2358.41  5462.9 2361.52  5506.9 2360.92
  5548.8 2363.35  5576.8 2362.72  5731.3 2364.71  6050.2 2367.85  6398.8 2372.62
  6654.8 2373.32  6719.7 2375.12  6743.2 2374.05  6919.0 2375.85  7102.4 2375.41
#Mann=14,-1,0
  2929.0   0.045       0  3413.9    0.07       0  4076.0   0.035       0
  4368.5    0.07       0  4659.6    0.16       0  4973.0    0.07       0
  4978.9    0.16       0  5047.6    0.07       0  5354.9   0.035       0
  5506.9    0.07       0  5576.8   0.035       0  5731.3    0.07       0
  6050.2   0.035       0  6654.8   0.045       0
Bank Sta=4973,4978.9
Exp/Cntr=0.3,0.1

Chan Stop Cuts=-1