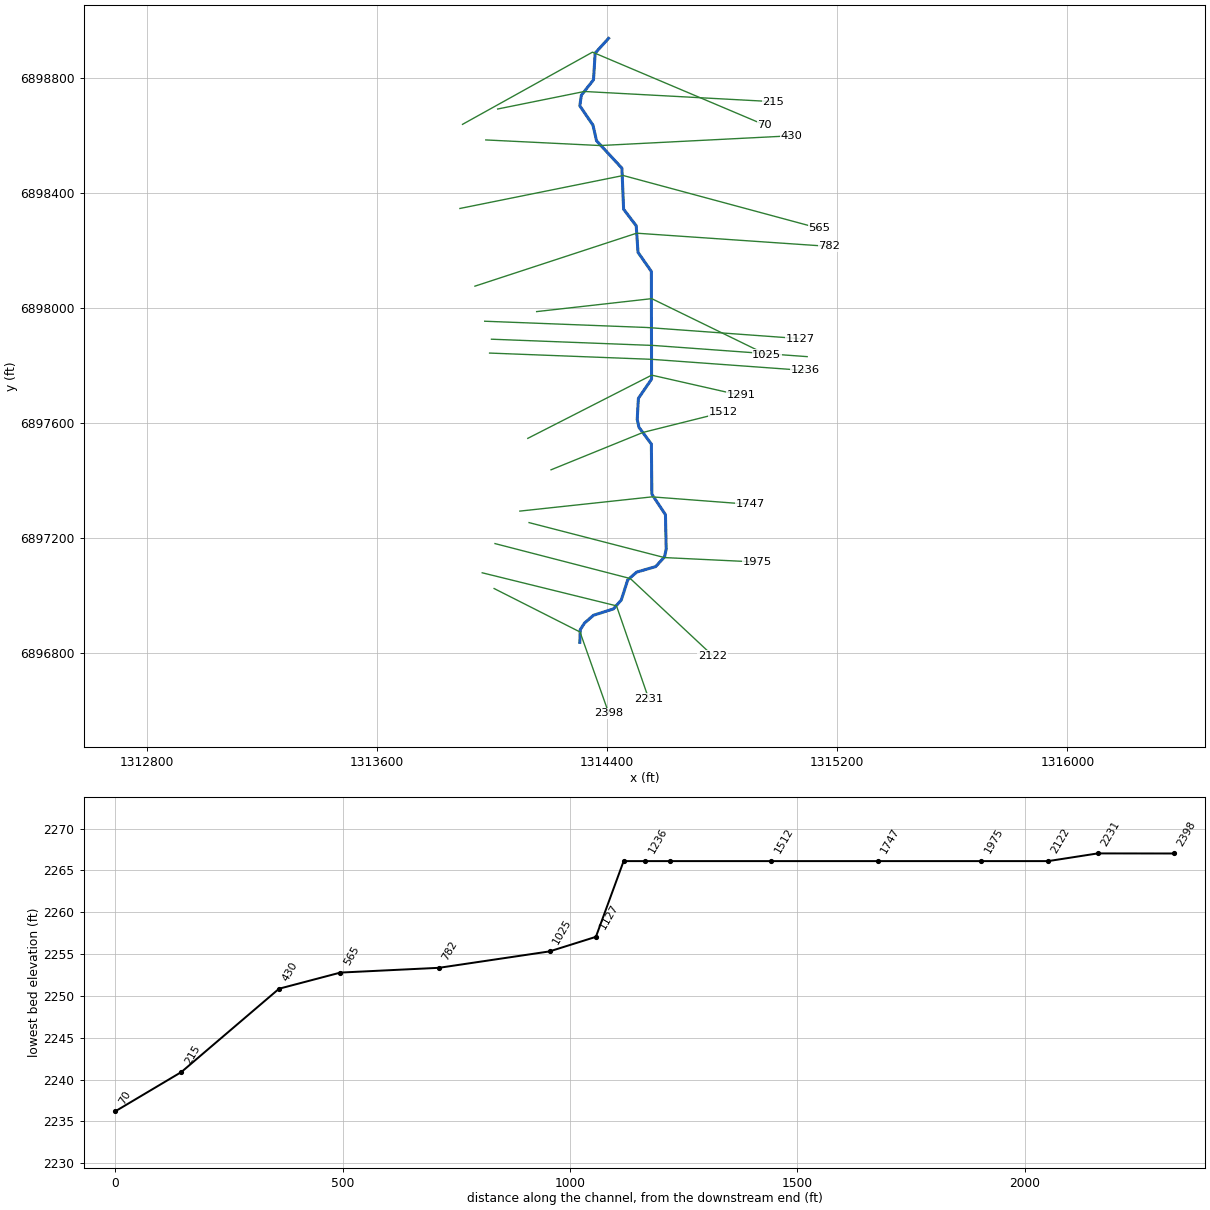
--- Linn Creek Trib058.prj (project) ---

Proj Title=Linn Creek Trib058 Base Level Engineering
Current Plan=p01
Default Exp/Contr=0.3,0.1
English Units
Geom File=g01
Flow File=f01
Plan File=p01
BEGIN DESCRIPTION:
Linn Creek Trib058
END DESCRIPTION:

--- Linn Creek Trib058.p01 (plan) ---

Plan Title=Multiple Run
Short Identifier=Multiple
Geom File=g01
Flow File=f01
Subcritical Flow
K Sum by GR= 0
Std Step Tol= 0.01
Critical Tol= 0.01
Num of Std Step Trials= 20
Max Error Tol= 0.3
Flow Tol Ratio= 0.001
Split Flow NTrial= 30
Split Flow Tol= 0.02
Split Flow Ratio= 0.02
Log Output Level= 0
Friction Slope Method= 1
Unsteady Friction Slope Method= 2
Unsteady Bridges Friction Slope Method= 1
Parabolic Critical Depth
Global Vel Dist=  1 , 1 , 1
Global Log Level= 0
CheckData=True
Encroach Param= -1, 0, 0, 0
BEGIN DESCRIPTION:
Multiple Run
END DESCRIPTION:

--- Linn Creek Trib058.f01 (steady flow) ---

Flow Title=Multiple
Number of Profiles=7
Profile Names=10-year,25-year,50-year,1pct_min,100-year,1pct_plu,500-year
River Rch & RM= Linn Creek Trib0,Reach-1,2398
     312     449     566     355     709    1414    1127
Boundary for River Rch & Prof#=Linn Creek Trib0,Reach-1,1
Up Type=0
Dn Type=3
Dn Slope=0.005
Boundary for River Rch & Prof#=Linn Creek Trib0,Reach-1,2
Up Type=0
Dn Type=3
Dn Slope=0.005
Boundary for River Rch & Prof#=Linn Creek Trib0,Reach-1,3
Up Type=0
Dn Type=3
Dn Slope=0.005
Boundary for River Rch & Prof#=Linn Creek Trib0,Reach-1,4
Up Type=0
Dn Type=3
Dn Slope=0.005
Boundary for River Rch & Prof#=Linn Creek Trib0,Reach-1,5
Up Type=0
Dn Type=3
Dn Slope=0.005
Boundary for River Rch & Prof#=Linn Creek Trib0,Reach-1,6
Up Type=0
Dn Type=3
Dn Slope=0.005
Boundary for River Rch & Prof#=Linn Creek Trib0,Reach-1,7
Up Type=0
Dn Type=3
Dn Slope=0.005

--- Linn Creek Trib058.g01 (geometry) ---

Geom Title=Existing Conditions

River Reach=Linn Creek Trib0,Reach-1
Reach XY= 30
      1314305.00      6896838.00      1314306.56      6896882.13
      1314321.36      6896905.23      1314352.52      6896932.28
      1314422.05      6896954.49      1314449.24      6896985.49
      1314471.50      6897055.04      1314502.49      6897082.23
      1314568.62      6897101.46      1314599.65      6897135.30
      1314605.36      6897162.80      1314602.75      6897282.06
      1314555.52      6897353.22      1314553.78      6897527.50
      1314510.68      6897585.69      1314504.60      6897613.00
      1314508.70      6897686.40      1314554.48      6897753.22
      1314553.78      6898127.50      1314507.36      6898193.98
      1314501.14      6898286.40      1314457.27      6898343.94
      1314451.45      6898486.53      1314363.16      6898581.95
      1314350.75      6898636.26      1314305.08      6898703.39
      1314310.37      6898740.18      1314352.65      6898793.95
      1314358.39      6898886.60      1314405.00      6898938.00

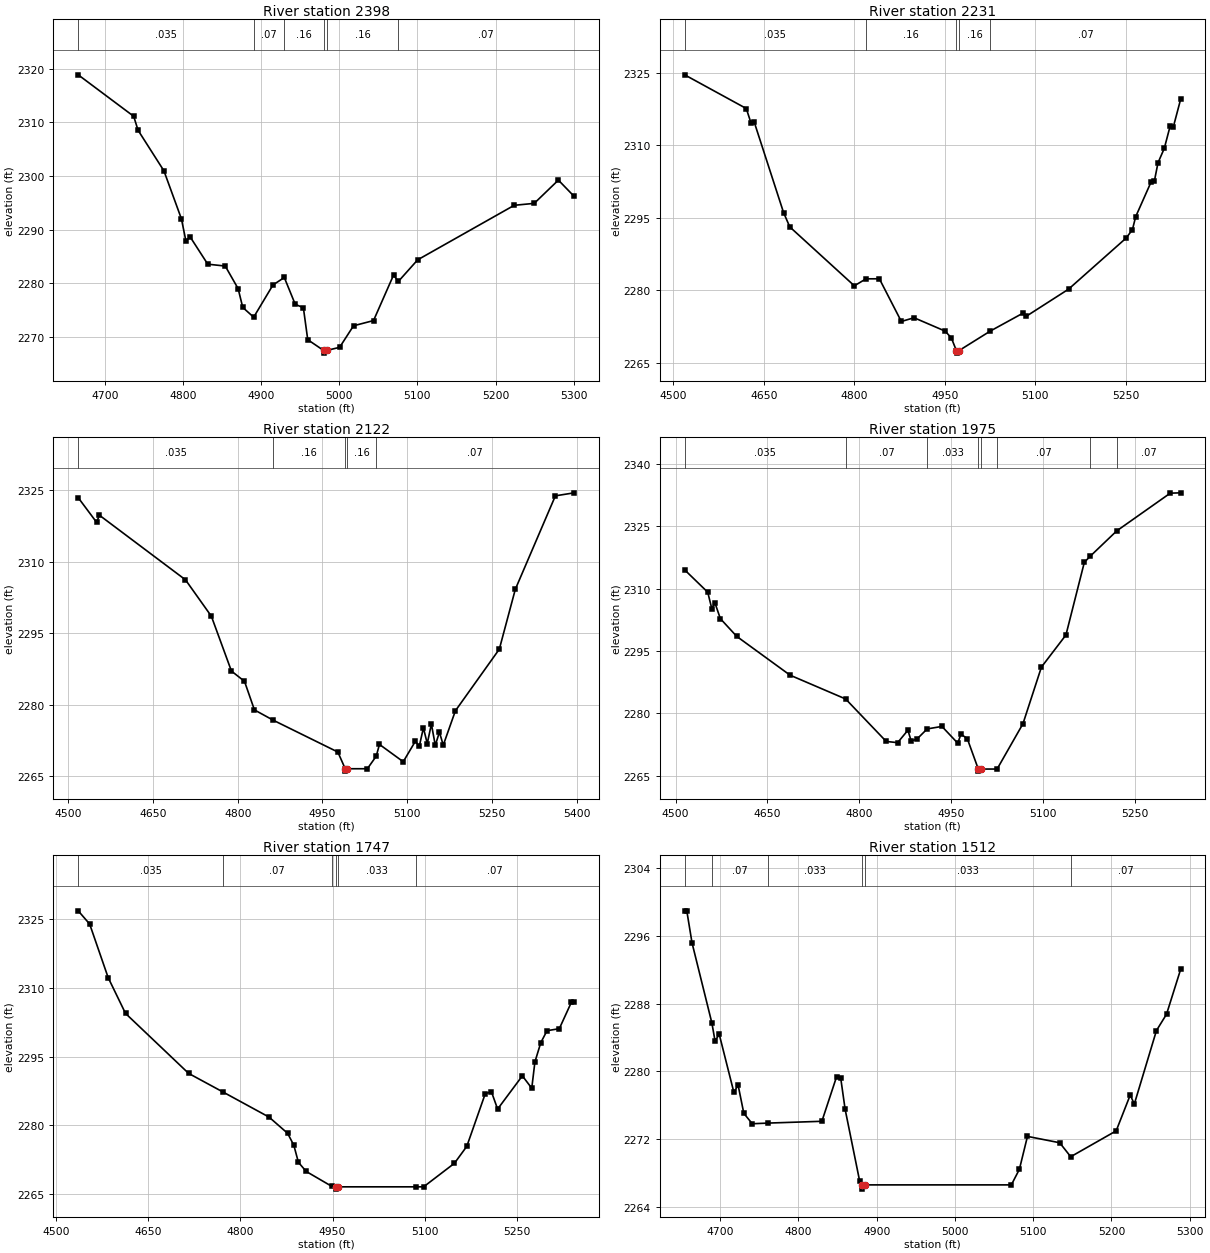
Type RM Length L Ch R = 1,2398,167,167,167
BEGIN DESCRIPTION:
Linn Creek Trib058 5.0
END DESCRIPTION:
XS GIS Cut Line= 3
      1314007.08      6897025.26      1314305.68      6896874.22
      1314405.77      6896591.23
#Sta/Elev= 30
  4665.8 2318.83  4736.8 2311.11  4742.4 2308.51  4775.5 2300.96  4797.9 2292.02
  4803.6 2287.94  4809.2 2288.63  4831.6 2283.58  4854.0 2283.23  4870.5 2279.02
  4876.4 2275.53  4890.4 2273.71  4915.1 2279.71  4929.6 2281.10  4943.6 2276.10
  4954.0 2275.48  4959.6 2269.52  4979.9 2267.52  4980.2 2267.02  4983.9 2267.52
  5000.4 2268.10  5018.2 2272.11  5043.8 2273.08  5069.4 2281.54  5075.6 2280.37
  5100.3 2284.39  5223.9 2294.54  5249.5 2294.90  5280.4 2299.23  5300.6 2296.20
#Mann=6,-1,0
  4665.8   0.035       0  4890.4    0.07       0  4929.6    0.16       0
  4979.9    0.07       0  4983.9    0.16       0  5075.6    0.07       0
Bank Sta=4979.9,4983.9
Exp/Cntr=0.3,0.1

Type RM Length L Ch R = 1,2231,109,109,109
BEGIN DESCRIPTION:
Linn Creek Trib058 4.6
END DESCRIPTION:
XS GIS Cut Line= 3
      1313965.82      6897079.95      1314432.54      6896965.02
      1314544.37      6896642.52
#Sta/Elev= 30
  4519.0 2324.53  4621.1 2317.57  4629.0 2314.55  4634.2 2314.79  4682.9 2296.07
  4693.2 2293.11  4800.2 2280.94  4819.6 2282.38  4841.7 2282.39  4878.1 2273.57
  4899.2 2274.34  4950.7 2271.58  4961.0 2270.17  4969.4 2267.53  4969.6 2267.03
  4973.4 2267.53  5025.7 2271.60  5079.7 2275.29  5085.0 2274.63  5155.3 2280.25
  5250.5 2290.78  5261.1 2292.53  5266.5 2295.21  5292.4 2302.49  5297.6 2302.65
  5303.5 2306.35  5314.0 2309.36  5323.5 2313.88  5328.8 2313.71  5341.0 2319.46
#Mann=5,-1,0
  4519.0   0.035       0  4819.6    0.16       0  4969.4    0.07       0
  4973.4    0.16       0  5025.7    0.07       0
Bank Sta=4969.4,4973.4
Exp/Cntr=0.3,0.1

Type RM Length L Ch R = 1,2122,147,147,147
BEGIN DESCRIPTION:
Linn Creek Trib058 4.5
END DESCRIPTION:
XS GIS Cut Line= 3
      1314010.15      6897181.50      1314480.60      6897059.98
      1314766.56      6896792.42
#Sta/Elev= 30
  4517.8 2323.41  4550.2 2318.27  4555.4 2319.73  4707.6 2306.20  4753.4 2298.57
  4788.9 2287.08  4812.0 2284.93  4829.6 2278.94  4862.7 2276.79  4977.2 2270.11
  4990.2 2266.61  4990.4 2266.11  4994.2 2266.61  5029.4 2266.61  5045.1 2269.24
  5050.8 2271.71  5092.9 2268.08  5114.4 2272.38  5121.2 2271.29  5128.6 2275.18
  5135.4 2271.88  5142.7 2275.98  5149.6 2271.51  5156.9 2274.28  5163.7 2271.55
  5185.2 2278.76  5262.9 2291.67  5291.2 2304.21  5362.1 2323.80  5395.3 2324.43
#Mann=5,-1,0
  4517.8   0.035       0  4862.7    0.16       0  4990.2    0.07       0
  4994.2    0.16       0  5045.1    0.07       0
Bank Sta=4990.2,4994.2
Exp/Cntr=0.3,0.1

Type RM Length L Ch R = 1,1975,228,228,228
BEGIN DESCRIPTION:
Linn Creek Trib058 4.0
END DESCRIPTION:
XS GIS Cut Line= 3
      1314128.60      6897254.42      1314599.09      6897132.90
      1314921.89      6897117.36
#Sta/Elev= 30
  4514.9 2314.51  4552.5 2309.14  4559.1 2305.22  4564.3 2306.56  4573.1 2302.78
  4599.8 2298.52  4686.8 2289.19  4777.5 2283.46  4843.7 2273.25  4862.3 2272.96
  4879.1 2275.95  4884.3 2273.42  4893.3 2273.74  4910.5 2276.26  4934.6 2276.86
  4960.4 2272.83  4965.6 2274.98  4975.9 2273.95  4993.9 2266.61  4994.2 2266.11
  4997.9 2266.61  5024.6 2266.61  5066.8 2277.51  5096.9 2291.13  5136.9 2298.85
  5166.9 2316.32  5176.5 2317.79  5219.8 2323.89  5307.1 2332.96  5324.0 2333.04
#Mann=8,-1,0
  4514.9   0.035       0  4777.5    0.07       0  4910.5   0.033       0
  4993.9   0.033       0  4997.9   0.033       0  5024.6    0.07       0
  5176.5   0.035       0  5219.8    0.07       0
Bank Sta=4993.9,4997.9
Exp/Cntr=0.3,0.1

Type RM Length L Ch R = 1,1747,235,235,235
BEGIN DESCRIPTION:
Linn Creek Trib058 3.5
END DESCRIPTION:
XS GIS Cut Line= 3
      1314096.55      6897294.44      1314556.24      6897343.93
      1314899.00      6897317.79
#Sta/Elev= 30
  4536.6 2326.74  4555.2 2323.86  4585.3 2312.18  4613.5 2304.39  4716.1 2291.32
  4771.5 2287.30  4846.8 2281.80  4877.0 2278.27  4887.1 2275.65  4894.5 2271.95
  4907.2 2269.96  4948.7 2266.72  4955.5 2266.61  4955.7 2266.11  4959.5 2266.61
  5085.8 2266.61  5098.0 2266.61  5148.1 2271.74  5168.2 2275.43  5198.3 2286.93
  5208.3 2287.30  5218.3 2283.55  5258.5 2290.79  5273.8 2288.09  5278.9 2293.81
  5288.5 2298.03  5298.6 2300.62  5318.6 2301.07  5338.2 2306.82  5342.7 2306.82
#Mann=6,-1,0
  4536.6   0.035       0  4771.5    0.07       0  4948.7   0.033       0
  4955.5   0.033       0  4959.5   0.033       0  5085.8    0.07       0
Bank Sta=4955.5,4959.5
Exp/Cntr=0.3,0.1

Type RM Length L Ch R = 1,1512,221,221,221
BEGIN DESCRIPTION:
Linn Creek Trib058 3.0
END DESCRIPTION:
XS GIS Cut Line= 3
      1314204.99      6897437.99      1314525.07      6897568.05
      1314804.97      6897637.99
#Sta/Elev= 30
  4654.5 2298.93  4657.2 2298.93  4663.9 2295.15  4689.3 2285.69  4693.3 2283.59
  4698.7 2284.36  4717.4 2277.52  4722.8 2278.38  4730.1 2275.05  4740.9 2273.82
  4761.6 2273.90  4829.9 2274.11  4848.6 2279.34  4854.0 2279.19  4859.6 2275.53
  4878.1 2267.10  4881.5 2266.61  4881.7 2266.11  4885.5 2266.61  5072.1 2266.61
  5082.4 2268.45  5092.7 2272.33  5133.9 2271.58  5148.0 2269.93  5206.1 2272.98
  5224.1 2277.21  5229.3 2276.14  5257.6 2284.81  5270.5 2286.74  5288.5 2292.02
#Mann=6,-1,0
  4654.5   0.035       0  4689.3    0.07       0  4761.6   0.033       0
  4881.5   0.033       0  4885.5   0.033       0  5148.0    0.07       0
Bank Sta=4881.5,4885.5
Exp/Cntr=0.3,0.1

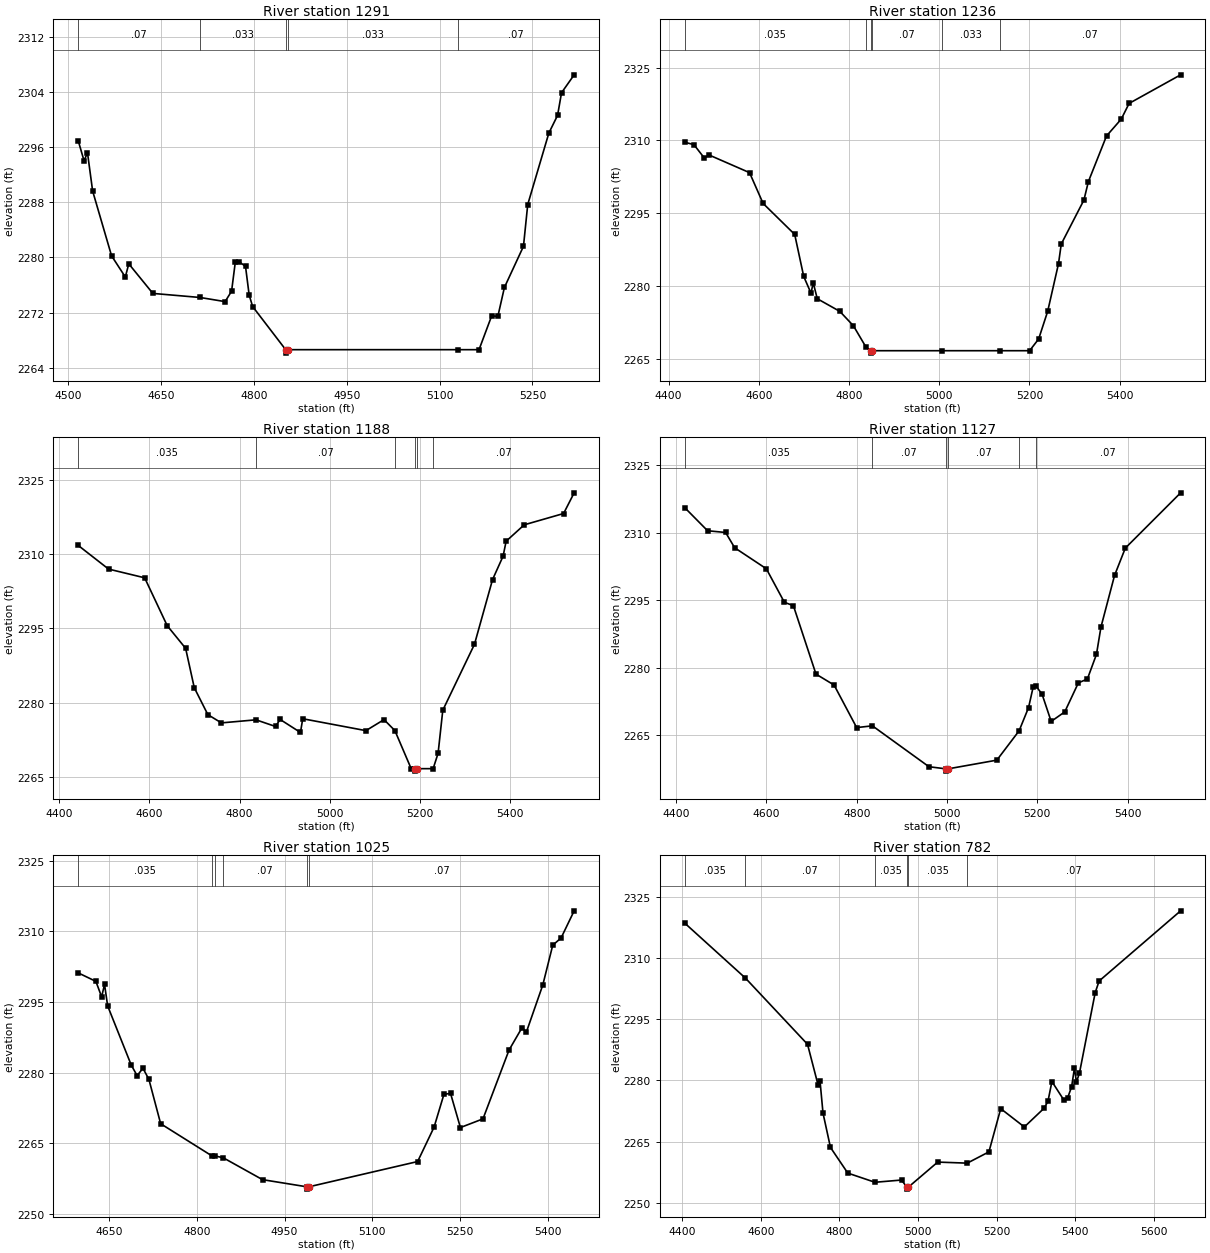
Type RM Length L Ch R = 1,1291,55,55,55
BEGIN DESCRIPTION:
Linn Creek Trib058 2.6
END DESCRIPTION:
XS GIS Cut Line= 3
      1314124.26      6897547.37      1314554.93      6897767.10
      1314864.86      6897696.78
#Sta/Elev= 30
  4516.1 2296.92  4525.5 2294.02  4531.1 2295.16  4539.4 2289.62  4570.0 2280.22
  4592.2 2277.15  4597.8 2279.06  4636.7 2274.77  4713.0 2274.18  4753.4 2273.58
  4763.9 2275.09  4770.0 2279.37  4775.6 2279.39  4786.4 2278.70  4792.3 2274.54
  4797.9 2272.87  4851.3 2266.61  4851.6 2266.11  4855.4 2266.61  5129.6 2266.61
  5163.7 2266.61  5184.2 2271.53  5194.1 2271.43  5204.7 2275.63  5235.5 2281.60
  5242.4 2287.66  5276.5 2298.02  5290.6 2300.59  5297.0 2303.87  5317.4 2306.47
#Mann=5,-1,0
  4516.1    0.07       0  4713.0   0.033       0  4851.3   0.033       0
  4855.4   0.033       0  5129.6    0.07       0
Bank Sta=4851.3,4855.4
Exp/Cntr=0.3,0.1

Type RM Length L Ch R = 1,1236,48,48,48
BEGIN DESCRIPTION:
Linn Creek Trib058 2.5
END DESCRIPTION:
XS GIS Cut Line= 3
      1313991.31      6897843.85      1314555.86      6897822.04
      1315088.88      6897783.28
#Sta/Elev= 30
  4435.7 2309.63  4456.1 2309.15  4479.4 2306.36  4489.4 2307.02  4579.5 2303.36
  4609.5 2297.01  4679.6 2290.61  4699.6 2281.93  4715.7 2278.49  4720.7 2280.63
  4729.6 2277.34  4779.6 2274.73  4809.7 2271.76  4837.8 2267.32  4847.7 2266.61
  4848.0 2266.11  4851.8 2266.61  5005.2 2266.61  5134.1 2266.61  5200.3 2266.61
  5220.4 2269.03  5240.4 2274.74  5264.4 2284.58  5270.5 2288.63  5320.7 2297.70
  5330.7 2301.53  5370.8 2310.93  5403.5 2314.41  5420.9 2317.65  5535.1 2323.55
#Mann=6,-1,0
  4435.7   0.035       0  4837.8    0.07       0  4847.7    0.07       0
  4851.8    0.07       0  5005.2   0.033       0  5134.1    0.07       0
Bank Sta=4847.7,4851.8
Exp/Cntr=0.3,0.1

Type RM Length L Ch R = 1,1188,61,61,61
BEGIN DESCRIPTION:
Linn Creek Trib058 2.2
END DESCRIPTION:
XS GIS Cut Line= 3
      1313997.86      6897892.03      1314562.37      6897870.22
      1315095.43      6897831.45
#Sta/Elev= 30
  4442.4 2311.82  4509.6 2307.03  4589.7 2305.26  4639.7 2295.56  4680.5 2290.98
  4699.7 2283.00  4729.8 2277.55  4759.8 2275.88  4836.5 2276.50  4879.9 2275.15
  4889.9 2276.58  4935.1 2273.94  4940.1 2276.72  5080.2 2274.31  5120.3 2276.54
  5144.4 2274.32  5180.4 2266.63  5188.4 2266.61  5188.7 2266.11  5192.5 2266.61
  5229.2 2266.61  5240.2 2269.73  5250.6 2278.44  5320.8 2291.79  5360.9 2304.90
  5384.3 2309.65  5391.0 2312.67  5431.1 2315.99  5518.4 2318.28  5541.8 2322.47
#Mann=6,-1,0
  4442.4   0.035       0  4836.5    0.07       0  5144.4   0.033       0
  5188.4    0.07       0  5192.5   0.033       0  5229.2    0.07       0
Bank Sta=5188.4,5192.5
Exp/Cntr=0.3,0.1

Type RM Length L Ch R = 1,1127,102,102,102
BEGIN DESCRIPTION:
Linn Creek Trib058 2.1
END DESCRIPTION:
XS GIS Cut Line= 3
      1313974.37      6897954.53      1314538.93      6897932.72
      1315070.94      6897894.03
#Sta/Elev= 30
  4418.9 2315.59  4469.6 2310.45  4509.6 2310.06  4529.6 2306.67  4599.7 2302.01
  4639.7 2294.56  4659.7 2293.80  4709.7 2278.61  4749.8 2276.18  4799.8 2266.73
  4834.7 2267.12  4959.9 2258.04  4997.9 2257.56  4998.2 2257.06  5002.0 2257.56
  5110.3 2259.50  5159.6 2266.02  5180.5 2271.17  5190.5 2275.64  5196.4 2276.04
  5210.5 2274.13  5230.6 2268.10  5260.7 2270.22  5290.8 2276.66  5310.8 2277.52
  5330.9 2282.99  5340.9 2289.07  5371.0 2300.53  5394.8 2306.59  5517.3 2318.87
#Mann=6,-1,0
  4418.9   0.035       0  4834.7    0.07       0  4997.9    0.07       0
  5002.0    0.07       0  5159.6   0.033       0  5196.4    0.07       0
Bank Sta=4997.9,5002
Exp/Cntr=0.3,0.1

Type RM Length L Ch R = 1,1025,243,243,243
BEGIN DESCRIPTION:
Linn Creek Trib058 2.0
END DESCRIPTION:
XS GIS Cut Line= 3
      1314154.99      6897988.00      1314555.06      6898033.03
      1314955.04      6897837.98
#Sta/Elev= 30
  4597.4 2301.18  4627.6 2299.38  4637.4 2296.10  4642.4 2298.72  4647.7 2294.18
  4688.0 2281.64  4698.0 2279.40  4708.1 2280.94  4718.2 2278.60  4738.3 2269.19
  4826.3 2262.34  4831.7 2262.35  4845.4 2261.96  4912.4 2257.33  4987.8 2255.82
  4988.1 2255.32  4991.9 2255.82  5177.5 2261.17  5205.6 2268.47  5222.4 2275.41
  5233.7 2275.64  5250.6 2268.38  5289.2 2270.22  5333.7 2284.81  5356.0 2289.58
  5363.3 2288.61  5391.4 2298.61  5408.4 2307.05  5422.7 2308.59  5445.0 2314.34
#Mann=6,-1,0
  4597.4   0.035       0  4826.3    0.07       0  4831.7   0.035       0
  4845.4    0.07       0  4987.8    0.07       0  4991.9    0.07       0
Bank Sta=4987.8,4991.9
Exp/Cntr=0.3,0.1

Type RM Length L Ch R = 1,782,217,217,217
BEGIN DESCRIPTION:
Linn Creek Trib058 1.5
END DESCRIPTION:
XS GIS Cut Line= 3
      1313940.44      6898076.44      1314502.55      6898260.58
      1315171.87      6898214.67
#Sta/Elev= 30
  4406.0 2318.59  4560.7 2305.09  4718.7 2288.87  4745.3 2278.99  4750.6 2279.79
  4758.1 2272.00  4777.1 2263.58  4821.2 2257.29  4890.4 2255.04  4958.0 2255.59
  4971.4 2253.86  4971.7 2253.36  4975.5 2253.86  5050.1 2259.99  5125.2 2259.73
  5180.4 2262.49  5210.5 2273.09  5270.6 2268.60  5320.7 2273.18  5330.7 2274.88
  5340.8 2279.74  5370.8 2275.25  5380.9 2275.78  5390.9 2278.42  5398.2 2283.07
  5403.2 2279.60  5410.9 2281.82  5451.0 2301.55  5461.0 2304.39  5668.4 2321.59
#Mann=6,-1,0
  4406.0   0.035       0  4560.7    0.07       0  4890.4   0.035       0
  4971.4   0.035       0  4975.5   0.035       0  5125.2    0.07       0
Bank Sta=4971.4,4975.5
Exp/Cntr=0.3,0.1

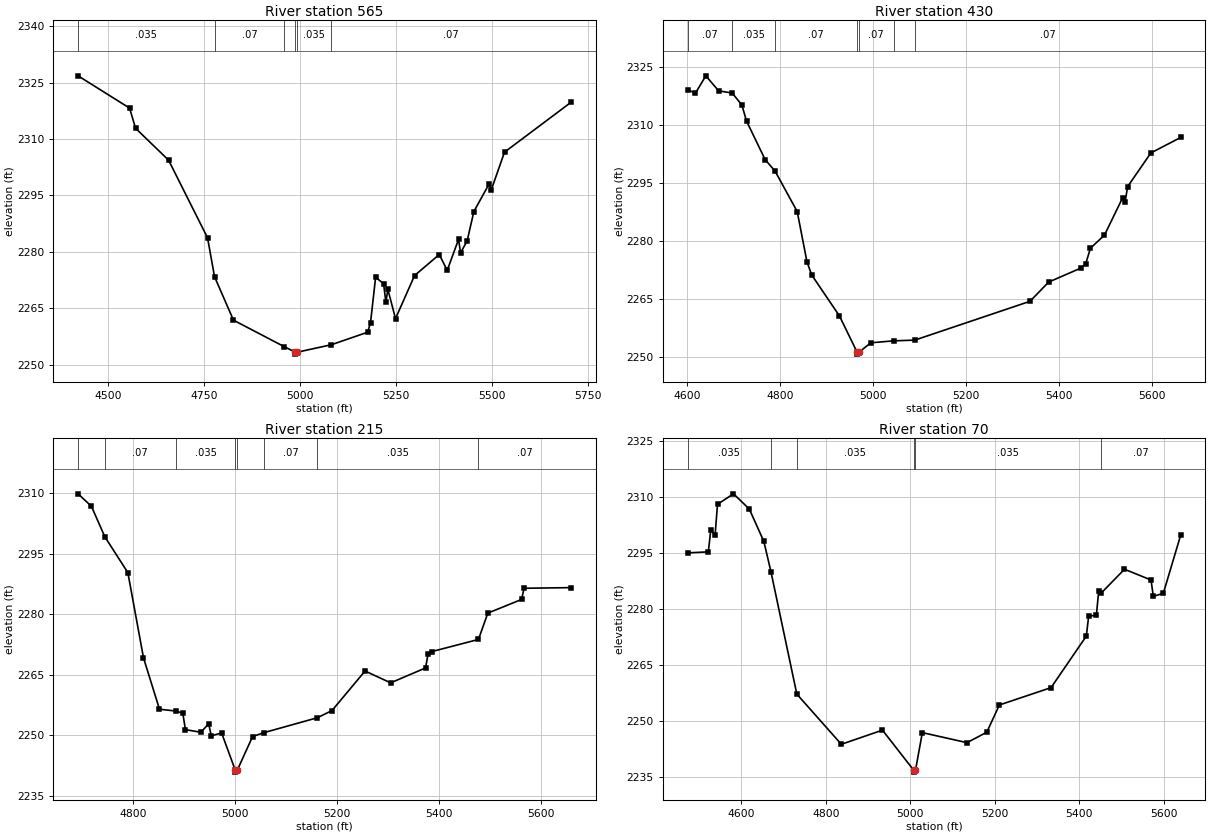
Type RM Length L Ch R = 1,565,135,135,135
BEGIN DESCRIPTION:
Linn Creek Trib058 1.2
END DESCRIPTION:
XS GIS Cut Line= 3
      1313888.26      6898346.53      1314455.98      6898461.11
      1315137.00      6898277.51
#Sta/Elev= 30
  4421.5 2326.80  4555.6 2318.22  4571.2 2312.86  4657.2 2304.37  4758.7 2283.72
  4776.9 2273.38  4826.2 2261.82  4958.3 2254.78  4987.4 2253.29  4987.7 2252.79
  4991.5 2253.29  5080.9 2255.28  5175.7 2258.62  5183.2 2261.20  5196.4 2273.24
  5217.2 2271.51  5223.1 2266.62  5228.3 2270.01  5248.2 2262.23  5297.8 2273.68
  5362.2 2279.28  5382.9 2275.06  5412.4 2283.32  5417.6 2279.72  5434.7 2282.89
  5452.3 2290.71  5492.2 2298.10  5497.4 2296.42  5532.1 2306.50  5706.0 2319.82
#Mann=6,-1,0
  4421.5   0.035       0  4776.9    0.07       0  4958.3   0.035       0
  4987.4   0.035       0  4991.5   0.035       0  5080.9    0.07       0
Bank Sta=4987.4,4991.5
Exp/Cntr=0.3,0.1

Type RM Length L Ch R = 1,430,215,215,215
BEGIN DESCRIPTION:
Linn Creek Trib058 1.0
END DESCRIPTION:
XS GIS Cut Line= 3
      1313978.07      6898584.81      1314375.25      6898565.28
      1315039.32      6898599.13
#Sta/Elev= 30
  4600.3 2319.19  4617.3 2318.27  4639.7 2322.76  4667.3 2318.88  4696.6 2318.31
  4717.4 2315.21  4727.4 2311.07  4767.4 2301.13  4788.9 2298.14  4836.6 2287.69
  4857.5 2274.76  4867.6 2271.35  4927.6 2260.72  4965.6 2251.36  4965.9 2250.86
  4969.7 2251.36  4995.3 2253.79  5044.2 2254.29  5089.8 2254.48  5338.2 2264.51
  5378.2 2269.47  5448.3 2273.12  5458.3 2274.25  5468.3 2278.23  5498.4 2281.58
  5537.9 2291.31  5542.9 2290.07  5548.4 2294.13  5598.5 2302.84  5662.9 2306.84
#Mann=7,-1,0
  4600.3    0.07       0  4696.6   0.035       0  4788.9    0.07       0
  4965.6    0.07       0  4969.7    0.07       0  5044.2   0.035       0
  5089.8    0.07       0
Bank Sta=4965.6,4969.7
Exp/Cntr=0.3,0.1

Type RM Length L Ch R = 1,215,145,145,145
BEGIN DESCRIPTION:
Linn Creek Trib058 0.5
END DESCRIPTION:
XS GIS Cut Line= 3
      1314019.43      6898692.28      1314320.94      6898753.24
      1314978.27      6898717.82
#Sta/Elev= 30
  4692.9 2309.86  4719.0 2306.78  4745.2 2299.24  4790.4 2290.33  4821.0 2269.23
  4852.3 2256.49  4884.1 2256.04  4898.0 2255.50  4903.1 2251.43  4933.2 2250.78
  4948.7 2252.86  4953.8 2249.89  4974.0 2250.60  5000.7 2241.40  5000.9 2240.90
  5004.8 2241.40  5034.6 2249.72  5057.4 2250.70  5161.6 2254.38  5190.3 2256.17
  5254.9 2265.96  5305.0 2263.02  5373.4 2266.72  5378.4 2270.27  5385.1 2270.75
  5477.0 2273.78  5495.3 2280.30  5561.4 2283.69  5566.4 2286.46  5658.8 2286.62
#Mann=8,-1,0
  4692.9   0.035       0  4745.2    0.07       0  4884.1   0.035       0
  5000.7   0.035       0  5004.8   0.035       0  5057.4    0.07       0
  5161.6   0.035       0  5477.0    0.07       0
Bank Sta=5000.7,5004.8
Exp/Cntr=0.3,0.1

Type RM Length L Ch R = 1,70,0,0,0
BEGIN DESCRIPTION:
Linn Creek Trib058 0.4
END DESCRIPTION:
XS GIS Cut Line= 3
      1313897.24      6898638.98      1314349.15      6898889.96
      1314947.56      6898636.77
#Sta/Elev= 30
  4473.2 2294.97  4522.4 2295.24  4528.1 2301.08  4538.4 2299.77  4544.1 2307.99
  4581.9 2310.79  4619.3 2306.72  4653.7 2298.04  4670.5 2289.91  4731.7 2257.13
  4837.0 2243.68  4934.3 2247.47  5008.3 2236.72  5008.6 2236.22  5012.4 2236.72
  5028.6 2246.81  5134.3 2244.11  5181.1 2246.92  5210.8 2254.21  5333.1 2258.86
  5416.6 2272.68  5422.0 2278.00  5440.3 2278.27  5445.7 2284.67  5450.9 2284.10
  5506.8 2290.58  5569.6 2287.70  5575.0 2283.31  5598.7 2284.14  5639.9 2299.80
#Mann=6,-1,0
  4473.2   0.035       0  4670.5    0.07       0  4731.7   0.035       0
  5008.3   0.035       0  5012.4   0.035       0  5450.9    0.07       0
Bank Sta=5008.3,5012.4
Exp/Cntr=0.3,0.1

Chan Stop Cuts=-1