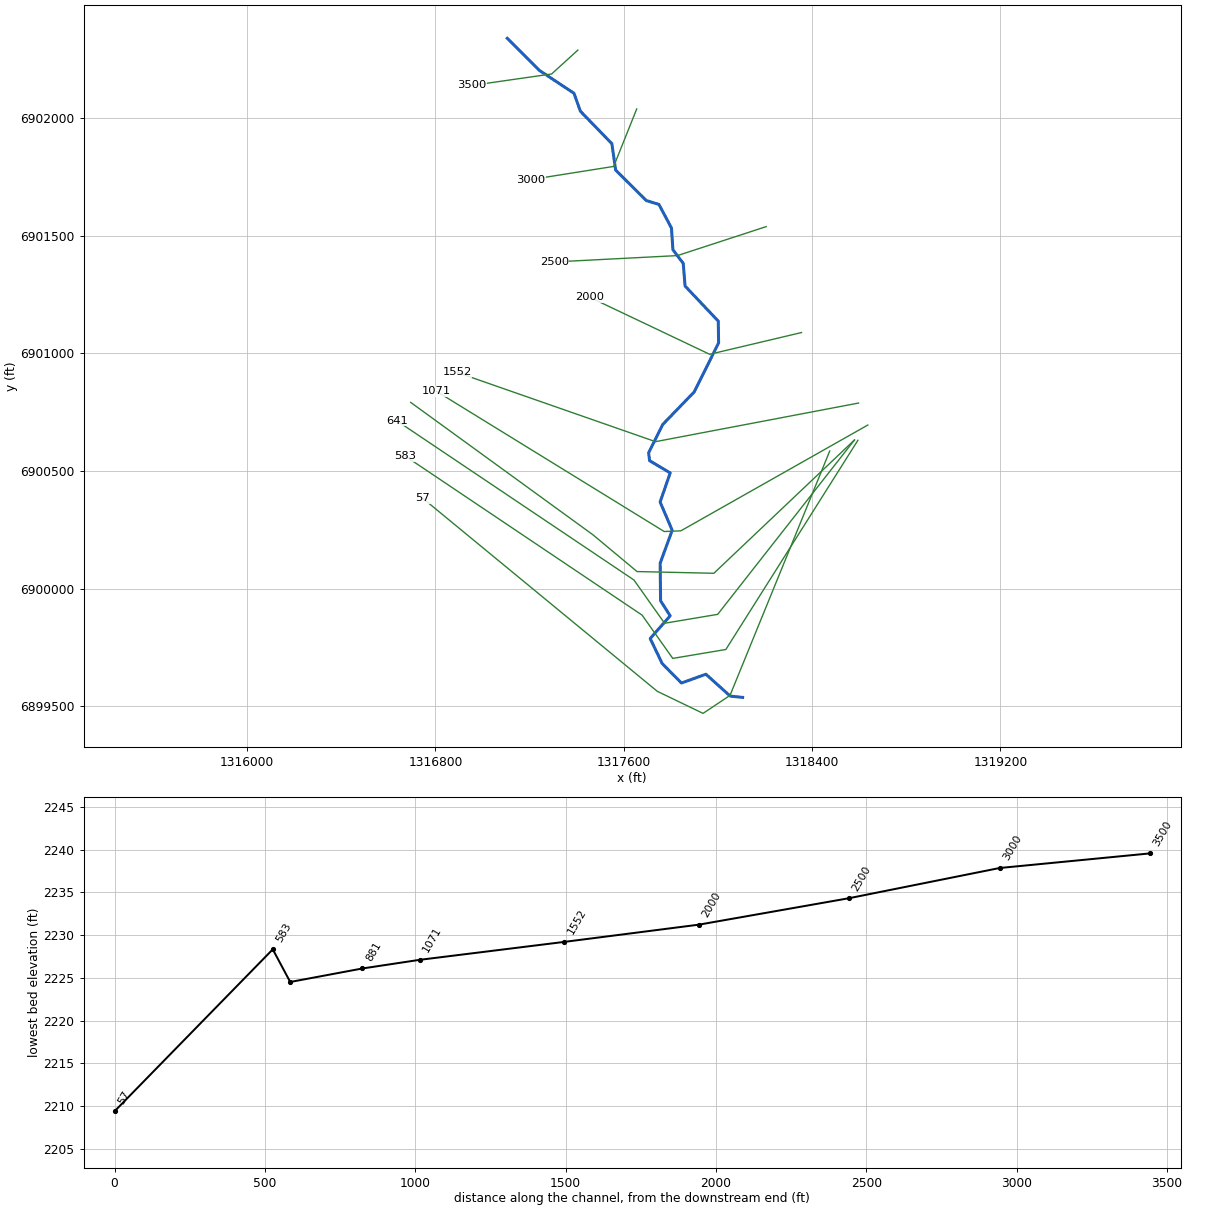
--- Linn Creek Trib059.prj (project) ---

Proj Title=Linn Creek Trib059 Base Level Engineering
Current Plan=p01
Default Exp/Contr=0.3,0.1
English Units
Geom File=g01
Flow File=f01
Plan File=p01
BEGIN DESCRIPTION:
Linn Creek Trib059
END DESCRIPTION:

--- Linn Creek Trib059.p01 (plan) ---

Plan Title=Multiple Run
Short Identifier=Multiple
Geom File=g01
Flow File=f01
Subcritical Flow
K Sum by GR= 0
Std Step Tol= 0.01
Critical Tol= 0.01
Num of Std Step Trials= 20
Max Error Tol= 0.3
Flow Tol Ratio= 0.001
Split Flow NTrial= 30
Split Flow Tol= 0.02
Split Flow Ratio= 0.02
Log Output Level= 0
Friction Slope Method= 1
Unsteady Friction Slope Method= 2
Unsteady Bridges Friction Slope Method= 1
Parabolic Critical Depth
Global Vel Dist=  1 , 1 , 1
Global Log Level= 0
CheckData=True
Encroach Param= -1, 0, 0, 0
BEGIN DESCRIPTION:
Multiple Run
END DESCRIPTION:

--- Linn Creek Trib059.f01 (steady flow) ---

Flow Title=Multiple
Number of Profiles=7
Profile Names=10-year,25-year,50-year,1pct_min,100-year,1pct_plu,500-year
River Rch & RM= Linn Creek Trib0,Reach-1,3500
     315     452     569     357     712    1421    1128
Boundary for River Rch & Prof#=Linn Creek Trib0,Reach-1,1
Up Type=0
Dn Type=3
Dn Slope=0.005
Boundary for River Rch & Prof#=Linn Creek Trib0,Reach-1,2
Up Type=0
Dn Type=3
Dn Slope=0.005
Boundary for River Rch & Prof#=Linn Creek Trib0,Reach-1,3
Up Type=0
Dn Type=3
Dn Slope=0.005
Boundary for River Rch & Prof#=Linn Creek Trib0,Reach-1,4
Up Type=0
Dn Type=3
Dn Slope=0.005
Boundary for River Rch & Prof#=Linn Creek Trib0,Reach-1,5
Up Type=0
Dn Type=3
Dn Slope=0.005
Boundary for River Rch & Prof#=Linn Creek Trib0,Reach-1,6
Up Type=0
Dn Type=3
Dn Slope=0.005
Boundary for River Rch & Prof#=Linn Creek Trib0,Reach-1,7
Up Type=0
Dn Type=3
Dn Slope=0.005

--- Linn Creek Trib059.g01 (geometry) ---

Geom Title=Existing Conditions

River Reach=Linn Creek Trib0,Reach-1
Reach XY= 30
      1317105.00      6902338.00      1317241.79      6902201.63
      1317388.36      6902104.71      1317415.78      6902028.32
      1317549.48      6901890.43      1317565.52      6901778.21
      1317695.58      6901648.89      1317749.41      6901632.39
      1317802.68      6901532.06      1317808.85      6901439.60
      1317852.64      6901382.02      1317860.52      6901285.57
      1318001.54      6901136.50      1318002.86      6901043.97
      1317899.17      6900835.70      1317765.76      6900697.68
      1317705.55      6900576.92      1317709.83      6900543.61
      1317797.26      6900491.65      1317754.42      6900367.96
      1317805.77      6900248.05      1317754.64      6900108.15
      1317756.39      6899948.43      1317797.18      6899884.58
      1317712.31      6899788.09      1317763.12      6899681.91
      1317844.92      6899599.10      1317948.95      6899636.35
      1318052.49      6899543.33      1318105.00      6899538.00

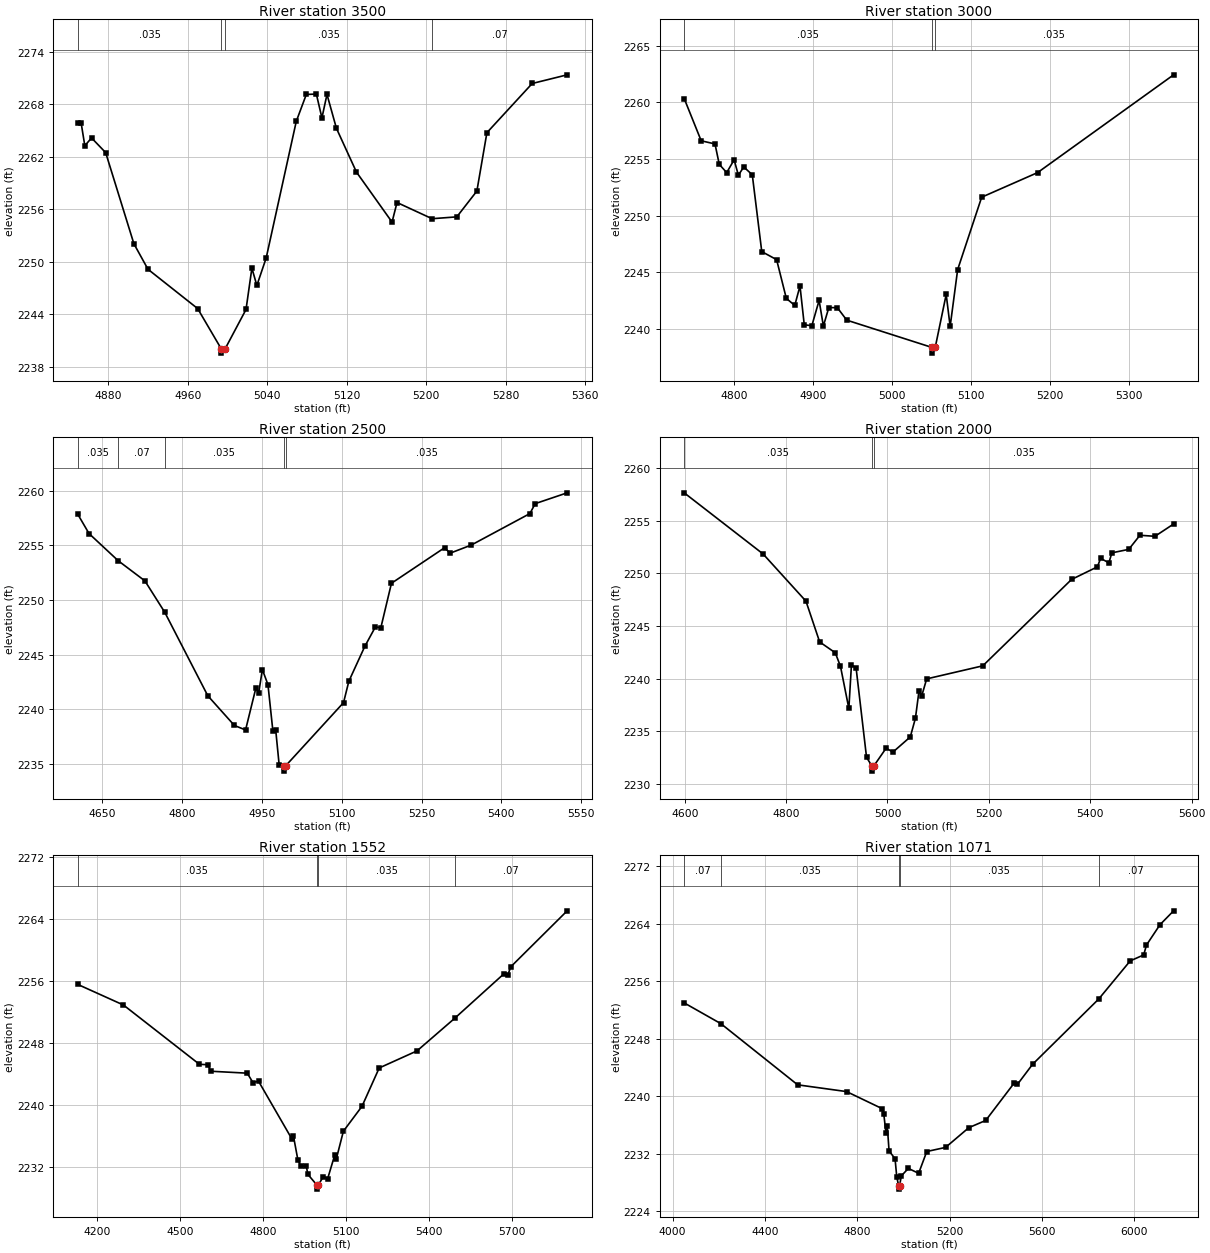
Type RM Length L Ch R = 1,3500,500,500,500
BEGIN DESCRIPTION:
Linn Creek Trib059 7.0
END DESCRIPTION:
XS GIS Cut Line= 3
      1317405.03      6902288.03      1317293.46      6902186.59
      1316955.03      6902138.00
#Sta/Elev= 30
  4849.2 2265.87  4852.6 2265.87  4856.3 2263.27  4863.1 2264.16  4877.3 2262.48
  4905.7 2252.07  4919.9 2249.15  4969.9 2244.66  4993.6 2240.07  4993.8 2239.57
  4997.6 2240.07  5018.6 2244.56  5024.5 2249.28  5029.5 2247.30  5038.9 2250.45
  5069.2 2266.06  5079.3 2269.13  5089.4 2269.17  5095.0 2266.45  5100.1 2269.13
  5109.6 2265.26  5129.8 2260.25  5165.6 2254.54  5170.6 2256.78  5205.9 2254.93
  5230.8 2255.14  5251.0 2258.09  5261.1 2264.76  5306.7 2270.38  5341.9 2271.37
#Mann=4,-1,0
  4849.2   0.035       0  4993.6   0.035       0  4997.6   0.035       0
  5205.9    0.07       0
Bank Sta=4993.6,4997.6
Exp/Cntr=0.3,0.1

Type RM Length L Ch R = 1,3000,500,500,500
BEGIN DESCRIPTION:
Linn Creek Trib059 6.0
END DESCRIPTION:
XS GIS Cut Line= 3
      1317654.99      6902037.98      1317557.16      6901793.86
      1317204.97      6901737.99
#Sta/Elev= 30
  4737.0 2260.33  4758.5 2256.60  4776.0 2256.32  4781.4 2254.52  4790.8 2253.79
  4800.2 2254.92  4805.6 2253.56  4812.4 2254.29  4823.2 2253.60  4835.2 2246.82
  4854.0 2246.11  4866.3 2242.69  4877.0 2242.07  4883.6 2243.79  4889.0 2240.36
  4898.6 2240.28  4907.8 2242.51  4913.2 2240.25  4920.1 2241.88  4930.9 2241.87
  4942.8 2240.77  5050.8 2238.36  5051.1 2237.86  5054.8 2238.36  5068.7 2243.04
  5073.7 2240.21  5083.2 2245.23  5113.6 2251.62  5184.4 2253.79  5356.6 2262.42
#Mann=3,-1,0
  4737.0   0.035       0  5050.8   0.035       0  5054.8   0.035       0
Bank Sta=5050.8,5054.8
Exp/Cntr=0.3,0.1

Type RM Length L Ch R = 1,2500,500,500,500
BEGIN DESCRIPTION:
Linn Creek Trib059 5.0
END DESCRIPTION:
XS GIS Cut Line= 3
      1318204.98      6901537.99      1317828.03      6901415.01
      1317305.03      6901388.00
#Sta/Elev= 30
  4603.5 2257.85  4624.7 2256.08  4679.6 2253.59  4729.7 2251.75  4767.0 2248.88
  4848.0 2241.23  4898.0 2238.51  4919.0 2238.10  4938.4 2241.94  4943.7 2241.49
  4950.6 2243.63  4961.1 2242.25  4970.3 2238.04  4975.6 2238.14  4982.2 2234.89
  4990.6 2234.83  4990.9 2234.33  4994.7 2234.83  5103.2 2240.60  5113.2 2242.56
  5143.2 2245.75  5163.2 2247.54  5173.3 2247.45  5193.3 2251.53  5293.4 2254.79
  5303.4 2254.28  5343.5 2255.03  5453.6 2257.91  5463.6 2258.82  5523.7 2259.81
#Mann=5,-1,0
  4603.5   0.035       0  4679.6    0.07       0  4767.0   0.035       0
  4990.6   0.035       0  4994.7   0.035       0
Bank Sta=4990.6,4994.7
Exp/Cntr=0.3,0.1

Type RM Length L Ch R = 1,2000,448,448,448
BEGIN DESCRIPTION:
Linn Creek Trib059 4.0
END DESCRIPTION:
XS GIS Cut Line= 3
      1318355.01      6901088.00      1317964.78      6900995.69
      1317455.04      6901237.98
#Sta/Elev= 30
  4599.0 2257.66  4754.7 2251.85  4839.2 2247.37  4866.2 2243.50  4897.0 2242.47
  4907.3 2241.18  4923.8 2237.18  4928.9 2241.31  4938.1 2241.03  4958.7 2232.54
  4969.1 2231.73  4969.4 2231.23  4973.2 2231.73  4997.3 2233.41  5010.8 2233.04
  5045.0 2234.48  5055.1 2236.25  5062.1 2238.82  5067.7 2238.40  5077.3 2239.99
  5188.0 2241.23  5363.0 2249.43  5414.0 2250.63  5420.5 2251.44  5436.7 2251.01
  5442.6 2251.96  5475.9 2252.29  5498.0 2253.63  5527.6 2253.53  5564.4 2254.70
#Mann=3,-1,0
  4599.0   0.035       0  4969.1   0.035       0  4973.2   0.035       0
Bank Sta=4969.1,4973.2
Exp/Cntr=0.3,0.1

Type RM Length L Ch R = 1,1552,481,481,481
BEGIN DESCRIPTION:
Linn Creek Trib059 3.0
END DESCRIPTION:
XS GIS Cut Line= 3
      1318597.42      6900788.49      1317734.93      6900624.47
      1316892.22      6900918.57
#Sta/Elev= 30
  4128.8 2255.55  4294.1 2252.90  4569.0 2245.27  4599.5 2245.22  4609.7 2244.38
  4742.0 2244.13  4762.4 2242.93  4782.7 2243.10  4903.7 2235.65  4908.8 2236.09
  4925.2 2232.95  4935.4 2232.23  4955.8 2232.15  4961.0 2231.12  4994.4 2229.71
  4994.7 2229.21  4998.6 2229.71  5017.3 2230.83  5032.9 2230.56  5058.7 2233.63
  5063.9 2233.06  5089.7 2236.66  5157.1 2239.87  5219.3 2244.80  5356.2 2247.00
  5492.4 2251.19  5669.3 2256.88  5684.5 2256.75  5695.1 2257.81  5899.3 2265.02
#Mann=4,-1,0
  4128.8   0.035       0  4994.4   0.035       0  4998.6   0.035       0
  5492.4    0.07       0
Bank Sta=4994.4,4998.6
Exp/Cntr=0.3,0.1

Type RM Length L Ch R = 1,1071,190,190,190
BEGIN DESCRIPTION:
Linn Creek Trib059 2.0
END DESCRIPTION:
XS GIS Cut Line= 4
      1318636.97      6900695.16      1317842.39      6900245.55
      1317771.69      6900242.72      1316804.99      6900838.00
#Sta/Elev= 30
  4050.4 2253.00  4209.4 2250.11  4541.6 2241.61  4753.5 2240.67  4908.1 2238.29
  4914.4 2237.61  4924.0 2234.91  4929.8 2235.84  4937.4 2232.44  4963.4 2231.32
  4970.8 2228.80  4978.7 2227.61  4978.9 2227.11  4982.9 2227.61  4990.8 2228.96
  5020.8 2229.99  5065.5 2229.31  5100.7 2232.34  5182.1 2232.91  5282.6 2235.65
  5356.0 2236.66  5477.8 2241.80  5493.2 2241.67  5558.7 2244.46  5845.2 2253.54
  5981.5 2258.84  6039.9 2259.67  6052.0 2261.05  6110.7 2263.88  6169.4 2265.80
#Mann=5,-1,0
  4050.4    0.07       0  4209.4   0.035       0  4978.7   0.035       0
  4982.9   0.035       0  5845.2    0.07       0
Bank Sta=4978.7,4982.9
Exp/Cntr=0.3,0.1

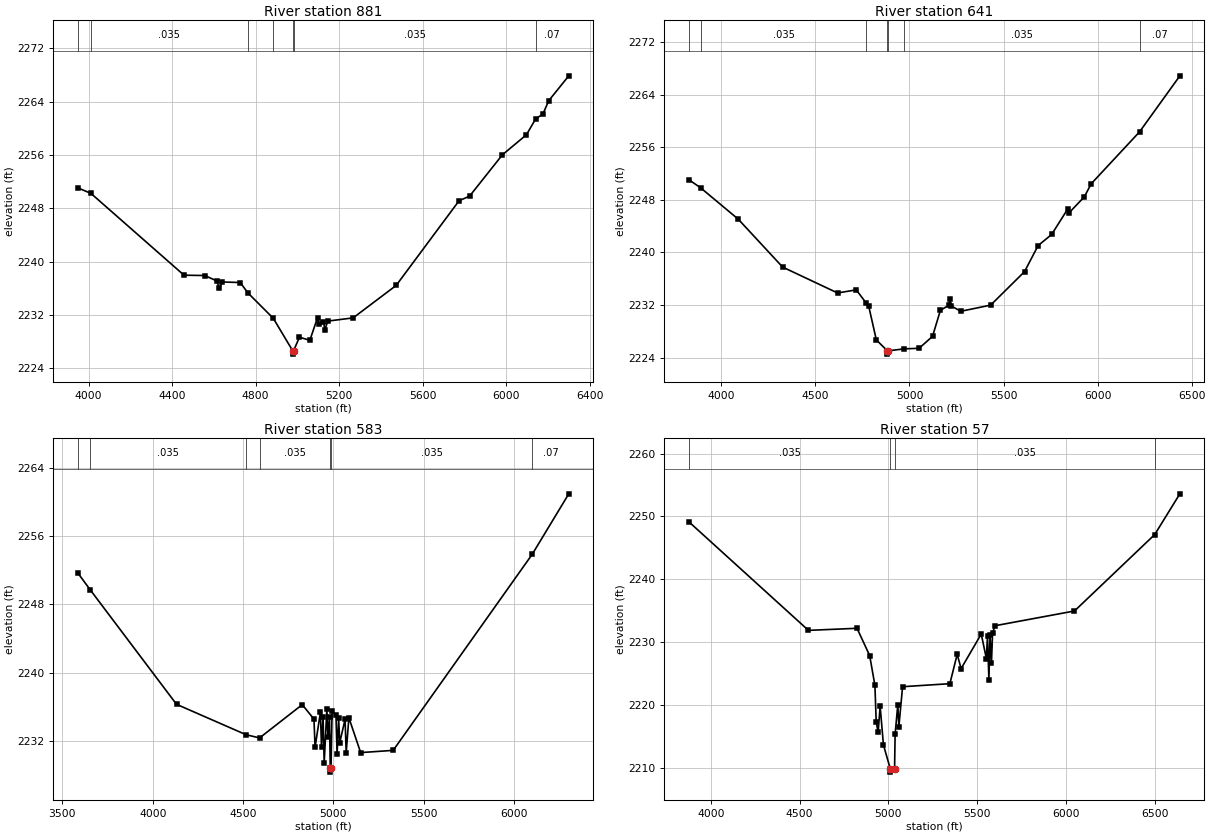
Type RM Length L Ch R = 1,881,240,240,240
BEGIN DESCRIPTION:
Linn Creek Trib059 1.6
END DESCRIPTION:
XS GIS Cut Line= 5
      1318580.07      6900631.62      1317982.77      6900065.32
      1317656.47      6900072.60      1317468.97      6900228.85
      1316694.66      6900791.35
#Sta/Elev= 30
  3948.8 2251.06  4011.1 2250.24  4457.1 2237.95  4556.2 2237.90  4612.9 2237.11
  4627.0 2236.00  4641.2 2236.93  4726.1 2236.85  4763.4 2235.28  4884.6 2231.48
  4977.6 2226.60  4977.9 2226.10  4981.8 2226.60  5009.7 2228.64  5059.7 2228.18
  5096.5 2231.58  5102.8 2230.57  5124.9 2230.96  5131.4 2229.76  5145.7 2231.06
  5266.8 2231.54  5472.8 2236.41  5774.2 2249.13  5824.5 2249.82  5981.4 2256.02
  6096.5 2259.03  6141.3 2261.44  6175.4 2262.13  6203.2 2264.14  6299.4 2267.88
#Mann=7,-1,0
  3948.8    0.07       0  4011.1   0.035       0  4763.4    0.07       0
  4884.6   0.035       0  4977.6   0.035       0  4981.8   0.035       0
  6141.3    0.07       0
Bank Sta=4977.6,4981.8
Exp/Cntr=0.3,0.1

Type RM Length L Ch R = 1,641,58,58,58
BEGIN DESCRIPTION:
Linn Creek Trib059 1.5
END DESCRIPTION:
XS GIS Cut Line= 5
      1318580.06      6900631.61      1317999.00      6899890.82
      1317773.39      6899852.97      1317643.10      6900036.84
      1316635.18      6900713.70
#Sta/Elev= 30
  3827.8 2251.06  3889.4 2249.85  4090.0 2245.06  4325.9 2237.77  4617.9 2233.83
  4717.4 2234.30  4771.5 2232.24  4783.5 2231.82  4824.0 2226.69  4882.7 2225.02
  4883.0 2224.52  4887.0 2225.02  4971.3 2225.32  5051.5 2225.41  5122.8 2227.23
  5164.6 2231.19  5209.0 2231.95  5215.1 2232.93  5221.1 2231.87  5272.8 2231.04
  5431.8 2231.98  5611.9 2237.08  5683.9 2241.04  5755.9 2242.73  5842.9 2246.68
  5848.9 2246.04  5929.9 2248.47  5965.9 2250.44  6223.1 2258.35  6437.5 2266.88
#Mann=7,-1,0
  3827.8    0.07       0  3889.4   0.035       0  4771.5    0.07       0
  4882.7   0.035       0  4887.0    0.07       0  4971.3   0.035       0
  6223.1    0.07       0
Bank Sta=4882.7,4887
Exp/Cntr=0.3,0.1

Type RM Length L Ch R = 1,583,526,526,526
BEGIN DESCRIPTION:
Linn Creek Trib059 1.0
END DESCRIPTION:
XS GIS Cut Line= 5
      1318594.57      6900630.13      1318033.72      6899741.52
      1317808.12      6899703.66      1317677.82      6899887.53
      1316671.00      6900563.66
#Sta/Elev= 30
  3585.4 2251.68  3655.0 2249.68  4131.6 2236.29  4517.2 2232.72  4591.4 2232.35
  4827.6 2236.25  4892.5 2234.55  4898.6 2231.26  4928.2 2235.35  4934.3 2231.25
  4942.9 2234.80  4949.1 2229.44  4963.8 2235.70  4970.0 2232.49  4978.6 2234.78
  4982.6 2228.84  4982.9 2228.34  4986.9 2228.84  4992.8 2235.45  5014.3 2235.07
  5020.4 2230.48  5029.1 2234.65  5035.2 2231.78  5064.7 2234.54  5070.9 2230.62
  5085.7 2234.72  5150.9 2230.63  5331.0 2230.89  6100.9 2253.88  6303.1 2260.96
#Mann=7,-1,0
  3585.4    0.07       0  3655.0   0.035       0  4517.2    0.07       0
  4591.4   0.035       0  4982.6   0.035       0  4986.9   0.035       0
  6100.9    0.07       0
Bank Sta=4982.6,4986.9
Exp/Cntr=0.3,0.1

Type RM Length L Ch R = 1,57,0,0,0
BEGIN DESCRIPTION:
Linn Creek Trib059 0.5
END DESCRIPTION:
XS GIS Cut Line= 5
      1318475.01      6900584.70      1318051.39      6899546.48
      1317936.80      6899470.09      1317742.36      6899563.84
      1316746.19      6900383.76
#Sta/Elev= 30
  3876.5 2249.15  4549.7 2231.91  4823.4 2232.24  4894.6 2227.90  4924.0 2223.18
  4931.4 2217.33  4942.2 2215.74  4953.5 2219.83  4972.1 2213.72  5010.8 2209.89
  5011.3 2209.39  5034.8 2209.89  5037.8 2215.37  5052.9 2220.10  5058.9 2216.59
  5079.9 2222.96  5346.2 2223.44  5387.4 2228.10  5409.6 2225.84  5523.0 2231.33
  5551.7 2227.43  5558.2 2231.08  5566.0 2224.06  5572.5 2231.18  5580.4 2226.69
  5586.8 2231.52  5601.2 2232.65  6048.1 2234.99  6499.9 2247.13  6641.6 2253.60
#Mann=4,-1,0
  3876.5   0.035       0  5010.8   0.035       0  5034.8   0.035       0
  6499.9    0.07       0
Bank Sta=5010.8,5034.8
Exp/Cntr=0.3,0.1

Chan Stop Cuts=-1