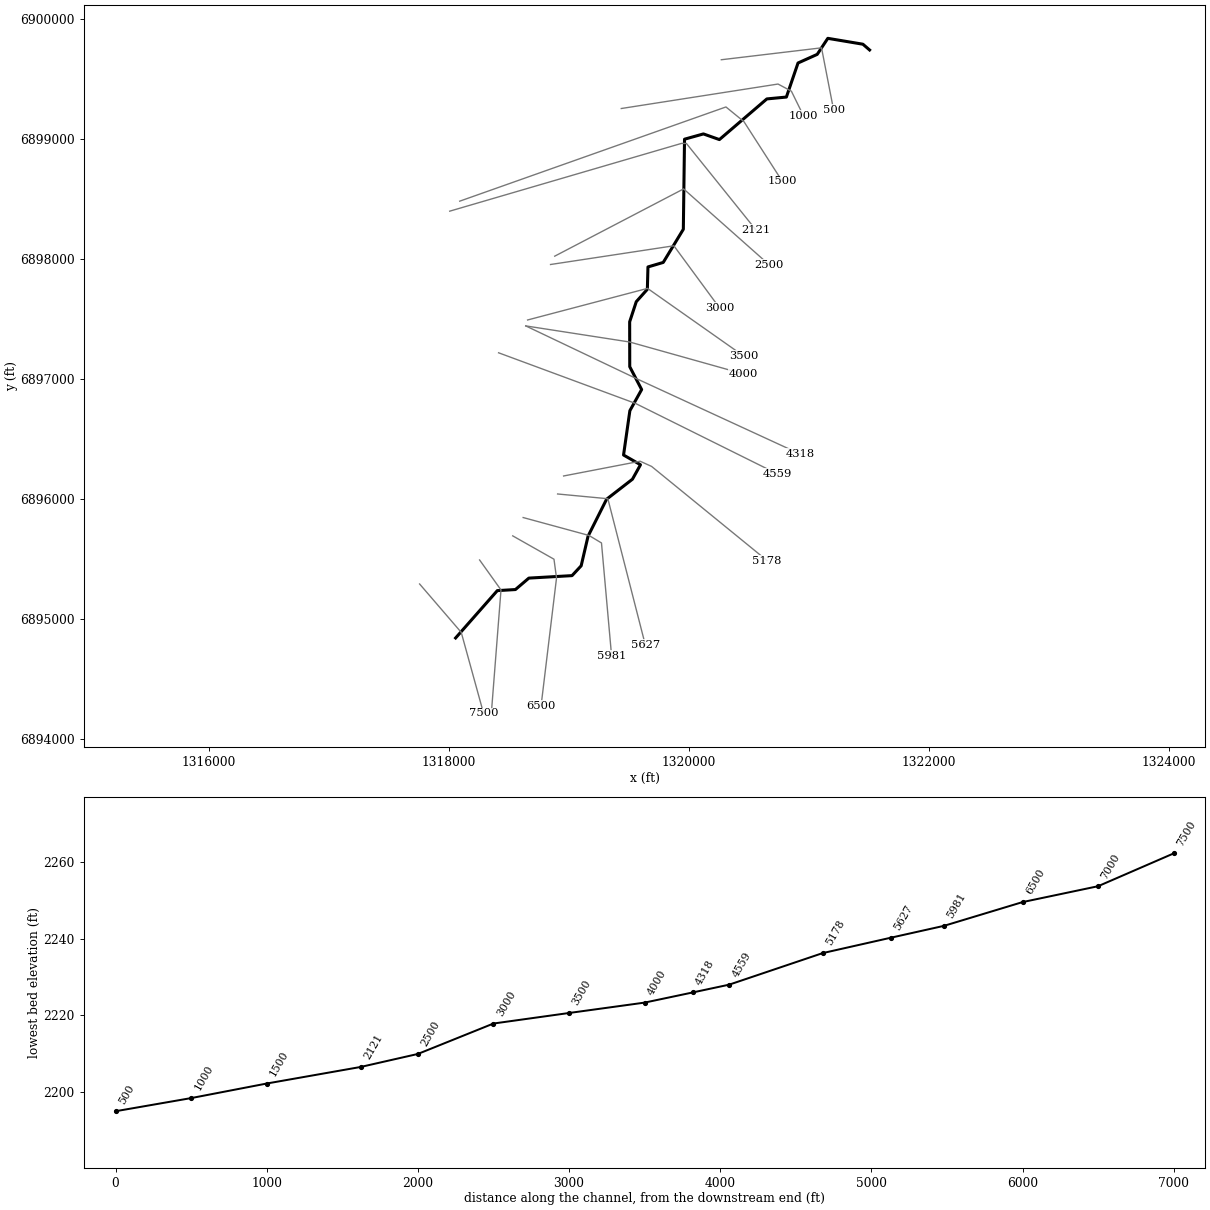
--- Linn Creek Trib061.prj (project) ---

Proj Title=Linn Creek Trib061 Base Level Engineering
Current Plan=p01
Default Exp/Contr=0.3,0.1
English Units
Geom File=g01
Flow File=f01
Plan File=p01
BEGIN DESCRIPTION:
Linn Creek Trib061
END DESCRIPTION:

--- Linn Creek Trib061.p01 (plan) ---

Plan Title=Multiple Run
Short Identifier=Multiple
Geom File=g01
Flow File=f01
Subcritical Flow
K Sum by GR= 0
Std Step Tol= 0.01
Critical Tol= 0.01
Num of Std Step Trials= 20
Max Error Tol= 0.3
Flow Tol Ratio= 0.001
Split Flow NTrial= 30
Split Flow Tol= 0.02
Split Flow Ratio= 0.02
Log Output Level= 0
Friction Slope Method= 1
Unsteady Friction Slope Method= 2
Unsteady Bridges Friction Slope Method= 1
Parabolic Critical Depth
Global Vel Dist=  1 , 1 , 1
Global Log Level= 0
CheckData=True
Encroach Param= -1, 0, 0, 0
BEGIN DESCRIPTION:
Multiple Run
END DESCRIPTION:

--- Linn Creek Trib061.f01 (steady flow) ---

Flow Title=Multiple
Number of Profiles=7
Profile Names=10-year,25-year,50-year,1pct_min,100-year,1pct_plu,500-year
River Rch & RM= Linn Creek Trib0,Reach-1,7500
     315     454     573     360     719    1434    1145
River Rch & RM= Linn Creek Trib0,Reach-1,4318
     384     558     708     447     891    1778    1432
Boundary for River Rch & Prof#=Linn Creek Trib0,Reach-1,1
Up Type=0
Dn Type=3
Dn Slope=0.005
Boundary for River Rch & Prof#=Linn Creek Trib0,Reach-1,2
Up Type=0
Dn Type=3
Dn Slope=0.005
Boundary for River Rch & Prof#=Linn Creek Trib0,Reach-1,3
Up Type=0
Dn Type=3
Dn Slope=0.005
Boundary for River Rch & Prof#=Linn Creek Trib0,Reach-1,4
Up Type=0
Dn Type=3
Dn Slope=0.005
Boundary for River Rch & Prof#=Linn Creek Trib0,Reach-1,5
Up Type=0
Dn Type=3
Dn Slope=0.005
Boundary for River Rch & Prof#=Linn Creek Trib0,Reach-1,6
Up Type=0
Dn Type=3
Dn Slope=0.005
Boundary for River Rch & Prof#=Linn Creek Trib0,Reach-1,7
Up Type=0
Dn Type=3
Dn Slope=0.005

--- Linn Creek Trib061.g01 (geometry) ---

Geom Title=Existing Conditions

River Reach=Linn Creek Trib0,Reach-1
Reach XY= 30
      1318055.00      6894838.00      1318402.55      6895232.53
      1318553.53      6895241.56      1318665.44      6895336.94
      1319025.21      6895357.59      1319101.39      6895439.48
      1319158.83      6895686.42      1319313.13      6895994.07
      1319528.74      6896161.12      1319595.83      6896281.62
      1319454.57      6896362.62      1319507.24      6896732.07
      1319605.30      6896908.18      1319506.20      6897098.50
      1319505.52      6897472.78      1319560.54      6897640.42
      1319652.93      6897743.86      1319657.94      6897930.03
      1319785.35      6897967.59      1319952.76      6898243.93
      1319962.67      6898994.52      1320120.16      6899038.47
      1320253.28      6898991.34      1320648.81      6899330.18
      1320811.52      6899345.68      1320908.50      6899629.54
      1321068.56      6899701.48      1321156.76      6899835.06
      1321449.22      6899786.11      1321505.00      6899738.00

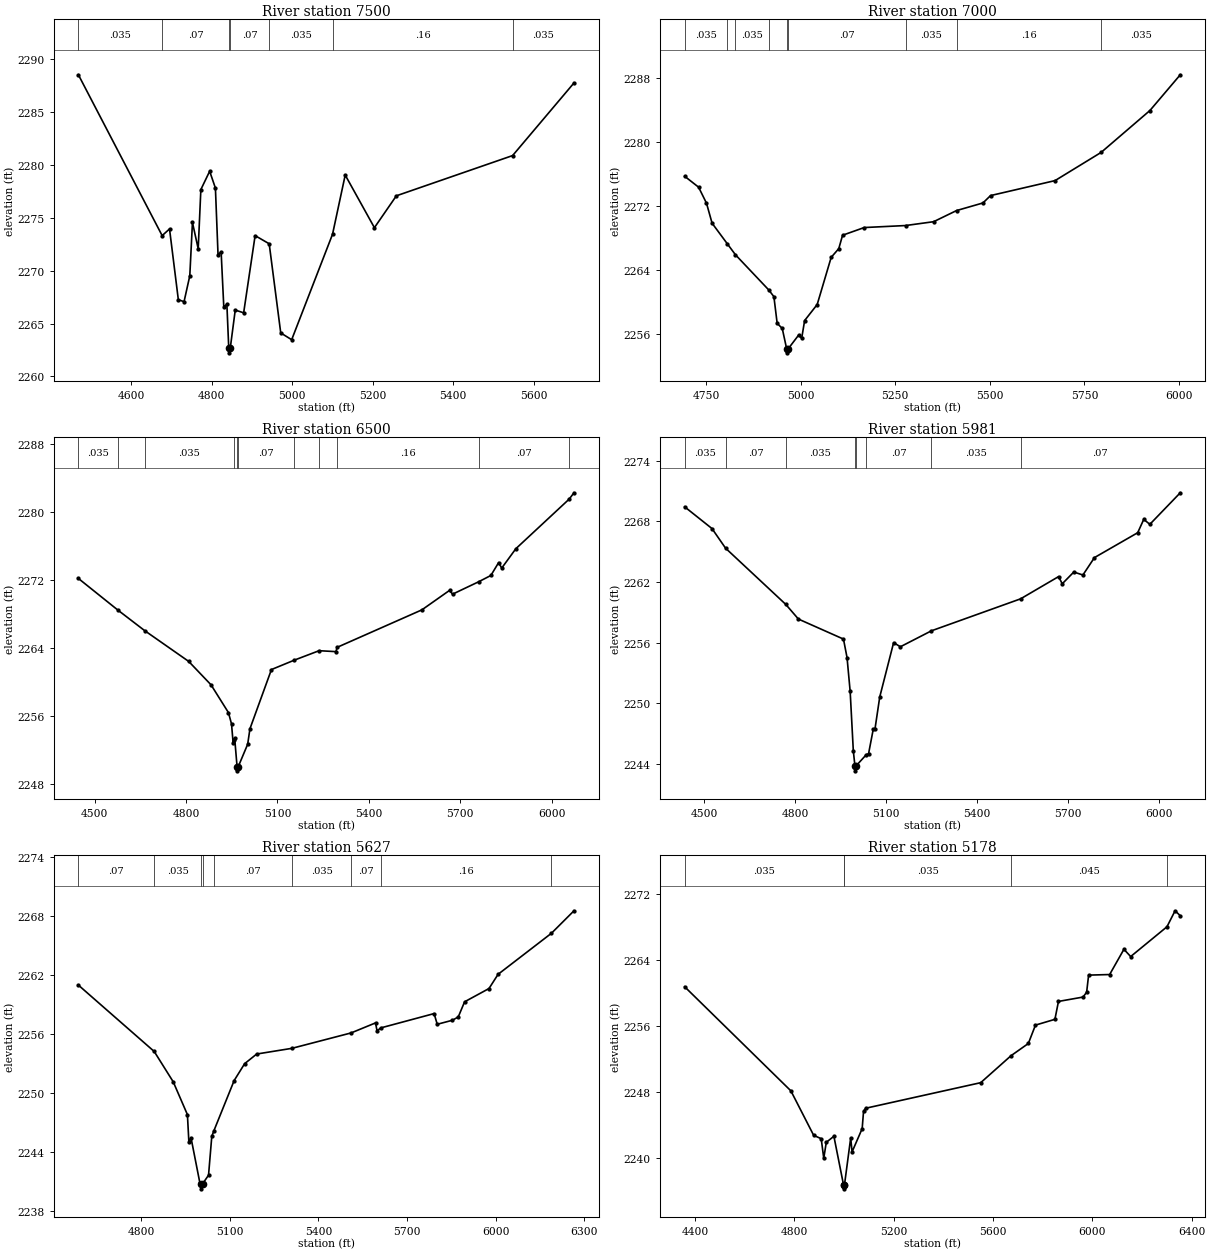
Type RM Length L Ch R = 1,7500,500,500,500
BEGIN DESCRIPTION:
Linn Creek Trib061 15.0
END DESCRIPTION:
XS GIS Cut Line= 3
      1317755.02      6895287.98      1318101.92      6894884.90
      1318288.03      6894209.68
#Sta/Elev= 30
  4468.2 2288.49  4676.5 2273.30  4694.8 2273.93  4716.7 2267.25  4730.9 2267.06
  4745.2 2269.51  4751.8 2274.54  4766.1 2272.06  4772.7 2277.65  4794.6 2279.38
  4808.9 2277.79  4815.4 2271.50  4823.1 2271.77  4829.7 2266.58  4837.4 2266.81
  4842.0 2262.73  4842.2 2262.23  4846.0 2262.73  4858.2 2266.27  4879.1 2266.01
  4907.6 2273.30  4942.6 2272.53  4971.3 2264.11  4998.5 2263.47  5100.1 2273.43
  5131.6 2279.02  5204.2 2274.05  5258.8 2277.06  5547.8 2280.86  5700.4 2287.72
#Mann=7,-1,0
  4468.2   0.035       0  4676.5    0.07       0  4842.0   0.035       0
  4846.0    0.07       0  4942.6   0.035       0  5100.1    0.16       0
  5547.8   0.035       0
Bank Sta=4842,4846
Exp/Cntr=0.3,0.1

Type RM Length L Ch R = 1,7000,500,500,500
BEGIN DESCRIPTION:
Linn Creek Trib061 14.0
END DESCRIPTION:
XS GIS Cut Line= 3
      1318255.03      6895487.96      1318433.25      6895238.36
      1318355.00      6894238.01
#Sta/Elev= 30
  4693.3 2275.71  4730.1 2274.35  4751.0 2272.35  4765.8 2269.85  4805.6 2267.31
  4827.6 2265.91  4915.8 2261.51  4929.2 2260.68  4937.8 2257.36  4951.3 2256.71
  4962.9 2254.17  4963.1 2253.67  4966.9 2254.17  4994.3 2255.87  5002.7 2255.50
  5010.4 2257.70  5043.6 2259.70  5080.6 2265.59  5100.7 2266.68  5110.7 2268.35
  5167.9 2269.31  5277.2 2269.56  5351.4 2270.04  5412.0 2271.43  5481.8 2272.38
  5501.9 2273.30  5672.4 2275.17  5794.2 2278.69  5923.2 2283.92  6003.4 2288.38
#Mann=9,-1,0
  4693.3   0.035       0  4805.6    0.07       0  4827.6   0.035       0
  4915.8    0.07       0  4962.9    0.07       0  4966.9    0.07       0
  5277.2   0.035       0  5412.0    0.16       0  5794.2   0.035       0
Bank Sta=4962.9,4966.9
Exp/Cntr=0.3,0.1

Type RM Length L Ch R = 1,6500,519,519,519
BEGIN DESCRIPTION:
Linn Creek Trib061 13.0
END DESCRIPTION:
XS GIS Cut Line= 4
      1318531.04      6895688.90      1318874.83      6895494.43
      1318896.00      6895337.93      1318767.23      6894272.58
#Sta/Elev= 30
  4447.1 2272.18  4577.5 2268.43  4664.7 2266.03  4809.0 2262.41  4882.3 2259.65
  4939.4 2256.38  4949.5 2255.05  4954.9 2252.77  4958.4 2253.17  4959.9 2253.34
  4967.7 2250.02  4967.9 2249.52  4971.7 2250.02  5002.5 2252.65  5010.0 2254.48
  5080.5 2261.45  5155.7 2262.56  5236.9 2263.67  5292.0 2263.56  5296.3 2264.07
  5574.1 2268.48  5664.7 2270.77  5674.8 2270.33  5760.4 2271.79  5800.4 2272.53
  5825.9 2274.05  5836.0 2273.40  5882.3 2275.68  6057.2 2281.52  6073.1 2282.27
#Mann=11,-1,0
  4447.1   0.035       0  4577.5    0.07       0  4664.7   0.035       0
  4958.4    0.07       0  4967.7    0.07       0  4971.7    0.07       0
  5155.7   0.035       0  5236.9    0.07       0  5296.3    0.16       0
  5760.4    0.07       0  6057.2   0.035       0
Bank Sta=4967.7,4971.7
Exp/Cntr=0.3,0.1

Type RM Length L Ch R = 1,5981,354,354,354
BEGIN DESCRIPTION:
Linn Creek Trib061 12.0
END DESCRIPTION:
XS GIS Cut Line= 4
      1318617.93      6895841.64      1319166.49      6895692.35
      1319270.66      6895629.85      1319355.00      6894688.01
#Sta/Elev= 30
  4435.4 2269.44  4525.6 2267.29  4570.4 2265.35  4769.1 2259.79  4810.8 2258.34
  4959.5 2256.36  4971.3 2254.53  4981.6 2251.18  4992.0 2245.30  4997.3 2243.83
  4997.6 2243.33  5001.3 2243.83  5034.9 2244.93  5042.3 2245.02  5057.8 2247.45
  5063.6 2247.49  5079.2 2250.64  5125.0 2256.01  5147.3 2255.60  5249.9 2257.18
  5544.0 2260.34  5669.4 2262.54  5681.5 2261.83  5719.6 2262.99  5749.7 2262.70
  5787.8 2264.42  5930.5 2266.88  5950.5 2268.20  5970.6 2267.71  6071.0 2270.83
#Mann=8,-1,0
  4435.4   0.035       0  4570.4    0.07       0  4769.1   0.035       0
  4997.3   0.035       0  5001.3   0.035       0  5034.9    0.07       0
  5249.9   0.035       0  5544.0    0.07       0
Bank Sta=4997.3,5001.3
Exp/Cntr=0.3,0.1

Type RM Length L Ch R = 1,5627,449,449,449
BEGIN DESCRIPTION:
Linn Creek Trib061 11.0
END DESCRIPTION:
XS GIS Cut Line= 3
      1318905.02      6896038.00      1319323.78      6895998.46
      1319636.27      6894778.88
#Sta/Elev= 30
  4586.3 2260.96  4843.3 2254.20  4907.7 2251.11  4955.8 2247.77  4960.8 2244.96
  4968.0 2245.41  4998.1 2240.80  5003.0 2240.71  5003.3 2240.21  5007.0 2240.71
  5027.4 2241.60  5038.4 2245.55  5044.8 2246.07  5114.2 2251.24  5149.8 2252.96
  5190.6 2253.94  5309.9 2254.52  5510.6 2256.09  5593.3 2257.11  5598.5 2256.30
  5611.0 2256.60  5791.9 2258.06  5802.4 2256.97  5853.9 2257.38  5873.7 2257.72
  5895.2 2259.26  5977.8 2260.61  6008.7 2262.06  6189.5 2266.24  6265.9 2268.53
#Mann=9,-1,0
  4586.3    0.07       0  4843.3   0.035       0  5003.0   0.035       0
  5007.0   0.035       0  5044.8    0.07       0  5309.9   0.035       0
  5510.6    0.07       0  5611.0    0.16       0  6189.5    0.07       0
Bank Sta=5003,5007
Exp/Cntr=0.3,0.1

Type RM Length L Ch R = 1,5178,619,619,619
BEGIN DESCRIPTION:
Linn Creek Trib061 10.0
END DESCRIPTION:
XS GIS Cut Line= 4
      1318955.01      6896188.00      1319592.88      6896310.96
      1319688.36      6896267.56      1320650.35      6895483.24
#Sta/Elev= 30
  4358.4 2260.71  4786.1 2248.09  4877.8 2242.70  4908.2 2242.29  4918.5 2239.92
  4928.7 2241.85  4959.3 2242.58  4998.0 2236.71  4998.2 2236.21  5002.0 2236.71
  5027.0 2242.39  5032.5 2240.69  5073.2 2243.51  5078.7 2245.60  5087.2 2245.98
  5550.5 2249.08  5672.6 2252.35  5742.3 2253.83  5771.0 2256.06  5849.3 2256.76
  5863.6 2258.93  5962.7 2259.46  5977.1 2260.05  5985.0 2262.12  6069.7 2262.19
  6127.2 2265.25  6154.4 2264.37  6300.5 2267.98  6333.2 2269.92  6354.1 2269.32
#Mann=5,-1,0
  4358.4   0.035       0  4998.0    0.07       0  5002.0   0.035       0
  5672.6   0.045       0  6300.5    0.07       0
Bank Sta=4998,5002
Exp/Cntr=0.3,0.1

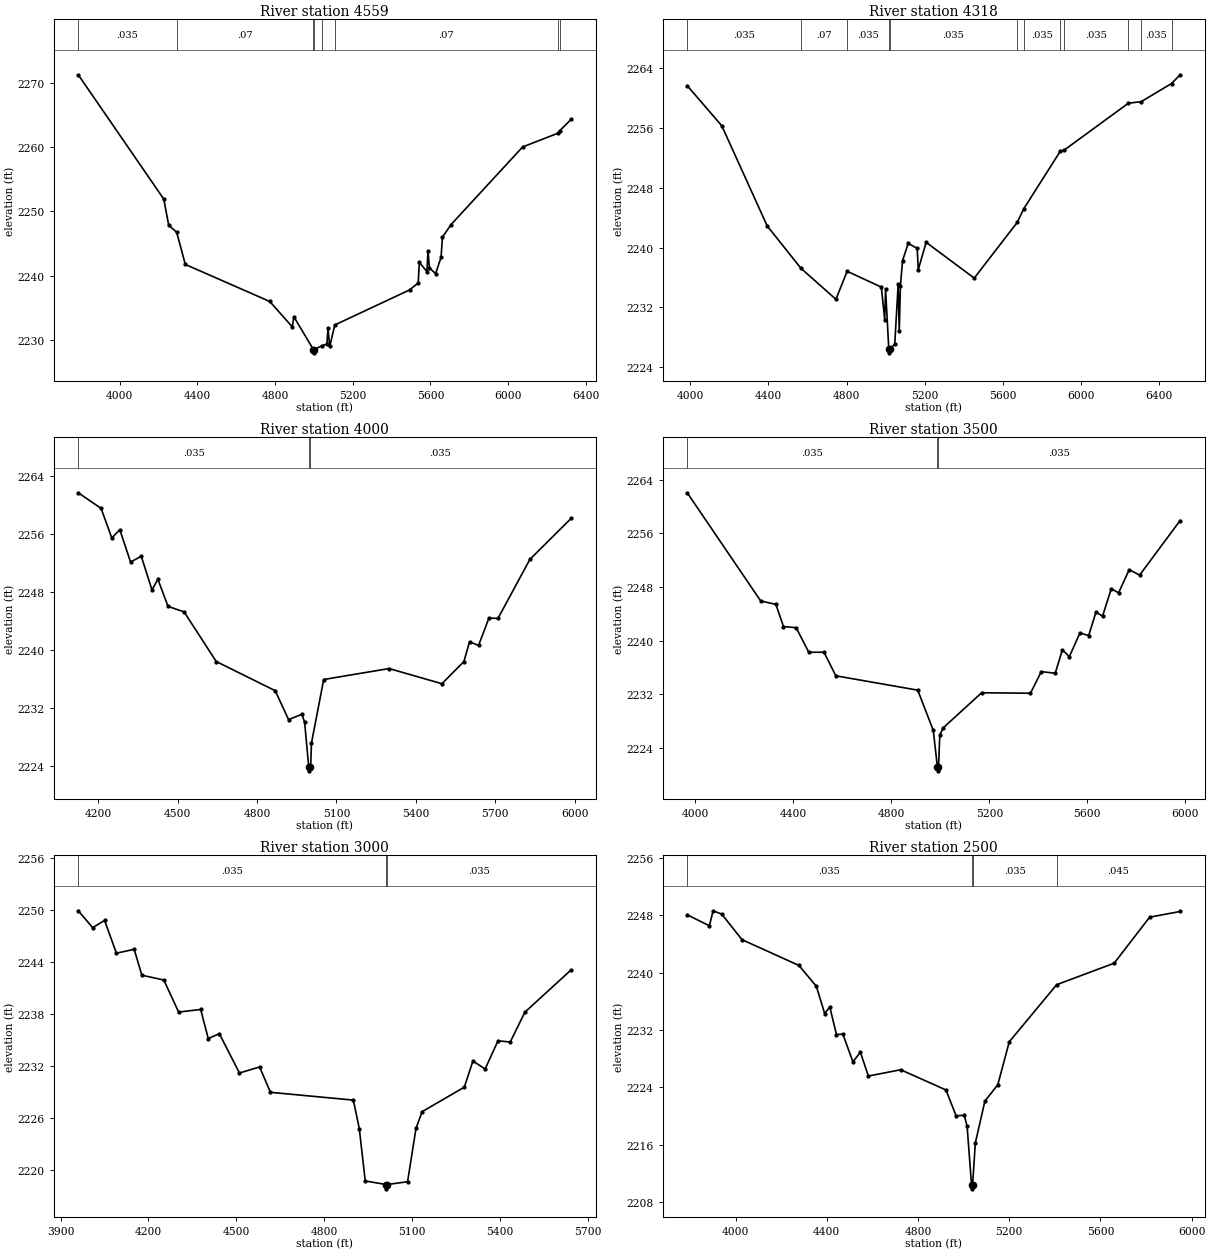
Type RM Length L Ch R = 1,4559,241,241,241
BEGIN DESCRIPTION:
Linn Creek Trib061 9.0
END DESCRIPTION:
XS GIS Cut Line= 3
      1318413.16      6897214.62      1319553.81      6896792.74
      1320738.72      6896204.19
#Sta/Elev= 30
  3785.7 2271.26  4226.5 2251.90  4251.5 2247.87  4292.8 2246.73  4337.4 2241.73
  4772.2 2235.97  4888.5 2232.02  4896.5 2233.59  4997.5 2228.47  4997.7 2227.97
  5001.5 2228.47  5041.6 2229.09  5066.7 2229.34  5072.2 2231.77  5081.4 2228.96
  5107.4 2232.31  5492.4 2237.76  5537.2 2238.85  5542.8 2242.06  5582.0 2240.63
  5587.6 2243.82  5595.0 2241.18  5626.8 2240.31  5654.8 2242.83  5662.0 2245.98
  5706.6 2247.95  6074.9 2260.02  6256.1 2262.15  6266.1 2262.55  6324.9 2264.32
#Mann=8,-1,0
  3785.7   0.035       0  4292.8    0.07       0  4997.5    0.07       0
  5001.5    0.07       0  5041.6   0.035       0  5107.4    0.07       0
  6256.1   0.035       0  6266.1   0.045       0
Bank Sta=4997.5,5001.5
Exp/Cntr=0.3,0.1

Type RM Length L Ch R = 1,4318,318,318,318
BEGIN DESCRIPTION:
Linn Creek Trib061 8.5
END DESCRIPTION:
XS GIS Cut Line= 3
      1318639.71      6897438.59      1319557.81      6897001.31
      1320925.18      6896371.17
#Sta/Elev= 30
  3984.9 2261.62  4161.6 2256.27  4394.1 2242.89  4566.5 2237.24  4745.8 2233.09
  4803.2 2236.83  4978.4 2234.72  4995.5 2230.33  4999.9 2234.43  5016.4 2226.44
  5016.7 2225.94  5020.6 2226.44  5046.9 2227.10  5064.4 2235.07  5069.9 2228.81
  5075.8 2234.85  5086.8 2238.24  5115.8 2240.56  5161.7 2239.89  5167.2 2237.05
  5207.6 2240.70  5453.7 2235.92  5673.7 2243.36  5706.8 2245.17  5894.7 2252.89
  5913.1 2253.00  6242.4 2259.28  6308.3 2259.49  6463.4 2261.91  6507.4 2263.08
#Mann=12,-1,0
  3984.9   0.035       0  4566.5    0.07       0  4803.2   0.035       0
  5016.4   0.035       0  5020.6   0.035       0  5673.7    0.07       0
  5706.8   0.035       0  5894.7    0.07       0  5913.1   0.035       0
  6242.4    0.07       0  6308.3   0.035       0  6463.4    0.07       0
Bank Sta=5016.4,5020.6
Exp/Cntr=0.3,0.1

Type RM Length L Ch R = 1,4000,500,500,500
BEGIN DESCRIPTION:
Linn Creek Trib061 8.0
END DESCRIPTION:
XS GIS Cut Line= 3
      1318639.70      6897438.58      1319504.99      6897304.55
      1320455.00      6897038.00
#Sta/Elev= 30
  4124.4 2261.62  4210.7 2259.47  4251.2 2255.39  4281.5 2256.53  4322.0 2252.07
  4362.5 2252.88  4403.0 2248.22  4425.2 2249.71  4463.7 2245.96  4524.4 2245.20
  4645.8 2238.36  4868.5 2234.34  4919.1 2230.35  4969.7 2231.09  4979.8 2229.97
  4995.4 2223.79  4995.7 2223.29  4999.6 2223.79  5002.6 2223.79  5005.5 2227.10
  5051.9 2235.88  5298.9 2237.39  5498.6 2235.30  5581.6 2238.36  5602.8 2241.07
  5636.9 2240.58  5676.2 2244.35  5710.3 2244.30  5830.9 2252.44  5986.7 2258.09
#Mann=3,-1,0
  4124.4   0.035       0  4995.4   0.035       0  4999.6   0.035       0
Bank Sta=4995.4,4999.6
Exp/Cntr=0.3,0.1

Type RM Length L Ch R = 1,3500,500,500,500
BEGIN DESCRIPTION:
Linn Creek Trib061 7.0
END DESCRIPTION:
XS GIS Cut Line= 3
      1318654.97      6897487.99      1319654.35      6897751.35
      1320455.02      6897187.99
#Sta/Elev= 30
  3966.5 2262.07  4266.4 2245.93  4328.5 2245.42  4359.5 2242.11  4411.2 2241.94
  4462.9 2238.27  4525.0 2238.28  4573.1 2234.76  4907.6 2232.62  4971.0 2226.63
  4988.2 2221.08  4988.5 2220.58  4992.4 2221.08  4997.7 2225.90  5010.7 2226.96
  5168.4 2232.23  5367.9 2232.16  5412.3 2235.39  5468.9 2235.14  5498.5 2238.65
  5526.6 2237.61  5570.0 2241.15  5605.7 2240.77  5635.3 2244.25  5662.3 2243.67
  5698.1 2247.77  5727.7 2247.13  5771.1 2250.59  5813.9 2249.79  5979.0 2257.93
#Mann=3,-1,0
  3966.5   0.035       0  4988.2   0.035       0  4992.4   0.035       0
Bank Sta=4988.2,4992.4
Exp/Cntr=0.3,0.1

Type RM Length L Ch R = 1,3000,500,500,500
BEGIN DESCRIPTION:
Linn Creek Trib061 6.0
END DESCRIPTION:
XS GIS Cut Line= 3
      1318846.14      6897950.30      1319873.96      6898106.38
      1320255.02      6897587.97
#Sta/Elev= 30
  3960.4 2249.95  4009.8 2248.00  4050.3 2248.84  4090.7 2245.05  4151.4 2245.50
  4177.5 2242.51  4252.6 2241.95  4303.1 2238.25  4378.5 2238.55  4404.3 2235.19
  4442.2 2235.75  4510.9 2231.21  4579.6 2231.91  4616.7 2228.98  4899.9 2228.08
  4920.1 2224.78  4940.4 2218.74  5011.3 2218.33  5011.6 2217.83  5015.6 2218.33
  5084.9 2218.65  5113.7 2224.81  5134.6 2226.74  5278.8 2229.58  5308.1 2232.60
  5349.8 2231.67  5393.7 2234.93  5435.4 2234.79  5485.6 2238.24  5643.4 2243.12
#Mann=3,-1,0
  3960.4   0.035       0  5011.3   0.035       0  5015.6   0.035       0
Bank Sta=5011.3,5015.6
Exp/Cntr=0.3,0.1

Type RM Length L Ch R = 1,2500,379,379,379
BEGIN DESCRIPTION:
Linn Creek Trib061 5.0
END DESCRIPTION:
XS GIS Cut Line= 3
      1318880.80      6898019.73      1319955.01      6898580.35
      1320665.51      6897950.32
#Sta/Elev= 30
  3788.3 2248.04  3885.4 2246.51  3901.8 2248.60  3939.7 2248.13  4028.7 2244.57
  4278.1 2240.99  4354.4 2238.09  4390.9 2234.29  4413.4 2235.20  4442.7 2231.36
  4470.4 2231.44  4514.9 2227.57  4547.5 2228.91  4582.6 2225.59  4724.2 2226.47
  4923.0 2223.65  4967.1 2220.06  5003.3 2220.12  5015.6 2218.58  5035.1 2210.39
  5035.4 2209.89  5039.5 2210.39  5051.5 2216.26  5093.5 2222.10  5150.2 2224.39
  5200.4 2230.36  5408.2 2238.31  5660.4 2241.30  5815.9 2247.71  5949.6 2248.50
#Mann=4,-1,0
  3788.3   0.035       0  5035.1   0.035       0  5039.5   0.035       0
  5408.2   0.045       0
Bank Sta=5035.1,5039.5
Exp/Cntr=0.3,0.1

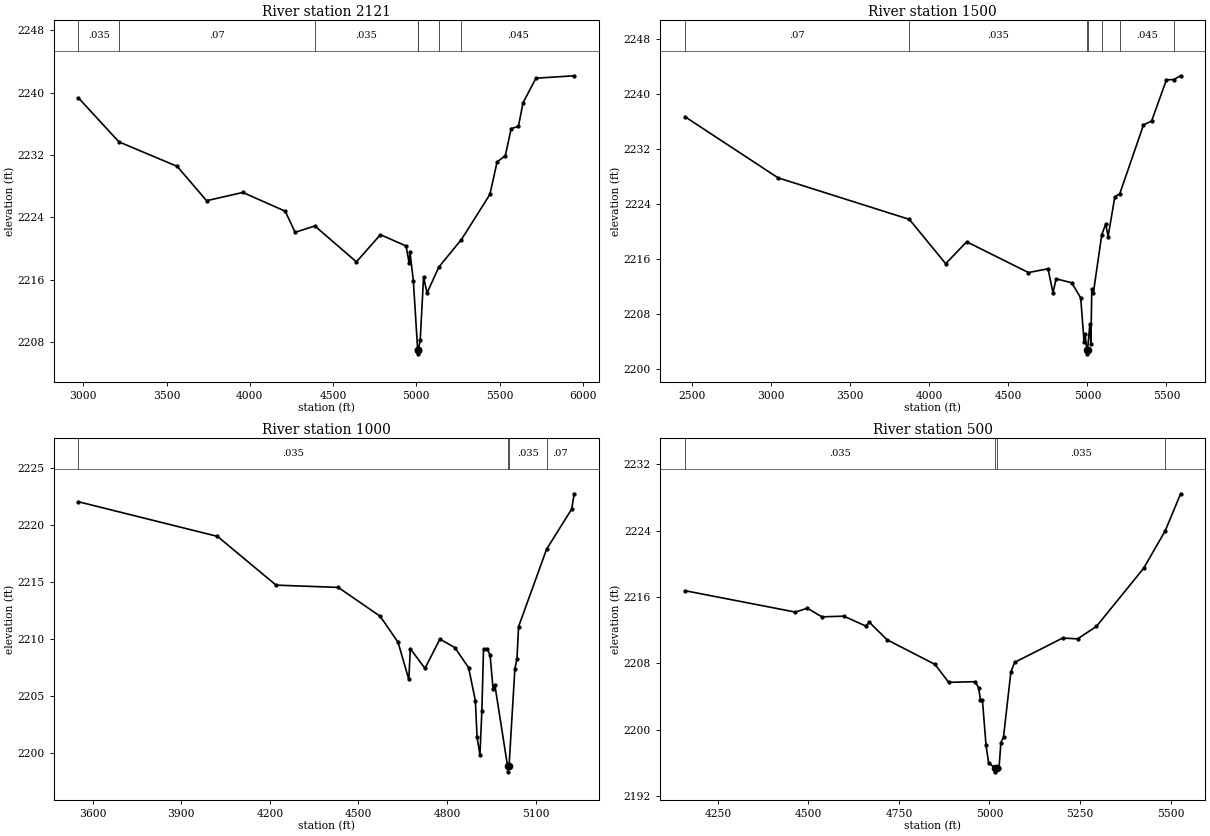
Type RM Length L Ch R = 1,2121,621,621,621
BEGIN DESCRIPTION:
Linn Creek Trib061 4.0
END DESCRIPTION:
XS GIS Cut Line= 4
      1318005.83      6898394.74      1319936.81      6898959.41
      1319978.04      6898959.41      1320557.50      6898238.88
#Sta/Elev= 30
  2970.4 2239.34  3213.7 2233.69  3563.4 2230.55  3740.5 2226.14  3958.0 2227.20
  4212.9 2224.79  4271.9 2222.08  4390.5 2222.90  4640.3 2218.29  4784.4 2221.78
  4938.7 2220.33  4956.9 2218.11  4962.1 2219.53  4982.2 2215.87  5008.2 2206.99
  5008.5 2206.49  5012.6 2206.99  5023.5 2208.24  5043.5 2216.34  5064.4 2214.30
  5135.5 2217.63  5271.0 2221.16  5441.9 2226.94  5485.1 2231.11  5534.7 2231.92
  5569.9 2235.40  5613.1 2235.67  5641.2 2238.71  5718.7 2241.86  5948.1 2242.17
#Mann=7,-1,0
  2970.4   0.035       0  3213.7    0.07       0  4390.5   0.035       0
  5008.2   0.035       0  5012.6   0.035       0  5135.5    0.07       0
  5271.0   0.045       0
Bank Sta=5008.2,5012.6
Exp/Cntr=0.3,0.1

Type RM Length L Ch R = 1,1500,500,500,500
BEGIN DESCRIPTION:
Linn Creek Trib061 3.0
END DESCRIPTION:
XS GIS Cut Line= 4
      1318089.20      6898478.08      1320307.91      6899263.23
      1320457.86      6899140.82      1320776.66      6898644.73
#Sta/Elev= 30
  2452.9 2236.69  3042.5 2227.79  3873.5 2221.74  4103.2 2215.29  4236.0 2218.48
  4627.1 2214.00  4750.7 2214.55  4782.1 2211.06  4801.9 2213.09  4900.6 2212.51
  4957.6 2210.31  4978.8 2203.86  4985.3 2205.08  4996.1 2202.67  4996.4 2202.17
  5000.5 2202.67  5015.2 2206.46  5021.8 2203.62  5027.8 2211.62  5037.0 2210.96
  5090.8 2219.52  5115.6 2221.05  5130.8 2219.23  5173.1 2225.00  5205.1 2225.50
  5354.7 2235.48  5406.2 2236.06  5500.0 2242.06  5545.1 2242.08  5589.7 2242.64
#Mann=7,-1,0
  2452.9    0.07       0  3873.5   0.035       0  4996.1   0.035       0
  5000.5   0.035       0  5090.8    0.07       0  5205.1   0.045       0
  5545.1    0.07       0
Bank Sta=4996.1,5000.5
Exp/Cntr=0.3,0.1

Type RM Length L Ch R = 1,1000,500,500,500
BEGIN DESCRIPTION:
Linn Creek Trib061 2.0
END DESCRIPTION:
XS GIS Cut Line= 4
      1319435.53      6899250.21      1320741.93      6899454.20
      1320853.21      6899394.53      1320955.02      6899187.96
#Sta/Elev= 30
  3551.5 2222.08  4022.5 2219.04  4220.9 2214.76  4431.5 2214.56  4573.2 2212.03
  4633.9 2209.75  4670.4 2206.48  4675.5 2209.18  4725.0 2207.45  4775.6 2210.02
  4826.2 2209.28  4872.8 2207.52  4895.8 2204.61  4901.5 2201.41  4911.3 2199.86
  4917.8 2203.75  4923.4 2209.15  4934.0 2209.18  4945.4 2208.66  4955.9 2205.61
  4961.6 2206.02  5004.8 2198.87  5005.2 2198.37  5009.8 2198.87  5029.6 2207.43
  5036.6 2208.29  5042.1 2211.12  5137.0 2217.92  5221.8 2221.43  5230.3 2222.78
#Mann=4,-1,0
  3551.5   0.035       0  5004.8   0.035       0  5009.8   0.035       0
  5137.0    0.07       0
Bank Sta=5004.8,5009.8
Exp/Cntr=0.3,0.1

Type RM Length L Ch R = 1,500,0,0,0
BEGIN DESCRIPTION:
Linn Creek Trib061 1.0
END DESCRIPTION:
XS GIS Cut Line= 3
      1320269.28      6899656.67      1321104.40      6899755.99
      1321205.01      6899237.97
#Sta/Elev= 30
  4159.0 2216.76  4464.2 2214.18  4497.1 2214.65  4537.4 2213.61  4597.8 2213.69
  4658.2 2212.51  4668.3 2212.96  4717.1 2210.85  4849.6 2207.88  4887.4 2205.72
  4960.3 2205.80  4970.0 2205.07  4975.1 2203.60  4980.5 2203.58  4990.5 2198.14
  4997.8 2195.96  5015.8 2195.44  5016.2 2194.94  5020.8 2195.44  5026.4 2195.44
  5031.5 2198.46  5038.7 2199.13  5059.1 2206.97  5069.3 2208.12  5201.7 2211.05
  5243.4 2210.96  5295.1 2212.45  5425.8 2219.47  5485.4 2223.99  5527.7 2228.43
#Mann=4,-1,0
  4159.0   0.035       0  5015.8   0.035       0  5020.8   0.035       0
  5485.4    0.07       0
Bank Sta=5015.8,5020.8
Exp/Cntr=0.3,0.1

Chan Stop Cuts=-1