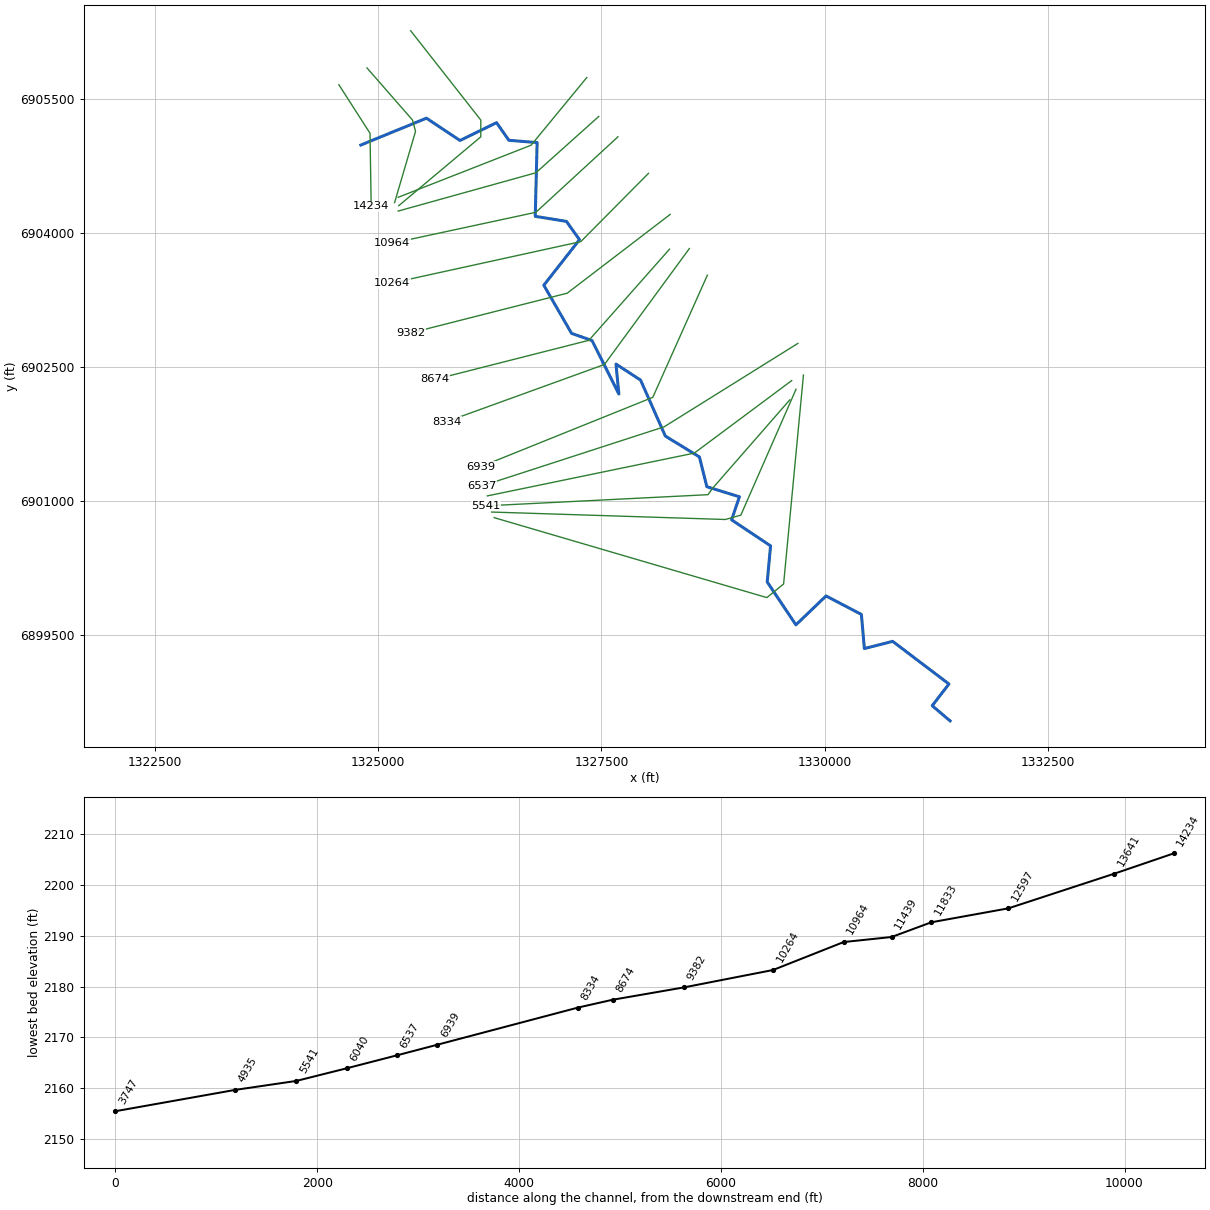
--- Linn Creek Trib063.prj (project) ---

Proj Title=Linn Creek Trib063 Base Level Engineering
Current Plan=p01
Default Exp/Contr=0.3,0.1
English Units
Geom File=g01
Flow File=f01
Plan File=p01
BEGIN DESCRIPTION:
Linn Creek Trib063
END DESCRIPTION:

--- Linn Creek Trib063.p01 (plan) ---

Plan Title=Multiple Run
Short Identifier=Multiple
Geom File=g01
Flow File=f01
Subcritical Flow
K Sum by GR= 0
Std Step Tol= 0.01
Critical Tol= 0.01
Num of Std Step Trials= 20
Max Error Tol= 0.3
Flow Tol Ratio= 0.001
Split Flow NTrial= 30
Split Flow Tol= 0.02
Split Flow Ratio= 0.02
Log Output Level= 0
Friction Slope Method= 1
Unsteady Friction Slope Method= 2
Unsteady Bridges Friction Slope Method= 1
Parabolic Critical Depth
Global Vel Dist=  1 , 1 , 1
Global Log Level= 0
CheckData=True
Encroach Param= -1, 0, 0, 0
BEGIN DESCRIPTION:
Multiple Run
END DESCRIPTION:

--- Linn Creek Trib063.f01 (steady flow) ---

Flow Title=Multiple
Number of Profiles=7
Profile Names=10-year,25-year,50-year,1pct_min,100-year,1pct_plu,500-year
River Rch & RM= Linn Creek Trib0,Reach-1,14234
     316     455     575     362     722    1440    1150
River Rch & RM= Linn Creek Trib0,Reach-1,11833
     456     668     851     539    1075    2145    1739
River Rch & RM= Linn Creek Trib0,Reach-1,3747
     553     815    1044     664    1324    2642    2160
Boundary for River Rch & Prof#=Linn Creek Trib0,Reach-1,1
Up Type=0
Dn Type=3
Dn Slope=0.005
Boundary for River Rch & Prof#=Linn Creek Trib0,Reach-1,2
Up Type=0
Dn Type=3
Dn Slope=0.005
Boundary for River Rch & Prof#=Linn Creek Trib0,Reach-1,3
Up Type=0
Dn Type=3
Dn Slope=0.005
Boundary for River Rch & Prof#=Linn Creek Trib0,Reach-1,4
Up Type=0
Dn Type=3
Dn Slope=0.005
Boundary for River Rch & Prof#=Linn Creek Trib0,Reach-1,5
Up Type=0
Dn Type=3
Dn Slope=0.005
Boundary for River Rch & Prof#=Linn Creek Trib0,Reach-1,6
Up Type=0
Dn Type=3
Dn Slope=0.005
Boundary for River Rch & Prof#=Linn Creek Trib0,Reach-1,7
Up Type=0
Dn Type=3
Dn Slope=0.005

--- Linn Creek Trib063.g01 (geometry) ---

Geom Title=Existing Conditions

River Reach=Linn Creek Trib0,Reach-1
Reach XY= 30
      1324805.00      6904988.00      1325539.82      6905288.44
      1325915.71      6905038.72      1326325.18      6905238.44
      1326462.97      6905040.93      1326779.48      6905015.16
      1326758.43      6904189.22      1327107.70      6904132.64
      1327254.06      6903927.52      1326854.58      6903417.57
      1327165.61      6902877.94      1327394.39      6902798.06
      1327695.12      6902198.88      1327662.56      6902535.03
      1327938.36      6902354.68      1328215.51      6901728.19
      1328596.98      6901494.34      1328680.97      6901160.65
      1329044.97      6901048.06      1328958.14      6900789.64
      1329394.02      6900498.37      1329356.91      6900093.72
      1329677.88      6899613.47      1330015.69      6899937.47
      1330411.50      6899730.28      1330444.93      6899348.03
      1330761.76      6899428.88      1331391.90      6898951.20
      1331204.52      6898708.16      1331405.00      6898538.00

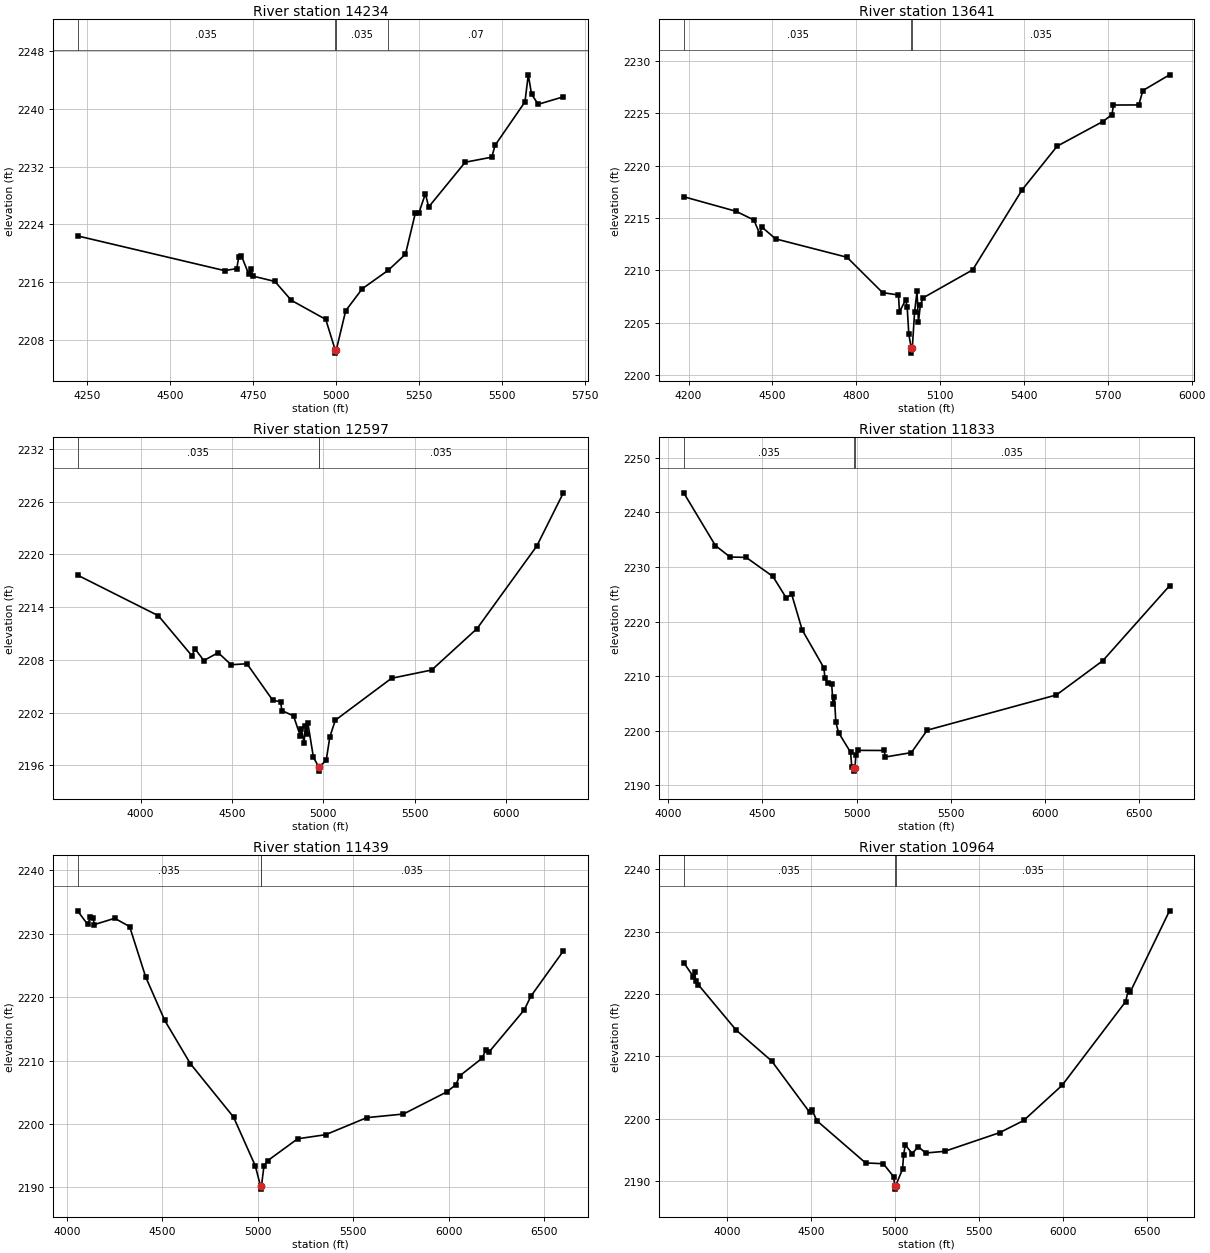
Type RM Length L Ch R = 1,14234,593,593,593
BEGIN DESCRIPTION:
Linn Creek Trib063 16.0
END DESCRIPTION:
XS GIS Cut Line= 3
      1324558.87      6905663.39      1324907.69      6905120.04
      1324921.09      6904302.33
#Sta/Elev= 30
  4221.7 2222.40  4664.9 2217.58  4701.3 2217.87  4707.2 2219.46  4715.3 2219.63
  4737.6 2217.07  4743.6 2217.77  4751.0 2216.81  4816.2 2216.08  4865.6 2213.46
  4969.4 2210.81  4997.4 2206.63  4997.7 2206.13  5001.4 2206.63  5029.4 2212.01
  5079.4 2215.07  5158.1 2217.65  5209.5 2219.86  5239.5 2225.61  5249.5 2225.54
  5269.5 2228.25  5279.5 2226.42  5389.5 2232.63  5469.5 2233.33  5479.5 2234.98
  5569.5 2241.00  5579.5 2244.76  5589.5 2242.05  5609.5 2240.67  5685.2 2241.71
#Mann=4,-1,0
  4221.7   0.035       0  4997.4   0.035       0  5001.4   0.035       0
  5158.1    0.07       0
Bank Sta=4997.4,5001.4
Exp/Cntr=0.3,0.1

Type RM Length L Ch R = 1,13641,1044,1044,1044
BEGIN DESCRIPTION:
Linn Creek Trib063 15.0
END DESCRIPTION:
XS GIS Cut Line= 4
      1324874.12      6905851.21      1325383.93      6905267.61
      1325417.47      6905140.16      1325182.85      6904342.46
#Sta/Elev= 30
  4182.5 2217.03  4369.9 2215.64  4433.5 2214.81  4454.4 2213.50  4462.0 2214.14
  4511.4 2213.01  4766.7 2211.26  4893.9 2207.89  4950.9 2207.66  4954.4 2206.05
  4976.9 2207.21  4982.1 2206.48  4988.0 2203.91  4996.4 2202.62  4996.6 2202.12
  5000.4 2202.62  5008.7 2206.07  5017.2 2208.00  5022.4 2205.08  5029.4 2206.73
  5039.7 2207.40  5216.5 2210.06  5393.7 2217.70  5518.8 2221.85  5681.6 2224.19
  5714.9 2224.85  5720.1 2225.77  5810.7 2225.78  5825.4 2227.15  5920.7 2228.65
#Mann=3,-1,0
  4182.5   0.035       0  4996.4   0.035       0  5000.4   0.035       0
Bank Sta=4996.4,5000.4
Exp/Cntr=0.3,0.1

Type RM Length L Ch R = 1,12597,764,764,764
BEGIN DESCRIPTION:
Linn Creek Trib063 14.0
END DESCRIPTION:
XS GIS Cut Line= 4
      1325363.83      6906267.03      1326148.61      6905267.61
      1326148.61      6905079.80      1325229.83      6904308.56
#Sta/Elev= 30
  3655.3 2217.64  4097.6 2213.02  4282.0 2208.44  4296.5 2209.29  4346.2 2207.93
  4424.8 2208.82  4495.3 2207.45  4582.1 2207.56  4723.1 2203.41  4766.5 2203.24
  4772.9 2202.24  4837.0 2201.63  4874.0 2199.35  4880.4 2200.12  4894.8 2198.55
  4901.2 2200.49  4909.3 2199.53  4915.6 2200.80  4945.6 2196.94  4973.6 2195.85
  4973.8 2195.35  4977.7 2195.85  5015.6 2196.56  5035.6 2199.24  5065.6 2201.14
  5373.2 2205.91  5593.1 2206.85  5841.5 2211.57  6168.0 2220.95  6313.4 2227.00
#Mann=3,-1,0
  3655.3   0.035       0  4973.6   0.035       0  4977.7   0.035       0
Bank Sta=4973.6,4977.7
Exp/Cntr=0.3,0.1

Type RM Length L Ch R = 1,11833,394,394,394
BEGIN DESCRIPTION:
Linn Creek Trib063 13.0
END DESCRIPTION:
XS GIS Cut Line= 3
      1327335.89      6905743.87      1326712.06      6904985.89
      1325223.84      6904402.67
#Sta/Elev= 30
  4081.9 2243.57  4250.0 2233.92  4328.2 2231.81  4413.3 2231.75  4555.8 2228.25
  4626.6 2224.32  4655.3 2224.98  4711.3 2218.45  4826.0 2211.54  4832.5 2209.58
  4846.8 2208.67  4867.7 2208.50  4875.5 2204.85  4882.0 2206.26  4889.9 2201.56
  4904.2 2199.67  4968.1 2196.06  4974.5 2193.40  4986.4 2193.11  4986.8 2192.61
  4991.4 2193.11  4996.1 2195.52  5009.7 2196.41  5146.3 2196.39  5152.7 2195.20
  5291.0 2196.00  5375.1 2200.11  6061.4 2206.56  6308.2 2212.84  6662.0 2226.54
#Mann=3,-1,0
  4081.9   0.035       0  4986.4   0.035       0  4991.4   0.035       0
Bank Sta=4986.4,4991.4
Exp/Cntr=0.3,0.1

Type RM Length L Ch R = 1,11439,475,475,475
BEGIN DESCRIPTION:
Linn Creek Trib063 12.0
END DESCRIPTION:
XS GIS Cut Line= 3
      1327469.99      6905307.83      1326765.72      6904677.33
      1325222.99      6904248.05
#Sta/Elev= 30
  4055.5 2233.63  4108.4 2231.48  4122.7 2232.65  4136.9 2232.46  4143.6 2231.46
  4250.1 2232.45  4328.3 2231.15  4412.7 2223.18  4512.2 2216.35  4646.7 2209.52
  4873.3 2201.08  4986.9 2193.41  5014.5 2190.22  5014.9 2189.72  5019.5 2190.22
  5032.6 2193.40  5051.2 2194.19  5209.1 2197.66  5356.1 2198.31  5571.8 2201.00
  5763.7 2201.57  5989.8 2205.04  6039.5 2206.22  6058.2 2207.58  6176.5 2210.38
  6195.2 2211.67  6210.7 2211.29  6397.4 2218.01  6431.6 2220.15  6602.1 2227.30
#Mann=3,-1,0
  4055.5   0.035       0  5014.5   0.035       0  5019.5   0.035       0
Bank Sta=5014.5,5019.5
Exp/Cntr=0.3,0.1

Type RM Length L Ch R = 1,10964,700,700,700
BEGIN DESCRIPTION:
Linn Creek Trib063 11.0
END DESCRIPTION:
XS GIS Cut Line= 3
      1327684.68      6905079.80      1326765.72      6904234.62
      1325155.02      6903888.00
#Sta/Elev= 30
  3740.0 2225.03  3797.5 2222.78  3804.9 2223.52  3811.7 2222.10  3825.9 2221.52
  4052.2 2214.23  4264.9 2209.25  4491.1 2201.02  4505.3 2201.41  4533.7 2199.69
  4824.1 2192.93  4930.1 2192.80  4991.5 2190.72  4997.9 2189.23  4998.3 2188.73
  5002.9 2189.23  5044.7 2191.94  5050.6 2194.13  5060.9 2195.83  5101.8 2194.42
  5138.2 2195.54  5182.4 2194.52  5296.1 2194.79  5623.5 2197.78  5766.7 2199.73
  5995.6 2205.36  6375.0 2218.79  6390.6 2220.67  6400.9 2220.26  6636.1 2233.33
#Mann=3,-1,0
  3740.0   0.035       0  4997.9   0.035       0  5002.9   0.035       0
Bank Sta=4997.9,5002.9
Exp/Cntr=0.3,0.1

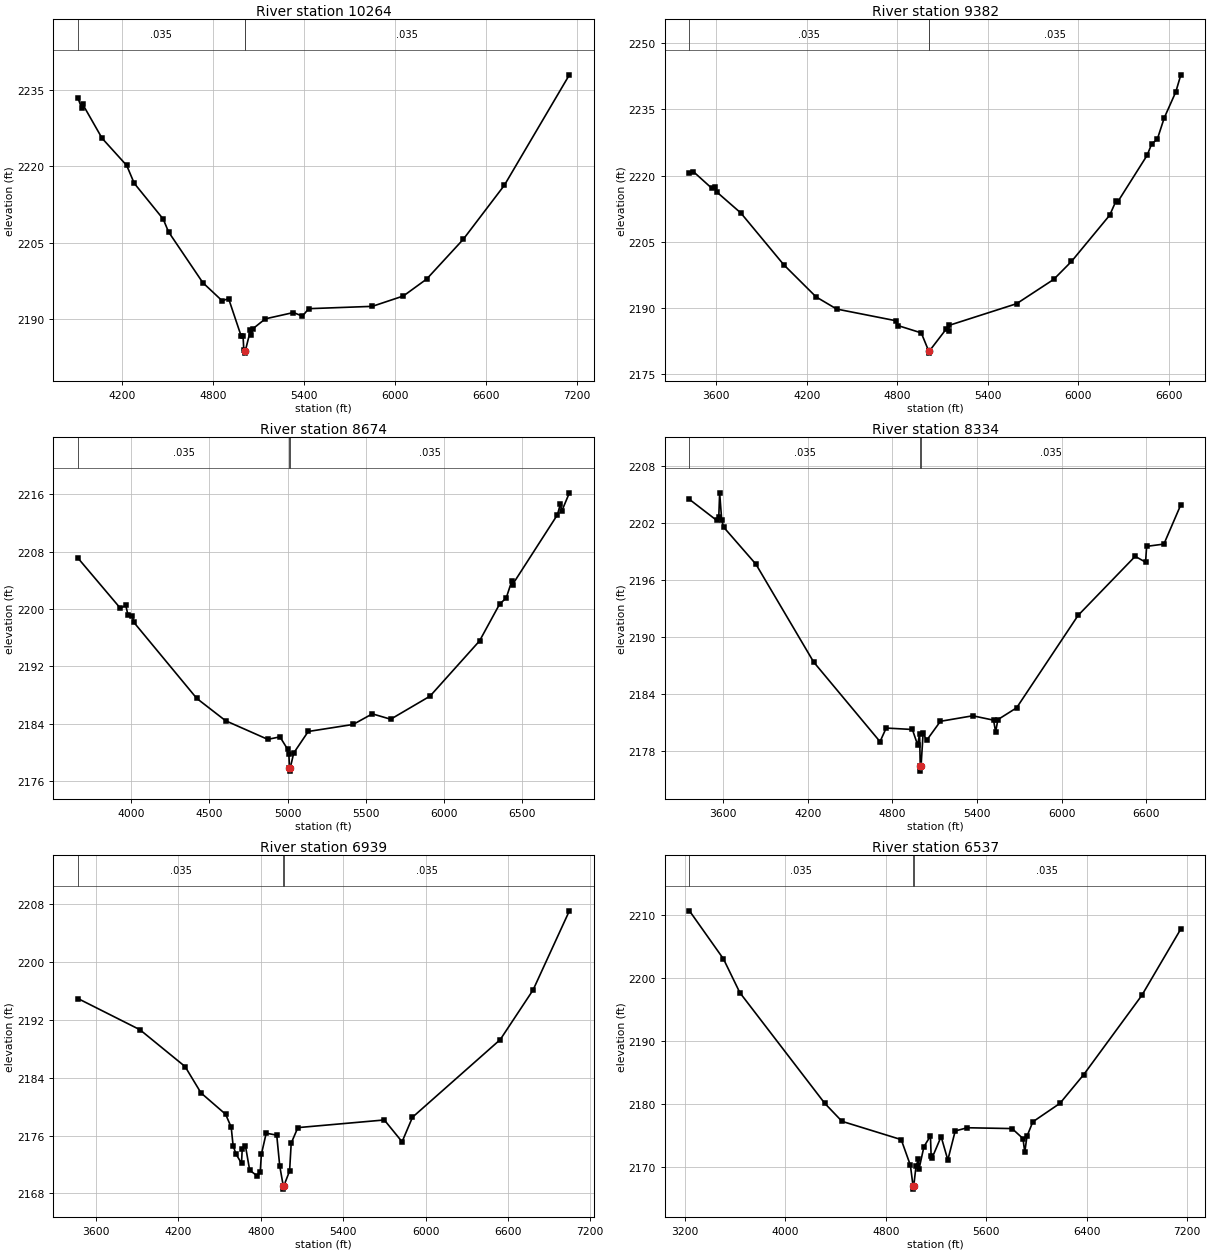
Type RM Length L Ch R = 1,10264,882,882,882
BEGIN DESCRIPTION:
Linn Creek Trib063 10.0
END DESCRIPTION:
XS GIS Cut Line= 3
      1328026.74      6904670.59      1327268.80      6903905.95
      1325155.84      6903443.11
#Sta/Elev= 30
  3910.0 2233.43  3934.3 2231.47  3941.4 2232.22  4068.6 2225.55  4231.3 2220.18
  4280.7 2216.68  4471.7 2209.64  4507.0 2207.11  4733.3 2197.10  4860.6 2193.54
  4903.0 2193.97  4985.8 2186.60  4998.0 2186.69  5003.2 2183.91  5008.4 2183.74
  5008.8 2183.24  5013.6 2183.74  5047.0 2187.72  5052.1 2186.79  5062.2 2188.02
  5144.9 2189.99  5330.5 2191.23  5389.8 2190.52  5430.7 2191.99  5850.4 2192.45
  6055.2 2194.49  6208.7 2197.82  6449.3 2205.62  6720.6 2216.27  7149.7 2238.03
#Mann=3,-1,0
  3910.0   0.035       0  5008.4   0.035       0  5013.6   0.035       0
Bank Sta=5008.4,5013.6
Exp/Cntr=0.3,0.1

Type RM Length L Ch R = 1,9382,708,708,708
BEGIN DESCRIPTION:
Linn Creek Trib063 9.0
END DESCRIPTION:
XS GIS Cut Line= 3
      1328269.45      6904210.42      1327116.70      6903328.50
      1325368.32      6902884.47
#Sta/Elev= 30
  3422.7 2220.62  3449.3 2220.90  3569.8 2217.18  3592.0 2217.49  3605.2 2216.26
  3763.0 2211.56  4047.7 2199.83  4261.7 2192.56  4397.8 2189.81  4789.4 2187.17
  4803.9 2186.07  4958.4 2184.41  5007.3 2180.33  5007.7 2179.83  5012.7 2180.33
  5123.5 2185.27  5139.6 2184.89  5144.8 2186.14  5590.0 2191.02  5835.7 2196.52
  5953.4 2200.58  6206.8 2211.06  6248.1 2214.26  6258.4 2213.99  6454.4 2224.60
  6485.7 2227.26  6521.5 2228.19  6567.9 2233.08  6644.3 2238.94  6678.0 2242.83
#Mann=3,-1,0
  3422.7   0.035       0  5007.3   0.035       0  5012.7   0.035       0
Bank Sta=5007.3,5012.7
Exp/Cntr=0.3,0.1

Type RM Length L Ch R = 1,8674,340,340,340
BEGIN DESCRIPTION:
Linn Creek Trib063 8.0
END DESCRIPTION:
XS GIS Cut Line= 3
      1328262.51      6903821.53      1327359.75      6902800.72
      1325638.74      6902363.53
#Sta/Elev= 30
  3661.1 2207.11  3931.4 2200.13  3966.5 2200.51  3980.7 2199.13  4009.2 2199.04
  4015.8 2198.21  4419.9 2187.54  4603.9 2184.43  4873.2 2181.83  4951.0 2182.18
  5000.8 2180.42  5007.9 2179.78  5011.8 2177.90  5012.3 2177.40  5017.3 2177.90
  5039.0 2179.93  5131.6 2182.93  5418.2 2183.91  5541.0 2185.39  5658.1 2184.64
  5909.5 2187.86  6225.6 2195.56  6354.7 2200.73  6395.7 2201.53  6431.4 2203.91
  6436.6 2203.43  6723.2 2213.16  6741.5 2214.64  6751.8 2213.72  6799.5 2216.22
#Mann=3,-1,0
  3661.1   0.035       0  5011.8   0.035       0  5017.3   0.035       0
Bank Sta=5011.8,5017.3
Exp/Cntr=0.3,0.1

Type RM Length L Ch R = 1,8334,1395,1395,1395
BEGIN DESCRIPTION:
Linn Creek Trib063 7.0
END DESCRIPTION:
XS GIS Cut Line= 3
      1328484.76      6903828.51      1327533.37      6902529.89
      1325769.72      6901891.09
#Sta/Elev= 30
  3360.1 2204.46  3553.6 2202.25  3568.2 2202.63  3574.4 2205.15  3589.1 2202.25
  3603.8 2201.52  3831.8 2197.64  4240.9 2187.36  4711.9 2178.98  4755.5 2180.41
  4941.5 2180.26  4978.8 2178.63  4992.5 2179.82  4997.3 2176.38  4997.8 2175.88
  5002.8 2176.38  5017.8 2179.90  5042.6 2179.12  5140.3 2181.12  5369.5 2181.70
  5517.3 2181.24  5531.9 2180.00  5548.0 2181.30  5680.8 2182.54  6116.9 2192.26
  6521.7 2198.47  6595.5 2197.86  6603.0 2199.52  6725.5 2199.76  6845.7 2203.90
#Mann=3,-1,0
  3360.1   0.035       0  4997.3   0.035       0  5002.8   0.035       0
Bank Sta=4997.3,5002.8
Exp/Cntr=0.3,0.1

Type RM Length L Ch R = 1,6939,402,402,402
BEGIN DESCRIPTION:
Linn Creek Trib063 6.0
END DESCRIPTION:
XS GIS Cut Line= 3
      1328686.15      6903529.91      1328075.03      6902161.83
      1326144.48      6901384.06
#Sta/Elev= 30
  3468.3 2194.95  3919.3 2190.64  4248.5 2185.54  4364.5 2181.89  4543.7 2178.94
  4584.4 2177.15  4598.5 2174.56  4620.4 2173.40  4659.5 2172.15  4665.0 2174.20
  4688.2 2174.56  4719.0 2171.20  4773.7 2170.41  4795.6 2170.89  4804.2 2173.39
  4839.4 2176.32  4916.1 2176.05  4938.0 2171.78  4963.2 2169.08  4963.7 2168.58
  4968.8 2169.08  5009.8 2171.09  5021.5 2174.94  5069.9 2177.09  5699.8 2178.15
  5829.2 2175.13  5905.1 2178.53  6544.3 2189.27  6783.3 2196.13  7048.0 2207.09
#Mann=3,-1,0
  3468.3   0.035       0  4963.2   0.035       0  4968.8   0.035       0
Bank Sta=4963.2,4968.8
Exp/Cntr=0.3,0.1

Type RM Length L Ch R = 1,6537,497,497,497
BEGIN DESCRIPTION:
Linn Creek Trib063 5.0
END DESCRIPTION:
XS GIS Cut Line= 3
      1329700.04      6902766.00      1328202.64      6901832.02
      1326159.20      6901169.05
#Sta/Elev= 30
  3235.2 2210.61  3505.9 2202.99  3636.8 2197.63  4312.8 2180.09  4449.7 2177.24
  4921.6 2174.34  4994.7 2170.26  5015.7 2166.99  5016.2 2166.49  5021.3 2166.99
  5039.6 2170.15  5058.5 2171.19  5063.7 2169.70  5102.7 2173.24  5154.4 2174.91
  5159.7 2171.82  5165.7 2171.35  5239.3 2174.82  5292.8 2171.11  5351.5 2175.71
  5447.4 2176.22  5804.4 2176.09  5891.1 2174.51  5905.5 2172.33  5922.7 2174.85
  5969.5 2177.16  6185.5 2180.09  6374.7 2184.64  6837.3 2197.20  7148.3 2207.74
#Mann=3,-1,0
  3235.2   0.035       0  5015.7   0.035       0  5021.3   0.035       0
Bank Sta=5015.7,5021.3
Exp/Cntr=0.3,0.1

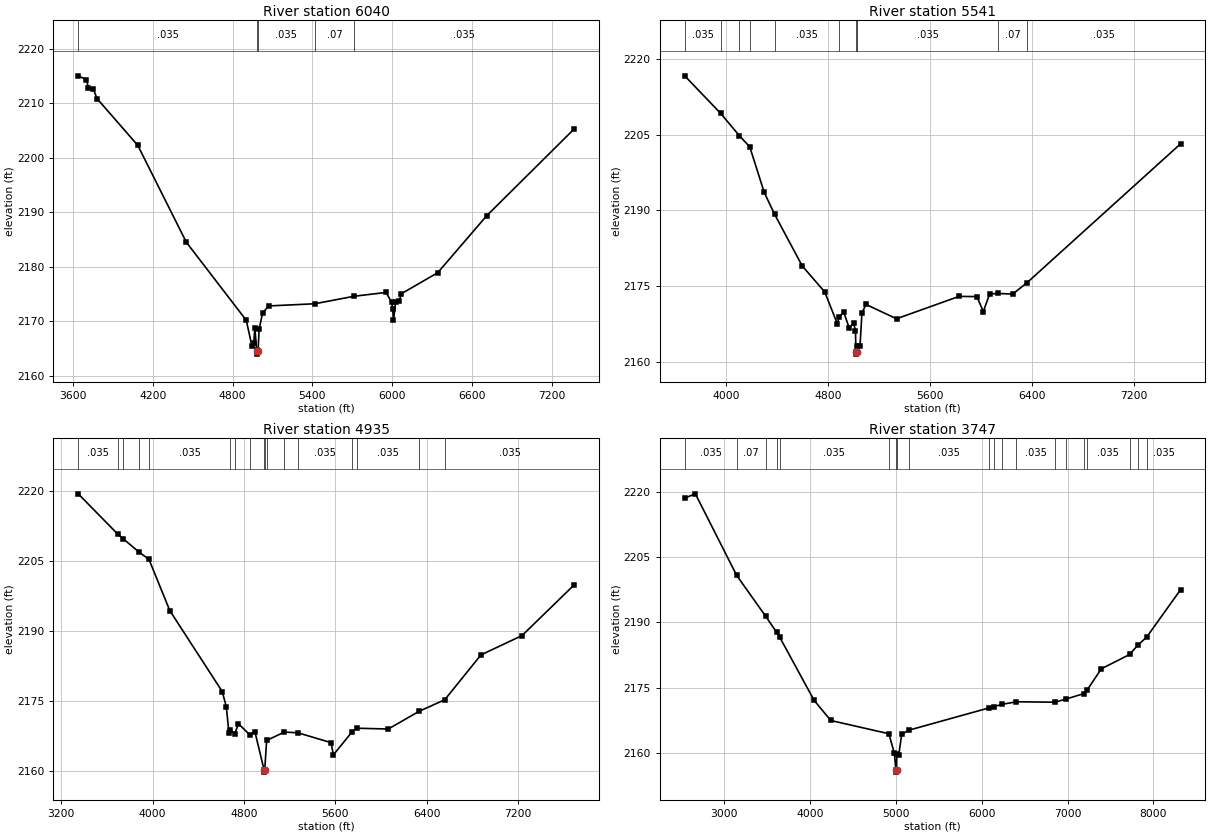
Type RM Length L Ch R = 1,6040,499,499,499
BEGIN DESCRIPTION:
Linn Creek Trib063 4.0
END DESCRIPTION:
XS GIS Cut Line= 3
      1329630.58      6902349.33      1328539.79      6901537.24
      1326220.86      6901057.67
#Sta/Elev= 30
  3640.1 2215.01  3702.0 2214.31  3716.7 2212.82  3752.1 2212.68  3781.3 2210.84
  4087.9 2202.25  4452.8 2184.48  4903.3 2170.16  4945.0 2165.53  4959.6 2166.01
  4968.0 2168.72  4981.0 2164.67  4985.8 2164.45  4986.3 2163.95  4991.8 2164.45
  4999.9 2168.50  5025.7 2171.45  5070.8 2172.79  5418.1 2173.19  5714.6 2174.57
  5954.3 2175.27  5995.4 2173.49  6004.5 2172.15  6009.6 2170.12  6026.0 2173.58
  6054.7 2173.72  6066.9 2175.00  6342.6 2178.89  6710.2 2189.33  7368.0 2205.26
#Mann=5,-1,0
  3640.1   0.035       0  4985.8   0.035       0  4991.8   0.035       0
  5418.1    0.07       0  5714.6   0.035       0
Bank Sta=4985.8,4991.8
Exp/Cntr=0.3,0.1

Type RM Length L Ch R = 1,5541,606,606,606
BEGIN DESCRIPTION:
Linn Creek Trib063 3.0
END DESCRIPTION:
XS GIS Cut Line= 4
      1329609.77      6902134.08      1328739.75      6901137.52
      1328693.09      6901071.56      1326208.53      6900946.63
#Sta/Elev= 30
  3677.1 2216.72  3960.0 2209.25  4105.7 2204.85  4187.9 2202.61  4301.3 2193.57
  4382.1 2189.26  4599.4 2178.98  4775.9 2173.82  4875.6 2167.46  4890.0 2168.91
  4925.0 2169.79  4967.7 2166.70  5002.8 2167.63  5017.3 2166.08  5020.9 2161.97
  5021.4 2161.47  5026.9 2161.97  5031.1 2163.09  5053.0 2163.15  5067.8 2169.56
  5098.9 2171.34  5339.2 2168.49  5829.8 2172.93  5970.0 2172.89  6020.1 2169.92
  6070.1 2173.41  6137.7 2173.51  6251.1 2173.39  6365.1 2175.69  7568.5 2203.23
#Mann=11,-1,0
  3677.1   0.035       0  3960.0    0.07       0  4105.7   0.035       0
  4187.9    0.07       0  4382.1   0.035       0  4890.0    0.07       0
  5020.9    0.07       0  5026.9    0.07       0  5031.1   0.035       0
  6137.7    0.07       0  6365.1   0.035       0
Bank Sta=5020.9,5026.9
Exp/Cntr=0.3,0.1

Type RM Length L Ch R = 1,4935,1188,1188,1188
BEGIN DESCRIPTION:
Linn Creek Trib063 2.0
END DESCRIPTION:
XS GIS Cut Line= 4
      1329679.20      6902252.12      1329061.14      6900842.39
      1328887.53      6900793.78      1326269.71      6900877.10
#Sta/Elev= 30
  3350.0 2219.30  3698.0 2210.62  3746.0 2209.62  3885.6 2206.76  3969.2 2205.26
  4151.6 2194.28  4610.2 2176.96  4645.7 2173.68  4669.1 2168.04  4682.0 2168.79
  4719.4 2167.90  4752.1 2170.07  4848.5 2167.76  4895.6 2168.39  4975.7 2160.21
  4976.2 2159.71  4981.8 2160.21  4998.5 2166.50  5154.1 2168.29  5272.5 2168.13
  5562.3 2166.02  5582.3 2163.40  5746.2 2168.34  5788.9 2169.11  6062.6 2168.94
  6333.8 2172.75  6556.4 2175.20  6873.0 2184.80  7233.2 2188.96  7688.7 2199.80
#Mann=17,-1,0
  3350.0   0.035       0  3698.0    0.07       0  3746.0   0.035       0
  3885.6    0.07       0  3969.2   0.035       0  4682.0    0.07       0
  4719.4   0.035       0  4848.5    0.07       0  4975.7   0.035       0
  4981.8    0.07       0  4998.5   0.035       0  5154.1    0.07       0
  5272.5   0.035       0  5746.2    0.07       0  5788.9   0.035       0
  6333.8    0.07       0  6556.4   0.035       0
Bank Sta=4975.7,4981.8
Exp/Cntr=0.3,0.1

Type RM Length L Ch R = 1,3747,0,0,0
BEGIN DESCRIPTION:
Linn Creek Trib063 1.0
END DESCRIPTION:
XS GIS Cut Line= 4
      1329762.53      6902411.84      1329540.31      6900071.56
      1329352.81      6899918.78      1326298.64      6900814.21
#Sta/Elev= 30
  2540.6 2218.62  2665.0 2219.60  3146.5 2200.80  3483.0 2191.43  3611.2 2187.72
  3648.8 2186.54  4047.3 2172.06  4242.1 2167.41  4918.5 2164.36  4983.1 2159.82
  5000.1 2156.02  5000.6 2155.52  5007.7 2156.02  5011.8 2159.80  5032.7 2159.36
  5067.8 2164.20  5149.9 2165.17  6086.8 2170.32  6142.5 2170.59  6231.8 2171.11
  6403.7 2171.72  6852.3 2171.62  6977.6 2172.32  7188.7 2173.60  7225.7 2174.38
  7392.5 2179.31  7722.2 2182.61  7817.6 2184.75  7919.9 2186.59  8316.0 2197.54
#Mann=20,-1,0
  2540.6   0.035       0  3146.5    0.07       0  3483.0   0.035       0
  3611.2    0.07       0  3648.8   0.035       0  4918.5    0.07       0
  5000.1    0.07       0  5007.7    0.07       0  5149.9   0.035       0
  6086.8    0.07       0  6142.5   0.035       0  6231.8    0.07       0
  6403.7   0.035       0  6852.3    0.07       0  6977.6   0.035       0
  7188.7    0.07       0  7225.7   0.035       0  7722.2    0.07       0
  7817.6   0.035       0  7919.9   0.035       0
Bank Sta=5000.1,5007.7
Exp/Cntr=0.3,0.1

Chan Stop Cuts=-1