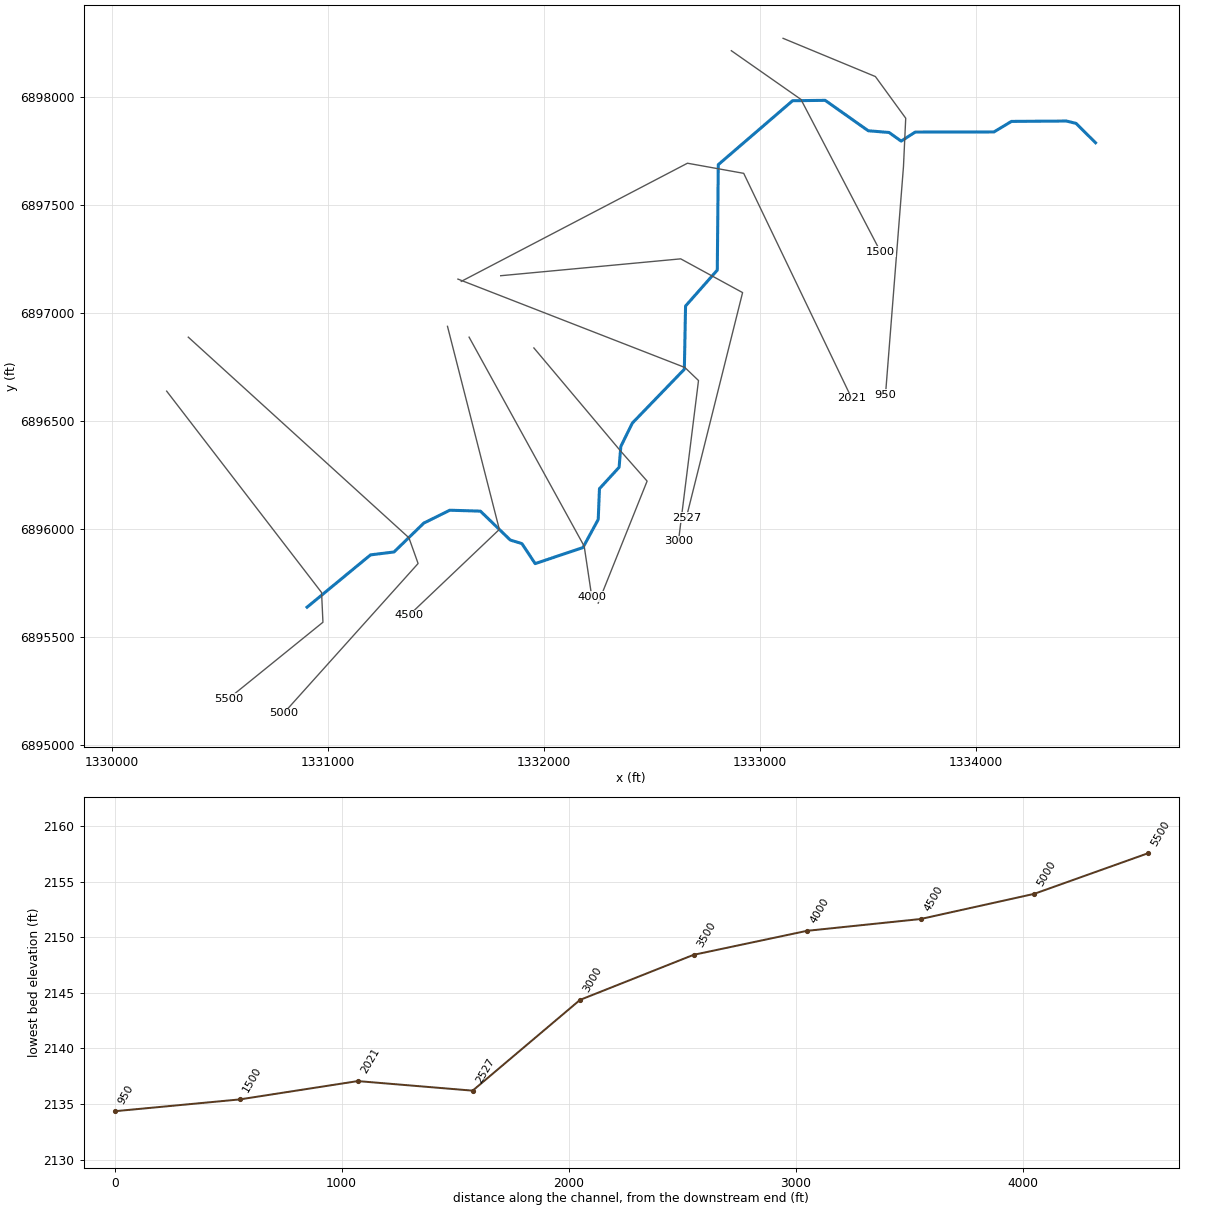
--- Linn Creek Trib065.prj (project) ---

Proj Title=Linn Creek Trib065 Base Level Engineering
Current Plan=p01
Default Exp/Contr=0.3,0.1
English Units
Geom File=g01
Flow File=f01
Plan File=p01
BEGIN DESCRIPTION:
Linn Creek Trib065
END DESCRIPTION:

--- Linn Creek Trib065.p01 (plan) ---

Plan Title=Multiple Run
Short Identifier=Multiple
Geom File=g01
Flow File=f01
Subcritical Flow
K Sum by GR= 0
Std Step Tol= 0.01
Critical Tol= 0.01
Num of Std Step Trials= 20
Max Error Tol= 0.3
Flow Tol Ratio= 0.001
Split Flow NTrial= 30
Split Flow Tol= 0.02
Split Flow Ratio= 0.02
Log Output Level= 0
Friction Slope Method= 1
Unsteady Friction Slope Method= 2
Unsteady Bridges Friction Slope Method= 1
Parabolic Critical Depth
Global Vel Dist=  1 , 1 , 1
Global Log Level= 0
CheckData=True
Encroach Param= -1, 0, 0, 0
BEGIN DESCRIPTION:
Multiple Run
END DESCRIPTION:

--- Linn Creek Trib065.f01 (steady flow) ---

Flow Title=Multiple
Number of Profiles=7
Profile Names=10-year,25-year,50-year,1pct_min,100-year,1pct_plu,500-year
River Rch & RM= Linn Creek Trib0,Reach-1,5500
     305     439     554     348     695    1386    1105
River Rch & RM= Linn Creek Trib0,Reach-1,4500
     315     452     570     357     713    1422    1129
Boundary for River Rch & Prof#=Linn Creek Trib0,Reach-1,1
Up Type=0
Dn Type=3
Dn Slope=0.005
Boundary for River Rch & Prof#=Linn Creek Trib0,Reach-1,2
Up Type=0
Dn Type=3
Dn Slope=0.005
Boundary for River Rch & Prof#=Linn Creek Trib0,Reach-1,3
Up Type=0
Dn Type=3
Dn Slope=0.005
Boundary for River Rch & Prof#=Linn Creek Trib0,Reach-1,4
Up Type=0
Dn Type=3
Dn Slope=0.005
Boundary for River Rch & Prof#=Linn Creek Trib0,Reach-1,5
Up Type=0
Dn Type=3
Dn Slope=0.005
Boundary for River Rch & Prof#=Linn Creek Trib0,Reach-1,6
Up Type=0
Dn Type=3
Dn Slope=0.005
Boundary for River Rch & Prof#=Linn Creek Trib0,Reach-1,7
Up Type=0
Dn Type=3
Dn Slope=0.005

--- Linn Creek Trib065.g01 (geometry) ---

Geom Title=Existing Conditions

River Reach=Linn Creek Trib0,Reach-1
Reach XY= 30
      1330905.00      6895638.00      1331198.83      6895880.14
      1331307.43      6895893.52      1331445.32      6896027.24
      1331565.50      6896086.81      1331707.45      6896082.55
      1331845.58      6895948.89      1331899.37      6895932.34
      1331960.86      6895839.57      1332182.19      6895914.04
      1332252.75      6896043.93      1332258.56      6896186.53
      1332349.46      6896285.58      1332357.33      6896382.03
      1332410.83      6896490.30      1332651.46      6896739.46
      1332657.06      6897032.15      1332803.95      6897198.43
      1332808.54      6897686.54      1333152.55      6897982.55
      1333303.44      6897984.26      1333502.58      6897843.53
      1333599.10      6897835.44      1333655.00      6897795.56
      1333720.16      6897837.34      1334084.97      6897838.07
      1334165.50      6897886.78      1334420.20      6897888.49
      1334464.84      6897877.61      1334555.00      6897788.00

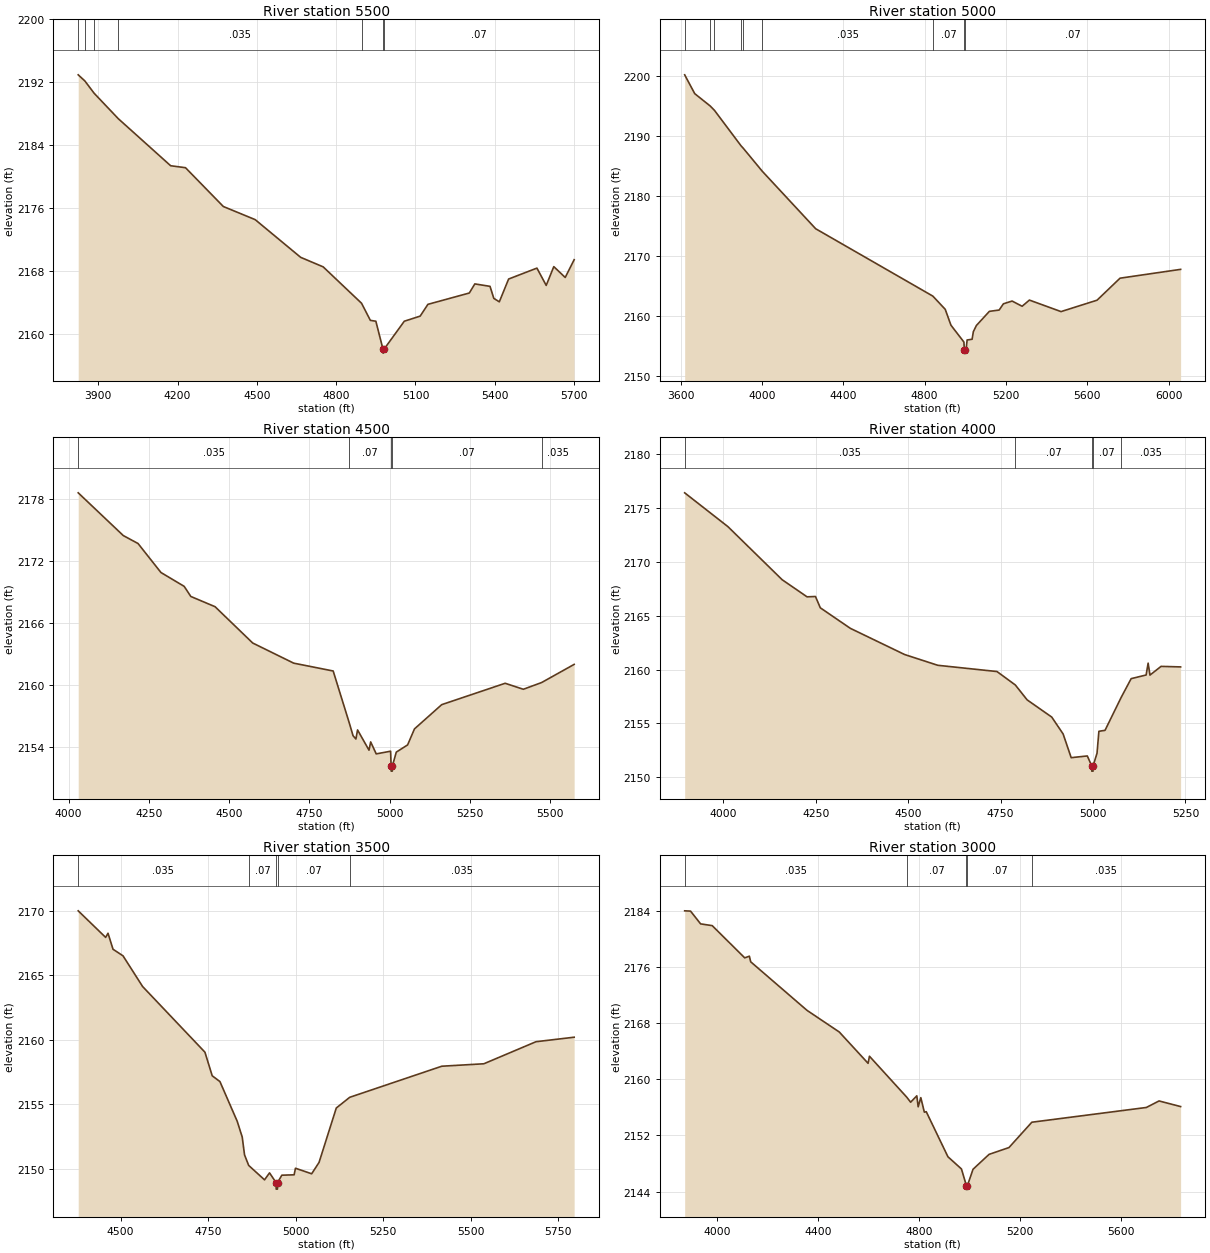
Type RM Length L Ch R = 1,5500,500,500,500
BEGIN DESCRIPTION:
Linn Creek Trib065 11.0
END DESCRIPTION:
XS GIS Cut Line= 4
      1330254.97      6896638.04      1330972.12      6895705.76
      1330978.36      6895568.21      1330540.84      6895214.03
#Sta/Elev= 30
  3823.8 2192.95  3849.0 2192.17  3884.2 2190.60  3975.4 2187.37  4173.6 2181.38
  4229.8 2181.13  4373.0 2176.19  4493.5 2174.52  4665.7 2169.72  4750.8 2168.51
  4896.0 2163.88  4929.4 2161.70  4950.2 2161.59  4977.2 2158.03  4977.4 2157.53
  4981.2 2158.03  5057.8 2161.59  5117.9 2162.24  5147.2 2163.74  5303.9 2165.18
  5324.7 2166.34  5382.2 2166.03  5396.6 2164.50  5417.4 2164.06  5452.6 2166.96
  5559.7 2168.35  5594.9 2166.15  5623.6 2168.54  5666.8 2167.16  5700.6 2169.42
#Mann=7,-1,0
  3823.8    0.07       0  3849.0   0.035       0  3884.2    0.07       0
  3975.4   0.035       0  4896.0    0.07       0  4977.2    0.07       0
  4981.2    0.07       0
Bank Sta=4977.2,4981.2
Exp/Cntr=0.3,0.1

Type RM Length L Ch R = 1,5000,500,500,500
BEGIN DESCRIPTION:
Linn Creek Trib065 10.0
END DESCRIPTION:
XS GIS Cut Line= 4
      1330355.03      6896887.97      1331376.36      6895959.32
      1331418.90      6895840.13      1330796.07      6895146.34
#Sta/Elev= 30
  3619.6 2200.27  3669.2 2197.13  3745.3 2195.07  3766.1 2194.35  3897.1 2188.43
  3907.4 2188.05  4001.3 2184.20  4263.9 2174.62  4840.3 2163.39  4901.1 2161.19
  4929.4 2158.54  4993.0 2155.74  4995.3 2154.39  4995.5 2153.89  4999.3 2154.39
  5003.4 2154.39  5008.8 2156.08  5033.3 2156.20  5039.6 2157.48  5054.5 2158.50
  5118.2 2160.85  5166.4 2161.07  5187.3 2162.11  5230.0 2162.57  5279.3 2161.70
  5315.2 2162.73  5470.7 2160.81  5647.8 2162.71  5761.0 2166.38  6058.9 2167.85
#Mann=9,-1,0
  3619.6    0.07       0  3745.3   0.035       0  3766.1    0.07       0
  3897.1   0.035       0  3907.4    0.07       0  4001.3   0.035       0
  4840.3    0.07       0  4995.3    0.07       0  4999.3    0.07       0
Bank Sta=4995.3,4999.3
Exp/Cntr=0.3,0.1

Type RM Length L Ch R = 1,4500,500,500,500
BEGIN DESCRIPTION:
Linn Creek Trib065 9.0
END DESCRIPTION:
XS GIS Cut Line= 3
      1331554.99      6896938.05      1331794.99      6895997.90
      1331377.94      6895601.32
#Sta/Elev= 30
  4029.7 2178.59  4170.2 2174.45  4216.2 2173.68  4287.6 2170.87  4360.0 2169.53
  4380.7 2168.55  4456.2 2167.56  4573.6 2164.04  4701.3 2162.09  4824.4 2161.33
  4873.0 2156.46  4886.4 2155.06  4895.3 2154.74  4900.4 2155.62  4936.1 2153.66
  4941.3 2154.46  4958.6 2153.30  5003.4 2153.56  5005.0 2152.13  5005.2 2151.63
  5008.7 2151.63  5009.0 2152.13  5021.1 2153.47  5056.4 2154.17  5077.8 2155.72
  5162.7 2158.07  5360.5 2160.14  5417.1 2159.56  5474.0 2160.21  5575.5 2161.97
#Mann=5,-1,0
  4029.7   0.035       0  4873.0    0.07       0  5005.0    0.07       0
  5009.0    0.07       0  5474.0   0.035       0
Bank Sta=5005,5009
Exp/Cntr=0.3,0.1

Type RM Length L Ch R = 1,4000,500,500,500
BEGIN DESCRIPTION:
Linn Creek Trib065 8.0
END DESCRIPTION:
XS GIS Cut Line= 3
      1331654.99      6896888.02      1332187.85      6895920.11
      1332223.00      6895685.73
#Sta/Elev= 30
  3895.1 2176.42  4012.1 2173.28  4158.8 2168.35  4226.2 2166.76  4249.0 2166.79
  4262.1 2165.74  4343.5 2163.83  4490.2 2161.40  4580.0 2160.40  4740.2 2159.82
  4789.8 2158.57  4821.7 2157.19  4888.3 2155.59  4919.1 2154.02  4940.9 2151.82
  4984.5 2151.98  4996.3 2151.07  4996.6 2150.57  5000.1 2150.57  5000.3 2151.07
  5010.8 2152.23  5015.9 2154.27  5032.5 2154.36  5076.5 2157.44  5103.2 2159.16
  5143.7 2159.50  5149.1 2160.60  5154.1 2159.49  5184.1 2160.30  5237.0 2160.25
#Mann=5,-1,0
  3895.1   0.035       0  4789.8    0.07       0  4996.3    0.07       0
  5000.3    0.07       0  5076.5   0.035       0
Bank Sta=4996.3,5000.3
Exp/Cntr=0.3,0.1

Type RM Length L Ch R = 1,3500,500,500,500
BEGIN DESCRIPTION:
Linn Creek Trib065 7.0
END DESCRIPTION:
XS GIS Cut Line= 4
      1331955.01      6896837.99      1332354.99      6896362.44
      1332479.06      6896221.60      1332252.67      6895656.77
#Sta/Elev= 30
  4378.6 2169.99  4457.0 2167.93  4463.8 2168.25  4478.1 2167.01  4506.7 2166.50
  4562.7 2164.12  4740.8 2159.03  4761.6 2157.20  4783.7 2156.75  4833.1 2153.67
  4847.4 2152.45  4854.0 2151.07  4865.8 2150.25  4911.2 2149.13  4925.5 2149.67
  4944.3 2148.91  4944.6 2148.41  4948.1 2148.41  4948.3 2148.91  4960.6 2149.49
  4995.8 2149.52  4999.6 2150.03  5045.9 2149.60  5067.0 2150.48  5116.3 2154.70
  5154.7 2155.53  5417.8 2157.94  5538.1 2158.13  5687.1 2159.84  5796.2 2160.19
#Mann=5,-1,0
  4378.6   0.035       0  4865.8    0.07       0  4944.3    0.07       0
  4948.3    0.07       0  5154.7   0.035       0
Bank Sta=4944.3,4948.3
Exp/Cntr=0.3,0.1

Type RM Length L Ch R = 1,3000,473,473,473
BEGIN DESCRIPTION:
Linn Creek Trib065 6.0
END DESCRIPTION:
XS GIS Cut Line= 4
      1331603.33      6897156.76      1332653.78      6896747.66
      1332716.98      6896687.24      1332624.19      6895943.24
#Sta/Elev= 30
  3872.7 2184.00  3896.0 2183.96  3935.8 2182.14  3981.8 2181.89  4110.6 2177.30
  4128.9 2177.54  4134.2 2176.74  4357.4 2169.82  4485.1 2166.74  4599.2 2162.28
  4604.6 2163.29  4752.8 2157.44  4767.7 2156.74  4792.2 2157.65  4797.6 2156.09
  4808.1 2157.39  4822.1 2155.32  4829.6 2155.39  4915.5 2148.97  4969.1 2147.23
  4988.6 2144.86  4988.8 2144.36  4992.7 2144.86  5014.9 2147.19  5078.4 2149.31
  5157.2 2150.28  5247.9 2153.89  5701.4 2155.99  5751.8 2156.92  5837.2 2156.12
#Mann=5,-1,0
  3872.7   0.035       0  4752.8    0.07       0  4988.6    0.07       0
  4992.7    0.07       0  5247.9   0.035       0
Bank Sta=4988.6,4992.7
Exp/Cntr=0.3,0.1

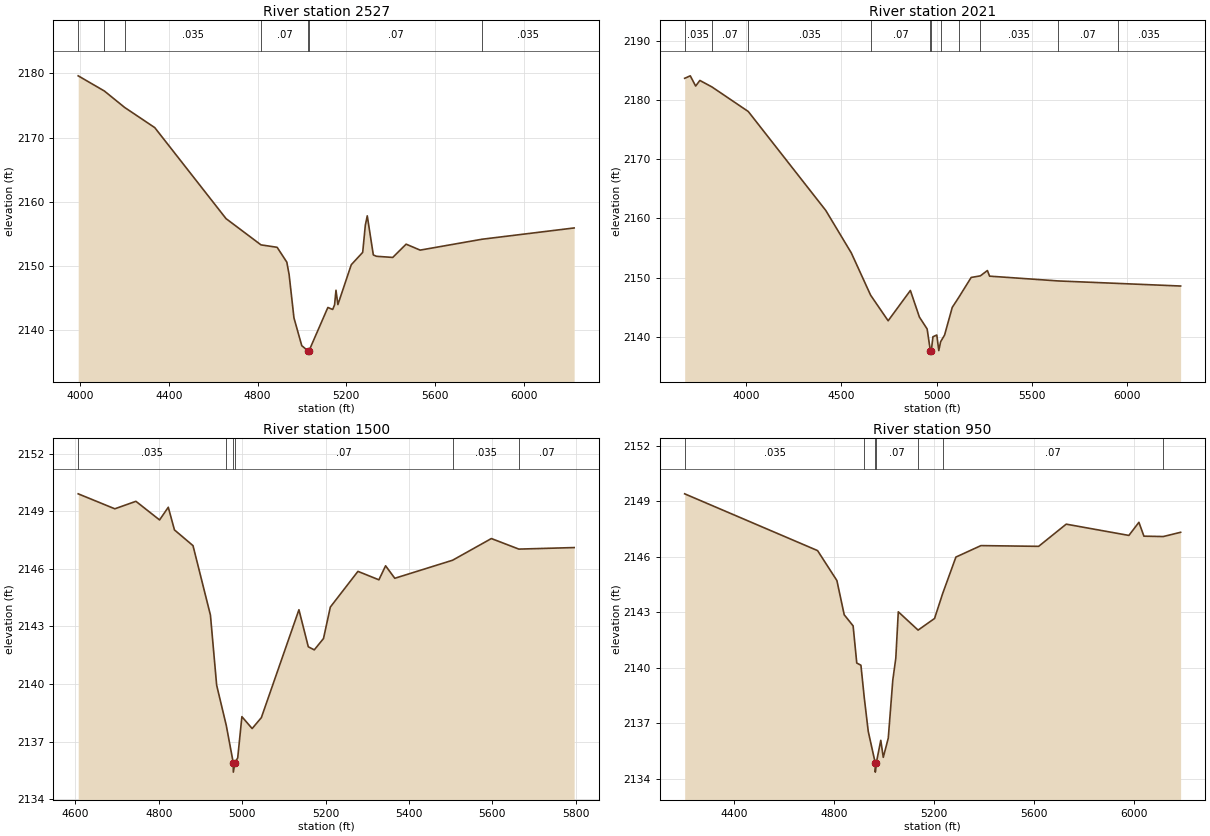
Type RM Length L Ch R = 1,2527,506,506,506
BEGIN DESCRIPTION:
Linn Creek Trib065 5.0
END DESCRIPTION:
XS GIS Cut Line= 4
      1331801.31      6897172.38      1332634.61      6897250.50
      1332921.07      6897094.25      1332660.69      6896052.75
#Sta/Elev= 30
  3991.0 2179.63  4109.0 2177.26  4200.3 2174.70  4336.2 2171.55  4657.6 2157.35
  4815.3 2153.25  4888.2 2152.87  4931.9 2150.55  4942.3 2148.60  4964.1 2141.85
  4999.3 2137.52  5027.6 2136.70  5027.8 2136.20  5031.7 2136.70  5117.0 2143.48
  5138.8 2143.17  5147.3 2143.90  5153.6 2146.17  5162.2 2143.93  5222.5 2150.15
  5274.1 2152.08  5285.9 2156.30  5294.7 2157.78  5322.0 2151.68  5335.9 2151.47
  5409.6 2151.29  5469.9 2153.36  5533.3 2152.43  5812.4 2154.13  6227.8 2155.89
#Mann=7,-1,0
  3991.0   0.035       0  4109.0    0.07       0  4200.3   0.035       0
  4815.3    0.07       0  5027.6    0.07       0  5031.7    0.07       0
  5812.4   0.035       0
Bank Sta=5027.6,5031.7
Exp/Cntr=0.3,0.1

Type RM Length L Ch R = 1,2021,521,521,521
BEGIN DESCRIPTION:
Linn Creek Trib065 4.0
END DESCRIPTION:
XS GIS Cut Line= 4
      1331618.95      6897146.31      1332665.86      6897693.21
      1332926.27      6897646.33      1333426.27      6896604.67
#Sta/Elev= 30
  3677.5 2183.68  3706.9 2184.10  3735.1 2182.37  3757.2 2183.32  3820.6 2182.22
  4011.1 2178.07  4417.7 2161.34  4551.6 2154.16  4652.8 2147.02  4744.7 2142.70
  4861.3 2147.82  4908.6 2143.33  4949.2 2141.31  4966.5 2137.56  4966.8 2137.06
  4970.7 2137.56  4979.7 2140.00  5000.0 2140.29  5010.2 2137.66  5020.0 2139.16
  5040.7 2140.29  5080.9 2144.96  5113.7 2146.58  5180.2 2150.02  5228.3 2150.29
  5265.3 2151.19  5276.7 2150.24  5636.8 2149.43  5951.5 2149.01  6278.7 2148.57
#Mann=11,-1,0
  3677.5   0.035       0  3820.6    0.07       0  4011.1   0.035       0
  4652.8    0.07       0  4966.5    0.07       0  4970.7    0.07       0
  5020.0   0.035       0  5113.7    0.07       0  5228.3   0.035       0
  5636.8    0.07       0  5951.5   0.035       0
Bank Sta=4966.5,4970.7
Exp/Cntr=0.3,0.1

Type RM Length L Ch R = 1,1500,550,550,550
BEGIN DESCRIPTION:
Linn Creek Trib065 3.0
END DESCRIPTION:
XS GIS Cut Line= 3
      1332869.01      6898214.02      1333191.25      6897988.53
      1333559.79      6897282.98
#Sta/Elev= 30
  4606.7 2149.91  4694.5 2149.13  4745.1 2149.52  4801.8 2148.55  4822.7 2149.21
  4837.5 2148.03  4882.0 2147.21  4923.8 2143.59  4938.7 2139.94  4961.8 2137.84
  4978.4 2135.91  4978.7 2135.41  4982.6 2135.91  4989.2 2136.15  4999.2 2138.30
  5023.8 2137.68  5045.9 2138.25  5136.0 2143.87  5158.5 2141.94  5172.8 2141.78
  5194.9 2142.37  5211.3 2144.01  5277.5 2145.87  5327.8 2145.43  5343.8 2146.16
  5365.9 2145.51  5504.5 2146.45  5597.5 2147.58  5663.4 2147.03  5796.0 2147.11
#Mann=6,-1,0
  4606.7   0.035       0  4961.8    0.07       0  4978.4    0.07       0
  4982.6    0.07       0  5504.5   0.035       0  5663.4    0.07       0
Bank Sta=4978.4,4982.6
Exp/Cntr=0.3,0.1

Type RM Length L Ch R = 1,950,0,0,0
BEGIN DESCRIPTION:
Linn Creek Trib065 2.0
END DESCRIPTION:
XS GIS Cut Line= 5
      1333108.56      6898271.33      1333535.88      6898094.42
      1333676.27      6897901.54      1333665.86      6897677.58
      1333582.63      6896621.61
#Sta/Elev= 30
  4202.3 2149.40  4734.1 2146.33  4811.4 2144.71  4840.7 2142.86  4876.3 2142.26
  4890.9 2140.25  4907.6 2140.13  4920.8 2138.39  4936.9 2136.55  4964.8 2134.85
  4965.1 2134.35  4969.1 2134.85  4987.0 2136.07  4997.0 2135.15  5017.0 2136.19
  5035.2 2139.34  5047.1 2140.51  5057.1 2143.02  5136.3 2142.03  5202.2 2142.66
  5234.7 2144.01  5287.6 2145.98  5387.9 2146.60  5618.7 2146.56  5729.0 2147.76
  5979.8 2147.15  6019.9 2147.86  6040.0 2147.11  6117.4 2147.09  6186.8 2147.32
#Mann=7,-1,0
  4202.3   0.035       0  4920.8    0.07       0  4964.8    0.07       0
  4969.1    0.07       0  5136.3   0.035       0  5234.7    0.07       0
  6117.4   0.035       0
Bank Sta=4964.8,4969.1
Exp/Cntr=0.3,0.1

Chan Stop Cuts=-1