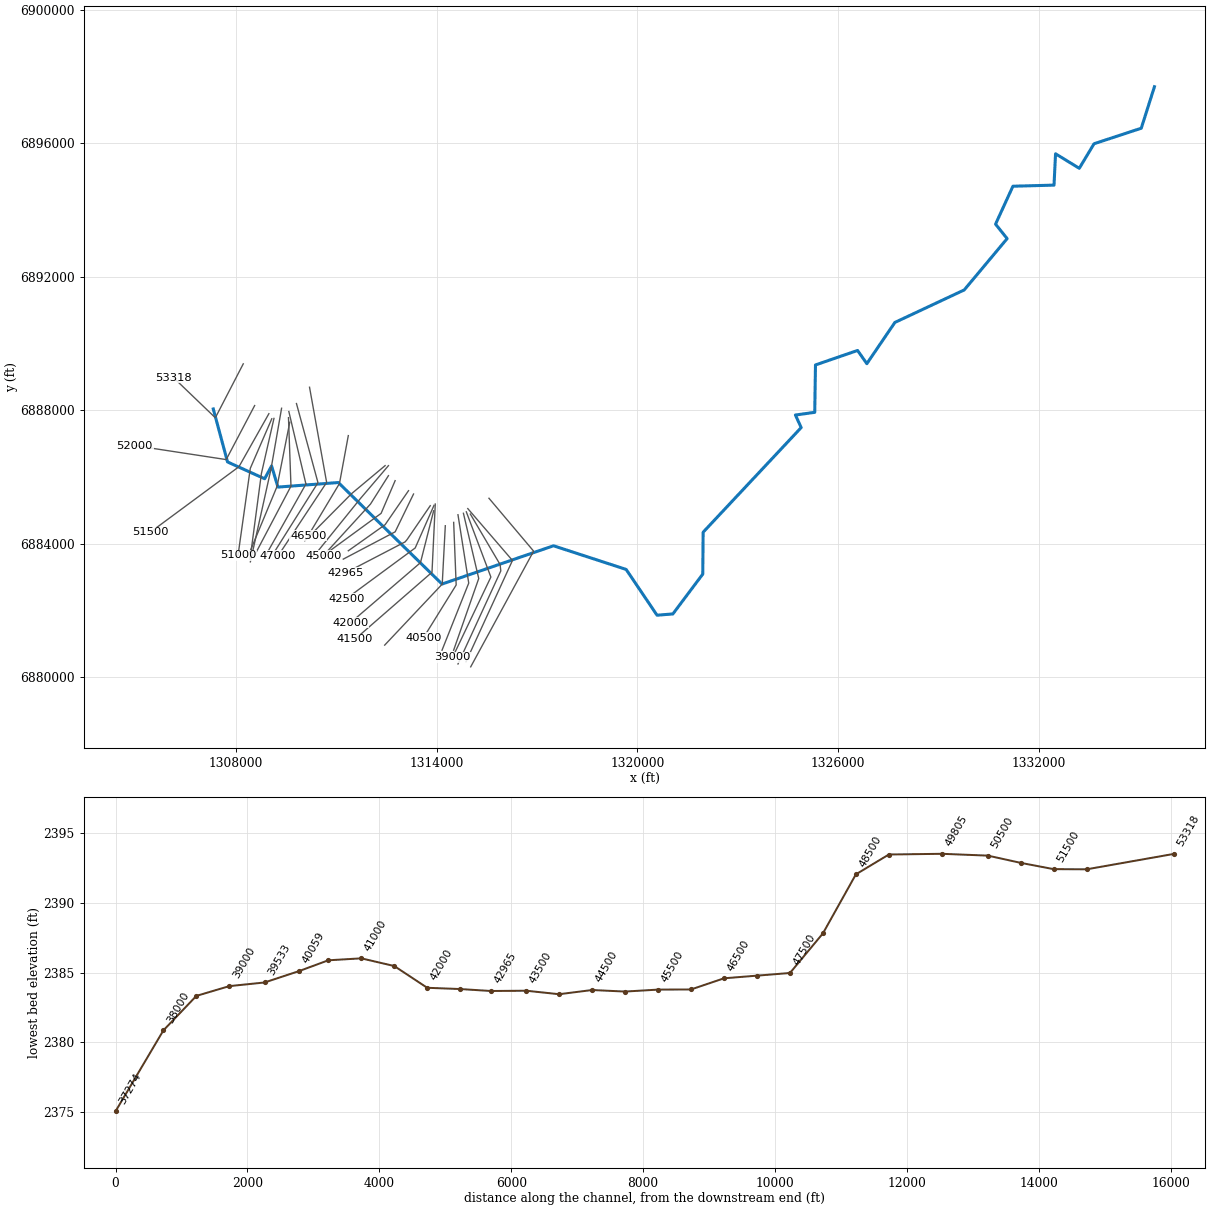
--- Linn Creek Trib066.prj (project) ---

Proj Title=Linn Creek Trib066 Base Level Engineering
Current Plan=p01
Default Exp/Contr=0.3,0.1
English Units
Geom File=g01
Flow File=f01
Plan File=p01
BEGIN DESCRIPTION:
Linn Creek Trib066
END DESCRIPTION:

--- Linn Creek Trib066.p01 (plan) ---

Plan Title=Multiple Run
Short Identifier=Multiple
Geom File=g01
Flow File=f01
Subcritical Flow
K Sum by GR= 0
Std Step Tol= 0.01
Critical Tol= 0.01
Num of Std Step Trials= 20
Max Error Tol= 0.3
Flow Tol Ratio= 0.001
Split Flow NTrial= 30
Split Flow Tol= 0.02
Split Flow Ratio= 0.02
Log Output Level= 0
Friction Slope Method= 1
Unsteady Friction Slope Method= 2
Unsteady Bridges Friction Slope Method= 1
Parabolic Critical Depth
Global Vel Dist=  1 , 1 , 1
Global Log Level= 0
CheckData=True
Encroach Param= -1, 0, 0, 0
BEGIN DESCRIPTION:
Multiple Run
END DESCRIPTION:

--- Linn Creek Trib066.f01 (steady flow) ---

Flow Title=Multiple
Number of Profiles=7
Profile Names=10-year,25-year,50-year,1pct_min,100-year,1pct_plu,500-year
River Rch & RM= Linn Creek Trib0,Reach-1,53318
      77      96     110      62     124     246     159
River Rch & RM= Linn Creek Trib0,Reach-1,51000
     156     204     240     140     280     558     384
River Rch & RM= Linn Creek Trib0,Reach-1,44500
     206     276     330     195     389     776     550
River Rch & RM= Linn Creek Trib0,Reach-1,37000
     425     607     760     472     941    1878    1464
River Rch & RM= Linn Creek Trib0,Reach-1,31000
     716    1052    1343     848    1693    3378    2731
River Rch & RM= Linn Creek Trib0,Reach-1,26500
     909    1345    1724    1094    2183    4355    3548
River Rch & RM= Linn Creek Trib0,Reach-1,19000
     991    1473    1896    1207    2408    4805    3941
River Rch & RM= Linn Creek Trib0,Reach-1,15500
    1115    1664    2147    1370    2733    5453    4494
River Rch & RM= Linn Creek Trib0,Reach-1,6647
    1170    1749    2259    1443    2879    5744    4742
Boundary for River Rch & Prof#=Linn Creek Trib0,Reach-1,1
Up Type=0
Dn Type=3
Dn Slope=0.005
Boundary for River Rch & Prof#=Linn Creek Trib0,Reach-1,2
Up Type=0
Dn Type=3
Dn Slope=0.005
Boundary for River Rch & Prof#=Linn Creek Trib0,Reach-1,3
Up Type=0
Dn Type=3
Dn Slope=0.005
Boundary for River Rch & Prof#=Linn Creek Trib0,Reach-1,4
Up Type=0
Dn Type=3
Dn Slope=0.005
Boundary for River Rch & Prof#=Linn Creek Trib0,Reach-1,5
Up Type=0
Dn Type=3
Dn Slope=0.005
Boundary for River Rch & Prof#=Linn Creek Trib0,Reach-1,6
Up Type=0
Dn Type=3
Dn Slope=0.005
Boundary for River Rch & Prof#=Linn Creek Trib0,Reach-1,7
Up Type=0
Dn Type=3
Dn Slope=0.005

--- Linn Creek Trib066.g01 (geometry) ---

Geom Title=Existing Conditions

River Reach=Linn Creek Trib0,Reach-1
Reach XY= 30
      1307318.56      6888035.38      1307744.95      6886448.59
      1308854.80      6885944.98      1309061.68      6886329.06
      1309251.67      6885695.62      1311057.30      6885832.20
      1314156.43      6882791.01      1317489.71      6883937.62
      1319661.74      6883228.87      1320584.87      6881857.76
      1321058.33      6881895.60      1321951.97      6883089.38
      1321963.15      6884344.07      1324894.26      6887478.30
      1324721.63      6887854.67      1325299.54      6887934.99
      1325321.63      6889354.71      1326579.70      6889788.62
      1326857.28      6889393.05      1327695.17      6890627.53
      1329768.30      6891601.40      1331051.55      6893139.49
      1330705.20      6893572.90      1331224.68      6894708.32
      1332453.37      6894741.09      1332498.48      6895680.33
      1333208.35      6895245.58      1333648.91      6895980.52
      1335061.20      6896445.80      1335455.00      6897688.00

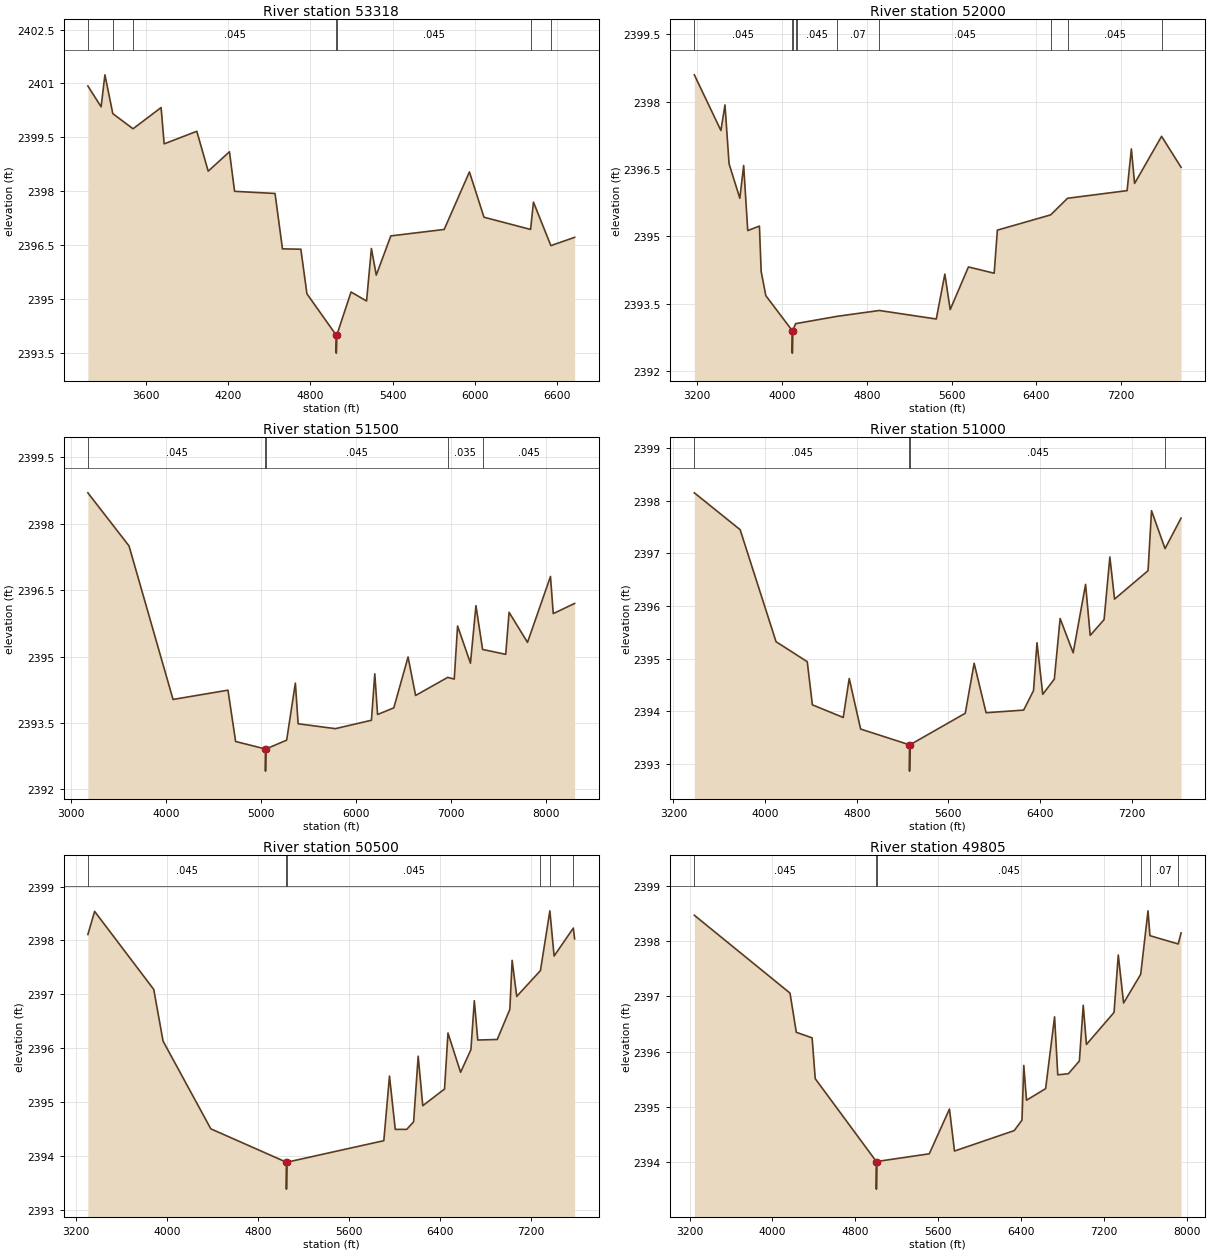
Type RM Length L Ch R = 1,53318,1318,1318,1318
BEGIN DESCRIPTION:
Linn Creek Trib066 99.5
END DESCRIPTION:
XS GIS Cut Line= 3
      1308214.70      6889387.96      1307379.83      6887772.27
      1306133.83      6888970.94
#Sta/Elev= 30
  3178.6 2400.93  3275.1 2400.35  3302.9 2401.24  3360.4 2400.16  3507.8 2399.74
  3712.4 2400.33  3734.6 2399.32  3972.6 2399.67  4055.5 2398.56  4210.6 2399.10
  4247.9 2398.00  4542.8 2397.94  4596.8 2396.40  4730.9 2396.39  4775.2 2395.15
  4988.8 2394.00  4989.0 2393.50  4992.8 2394.00  5096.7 2395.20  5209.9 2394.95
  5245.1 2396.41  5280.6 2395.67  5386.6 2396.76  5775.6 2396.94  5959.6 2398.54
  6065.6 2397.28  6405.3 2396.94  6426.3 2397.70  6553.3 2396.49  6726.2 2396.72
#Mann=7,-1,0
  3178.6   0.045       0  3360.4   0.035       0  3507.8   0.045       0
  4988.8   0.045       0  4992.8   0.045       0  6405.3   0.035       0
  6553.3   0.045       0
Bank Sta=4988.8,4992.8
Exp/Cntr=0.3,0.1

Type RM Length L Ch R = 1,52000,500,500,500
BEGIN DESCRIPTION:
Linn Creek Trib066 99.0
END DESCRIPTION:
XS GIS Cut Line= 3
      1308555.02      6888138.03      1307704.57      6886519.45
      1304971.36      6886938.16
#Sta/Elev= 30
  3171.6 2398.60  3422.3 2397.36  3460.8 2397.93  3499.2 2396.62  3600.9 2395.85
  3637.1 2396.58  3675.6 2395.13  3785.8 2395.23  3802.2 2394.22  3846.3 2393.68
  4095.9 2392.90  4096.2 2392.40  4099.9 2392.90  4128.2 2393.06  4136.0 2393.06
  4519.1 2393.22  4918.2 2393.35  5454.8 2393.16  5535.7 2394.16  5586.3 2393.37
  5758.3 2394.32  6001.1 2394.18  6031.5 2395.14  6534.3 2395.48  6693.8 2395.85
  7255.6 2396.02  7296.0 2396.95  7326.4 2396.18  7581.0 2397.23  7765.1 2396.54
#Mann=10,-1,0
  3171.6   0.045       0  4095.9   0.045       0  4099.9   0.045       0
  4128.2    0.07       0  4136.0   0.045       0  4519.1    0.07       0
  4918.2   0.045       0  6534.3   0.035       0  6693.8   0.045       0
  7581.0   0.035       0
Bank Sta=4095.9,4099.9
Exp/Cntr=0.3,0.1

Type RM Length L Ch R = 1,51500,500,500,500
BEGIN DESCRIPTION:
Linn Creek Trib066 98.0
END DESCRIPTION:
XS GIS Cut Line= 3
      1308980.62      6887894.54      1308086.59      6886306.63
      1305429.43      6884338.94
#Sta/Elev= 30
  3177.7 2398.70  3611.3 2397.50  4075.2 2394.03  4654.1 2394.24  4734.5 2393.08
  5049.0 2392.91  5049.3 2392.41  5053.0 2392.91  5272.2 2393.11  5364.0 2394.40
  5393.3 2393.48  5785.9 2393.37  6165.5 2393.56  6200.9 2394.61  6230.2 2393.69
  6401.3 2393.84  6551.6 2394.99  6630.9 2394.12  6970.2 2394.53  7037.9 2394.49
  7073.4 2395.69  7209.0 2394.85  7266.7 2396.15  7336.9 2395.16  7580.5 2395.05
  7616.0 2396.00  7810.1 2395.32  8052.2 2396.81  8081.4 2395.97  8306.4 2396.20
#Mann=5,-1,0
  3177.7   0.045       0  5049.0   0.045       0  5053.0   0.045       0
  6970.2   0.035       0  7336.9   0.045       0
Bank Sta=5049,5053
Exp/Cntr=0.3,0.1

Type RM Length L Ch R = 1,51000,500,500,500
BEGIN DESCRIPTION:
Linn Creek Trib066 97.0
END DESCRIPTION:
XS GIS Cut Line= 3
      1309067.44      6887742.66      1308425.30      6886258.41
      1308058.40      6883652.51
#Sta/Elev= 30
  3382.8 2398.15  3782.4 2397.45  4096.1 2395.32  4368.5 2394.94  4413.2 2394.12
  4682.5 2393.88  4734.9 2394.62  4834.3 2393.66  5260.9 2393.36  5261.2 2392.86
  5265.0 2393.36  5747.7 2393.96  5825.2 2394.91  5929.5 2393.97  6257.5 2394.02
  6343.5 2394.39  6373.8 2395.30  6424.3 2394.32  6525.3 2394.61  6575.8 2395.76
  6689.8 2395.11  6798.0 2396.41  6838.4 2395.44  6959.5 2395.74  7010.0 2396.93
  7050.9 2396.13  7343.3 2396.67  7373.6 2397.81  7491.7 2397.09  7631.6 2397.67
#Mann=4,-1,0
  3382.8   0.045       0  5260.9   0.045       0  5265.0   0.045       0
  7491.7   0.035       0
Bank Sta=5260.9,5265
Exp/Cntr=0.3,0.1

Type RM Length L Ch R = 1,50500,695,695,695
BEGIN DESCRIPTION:
Linn Creek Trib066 96.0
END DESCRIPTION:
XS GIS Cut Line= 3
      1309132.53      6887753.47      1308756.45      6886097.95
      1308416.42      6883532.78
#Sta/Elev= 30
  3302.3 2398.11  3361.6 2398.54  3882.2 2397.09  3964.2 2396.13  4384.7 2394.50
  5050.2 2393.88  5050.5 2393.38  5054.3 2393.88  5907.8 2394.28  5957.7 2395.48
  6008.7 2394.49  6109.5 2394.49  6170.1 2394.63  6210.4 2395.85  6250.8 2394.93
  6442.5 2395.24  6472.7 2396.28  6583.7 2395.55  6674.5 2395.97  6704.7 2396.88
  6735.0 2396.15  6906.5 2396.16  7017.4 2396.72  7037.6 2397.63  7078.0 2396.96
  7286.8 2397.44  7369.8 2398.55  7407.0 2397.71  7576.4 2398.23  7587.6 2398.03
#Mann=6,-1,0
  3302.3   0.045       0  5050.2   0.045       0  5054.3   0.045       0
  7286.8   0.035       0  7369.8    0.07       0  7576.4   0.045       0
Bank Sta=5050.2,5054.3
Exp/Cntr=0.3,0.1

Type RM Length L Ch R = 1,49805,805,805,805
BEGIN DESCRIPTION:
Linn Creek Trib066 95.0
END DESCRIPTION:
XS GIS Cut Line= 3
      1309360.40      6888057.33      1309045.73      6886245.24
      1308427.24      6883456.62
#Sta/Elev= 30
  3246.4 2398.47  4169.3 2397.06  4230.2 2396.35  4382.5 2396.25  4412.8 2395.51
  5002.4 2394.01  5002.6 2393.51  5006.5 2394.01  5513.0 2394.15  5707.5 2394.96
  5756.2 2394.20  6332.4 2394.57  6407.2 2394.76  6424.6 2395.75  6450.8 2395.12
  6635.4 2395.33  6721.7 2396.63  6752.4 2395.58  6854.8 2395.60  6960.9 2395.83
  6998.2 2396.84  7029.0 2396.13  7295.3 2396.71  7336.2 2397.75  7387.5 2396.88
  7552.5 2397.40  7623.0 2398.55  7641.5 2398.10  7914.1 2397.95  7942.0 2398.15
#Mann=6,-1,0
  3246.4   0.045       0  5002.4   0.045       0  5006.5   0.045       0
  7552.5   0.035       0  7641.5    0.07       0  7914.1   0.045       0
Bank Sta=5002.4,5006.5
Exp/Cntr=0.3,0.1

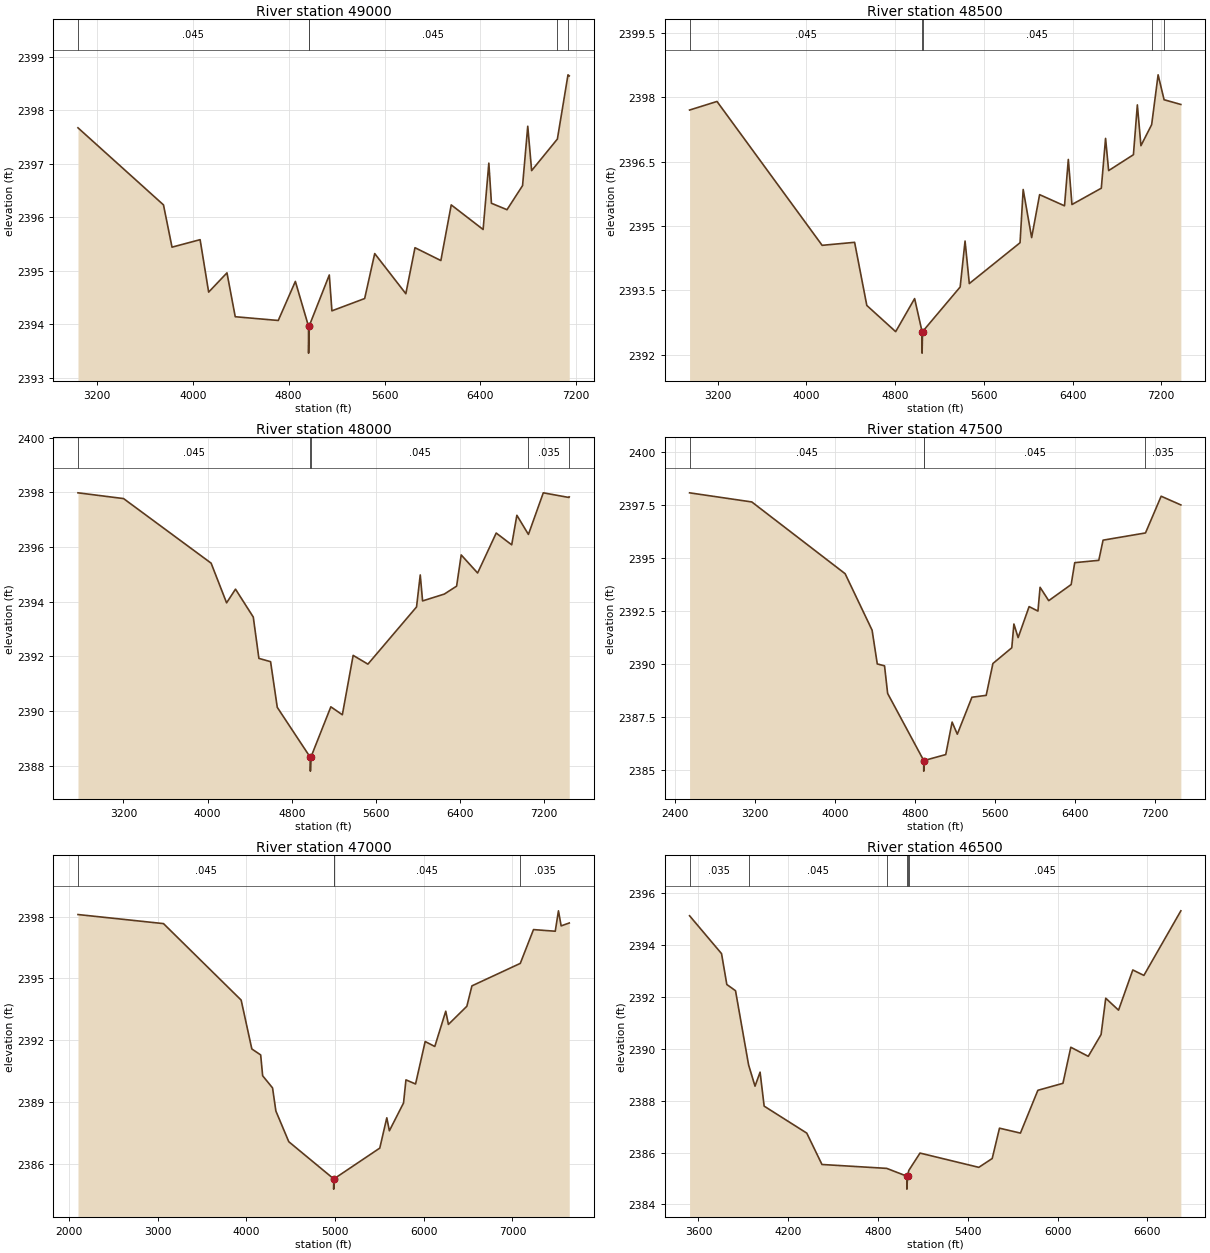
Type RM Length L Ch R = 1,49000,500,500,500
BEGIN DESCRIPTION:
Linn Creek Trib066 94.0
END DESCRIPTION:
XS GIS Cut Line= 3
      1309605.00      6887638.02      1309225.35      6885716.77
      1308404.99      6883737.98
#Sta/Elev= 30
  3041.6 2397.67  3755.2 2396.23  3826.5 2395.44  4061.0 2395.58  4132.3 2394.60
  4285.2 2394.96  4354.2 2394.14  4713.2 2394.07  4856.0 2394.80  4966.1 2393.96
  4966.4 2393.46  4970.2 2393.96  5139.3 2394.92  5161.1 2394.25  5434.4 2394.48
  5518.3 2395.32  5778.1 2394.57  5854.4 2395.43  6070.4 2395.19  6157.0 2396.23
  6423.1 2395.77  6470.9 2397.01  6492.6 2396.26  6622.5 2396.14  6752.4 2396.59
  6795.7 2397.70  6828.1 2396.87  7042.9 2397.46  7131.6 2398.66  7142.1 2398.64
#Mann=5,-1,0
  3041.6   0.045       0  4966.1   0.045       0  4970.2   0.045       0
  7042.9   0.035       0  7131.6    0.07       0
Bank Sta=4966.1,4970.2
Exp/Cntr=0.3,0.1

Type RM Length L Ch R = 1,48500,500,500,500
BEGIN DESCRIPTION:
Linn Creek Trib066 93.0
END DESCRIPTION:
XS GIS Cut Line= 3
      1309566.56      6887775.14      1309641.01      6885723.59
      1308535.77      6883619.41
#Sta/Elev= 30
  2947.1 2397.70  3194.4 2397.90  4142.4 2394.55  4435.2 2394.62  4545.3 2393.15
  4805.5 2392.54  4976.3 2393.31  5043.5 2392.54  5043.7 2392.04  5047.6 2392.54
  5387.0 2393.58  5431.1 2394.65  5469.4 2393.66  5926.9 2394.61  5955.1 2395.85
  6031.5 2394.73  6103.3 2395.73  6327.9 2395.47  6362.2 2396.55  6395.0 2395.50
  6659.6 2395.88  6698.0 2397.04  6725.7 2396.29  6949.2 2396.66  6984.6 2397.82
  7016.9 2396.87  7113.6 2397.36  7171.8 2398.52  7225.7 2397.94  7376.8 2397.83
#Mann=5,-1,0
  2947.1   0.045       0  5043.5   0.045       0  5047.6   0.045       0
  7113.6   0.035       0  7225.7    0.07       0
Bank Sta=5043.5,5047.6
Exp/Cntr=0.3,0.1

Type RM Length L Ch R = 1,48000,500,500,500
BEGIN DESCRIPTION:
Linn Creek Trib066 92.0
END DESCRIPTION:
XS GIS Cut Line= 3
      1309577.41      6887959.63      1310087.87      6885787.51
      1308893.90      6883662.92
#Sta/Elev= 30
  2768.7 2397.98  3201.8 2397.77  4033.9 2395.41  4180.8 2393.96  4265.6 2394.46
  4434.5 2393.44  4487.9 2391.93  4598.9 2391.81  4662.6 2390.14  4976.9 2388.31
  4977.2 2387.81  4981.1 2388.31  5171.5 2390.16  5280.9 2389.87  5383.6 2392.04
  5523.9 2391.72  5985.9 2393.81  6021.2 2394.98  6043.3 2394.03  6249.8 2394.28
  6366.7 2394.57  6410.4 2395.71  6566.3 2395.05  6743.0 2396.51  6890.2 2396.08
  6939.3 2397.16  7049.1 2396.46  7190.4 2397.98  7434.1 2397.81  7437.1 2397.83
#Mann=5,-1,0
  2768.7   0.045       0  4976.9   0.045       0  4981.1   0.045       0
  7049.1   0.035       0  7434.1    0.07       0
Bank Sta=4976.9,4981.1
Exp/Cntr=0.3,0.1

Type RM Length L Ch R = 1,47500,500,500,500
BEGIN DESCRIPTION:
Linn Creek Trib066 91.0
END DESCRIPTION:
XS GIS Cut Line= 4
      1309805.27      6888198.37      1310447.17      6885831.88
      1310447.21      6885827.46      1309143.38      6883749.57
#Sta/Elev= 30
  2548.0 2398.08  3170.1 2397.65  4102.6 2394.27  4372.0 2391.61  4423.8 2390.02
  4496.3 2389.93  4527.4 2388.63  4887.9 2385.47  4888.2 2384.97  4892.2 2385.47
  5108.1 2385.75  5171.7 2387.28  5223.6 2386.71  5369.7 2388.45  5512.2 2388.54
  5579.4 2390.04  5767.9 2390.78  5789.1 2391.90  5831.5 2391.26  5941.1 2392.72
  6029.5 2392.51  6050.7 2393.63  6137.1 2393.00  6361.4 2393.76  6397.1 2394.79
  6637.4 2394.90  6680.2 2395.85  7104.2 2396.19  7260.7 2397.92  7457.5 2397.51
#Mann=4,-1,0
  2548.0   0.045       0  4887.9   0.045       0  4892.2   0.045       0
  7104.2   0.035       0
Bank Sta=4887.9,4892.2
Exp/Cntr=0.3,0.1

Type RM Length L Ch R = 1,47000,500,500,500
BEGIN DESCRIPTION:
Linn Creek Trib066 90.0
END DESCRIPTION:
XS GIS Cut Line= 3
      1310195.89      6888686.69      1310707.32      6885835.39
      1309252.81      6883631.61
#Sta/Elev= 30
  2103.2 2398.10  3067.0 2397.66  3942.4 2393.95  4062.7 2391.58  4162.4 2391.29
  4184.6 2390.28  4296.3 2389.69  4333.7 2388.57  4479.2 2387.08  4985.0 2385.28
  4985.3 2384.78  4989.3 2385.28  5504.8 2386.77  5584.0 2388.24  5613.1 2387.61
  5772.7 2388.96  5799.8 2390.08  5908.1 2389.88  6016.5 2391.94  6124.9 2391.70
  6248.4 2393.41  6278.5 2392.77  6486.2 2393.65  6543.4 2394.64  7088.5 2395.73
  7237.4 2397.37  7482.6 2397.29  7518.8 2398.28  7548.9 2397.55  7640.5 2397.69
#Mann=4,-1,0
  2103.2   0.045       0  4985.0   0.045       0  4989.3   0.045       0
  7088.5   0.035       0
Bank Sta=4985,4989.3
Exp/Cntr=0.3,0.1

Type RM Length L Ch R = 1,46500,500,500,500
BEGIN DESCRIPTION:
Linn Creek Trib066 89.0
END DESCRIPTION:
XS GIS Cut Line= 3
      1311355.01      6887238.03      1311090.78      6885802.85
      1310155.00      6884238.00
#Sta/Elev= 30
  3540.7 2395.13  3754.3 2393.67  3789.6 2392.48  3847.7 2392.24  3935.1 2389.38
  3978.0 2388.56  4011.9 2389.10  4039.0 2387.79  4323.7 2386.75  4425.4 2385.54
  4857.9 2385.39  4992.4 2385.09  4992.8 2384.59  4997.1 2385.09  5005.5 2385.31
  5080.4 2385.98  5473.3 2385.43  5562.8 2385.77  5611.5 2386.94  5751.4 2386.75
  5867.9 2388.40  6035.5 2388.67  6088.0 2390.06  6204.7 2389.71  6290.3 2390.55
  6321.5 2391.95  6407.0 2391.49  6502.3 2393.04  6576.3 2392.83  6823.3 2395.32
#Mann=6,-1,0
  3540.7   0.035       0  3935.1   0.045       0  4857.9   0.035       0
  4992.4   0.035       0  4997.1   0.035       0  5005.5   0.045       0
Bank Sta=4992.4,4997.1
Exp/Cntr=0.3,0.1

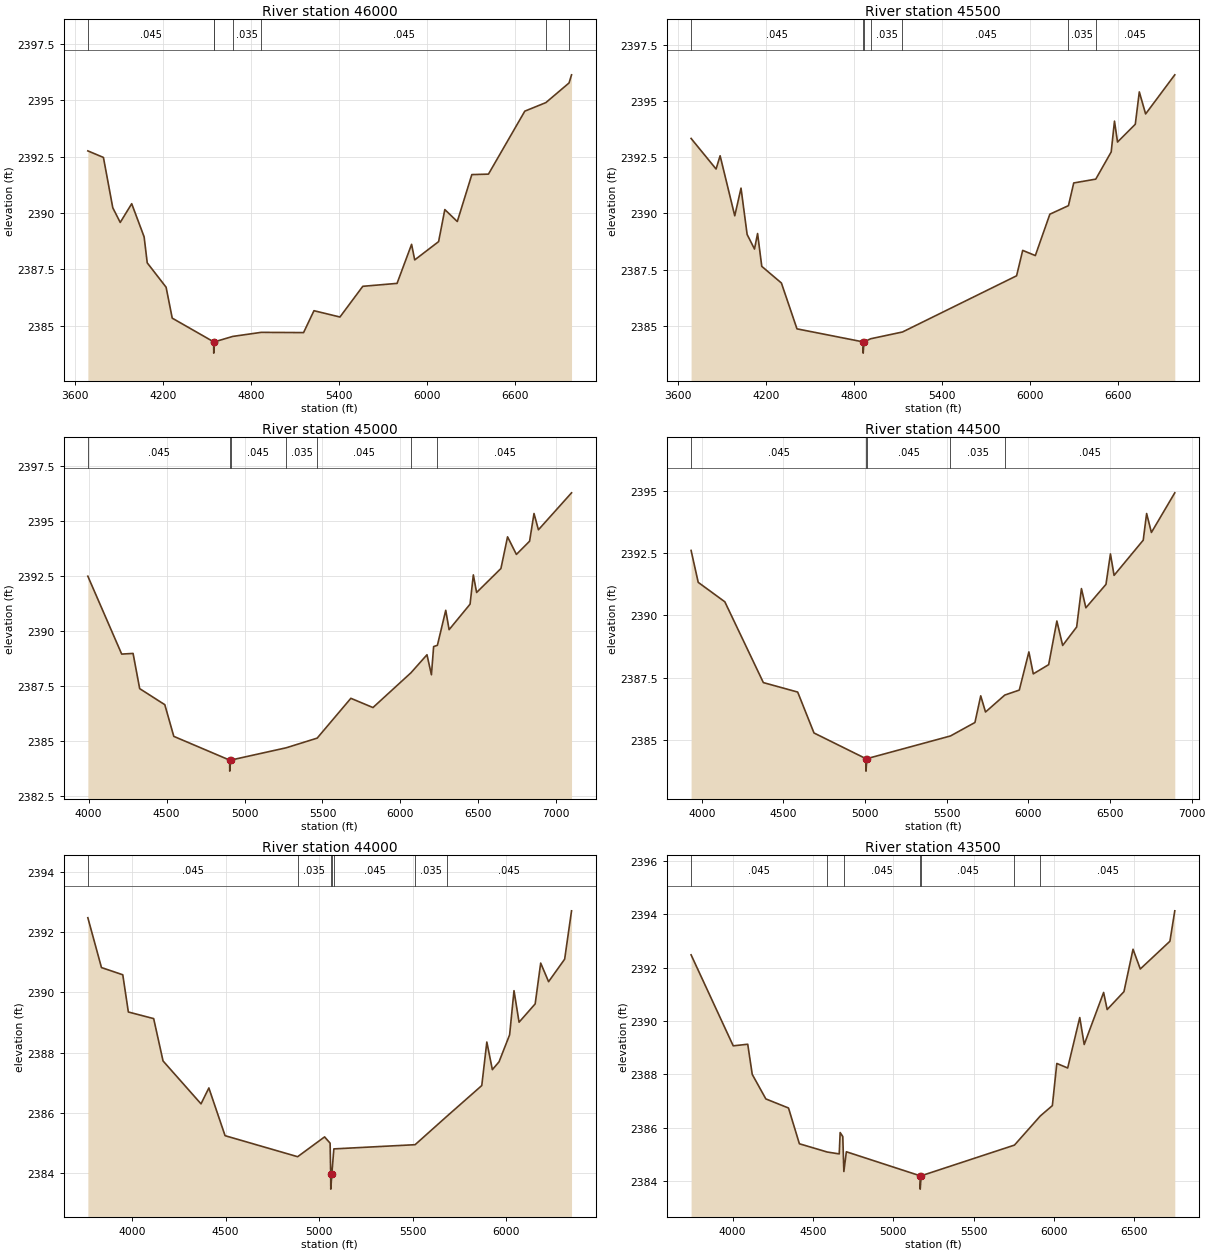
Type RM Length L Ch R = 1,46000,500,500,500
BEGIN DESCRIPTION:
Linn Creek Trib066 88.0
END DESCRIPTION:
XS GIS Cut Line= 3
      1312455.01      6886338.01      1311450.38      6885496.82
      1310054.99      6884087.99
#Sta/Elev= 30
  3689.7 2392.75  3795.8 2392.46  3859.5 2390.23  3910.2 2389.58  3988.3 2390.41
  4072.9 2388.94  4094.0 2387.79  4222.5 2386.71  4264.2 2385.34  4546.3 2384.29
  4546.8 2383.79  4551.9 2384.29  4676.3 2384.53  4869.9 2384.71  5158.5 2384.70
  5229.2 2385.67  5406.1 2385.39  5561.6 2386.75  5794.9 2386.88  5893.9 2388.61
  5915.1 2387.92  6077.8 2388.73  6120.2 2390.15  6205.1 2389.62  6304.1 2391.70
  6417.2 2391.72  6664.7 2394.51  6808.3 2394.89  6966.0 2395.76  6982.9 2396.12
#Mann=7,-1,0
  3689.7   0.045       0  4546.3   0.045       0  4551.9   0.045       0
  4676.3   0.035       0  4869.9   0.045       0  6808.3   0.035       0
  6966.0   0.045       0
Bank Sta=4546.3,4551.9
Exp/Cntr=0.3,0.1

Type RM Length L Ch R = 1,45500,500,500,500
BEGIN DESCRIPTION:
Linn Creek Trib066 87.0
END DESCRIPTION:
XS GIS Cut Line= 3
      1312554.99      6886337.98      1311704.59      6885337.59
      1310454.97      6883787.96
#Sta/Elev= 30
  3687.0 2393.33  3857.6 2391.97  3885.2 2392.56  3985.2 2389.89  4028.0 2391.12
  4069.7 2389.06  4120.1 2388.41  4141.1 2389.10  4169.7 2387.64  4303.8 2386.90
  4410.2 2384.86  4862.0 2384.28  4862.4 2383.78  4867.8 2384.28  4914.1 2384.42
  5130.8 2384.72  5910.2 2387.22  5951.9 2388.35  6038.2 2388.12  6137.4 2389.96
  6264.4 2390.34  6300.5 2391.35  6451.0 2391.52  6556.4 2392.73  6578.8 2394.10
  6599.6 2393.17  6720.9 2393.96  6748.4 2395.40  6791.5 2394.42  6990.7 2396.16
#Mann=7,-1,0
  3687.0   0.045       0  4862.0   0.035       0  4867.8   0.045       0
  4914.1   0.035       0  5130.8   0.045       0  6264.4   0.035       0
  6451.0   0.045       0
Bank Sta=4862,4867.8
Exp/Cntr=0.3,0.1

Type RM Length L Ch R = 1,45000,500,500,500
BEGIN DESCRIPTION:
Linn Creek Trib066 86.0
END DESCRIPTION:
XS GIS Cut Line= 3
      1312554.98      6886037.97      1312018.84      6885187.69
      1310605.02      6883638.02
#Sta/Elev= 30
  3994.8 2392.50  4211.9 2388.96  4284.9 2388.99  4327.3 2387.39  4488.5 2386.66
  4546.2 2385.22  4904.5 2384.14  4905.0 2383.64  4910.5 2384.14  5266.9 2384.70
  5465.9 2385.14  5682.0 2386.95  5823.8 2386.53  6067.5 2388.11  6170.4 2388.93
  6198.8 2388.02  6213.0 2389.30  6237.2 2389.36  6290.7 2390.95  6312.3 2390.07
  6446.8 2391.23  6467.7 2392.56  6488.7 2391.76  6644.7 2392.85  6687.3 2394.29
  6744.0 2393.49  6828.5 2394.09  6856.9 2395.35  6885.3 2394.61  7097.7 2396.29
#Mann=7,-1,0
  3994.8   0.045       0  4904.5   0.045       0  4910.5   0.045       0
  5266.9   0.035       0  5465.9   0.045       0  6067.5   0.035       0
  6237.2   0.045       0
Bank Sta=4904.5,4910.5
Exp/Cntr=0.3,0.1

Type RM Length L Ch R = 1,44500,500,500,500
BEGIN DESCRIPTION:
Linn Creek Trib066 85.0
END DESCRIPTION:
XS GIS Cut Line= 3
      1312755.01      6885888.02      1312335.44      6884908.39
      1310805.01      6883788.01
#Sta/Elev= 30
  3934.3 2392.60  3977.9 2391.32  4141.0 2390.54  4376.9 2387.30  4587.2 2386.92
  4687.0 2385.28  5004.9 2384.25  5005.4 2383.75  5011.0 2384.25  5522.8 2385.16
  5672.7 2385.70  5708.2 2386.77  5737.5 2386.12  5855.4 2386.80  5944.4 2387.00
  6003.1 2388.53  6030.1 2387.65  6124.3 2388.02  6174.5 2389.77  6210.0 2388.79
  6295.7 2389.53  6325.0 2391.07  6352.1 2390.30  6475.3 2391.24  6502.6 2392.46
  6524.9 2391.60  6703.3 2393.01  6724.2 2394.08  6753.5 2393.32  6896.7 2394.91
#Mann=5,-1,0
  3934.3   0.045       0  5004.9   0.045       0  5011.0   0.045       0
  5522.8   0.035       0  5855.4   0.045       0
Bank Sta=5004.9,5011
Exp/Cntr=0.3,0.1

Type RM Length L Ch R = 1,44000,500,500,500
BEGIN DESCRIPTION:
Linn Creek Trib066 84.0
END DESCRIPTION:
XS GIS Cut Line= 3
      1313154.98      6885587.97      1312454.81      6884568.56
      1311354.96      6883787.97
#Sta/Elev= 30
  3763.3 2392.49  3836.1 2390.83  3950.0 2390.59  3979.8 2389.35  4115.1 2389.13
  4165.2 2387.72  4368.2 2386.29  4410.1 2386.82  4496.8 2385.23  4884.7 2384.53
  5028.7 2385.19  5058.2 2384.98  5061.3 2383.95  5061.8 2383.45  5067.4 2383.95
  5078.2 2384.79  5512.5 2384.93  5683.1 2385.88  5868.9 2386.90  5895.9 2388.35
  5925.5 2387.43  5961.1 2387.69  6017.7 2388.59  6041.1 2390.06  6068.2 2389.01
  6154.3 2389.62  6183.8 2390.98  6226.0 2390.36  6311.9 2391.11  6348.7 2392.72
#Mann=7,-1,0
  3763.3   0.045       0  4884.7   0.035       0  5061.3   0.035       0
  5067.4   0.035       0  5078.2   0.045       0  5512.5   0.035       0
  5683.1   0.045       0
Bank Sta=5061.3,5067.4
Exp/Cntr=0.3,0.1

Type RM Length L Ch R = 1,43500,535,535,535
BEGIN DESCRIPTION:
Linn Creek Trib066 83.0
END DESCRIPTION:
XS GIS Cut Line= 3
      1313304.99      6885487.98      1312755.83      6884355.18
      1311204.96      6883537.98
#Sta/Elev= 30
  3741.1 2392.48  4003.5 2389.07  4093.8 2389.13  4121.9 2388.00  4206.6 2387.08
  4347.7 2386.74  4415.4 2385.40  4589.3 2385.09  4663.5 2385.02  4669.3 2385.82
  4685.7 2385.67  4692.3 2384.36  4707.9 2385.10  5167.2 2384.20  5167.7 2383.70
  5173.7 2384.20  5754.7 2385.35  5915.3 2386.44  5990.7 2386.83  6018.4 2388.41
  6086.1 2388.24  6161.3 2390.13  6189.0 2389.12  6309.8 2391.07  6331.9 2390.43
  6436.4 2391.10  6493.0 2392.69  6538.2 2391.95  6722.7 2392.99  6753.0 2394.13
#Mann=7,-1,0
  3741.1   0.045       0  4589.3   0.035       0  4692.3   0.045       0
  5167.2   0.045       0  5173.7   0.045       0  5754.7   0.035       0
  5915.3   0.045       0
Bank Sta=5167.2,5173.7
Exp/Cntr=0.3,0.1

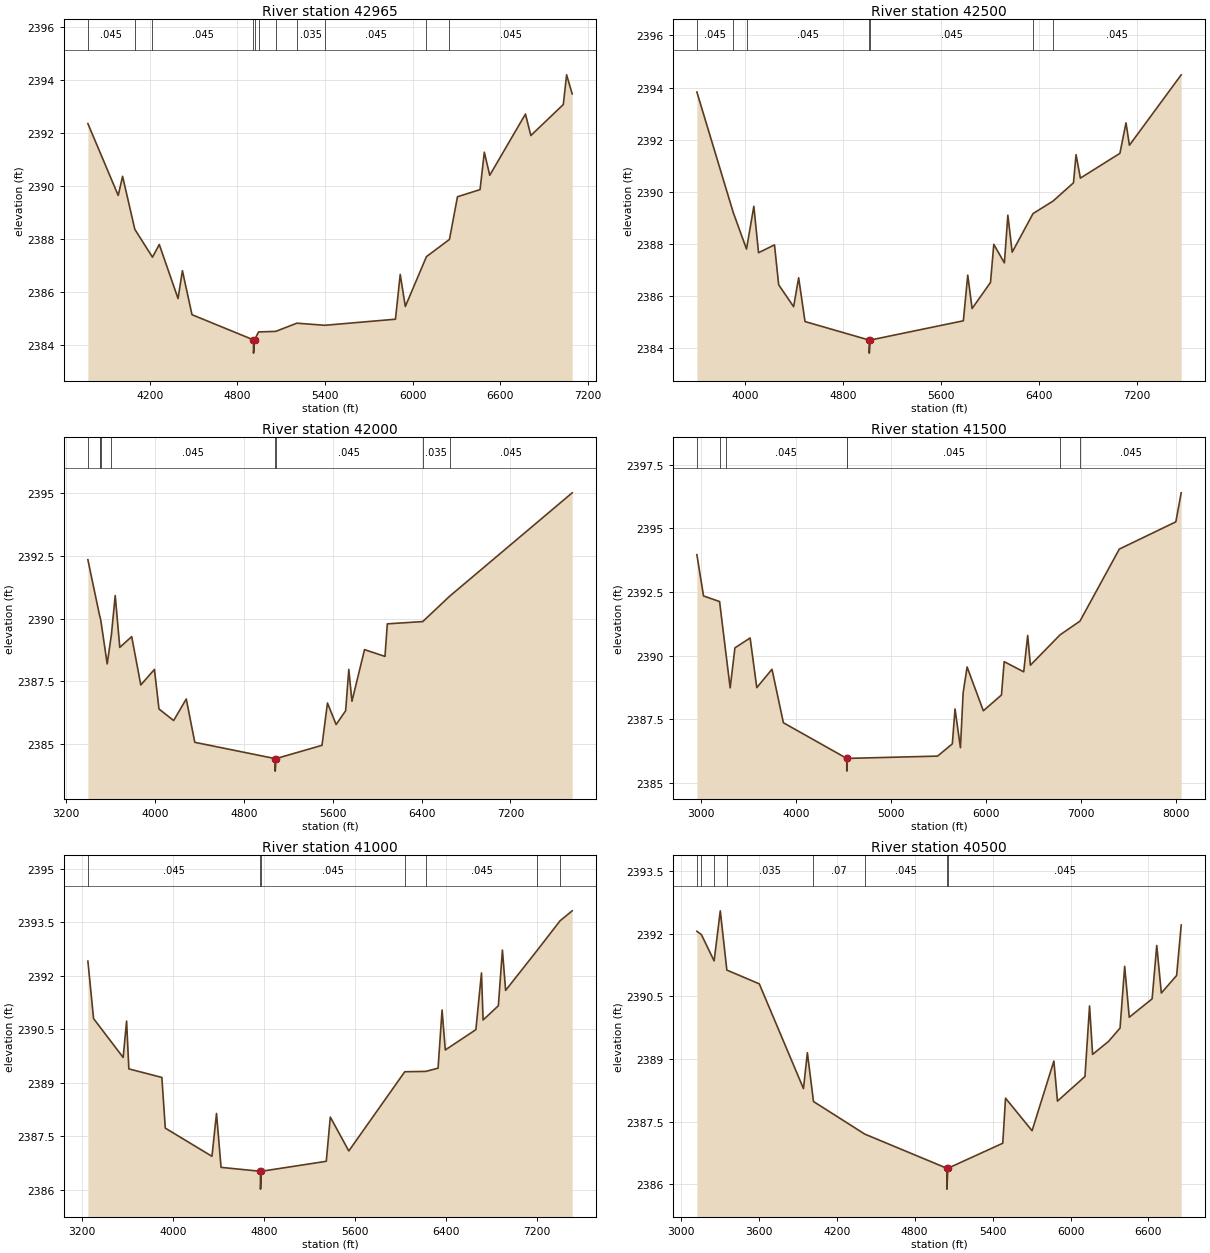
Type RM Length L Ch R = 1,42965,465,465,465
BEGIN DESCRIPTION:
Linn Creek Trib066 82.0
END DESCRIPTION:
XS GIS Cut Line= 4
      1313805.01      6885138.02      1313111.30      6884121.91
      1313053.21      6884053.72      1311281.00      6883131.10
#Sta/Elev= 30
  3775.3 2392.34  3983.2 2389.63  4013.1 2390.35  4097.0 2388.35  4217.9 2387.30
  4264.4 2387.78  4393.0 2385.74  4422.9 2386.79  4488.6 2385.13  4909.7 2384.18
  4910.2 2383.68  4917.0 2384.18  4944.5 2384.48  5062.0 2384.50  5207.0 2384.81
  5398.3 2384.73  5882.4 2384.96  5915.1 2386.65  5950.0 2385.44  6094.7 2387.32
  6252.4 2387.97  6307.3 2389.58  6462.0 2389.85  6491.2 2391.26  6528.3 2390.39
  6773.0 2392.70  6810.0 2391.89  7032.3 2393.06  7054.9 2394.18  7093.2 2393.46
#Mann=11,-1,0
  3775.3   0.045       0  4097.0   0.035       0  4217.9   0.045       0
  4909.7   0.035       0  4917.0   0.045       0  4944.5   0.035       0
  5062.0   0.045       0  5207.0   0.035       0  5398.3   0.045       0
  6094.7   0.035       0  6252.4   0.045       0
Bank Sta=4909.7,4917
Exp/Cntr=0.3,0.1

Type RM Length L Ch R = 1,42500,500,500,500
BEGIN DESCRIPTION:
Linn Creek Trib066 81.0
END DESCRIPTION:
XS GIS Cut Line= 3
      1313917.70      6885149.35      1313355.12      6883872.38
      1311291.85      6882349.86
#Sta/Elev= 30
  3604.6 2393.83  3902.0 2389.21  4010.3 2387.81  4070.3 2389.45  4108.7 2387.67
  4239.1 2387.97  4273.4 2386.44  4395.5 2385.60  4436.6 2386.71  4488.8 2385.03
  5013.6 2384.32  5014.1 2383.82  5021.0 2384.32  5783.1 2385.06  5819.2 2386.81
  5854.7 2385.53  6005.0 2386.53  6032.1 2387.99  6118.7 2387.28  6147.0 2389.11
  6182.4 2387.69  6352.8 2389.17  6516.5 2389.65  6683.6 2390.35  6704.5 2391.43
  6740.0 2390.53  7063.2 2391.48  7112.9 2392.65  7140.9 2391.79  7564.2 2394.49
#Mann=7,-1,0
  3604.6   0.045       0  3902.0   0.035       0  4010.3   0.045       0
  5013.6   0.045       0  5021.0   0.045       0  6352.8   0.035       0
  6516.5   0.045       0
Bank Sta=5013.6,5021
Exp/Cntr=0.3,0.1

Type RM Length L Ch R = 1,42000,500,500,500
BEGIN DESCRIPTION:
Linn Creek Trib066 80.0
END DESCRIPTION:
XS GIS Cut Line= 3
      1313906.83      6884986.52      1313511.95      6883431.17
      1311422.01      6881633.67
#Sta/Elev= 30
  3395.3 2392.35  3502.3 2390.09  3505.8 2390.06  3513.7 2389.87  3569.2 2388.19
  3607.5 2389.37  3641.4 2390.92  3682.7 2388.85  3789.9 2389.28  3871.8 2387.35
  3994.7 2387.97  4035.6 2386.39  4167.6 2385.93  4281.3 2386.79  4358.1 2385.06
  5081.8 2384.41  5082.3 2383.91  5089.2 2384.41  5503.5 2384.94  5552.9 2386.63
  5630.8 2385.77  5716.4 2386.32  5744.9 2387.97  5773.4 2386.70  5886.5 2388.76
  6070.8 2388.49  6091.7 2389.79  6410.8 2389.88  6654.9 2390.90  7756.6 2395.02
#Mann=9,-1,0
  3395.3   0.045       0  3502.3   0.035       0  3505.8   0.045       0
  3513.7   0.035       0  3607.5   0.045       0  5081.8   0.045       0
  5089.2   0.045       0  6410.8   0.035       0  6654.9   0.045       0
Bank Sta=5081.8,5089.2
Exp/Cntr=0.3,0.1

Type RM Length L Ch R = 1,41500,500,500,500
BEGIN DESCRIPTION:
Linn Creek Trib066 79.0
END DESCRIPTION:
XS GIS Cut Line= 3
      1313955.00      6885188.01      1313857.32      6883145.14
      1311554.99      6881137.99
#Sta/Elev= 30
  2954.8 2393.97  3024.9 2392.35  3193.8 2392.13  3262.0 2390.05  3305.2 2388.74
  3355.3 2390.31  3515.5 2390.70  3585.5 2388.75  3745.7 2389.47  3865.8 2387.37
  4532.7 2385.97  4533.2 2385.47  4540.6 2385.97  5488.8 2386.06  5644.5 2386.54
  5672.9 2387.91  5729.9 2386.39  5758.4 2388.55  5800.1 2389.56  5971.0 2387.84
  6161.9 2388.46  6190.3 2389.77  6396.1 2389.37  6438.1 2390.80  6466.6 2389.63
  6778.0 2390.82  6988.2 2391.36  7402.7 2394.19  7997.9 2395.26  8054.4 2396.40
#Mann=7,-1,0
  2954.8   0.045       0  3193.8   0.035       0  3262.0   0.045       0
  4532.7   0.045       0  4540.6   0.045       0  6778.0   0.035       0
  6988.2   0.045       0
Bank Sta=4532.7,4540.6
Exp/Cntr=0.3,0.1

Type RM Length L Ch R = 1,41000,500,500,500
BEGIN DESCRIPTION:
Linn Creek Trib066 78.0
END DESCRIPTION:
XS GIS Cut Line= 3
      1314255.00      6884538.02      1314162.99      6882789.04
      1312442.97      6880961.98
#Sta/Elev= 30
  3248.6 2392.41  3298.7 2390.80  3559.0 2389.71  3589.1 2390.73  3609.1 2389.39
  3899.5 2389.15  3929.6 2387.73  4340.1 2386.94  4380.2 2388.14  4420.2 2386.63
  4766.8 2386.52  4767.3 2386.02  4774.7 2386.52  5345.8 2386.80  5381.4 2388.04
  5544.0 2387.09  6036.4 2389.31  6221.8 2389.32  6329.4 2389.41  6364.5 2391.04
  6392.9 2389.92  6661.9 2390.49  6711.3 2392.08  6725.4 2390.76  6859.8 2391.16
  6895.4 2392.72  6923.7 2391.59  7203.3 2392.72  7402.3 2393.54  7509.3 2393.82
#Mann=7,-1,0
  3248.6   0.045       0  4766.8   0.045       0  4774.7   0.045       0
  6036.4    0.07       0  6221.8   0.045       0  7203.3   0.035       0
  7402.3   0.045       0
Bank Sta=4766.8,4774.7
Exp/Cntr=0.3,0.1

Type RM Length L Ch R = 1,40500,441,441,441
BEGIN DESCRIPTION:
Linn Creek Trib066 77.0
END DESCRIPTION:
XS GIS Cut Line= 3
      1314505.00      6884638.04      1314579.78      6882762.83
      1313605.00      6881188.00
#Sta/Elev= 30
  3123.3 2392.06  3158.1 2391.98  3256.0 2391.35  3303.5 2392.55  3353.9 2391.13
  3603.7 2390.80  3944.0 2388.29  3974.0 2389.15  4021.1 2387.98  4415.3 2387.20
  5047.8 2386.38  5048.3 2385.88  5055.7 2386.38  5478.3 2386.98  5499.6 2388.06
  5704.0 2387.28  5871.8 2388.95  5899.5 2387.99  6111.2 2388.58  6146.5 2390.27
  6170.0 2389.11  6292.5 2389.42  6381.2 2389.74  6417.0 2391.22  6452.2 2390.00
  6628.2 2390.44  6663.9 2391.72  6699.2 2390.58  6816.8 2391.00  6852.1 2392.21
#Mann=8,-1,0
  3123.3   0.035       0  3158.1   0.045       0  3256.0    0.07       0
  3353.9   0.035       0  4021.1    0.07       0  4415.3   0.045       0
  5047.8   0.045       0  5055.7   0.045       0
Bank Sta=5047.8,5055.7
Exp/Cntr=0.3,0.1

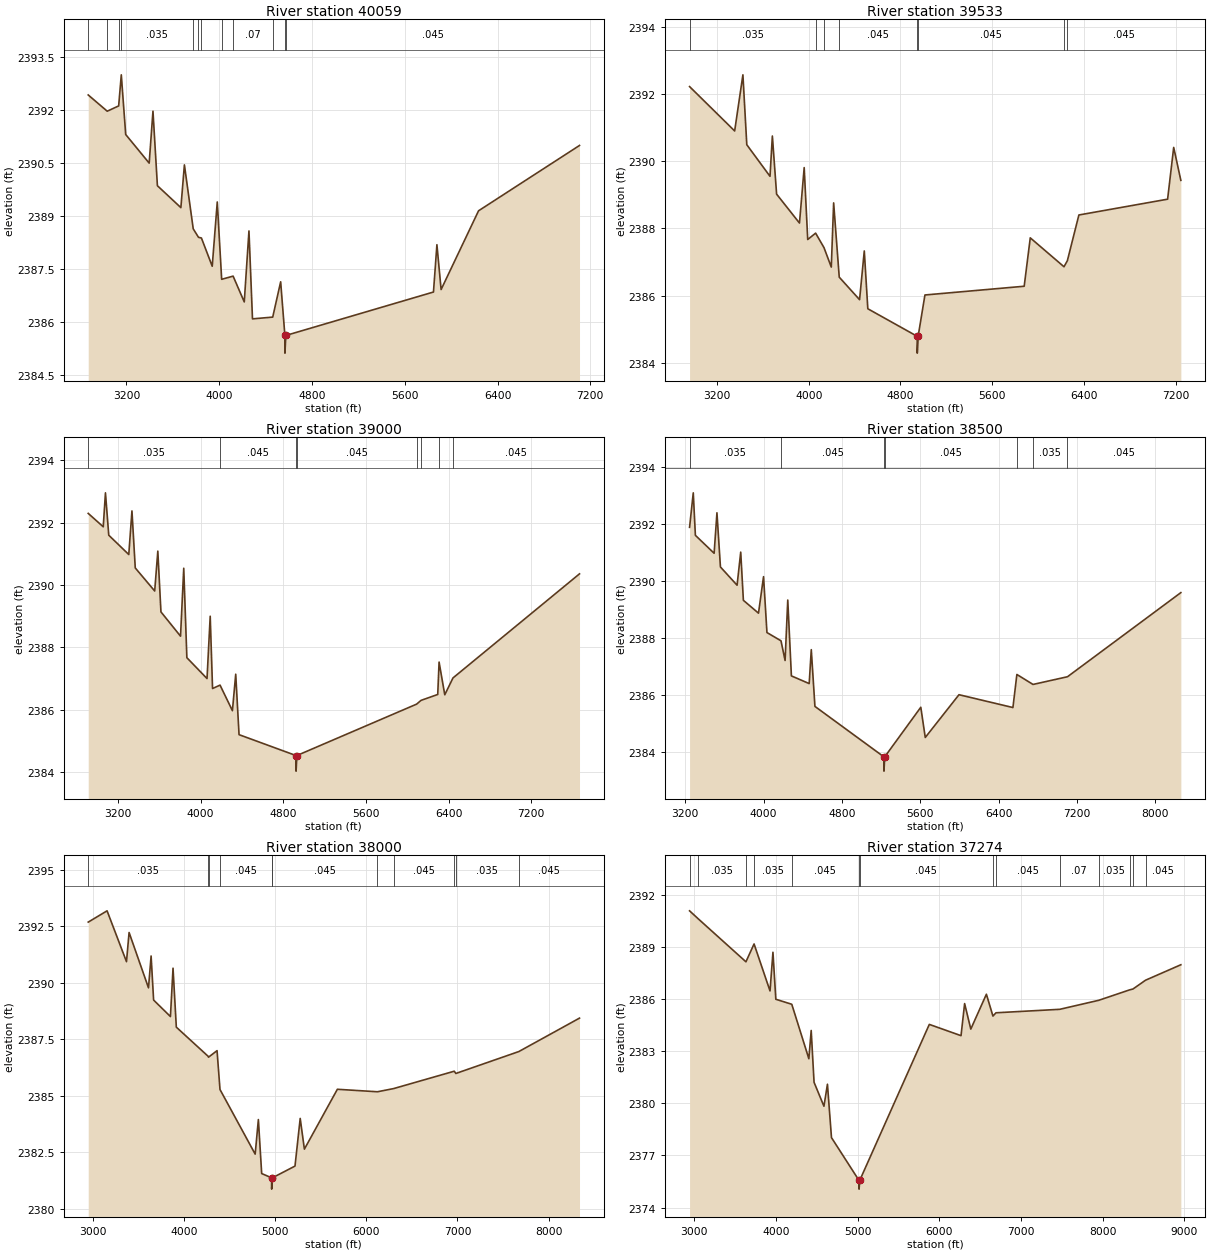
Type RM Length L Ch R = 1,40059,526,526,526
BEGIN DESCRIPTION:
Linn Creek Trib066 76.0
END DESCRIPTION:
XS GIS Cut Line= 3
      1314633.83      6884867.25      1314955.41      6882819.45
      1314156.39      6880809.00
#Sta/Elev= 30
  2870.7 2392.42  3034.5 2391.96  3133.2 2392.11  3155.8 2392.99  3193.9 2391.30
  3396.3 2390.49  3429.0 2391.96  3467.2 2389.85  3669.6 2389.23  3700.0 2390.44
  3776.1 2388.63  3821.3 2388.39  3846.8 2388.37  3939.9 2387.57  3983.4 2389.39
  4021.3 2387.20  4120.0 2387.29  4216.2 2386.56  4256.7 2388.57  4287.1 2386.08
  4461.6 2386.13  4530.0 2387.13  4566.5 2385.61  4567.0 2385.11  4574.5 2385.61
  5847.7 2386.84  5877.4 2388.18  5913.6 2386.91  6236.5 2389.14  7107.0 2390.99
#Mann=12,-1,0
  2870.7    0.07       0  3034.5   0.035       0  3133.2    0.07       0
  3155.8   0.035       0  3776.1    0.07       0  3821.3   0.035       0
  3846.8    0.07       0  4021.3   0.045       0  4120.0    0.07       0
  4461.6   0.045       0  4566.5   0.045       0  4574.5   0.045       0
Bank Sta=4566.5,4574.5
Exp/Cntr=0.3,0.1

Type RM Length L Ch R = 1,39533,533,533,533
BEGIN DESCRIPTION:
Linn Creek Trib066 75.0
END DESCRIPTION:
XS GIS Cut Line= 3
      1314796.60      6884910.57      1315254.53      6882957.67
      1314503.64      6880809.07
#Sta/Elev= 30
  2961.8 2392.22  3354.8 2390.90  3426.7 2392.57  3460.6 2390.49  3662.9 2389.55
  3683.4 2390.75  3720.4 2389.02  3919.7 2388.16  3960.8 2389.81  3991.6 2387.67
  4060.4 2387.86  4133.2 2387.43  4197.0 2386.85  4217.5 2388.76  4266.3 2386.55
  4443.5 2385.88  4484.6 2387.33  4515.4 2385.61  4945.9 2384.79  4946.4 2384.29
  4953.9 2384.79  5013.3 2386.02  5878.3 2386.28  5931.3 2387.72  6225.2 2386.86
  6254.6 2387.04  6355.0 2388.40  7128.3 2388.87  7181.3 2390.41  7243.7 2389.43
#Mann=8,-1,0
  2961.8   0.035       0  4060.4   0.045       0  4133.2   0.035       0
  4266.3   0.045       0  4945.9   0.045       0  4953.9   0.045       0
  6225.2    0.07       0  6254.6   0.045       0
Bank Sta=4945.9,4953.9
Exp/Cntr=0.3,0.1

Type RM Length L Ch R = 1,39000,500,500,500
BEGIN DESCRIPTION:
Linn Creek Trib066 74.0
END DESCRIPTION:
XS GIS Cut Line= 3
      1314883.39      6884954.03      1315617.44      6883000.59
      1314471.32      6880592.53
#Sta/Elev= 30
  2913.2 2392.30  3058.5 2391.87  3079.9 2392.96  3111.9 2391.60  3305.6 2390.98
  3336.3 2392.38  3368.3 2390.55  3556.3 2389.81  3586.6 2391.09  3616.8 2389.14
  3806.3 2388.36  3837.4 2390.54  3867.6 2387.67  4062.7 2387.00  4093.5 2389.00
  4116.1 2386.68  4188.7 2386.79  4308.4 2385.97  4340.4 2387.14  4372.5 2385.20
  4923.9 2384.53  4924.4 2384.03  4932.0 2384.53  6090.9 2386.18  6133.5 2386.30
  6295.1 2386.49  6308.1 2387.53  6363.2 2386.48  6442.6 2387.02  7666.9 2390.36
#Mann=8,-1,0
  2913.2   0.035       0  4188.7   0.045       0  4923.9   0.045       0
  4932.0   0.045       0  6090.9    0.07       0  6133.5   0.035       0
  6308.1    0.07       0  6442.6   0.045       0
Bank Sta=4923.9,4932
Exp/Cntr=0.3,0.1

Type RM Length L Ch R = 1,38500,500,500,500
BEGIN DESCRIPTION:
Linn Creek Trib066 73.0
END DESCRIPTION:
XS GIS Cut Line= 4
      1315002.77      6884888.88      1315892.78      6883375.95
      1315914.22      6883185.34      1314633.85      6880396.74
#Sta/Elev= 30
  3244.7 2391.88  3282.5 2393.09  3304.0 2391.60  3495.4 2390.97  3524.2 2392.39
  3559.8 2390.49  3729.7 2389.85  3766.9 2391.01  3794.1 2389.32  3948.4 2388.87
  3999.9 2390.15  4034.7 2388.19  4178.2 2387.90  4219.9 2387.21  4247.2 2389.33
  4284.3 2386.67  4465.9 2386.40  4487.3 2387.59  4524.5 2385.60  5228.9 2383.83
  5229.4 2383.33  5237.0 2383.83  5605.4 2385.57  5651.0 2384.51  5995.2 2386.01
  6545.9 2385.56  6586.3 2386.72  6751.1 2386.37  7103.0 2386.64  8260.3 2389.59
#Mann=7,-1,0
  3244.7   0.035       0  4178.2   0.045       0  5228.9   0.045       0
  5237.0   0.045       0  6586.3    0.07       0  6751.1   0.035       0
  7103.0   0.045       0
Bank Sta=5228.9,5237
Exp/Cntr=0.3,0.1

Type RM Length L Ch R = 1,38000,726,726,726
BEGIN DESCRIPTION:
Linn Creek Trib066 72.0
END DESCRIPTION:
XS GIS Cut Line= 3
      1314926.83      6885051.63      1316262.64      6883497.78
      1314872.83      6880462.43
#Sta/Elev= 30
  2950.9 2392.68  3157.6 2393.18  3370.5 2390.93  3399.0 2392.22  3611.9 2389.77
  3640.4 2391.18  3667.9 2389.23  3852.4 2388.50  3880.8 2390.64  3917.0 2388.03
  4266.0 2386.74  4269.8 2386.70  4363.6 2386.99  4395.9 2385.27  4781.7 2382.41
  4816.8 2383.94  4853.0 2381.55  4961.9 2381.36  4962.4 2380.86  4970.2 2381.36
  5218.4 2381.88  5275.4 2383.99  5321.4 2382.63  5683.0 2385.28  6122.5 2385.17
  6299.3 2385.31  6964.7 2386.08  6982.2 2385.98  7672.9 2386.95  8338.4 2388.43
#Mann=11,-1,0
  2950.9   0.035       0  4266.0   0.045       0  4269.8   0.035       0
  4395.9   0.045       0  4961.9   0.045       0  4970.2   0.045       0
  6122.5    0.07       0  6299.3   0.045       0  6964.7    0.07       0
  6982.2   0.035       0  7672.9   0.045       0
Bank Sta=4961.9,4970.2
Exp/Cntr=0.3,0.1

Type RM Length L Ch R = 1,37274,274,274,274
BEGIN DESCRIPTION:
Linn Creek Trib066 71.0
END DESCRIPTION:
XS GIS Cut Line= 3
      1315560.20      6885361.20      1316894.81      6883777.03
      1315014.43      6880311.41
#Sta/Elev= 30
  2943.2 2391.11  3044.4 2390.67  3633.4 2388.17  3732.7 2389.20  3928.1 2386.49
  3964.0 2388.72  3999.1 2386.01  4194.6 2385.72  4403.6 2382.58  4432.2 2384.21
  4467.3 2381.22  4588.2 2379.84  4631.1 2381.11  4680.6 2378.03  5017.7 2375.56
  5018.2 2375.06  5026.1 2375.56  5878.2 2384.56  6266.3 2383.91  6310.5 2385.76
  6386.1 2384.29  6577.1 2386.30  6657.1 2385.04  6694.6 2385.23  7475.3 2385.43
  7952.5 2385.95  8329.4 2386.55  8371.2 2386.60  8525.9 2387.11  8957.5 2388.00
#Mann=14,-1,0
  2943.2   0.045       0  3044.4   0.035       0  3633.4    0.07       0
  3732.7   0.035       0  4194.6   0.045       0  5017.7   0.045       0
  5026.1   0.045       0  6657.1    0.07       0  6694.6   0.045       0
  7475.3    0.07       0  7952.5   0.035       0  8329.4    0.07       0
  8371.2   0.035       0  8525.9   0.045       0
Bank Sta=5017.7,5026.1
Exp/Cntr=0.3,0.1