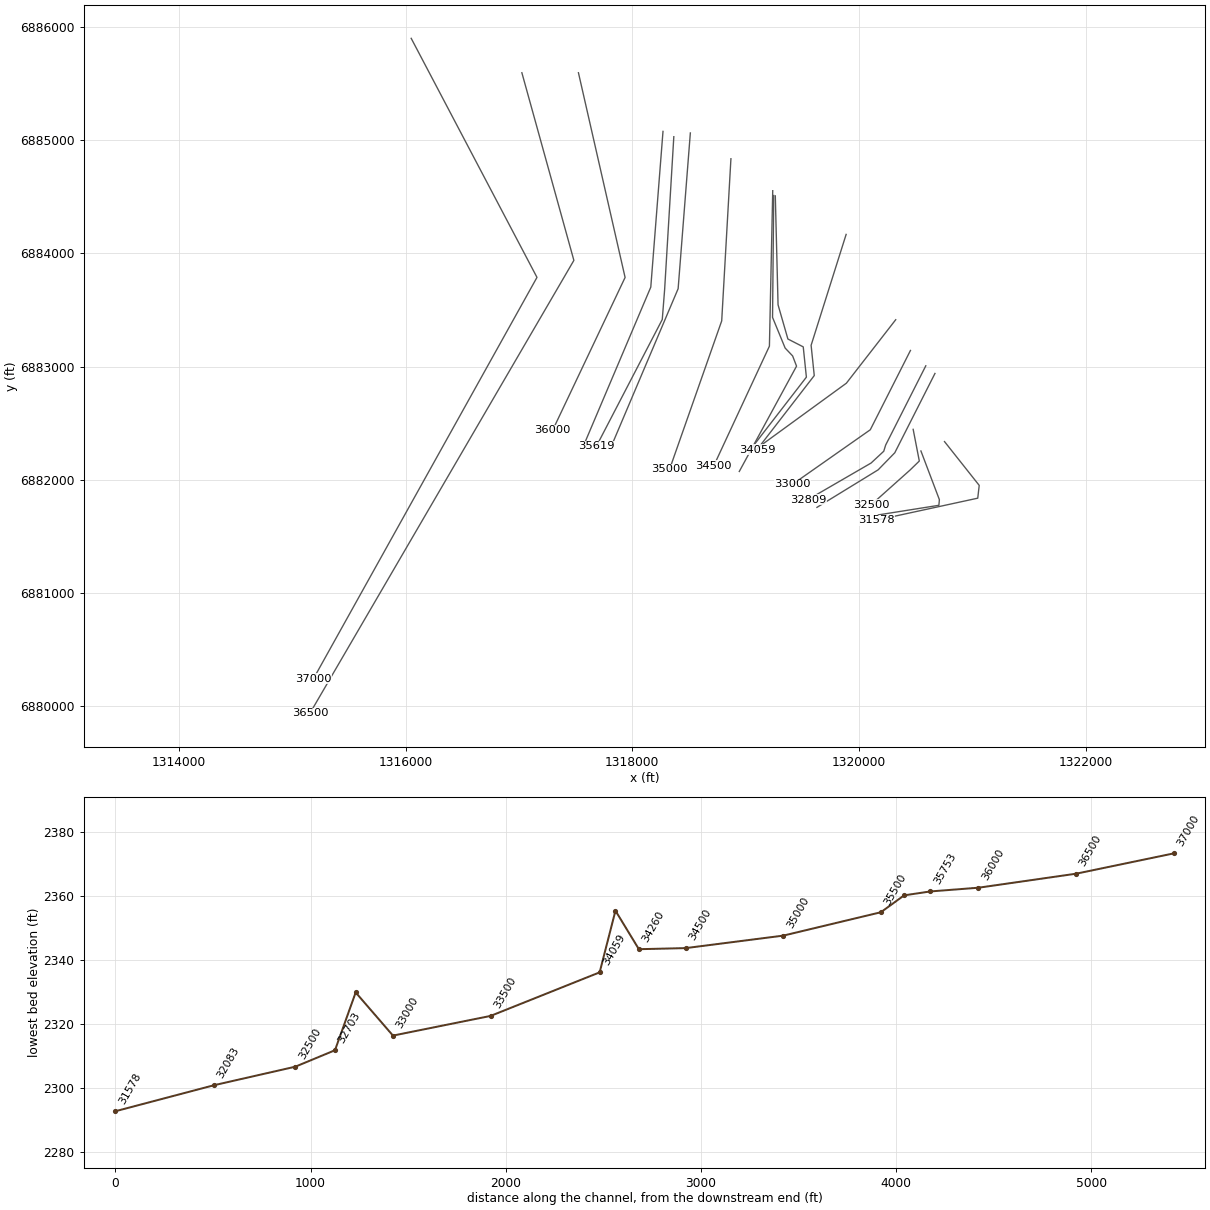
HEC-RAS study Linn Creek Trib066.prj: Linn Creek Trib066 Base Level Engineering

--- Linn Creek Trib066.g01 (geometry) --- (continued)

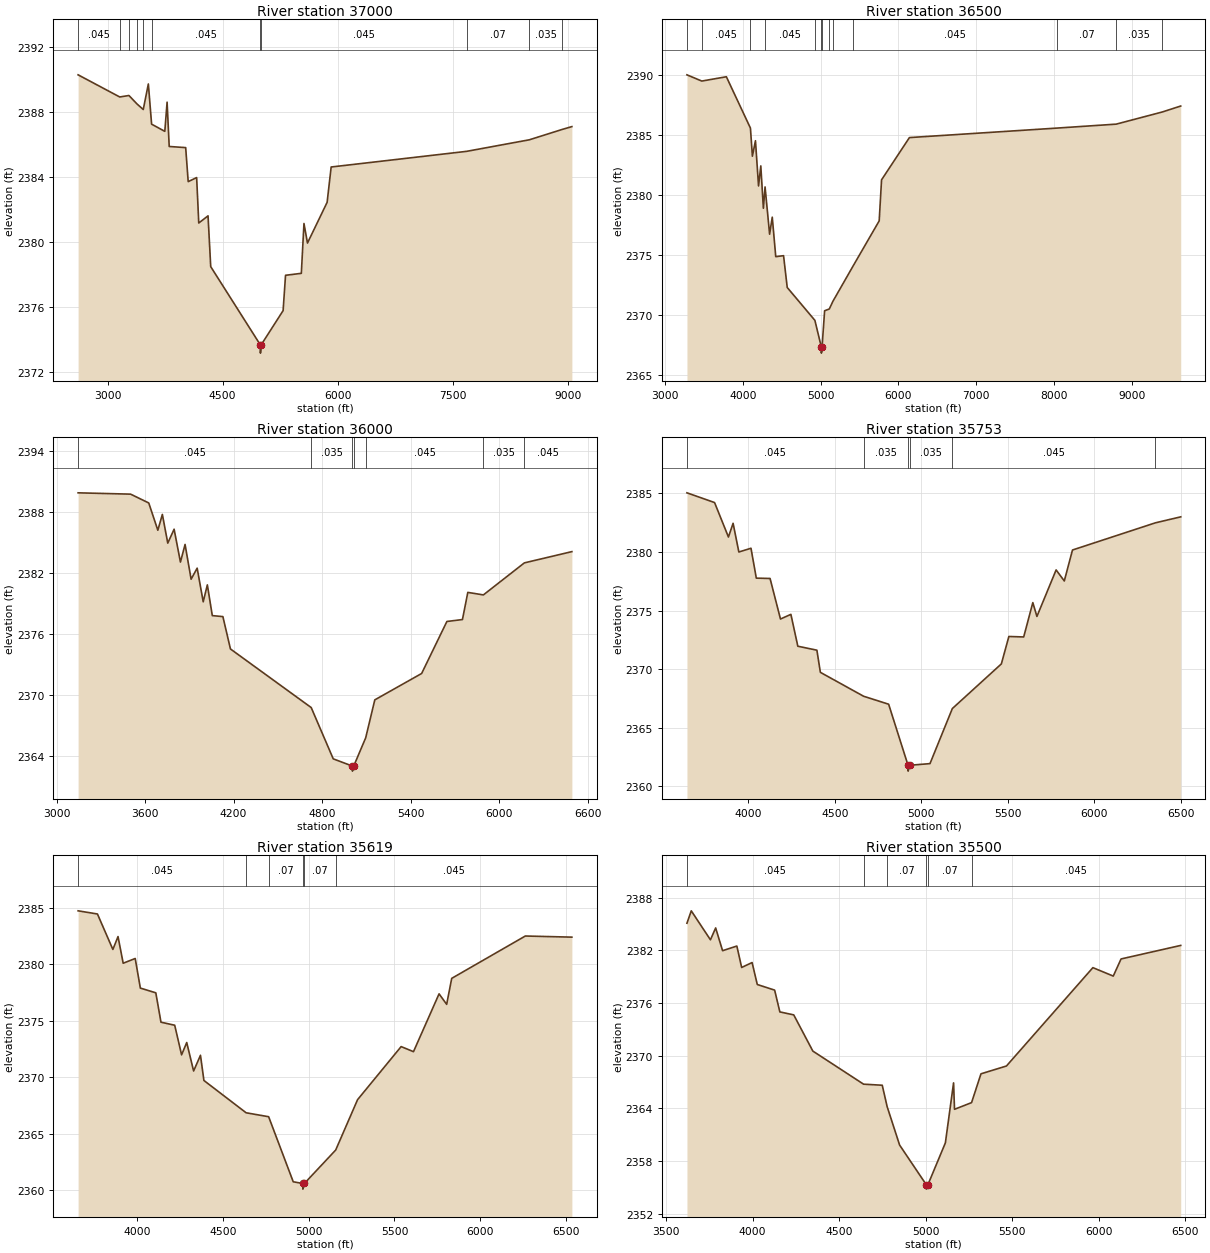
Type RM Length L Ch R = 1,37000,500,500,500
BEGIN DESCRIPTION:
Linn Creek Trib066 70.0
END DESCRIPTION:
XS GIS Cut Line= 3
      1316049.19      6885898.90      1317159.04      6883788.10
      1315187.22      6880244.80
#Sta/Elev= 30
  2615.2 2390.27  3158.1 2388.91  3278.2 2389.00  3383.6 2388.48  3464.9 2388.14
  3531.4 2389.71  3573.9 2387.24  3746.0 2386.80  3775.8 2388.59  3803.5 2385.87
  4018.2 2385.80  4051.0 2383.71  4161.2 2383.96  4188.9 2381.17  4309.9 2381.61
  4344.8 2378.49  4992.8 2373.68  4993.3 2373.18  5001.6 2373.68  5288.9 2375.79
  5320.5 2377.96  5526.5 2378.08  5560.9 2381.14  5606.7 2379.94  5862.9 2382.44
  5915.6 2384.61  7680.9 2385.57  8500.0 2386.28  8924.1 2386.91  9055.0 2387.09
#Mann=11,-1,0
  2615.2   0.045       0  3158.1   0.035       0  3278.2    0.07       0
  3383.6   0.035       0  3464.9    0.07       0  3573.9   0.045       0
  4992.8   0.045       0  5001.6   0.045       0  7680.9    0.07       0
  8500.0   0.035       0  8924.1   0.045       0
Bank Sta=4992.8,5001.6
Exp/Cntr=0.3,0.1

Type RM Length L Ch R = 1,36500,500,500,500
BEGIN DESCRIPTION:
Linn Creek Trib066 69.0
END DESCRIPTION:
XS GIS Cut Line= 3
      1317025.76      6885595.06      1317484.60      6883938.12
      1315155.02      6879938.04
#Sta/Elev= 30
  3280.7 2390.03  3471.7 2389.51  3787.5 2389.87  4097.0 2385.59  4122.1 2383.25
  4161.6 2384.54  4201.1 2380.77  4230.2 2382.44  4263.4 2378.91  4285.0 2380.69
  4343.5 2376.75  4377.5 2378.17  4422.5 2374.88  4522.8 2374.96  4570.0 2372.31
  4925.6 2369.57  5008.8 2367.34  5009.3 2366.84  5017.8 2367.34  5050.6 2370.37
  5111.1 2370.52  5157.4 2371.16  5410.5 2374.03  5752.3 2377.86  5782.7 2381.28
  6140.9 2384.80  8033.6 2385.59  8798.9 2385.92  9390.2 2386.93  9629.0 2387.43
#Mann=13,-1,0
  3280.7   0.035       0  3471.7   0.045       0  4097.0   0.035       0
  4285.0   0.045       0  4925.6   0.035       0  5008.8   0.035       0
  5017.8   0.035       0  5111.1   0.045       0  5157.4   0.035       0
  5410.5   0.045       0  8033.6    0.07       0  8798.9   0.035       0
  9390.2   0.045       0
Bank Sta=5008.8,5017.8
Exp/Cntr=0.3,0.1

Type RM Length L Ch R = 1,36000,247,247,247
BEGIN DESCRIPTION:
Linn Creek Trib066 68.0
END DESCRIPTION:
XS GIS Cut Line= 3
      1317524.89      6885595.08      1317936.54      6883787.35
      1317297.02      6882437.48
#Sta/Elev= 30
  3146.0 2389.92  3502.0 2389.79  3625.0 2388.92  3686.6 2386.23  3717.3 2387.79
  3753.9 2384.96  3796.9 2386.33  3839.9 2383.09  3871.2 2384.83  3912.2 2381.40
  3953.2 2382.49  3994.2 2379.17  4022.3 2380.84  4055.8 2377.81  4127.6 2377.71
  4178.9 2374.52  4726.4 2368.74  4875.8 2363.68  5005.4 2362.97  5005.9 2362.47
  5014.7 2362.97  5095.9 2365.76  5157.6 2369.50  5475.1 2372.10  5646.3 2377.23
  5751.7 2377.42  5788.2 2380.10  5893.7 2379.85  6171.5 2383.01  6493.7 2384.12
#Mann=7,-1,0
  3146.0   0.045       0  4726.4   0.035       0  5005.4   0.035       0
  5014.7   0.035       0  5095.9   0.045       0  5893.7   0.035       0
  6171.5   0.045       0
Bank Sta=5005.4,5014.7
Exp/Cntr=0.3,0.1

Type RM Length L Ch R = 1,35753,134,134,134
BEGIN DESCRIPTION:
Linn Creek Trib066 67.6
END DESCRIPTION:
XS GIS Cut Line= 3
      1318270.99      6885077.25      1318163.25      6883701.97
      1317587.41      6882342.92
#Sta/Elev= 30
  3645.3 2385.05  3805.0 2384.22  3885.3 2381.28  3912.2 2382.45  3945.5 2380.00
  4015.7 2380.32  4046.4 2377.77  4126.0 2377.74  4186.2 2374.28  4246.4 2374.68
  4286.5 2371.96  4396.8 2371.62  4416.9 2369.73  4667.0 2367.69  4811.7 2367.01
  4923.8 2361.80  4924.3 2361.30  4933.1 2361.80  5050.8 2361.94  5180.1 2366.64
  5463.5 2370.45  5507.0 2372.79  5592.7 2372.75  5645.5 2375.68  5669.2 2374.50
  5780.2 2378.47  5827.5 2377.53  5874.9 2380.17  6354.4 2382.49  6500.8 2383.00
#Mann=6,-1,0
  3645.3   0.045       0  4667.0   0.035       0  4923.8   0.035       0
  4933.1   0.035       0  5180.1   0.045       0  6354.4   0.035       0
Bank Sta=4923.8,4933.1
Exp/Cntr=0.3,0.1

Type RM Length L Ch R = 1,35619,119,119,119
BEGIN DESCRIPTION:
Linn Creek Trib066 67.5
END DESCRIPTION:
XS GIS Cut Line= 4
      1318366.47      6885030.39      1318285.39      6883680.16
      1318264.56      6883416.27      1317682.90      6882296.05
#Sta/Elev= 30
  3655.0 2384.72  3767.8 2384.44  3857.8 2381.30  3887.8 2382.44  3917.9 2380.08
  3988.0 2380.50  4018.0 2377.88  4108.2 2377.46  4138.3 2374.86  4218.4 2374.59
  4258.5 2371.97  4288.5 2373.06  4328.6 2370.54  4368.7 2371.93  4388.7 2369.70
  4634.8 2366.84  4766.2 2366.49  4909.6 2360.73  4965.1 2360.58  4965.6 2360.08
  4974.4 2360.58  5157.2 2363.54  5284.8 2368.00  5538.9 2372.70  5610.9 2372.25
  5760.1 2377.37  5804.4 2376.44  5833.8 2378.74  6263.2 2382.49  6534.6 2382.39
#Mann=6,-1,0
  3655.0   0.045       0  4634.8   0.035       0  4766.2    0.07       0
  4965.1    0.07       0  4974.4    0.07       0  5157.2   0.045       0
Bank Sta=4965.1,4974.4
Exp/Cntr=0.3,0.1

Type RM Length L Ch R = 1,35500,500,500,500
BEGIN DESCRIPTION:
Linn Creek Trib066 67.0
END DESCRIPTION:
XS GIS Cut Line= 3
      1318512.31      6885063.37      1318404.57      6883688.08
      1317829.36      6882330.52
#Sta/Elev= 30
  3620.5 2385.09  3645.5 2386.50  3756.3 2383.20  3786.4 2384.55  3826.5 2381.96
  3908.9 2382.49  3936.8 2380.05  3997.0 2380.61  4027.1 2378.11  4127.4 2377.47
  4157.4 2374.99  4237.8 2374.65  4348.1 2370.53  4641.4 2366.76  4749.3 2366.64
  4777.5 2364.21  4849.6 2359.83  5003.9 2355.31  5004.4 2354.81  5013.3 2355.31
  5114.2 2360.08  5161.5 2366.91  5167.0 2363.90  5265.5 2364.66  5319.9 2367.94
  5467.1 2368.83  5966.7 2380.03  6084.5 2379.07  6129.6 2381.02  6474.4 2382.56
#Mann=6,-1,0
  3620.5   0.045       0  4641.4   0.035       0  4777.5    0.07       0
  5003.9    0.07       0  5013.3    0.07       0  5265.5   0.045       0
Bank Sta=5003.9,5013.3
Exp/Cntr=0.3,0.1

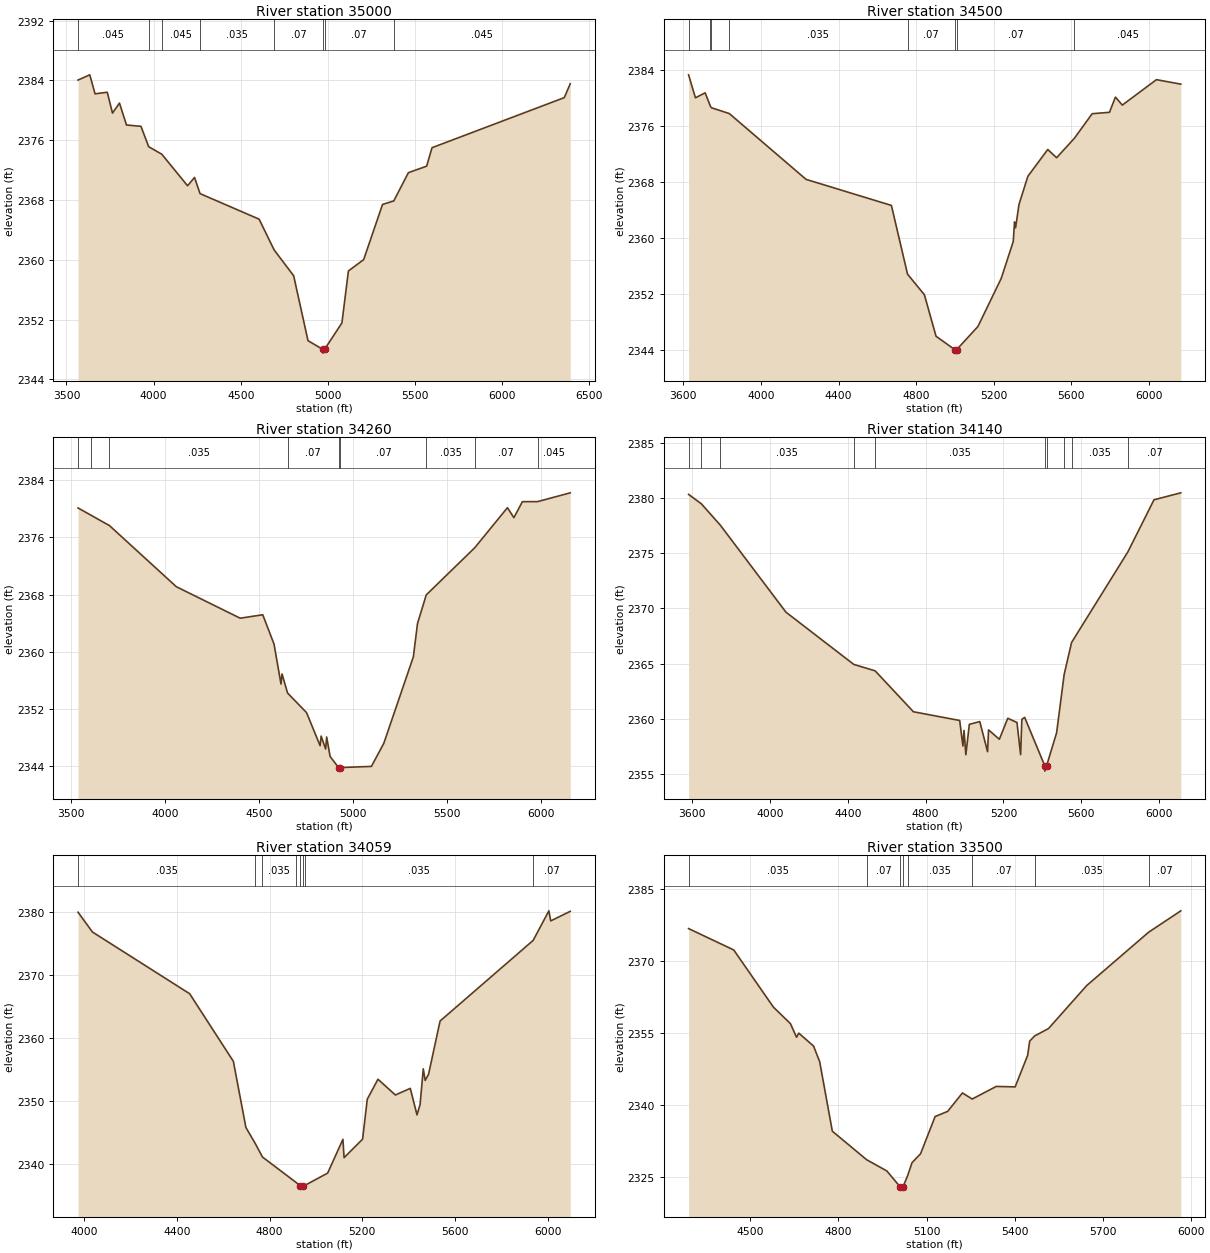
Type RM Length L Ch R = 1,35000,500,500,500
BEGIN DESCRIPTION:
Linn Creek Trib066 66.0
END DESCRIPTION:
XS GIS Cut Line= 3
      1318870.38      6884835.53      1318789.03      6883404.03
      1318328.32      6882091.65
#Sta/Elev= 30
  3566.2 2384.04  3633.8 2384.74  3663.9 2382.20  3734.0 2382.41  3764.0 2379.62
  3804.1 2380.96  3844.2 2378.03  3927.4 2377.85  3971.8 2375.12  4047.0 2374.12
  4194.7 2369.90  4234.8 2371.01  4266.4 2368.85  4605.4 2365.43  4691.2 2361.33
  4803.7 2357.86  4885.9 2349.18  4971.1 2348.01  4971.6 2347.51  4980.9 2348.01
  5080.6 2351.55  5117.8 2358.50  5205.4 2360.02  5313.7 2367.40  5378.2 2367.87
  5462.1 2371.65  5566.8 2372.52  5597.7 2374.99  6356.7 2381.69  6390.9 2383.55
#Mann=8,-1,0
  3566.2   0.045       0  3971.8   0.035       0  4047.0   0.045       0
  4266.4   0.035       0  4691.2    0.07       0  4971.1    0.07       0
  4980.9    0.07       0  5378.2   0.045       0
Bank Sta=4971.1,4980.9
Exp/Cntr=0.3,0.1

Type RM Length L Ch R = 1,34500,240,240,240
BEGIN DESCRIPTION:
Linn Creek Trib066 65.0
END DESCRIPTION:
XS GIS Cut Line= 3
      1319239.31      6884553.43      1319210.01      6883180.84
      1318719.27      6882124.57
#Sta/Elev= 30
  3627.1 2383.33  3662.5 2380.05  3712.5 2380.76  3739.1 2378.89  3744.4 2378.64
  3837.1 2377.80  4232.7 2368.41  4672.8 2364.69  4755.9 2354.88  4842.8 2351.94
  4902.8 2346.02  4999.4 2344.11  4999.9 2343.61  5009.3 2344.11  5118.8 2347.41
  5238.8 2354.27  5300.8 2359.53  5307.5 2362.34  5313.0 2361.50  5330.4 2364.81
  5376.1 2368.84  5478.7 2372.67  5524.5 2371.50  5616.5 2374.29  5707.7 2377.78
  5797.0 2377.98  5827.7 2380.15  5863.2 2379.01  6039.2 2382.64  6164.7 2382.00
#Mann=8,-1,0
  3627.1    0.07       0  3739.1   0.045       0  3744.4    0.07       0
  3837.1   0.035       0  4755.9    0.07       0  4999.4    0.07       0
  5009.3    0.07       0  5616.5   0.045       0
Bank Sta=4999.4,5009.3
Exp/Cntr=0.3,0.1

Type RM Length L Ch R = 1,34260,120,120,120
BEGIN DESCRIPTION:
Linn Creek Trib066 64.6
END DESCRIPTION:
XS GIS Cut Line= 6
      1319248.06      6884511.18      1319237.65      6883434.79
      1319348.76      6883163.96      1319414.73      6883094.51
      1319449.45      6883004.24      1318944.16      6882074.23
#Sta/Elev= 30
  3538.2 2380.13  3607.6 2379.11  3705.6 2377.66  4061.4 2369.10  4401.4 2364.69
  4521.4 2365.17  4581.4 2361.08  4618.7 2355.47  4624.1 2356.88  4653.6 2354.21
  4754.8 2351.46  4826.8 2346.83  4832.2 2348.18  4856.2 2346.37  4861.6 2348.05
  4880.1 2345.32  4925.0 2343.77  4925.5 2343.27  4935.0 2343.77  5099.9 2343.93
  5165.6 2347.15  5323.2 2359.28  5345.2 2363.94  5391.7 2367.95  5650.0 2374.56
  5824.0 2380.17  5858.3 2378.77  5903.6 2381.01  5984.5 2381.02  6158.3 2382.25
#Mann=9,-1,0
  3538.2    0.07       0  3607.6   0.045       0  3705.6   0.035       0
  4653.6    0.07       0  4925.0    0.07       0  4935.0    0.07       0
  5391.7   0.035       0  5650.0    0.07       0  5984.5   0.045       0
Bank Sta=4925,4935
Exp/Cntr=0.3,0.1

Type RM Length L Ch R = 1,34140,81,81,81
BEGIN DESCRIPTION:
Linn Creek Trib066 64.5
END DESCRIPTION:
XS GIS Cut Line= 6
      1319261.95      6884507.66      1319286.26      6883545.90
      1319373.06      6883243.82      1319508.48      6883174.37
      1319536.26      6882907.01      1319028.81      6882250.03
#Sta/Elev= 30
  3583.0 2380.32  3648.5 2379.47  3746.3 2377.53  4082.8 2369.67  4431.4 2364.94
  4541.0 2364.36  4737.5 2360.66  4975.1 2359.87  4991.7 2357.56  4997.3 2358.97
  5006.8 2356.77  5024.6 2359.52  5078.3 2359.77  5118.3 2357.05  5123.3 2359.02
  5178.8 2358.17  5221.9 2360.07  5269.3 2359.69  5288.0 2356.78  5294.3 2359.97
  5308.8 2360.15  5411.6 2355.79  5412.1 2355.29  5421.6 2355.79  5472.8 2358.76
  5511.6 2364.03  5549.5 2366.92  5838.8 2375.12  5972.7 2379.83  6110.5 2380.46
#Mann=10,-1,0
  3583.0    0.07       0  3648.5   0.045       0  3746.3   0.035       0
  4431.4    0.07       0  4541.0   0.035       0  5411.6   0.035       0
  5421.6   0.035       0  5511.6    0.07       0  5549.5   0.035       0
  5838.8    0.07       0
Bank Sta=5411.6,5421.6
Exp/Cntr=0.3,0.1

Type RM Length L Ch R = 1,34059,559,559,559
BEGIN DESCRIPTION:
Linn Creek Trib066 64.0
END DESCRIPTION:
XS GIS Cut Line= 4
      1319886.96      6884167.46      1319577.93      6883188.26
      1319605.70      6882920.90      1319099.14      6882265.06
#Sta/Elev= 30
  3973.0 2379.96  4035.3 2376.82  4454.8 2367.03  4643.5 2356.30  4697.5 2345.82
  4738.1 2343.26  4769.1 2341.13  4914.5 2337.09  4932.2 2336.54  4932.7 2336.04
  4942.2 2336.54  4954.6 2336.69  5050.3 2338.58  5116.2 2343.94  5121.2 2341.03
  5201.1 2343.96  5221.3 2350.30  5267.5 2353.47  5342.6 2350.97  5406.9 2352.02
  5435.9 2347.82  5449.2 2349.46  5463.0 2355.12  5471.2 2353.28  5485.7 2354.24
  5535.5 2362.70  5937.2 2375.49  6005.1 2380.18  6012.8 2378.58  6097.3 2380.10
#Mann=8,-1,0
  3973.0   0.035       0  4738.1    0.07       0  4769.1   0.035       0
  4914.5    0.07       0  4932.2   0.035       0  4942.2    0.07       0
  4954.6   0.035       0  5937.2    0.07       0
Bank Sta=4932.2,4942.2
Exp/Cntr=0.3,0.1

Type RM Length L Ch R = 1,33500,500,500,500
BEGIN DESCRIPTION:
Linn Creek Trib066 63.0
END DESCRIPTION:
XS GIS Cut Line= 3
      1320324.40      6883414.10      1319888.99      6882853.54
      1319109.56      6882285.94
#Sta/Elev= 30
  4290.2 2376.71  4443.8 2372.26  4578.7 2360.35  4636.6 2356.91  4657.4 2354.07
  4665.1 2354.93  4715.3 2352.23  4736.1 2348.97  4779.1 2334.50  4895.9 2328.55
  4964.2 2326.23  5009.5 2322.93  5010.0 2322.43  5019.6 2322.93  5034.8 2325.16
  5050.1 2327.94  5079.2 2329.80  5128.6 2337.55  5171.4 2338.63  5221.6 2342.47
  5254.8 2341.20  5336.7 2343.83  5400.8 2343.73  5443.3 2350.29  5450.3 2353.26
  5467.1 2354.34  5514.4 2355.89  5644.2 2364.84  5854.5 2375.94  5964.2 2380.41
#Mann=8,-1,0
  4290.2   0.035       0  4895.9    0.07       0  5009.5    0.07       0
  5019.6    0.07       0  5034.8   0.035       0  5254.8    0.07       0
  5467.1   0.035       0  5854.5    0.07       0
Bank Sta=5009.5,5019.6
Exp/Cntr=0.3,0.1

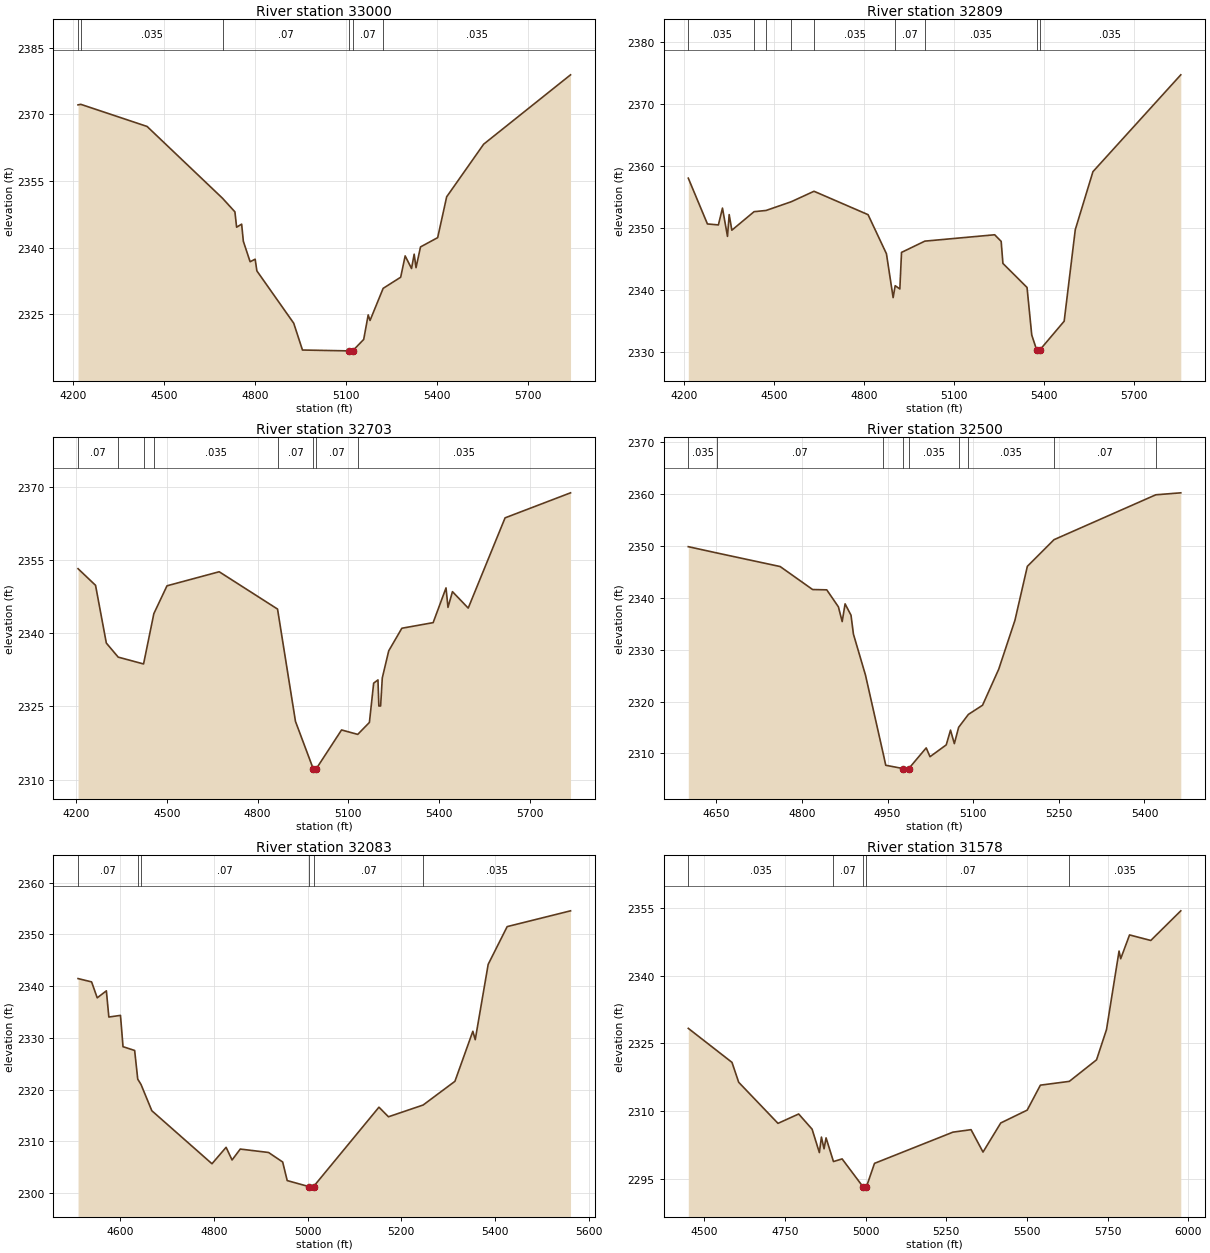
Type RM Length L Ch R = 1,33000,191,191,191
BEGIN DESCRIPTION:
Linn Creek Trib066 62.0
END DESCRIPTION:
XS GIS Cut Line= 3
      1320454.60      6883142.83      1320100.18      6882442.51
      1319412.90      6881960.07
#Sta/Elev= 30
  4215.1 2372.16  4224.2 2372.28  4442.9 2367.30  4691.7 2351.14  4732.6 2348.08
  4738.2 2344.63  4754.8 2345.32  4760.4 2341.46  4782.7 2336.86  4799.4 2337.43
  4805.0 2334.80  4926.6 2323.02  4955.4 2316.99  5110.5 2316.79  5111.0 2316.29
  5120.7 2316.79  5157.4 2319.37  5172.2 2324.89  5178.3 2323.64  5221.6 2330.87
  5279.4 2333.37  5294.2 2338.17  5315.2 2335.33  5323.9 2338.56  5330.0 2335.52
  5344.8 2340.19  5401.4 2342.28  5431.1 2351.47  5553.1 2363.31  5839.7 2378.92
#Mann=6,-1,0
  4215.1    0.07       0  4224.2   0.035       0  4691.7    0.07       0
  5110.5    0.07       0  5120.7    0.07       0  5221.6   0.035       0
Bank Sta=5110.5,5120.7
Exp/Cntr=0.3,0.1

Type RM Length L Ch R = 1,32809,106,106,106
BEGIN DESCRIPTION:
Linn Creek Trib066 61.6
END DESCRIPTION:
XS GIS Cut Line= 5
      1320589.98      6883007.36      1320235.60      6882307.09
      1320218.94      6882252.72      1320106.96      6882148.55
      1319549.17      6881825.15
#Sta/Elev= 30
  4215.4 2358.04  4279.1 2350.64  4315.6 2350.48  4329.2 2353.20  4345.9 2348.63
  4351.5 2352.15  4360.4 2349.63  4434.3 2352.62  4474.5 2352.82  4558.2 2354.23
  4633.9 2355.92  4813.8 2352.14  4875.0 2345.82  4897.3 2338.73  4904.1 2340.66
  4919.6 2340.13  4925.2 2346.04  5002.8 2347.86  5235.3 2348.89  5256.9 2347.82
  5262.7 2344.26  5343.0 2340.37  5358.7 2332.68  5375.2 2330.26  5375.7 2329.76
  5385.4 2330.26  5466.6 2334.92  5503.6 2349.72  5562.4 2359.09  5854.8 2374.74
#Mann=9,-1,0
  4215.4   0.035       0  4434.3    0.07       0  4474.5   0.035       0
  4558.2    0.07       0  4633.9   0.035       0  4904.1    0.07       0
  5002.8   0.035       0  5375.2    0.07       0  5385.4   0.035       0
Bank Sta=5375.2,5385.4
Exp/Cntr=0.3,0.1

Type RM Length L Ch R = 1,32703,203,203,203
BEGIN DESCRIPTION:
Linn Creek Trib066 61.5
END DESCRIPTION:
XS GIS Cut Line= 4
      1320670.71      6882939.65      1320316.32      6882239.38
      1320169.46      6882088.65      1319629.54      6881757.25
#Sta/Elev= 30
  4206.2 2353.22  4264.1 2349.81  4299.8 2337.97  4339.0 2335.09  4422.9 2333.69
  4456.9 2344.00  4500.4 2349.71  4673.0 2352.59  4866.0 2344.94  4925.3 2321.92
  4983.9 2312.22  4984.4 2311.72  4994.2 2312.22  5077.7 2320.16  5131.2 2319.25
  5169.8 2321.70  5183.9 2329.75  5198.1 2330.42  5201.1 2325.07  5206.9 2325.07
  5212.4 2330.82  5233.7 2336.38  5277.1 2341.01  5380.6 2342.16  5423.2 2349.28
  5429.7 2345.29  5444.5 2348.51  5496.6 2345.14  5618.5 2363.64  5835.0 2368.77
#Mann=8,-1,0
  4206.2    0.07       0  4339.0   0.035       0  4422.9    0.07       0
  4456.9   0.035       0  4866.0    0.07       0  4983.9    0.07       0
  4994.2    0.07       0  5131.2   0.035       0
Bank Sta=4983.9,4994.2
Exp/Cntr=0.3,0.1

Type RM Length L Ch R = 1,32500,417,417,417
BEGIN DESCRIPTION:
Linn Creek Trib066 61.0
END DESCRIPTION:
XS GIS Cut Line= 4
      1320478.46      6882446.18      1320532.67      6882166.28
      1320450.88      6882086.73      1320105.21      6881777.80
#Sta/Elev= 30
  4600.8 2349.84  4650.5 2348.64  4761.8 2346.01  4818.6 2341.58  4843.4 2341.52
  4863.8 2338.24  4870.4 2335.40  4875.5 2338.82  4885.9 2336.62  4890.1 2332.99
  4911.2 2325.10  4942.7 2309.74  4946.7 2307.71  4976.8 2307.08  4977.3 2306.58
  4987.1 2307.08  5017.6 2311.06  5024.3 2309.36  5052.7 2311.64  5060.2 2314.48
  5066.9 2311.88  5074.4 2315.02  5091.5 2317.51  5116.3 2319.28  5144.7 2326.24
  5173.1 2335.67  5194.8 2346.05  5241.5 2351.19  5419.8 2359.84  5463.6 2360.22
#Mann=9,-1,0
  4600.8   0.035       0  4650.5    0.07       0  4942.7   0.035       0
  4976.8   0.035       0  4987.1   0.035       0  5074.4    0.07       0
  5091.5   0.035       0  5241.5    0.07       0  5419.8   0.035       0
Bank Sta=4976.8,4987.1
Exp/Cntr=0.3,0.1

Type RM Length L Ch R = 1,32083,505,505,505
BEGIN DESCRIPTION:
Linn Creek Trib066 60.0
END DESCRIPTION:
XS GIS Cut Line= 4
      1320546.95      6882255.07      1320709.73      6881825.35
      1320705.38      6881775.44      1320171.56      6881690.81
#Sta/Elev= 30
  4510.6 2341.47  4539.5 2340.83  4551.5 2337.75  4571.0 2339.10  4576.3 2334.04
  4601.1 2334.36  4606.5 2328.31  4631.3 2327.58  4637.9 2322.04  4644.8 2321.03
  4667.9 2315.94  4796.2 2305.69  4826.3 2308.87  4839.0 2306.42  4856.5 2308.53
  4916.8 2307.87  4946.9 2306.03  4956.6 2302.44  5002.5 2301.29  5003.0 2300.79
  5012.8 2301.29  5152.2 2316.62  5172.5 2314.77  5246.4 2317.04  5314.2 2321.62
  5352.4 2331.29  5357.5 2329.66  5385.1 2344.22  5425.6 2351.51  5560.7 2354.56
#Mann=6,-1,0
  4510.6    0.07       0  4637.9   0.035       0  4644.8    0.07       0
  5002.5    0.07       0  5012.8    0.07       0  5246.4   0.035       0
Bank Sta=5002.5,5012.8
Exp/Cntr=0.3,0.1

Type RM Length L Ch R = 1,31578,578,578,578
BEGIN DESCRIPTION:
Linn Creek Trib066 59.0
END DESCRIPTION:
XS GIS Cut Line= 4
      1320755.03      6882337.97      1321061.29      6881951.22
      1321048.27      6881838.37      1320149.87      6881643.07
#Sta/Elev= 30
  4450.2 2328.36  4585.6 2320.81  4606.4 2316.39  4728.2 2307.27  4792.3 2309.35
  4833.9 2305.98  4856.4 2300.79  4862.8 2304.22  4870.9 2301.62  4877.2 2304.05
  4900.1 2298.79  4926.9 2299.38  4991.9 2293.17  4992.4 2292.67  5002.2 2293.17
  5027.3 2298.39  5270.5 2305.32  5326.5 2305.87  5363.6 2300.90  5418.6 2307.36
  5500.5 2310.21  5541.4 2315.75  5631.0 2316.59  5715.4 2321.37  5746.3 2328.09
  5785.2 2345.52  5790.3 2343.82  5817.7 2349.10  5883.5 2347.87  5976.5 2354.45
#Mann=5,-1,0
  4450.2   0.035       0  4900.1    0.07       0  4991.9    0.07       0
  5002.2    0.07       0  5631.0   0.035       0
Bank Sta=4991.9,5002.2
Exp/Cntr=0.3,0.1