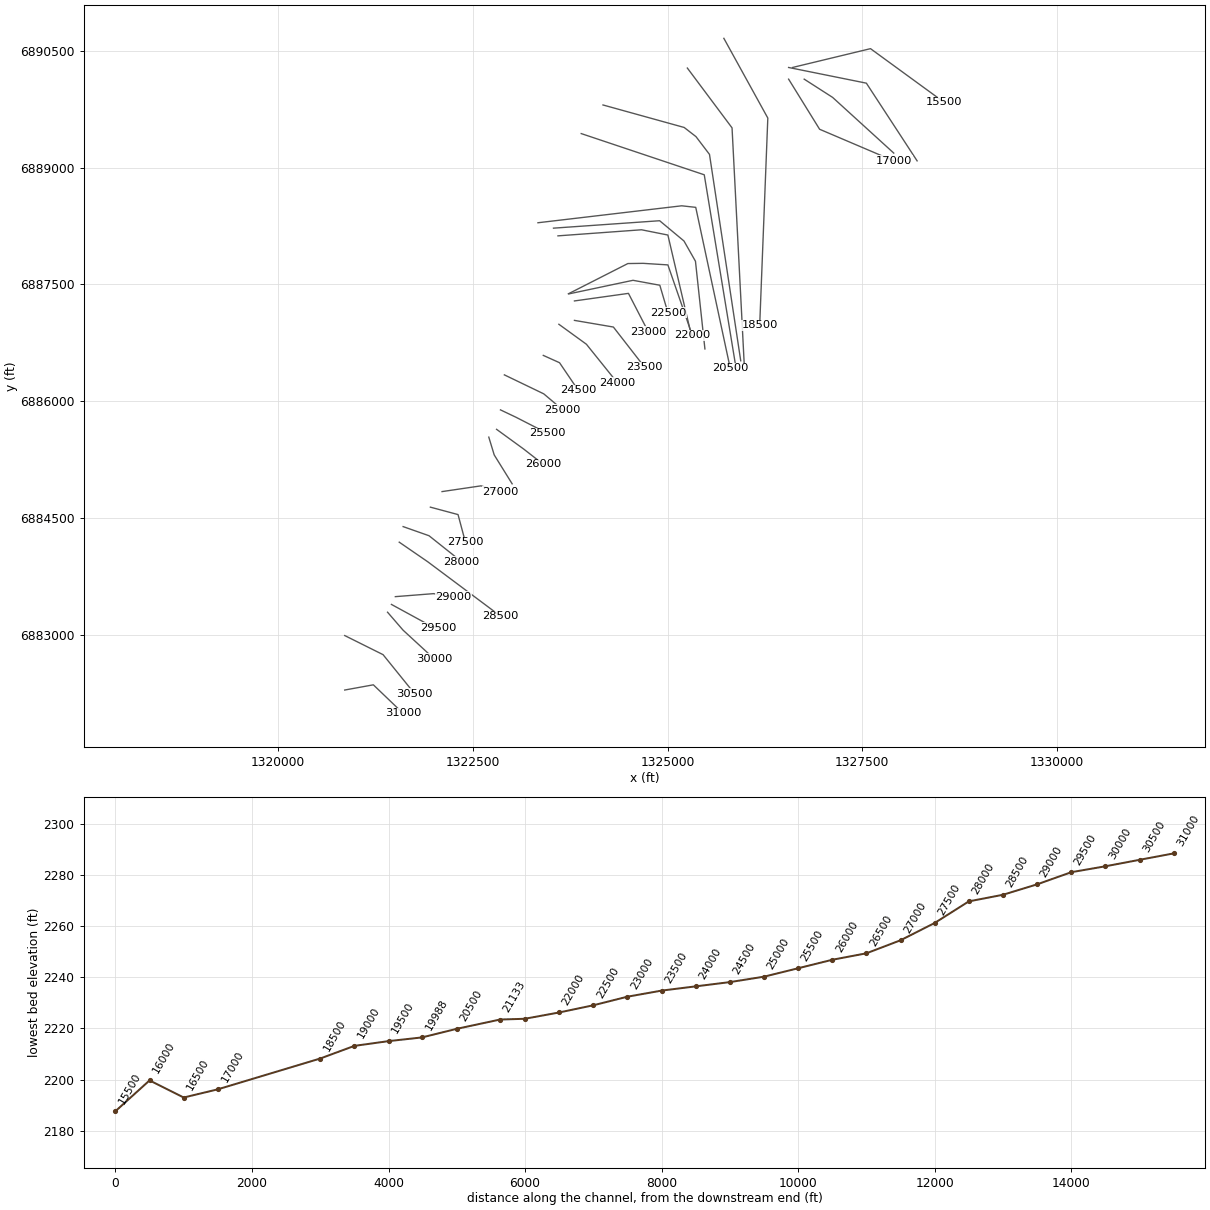
HEC-RAS study Linn Creek Trib066.prj: Linn Creek Trib066 Base Level Engineering

--- Linn Creek Trib066.g01 (geometry) --- (continued)

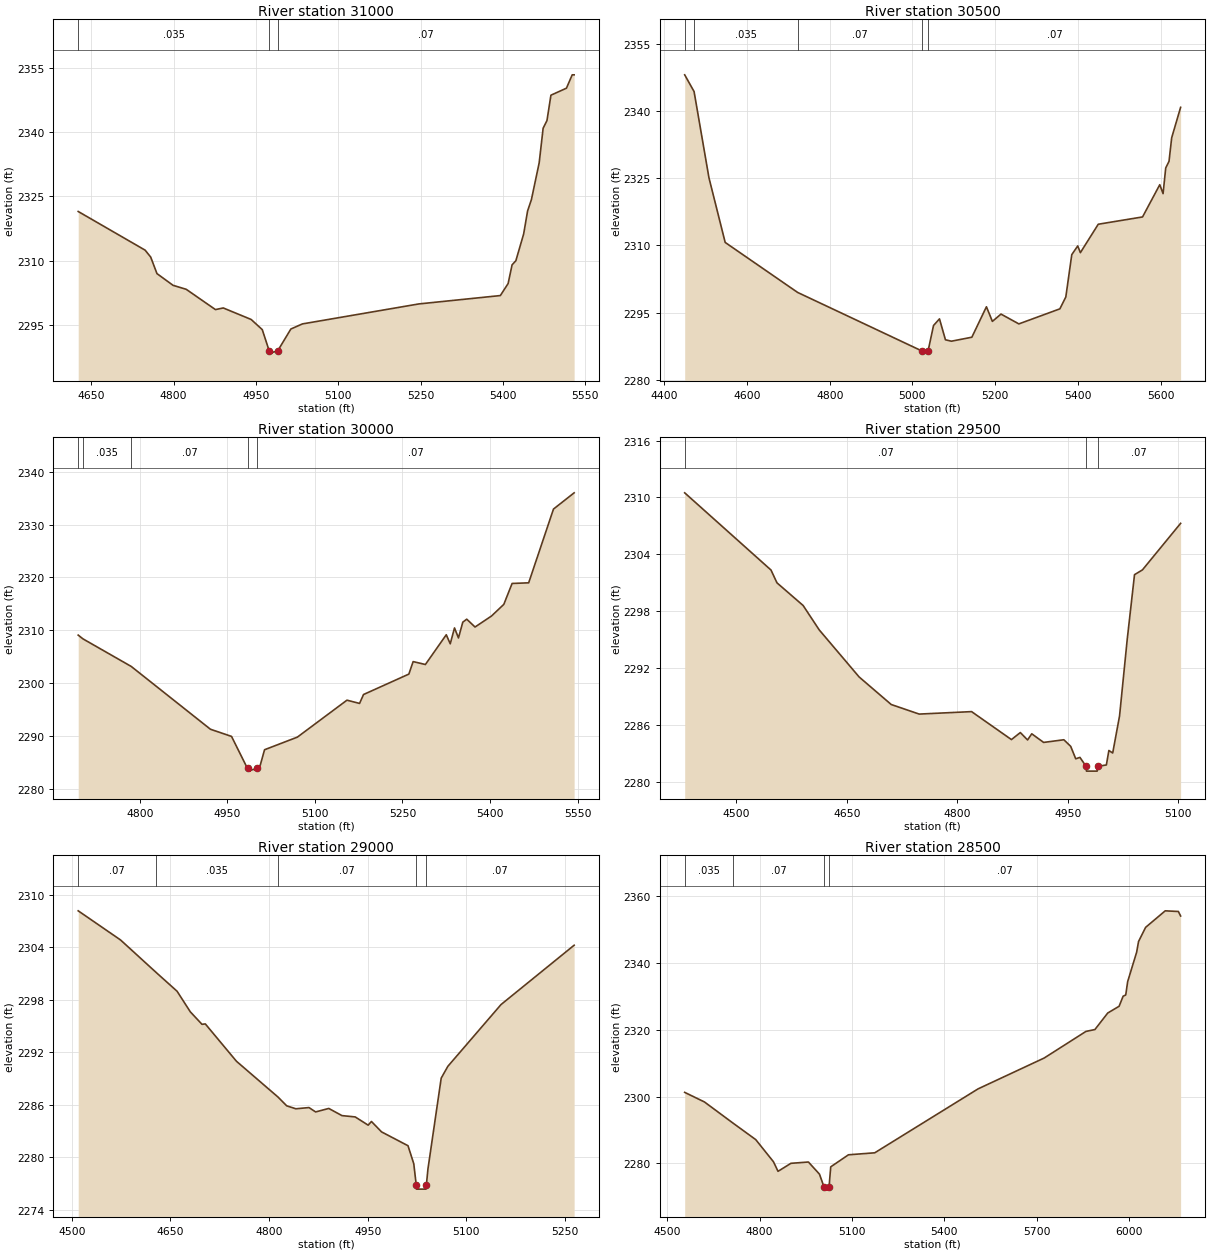
Type RM Length L Ch R = 1,31000,500,500,500
BEGIN DESCRIPTION:
Linn Creek Trib066 58.0
END DESCRIPTION:
XS GIS Cut Line= 3
      1320854.99      6882288.00      1321222.75      6882354.95
      1321605.02      6881987.99
#Sta/Elev= 30
  4626.2 2321.48  4748.2 2312.46  4758.3 2310.85  4769.7 2307.00  4799.0 2304.27
  4823.0 2303.34  4876.3 2298.61  4890.5 2298.99  4941.3 2296.31  4961.6 2293.94
  4974.3 2288.96  4974.8 2288.46  4989.6 2288.96  5013.7 2294.08  5034.7 2295.27
  5247.0 2299.93  5395.4 2301.88  5409.6 2304.68  5416.8 2309.04  5423.7 2310.00
  5437.9 2316.24  5445.1 2321.62  5452.0 2324.23  5466.2 2332.83  5473.4 2340.89
  5480.4 2342.69  5487.6 2348.59  5515.9 2350.23  5526.4 2353.34  5529.9 2353.34
#Mann=3,-1,0
  4626.2   0.035       0  4974.3    0.07       0  4989.6    0.07       0
Bank Sta=4974.3,4989.6
Exp/Cntr=0.3,0.1

Type RM Length L Ch R = 1,30500,500,500,500
BEGIN DESCRIPTION:
Linn Creek Trib066 57.0
END DESCRIPTION:
XS GIS Cut Line= 3
      1320855.02      6882987.99      1321347.67      6882742.33
      1321755.01      6882237.98
#Sta/Elev= 30
  4449.5 2348.03  4472.2 2344.30  4508.2 2325.05  4547.4 2310.64  4722.5 2299.49
  5022.5 2286.45  5023.0 2285.95  5037.9 2286.45  5051.0 2292.11  5065.4 2293.59
  5079.8 2288.93  5094.2 2288.61  5143.7 2289.50  5178.9 2296.29  5193.3 2293.03
  5214.1 2294.66  5257.3 2292.47  5356.5 2295.83  5370.8 2298.48  5385.2 2307.92
  5399.6 2309.86  5406.0 2308.36  5449.2 2314.70  5556.3 2316.33  5597.9 2323.52
  5605.9 2321.53  5612.3 2327.25  5620.3 2328.75  5626.7 2333.99  5648.3 2340.78
#Mann=5,-1,0
  4449.5    0.07       0  4472.2   0.035       0  4722.5    0.07       0
  5022.5    0.07       0  5037.9    0.07       0
Bank Sta=5022.5,5037.9
Exp/Cntr=0.3,0.1

Type RM Length L Ch R = 1,30000,500,500,500
BEGIN DESCRIPTION:
Linn Creek Trib066 56.0
END DESCRIPTION:
XS GIS Cut Line= 3
      1321404.97      6883288.03      1321604.82      6883056.84
      1322004.98      6882688.02
#Sta/Elev= 30
  4694.4 2309.11  4702.6 2308.40  4785.3 2303.19  4921.0 2291.33  4957.1 2289.98
  4984.5 2283.92  4985.0 2283.42  5000.0 2283.92  5006.4 2284.56  5013.7 2287.46
  5069.9 2289.84  5154.9 2296.82  5176.5 2296.21  5183.3 2297.89  5261.0 2301.75
  5268.3 2304.11  5289.3 2303.56  5325.1 2309.18  5331.9 2307.47  5339.2 2310.47
  5346.0 2308.58  5353.4 2311.56  5360.2 2312.12  5374.4 2310.64  5402.7 2312.73
  5423.7 2314.92  5437.9 2318.87  5466.3 2318.99  5508.8 2332.92  5544.2 2335.99
#Mann=5,-1,0
  4694.4    0.07       0  4702.6   0.035       0  4785.3    0.07       0
  4984.5    0.07       0  5000.0    0.07       0
Bank Sta=4984.5,5000
Exp/Cntr=0.3,0.1

Type RM Length L Ch R = 1,29500,500,500,500
BEGIN DESCRIPTION:
Linn Creek Trib066 55.0
END DESCRIPTION:
XS GIS Cut Line= 3
      1321455.01      6883387.99      1321955.48      6883114.75
      1322055.05      6883087.99
#Sta/Elev= 30
  4429.8 2310.48  4547.0 2302.33  4555.1 2300.98  4590.6 2298.59  4612.5 2296.01
  4666.6 2291.05  4710.2 2288.14  4748.2 2287.13  4819.3 2287.39  4873.4 2284.44
  4885.5 2285.18  4895.3 2284.40  4901.0 2285.05  4917.1 2284.14  4944.6 2284.42
  4953.9 2283.72  4960.7 2282.41  4966.4 2282.56  4974.8 2281.61  4975.3 2281.11
  4989.8 2281.11  4990.3 2281.61  5002.3 2281.76  5005.7 2283.29  5010.9 2283.02
  5020.2 2286.94  5030.6 2295.01  5040.5 2301.84  5051.3 2302.35  5103.1 2307.26
#Mann=3,-1,0
  4429.8    0.07       0  4974.8    0.07       0  4990.3    0.07       0
Bank Sta=4974.8,4990.3
Exp/Cntr=0.3,0.1

Type RM Length L Ch R = 1,29000,500,500,500
BEGIN DESCRIPTION:
Linn Creek Trib066 54.0
END DESCRIPTION:
XS GIS Cut Line= 3
      1321505.04      6883488.00      1321993.73      6883526.50
      1322255.01      6883488.00
#Sta/Elev= 30
  4509.8 2308.16  4574.2 2304.83  4628.3 2301.12  4660.2 2298.97  4680.3 2296.62
  4698.1 2295.19  4703.1 2295.24  4750.5 2290.97  4813.7 2286.88  4826.9 2285.88
  4840.8 2285.54  4860.8 2285.68  4870.9 2285.18  4890.9 2285.58  4911.0 2284.76
  4931.1 2284.61  4950.8 2283.67  4955.8 2284.09  4971.2 2282.90  5011.4 2281.32
  5020.2 2279.26  5023.9 2276.86  5024.4 2276.36  5038.9 2276.36  5039.4 2276.86
  5041.7 2278.64  5061.9 2289.04  5072.0 2290.39  5152.9 2297.45  5264.1 2304.23
#Mann=5,-1,0
  4509.8    0.07       0  4628.3   0.035       0  4813.7    0.07       0
  5023.9    0.07       0  5039.4    0.07       0
Bank Sta=5023.9,5039.4
Exp/Cntr=0.3,0.1

Type RM Length L Ch R = 1,28500,500,500,500
BEGIN DESCRIPTION:
Linn Creek Trib066 53.0
END DESCRIPTION:
XS GIS Cut Line= 3
      1321555.00      6884188.00      1321920.27      6883936.82
      1322855.02      6883237.99
#Sta/Elev= 30
  4556.7 2301.26  4621.0 2298.38  4714.7 2291.98  4787.3 2287.12  4844.9 2280.49
  4859.8 2277.61  4901.7 2280.01  4958.5 2280.40  4994.4 2276.76  5009.8 2272.78
  5010.3 2272.28  5025.4 2272.78  5030.9 2278.95  5088.5 2282.56  5173.9 2283.16
  5509.5 2302.31  5724.2 2311.55  5859.6 2319.51  5888.8 2320.08  5930.5 2325.03
  5967.3 2327.04  5980.5 2330.07  5988.9 2330.42  5995.1 2334.42  6024.3 2343.23
  6030.5 2346.43  6053.5 2350.68  6117.1 2355.63  6159.8 2355.43  6167.1 2354.09
#Mann=4,-1,0
  4556.7   0.035       0  4714.7    0.07       0  5009.8    0.07       0
  5025.4    0.07       0
Bank Sta=5009.8,5025.4
Exp/Cntr=0.3,0.1

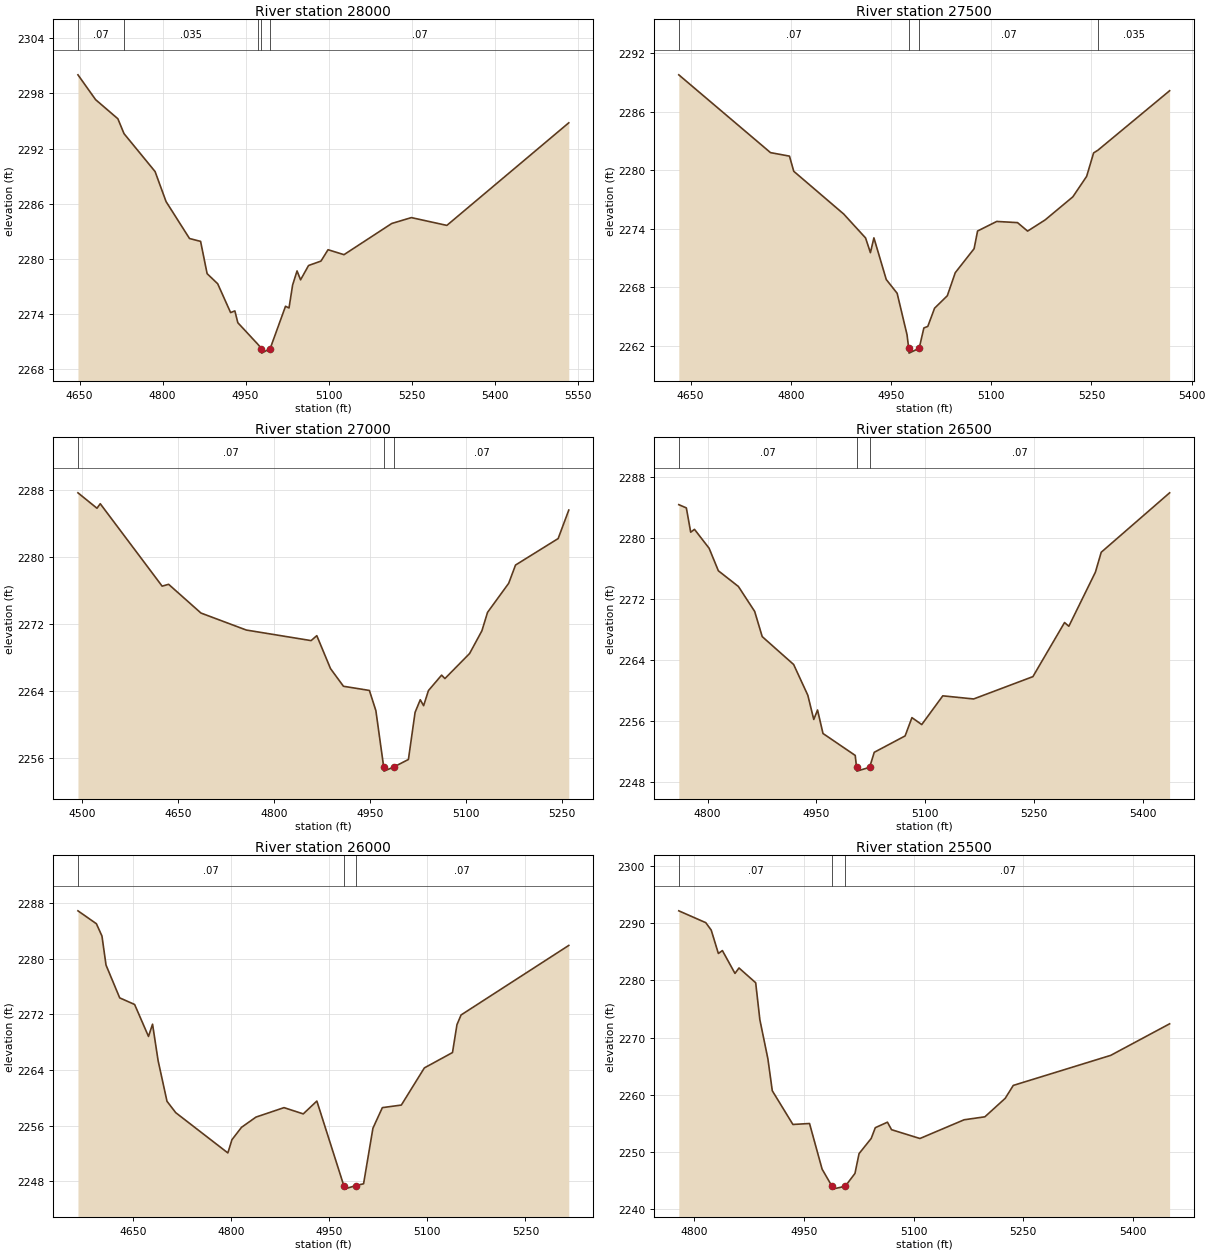
Type RM Length L Ch R = 1,28000,500,500,500
BEGIN DESCRIPTION:
Linn Creek Trib066 52.0
END DESCRIPTION:
XS GIS Cut Line= 3
      1321604.97      6884388.01      1321937.69      6884270.69
      1322355.01      6883937.99
#Sta/Elev= 30
  4647.2 2300.03  4679.0 2297.33  4719.3 2295.24  4730.4 2293.62  4786.5 2289.49
  4806.3 2286.22  4848.7 2282.19  4868.7 2281.88  4880.5 2278.36  4899.6 2277.26
  4922.9 2274.12  4930.6 2274.30  4935.9 2273.02  4971.9 2270.68  4978.7 2270.20
  4979.2 2269.70  4994.4 2270.20  5022.1 2274.81  5028.4 2274.62  5034.9 2277.12
  5042.9 2278.66  5049.3 2277.69  5063.7 2279.25  5086.1 2279.73  5098.9 2280.97
  5127.7 2280.43  5214.0 2283.83  5249.4 2284.47  5313.5 2283.62  5533.7 2294.80
#Mann=5,-1,0
  4647.2    0.07       0  4730.4   0.035       0  4971.9    0.07       0
  4978.7    0.07       0  4994.4    0.07       0
Bank Sta=4978.7,4994.4
Exp/Cntr=0.3,0.1

Type RM Length L Ch R = 1,27500,500,500,500
BEGIN DESCRIPTION:
Linn Creek Trib066 51.0
END DESCRIPTION:
XS GIS Cut Line= 3
      1321955.02      6884638.00      1322310.22      6884542.57
      1322404.99      6884188.02
#Sta/Elev= 30
  4632.2 2289.77  4769.5 2281.80  4797.9 2281.44  4804.3 2279.89  4879.1 2275.51
  4911.8 2273.06  4919.1 2271.55  4924.3 2273.07  4942.8 2268.80  4959.1 2267.39
  4973.9 2263.14  4976.4 2261.76  4976.9 2261.26  4992.1 2261.76  4999.1 2263.84
  5005.0 2264.00  5015.1 2265.86  5034.2 2267.14  5046.1 2269.50  5074.3 2271.96
  5079.5 2273.77  5108.2 2274.75  5139.3 2274.63  5154.4 2273.76  5180.7 2274.91
  5222.1 2277.27  5242.8 2279.37  5253.2 2281.77  5259.7 2282.05  5367.0 2288.14
#Mann=4,-1,0
  4632.2    0.07       0  4976.4    0.07       0  4992.1    0.07       0
  5259.7   0.035       0
Bank Sta=4976.4,4992.1
Exp/Cntr=0.3,0.1

Type RM Length L Ch R = 1,27000,500,500,500
BEGIN DESCRIPTION:
Linn Creek Trib066 50.0
END DESCRIPTION:
XS GIS Cut Line= 3
      1322105.02      6884838.00      1322605.50      6884911.89
      1322854.99      6884838.00
#Sta/Elev= 30
  4494.1 2287.71  4523.8 2285.87  4528.9 2286.41  4625.5 2276.57  4635.6 2276.79
  4686.1 2273.36  4756.9 2271.33  4858.0 2270.07  4866.9 2270.66  4888.3 2266.73
  4908.5 2264.62  4949.0 2264.12  4959.1 2261.71  4971.3 2254.99  4971.8 2254.49
  4987.2 2254.99  5009.9 2255.88  5020.3 2261.50  5028.4 2263.01  5033.6 2262.30
  5041.2 2264.11  5061.7 2265.95  5066.9 2265.54  5105.4 2268.53  5124.6 2271.24
  5133.4 2273.44  5166.4 2276.91  5177.1 2279.09  5243.6 2282.25  5260.2 2285.65
#Mann=3,-1,0
  4494.1    0.07       0  4971.3    0.07       0  4987.2    0.07       0
Bank Sta=4971.3,4987.2
Exp/Cntr=0.3,0.1

Type RM Length L Ch R = 1,26500,500,500,500
BEGIN DESCRIPTION:
Linn Creek Trib066 49.0
END DESCRIPTION:
XS GIS Cut Line= 3
      1322705.01      6885537.96      1322774.78      6885308.74
      1323005.00      6884938.00
#Sta/Elev= 30
  4760.4 2284.36  4770.8 2283.93  4776.8 2280.74  4782.0 2281.12  4802.2 2278.63
  4814.9 2275.68  4842.5 2273.62  4864.9 2270.35  4875.3 2267.04  4918.6 2263.38
  4938.1 2259.35  4946.3 2256.17  4951.5 2257.41  4959.0 2254.33  5003.4 2251.45
  5005.2 2249.89  5005.7 2249.39  5023.2 2249.89  5029.6 2251.86  5072.1 2254.01
  5081.5 2256.41  5095.0 2255.50  5124.0 2259.27  5166.5 2258.86  5248.1 2261.79
  5291.7 2268.89  5297.6 2268.40  5334.2 2275.50  5342.2 2278.11  5436.4 2285.91
#Mann=3,-1,0
  4760.4    0.07       0  5005.2    0.07       0  5023.2    0.07       0
Bank Sta=5005.2,5023.2
Exp/Cntr=0.3,0.1

Type RM Length L Ch R = 1,26000,500,500,500
BEGIN DESCRIPTION:
Linn Creek Trib066 48.0
END DESCRIPTION:
XS GIS Cut Line= 3
      1322805.00      6885638.00      1323155.82      6885382.68
      1323404.99      6885188.01
#Sta/Elev= 30
  4566.1 2286.92  4594.3 2285.06  4602.8 2283.29  4609.0 2279.11  4629.9 2274.39
  4652.7 2273.44  4673.9 2268.84  4680.1 2270.60  4688.6 2265.35  4702.2 2259.50
  4715.6 2257.86  4795.2 2252.07  4801.4 2253.97  4816.1 2255.76  4838.2 2257.23
  4881.0 2258.59  4910.4 2257.69  4931.2 2259.54  4972.4 2247.36  4972.9 2246.86
  4990.4 2247.36  5002.6 2247.63  5016.9 2255.63  5031.3 2258.59  5060.3 2258.96
  5095.5 2264.31  5138.5 2266.52  5145.3 2270.53  5151.6 2271.93  5316.2 2281.94
#Mann=3,-1,0
  4566.1    0.07       0  4972.4    0.07       0  4990.4    0.07       0
Bank Sta=4972.4,4990.4
Exp/Cntr=0.3,0.1

Type RM Length L Ch R = 1,25500,500,500,500
BEGIN DESCRIPTION:
Linn Creek Trib066 47.0
END DESCRIPTION:
XS GIS Cut Line= 3
      1322854.96      6885888.02      1323054.48      6885793.20
      1323454.97      6885588.01
#Sta/Elev= 30
  4779.1 2292.14  4816.0 2290.07  4823.4 2288.78  4833.2 2284.69  4838.7 2285.20
  4855.9 2281.21  4861.4 2282.16  4884.2 2279.58  4889.9 2273.13  4900.9 2266.29
  4906.9 2260.72  4935.1 2254.83  4957.8 2255.00  4975.0 2247.03  4988.5 2244.04
  4989.0 2243.54  5006.6 2244.04  5019.9 2246.28  5025.5 2249.74  5042.1 2252.39
  5047.7 2254.27  5064.3 2255.23  5069.9 2253.92  5108.7 2252.38  5169.1 2255.65
  5197.5 2256.17  5225.3 2259.40  5236.3 2261.65  5369.5 2266.90  5450.0 2272.41
#Mann=3,-1,0
  4779.1    0.07       0  4988.5    0.07       0  5006.6    0.07       0
Bank Sta=4988.5,5006.6
Exp/Cntr=0.3,0.1

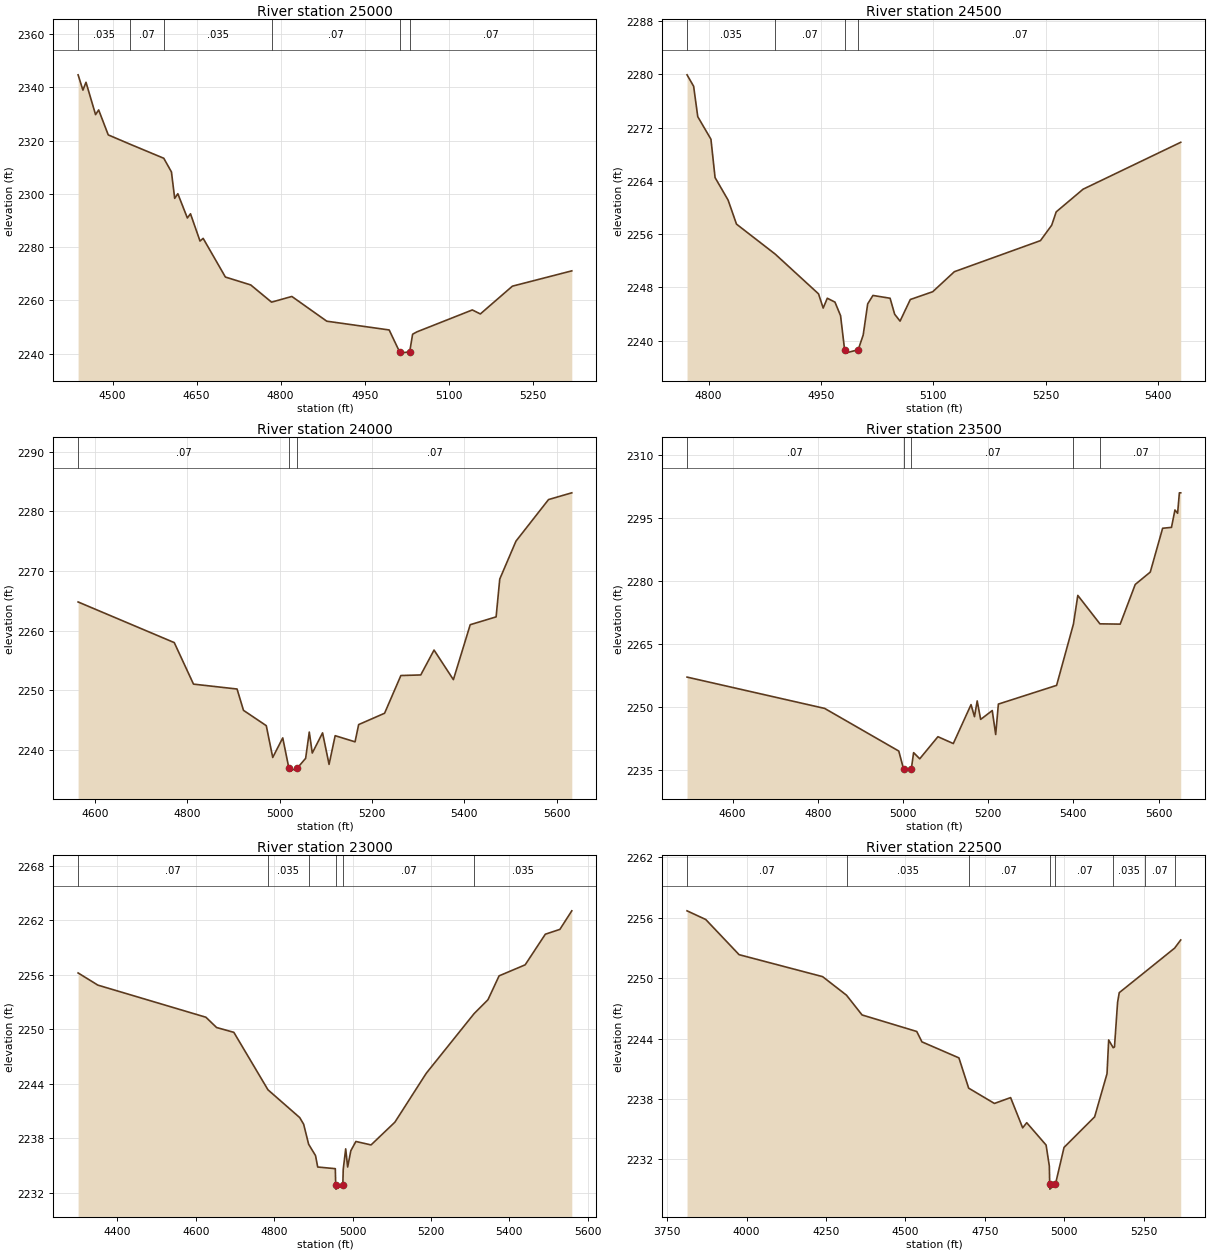
Type RM Length L Ch R = 1,25000,500,500,500
BEGIN DESCRIPTION:
Linn Creek Trib066 46.0
END DESCRIPTION:
XS GIS Cut Line= 3
      1322904.97      6886338.02      1323410.72      6886094.10
      1323654.99      6885888.01
#Sta/Elev= 30
  4438.5 2344.65  4447.1 2338.92  4452.6 2341.86  4469.7 2329.71  4475.2 2331.48
  4492.3 2322.12  4530.6 2318.68  4591.4 2313.35  4605.1 2308.22  4610.9 2298.30
  4616.5 2300.05  4633.5 2290.95  4639.1 2292.52  4656.1 2282.29  4661.7 2283.30
  4701.4 2268.79  4746.6 2265.83  4783.8 2259.37  4820.0 2261.51  4882.3 2252.23
  4993.7 2248.94  5012.2 2240.75  5012.7 2240.25  5030.3 2240.75  5035.5 2247.34
  5043.3 2248.24  5142.1 2256.45  5156.4 2254.95  5213.6 2265.37  5319.6 2271.11
#Mann=6,-1,0
  4438.5   0.035       0  4530.6    0.07       0  4591.4   0.035       0
  4783.8    0.07       0  5012.2    0.07       0  5030.3    0.07       0
Bank Sta=5012.2,5030.3
Exp/Cntr=0.3,0.1

Type RM Length L Ch R = 1,24500,500,500,500
BEGIN DESCRIPTION:
Linn Creek Trib066 45.0
END DESCRIPTION:
XS GIS Cut Line= 3
      1323405.04      6886587.98      1323613.55      6886494.03
      1323855.01      6886137.99
#Sta/Elev= 30
  4771.3 2279.95  4780.1 2278.23  4785.6 2273.66  4803.2 2270.27  4808.7 2264.51
  4826.1 2261.12  4837.3 2257.51  4888.9 2253.01  4946.8 2247.03  4953.0 2244.89
  4958.5 2246.37  4968.7 2245.79  4976.2 2243.75  4981.6 2238.62  4982.1 2238.12
  4999.7 2238.62  5006.4 2240.84  5012.4 2245.52  5019.4 2246.79  5042.3 2246.37
  5048.4 2243.97  5055.6 2242.93  5069.3 2246.18  5099.2 2247.35  5128.1 2250.36
  5243.0 2255.03  5258.0 2257.35  5264.0 2259.35  5299.9 2262.76  5430.2 2269.81
#Mann=4,-1,0
  4771.3   0.035       0  4888.9    0.07       0  4981.6    0.07       0
  4999.7    0.07       0
Bank Sta=4981.6,4999.7
Exp/Cntr=0.3,0.1

Type RM Length L Ch R = 1,24000,500,500,500
BEGIN DESCRIPTION:
Linn Creek Trib066 44.0
END DESCRIPTION:
XS GIS Cut Line= 3
      1323604.96      6886988.03      1323958.48      6886731.48
      1324355.03      6886237.96
#Sta/Elev= 30
  4563.2 2264.81  4771.6 2258.00  4813.3 2251.04  4907.7 2250.22  4921.6 2246.65
  4971.0 2244.08  4985.0 2238.75  5006.7 2242.03  5020.0 2236.96  5020.5 2236.46
  5038.1 2236.96  5056.3 2238.60  5064.2 2243.01  5070.7 2239.49  5093.0 2242.87
  5107.1 2237.59  5120.3 2242.40  5163.4 2241.37  5171.2 2244.26  5227.4 2246.16
  5262.7 2252.48  5305.8 2252.58  5334.6 2256.75  5376.5 2251.79  5413.0 2261.00
  5469.1 2262.31  5477.0 2268.65  5512.2 2275.01  5582.7 2281.97  5633.1 2283.10
#Mann=3,-1,0
  4563.2    0.07       0  5020.0    0.07       0  5038.1    0.07       0
Bank Sta=5020,5038.1
Exp/Cntr=0.3,0.1

Type RM Length L Ch R = 1,23500,500,500,500
BEGIN DESCRIPTION:
Linn Creek Trib066 43.0
END DESCRIPTION:
XS GIS Cut Line= 3
      1323805.00      6887038.00      1324304.87      6886952.63
      1324705.01      6886437.99
#Sta/Elev= 30
  4492.9 2257.20  4816.0 2249.74  4990.0 2239.58  5001.2 2235.30  5001.7 2234.80
  5019.4 2235.30  5024.8 2239.20  5039.2 2237.74  5081.9 2243.00  5118.0 2241.37
  5159.6 2250.64  5167.7 2247.77  5174.1 2251.52  5182.2 2247.12  5209.4 2249.23
  5217.5 2243.52  5223.8 2250.77  5360.5 2255.23  5400.0 2269.83  5410.3 2276.66
  5462.2 2269.89  5509.8 2269.82  5545.1 2279.27  5580.4 2282.22  5609.4 2292.66
  5630.2 2292.87  5638.3 2297.01  5644.6 2296.23  5648.7 2301.10  5651.9 2301.10
#Mann=5,-1,0
  4492.9    0.07       0  5001.2    0.07       0  5019.4    0.07       0
  5400.0   0.035       0  5462.2    0.07       0
Bank Sta=5001.2,5019.4
Exp/Cntr=0.3,0.1

Type RM Length L Ch R = 1,23000,500,500,500
BEGIN DESCRIPTION:
Linn Creek Trib066 42.0
END DESCRIPTION:
XS GIS Cut Line= 3
      1323805.03      6887288.00      1324498.45      6887385.25
      1324754.98      6886888.03
#Sta/Elev= 30
  4299.8 2256.19  4350.3 2254.85  4625.9 2251.32  4653.2 2250.19  4697.2 2249.66
  4784.3 2243.34  4865.2 2240.29  4875.3 2239.56  4888.1 2237.35  4905.6 2236.11
  4911.2 2234.85  4956.1 2234.67  4957.1 2232.92  4957.6 2232.42  4975.3 2232.92
  4976.3 2234.58  4982.6 2236.85  4987.6 2234.85  4995.7 2236.64  5008.6 2237.66
  5047.3 2237.28  5108.1 2239.78  5188.2 2245.16  5310.1 2251.71  5345.7 2253.25
  5374.0 2255.87  5440.5 2257.08  5492.0 2260.45  5529.1 2260.98  5559.5 2263.02
#Mann=6,-1,0
  4299.8    0.07       0  4784.3   0.035       0  4888.1    0.07       0
  4957.1    0.07       0  4975.3    0.07       0  5310.1   0.035       0
Bank Sta=4957.1,4975.3
Exp/Cntr=0.3,0.1

Type RM Length L Ch R = 1,22500,500,500,500
BEGIN DESCRIPTION:
Linn Creek Trib066 41.0
END DESCRIPTION:
XS GIS Cut Line= 4
      1323737.40      6887379.50      1324556.84      6887553.11
      1324901.14      6887489.77      1325005.00      6887137.98
#Sta/Elev= 30
  3812.3 2256.67  3871.2 2255.81  3976.2 2252.32  4239.2 2250.14  4314.4 2248.30
  4363.4 2246.34  4535.6 2244.70  4551.9 2243.67  4668.4 2242.08  4699.0 2239.08
  4780.2 2237.56  4831.1 2238.14  4869.1 2235.14  4881.9 2235.65  4942.9 2233.43
  4953.1 2231.34  4954.2 2229.56  4954.7 2229.06  4972.4 2229.56  4999.4 2233.20
  5095.7 2236.23  5134.7 2240.51  5139.9 2243.86  5154.1 2243.09  5158.2 2243.16
  5168.0 2247.60  5173.2 2248.55  5255.4 2250.63  5347.6 2252.97  5366.8 2253.78
#Mann=8,-1,0
  3812.3    0.07       0  4314.4   0.035       0  4699.0    0.07       0
  4954.2    0.07       0  4972.4    0.07       0  5154.1   0.035       0
  5255.4    0.07       0  5347.6   0.035       0
Bank Sta=4954.2,4972.4
Exp/Cntr=0.3,0.1

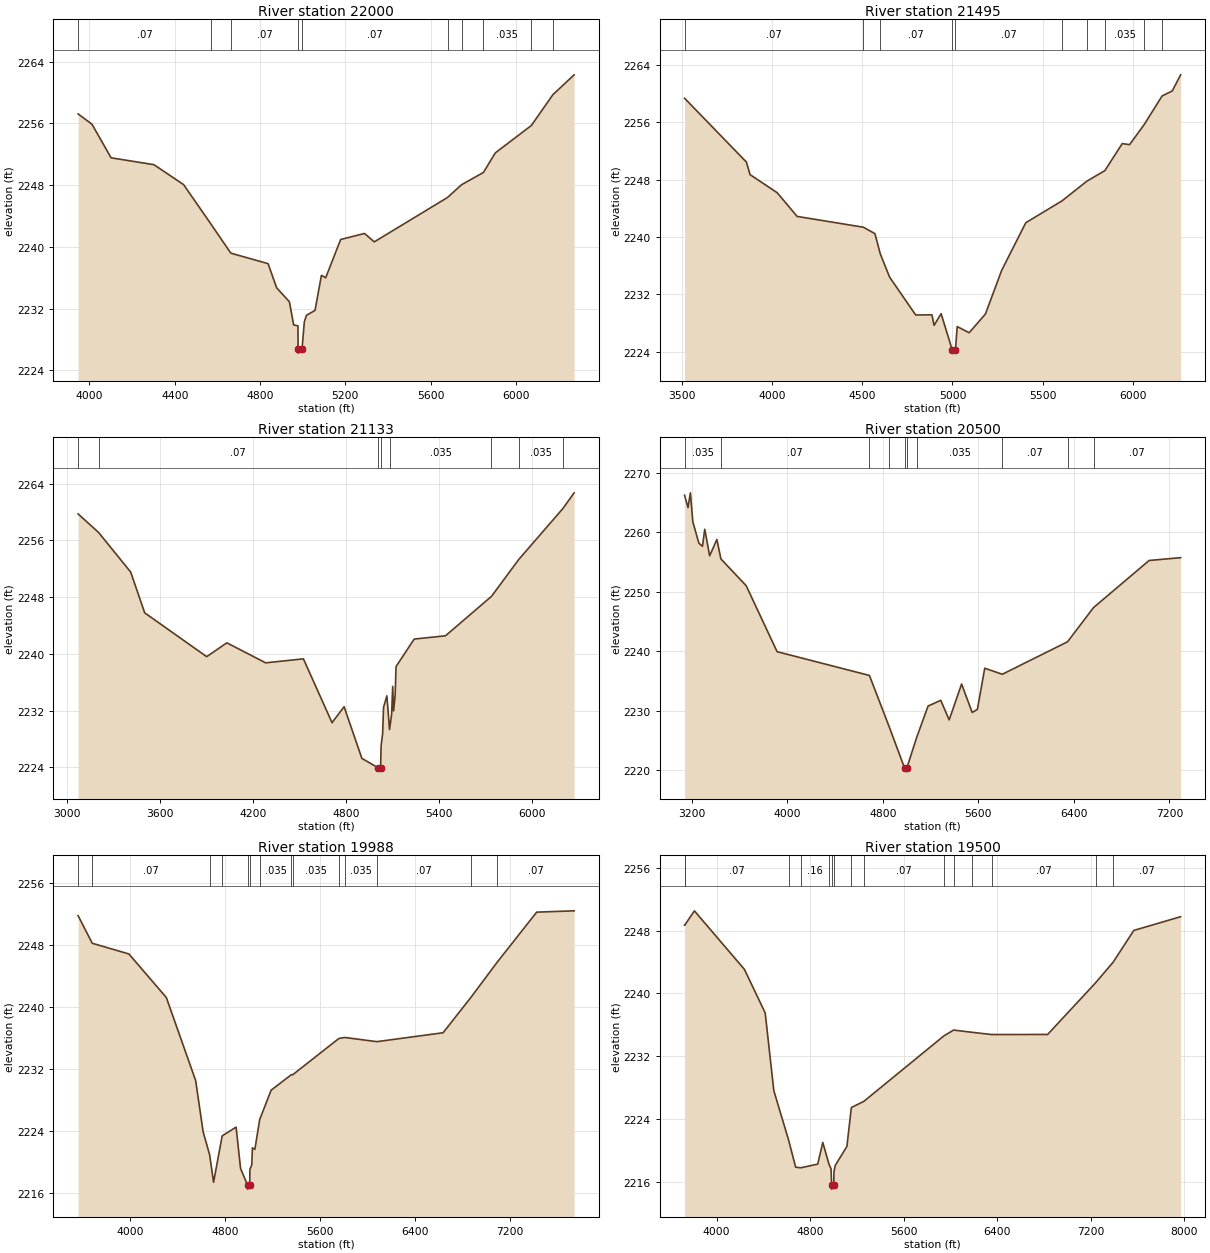
Type RM Length L Ch R = 1,22000,505,505,505
BEGIN DESCRIPTION:
Linn Creek Trib066 40.0
END DESCRIPTION:
XS GIS Cut Line= 5
      1323726.99      6887379.51      1324490.87      6887768.39
      1324687.19      6887771.06      1325004.76      6887751.03
      1325317.24      6886848.28
#Sta/Elev= 30
  3946.5 2257.24  4011.6 2255.90  4101.4 2251.55  4302.3 2250.66  4441.4 2248.08
  4568.5 2243.02  4663.0 2239.20  4837.8 2237.84  4877.8 2234.72  4937.8 2232.90
  4957.8 2229.90  4977.8 2229.79  4978.7 2226.75  4979.2 2226.25  4996.9 2226.75
  5007.8 2230.30  5017.8 2231.15  5057.9 2231.78  5088.0 2236.33  5108.0 2236.01
  5178.2 2240.97  5290.1 2241.75  5335.8 2240.66  5679.4 2246.41  5745.2 2248.06
  5847.8 2249.65  5903.4 2252.18  6072.9 2255.74  6173.8 2259.73  6273.5 2262.30
#Mann=10,-1,0
  3946.5    0.07       0  4568.5   0.035       0  4663.0    0.07       0
  4978.7    0.07       0  4996.9    0.07       0  5679.4   0.035       0
  5745.2    0.07       0  5847.8   0.035       0  6072.9    0.07       0
  6173.8   0.035       0
Bank Sta=4978.7,4996.9
Exp/Cntr=0.3,0.1

Type RM Length L Ch R = 1,21495,362,362,362
BEGIN DESCRIPTION:
Linn Creek Trib066 39.0
END DESCRIPTION:
XS GIS Cut Line= 4
      1323593.29      6888124.29      1324666.21      6888202.42
      1325004.76      6888134.71      1325306.83      6886843.07
#Sta/Elev= 30
  3516.3 2259.39  3858.9 2250.47  3879.0 2248.72  4029.4 2246.19  4139.7 2242.88
  4507.0 2241.37  4570.8 2240.47  4600.5 2237.64  4652.0 2234.40  4796.5 2229.11
  4886.6 2229.13  4898.4 2227.66  4937.3 2229.29  4998.4 2224.28  4998.9 2223.78
  5016.7 2224.28  5026.4 2227.49  5092.6 2226.63  5182.7 2229.24  5272.8 2235.35
  5406.3 2242.00  5606.9 2245.05  5744.5 2247.80  5844.4 2249.28  5940.4 2253.05
  5981.4 2252.91  6062.3 2255.72  6161.3 2259.71  6217.7 2260.41  6263.8 2262.66
#Mann=10,-1,0
  3516.3    0.07       0  4507.0   0.035       0  4600.5    0.07       0
  4998.4    0.07       0  5016.7    0.07       0  5606.9   0.035       0
  5744.5    0.07       0  5844.4   0.035       0  6062.3    0.07       0
  6161.3   0.035       0
Bank Sta=4998.4,5016.7
Exp/Cntr=0.3,0.1

Type RM Length L Ch R = 1,21133,633,633,633
BEGIN DESCRIPTION:
Linn Creek Trib066 38.0
END DESCRIPTION:
XS GIS Cut Line= 5
      1323536.00      6888223.25      1324898.85      6888318.73
      1325211.35      6888058.32      1325358.92      6887797.90
      1325480.26      6886671.21
#Sta/Elev= 30
  3069.2 2259.75  3202.1 2257.12  3409.0 2251.55  3499.6 2245.80  3900.2 2239.62
  4030.5 2241.57  4281.2 2238.75  4525.2 2239.31  4710.1 2230.31  4788.2 2232.56
  4903.0 2225.28  5005.8 2223.98  5006.3 2223.48  5024.1 2223.98  5027.1 2227.03
  5037.2 2228.77  5043.0 2232.47  5064.6 2234.10  5081.8 2229.35  5095.4 2231.51
  5102.1 2235.43  5107.9 2231.97  5118.0 2234.15  5123.8 2238.22  5241.0 2242.10
  5443.1 2242.56  5740.4 2248.12  5916.7 2253.32  6202.1 2260.51  6274.7 2262.72
#Mann=8,-1,0
  3069.2   0.035       0  3202.1    0.07       0  5005.8    0.07       0
  5024.1    0.07       0  5081.8   0.035       0  5740.4    0.07       0
  5916.7   0.035       0  6202.1    0.07       0
Bank Sta=5005.8,5024.1
Exp/Cntr=0.3,0.1

Type RM Length L Ch R = 1,20500,512,512,512
BEGIN DESCRIPTION:
Linn Creek Trib066 37.0
END DESCRIPTION:
XS GIS Cut Line= 4
      1323336.31      6888292.69      1325182.20      6888510.53
      1325362.39      6888490.61      1325805.11      6886424.60
#Sta/Elev= 30
  3141.3 2266.19  3170.2 2264.11  3190.3 2266.59  3210.5 2261.74  3260.8 2258.15
  3291.0 2257.60  3310.4 2260.47  3351.4 2256.01  3411.9 2258.75  3445.7 2255.49
  3657.2 2250.99  3916.1 2239.91  4688.9 2235.92  4854.2 2227.32  4983.6 2220.35
  4984.1 2219.85  5001.9 2220.35  5083.8 2225.47  5180.1 2230.78  5286.2 2231.74
  5356.7 2228.45  5460.7 2234.48  5549.3 2229.70  5593.0 2230.22  5654.4 2237.13
  5801.7 2236.12  6347.4 2241.57  6564.9 2247.31  7030.6 2255.23  7294.2 2255.70
#Mann=10,-1,0
  3141.3   0.035       0  3445.7    0.07       0  4688.9   0.035       0
  4854.2    0.07       0  4983.6    0.07       0  5001.9    0.07       0
  5083.8   0.035       0  5801.7    0.07       0  6347.4   0.035       0
  6564.9    0.07       0
Bank Sta=4983.6,5001.9
Exp/Cntr=0.3,0.1

Type RM Length L Ch R = 1,19988,488,488,488
BEGIN DESCRIPTION:
Linn Creek Trib066 36.0
END DESCRIPTION:
XS GIS Cut Line= 3
      1323891.90      6889438.53      1325471.77      6888909.01
      1325879.76      6886426.36
#Sta/Elev= 30
  3561.9 2251.81  3681.2 2248.24  3990.3 2246.86  4305.9 2241.23  4553.0 2230.51
  4616.1 2223.89  4671.2 2220.90  4704.2 2217.36  4776.6 2223.36  4894.1 2224.49
  4931.7 2219.15  4990.9 2216.98  4991.4 2216.48  5009.2 2216.98  5010.1 2219.02
  5026.3 2219.60  5031.6 2221.81  5052.3 2221.61  5093.0 2225.47  5189.4 2229.26
  5360.7 2231.27  5371.0 2231.25  5760.5 2235.94  5809.8 2236.07  6081.2 2235.53
  6639.2 2236.68  6874.9 2241.27  7092.6 2245.74  7428.3 2252.26  7744.1 2252.43
#Mann=14,-1,0
  3561.9   0.035       0  3681.2    0.07       0  4671.2    0.16       0
  4776.6    0.07       0  4990.9    0.07       0  5009.2    0.07       0
  5093.0   0.035       0  5360.7    0.07       0  5371.0   0.035       0
  5760.5    0.07       0  5809.8   0.035       0  6081.2    0.07       0
  6874.9   0.035       0  7092.6    0.07       0
Bank Sta=4990.9,5009.2
Exp/Cntr=0.3,0.1

Type RM Length L Ch R = 1,19500,500,500,500
BEGIN DESCRIPTION:
Linn Creek Trib066 35.0
END DESCRIPTION:
XS GIS Cut Line= 5
      1324171.54      6889806.25      1325213.80      6889517.19
      1325365.61      6889399.33      1325539.14      6889170.90
      1325940.10      6886519.11
#Sta/Elev= 30
  3726.2 2248.70  3727.3 2248.70  3810.4 2250.54  4238.3 2243.07  4415.9 2237.51
  4489.6 2227.61  4615.8 2221.31  4676.6 2217.84  4719.3 2217.76  4864.9 2218.23
  4908.4 2220.99  4962.2 2218.19  4979.0 2217.63  4984.2 2215.54  4984.7 2215.04
  5002.7 2215.54  5003.6 2217.20  5014.2 2218.04  5114.7 2220.48  5152.8 2225.45
  5259.2 2226.23  5944.4 2234.59  6027.5 2235.33  6181.9 2235.05  6353.2 2234.76
  6831.6 2234.77  7242.2 2241.37  7390.9 2243.97  7568.6 2248.04  7968.8 2249.79
#Mann=15,-1,0
  3726.2   0.035       0  3727.3    0.07       0  4615.8   0.035       0
  4719.3    0.16       0  4962.2    0.07       0  4984.2    0.07       0
  5002.7    0.07       0  5152.8   0.035       0  5259.2    0.07       0
  5944.4   0.035       0  6027.5    0.07       0  6181.9   0.035       0
  6353.2    0.07       0  7242.2   0.035       0  7390.9    0.07       0
Bank Sta=4984.2,5002.7
Exp/Cntr=0.3,0.1

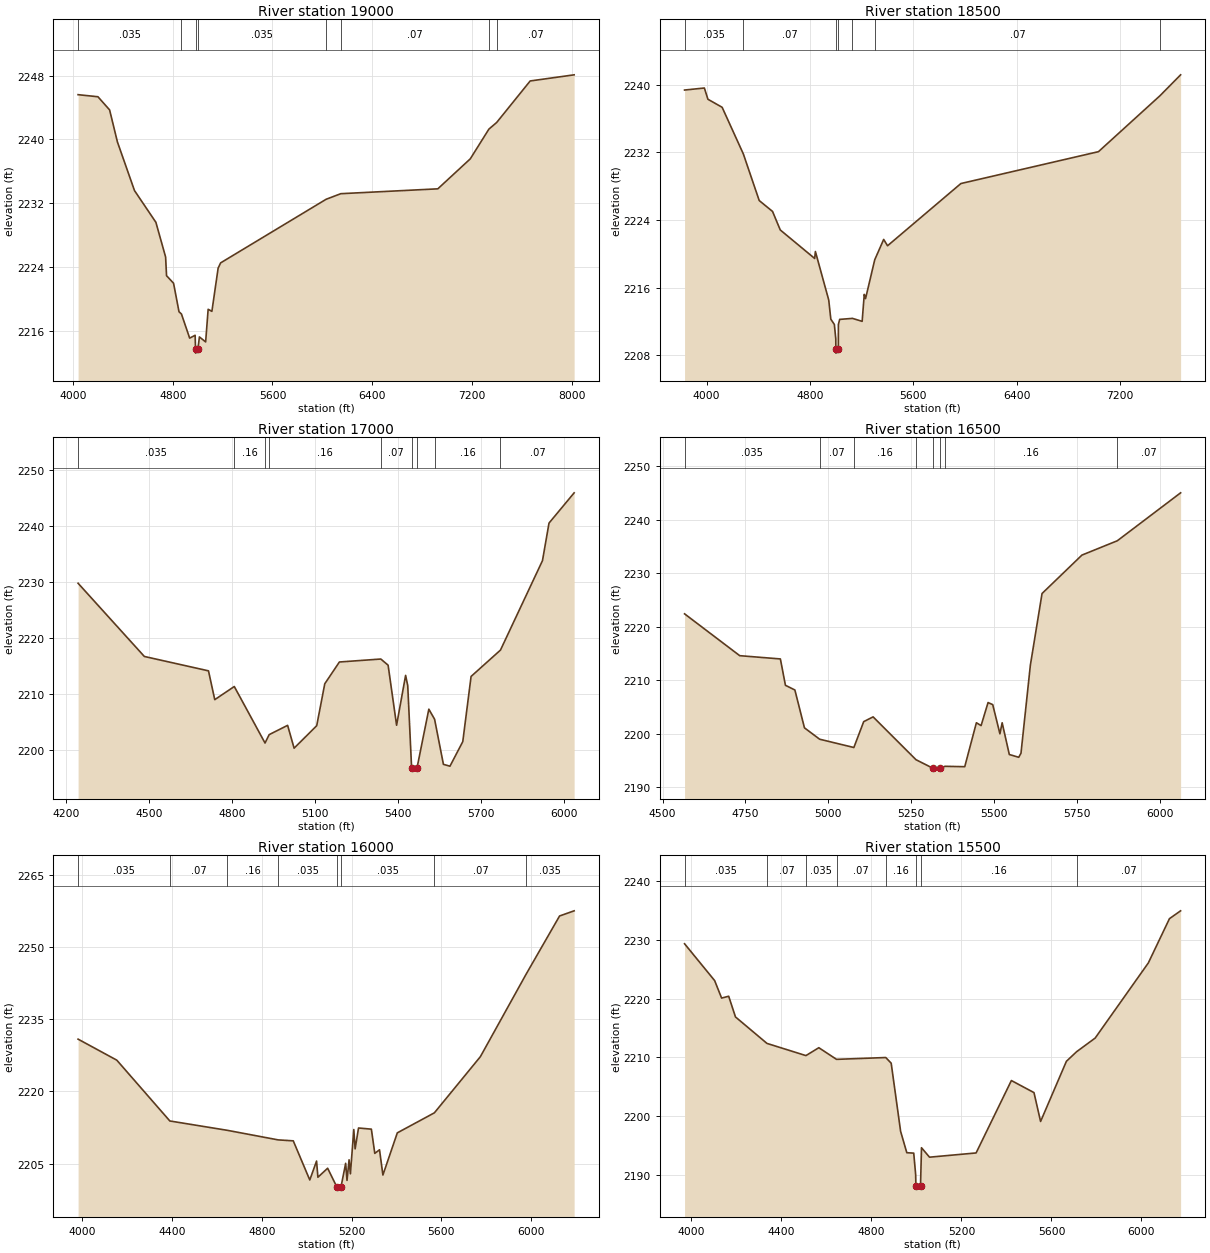
Type RM Length L Ch R = 1,19000,500,500,500
BEGIN DESCRIPTION:
Linn Creek Trib066 34.0
END DESCRIPTION:
XS GIS Cut Line= 3
      1325254.74      6890280.56      1325828.63      6889511.86
      1325983.92      6886495.85
#Sta/Elev= 30
  4040.7 2245.60  4199.9 2245.34  4293.5 2243.69  4356.2 2239.67  4493.2 2233.57
  4664.8 2229.59  4742.7 2225.24  4750.3 2222.89  4806.5 2221.95  4850.3 2218.37
  4869.8 2218.09  4935.8 2215.06  4979.6 2215.42  4982.8 2213.68  4983.3 2213.18
  5001.9 2213.68  5013.9 2215.21  5063.9 2214.59  5084.0 2218.68  5114.0 2218.42
  5164.1 2223.84  5184.1 2224.50  6030.5 2232.48  6148.2 2233.18  6926.4 2233.79
  7186.8 2237.55  7336.2 2241.28  7398.4 2242.11  7667.4 2247.32  8020.0 2248.09
#Mann=8,-1,0
  4040.7   0.035       0  4869.8    0.07       0  4982.8    0.07       0
  5001.9   0.035       0  6030.5   0.035       0  6148.2    0.07       0
  7336.2   0.035       0  7398.4    0.07       0
Bank Sta=4982.8,5001.9
Exp/Cntr=0.3,0.1

Type RM Length L Ch R = 1,18500,1500,1500,1500
BEGIN DESCRIPTION:
Linn Creek Trib066 33.0
END DESCRIPTION:
XS GIS Cut Line= 3
      1325723.50      6890662.50      1326287.92      6889637.99
      1326183.57      6886973.23
#Sta/Elev= 30
  3830.3 2239.36  3983.5 2239.60  4011.0 2238.27  4120.9 2237.32  4285.0 2231.80
  4407.7 2226.29  4510.8 2225.00  4570.5 2222.81  4836.5 2219.44  4842.2 2220.26
  4945.4 2214.52  4961.4 2212.26  4988.9 2211.63  5000.0 2209.91  5000.4 2208.74
  5000.9 2208.24  5019.6 2208.74  5020.0 2211.63  5030.0 2212.23  5128.7 2212.35
  5203.8 2212.00  5220.2 2215.19  5230.2 2214.69  5301.1 2219.28  5370.3 2221.69
  5400.3 2220.94  5967.4 2228.30  7031.5 2232.07  7507.4 2238.69  7666.8 2241.16
#Mann=7,-1,0
  3830.3   0.035       0  4285.0    0.07       0  5000.4    0.07       0
  5019.6    0.07       0  5128.7    0.16       0  5301.1    0.07       0
  7507.4   0.035       0
Bank Sta=5000.4,5019.6
Exp/Cntr=0.3,0.1

Type RM Length L Ch R = 1,17000,500,500,500
BEGIN DESCRIPTION:
Linn Creek Trib066 32.0
END DESCRIPTION:
XS GIS Cut Line= 3
      1326555.02      6890137.96      1326953.01      6889494.14
      1327905.00      6889088.00
#Sta/Elev= 30
  4243.1 2229.76  4482.4 2216.68  4714.1 2214.11  4736.8 2208.96  4807.3 2211.31
  4918.4 2201.21  4933.3 2202.71  5000.0 2204.37  5023.4 2200.29  5105.1 2204.31
  5134.2 2211.80  5187.0 2215.69  5336.7 2216.22  5363.0 2215.12  5393.6 2204.39
  5426.2 2213.30  5433.9 2211.46  5447.9 2196.69  5448.4 2196.19  5467.1 2196.69
  5510.1 2207.26  5530.9 2205.46  5562.8 2197.40  5586.4 2197.07  5632.7 2201.46
  5662.7 2213.11  5768.9 2217.82  5920.6 2233.80  5944.2 2240.51  6035.0 2245.92
#Mann=9,-1,0
  4243.1   0.035       0  4807.3    0.16       0  4918.4    0.07       0
  4933.3    0.16       0  5336.7    0.07       0  5447.9    0.07       0
  5467.1    0.07       0  5530.9    0.16       0  5768.9    0.07       0
Bank Sta=5447.9,5467.1
Exp/Cntr=0.3,0.1

Type RM Length L Ch R = 1,16500,500,500,500
BEGIN DESCRIPTION:
Linn Creek Trib066 31.0
END DESCRIPTION:
XS GIS Cut Line= 3
      1326755.03      6890137.98      1327119.86      6889903.67
      1327905.03      6889187.98
#Sta/Elev= 30
  4566.4 2222.41  4732.8 2214.58  4855.4 2213.97  4870.6 2209.04  4899.1 2208.16
  4928.0 2201.08  4973.8 2198.95  5077.0 2197.40  5106.7 2202.24  5135.0 2203.13
  5264.3 2195.12  5316.6 2193.48  5317.1 2192.98  5335.8 2193.48  5352.0 2193.88
  5411.4 2193.81  5446.5 2202.03  5460.7 2201.50  5481.7 2205.81  5495.8 2205.42
  5517.5 2199.96  5524.2 2202.03  5545.8 2196.09  5574.2 2195.57  5581.0 2196.33
  5609.3 2212.81  5644.5 2226.21  5764.8 2233.40  5871.5 2236.08  6062.4 2245.05
#Mann=8,-1,0
  4566.4   0.035       0  4973.8    0.07       0  5077.0    0.16       0
  5264.3    0.07       0  5316.6    0.07       0  5335.8    0.07       0
  5352.0    0.16       0  5871.5    0.07       0
Bank Sta=5316.6,5335.8
Exp/Cntr=0.3,0.1

Type RM Length L Ch R = 1,16000,500,500,500
BEGIN DESCRIPTION:
Linn Creek Trib066 30.0
END DESCRIPTION:
XS GIS Cut Line= 3
      1326555.01      6890288.00      1327553.47      6890086.42
      1328205.00      6889088.00
#Sta/Elev= 30
  3981.4 2230.84  4154.0 2226.47  4390.3 2213.84  4646.2 2211.90  4873.1 2209.91
  4940.4 2209.71  5014.0 2201.58  5044.2 2205.51  5050.2 2202.15  5093.6 2204.02
  5134.1 2200.18  5134.6 2199.68  5153.3 2200.18  5173.9 2205.04  5179.9 2201.49
  5189.1 2205.77  5195.0 2202.86  5210.2 2212.06  5216.1 2208.04  5231.2 2212.38
  5288.5 2212.14  5303.7 2207.11  5324.8 2207.85  5339.9 2202.61  5404.1 2211.37
  5569.3 2215.53  5774.3 2227.20  5978.7 2244.38  6127.3 2256.43  6192.2 2257.50
#Mann=8,-1,0
  3981.4   0.035       0  4390.3    0.07       0  4646.2    0.16       0
  4873.1   0.035       0  5134.1   0.035       0  5153.3   0.035       0
  5569.3    0.07       0  5978.7   0.035       0
Bank Sta=5134.1,5153.3
Exp/Cntr=0.3,0.1

Type RM Length L Ch R = 1,15500,700,700,700
BEGIN DESCRIPTION:
Linn Creek Trib066 29.0
END DESCRIPTION:
XS GIS Cut Line= 3
      1326605.04      6890288.01      1327606.55      6890529.88
      1328555.01      6889837.99
#Sta/Elev= 30
  3969.7 2229.33  4103.4 2223.07  4134.3 2220.10  4165.8 2220.41  4196.0 2216.89
  4336.0 2212.39  4509.0 2210.32  4566.3 2211.66  4645.1 2209.68  4863.8 2209.99
  4887.9 2209.03  4929.8 2197.44  4957.3 2193.81  4988.1 2193.74  4996.6 2190.10
  4997.8 2188.12  4998.3 2187.62  5018.2 2188.12  5022.6 2194.66  5058.2 2193.05
  5265.2 2193.77  5422.0 2206.08  5522.4 2204.03  5551.8 2199.12  5666.5 2209.35
  5711.5 2210.97  5794.3 2213.30  6030.7 2226.08  6124.5 2233.60  6174.0 2234.93
#Mann=8,-1,0
  3969.7   0.035       0  4336.0    0.07       0  4509.0   0.035       0
  4645.1    0.07       0  4863.8    0.16       0  4997.8    0.07       0
  5018.2    0.16       0  5711.5    0.07       0
Bank Sta=4997.8,5018.2
Exp/Cntr=0.3,0.1