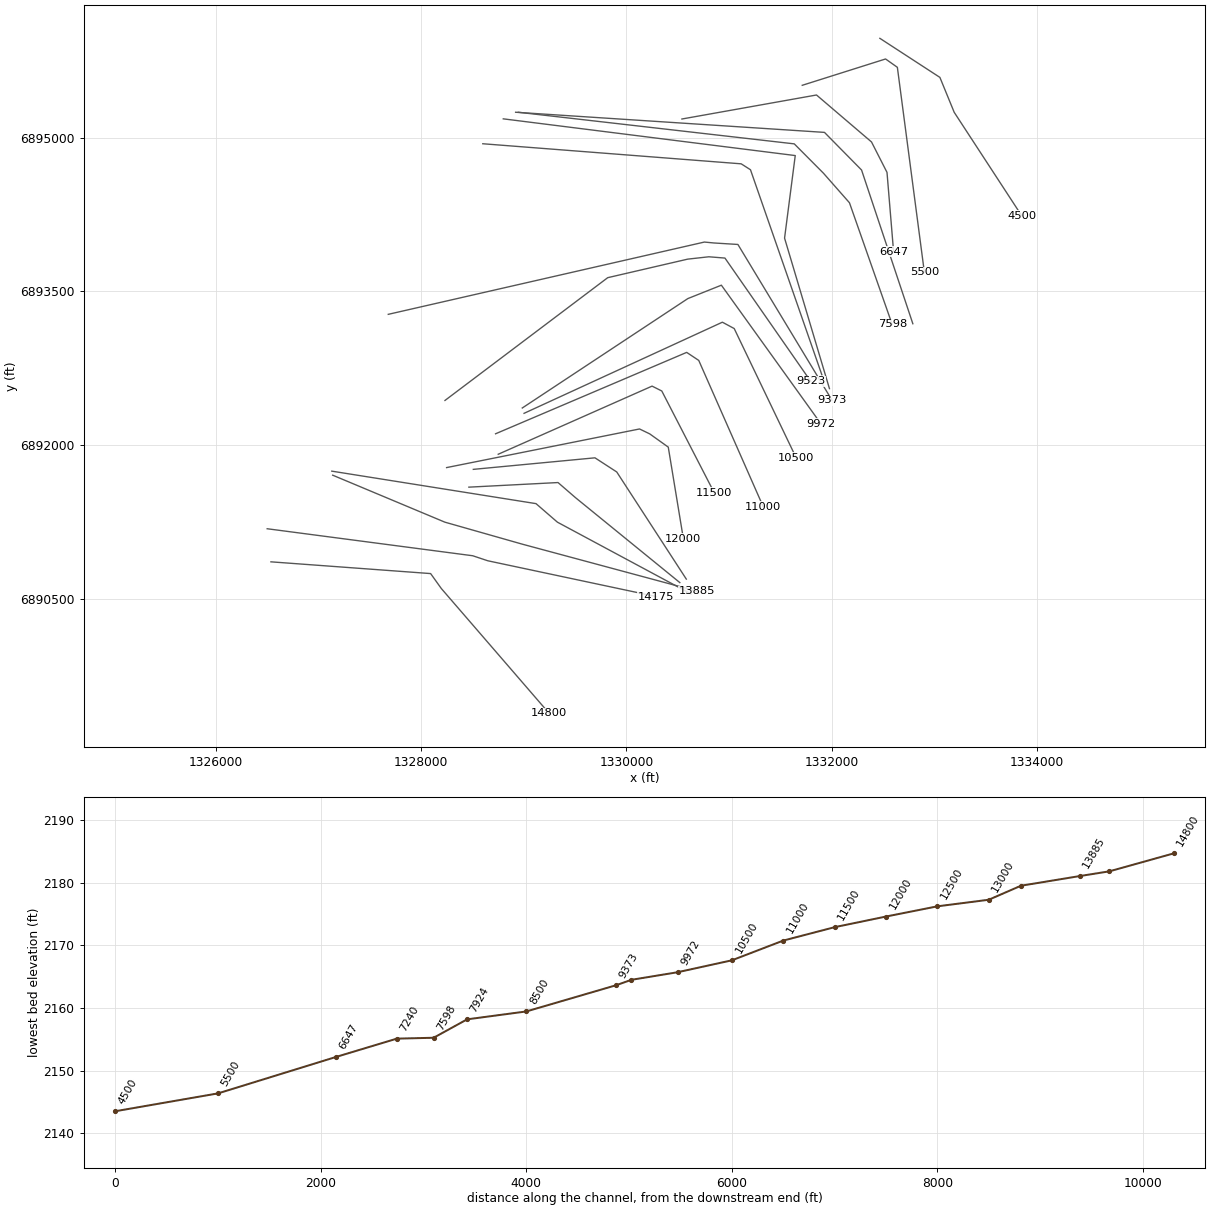
HEC-RAS study Linn Creek Trib066.prj: Linn Creek Trib066 Base Level Engineering

--- Linn Creek Trib066.g01 (geometry) --- (continued)

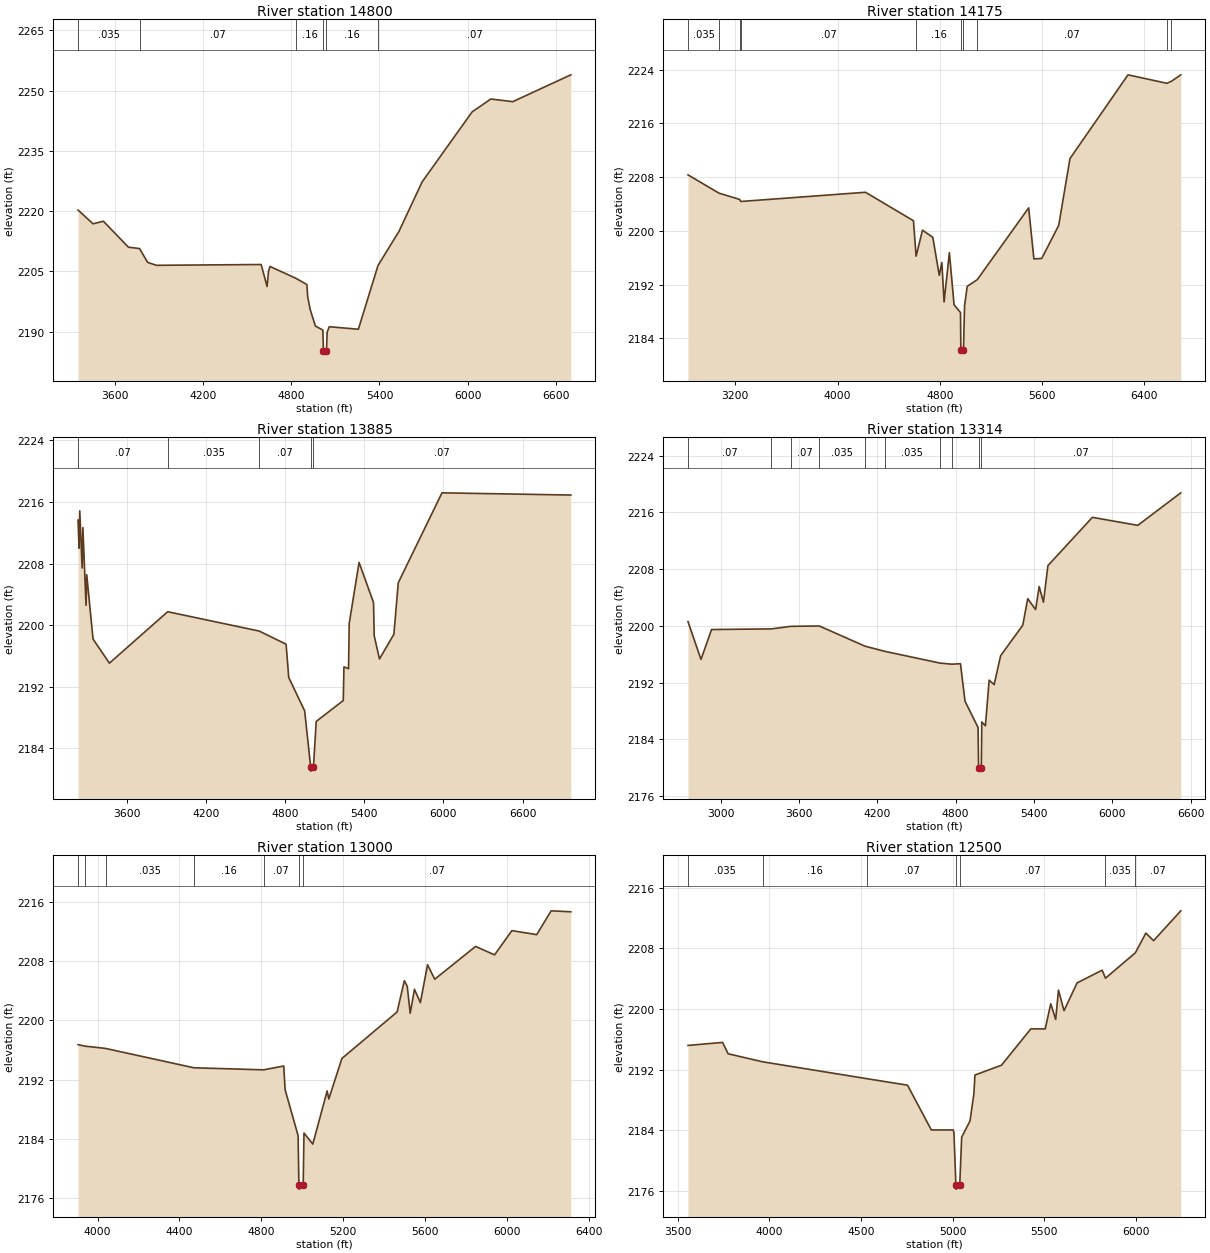
Type RM Length L Ch R = 1,14800,625,625,625
BEGIN DESCRIPTION:
Linn Creek Trib066 28.0
END DESCRIPTION:
XS GIS Cut Line= 4
      1326533.35      6890861.49      1328090.66      6890746.90
      1328194.82      6890601.07      1329246.60      6889382.68
#Sta/Elev= 30
  3350.6 2220.28  3452.5 2216.85  3522.7 2217.50  3693.2 2211.03  3769.0 2210.69
  3823.5 2207.25  3883.7 2206.52  4595.6 2206.72  4635.7 2201.25  4645.7 2205.08
  4655.8 2206.23  4830.2 2203.32  4906.4 2201.73  4911.8 2198.72  4928.7 2195.52
  4964.3 2191.41  5014.7 2190.40  5019.3 2185.16  5019.8 2184.66  5039.7 2185.16
  5044.2 2189.86  5058.2 2191.23  5256.4 2190.61  5389.9 2206.47  5532.8 2214.99
  5689.7 2227.27  6029.7 2244.71  6157.0 2247.92  6306.2 2247.26  6700.9 2253.94
#Mann=6,-1,0
  3350.6   0.035       0  3769.0    0.07       0  4830.2    0.16       0
  5019.3    0.07       0  5039.7    0.16       0  5389.9    0.07       0
Bank Sta=5019.3,5039.7
Exp/Cntr=0.3,0.1

Type RM Length L Ch R = 1,14175,290,290,290
BEGIN DESCRIPTION:
Linn Creek Trib066 27.0
END DESCRIPTION:
XS GIS Cut Line= 4
      1326496.87      6891184.41      1328501.07      6890920.86
      1328647.95      6890871.90      1330288.48      6890522.97
#Sta/Elev= 30
  2830.7 2208.33  3073.2 2205.61  3234.0 2204.68  3244.0 2204.37  4218.9 2205.74
  4593.9 2201.50  4614.5 2196.23  4664.5 2200.10  4745.2 2199.03  4795.6 2193.38
  4815.8 2195.29  4833.3 2189.42  4874.6 2196.76  4911.5 2188.99  4961.7 2187.84
  4964.4 2182.30  4964.9 2181.80  4984.9 2182.30  4993.3 2188.83  5014.2 2191.74
  5092.9 2192.74  5494.7 2203.42  5535.6 2195.82  5596.9 2195.89  5729.8 2200.82
  5817.8 2210.76  6271.7 2223.22  6575.4 2221.96  6610.6 2222.26  6684.2 2223.22
#Mann=10,-1,0
  2830.7   0.035       0  3073.2    0.07       0  3234.0   0.035       0
  3244.0    0.07       0  4614.5    0.16       0  4964.4    0.07       0
  4984.9    0.16       0  5092.9    0.07       0  6575.4   0.035       0
  6610.6    0.07       0
Bank Sta=4964.4,4984.9
Exp/Cntr=0.3,0.1

Type RM Length L Ch R = 1,13885,571,571,571
BEGIN DESCRIPTION:
Linn Creek Trib066 26.0
END DESCRIPTION:
XS GIS Cut Line= 4
      1327135.80      6891706.97      1328229.55      6891248.64
      1328986.49      6891033.36      1330687.88      6890575.03
#Sta/Elev= 30
  3231.1 2213.63  3238.5 2209.99  3243.9 2214.84  3262.3 2207.42  3267.7 2212.67
  3291.5 2202.58  3296.9 2206.55  3344.5 2198.20  3468.8 2195.06  3910.4 2201.74
  4604.1 2199.23  4807.9 2197.52  4828.1 2193.19  4948.5 2188.87  4994.4 2181.54
  4994.9 2181.04  5015.3 2181.54  5036.1 2187.49  5241.2 2190.21  5246.4 2194.58
  5281.2 2194.34  5286.3 2200.22  5361.0 2208.14  5470.5 2202.94  5475.7 2198.63
  5515.6 2195.60  5625.0 2198.82  5658.1 2205.50  5989.5 2217.18  6966.0 2216.89
#Mann=5,-1,0
  3231.1    0.07       0  3910.4   0.035       0  4604.1    0.07       0
  4994.4    0.07       0  5015.3    0.07       0
Bank Sta=4994.4,5015.3
Exp/Cntr=0.3,0.1

Type RM Length L Ch R = 1,13314,314,314,314
BEGIN DESCRIPTION:
Linn Creek Trib066 25.0
END DESCRIPTION:
XS GIS Cut Line= 4
      1327126.72      6891746.49      1329118.16      6891429.48
      1329326.77      6891248.64      1330631.15      6890547.88
#Sta/Elev= 30
  2750.7 2200.60  2850.2 2195.26  2931.2 2199.48  3390.0 2199.57  3537.7 2199.93
  3756.7 2199.98  4105.0 2197.14  4256.0 2196.41  4681.9 2194.74  4772.5 2194.59
  4837.0 2194.66  4872.1 2189.36  4971.9 2185.65  4975.7 2180.00  4976.2 2179.50
  4996.6 2180.00  5000.4 2186.44  5027.9 2185.90  5056.8 2192.34  5094.9 2191.71
  5144.4 2195.78  5314.1 2200.09  5352.2 2203.84  5412.3 2202.30  5439.9 2205.55
  5472.4 2203.34  5506.7 2208.50  5847.3 2215.31  6194.9 2214.18  6524.0 2218.77
#Mann=10,-1,0
  2750.7    0.07       0  3390.0   0.035       0  3537.7    0.07       0
  3756.7   0.035       0  4105.0    0.07       0  4256.0   0.035       0
  4681.9    0.16       0  4772.5    0.07       0  4975.7    0.07       0
  4996.6    0.07       0
Bank Sta=4975.7,4996.6
Exp/Cntr=0.3,0.1

Type RM Length L Ch R = 1,13000,500,500,500
BEGIN DESCRIPTION:
Linn Creek Trib066 24.0
END DESCRIPTION:
XS GIS Cut Line= 4
      1328463.49      6891590.24      1329332.89      6891635.19
      1329502.72      6891488.15      1330520.57      6890658.89
#Sta/Elev= 30
  3904.8 2196.74  3940.5 2196.53  4039.0 2196.23  4470.9 2193.62  4811.1 2193.34
  4910.0 2193.86  4916.6 2190.68  4980.2 2184.46  4984.1 2177.76  4984.6 2177.26
  5005.0 2177.76  5008.8 2184.82  5051.9 2183.33  5122.2 2190.50  5130.1 2189.41
  5194.1 2194.87  5464.1 2201.15  5499.2 2205.36  5513.6 2204.59  5528.0 2200.98
  5548.8 2204.20  5577.5 2202.40  5612.7 2207.51  5647.9 2205.56  5847.5 2209.98
  5940.2 2208.84  6024.9 2212.11  6146.3 2211.57  6216.6 2214.78  6312.9 2214.65
#Mann=7,-1,0
  3904.8   0.035       0  3940.5    0.07       0  4039.0   0.035       0
  4470.9    0.16       0  4811.1    0.07       0  4984.1    0.07       0
  5005.0    0.07       0
Bank Sta=4984.1,5005
Exp/Cntr=0.3,0.1

Type RM Length L Ch R = 1,12500,500,500,500
BEGIN DESCRIPTION:
Linn Creek Trib066 23.0
END DESCRIPTION:
XS GIS Cut Line= 4
      1328506.93      6891763.86      1329692.97      6891876.51
      1329905.49      6891738.46      1330583.71      6890693.09
#Sta/Elev= 30
  3555.2 2195.19  3744.1 2195.59  3774.2 2194.09  3962.2 2193.03  4534.4 2190.79
  4754.0 2189.94  4883.8 2184.03  5003.3 2184.03  5007.4 2183.68  5018.1 2176.71
  5018.6 2176.21  5039.0 2176.71  5049.6 2183.07  5095.1 2185.22  5116.2 2188.77
  5122.1 2191.28  5267.1 2192.58  5427.3 2197.38  5505.8 2197.37  5536.1 2200.69
  5563.1 2198.63  5578.3 2202.50  5608.5 2199.78  5680.0 2203.45  5816.9 2205.13
  5834.9 2204.07  5998.1 2207.43  6055.5 2210.03  6097.7 2209.03  6246.1 2212.97
#Mann=7,-1,0
  3555.2   0.035       0  3962.2    0.16       0  4534.4    0.07       0
  5018.1    0.07       0  5039.0    0.07       0  5834.9   0.035       0
  5998.1    0.07       0
Bank Sta=5018.1,5039
Exp/Cntr=0.3,0.1

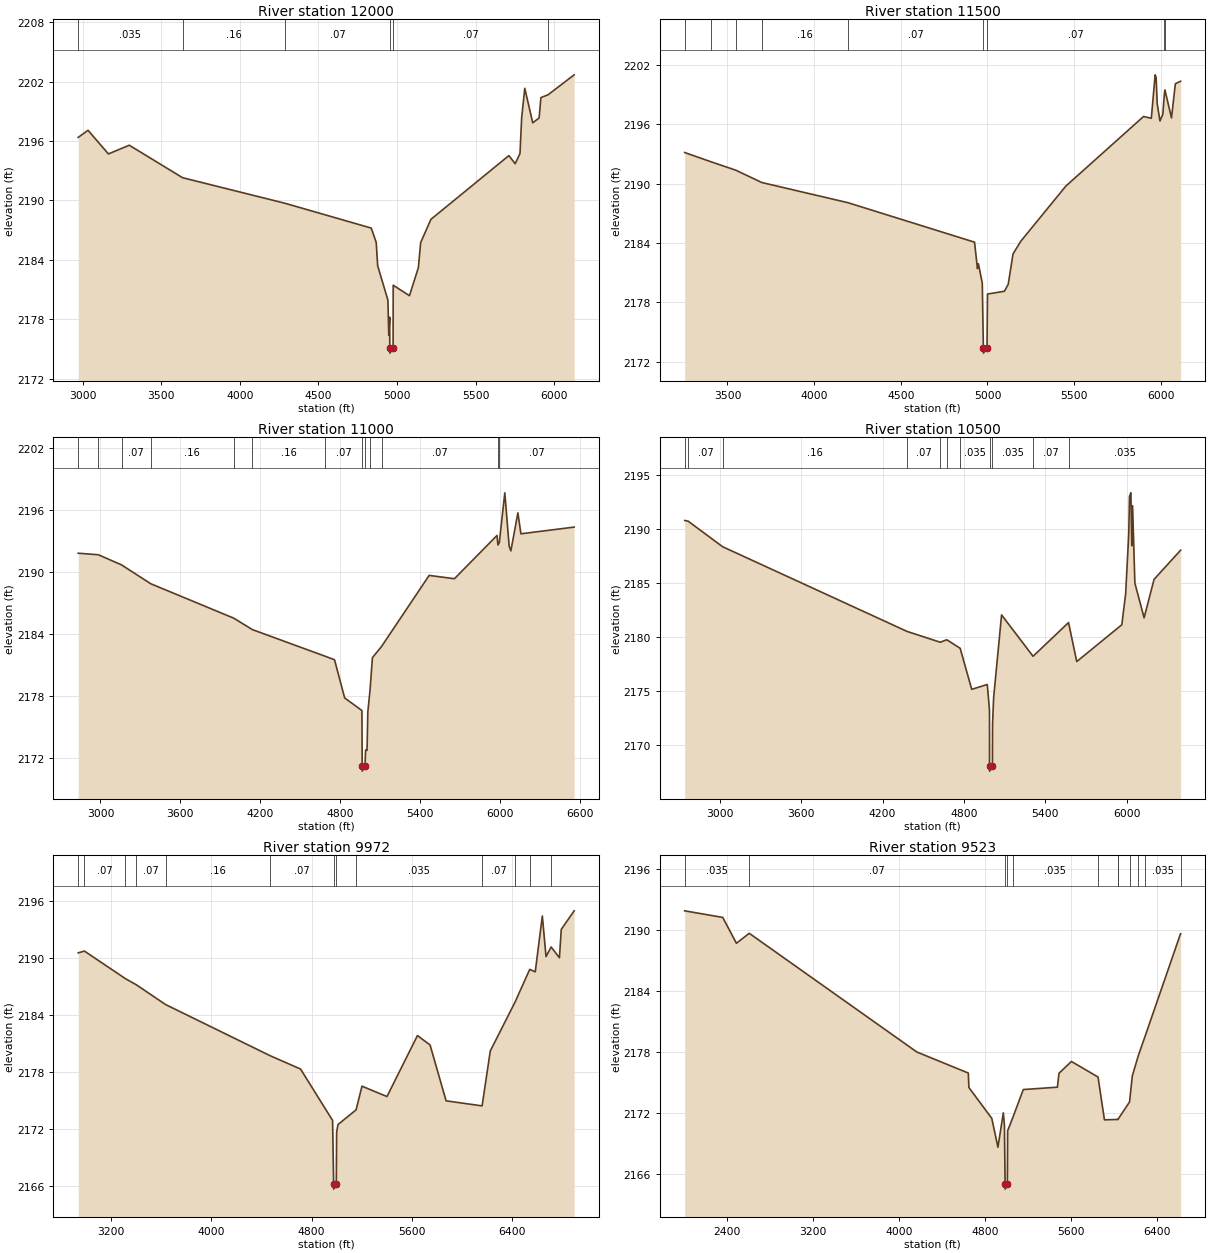
Type RM Length L Ch R = 1,12000,500,500,500
BEGIN DESCRIPTION:
Linn Creek Trib066 22.0
END DESCRIPTION:
XS GIS Cut Line= 5
      1328246.48      6891781.21      1330127.72      6892158.11
      1330227.08      6892110.05      1330407.94      6891980.87
      1330555.01      6891087.95
#Sta/Elev= 30
  2971.0 2196.37  3033.4 2197.09  3163.3 2194.70  3295.9 2195.58  3635.0 2192.30
  4286.2 2189.72  4835.9 2187.21  4867.6 2185.76  4876.7 2183.41  4941.9 2179.94
  4947.5 2176.38  4953.3 2178.21  4953.9 2175.08  4954.4 2174.58  4974.9 2175.08
  4975.6 2181.44  5079.1 2180.38  5135.7 2183.21  5150.4 2185.74  5215.5 2188.09
  5711.6 2194.53  5752.2 2193.71  5782.6 2194.75  5793.2 2198.37  5813.0 2201.33
  5863.7 2197.84  5904.2 2198.33  5915.6 2200.39  5961.7 2200.68  6127.2 2202.69
#Mann=6,-1,0
  2971.0   0.035       0  3635.0    0.16       0  4286.2    0.07       0
  4953.9    0.07       0  4974.9    0.07       0  5961.7   0.035       0
Bank Sta=4953.9,4974.9
Exp/Cntr=0.3,0.1

Type RM Length L Ch R = 1,11500,500,500,500
BEGIN DESCRIPTION:
Linn Creek Trib066 21.0
END DESCRIPTION:
XS GIS Cut Line= 4
      1328749.93      6891911.41      1330249.88      6892576.21
      1330344.82      6892528.56      1330854.99      6891538.03
#Sta/Elev= 30
  3253.1 2193.15  3405.7 2192.21  3548.6 2191.36  3697.7 2190.12  4195.2 2188.08
  4925.4 2184.09  4942.1 2181.42  4947.7 2181.91  4970.0 2179.94  4976.3 2173.38
  4976.8 2172.88  4997.3 2173.38  5000.0 2178.85  5097.5 2179.13  5119.6 2179.83
  5147.4 2182.90  5191.9 2184.18  5452.2 2189.76  5900.5 2196.79  5945.2 2196.61
  5967.3 2201.00  5972.9 2200.72  5979.2 2198.07  5995.1 2196.34  6011.7 2197.02
  6020.4 2199.06  6023.5 2199.48  6061.6 2196.65  6083.8 2200.10  6114.2 2200.35
#Mann=9,-1,0
  3253.1   0.035       0  3405.7    0.16       0  3548.6    0.07       0
  3697.7    0.16       0  4195.2    0.07       0  4976.3    0.07       0
  4997.3    0.07       0  6020.4   0.035       0  6023.5    0.07       0
Bank Sta=4976.3,4997.3
Exp/Cntr=0.3,0.1

Type RM Length L Ch R = 1,11000,500,500,500
BEGIN DESCRIPTION:
Linn Creek Trib066 20.0
END DESCRIPTION:
XS GIS Cut Line= 4
      1328723.94      6892111.09      1330587.35      6892905.35
      1330705.16      6892827.01      1331332.99      6891401.33
#Sta/Elev= 30
  2832.9 2191.85  2984.4 2191.70  3158.3 2190.72  3378.2 2188.89  4000.9 2185.56
  4141.0 2184.45  4687.6 2181.87  4758.1 2181.53  4834.2 2177.83  4963.8 2176.61
  4965.9 2171.24  4966.4 2170.74  4987.0 2171.24  4991.5 2172.80  5002.2 2172.75
  5008.2 2176.47  5024.9 2178.61  5042.6 2181.73  5110.9 2182.81  5468.8 2189.70
  5658.6 2189.38  5978.3 2193.57  5985.4 2192.65  5995.5 2192.87  6037.0 2197.70
  6069.7 2192.53  6082.5 2192.08  6135.3 2195.76  6158.0 2193.73  6557.8 2194.38
#Mann=13,-1,0
  2832.9   0.035       0  2984.4    0.16       0  3158.3    0.07       0
  3378.2    0.16       0  4000.9    0.07       0  4141.0    0.16       0
  4687.6    0.07       0  4965.9    0.07       0  4987.0    0.07       0
  5024.9   0.035       0  5110.9    0.07       0  5985.4   0.035       0
  5995.5    0.07       0
Bank Sta=4965.9,4987
Exp/Cntr=0.3,0.1

Type RM Length L Ch R = 1,10500,528,528,528
BEGIN DESCRIPTION:
Linn Creek Trib066 19.0
END DESCRIPTION:
XS GIS Cut Line= 4
      1329001.66      6892310.71      1330935.47      6893199.96
      1331050.86      6893138.10      1331654.90      6891877.10
#Sta/Elev= 30
  2740.6 2190.79  2765.8 2190.73  3020.6 2188.36  4380.9 2180.52  4625.5 2179.52
  4673.8 2179.75  4772.2 2178.96  4857.7 2175.16  4972.4 2175.61  4988.7 2173.22
  4989.0 2168.09  4989.5 2167.59  5010.1 2168.09  5011.2 2171.92  5018.9 2174.35
  5077.7 2182.05  5310.0 2178.22  5571.7 2181.34  5632.1 2177.73  5964.7 2181.14
  5992.9 2184.03  6015.6 2189.51  6021.1 2193.02  6031.3 2193.35  6038.2 2188.45
  6043.8 2192.16  6060.9 2184.99  6128.9 2181.78  6202.4 2185.34  6398.2 2188.04
#Mann=11,-1,0
  2740.6    0.16       0  2765.8    0.07       0  3020.6    0.16       0
  4380.9    0.07       0  4625.5   0.035       0  4673.8    0.07       0
  4772.2   0.035       0  4989.0   0.035       0  5010.1   0.035       0
  5310.0    0.07       0  5571.7   0.035       0
Bank Sta=4989,5010.1
Exp/Cntr=0.3,0.1

Type RM Length L Ch R = 1,9972,449,449,449
BEGIN DESCRIPTION:
Linn Creek Trib066 18.0
END DESCRIPTION:
XS GIS Cut Line= 4
      1328984.33      6892362.81      1330598.91      6893430.52
      1330925.73      6893561.14      1331897.97      6892206.95
#Sta/Elev= 30
  2938.4 2190.52  2987.9 2190.71  3315.0 2187.81  3401.6 2187.17  3635.1 2185.09
  4469.3 2179.71  4711.5 2178.31  4966.9 2172.91  4975.2 2166.19  4975.7 2165.69
  4996.3 2166.19  4999.1 2171.67  5009.9 2172.48  5154.2 2174.02  5201.2 2176.51
  5400.5 2175.42  5643.6 2181.83  5744.3 2180.84  5872.0 2174.97  6159.0 2174.44
  6224.4 2180.21  6422.6 2185.37  6539.0 2188.79  6582.9 2188.53  6639.4 2194.40
  6668.9 2190.13  6709.6 2191.14  6775.7 2190.01  6790.4 2192.99  6893.1 2194.94
#Mann=13,-1,0
  2938.4    0.16       0  2987.9    0.07       0  3315.0    0.16       0
  3401.6    0.07       0  3635.1    0.16       0  4469.3    0.07       0
  4975.2    0.07       0  4996.3    0.07       0  5154.2   0.035       0
  6159.0    0.07       0  6422.6   0.035       0  6539.0    0.07       0
  6709.6   0.035       0
Bank Sta=4975.2,4996.3
Exp/Cntr=0.3,0.1

Type RM Length L Ch R = 1,9523,150,150,150
BEGIN DESCRIPTION:
Linn Creek Trib066 17.0
END DESCRIPTION:
XS GIS Cut Line= 6
      1328230.52      6892436.43      1329817.37      6893634.38
      1330597.31      6893815.37      1330803.50      6893838.33
      1330960.60      6893825.78      1331796.82      6892623.24
#Sta/Elev= 30
  2002.9 2191.84  2357.7 2191.19  2484.7 2188.65  2604.3 2189.63  4165.2 2177.96
  4644.6 2175.89  4649.7 2174.47  4862.9 2171.44  4920.3 2168.60  4970.6 2171.98
  4980.7 2170.77  4987.0 2164.98  4987.5 2164.48  5008.1 2164.98  5010.8 2170.22
  5057.6 2171.48  5156.6 2174.27  5474.0 2174.50  5488.9 2175.87  5604.8 2177.03
  5852.6 2175.50  5912.2 2171.29  6034.7 2171.33  6036.5 2171.31  6146.0 2173.05
  6171.5 2175.60  6225.8 2177.54  6289.2 2179.46  6620.9 2189.59  6621.6 2189.59
#Mann=12,-1,0
  2002.9   0.035       0  2604.3    0.07       0  4987.0    0.07       0
  5008.1    0.07       0  5057.6   0.035       0  5852.6    0.07       0
  6034.7   0.035       0  6036.5    0.07       0  6146.0   0.035       0
  6225.8    0.07       0  6289.2   0.035       0  6620.9    0.07       0
Bank Sta=4987,5008.1
Exp/Cntr=0.3,0.1

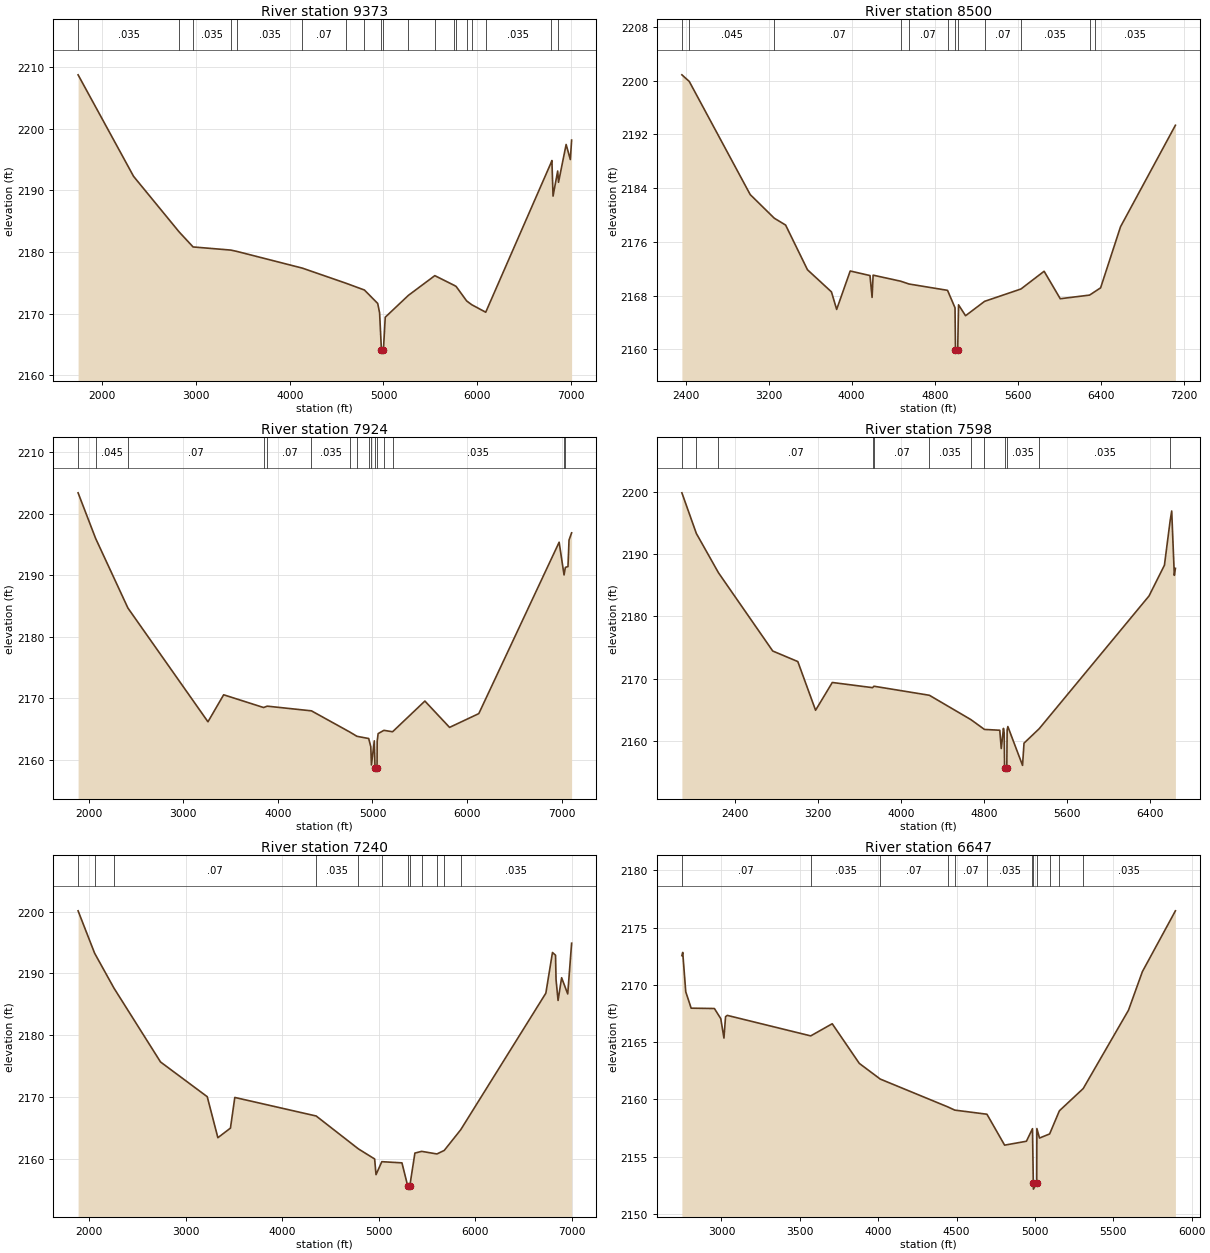
Type RM Length L Ch R = 1,9373,873,873,873
BEGIN DESCRIPTION:
Linn Creek Trib066 16.0
END DESCRIPTION:
XS GIS Cut Line= 5
      1327677.62      6893276.74      1330760.07      6893982.03
      1330855.13      6893972.92      1331086.90      6893958.60
      1332005.01      6892437.99
#Sta/Elev= 30
  1741.2 2208.72  2333.5 2192.26  2820.4 2183.24  2968.4 2180.82  3372.0 2180.31
  3435.4 2180.10  4133.8 2177.39  4599.8 2174.94  4796.5 2173.84  4938.4 2171.66
  4958.5 2170.13  4978.0 2164.11  4978.5 2163.61  4999.2 2164.11  5018.7 2169.43
  5265.5 2172.97  5547.7 2176.17  5755.6 2174.59  5774.9 2174.42  5887.3 2172.07
  5941.3 2171.46  6090.8 2170.24  6787.1 2194.44  6797.0 2194.83  6809.3 2189.06
  6858.8 2193.13  6867.6 2191.30  6948.9 2197.43  6993.7 2194.99  7007.3 2198.14
#Mann=19,-1,0
  1741.2   0.035       0  2820.4    0.07       0  2968.4   0.035       0
  3372.0    0.07       0  3435.4   0.035       0  4133.8    0.07       0
  4599.8   0.035       0  4796.5    0.07       0  4978.0    0.07       0
  4999.2    0.07       0  5265.5   0.035       0  5547.7    0.07       0
  5755.6   0.035       0  5774.9    0.07       0  5887.3   0.035       0
  5941.3    0.07       0  6090.8   0.035       0  6787.1    0.07       0
  6858.8   0.035       0
Bank Sta=4978,4999.2
Exp/Cntr=0.3,0.1

Type RM Length L Ch R = 1,8500,576,576,576
BEGIN DESCRIPTION:
Linn Creek Trib066 15.0
END DESCRIPTION:
XS GIS Cut Line= 4
      1328599.30      6894941.35      1331119.08      6894745.42
      1331209.58      6894687.57      1331904.99      6892688.04
#Sta/Elev= 30
  2365.2 2200.87  2436.4 2199.88  3022.9 2183.04  3254.8 2179.52  3363.9 2178.50
  3574.5 2171.84  3805.2 2168.55  3855.4 2165.94  3985.8 2171.66  4176.4 2170.98
  4196.4 2167.73  4206.4 2171.04  4471.7 2170.14  4552.6 2169.72  4922.8 2168.78
  4995.0 2166.18  4999.5 2159.93  5000.0 2159.43  5020.7 2159.93  5028.9 2166.62
  5096.4 2165.00  5279.6 2167.14  5629.8 2168.98  5852.8 2171.62  6008.3 2167.53
  6290.3 2168.07  6339.5 2168.57  6396.7 2169.15  6588.6 2178.25  7117.0 2193.36
#Mann=12,-1,0
  2365.2   0.035       0  2436.4   0.045       0  3254.8    0.07       0
  4471.7   0.035       0  4552.6    0.07       0  4922.8   0.035       0
  4999.5   0.035       0  5020.7   0.035       0  5279.6    0.07       0
  5629.8   0.035       0  6290.3    0.07       0  6339.5   0.035       0
Bank Sta=4999.5,5020.7
Exp/Cntr=0.3,0.1

Type RM Length L Ch R = 1,7924,326,326,326
BEGIN DESCRIPTION:
Linn Creek Trib066 14.0
END DESCRIPTION:
XS GIS Cut Line= 4
      1328799.00      6895184.40      1331646.11      6894826.07
      1331541.94      6894020.52      1331979.66      6892551.79
#Sta/Elev= 30
  1889.9 2203.41  2074.9 2196.01  2416.5 2184.68  3262.1 2166.19  3427.9 2170.58
  3849.7 2168.51  3888.7 2168.73  4355.6 2167.97  4759.0 2164.54  4836.3 2163.83
  4960.4 2163.47  4982.5 2162.15  4989.4 2159.17  5019.7 2163.10  5027.3 2158.67
  5027.8 2158.17  5048.5 2158.67  5049.9 2163.00  5060.0 2164.27  5121.1 2164.80
  5212.7 2164.57  5554.1 2169.56  5814.8 2165.28  6123.7 2167.52  6972.6 2195.38
  7024.4 2190.06  7038.5 2191.29  7065.9 2191.42  7077.0 2195.73  7104.3 2196.90
#Mann=16,-1,0
  1889.9   0.035       0  2074.9   0.045       0  2416.5    0.07       0
  3849.7   0.035       0  3888.7    0.07       0  4355.6   0.035       0
  4759.0    0.07       0  4836.3   0.035       0  4960.4    0.07       0
  4982.5   0.035       0  5027.3   0.035       0  5048.5   0.035       0
  5121.1    0.07       0  5212.7   0.035       0  7024.4    0.07       0
  7038.5   0.035       0
Bank Sta=5027.3,5048.5
Exp/Cntr=0.3,0.1

Type RM Length L Ch R = 1,7598,358,358,358
BEGIN DESCRIPTION:
Linn Creek Trib066 13.0
END DESCRIPTION:
XS GIS Cut Line= 5
      1328945.34      6895248.76      1331636.56      6894940.22
      1331921.28      6894653.76      1332174.75      6894365.57
      1332591.41      6893178.09
#Sta/Elev= 30
  1887.0 2199.81  2026.3 2193.30  2239.3 2187.01  2762.4 2174.47  3003.9 2172.78
  3175.0 2164.98  3336.1 2169.43  3724.2 2168.60  3737.1 2168.83  4271.6 2167.38
  4671.8 2163.48  4801.9 2161.91  4949.9 2161.78  4964.0 2158.85  4985.2 2162.08
  4992.3 2161.35  4996.2 2155.73  4996.7 2155.23  5017.4 2155.73  5020.7 2161.81
  5027.7 2162.37  5169.1 2156.15  5183.3 2159.71  5329.8 2162.03  6387.7 2183.29
  6536.1 2188.21  6592.0 2195.43  6606.3 2196.90  6631.5 2186.59  6642.0 2187.71
#Mann=12,-1,0
  1887.0   0.035       0  2026.3   0.045       0  2239.3    0.07       0
  3724.2   0.035       0  3737.1    0.07       0  4271.6   0.035       0
  4671.8    0.07       0  4801.9   0.035       0  4996.2   0.035       0
  5017.4   0.035       0  5329.8   0.035       0  6592.0    0.07       0
Bank Sta=4996.2,5017.4
Exp/Cntr=0.3,0.1

Type RM Length L Ch R = 1,7240,593,593,593
BEGIN DESCRIPTION:
Linn Creek Trib066 12.0
END DESCRIPTION:
XS GIS Cut Line= 4
      1328919.36      6895248.76      1331931.10      6895052.26
      1332292.81      6894685.01      1332792.79      6893185.06
#Sta/Elev= 30
  1882.8 2200.11  2054.2 2193.25  2254.9 2187.60  2737.2 2175.66  3221.3 2170.04
  3331.5 2163.41  3461.8 2164.96  3507.0 2169.92  4350.3 2166.92  4787.8 2161.60
  4956.2 2159.97  4970.4 2157.43  5030.6 2159.53  5239.1 2159.34  5299.2 2155.59
  5299.7 2155.09  5320.4 2155.59  5373.4 2160.92  5443.1 2161.20  5601.8 2160.78
  5677.5 2161.35  5848.4 2164.70  6730.6 2186.79  6799.2 2193.37  6830.8 2192.93
  6836.3 2188.97  6857.1 2185.61  6894.0 2189.29  6957.3 2186.66  6997.5 2194.87
#Mann=12,-1,0
  1882.8   0.035       0  2054.2   0.045       0  2254.9    0.07       0
  4350.3   0.035       0  4787.8    0.07       0  5030.6   0.035       0
  5299.2    0.07       0  5320.4   0.035       0  5443.1    0.07       0
  5601.8   0.035       0  5677.5    0.07       0  5848.4   0.035       0
Bank Sta=5299.2,5320.4
Exp/Cntr=0.3,0.1

Type RM Length L Ch R = 1,6647,1147,1147,1147
BEGIN DESCRIPTION:
Linn Creek Trib066 11.0
END DESCRIPTION:
XS GIS Cut Line= 5
      1330540.83      6895182.78      1331853.36      6895417.16
      1332389.82      6894958.83      1332540.86      6894661.96
      1332605.00      6893887.98
#Sta/Elev= 30
  2747.8 2172.55  2753.1 2172.83  2772.4 2169.39  2806.9 2167.96  2955.2 2167.93
  2995.8 2167.05  3016.1 2165.35  3026.3 2167.22  3037.5 2167.33  3569.7 2165.54
  3706.9 2166.60  3879.6 2163.14  4013.2 2161.77  4444.3 2159.34  4488.6 2159.06
  4694.0 2158.70  4806.8 2156.00  4945.9 2156.34  4984.6 2157.44  4989.9 2152.66
  4990.4 2152.16  5011.6 2152.66  5012.6 2157.45  5029.3 2156.62  5094.0 2156.98
  5156.2 2159.00  5308.1 2160.94  5597.0 2167.78  5685.7 2171.15  5896.4 2176.46
#Mann=12,-1,0
  2747.8    0.07       0  3569.7   0.035       0  4013.2    0.07       0
  4444.3   0.035       0  4488.6    0.07       0  4694.0   0.035       0
  4984.6    0.07       0  4989.9    0.07       0  5011.6    0.07       0
  5094.0   0.035       0  5156.2    0.07       0  5308.1   0.035       0
Bank Sta=4989.9,5011.6
Exp/Cntr=0.3,0.1

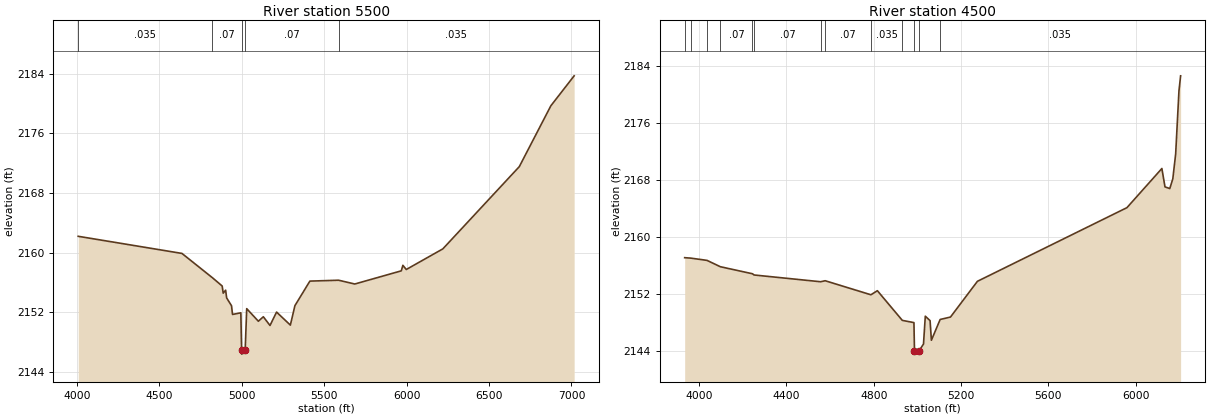
Type RM Length L Ch R = 1,5500,1000,1000,1000
BEGIN DESCRIPTION:
Linn Creek Trib066 9.0
END DESCRIPTION:
XS GIS Cut Line= 4
      1331714.39      6895511.73      1332526.85      6895768.66
      1332641.91      6895687.20      1332905.00      6893688.03
#Sta/Elev= 30
  4006.9 2162.18  4636.4 2159.88  4821.6 2156.61  4880.6 2155.50  4886.8 2154.54
  4901.5 2154.94  4907.7 2153.90  4937.2 2152.85  4943.3 2151.68  4993.8 2151.90
  4998.4 2146.85  4998.9 2146.35  5020.1 2146.85  5029.4 2152.46  5100.1 2150.77
  5130.3 2151.37  5170.7 2150.20  5210.6 2152.00  5294.3 2150.25  5321.9 2152.86
  5412.7 2156.16  5587.0 2156.28  5685.1 2155.77  5967.5 2157.54  5977.1 2158.28
  5997.7 2157.72  6219.6 2160.49  6683.6 2171.54  6875.2 2179.72  7016.4 2183.74
#Mann=5,-1,0
  4006.9   0.035       0  4821.6    0.07       0  4998.4    0.07       0
  5020.1    0.07       0  5587.0   0.035       0
Bank Sta=4998.4,5020.1
Exp/Cntr=0.3,0.1

Type RM Length L Ch R = 1,4500,603,603,603
BEGIN DESCRIPTION:
Linn Creek Trib066 7.0
END DESCRIPTION:
XS GIS Cut Line= 4
      1332471.30      6895970.05      1333056.60      6895588.91
      1333196.06      6895248.32      1333854.99      6894238.01
#Sta/Elev= 30
  3933.5 2157.05  3960.8 2156.99  4035.9 2156.67  4097.0 2155.78  4244.2 2154.79
  4251.5 2154.62  4556.2 2153.67  4577.4 2153.81  4786.9 2151.84  4816.6 2152.41
  4930.9 2148.24  4984.1 2147.93  4986.6 2144.00  4987.1 2143.50  5008.4 2144.00
  5027.9 2144.92  5036.2 2148.83  5058.1 2148.20  5064.1 2145.45  5104.3 2148.37
  5151.6 2148.71  5275.0 2153.73  5960.3 2164.08  6120.3 2169.58  6134.6 2167.00
  6156.5 2166.76  6170.4 2168.12  6183.5 2171.62  6198.6 2180.48  6206.2 2182.60
#Mann=13,-1,0
  3933.5   0.035       0  3960.8    0.07       0  4035.9   0.035       0
  4097.0    0.07       0  4244.2   0.035       0  4251.5    0.07       0
  4556.2   0.035       0  4577.4    0.07       0  4786.9   0.035       0
  4930.9    0.07       0  4986.6    0.07       0  5008.4    0.07       0
  5104.3   0.035       0
Bank Sta=4986.6,5008.4
Exp/Cntr=0.3,0.1