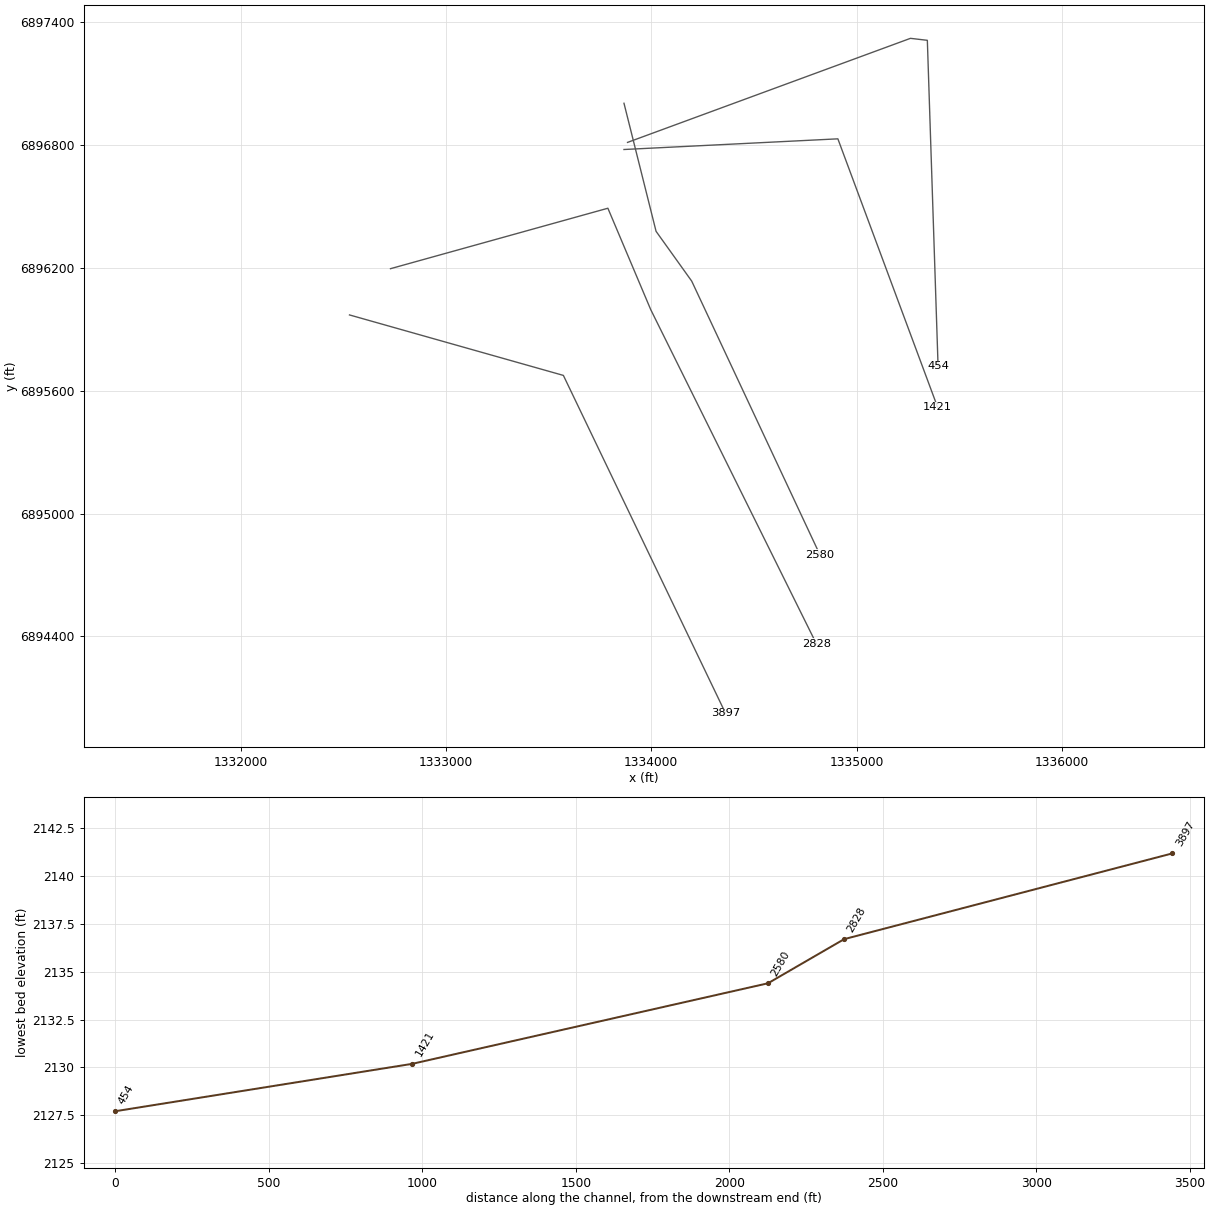
HEC-RAS study Linn Creek Trib066.prj: Linn Creek Trib066 Base Level Engineering

--- Linn Creek Trib066.g01 (geometry) --- (continued)

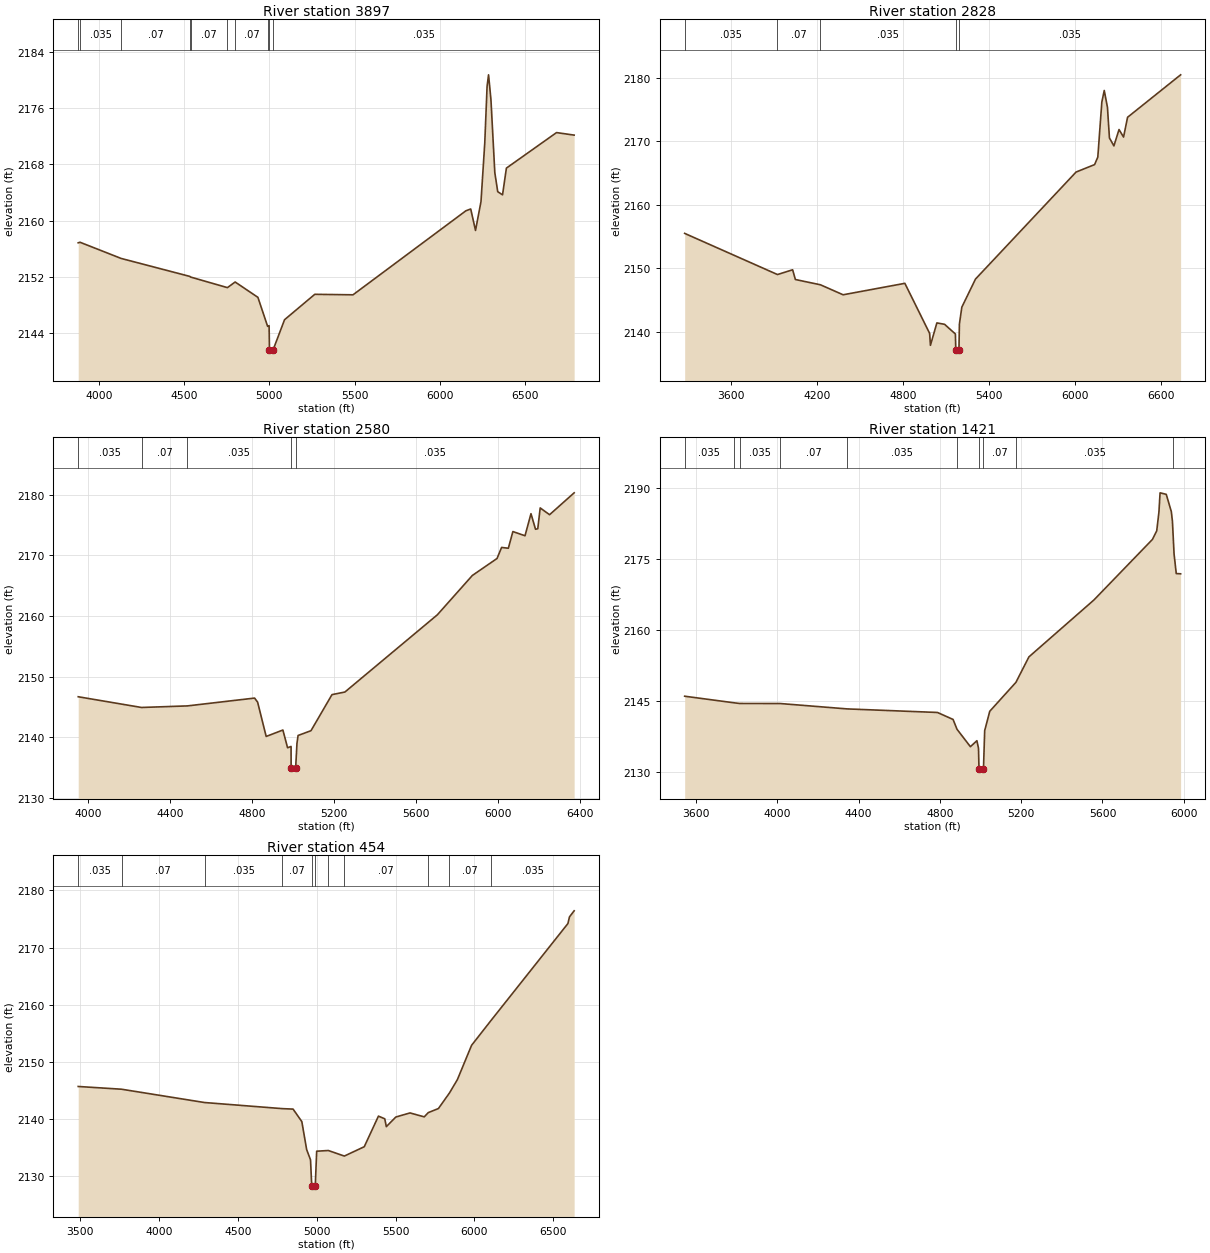
Type RM Length L Ch R = 1,3897,1069,1069,1069
BEGIN DESCRIPTION:
Linn Creek Trib066 6.0
END DESCRIPTION:
XS GIS Cut Line= 3
      1332530.45      6895969.25      1333572.11      6895674.11
      1334362.05      6894024.79
#Sta/Elev= 30
  3877.7 2156.84  3888.3 2156.92  4129.7 2154.62  4532.2 2152.07  4538.0 2151.97
  4753.7 2150.47  4799.0 2151.27  4932.6 2149.09  4989.7 2144.96  4998.3 2145.07
  5000.5 2141.66  5001.0 2141.16  5022.4 2141.66  5089.0 2145.91  5266.5 2149.52
  5490.9 2149.45  6153.5 2161.39  6181.9 2161.65  6210.1 2158.60  6242.2 2162.70
  6264.4 2171.04  6278.0 2179.09  6286.6 2180.72  6300.7 2177.18  6323.4 2166.81
  6340.5 2164.11  6368.7 2163.66  6391.4 2167.46  6685.7 2172.51  6789.1 2172.15
#Mann=10,-1,0
  3877.7    0.07       0  3888.3   0.035       0  4129.7    0.07       0
  4532.2   0.035       0  4538.0    0.07       0  4753.7   0.035       0
  4799.0    0.07       0  4989.7   0.035       0  5000.5   0.035       0
  5022.4   0.035       0
Bank Sta=5000.5,5022.4
Exp/Cntr=0.3,0.1

Type RM Length L Ch R = 1,2828,248,248,248
BEGIN DESCRIPTION:
Linn Creek Trib066 5.0
END DESCRIPTION:
XS GIS Cut Line= 4
      1332730.10      6896194.94      1333788.85      6896489.97
      1333997.45      6895995.29      1334804.76      6894363.31
#Sta/Elev= 30
  3277.9 2155.51  3924.7 2149.04  4030.4 2149.79  4049.5 2148.26  4224.2 2147.43
  4382.2 2145.86  4812.6 2147.66  4985.3 2139.79  4990.9 2137.92  5035.7 2141.44
  5089.3 2141.22  5164.8 2139.70  5167.6 2137.19  5168.1 2136.69  5189.5 2137.19
  5192.8 2141.26  5209.6 2143.91  5304.9 2148.33  6006.0 2165.15  6135.0 2166.32
  6157.4 2167.50  6185.4 2176.13  6202.3 2177.97  6224.7 2175.32  6238.5 2170.51
  6269.6 2169.26  6305.4 2171.83  6336.9 2170.65  6364.9 2173.76  6734.6 2180.43
#Mann=5,-1,0
  3277.9   0.035       0  3924.7    0.07       0  4224.2   0.035       0
  5167.6   0.035       0  5189.5   0.035       0
Bank Sta=5167.6,5189.5
Exp/Cntr=0.3,0.1

Type RM Length L Ch R = 1,2580,1159,1159,1159
BEGIN DESCRIPTION:
Linn Creek Trib066 4.0
END DESCRIPTION:
XS GIS Cut Line= 4
      1333867.24      6897002.26      1334023.50      6896377.23
      1334197.11      6896134.18      1334822.13      6894797.33
#Sta/Elev= 30
  3952.0 2146.66  4260.7 2144.89  4484.8 2145.15  4812.1 2146.44  4826.9 2145.78
  4868.7 2140.11  4950.2 2141.17  4973.1 2138.25  4990.1 2138.46  4990.4 2134.89
  4990.9 2134.39  5012.5 2134.89  5018.8 2138.96  5024.3 2140.27  5087.3 2141.06
  5189.7 2147.01  5252.7 2147.44  5703.3 2160.17  5874.3 2166.67  5994.6 2169.47
  6016.9 2171.29  6049.8 2171.16  6071.9 2173.91  6131.1 2173.22  6160.2 2176.86
  6182.3 2174.29  6193.3 2174.38  6205.1 2177.81  6250.8 2176.69  6370.7 2180.30
#Mann=5,-1,0
  3952.0   0.035       0  4260.7    0.07       0  4484.8   0.035       0
  4990.4   0.035       0  5012.5   0.035       0
Bank Sta=4990.4,5012.5
Exp/Cntr=0.3,0.1

Type RM Length L Ch R = 1,1421,967,967,967
BEGIN DESCRIPTION:
Linn Creek Trib066 2.0
END DESCRIPTION:
XS GIS Cut Line= 3
      1333867.22      6896776.54      1334908.91      6896828.62
      1335395.03      6895517.85
#Sta/Elev= 30
  3543.8 2146.00  3785.2 2144.62  3813.8 2144.47  4012.8 2144.46  4344.5 2143.32
  4788.0 2142.57  4864.8 2141.10  4884.3 2139.02  4950.1 2135.35  4982.1 2136.61
  4990.0 2135.01  4992.4 2130.69  4992.9 2130.19  5014.5 2130.69  5020.4 2138.73
  5045.4 2142.82  5174.2 2148.93  5238.1 2154.30  5558.0 2166.31  5846.0 2179.09
  5867.3 2180.92  5878.0 2184.84  5883.7 2188.93  5914.1 2188.61  5939.1 2184.96
  5944.5 2182.94  5949.4 2178.75  5952.6 2176.02  5963.3 2171.89  5984.8 2171.84
#Mann=10,-1,0
  3543.8   0.035       0  3785.2    0.07       0  3813.8   0.035       0
  4012.8    0.07       0  4344.5   0.035       0  4884.3    0.07       0
  4992.4    0.07       0  5014.5    0.07       0  5174.2   0.035       0
  5949.4    0.07       0
Bank Sta=4992.4,5014.5
Exp/Cntr=0.3,0.1

Type RM Length L Ch R = 1,454,0,0,0
BEGIN DESCRIPTION:
Linn Creek Trib066 1.0
END DESCRIPTION:
XS GIS Cut Line= 4
      1333884.56      6896811.25      1335262.46      6897319.07
      1335344.64      6897309.38      1335396.94      6895718.39
#Sta/Elev= 30
  3488.9 2145.69  3763.4 2145.21  4289.6 2142.88  4782.9 2141.81  4850.6 2141.73
  4906.2 2139.54  4936.7 2134.64  4961.2 2132.85  4969.0 2128.22  4969.5 2127.72
  4991.2 2128.22  5000.2 2134.36  5074.1 2134.48  5175.5 2133.51  5301.7 2135.14
  5391.7 2140.50  5431.7 2140.03  5441.7 2138.66  5501.8 2140.34  5591.8 2141.06
  5681.9 2140.37  5707.3 2141.11  5771.9 2141.83  5841.9 2144.56  5892.0 2146.89
  5982.0 2152.90  6103.6 2157.19  6592.4 2174.21  6602.4 2175.38  6632.0 2176.44
#Mann=11,-1,0
  3488.9   0.035       0  3763.4    0.07       0  4289.6   0.035       0
  4782.9    0.07       0  4969.0    0.07       0  4991.2    0.07       0
  5074.1   0.035       0  5175.5    0.07       0  5707.3   0.035       0
  5841.9    0.07       0  6103.6   0.035       0
Bank Sta=4969,4991.2
Exp/Cntr=0.3,0.1

Chan Stop Cuts=-1