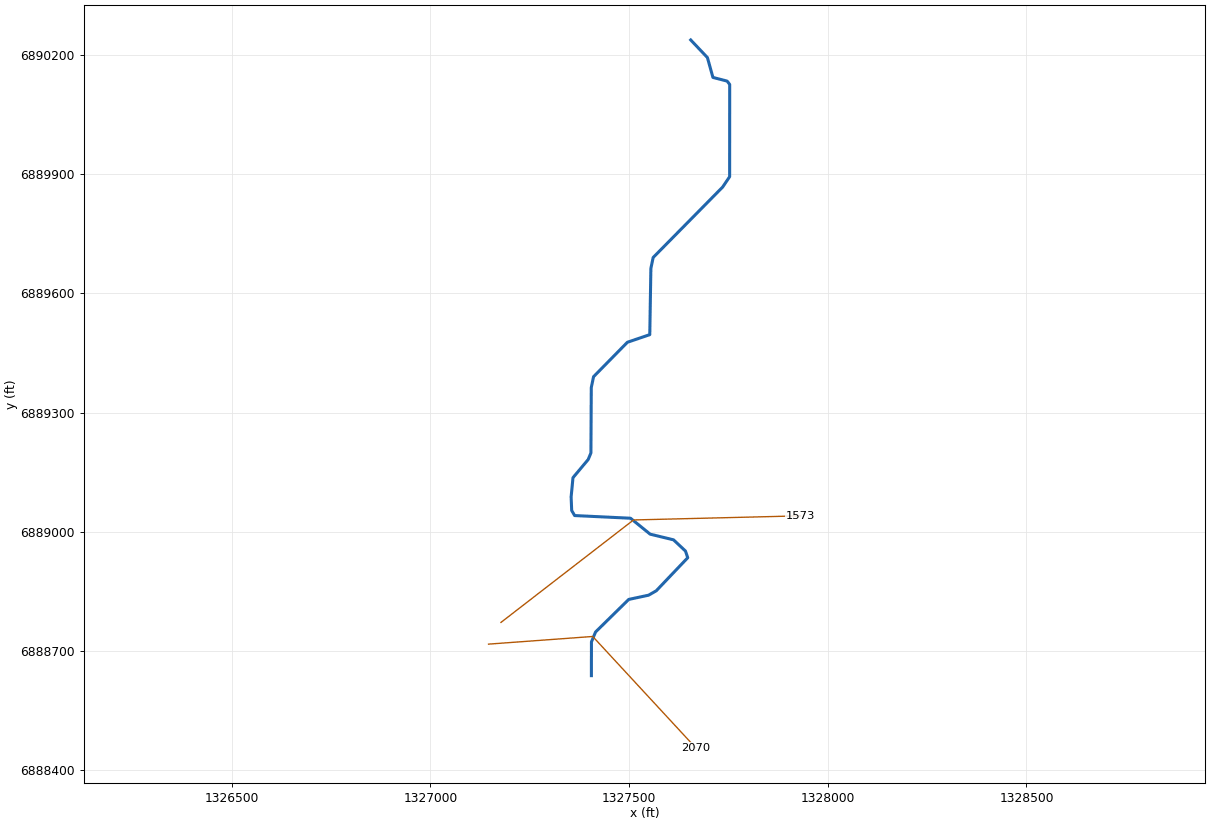
--- Linn Creek Trib066_11.prj (project) ---

Proj Title=Linn Creek Trib066_11 Base Level Engineering
Current Plan=p01
Default Exp/Contr=0.3,0.1
English Units
Geom File=g01
Flow File=f01
Plan File=p01
BEGIN DESCRIPTION:
Linn Creek Trib066_11
END DESCRIPTION:

--- Linn Creek Trib066_11.p01 (plan) ---

Plan Title=Multiple Run
Short Identifier=Multiple
Geom File=g01
Flow File=f01
Subcritical Flow
K Sum by GR= 0
Std Step Tol= 0.01
Critical Tol= 0.01
Num of Std Step Trials= 20
Max Error Tol= 0.3
Flow Tol Ratio= 0.001
Split Flow NTrial= 30
Split Flow Tol= 0.02
Split Flow Ratio= 0.02
Log Output Level= 0
Friction Slope Method= 1
Unsteady Friction Slope Method= 2
Unsteady Bridges Friction Slope Method= 1
Parabolic Critical Depth
Global Vel Dist=  1 , 1 , 1
Global Log Level= 0
CheckData=True
Encroach Param= -1, 0, 0, 0
BEGIN DESCRIPTION:
Multiple Run
END DESCRIPTION:

--- Linn Creek Trib066_11.f01 (steady flow) ---

Flow Title=Multiple
Number of Profiles=7
Profile Names=10-year,25-year,50-year,1pct_min,100-year,1pct_plu,500-year
River Rch & RM= Linn Creek Trib0,Reach-1,2070
     296     428     541     340     679    1354    1083
Boundary for River Rch & Prof#=Linn Creek Trib0,Reach-1,1
Up Type=0
Dn Type=3
Dn Slope=0.005
Boundary for River Rch & Prof#=Linn Creek Trib0,Reach-1,2
Up Type=0
Dn Type=3
Dn Slope=0.005
Boundary for River Rch & Prof#=Linn Creek Trib0,Reach-1,3
Up Type=0
Dn Type=3
Dn Slope=0.005
Boundary for River Rch & Prof#=Linn Creek Trib0,Reach-1,4
Up Type=0
Dn Type=3
Dn Slope=0.005
Boundary for River Rch & Prof#=Linn Creek Trib0,Reach-1,5
Up Type=0
Dn Type=3
Dn Slope=0.005
Boundary for River Rch & Prof#=Linn Creek Trib0,Reach-1,6
Up Type=0
Dn Type=3
Dn Slope=0.005
Boundary for River Rch & Prof#=Linn Creek Trib0,Reach-1,7
Up Type=0
Dn Type=3
Dn Slope=0.005

--- Linn Creek Trib066_11.g01 (geometry) ---

Geom Title=Existing Conditions

River Reach=Linn Creek Trib0,Reach-1
Reach XY= 30
      1327405.00      6888638.00      1327405.11      6888722.96
      1327415.42      6888747.84      1327498.93      6888829.85
      1327548.97      6888840.54      1327568.27      6888851.63
      1327647.50      6888934.84      1327641.74      6888951.68
      1327611.72      6888979.86      1327552.88      6888994.14
      1327503.44      6889034.24      1327362.85      6889040.94
      1327355.40      6889053.60      1327353.97      6889087.55
      1327358.67      6889136.32      1327396.85      6889181.94
      1327403.78      6889198.50      1327404.71      6889363.12
      1327410.46      6889390.47      1327495.60      6889477.10
      1327551.93      6889496.30      1327554.71      6889663.12
      1327560.46      6889690.45      1327735.40      6889867.84
      1327752.94      6889893.85      1327753.10      6890126.07
      1327746.54      6890134.50      1327710.92      6890143.71
      1327696.96      6890193.73      1327655.00      6890238.00

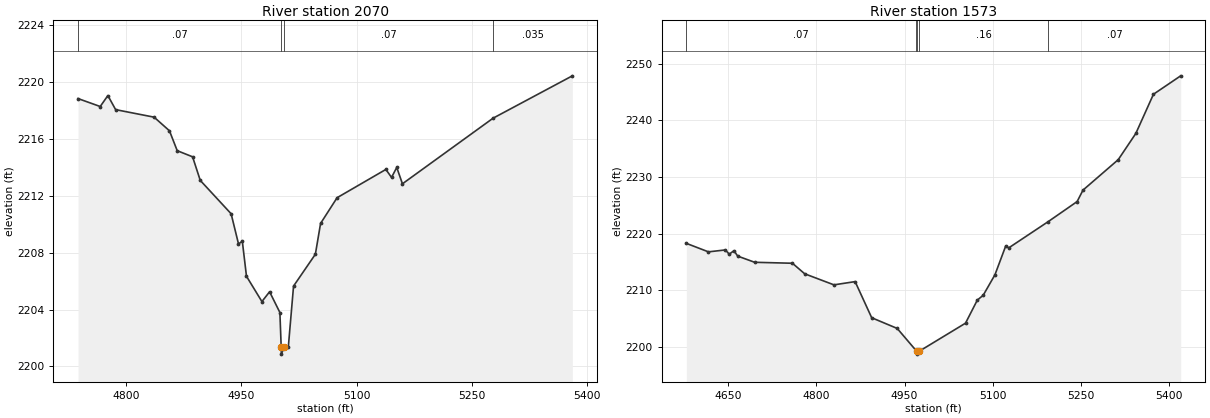
Type RM Length L Ch R = 1,2070,497,497,497
BEGIN DESCRIPTION:
Linn Creek Trib066_11 2.0
END DESCRIPTION:
XS GIS Cut Line= 3
      1327146.18      6888717.36      1327408.38      6888736.61
      1327667.01      6888456.98
#Sta/Elev= 30
  4737.1 2218.85  4766.0 2218.29  4776.0 2219.06  4786.1 2218.07  4836.2 2217.54
  4856.2 2216.58  4866.3 2215.18  4886.3 2214.75  4896.3 2213.09  4936.5 2210.74
  4946.1 2208.62  4951.1 2208.80  4956.5 2206.34  4976.6 2204.56  4986.6 2205.25
  5000.0 2203.79  5001.7 2201.36  5001.9 2200.86  5005.7 2201.36  5011.0 2201.37
  5017.8 2205.65  5046.2 2207.89  5053.0 2210.06  5074.5 2211.87  5138.0 2213.86
  5145.4 2213.30  5152.2 2214.00  5159.6 2212.85  5277.7 2217.47  5380.9 2220.45
#Mann=4,-1,0
  4737.1    0.07       0  5001.7    0.07       0  5005.7    0.07       0
  5277.7   0.035       0
Bank Sta=5001.7,5005.7
Exp/Cntr=0.3,0.1

Type RM Length L Ch R = 1,1573,0,0,0
BEGIN DESCRIPTION:
Linn Creek Trib066_11 1.0
END DESCRIPTION:
XS GIS Cut Line= 3
      1327177.49      6888772.08      1327511.07      6889029.90
      1327931.34      6889040.25
#Sta/Elev= 30
  4578.4 2218.30  4616.0 2216.80  4645.0 2217.14  4651.4 2216.39  4659.5 2217.00
  4665.9 2216.05  4694.8 2214.96  4759.1 2214.79  4780.0 2212.93  4829.8 2210.98
  4865.9 2211.55  4894.1 2205.18  4937.6 2203.29  4968.8 2199.50  4970.9 2199.26
  4971.1 2198.76  4974.9 2199.26  5053.9 2204.22  5074.0 2208.29  5084.0 2209.14
  5104.0 2212.75  5122.5 2217.87  5127.5 2217.50  5194.3 2222.10  5244.0 2225.67
  5254.0 2227.69  5314.0 2233.06  5344.0 2237.69  5374.0 2244.60  5420.4 2247.85
#Mann=5,-1,0
  4578.4    0.07       0  4968.8    0.16       0  4970.9    0.07       0
  4974.9    0.16       0  5194.3    0.07       0
Bank Sta=4970.9,4974.9
Exp/Cntr=0.3,0.1

Chan Stop Cuts=-1