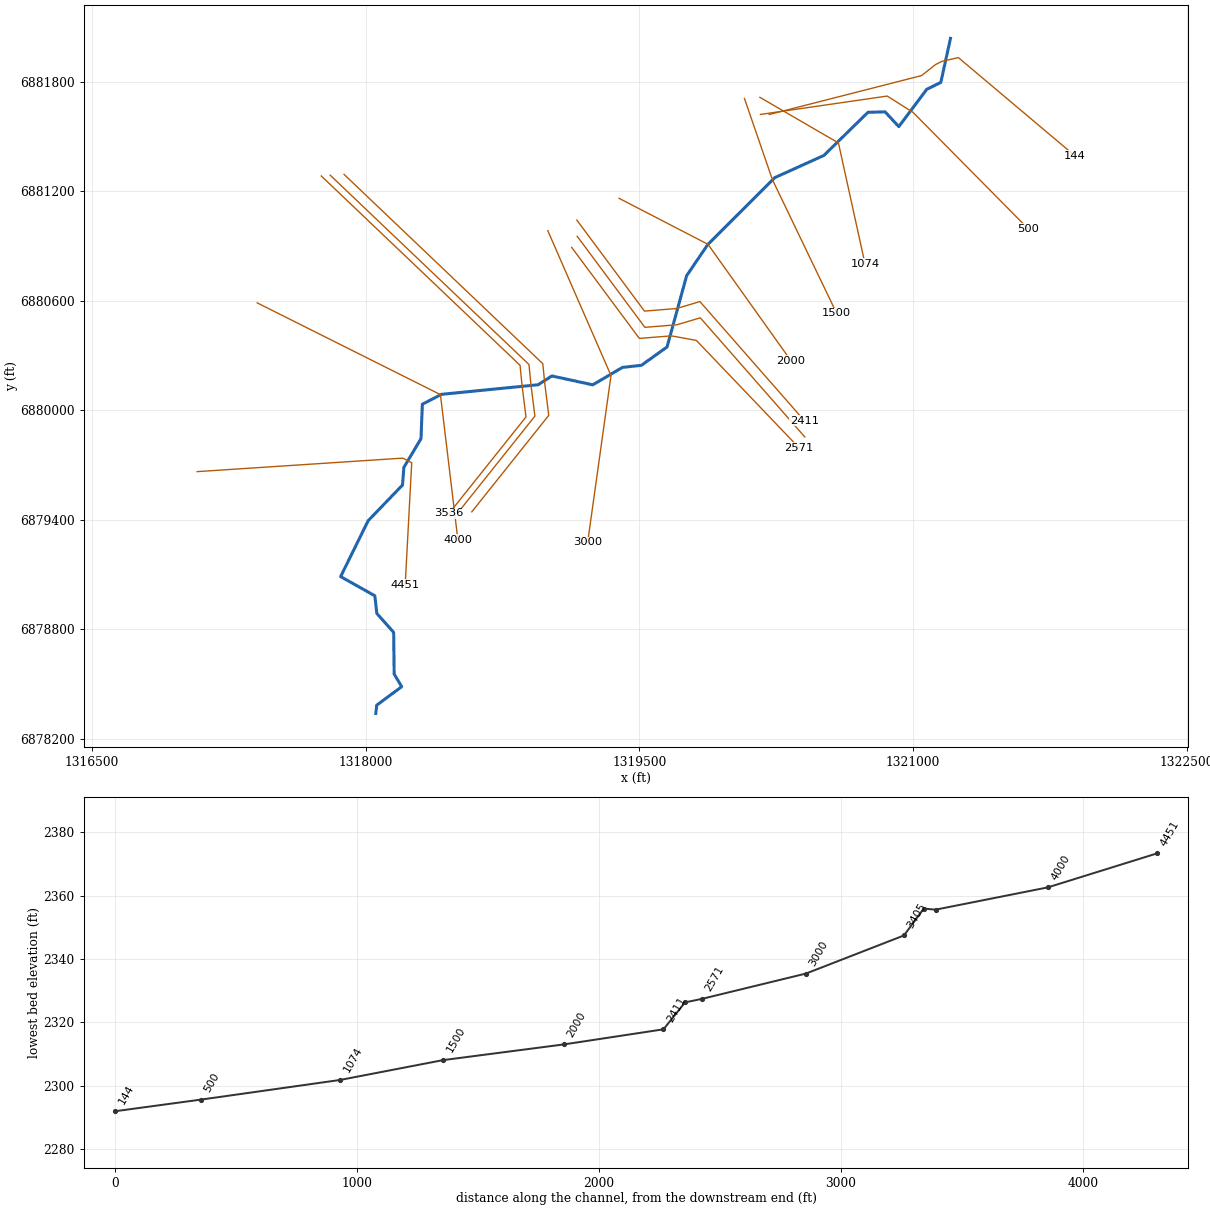
--- Linn Creek Trib066_7.prj (project) ---

Proj Title=Linn Creek Trib066_7 Base Level Engineering
Current Plan=p01
Default Exp/Contr=0.3,0.1
English Units
Geom File=g01
Flow File=f01
Plan File=p01
BEGIN DESCRIPTION:
Linn Creek Trib066_7
END DESCRIPTION:

--- Linn Creek Trib066_7.p01 (plan) ---

Plan Title=Multiple Run
Short Identifier=Multiple
Geom File=g01
Flow File=f01
Subcritical Flow
K Sum by GR= 0
Std Step Tol= 0.01
Critical Tol= 0.01
Num of Std Step Trials= 20
Max Error Tol= 0.3
Flow Tol Ratio= 0.001
Split Flow NTrial= 30
Split Flow Tol= 0.02
Split Flow Ratio= 0.02
Log Output Level= 0
Friction Slope Method= 1
Unsteady Friction Slope Method= 2
Unsteady Bridges Friction Slope Method= 1
Parabolic Critical Depth
Global Vel Dist=  1 , 1 , 1
Global Log Level= 0
CheckData=True
Encroach Param= -1, 0, 0, 0
BEGIN DESCRIPTION:
Multiple Run
END DESCRIPTION:

--- Linn Creek Trib066_7.f01 (steady flow) ---

Flow Title=Multiple
Number of Profiles=7
Profile Names=10-year,25-year,50-year,1pct_min,100-year,1pct_plu,500-year
River Rch & RM= Linn Creek Trib0,Reach-1,4451
     202     277     338     204     408     814     603
River Rch & RM= Linn Creek Trib0,Reach-1,4000
     345     495     621     388     773    1543    1215
River Rch & RM= Linn Creek Trib0,Reach-1,144
     444     645     818     515    1027    2049    1642
Boundary for River Rch & Prof#=Linn Creek Trib0,Reach-1,1
Up Type=0
Dn Type=3
Dn Slope=0.005
Boundary for River Rch & Prof#=Linn Creek Trib0,Reach-1,2
Up Type=0
Dn Type=3
Dn Slope=0.005
Boundary for River Rch & Prof#=Linn Creek Trib0,Reach-1,3
Up Type=0
Dn Type=3
Dn Slope=0.005
Boundary for River Rch & Prof#=Linn Creek Trib0,Reach-1,4
Up Type=0
Dn Type=3
Dn Slope=0.005
Boundary for River Rch & Prof#=Linn Creek Trib0,Reach-1,5
Up Type=0
Dn Type=3
Dn Slope=0.005
Boundary for River Rch & Prof#=Linn Creek Trib0,Reach-1,6
Up Type=0
Dn Type=3
Dn Slope=0.005
Boundary for River Rch & Prof#=Linn Creek Trib0,Reach-1,7
Up Type=0
Dn Type=3
Dn Slope=0.005

--- Linn Creek Trib066_7.g01 (geometry) ---

Geom Title=Existing Conditions

River Reach=Linn Creek Trib0,Reach-1
Reach XY= 30
      1318055.00      6878338.00      1318059.92      6878382.67
      1318197.21      6878484.57      1318155.66      6878553.16
      1318152.93      6878782.14      1318060.56      6878885.64
      1318049.75      6878982.56      1317862.22      6879087.69
      1318013.16      6879394.05      1318201.39      6879589.50
      1318208.83      6879686.41      1318302.76      6879843.93
      1318310.17      6880032.59      1318415.48      6880086.81
      1318944.49      6880139.22      1319020.22      6880187.49
      1319244.32      6880138.75      1319406.59      6880234.17
      1319511.17      6880245.88      1319651.49      6880346.48
      1319758.62      6880736.50      1319874.79      6880908.09
      1320241.79      6881274.38      1320511.06      6881396.14
      1320752.63      6881632.63      1320846.66      6881634.98
      1320921.58      6881554.17      1321074.74      6881758.43
      1321151.90      6881796.31      1321205.00      6882038.00

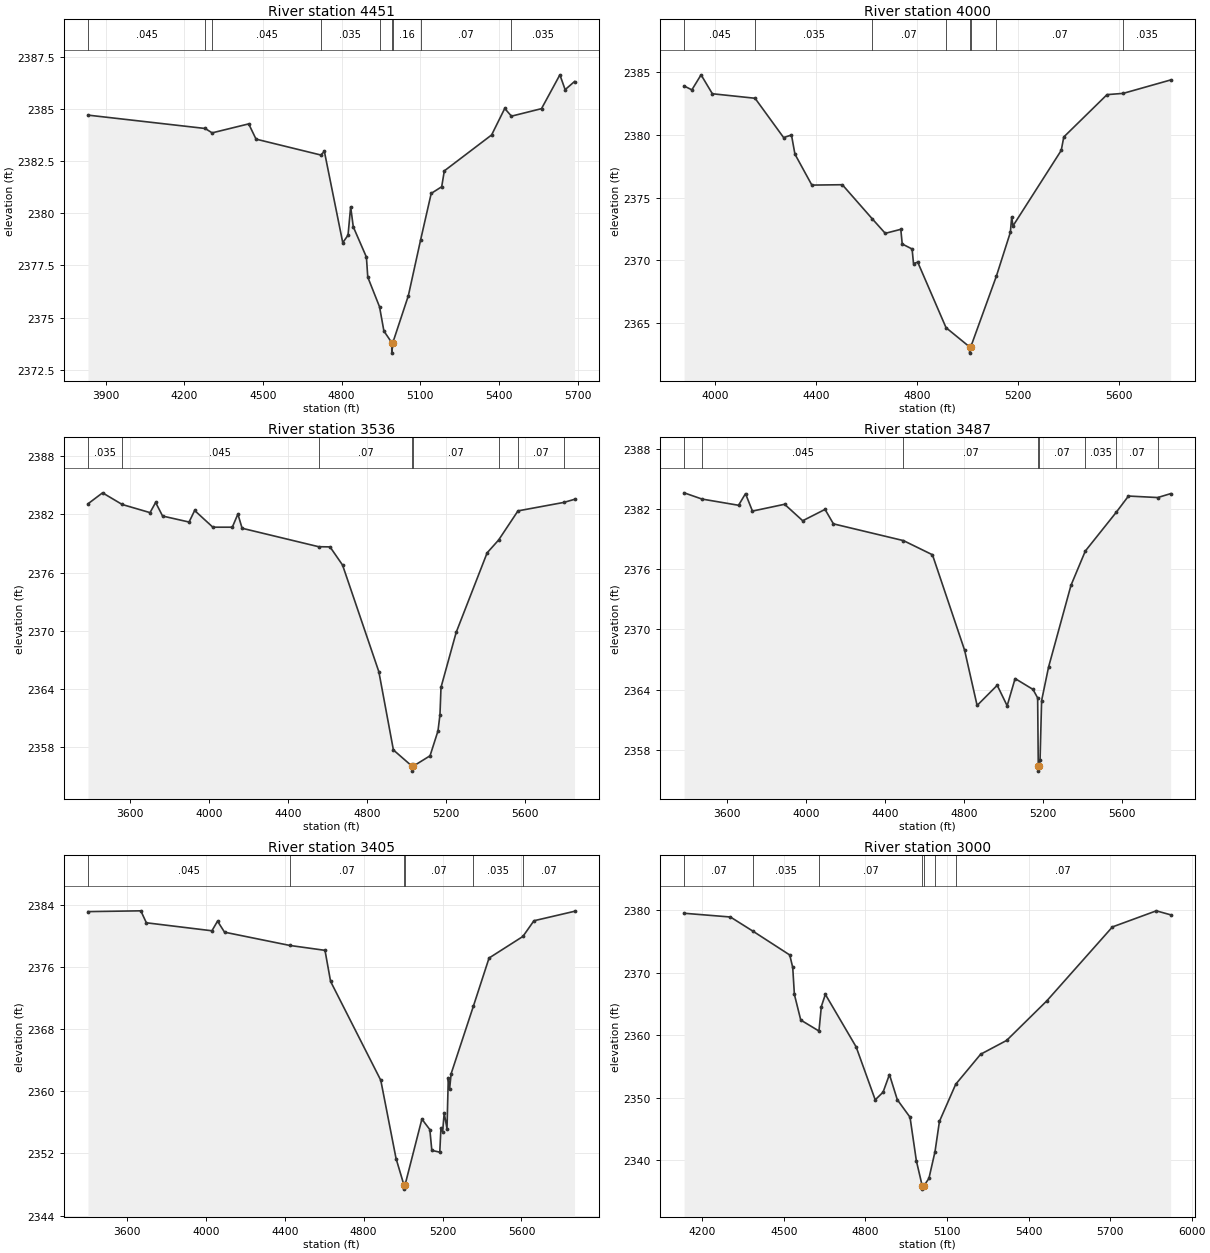
Type RM Length L Ch R = 1,4451,451,451,451
BEGIN DESCRIPTION:
Linn Creek Trib066_7 9.0
END DESCRIPTION:
XS GIS Cut Line= 4
      1317075.57      6879663.01      1318203.05      6879737.12
      1318251.85      6879711.64      1318216.12      6879042.25
#Sta/Elev= 30
  3832.6 2384.70  4279.4 2384.06  4306.0 2383.85  4445.4 2384.28  4473.4 2383.55
  4720.2 2382.79  4734.0 2382.96  4804.1 2378.59  4824.2 2378.95  4834.2 2380.31
  4844.2 2379.35  4894.3 2377.90  4899.5 2376.94  4944.3 2375.52  4961.0 2374.36
  4991.0 2373.80  4991.2 2373.30  4995.0 2373.80  5054.2 2376.05  5101.1 2378.73
  5141.4 2380.95  5181.4 2381.27  5191.4 2382.03  5371.7 2383.75  5421.8 2385.02
  5447.3 2384.65  5562.0 2385.01  5632.1 2386.63  5652.1 2385.92  5687.9 2386.31
#Mann=9,-1,0
  3832.6   0.045       0  4279.4    0.07       0  4306.0   0.045       0
  4720.2   0.035       0  4944.3    0.16       0  4991.0    0.07       0
  4995.0    0.16       0  5101.1    0.07       0  5447.3   0.035       0
Bank Sta=4991,4995
Exp/Cntr=0.3,0.1

Type RM Length L Ch R = 1,4000,464,464,464
BEGIN DESCRIPTION:
Linn Creek Trib066_7 8.0
END DESCRIPTION:
XS GIS Cut Line= 3
      1317404.99      6880588.00      1318409.26      6880085.21
      1318505.00      6879288.04
#Sta/Elev= 30
  3876.9 2383.90  3907.6 2383.59  3944.0 2384.79  3988.7 2383.28  4157.7 2382.92
  4270.9 2379.78  4301.9 2379.99  4315.6 2378.46  4382.6 2375.99  4503.2 2376.02
  4621.6 2373.30  4673.2 2372.14  4734.7 2372.46  4740.3 2371.29  4779.4 2370.89
  4785.0 2369.73  4801.7 2369.84  4913.8 2364.61  5006.8 2363.08  5007.2 2362.58
  5011.7 2363.08  5113.0 2368.72  5168.4 2372.22  5173.7 2373.46  5178.7 2372.73
  5369.8 2378.76  5379.9 2379.83  5551.1 2383.21  5615.0 2383.31  5802.9 2384.38
#Mann=8,-1,0
  3876.9   0.045       0  4157.7   0.035       0  4621.6    0.07       0
  4913.8    0.16       0  5006.8    0.07       0  5011.7    0.16       0
  5113.0    0.07       0  5615.0   0.035       0
Bank Sta=5006.8,5011.7
Exp/Cntr=0.3,0.1

Type RM Length L Ch R = 1,3536,49,49,49
BEGIN DESCRIPTION:
Linn Creek Trib066_7 7.5
END DESCRIPTION:
XS GIS Cut Line= 5
      1317756.16      6881283.67      1318845.64      6880245.97
      1318856.49      6880136.38      1318878.19      6879962.77
      1318456.16      6879433.64
#Sta/Elev= 30
  3386.9 2383.08  3460.8 2384.21  3560.2 2383.01  3701.4 2382.17  3729.8 2383.22
  3765.0 2381.82  3899.3 2381.20  3927.6 2382.39  4019.8 2380.67  4118.5 2380.67
  4146.8 2382.02  4168.2 2380.56  4556.0 2378.66  4613.9 2378.64  4677.4 2376.77
  4861.4 2365.78  4935.2 2357.72  5030.1 2356.04  5030.5 2355.54  5035.0 2356.04
  5120.9 2357.12  5161.2 2359.68  5171.3 2361.36  5176.5 2364.17  5253.5 2369.84
  5410.4 2378.03  5468.6 2379.35  5566.7 2382.35  5798.6 2383.22  5853.4 2383.54
#Mann=8,-1,0
  3386.9   0.035       0  3560.2   0.045       0  4556.0    0.07       0
  5030.1    0.07       0  5035.0    0.07       0  5468.6   0.035       0
  5566.7    0.07       0  5798.6   0.035       0
Bank Sta=5030.1,5035
Exp/Cntr=0.3,0.1

Type RM Length L Ch R = 1,3487,82,82,82
BEGIN DESCRIPTION:
Linn Creek Trib066_7 7.0
END DESCRIPTION:
XS GIS Cut Line= 5
      1317805.03      6881287.97      1318894.47      6880250.31
      1318905.32      6880140.72      1318927.02      6879967.11
      1318505.01      6879438.01
#Sta/Elev= 30
  3382.2 2383.60  3472.7 2382.98  3658.2 2382.36  3693.4 2383.52  3728.6 2381.78
  3891.6 2382.46  3983.4 2380.82  4096.6 2381.95  4139.1 2380.51  4494.2 2378.84
  4641.1 2377.43  4804.0 2367.93  4867.5 2362.42  4969.4 2364.43  5019.8 2362.39
  5060.1 2365.10  5150.8 2364.02  5174.4 2363.17  5177.6 2356.38  5178.0 2355.88
  5182.5 2356.38  5186.5 2356.94  5194.5 2362.91  5229.7 2366.24  5343.4 2374.39
  5416.0 2377.80  5572.7 2381.66  5634.8 2383.28  5783.0 2383.13  5848.6 2383.52
#Mann=8,-1,0
  3382.2   0.035       0  3472.7   0.045       0  4494.2    0.07       0
  5177.6    0.07       0  5182.5    0.07       0  5416.0   0.035       0
  5572.7    0.07       0  5783.0   0.035       0
Bank Sta=5177.6,5182.5
Exp/Cntr=0.3,0.1

Type RM Length L Ch R = 1,3405,405,405,405
BEGIN DESCRIPTION:
Linn Creek Trib066_7 6.5
END DESCRIPTION:
XS GIS Cut Line= 5
      1317880.94      6881292.35      1318970.42      6880254.65
      1318981.28      6880145.06      1319002.98      6879971.45
      1318581.19      6879442.64
#Sta/Elev= 30
  3402.9 2383.15  3670.7 2383.25  3698.7 2381.71  4031.1 2380.68  4059.5 2381.92
  4095.0 2380.50  4425.8 2378.79  4604.2 2378.16  4632.5 2374.16  4887.0 2361.42
  4964.4 2351.34  5004.7 2347.90  5005.1 2347.40  5009.6 2347.90  5095.3 2356.42
  5135.6 2355.07  5145.7 2352.39  5186.0 2352.16  5191.8 2355.22  5200.4 2354.80
  5208.4 2357.19  5222.6 2355.20  5229.2 2361.76  5235.6 2360.25  5243.6 2362.27
  5356.9 2371.01  5435.8 2377.17  5607.3 2379.95  5663.2 2381.97  5869.0 2383.19
#Mann=6,-1,0
  3402.9   0.045       0  4425.8    0.07       0  5004.7    0.07       0
  5009.6    0.07       0  5356.9   0.035       0  5607.3    0.07       0
Bank Sta=5004.7,5009.6
Exp/Cntr=0.3,0.1

Type RM Length L Ch R = 1,3000,429,429,429
BEGIN DESCRIPTION:
Linn Creek Trib066_7 6.0
END DESCRIPTION:
XS GIS Cut Line= 3
      1318997.59      6880984.14      1319344.17      6880189.64
      1319216.35      6879275.84
#Sta/Elev= 30
  4133.2 2379.55  4303.5 2378.95  4385.7 2376.70  4521.7 2372.87  4532.7 2370.87
  4538.8 2366.55  4562.2 2362.45  4629.2 2360.69  4637.9 2364.61  4652.7 2366.56
  4765.9 2358.15  4836.1 2349.67  4865.0 2350.90  4888.4 2353.72  4917.3 2349.69
  4964.1 2346.89  4987.5 2339.89  5009.1 2335.87  5009.5 2335.37  5014.5 2335.87
  5033.6 2337.08  5056.1 2341.39  5072.3 2346.22  5132.2 2352.17  5223.8 2356.97
  5319.3 2359.18  5467.2 2365.52  5708.5 2377.36  5870.0 2379.94  5922.7 2379.30
#Mann=7,-1,0
  4133.2    0.07       0  4385.7   0.035       0  4629.2    0.07       0
  5009.1    0.07       0  5014.5    0.07       0  5056.1   0.035       0
  5132.2    0.07       0
Bank Sta=5009.1,5014.5
Exp/Cntr=0.3,0.1

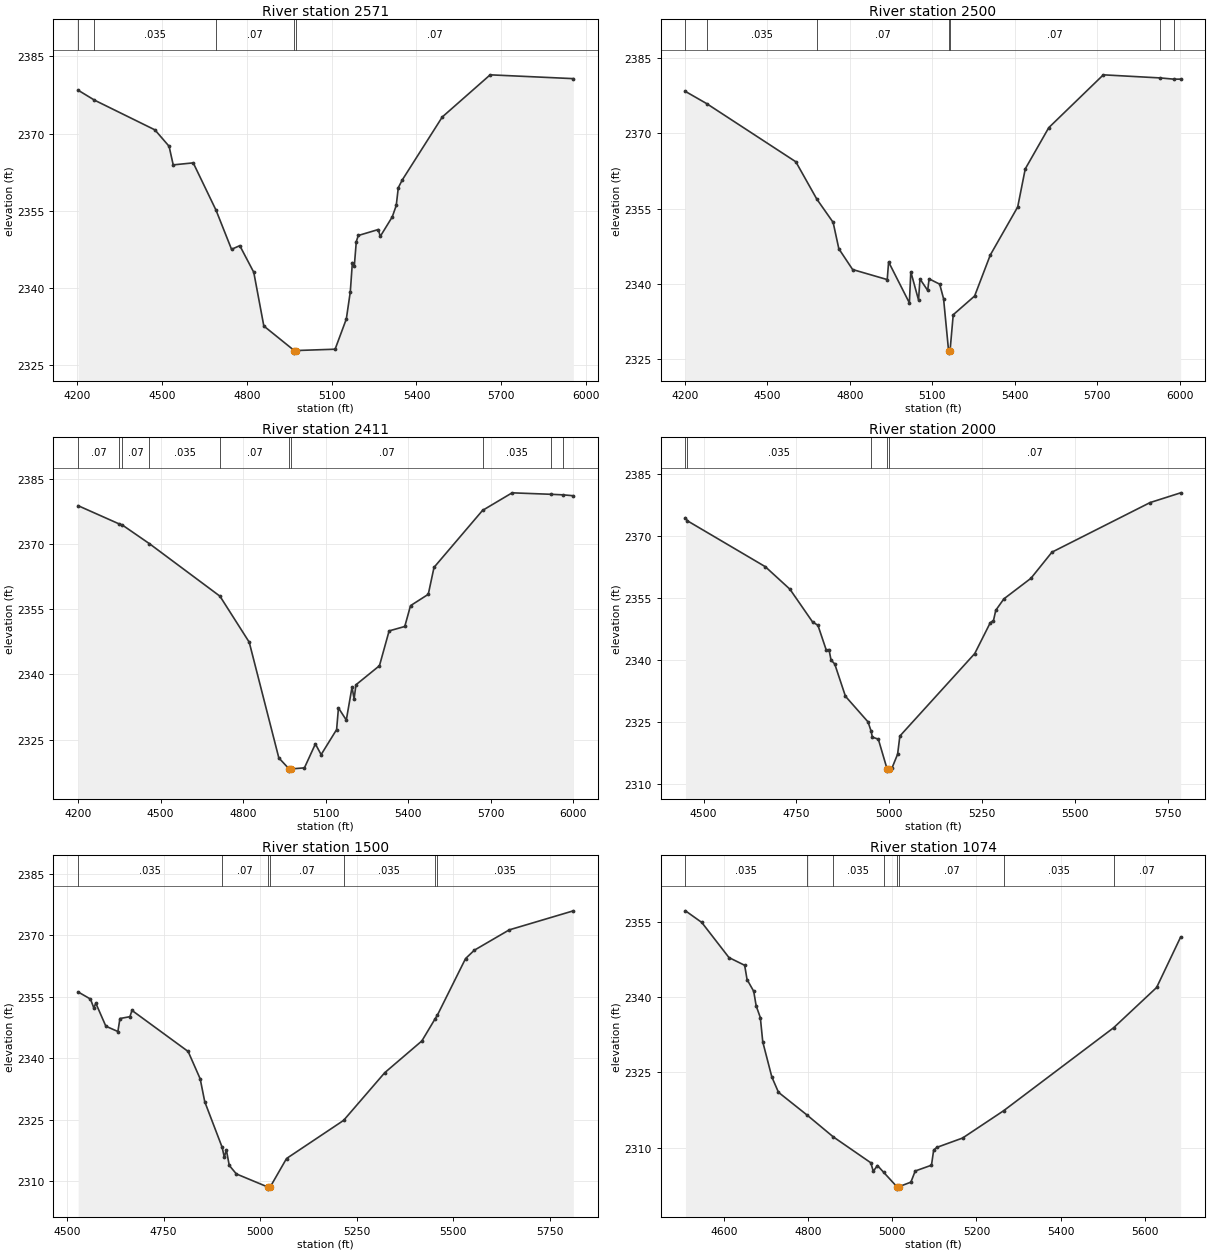
Type RM Length L Ch R = 1,2571,71,71,71
BEGIN DESCRIPTION:
Linn Creek Trib066_7 5.5
END DESCRIPTION:
XS GIS Cut Line= 5
      1319128.67      6880892.11      1319499.52      6880393.19
      1319674.95      6880407.24      1319812.02      6880382.34
      1320375.83      6879792.52
#Sta/Elev= 30
  4202.4 2378.40  4260.1 2376.48  4474.1 2370.71  4524.2 2367.53  4538.8 2363.92
  4609.7 2364.31  4690.7 2355.09  4745.3 2347.54  4774.5 2348.25  4824.0 2343.08
  4859.6 2332.66  4967.3 2327.90  4967.7 2327.40  4972.7 2327.90  5111.9 2328.16
  5151.6 2334.02  5165.7 2339.30  5173.0 2344.97  5179.9 2344.30  5186.9 2349.04
  5194.0 2350.22  5264.8 2351.38  5271.7 2350.04  5314.2 2353.83  5328.3 2356.04
  5335.6 2359.50  5349.7 2361.00  5491.2 2373.21  5660.8 2381.39  5955.3 2380.65
#Mann=5,-1,0
  4202.4    0.07       0  4260.1   0.035       0  4690.7    0.07       0
  4967.3    0.07       0  4972.7    0.07       0
Bank Sta=4967.3,4972.7
Exp/Cntr=0.3,0.1

Type RM Length L Ch R = 1,2500,89,89,89
BEGIN DESCRIPTION:
Linn Creek Trib066_7 5.0
END DESCRIPTION:
XS GIS Cut Line= 5
      1319159.08      6880952.84      1319529.90      6880453.96
      1319705.34      6880468.01      1319833.72      6880506.04
      1320406.53      6879852.95
#Sta/Elev= 30
  4202.4 2378.35  4278.9 2375.95  4603.6 2364.35  4679.9 2356.92  4739.2 2352.29
  4760.0 2347.03  4810.1 2342.90  4935.9 2340.90  4940.9 2344.41  5016.4 2336.26
  5021.6 2342.46  5049.7 2336.83  5054.9 2341.02  5082.9 2338.75  5088.1 2341.04
  5126.6 2339.99  5140.7 2337.10  5158.9 2326.76  5159.3 2326.26  5164.3 2326.76
  5175.8 2333.90  5253.6 2337.63  5310.6 2345.80  5410.2 2355.36  5437.7 2362.94
  5523.1 2371.14  5721.5 2381.66  5929.1 2381.04  5977.3 2380.80  6002.6 2380.80
#Mann=7,-1,0
  4202.4    0.07       0  4278.9   0.035       0  4679.9    0.07       0
  5158.9    0.07       0  5164.3    0.07       0  5929.1   0.035       0
  5977.3    0.07       0
Bank Sta=5158.9,5164.3
Exp/Cntr=0.3,0.1

Type RM Length L Ch R = 1,2411,411,411,411
BEGIN DESCRIPTION:
Linn Creek Trib066_7 4.5
END DESCRIPTION:
XS GIS Cut Line= 5
      1319156.91      6881041.81      1319527.73      6880542.93
      1319703.17      6880556.98      1319831.55      6880595.02
      1320403.97      6879942.38
#Sta/Elev= 30
  4200.8 2378.76  4347.4 2374.64  4360.2 2374.37  4459.4 2370.05  4716.0 2357.97
  4822.4 2347.40  4930.0 2320.81  4967.4 2318.27  4967.8 2317.77  4972.9 2318.27
  5023.0 2318.52  5062.9 2324.02  5083.7 2321.56  5140.0 2327.32  5146.7 2332.29
  5175.2 2329.51  5196.0 2337.07  5203.6 2334.38  5210.3 2337.61  5295.7 2341.99
  5330.8 2349.99  5387.7 2351.01  5408.6 2355.79  5473.1 2358.40  5494.0 2364.59
  5670.3 2377.68  5777.8 2381.72  5920.1 2381.38  5964.2 2381.25  6000.4 2381.05
#Mann=10,-1,0
  4200.8    0.07       0  4347.4   0.035       0  4360.2    0.07       0
  4459.4   0.035       0  4716.0    0.07       0  4967.4    0.07       0
  4972.9    0.07       0  5670.3   0.035       0  5920.1    0.07       0
  5964.2   0.035       0
Bank Sta=4967.4,4972.9
Exp/Cntr=0.3,0.1

Type RM Length L Ch R = 1,2000,500,500,500
BEGIN DESCRIPTION:
Linn Creek Trib066_7 4.0
END DESCRIPTION:
XS GIS Cut Line= 3
      1319388.25      6881161.19      1319875.69      6880909.03
      1320330.91      6880270.60
#Sta/Elev= 30
  4451.2 2374.45  4456.5 2373.72  4666.0 2362.60  4732.4 2357.13  4793.2 2349.21
  4807.8 2348.37  4830.3 2342.33  4837.5 2342.50  4843.1 2339.93  4852.9 2339.02
  4881.8 2331.17  4942.6 2324.95  4951.0 2322.69  4954.2 2321.26  4970.3 2320.76
  4994.0 2313.51  4994.4 2313.01  4999.5 2313.51  5007.4 2313.83  5022.2 2317.11
  5028.3 2321.52  5229.9 2341.53  5271.7 2349.02  5280.3 2349.54  5286.5 2352.03
  5308.3 2354.79  5381.1 2359.78  5437.7 2366.12  5701.9 2378.15  5784.1 2380.51
#Mann=5,-1,0
  4451.2    0.07       0  4456.5   0.035       0  4951.0    0.07       0
  4994.0    0.07       0  4999.5    0.07       0
Bank Sta=4994,4999.5
Exp/Cntr=0.3,0.1

Type RM Length L Ch R = 1,1500,426,426,426
BEGIN DESCRIPTION:
Linn Creek Trib066_7 3.0
END DESCRIPTION:
XS GIS Cut Line= 3
      1320075.73      6881708.07      1320229.16      6881262.65
      1320580.92      6880531.02
#Sta/Elev= 30
  4528.9 2356.16  4560.7 2354.43  4569.4 2352.27  4574.6 2353.42  4600.6 2347.81
  4631.8 2346.51  4637.1 2349.68  4663.0 2350.13  4668.3 2351.66  4813.8 2341.64
  4845.0 2334.96  4856.8 2329.38  4902.0 2318.23  4907.5 2315.81  4912.7 2317.67
  4920.3 2313.84  4938.7 2311.76  5020.6 2308.55  5021.1 2308.05  5026.2 2308.55
  5068.7 2315.52  5216.5 2324.82  5323.2 2336.47  5419.3 2344.21  5453.4 2349.58
  5459.8 2350.56  5532.5 2364.31  5555.1 2366.34  5645.6 2371.31  5811.8 2375.96
#Mann=7,-1,0
  4528.9   0.035       0  4902.0    0.07       0  5020.6    0.07       0
  5026.2    0.07       0  5216.5   0.035       0  5453.4    0.07       0
  5459.8   0.035       0
Bank Sta=5020.6,5026.2
Exp/Cntr=0.3,0.1

Type RM Length L Ch R = 1,1074,574,574,574
BEGIN DESCRIPTION:
Linn Creek Trib066_7 2.0
END DESCRIPTION:
XS GIS Cut Line= 3
      1320160.29      6881714.65      1320590.80      6881464.68
      1320736.47      6880802.23
#Sta/Elev= 30
  4508.8 2357.17  4547.5 2354.86  4612.1 2347.87  4649.4 2346.33  4655.1 2343.49
  4670.9 2341.16  4676.7 2338.27  4686.6 2335.92  4692.4 2331.08  4713.9 2324.11
  4729.7 2321.05  4796.3 2316.61  4859.7 2312.19  4949.1 2307.02  4954.8 2305.33
  4964.8 2306.48  4979.5 2305.13  5010.7 2302.28  5011.1 2301.78  5016.3 2302.28
  5044.2 2303.17  5054.5 2305.39  5093.1 2306.54  5098.3 2309.56  5105.6 2310.08
  5167.0 2311.95  5264.2 2317.37  5525.7 2333.90  5627.8 2341.91  5684.9 2351.96
#Mann=8,-1,0
  4508.8   0.035       0  4796.3    0.07       0  4859.7   0.035       0
  4979.5    0.07       0  5010.7    0.07       0  5016.3    0.07       0
  5264.2   0.035       0  5525.7    0.07       0
Bank Sta=5010.7,5016.3
Exp/Cntr=0.3,0.1

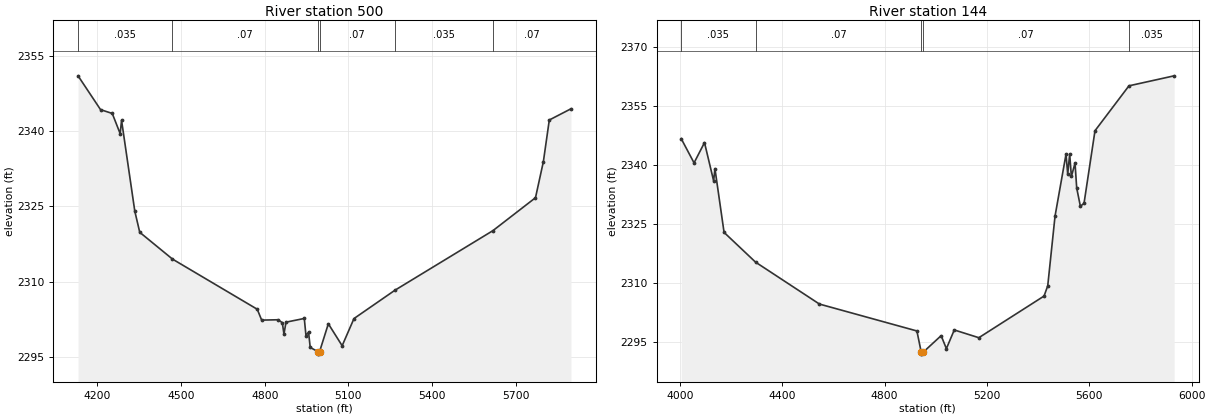
Type RM Length L Ch R = 1,500,356,356,356
BEGIN DESCRIPTION:
Linn Creek Trib066_7 1.0
END DESCRIPTION:
XS GIS Cut Line= 4
      1320163.68      6881620.92      1320858.16      6881721.62
      1320999.57      6881632.30      1321630.93      6880994.00
#Sta/Elev= 30
  4131.0 2350.98  4211.6 2344.25  4253.6 2343.49  4281.9 2339.47  4286.9 2342.12
  4334.4 2324.03  4352.1 2319.84  4469.3 2314.51  4773.3 2304.52  4789.1 2302.36
  4847.8 2302.43  4863.1 2301.85  4869.0 2299.58  4876.3 2301.95  4941.9 2302.69
  4947.9 2299.28  4957.2 2299.97  4963.1 2296.92  4990.7 2296.09  4991.2 2295.59
  4996.7 2296.09  5028.1 2301.63  5077.6 2297.26  5120.0 2302.67  5266.6 2308.30
  5618.1 2320.17  5770.6 2326.72  5798.8 2333.89  5820.1 2342.19  5897.8 2344.42
#Mann=6,-1,0
  4131.0   0.035       0  4469.3    0.07       0  4990.7    0.07       0
  4996.7    0.07       0  5266.6   0.035       0  5618.1    0.07       0
Bank Sta=4990.7,4996.7
Exp/Cntr=0.3,0.1

Type RM Length L Ch R = 1,144,0,0,0
BEGIN DESCRIPTION:
Linn Creek Trib066_7 0.5
END DESCRIPTION:
XS GIS Cut Line= 6
      1320211.62      6881620.52      1321046.35      6881833.81
      1321123.09      6881894.25      1321157.81      6881911.61
      1321248.09      6881932.45      1321887.00      6881394.23
#Sta/Elev= 30
  4005.4 2346.63  4055.6 2340.47  4096.4 2345.63  4132.1 2335.91  4137.2 2339.01
  4172.9 2322.82  4295.9 2315.27  4545.6 2304.62  4926.4 2297.79  4943.3 2292.41
  4943.8 2291.91  4951.1 2292.41  5021.1 2296.60  5041.6 2293.30  5072.4 2298.05
  5168.4 2296.08  5423.3 2306.66  5437.6 2309.25  5466.2 2326.97  5509.1 2342.69
  5515.7 2337.58  5523.4 2342.70  5530.0 2337.02  5544.3 2340.41  5550.8 2334.10
  5565.1 2329.48  5579.4 2330.18  5622.3 2348.64  5755.0 2360.04  5931.5 2362.58
#Mann=5,-1,0
  4005.4   0.035       0  4295.9    0.07       0  4943.3    0.07       0
  4951.1    0.07       0  5755.0   0.035       0
Bank Sta=4943.3,4951.1
Exp/Cntr=0.3,0.1

Chan Stop Cuts=-1