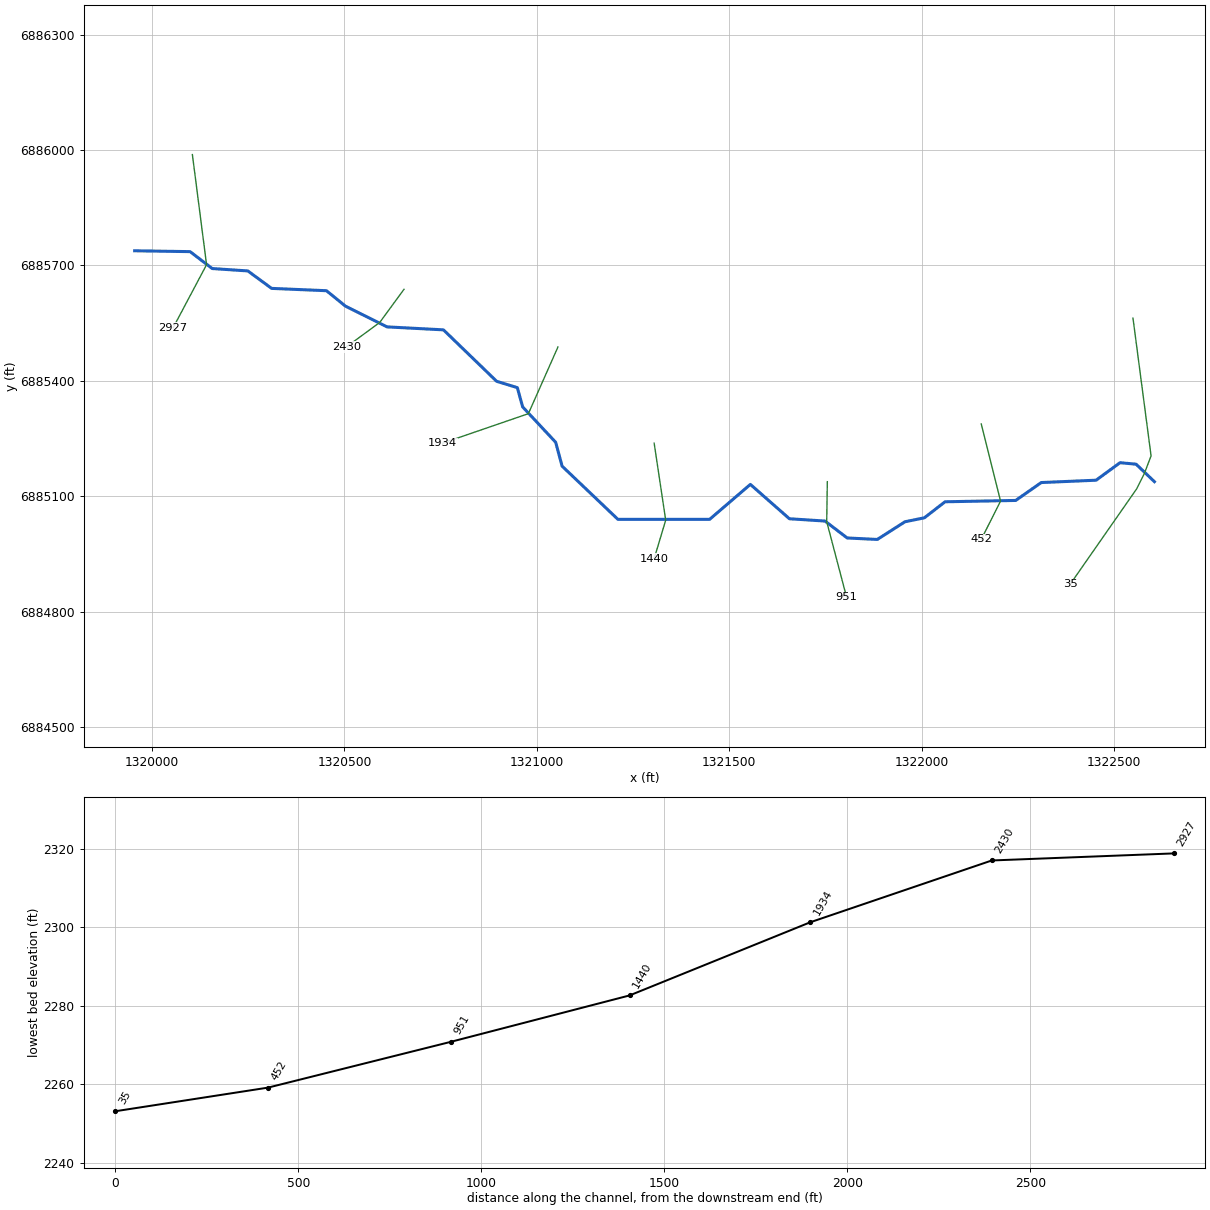
--- Linn Creek Trib066_9.prj (project) ---

Proj Title=Linn Creek Trib066_9 Base Level Engineering
Current Plan=p01
Default Exp/Contr=0.3,0.1
English Units
Geom File=g01
Flow File=f01
Plan File=p01
BEGIN DESCRIPTION:
Linn Creek Trib066_9
END DESCRIPTION:

--- Linn Creek Trib066_9.p01 (plan) ---

Plan Title=Multiple Run
Short Identifier=Multiple
Geom File=g01
Flow File=f01
Subcritical Flow
K Sum by GR= 0
Std Step Tol= 0.01
Critical Tol= 0.01
Num of Std Step Trials= 20
Max Error Tol= 0.3
Flow Tol Ratio= 0.001
Split Flow NTrial= 30
Split Flow Tol= 0.02
Split Flow Ratio= 0.02
Log Output Level= 0
Friction Slope Method= 1
Unsteady Friction Slope Method= 2
Unsteady Bridges Friction Slope Method= 1
Parabolic Critical Depth
Global Vel Dist=  1 , 1 , 1
Global Log Level= 0
CheckData=True
Encroach Param= -1, 0, 0, 0
BEGIN DESCRIPTION:
Multiple Run
END DESCRIPTION:

--- Linn Creek Trib066_9.f01 (steady flow) ---

Flow Title=Multiple
Number of Profiles=7
Profile Names=10-year,25-year,50-year,1pct_min,100-year,1pct_plu,500-year
River Rch & RM= Linn Creek Trib0,Reach-1,2927
     217     301     370     227     452     902     681
River Rch & RM= Linn Creek Trib0,Reach-1,1440
     266     374     465     288     574    1145     884
River Rch & RM= Linn Creek Trib0,Reach-1,35
     909    1345    1724    1094    2183    4355    3548
Boundary for River Rch & Prof#=Linn Creek Trib0,Reach-1,1
Up Type=0
Dn Type=3
Dn Slope=0.005
Boundary for River Rch & Prof#=Linn Creek Trib0,Reach-1,2
Up Type=0
Dn Type=3
Dn Slope=0.005
Boundary for River Rch & Prof#=Linn Creek Trib0,Reach-1,3
Up Type=0
Dn Type=3
Dn Slope=0.005
Boundary for River Rch & Prof#=Linn Creek Trib0,Reach-1,4
Up Type=0
Dn Type=3
Dn Slope=0.005
Boundary for River Rch & Prof#=Linn Creek Trib0,Reach-1,5
Up Type=0
Dn Type=3
Dn Slope=0.005
Boundary for River Rch & Prof#=Linn Creek Trib0,Reach-1,6
Up Type=0
Dn Type=3
Dn Slope=0.005
Boundary for River Rch & Prof#=Linn Creek Trib0,Reach-1,7
Up Type=0
Dn Type=3
Dn Slope=0.005

--- Linn Creek Trib066_9.g01 (geometry) ---

Geom Title=Existing Conditions

River Reach=Linn Creek Trib0,Reach-1
Reach XY= 30
      1319955.00      6885738.00      1320099.08      6885735.78
      1320156.60      6885691.85      1320249.02      6885685.64
      1320310.94      6885640.27      1320453.44      6885634.24
      1320502.82      6885594.12      1320610.93      6885540.25
      1320757.45      6885532.53      1320895.58      6885398.89
      1320949.38      6885382.38      1320963.30      6885332.26
      1321049.13      6885240.28      1321065.78      6885178.32
      1321210.85      6885040.06      1321449.15      6885040.08
      1321555.00      6885130.90      1321656.50      6885041.64
      1321749.02      6885035.64      1321806.60      6884991.70
      1321884.91      6884987.89      1321956.73      6885033.81
      1322007.18      6885044.12      1322060.93      6885085.76
      1322244.49      6885089.22      1322310.94      6885135.73
      1322453.45      6885141.80      1322515.63      6885187.32
      1322557.37      6885183.39      1322605.00      6885138.00

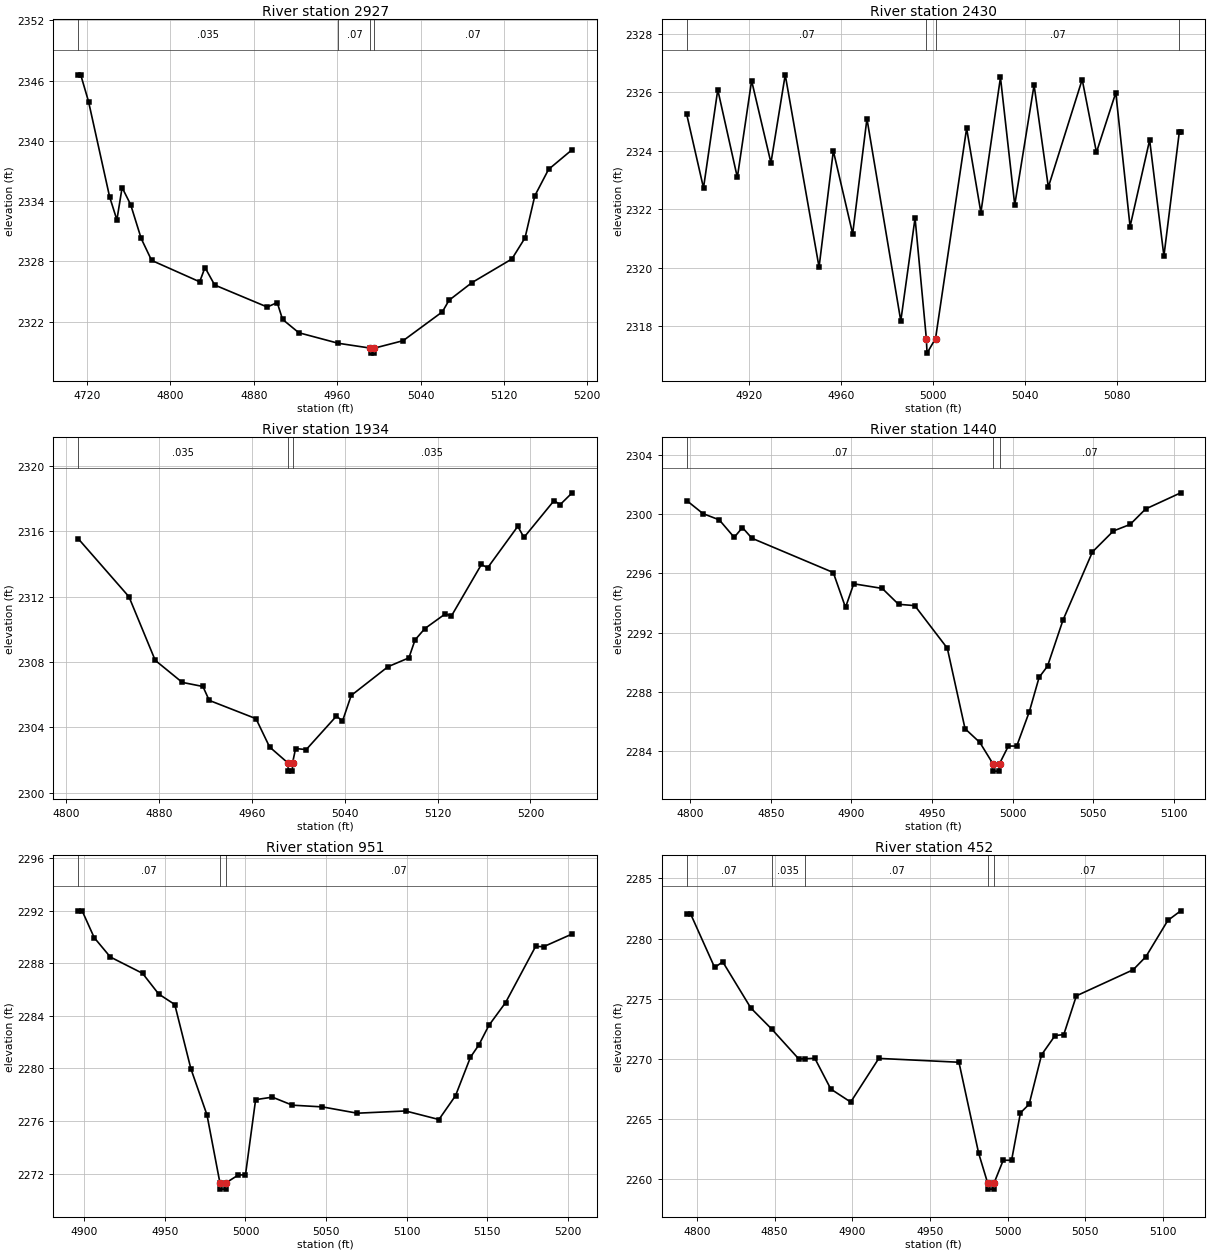
Type RM Length L Ch R = 1,2927,497,497,497
BEGIN DESCRIPTION:
Linn Creek Trib066_9 6.0
END DESCRIPTION:
XS GIS Cut Line= 3
      1320105.01      6885987.95      1320141.87      6885701.82
      1320055.01      6885538.02
#Sta/Elev= 30
  4711.5 2346.58  4714.0 2346.58  4721.5 2343.92  4741.7 2334.44  4748.7 2332.14
  4753.7 2335.36  4761.9 2333.66  4772.0 2330.29  4782.0 2328.11  4828.1 2325.98
  4833.2 2327.40  4842.5 2325.66  4892.9 2323.47  4902.5 2323.91  4907.6 2322.24
  4923.2 2320.91  4961.1 2319.86  4991.8 2319.38  4992.0 2318.88  4995.5 2318.88
  4995.8 2319.38  5023.3 2320.12  5060.9 2322.99  5067.3 2324.14  5089.3 2325.90
  5127.6 2328.25  5140.2 2330.35  5149.6 2334.54  5162.8 2337.17  5185.4 2339.13
#Mann=4,-1,0
  4711.5   0.035       0  4961.1    0.07       0  4991.8    0.07       0
  4995.8    0.07       0
Bank Sta=4991.8,4995.8
Exp/Cntr=0.3,0.1

Type RM Length L Ch R = 1,2430,496,496,496
BEGIN DESCRIPTION:
Linn Creek Trib066_9 5.0
END DESCRIPTION:
XS GIS Cut Line= 3
      1320654.98      6885637.98      1320591.83      6885551.73
      1320505.00      6885488.00
#Sta/Elev= 30
  4893.1 2325.25  4900.4 2322.73  4906.6 2326.09  4915.1 2323.09  4921.3 2326.40
  4929.7 2323.59  4935.9 2326.60  4950.6 2320.02  4956.8 2324.00  4965.2 2321.16
  4971.4 2325.10  4986.1 2318.18  4992.3 2321.70  4997.2 2317.58  4997.5 2317.08
  5001.2 2317.58  5014.7 2324.77  5020.9 2321.89  5029.4 2326.51  5035.6 2322.15
  5044.0 2326.25  5050.2 2322.76  5064.9 2326.44  5071.1 2323.95  5079.5 2325.99
  5085.7 2321.41  5094.2 2324.37  5100.4 2320.40  5107.1 2324.65  5107.7 2324.65
#Mann=4,-1,0
  4893.1    0.07       0  4997.2    0.07       0  5001.2    0.07       0
  5107.1   0.035       0
Bank Sta=4997.2,5001.2
Exp/Cntr=0.3,0.1

Type RM Length L Ch R = 1,1934,494,494,494
BEGIN DESCRIPTION:
Linn Creek Trib066_9 4.0
END DESCRIPTION:
XS GIS Cut Line= 3
      1321055.00      6885488.01      1320978.12      6885314.69
      1320755.03      6885238.01
#Sta/Elev= 30
  4810.4 2315.56  4854.2 2312.00  4876.8 2308.11  4900.1 2306.76  4917.9 2306.51
  4923.3 2305.66  4963.6 2304.54  4975.3 2302.81  4991.1 2301.83  4991.4 2301.33
  4994.9 2301.33  4995.1 2301.83  4997.7 2302.71  5006.9 2302.65  5032.9 2304.70
  5038.1 2304.39  5045.6 2305.96  5077.3 2307.72  5095.3 2308.26  5100.6 2309.36
  5109.0 2310.05  5126.6 2310.95  5131.9 2310.82  5157.8 2313.98  5163.1 2313.77
  5189.1 2316.31  5194.4 2315.63  5220.3 2317.88  5225.6 2317.64  5235.9 2318.36
#Mann=3,-1,0
  4810.4   0.035       0  4991.1   0.035       0  4995.1   0.035       0
Bank Sta=4991.1,4995.1
Exp/Cntr=0.3,0.1

Type RM Length L Ch R = 1,1440,489,489,489
BEGIN DESCRIPTION:
Linn Creek Trib066_9 3.0
END DESCRIPTION:
XS GIS Cut Line= 3
      1321305.00      6885238.01      1321335.00      6885037.95
      1321304.99      6884937.96
#Sta/Elev= 30
  4797.7 2300.90  4807.8 2300.02  4817.9 2299.60  4827.2 2298.42  4832.3 2299.08
  4838.2 2298.36  4888.7 2296.05  4896.3 2293.70  4901.4 2295.29  4919.1 2294.98
  4929.2 2293.91  4939.3 2293.82  4959.5 2290.95  4970.5 2285.53  4979.7 2284.60
  4987.8 2283.17  4988.0 2282.67  4991.6 2282.67  4991.9 2283.17  4997.4 2284.36
  5002.6 2284.36  5010.4 2286.67  5016.5 2288.99  5021.7 2289.74  5031.3 2292.84
  5049.6 2297.44  5062.6 2298.85  5073.0 2299.29  5082.6 2300.33  5104.4 2301.42
#Mann=3,-1,0
  4797.7    0.07       0  4987.8    0.07       0  4991.9    0.07       0
Bank Sta=4987.8,4991.9
Exp/Cntr=0.3,0.1

Type RM Length L Ch R = 1,951,499,499,499
BEGIN DESCRIPTION:
Linn Creek Trib066_9 2.0
END DESCRIPTION:
XS GIS Cut Line= 3
      1321755.00      6885138.03      1321753.40      6885034.14
      1321805.00      6884838.01
#Sta/Elev= 30
  4896.1 2291.98  4898.6 2291.98  4906.1 2289.94  4916.1 2288.47  4936.1 2287.23
  4946.1 2285.66  4956.1 2284.86  4966.1 2279.98  4976.1 2276.47  4984.1 2271.33
  4984.3 2270.83  4987.9 2270.83  4988.2 2271.33  4995.6 2271.91  5000.0 2271.91
  5006.3 2277.63  5016.7 2277.82  5029.1 2277.21  5047.7 2277.08  5069.4 2276.60
  5099.4 2276.77  5120.1 2276.12  5130.4 2277.93  5139.7 2280.86  5144.9 2281.79
  5151.1 2283.27  5161.5 2285.01  5180.1 2289.27  5185.2 2289.26  5202.8 2290.22
#Mann=3,-1,0
  4896.1    0.07       0  4984.1    0.07       0  4988.2    0.07       0
Bank Sta=4984.1,4988.2
Exp/Cntr=0.3,0.1

Type RM Length L Ch R = 1,452,417,417,417
BEGIN DESCRIPTION:
Linn Creek Trib066_9 1.0
END DESCRIPTION:
XS GIS Cut Line= 3
      1322155.00      6885288.02      1322205.17      6885087.60
      1322155.01      6884988.02
#Sta/Elev= 30
  4793.4 2282.03  4796.0 2282.03  4811.4 2277.60  4816.6 2278.07  4834.7 2274.23
  4848.2 2272.47  4865.6 2269.99  4869.6 2270.01  4875.9 2270.05  4886.2 2267.49
  4899.0 2266.41  4917.1 2270.04  4968.7 2269.72  4981.4 2262.15  4987.2 2259.67
  4987.5 2259.17  4991.1 2259.17  4991.3 2259.67  4997.2 2261.57  5002.6 2261.57
  5008.3 2265.51  5013.9 2266.23  5021.9 2270.34  5030.6 2271.94  5036.2 2272.02
  5044.3 2275.24  5080.9 2277.41  5089.1 2278.50  5103.2 2281.51  5111.5 2282.31
#Mann=5,-1,0
  4793.4    0.07       0  4848.2   0.035       0  4869.6    0.07       0
  4987.2    0.07       0  4991.3    0.07       0
Bank Sta=4987.2,4991.3
Exp/Cntr=0.3,0.1

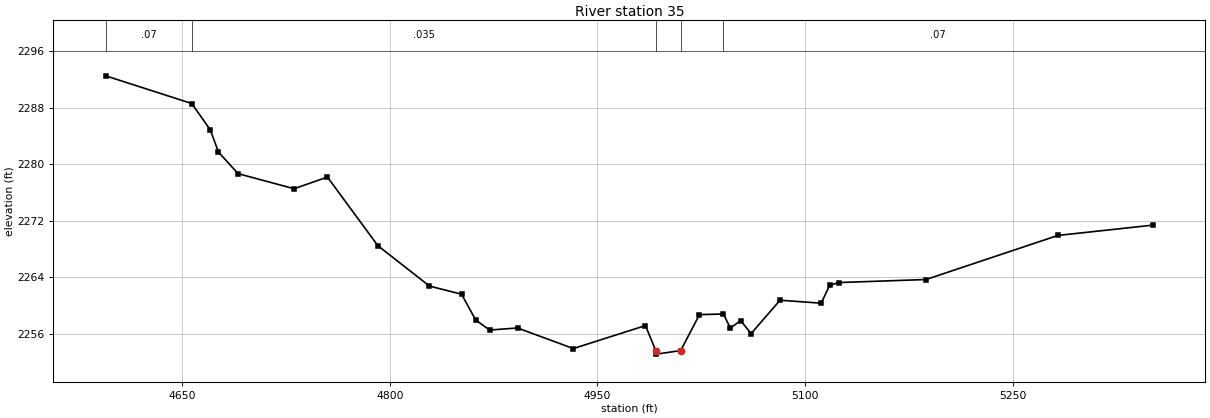
Type RM Length L Ch R = 1,35,0,0,0
BEGIN DESCRIPTION:
Linn Creek Trib066_9 0.5
END DESCRIPTION:
XS GIS Cut Line= 5
      1322549.28      6885562.93      1322596.27      6885205.07
      1322578.86      6885159.21      1322558.64      6885119.07
      1322386.21      6884871.65
#Sta/Elev= 30
  4594.8 2292.54  4657.0 2288.62  4670.4 2284.88  4676.3 2281.74  4690.5 2278.69
  4730.9 2276.56  4755.0 2278.21  4791.4 2268.50  4828.7 2262.78  4851.9 2261.63
  4862.0 2257.99  4872.1 2256.56  4892.3 2256.85  4932.6 2253.94  4984.7 2257.19
  4992.1 2253.65  4992.6 2253.15  5010.1 2253.65  5023.7 2258.74  5041.0 2258.83
  5046.0 2256.83  5053.4 2257.90  5061.0 2256.06  5081.9 2260.78  5111.6 2260.36
  5117.7 2262.88  5124.2 2263.28  5187.3 2263.71  5282.6 2269.95  5351.3 2271.41
#Mann=5,-1,0
  4594.8    0.07       0  4657.0   0.035       0  4992.1   0.035       0
  5010.1   0.035       0  5041.0    0.07       0
Bank Sta=4992.1,5010.1
Exp/Cntr=0.3,0.1

Chan Stop Cuts=-1