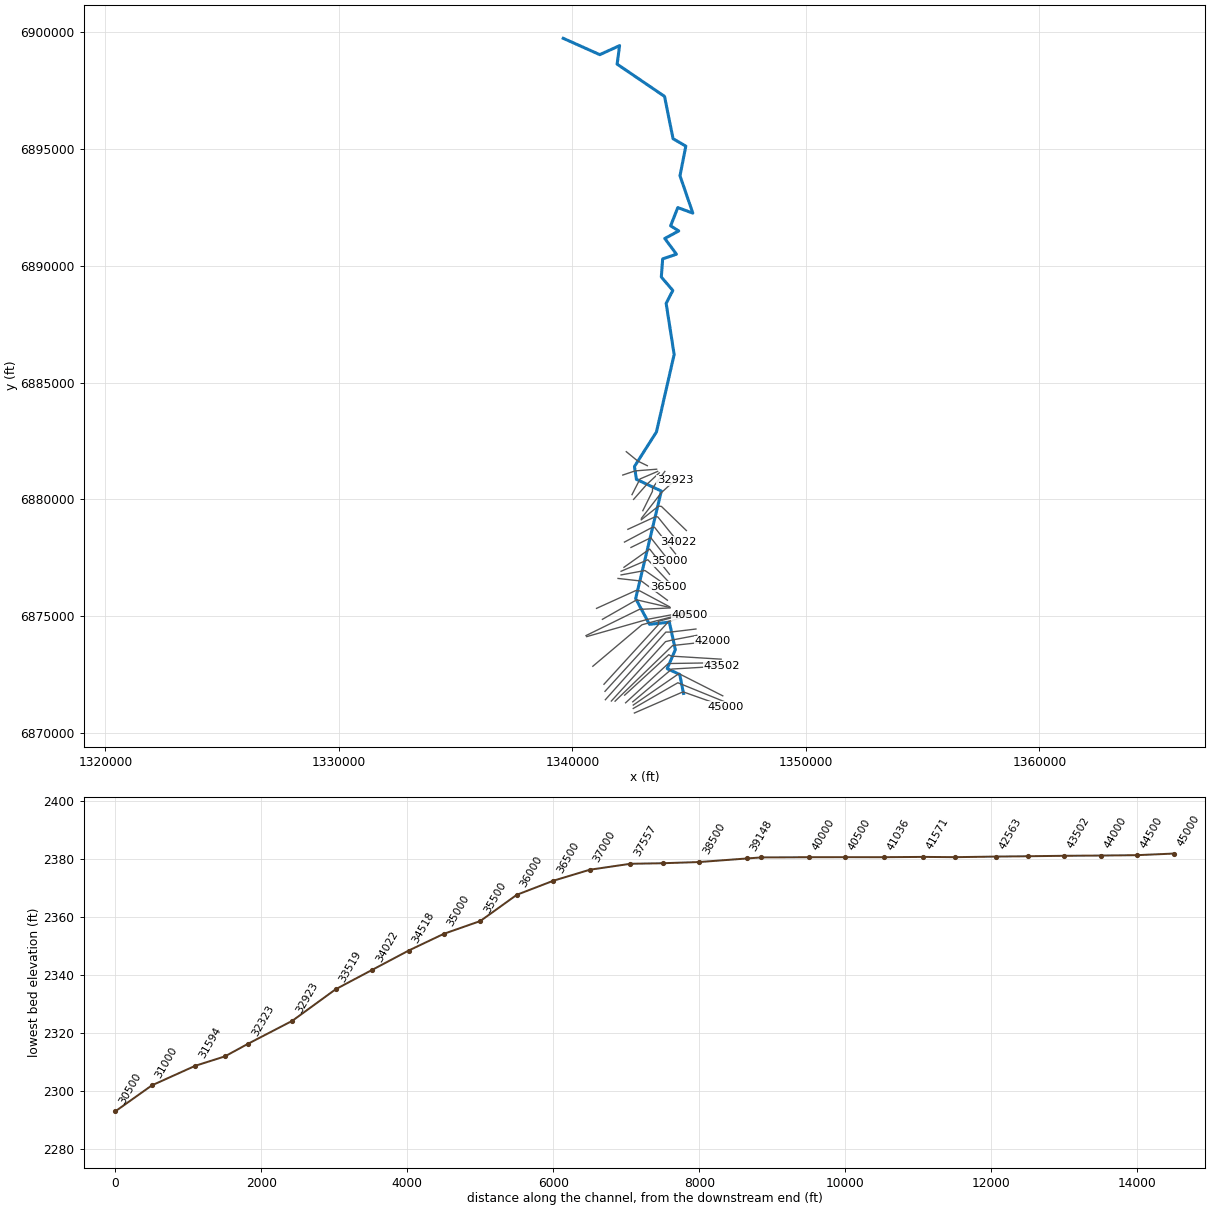
--- Live Oak Creek.prj (project) ---

Proj Title=Live Oak Creek Base Level Engineering
Current Plan=p01
Default Exp/Contr=0.3,0.1
English Units
Geom File=g01
Flow File=f01
Plan File=p01
BEGIN DESCRIPTION:
Live Oak Creek
END DESCRIPTION:

--- Live Oak Creek.p01 (plan) ---

Plan Title=Multiple Run
Short Identifier=Multiple
Geom File=g01
Flow File=f01
Subcritical Flow
K Sum by GR= 0
Std Step Tol= 0.01
Critical Tol= 0.01
Num of Std Step Trials= 20
Max Error Tol= 0.3
Flow Tol Ratio= 0.001
Split Flow NTrial= 30
Split Flow Tol= 0.02
Split Flow Ratio= 0.02
Log Output Level= 0
Friction Slope Method= 1
Unsteady Friction Slope Method= 2
Unsteady Bridges Friction Slope Method= 1
Parabolic Critical Depth
Global Vel Dist=  1 , 1 , 1
Global Log Level= 0
CheckData=True
Encroach Param= -1, 0, 0, 0
BEGIN DESCRIPTION:
Multiple Run
END DESCRIPTION:

--- Live Oak Creek.f01 (steady flow) ---

Flow Title=Multiple
Number of Profiles=7
Profile Names=10-year,25-year,50-year,1pct_min,100-year,1pct_plu,500-year
River Rch & RM= Live Oak Creek,Reach-1,45000
      57      70      78      43      87     173     108
River Rch & RM= Live Oak Creek,Reach-1,43502
      99     125     143      81     162     323     210
River Rch & RM= Live Oak Creek,Reach-1,41036
     342     483     599     369     736    1468    1126
River Rch & RM= Live Oak Creek,Reach-1,31000
     506     737     935     588    1173    2340    1874
River Rch & RM= Live Oak Creek,Reach-1,20500
     682    1000    1276     806    1608    3209    2593
River Rch & RM= Live Oak Creek,Reach-1,13418
     768    1131    1448     917    1830    3651    2967
River Rch & RM= Live Oak Creek,Reach-1,9487
     844    1249    1603    1018    2031    4052    3308
River Rch & RM= Live Oak Creek,Reach-1,7000
     893    1325    1702    1082    2159    4308    3526
Boundary for River Rch & Prof#=Live Oak Creek,Reach-1,1
Up Type=0
Dn Type=3
Dn Slope=0.005
Boundary for River Rch & Prof#=Live Oak Creek,Reach-1,2
Up Type=0
Dn Type=3
Dn Slope=0.005
Boundary for River Rch & Prof#=Live Oak Creek,Reach-1,3
Up Type=0
Dn Type=3
Dn Slope=0.005
Boundary for River Rch & Prof#=Live Oak Creek,Reach-1,4
Up Type=0
Dn Type=3
Dn Slope=0.005
Boundary for River Rch & Prof#=Live Oak Creek,Reach-1,5
Up Type=0
Dn Type=3
Dn Slope=0.005
Boundary for River Rch & Prof#=Live Oak Creek,Reach-1,6
Up Type=0
Dn Type=3
Dn Slope=0.005
Boundary for River Rch & Prof#=Live Oak Creek,Reach-1,7
Up Type=0
Dn Type=3
Dn Slope=0.005

--- Live Oak Creek.g01 (geometry) ---

Geom Title=Existing Conditions

River Reach=Live Oak Creek,Reach-1
Reach XY= 30
      1344755.00      6871688.00      1344593.76      6872498.05
      1344055.57      6872748.47      1344405.41      6873558.13
      1344149.89      6874740.30      1343298.32      6874646.14
      1342705.93      6875748.48      1343805.49      6880353.20
      1342738.29      6880854.21      1342654.49      6881403.26
      1343597.19      6882884.59      1344354.41      6886198.62
      1344011.87      6888388.00      1344297.48      6888941.56
      1343804.70      6889517.82      1343862.67      6890294.52
      1344453.02      6890493.67      1343954.62      6891167.81
      1344551.66      6891489.36      1344204.35      6891708.57
      1344510.34      6892490.74      1345154.36      6892253.26
      1344605.07      6893853.39      1344854.48      6895122.11
      1344308.42      6895439.09      1343941.81      6897251.65
      1341912.77      6898631.83      1342018.01      6899425.00
      1341171.04      6899038.17      1339605.00      6899738.00

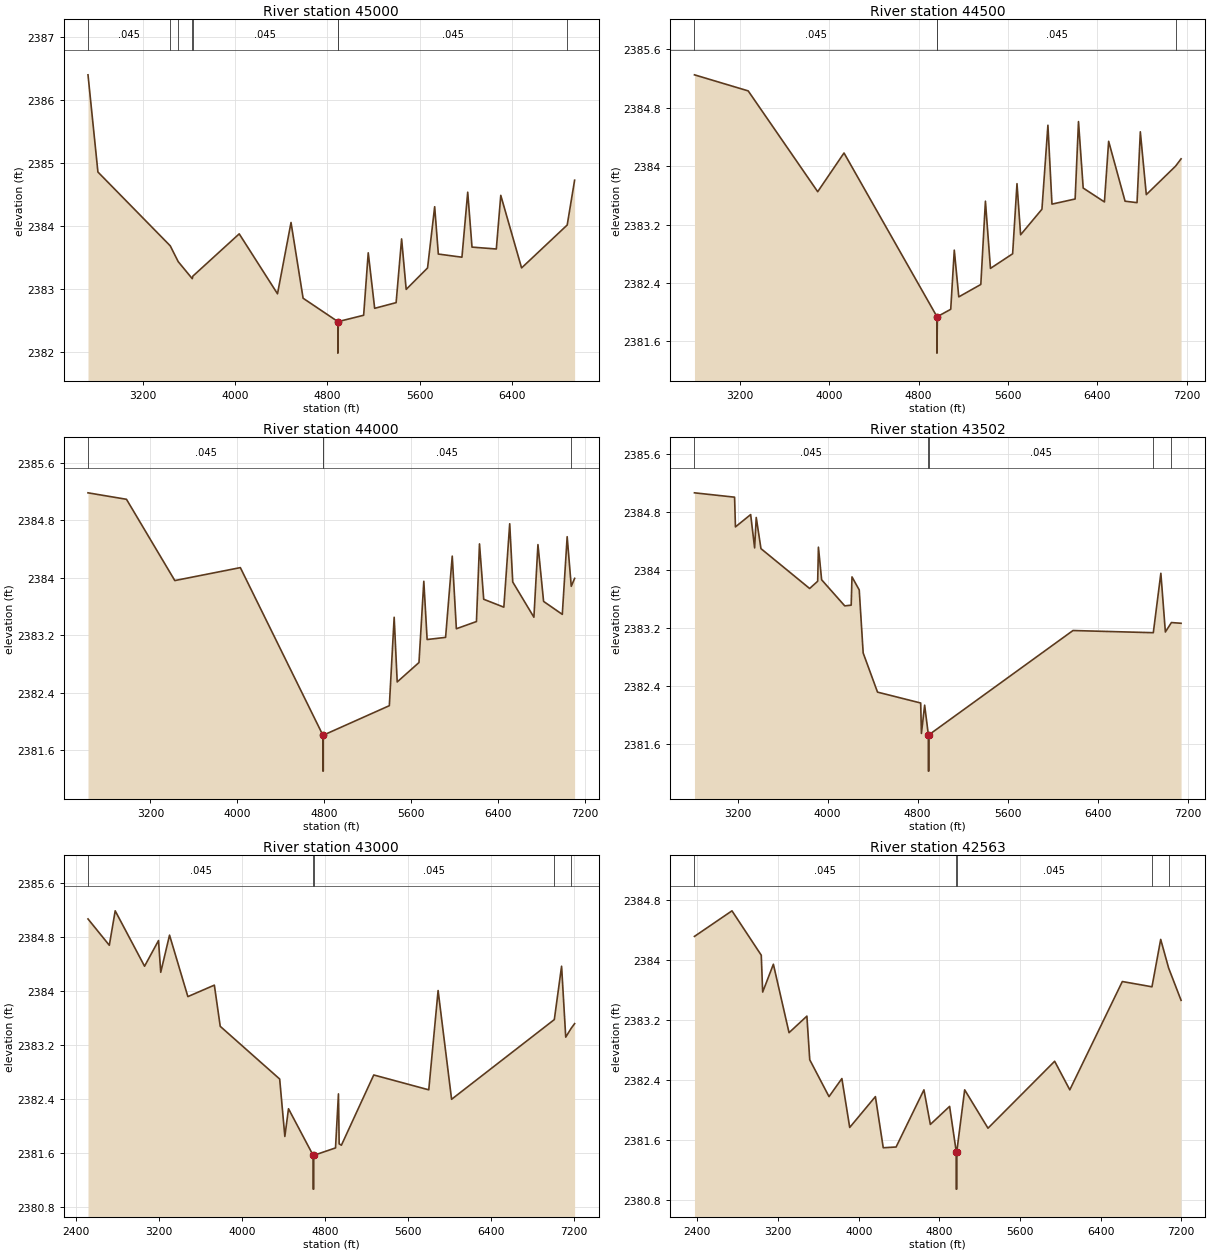
Type RM Length L Ch R = 1,45000,500,500,500
BEGIN DESCRIPTION:
Live Oak Creek 88.0
END DESCRIPTION:
XS GIS Cut Line= 3
      1342651.48      6870848.54      1344736.06      6871755.91
      1346568.13      6871105.47
#Sta/Elev= 30
  2726.5 2386.40  2812.5 2384.86  3439.5 2383.69  3508.2 2383.44  3630.1 2383.17
  3635.5 2383.21  4037.1 2383.88  4369.0 2382.93  4486.2 2384.06  4590.8 2382.86
  4891.9 2382.49  4892.1 2381.99  4895.9 2382.49  5115.6 2382.59  5155.4 2383.58
  5211.1 2382.70  5397.0 2382.79  5444.6 2383.80  5484.3 2383.00  5669.5 2383.34
  5731.2 2384.31  5762.9 2383.56  5967.5 2383.51  6017.6 2384.54  6054.8 2383.67
  6265.5 2383.64  6304.1 2384.49  6484.5 2383.34  6879.8 2384.02  6944.1 2384.73
#Mann=8,-1,0
  2726.5   0.045       0  3439.5    0.07       0  3508.2   0.045       0
  3630.1    0.07       0  3635.5   0.045       0  4891.9   0.045       0
  4895.9   0.045       0  6879.8   0.035       0
Bank Sta=4891.9,4895.9
Exp/Cntr=0.3,0.1

Type RM Length L Ch R = 1,44500,500,500,500
BEGIN DESCRIPTION:
Live Oak Creek 87.0
END DESCRIPTION:
XS GIS Cut Line= 3
      1342602.88      6871042.99      1344513.87      6872144.45
      1346505.64      6871334.63
#Sta/Elev= 30
  2794.3 2385.25  3275.3 2385.03  3897.4 2383.65  4132.9 2384.18  4964.7 2381.94
  4964.9 2381.44  4968.7 2381.94  5088.2 2382.04  5120.0 2382.85  5160.4 2382.21
  5357.5 2382.38  5398.7 2383.52  5443.8 2382.60  5642.3 2382.80  5681.3 2383.76
  5713.7 2383.06  5904.6 2383.41  5958.1 2384.56  5994.4 2383.48  6201.7 2383.55
  6231.8 2384.61  6273.9 2383.70  6464.0 2383.51  6501.7 2384.34  6648.7 2383.52
  6755.8 2383.50  6785.3 2384.47  6838.8 2383.61  7100.9 2384.00  7150.1 2384.10
#Mann=4,-1,0
  2794.3   0.045       0  4964.7   0.045       0  4968.7   0.045       0
  7100.9   0.035       0
Bank Sta=4964.7,4968.7
Exp/Cntr=0.3,0.1

Type RM Length L Ch R = 1,44000,498,498,498
BEGIN DESCRIPTION:
Live Oak Creek 86.0
END DESCRIPTION:
XS GIS Cut Line= 3
      1342602.88      6871188.83      1344558.05      6872535.92
      1346436.17      6871584.64
#Sta/Elev= 30
  2625.7 2385.18  2980.0 2385.09  3424.9 2383.96  4028.2 2384.14  4787.9 2381.81
  4788.1 2381.31  4791.6 2381.31  4791.9 2381.81  5399.7 2382.22  5444.2 2383.45
  5472.1 2382.55  5672.6 2382.82  5717.1 2383.95  5747.6 2383.14  5917.6 2383.17
  5978.8 2384.30  6016.7 2383.29  6201.6 2383.39  6229.6 2384.47  6268.4 2383.70
  6453.8 2383.59  6507.8 2384.75  6535.7 2383.94  6730.6 2383.45  6767.7 2384.46
  6819.7 2383.67  6991.9 2383.49  7036.7 2384.57  7074.4 2383.88  7105.3 2383.99
#Mann=4,-1,0
  2625.7   0.045       0  4787.9   0.045       0  4791.9   0.045       0
  7074.4   0.035       0
Bank Sta=4787.9,4791.9
Exp/Cntr=0.3,0.1

Type RM Length L Ch R = 1,43502,502,502,502
BEGIN DESCRIPTION:
Live Oak Creek 85.0
END DESCRIPTION:
XS GIS Cut Line= 3
      1342582.04      6871327.72      1344254.12      6872730.57
      1346394.46      6872855.47
#Sta/Elev= 30
  2815.5 2385.06  3172.2 2385.00  3179.9 2384.59  3315.2 2384.76  3350.4 2384.30
  3364.7 2384.72  3406.8 2384.29  3839.5 2383.74  3911.1 2383.84  3917.6 2384.31
  3946.2 2383.86  4151.8 2383.50  4209.0 2383.51  4216.1 2383.90  4280.5 2383.72
  4315.6 2382.85  4443.1 2382.31  4826.9 2382.16  4833.4 2381.74  4862.0 2382.13
  4895.2 2381.72  4895.4 2381.22  4898.9 2381.22  4899.2 2381.72  6181.0 2383.16
  6895.2 2383.13  6962.3 2383.95  7002.4 2383.14  7056.1 2383.27  7142.1 2383.26
#Mann=5,-1,0
  2815.5   0.045       0  4895.2   0.045       0  4899.2   0.045       0
  6895.2   0.035       0  7056.1   0.045       0
Bank Sta=4895.2,4899.2
Exp/Cntr=0.3,0.1

Type RM Length L Ch R = 1,43000,437,437,437
BEGIN DESCRIPTION:
Live Oak Creek 84.0
END DESCRIPTION:
XS GIS Cut Line= 3
      1342276.47      6871286.04      1344105.21      6872967.56
      1346310.55      6873001.29
#Sta/Elev= 30
  2515.7 2385.07  2721.2 2384.68  2777.9 2385.19  3060.9 2384.37  3195.3 2384.75
  3216.8 2384.28  3301.6 2384.83  3478.3 2383.92  3733.5 2384.09  3790.2 2383.48
  4363.0 2382.70  4412.9 2381.85  4448.1 2382.26  4685.7 2381.57  4686.1 2381.07
  4690.9 2381.07  4691.4 2381.57  4901.2 2381.68  4929.6 2382.48  4936.4 2381.74
  4957.9 2381.72  5269.8 2382.76  5799.9 2382.54  5889.9 2384.01  6019.9 2382.40
  7010.0 2383.58  7080.0 2384.37  7120.0 2383.32  7172.1 2383.45  7205.6 2383.52
#Mann=5,-1,0
  2515.7   0.045       0  4685.7   0.045       0  4691.4   0.045       0
  7010.0   0.035       0  7172.1   0.045       0
Bank Sta=4685.7,4691.4
Exp/Cntr=0.3,0.1

Type RM Length L Ch R = 1,42563,563,563,563
BEGIN DESCRIPTION:
Live Oak Creek 83.0
END DESCRIPTION:
XS GIS Cut Line= 4
      1342234.76      6871612.38      1344125.70      6873346.10
      1344229.87      6873285.33      1346366.72      6873154.08
#Sta/Elev= 30
  2370.7 2384.31  2742.8 2384.65  3033.3 2384.06  3047.4 2383.57  3153.5 2383.94
  3308.9 2383.03  3485.9 2383.25  3514.2 2382.67  3705.4 2382.18  3833.0 2382.42
  3910.7 2381.77  4165.4 2382.18  4243.3 2381.50  4370.7 2381.51  4646.9 2382.27
  4710.5 2381.81  4901.6 2382.05  4967.2 2381.45  4967.6 2380.95  4972.4 2380.95
  4972.9 2381.45  5051.0 2382.27  5282.3 2381.76  5943.5 2382.65  6093.8 2382.27
  6614.8 2383.71  6908.9 2383.64  6995.5 2384.27  7074.0 2383.89  7197.6 2383.46
#Mann=5,-1,0
  2370.7   0.045       0  4967.2   0.045       0  4972.9   0.045       0
  6908.9   0.035       0  7074.0   0.045       0
Bank Sta=4967.2,4972.9
Exp/Cntr=0.3,0.1

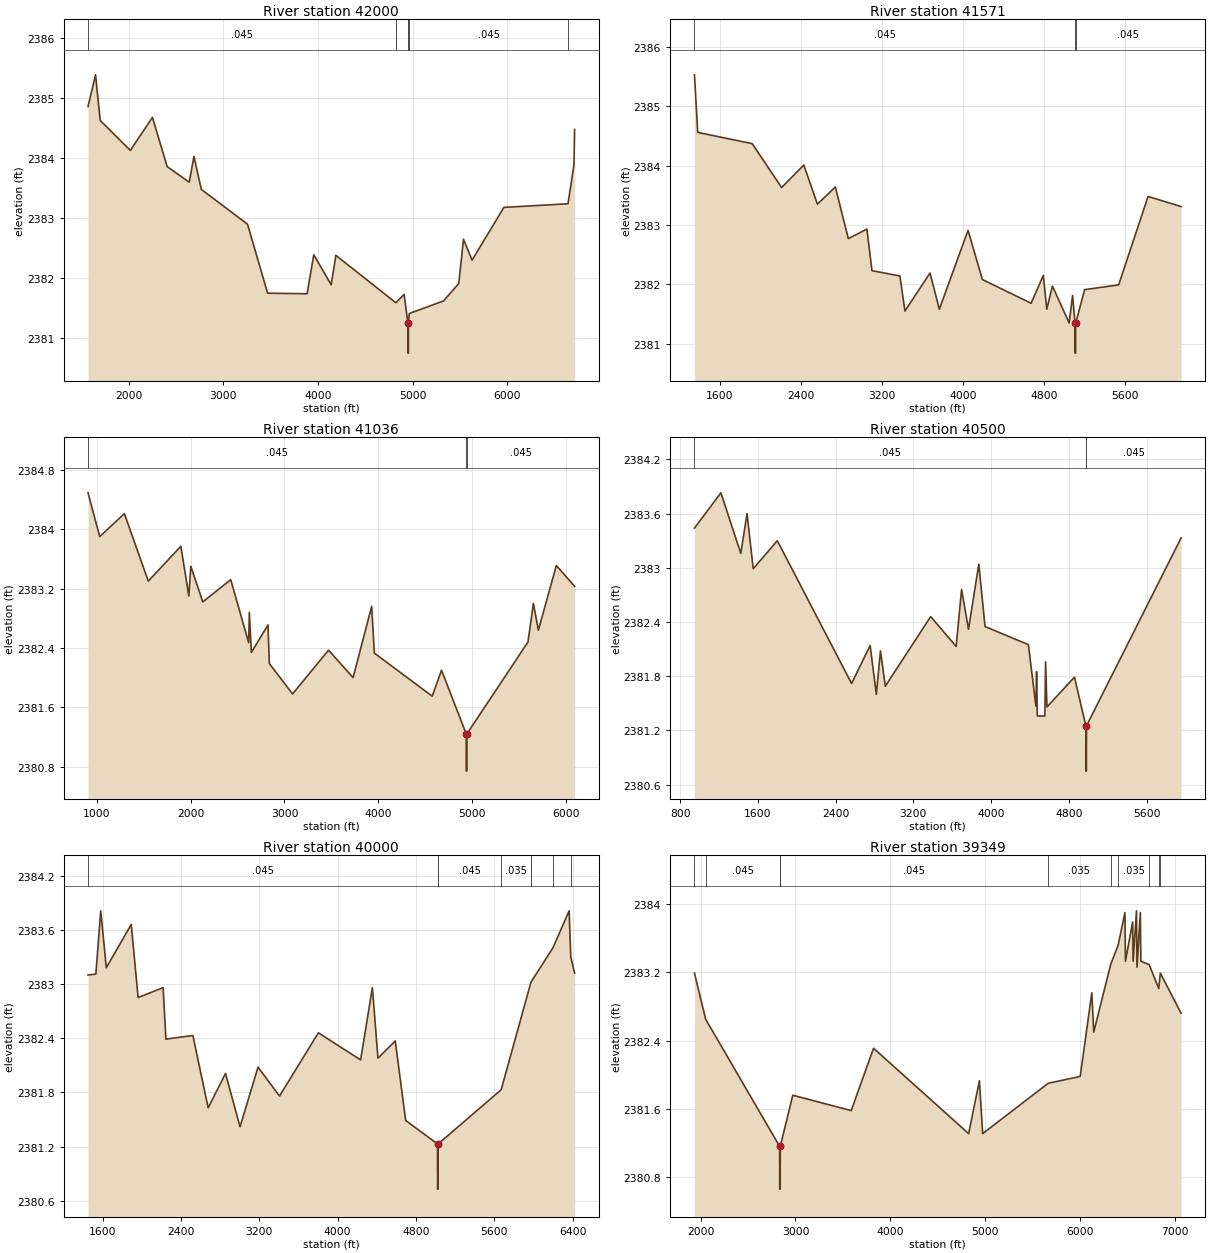
Type RM Length L Ch R = 1,42000,429,429,429
BEGIN DESCRIPTION:
Live Oak Creek 82.0
END DESCRIPTION:
XS GIS Cut Line= 3
      1341825.05      6871355.46      1344289.70      6873738.04
      1345991.73      6873924.40
#Sta/Elev= 30
  1572.0 2384.86  1651.6 2385.39  1701.0 2384.63  2019.2 2384.13  2252.8 2384.68
  2408.2 2383.86  2641.7 2383.60  2691.1 2384.03  2768.8 2383.48  3256.8 2382.90
  3469.1 2381.75  3886.3 2381.74  3957.0 2382.39  4141.0 2381.89  4190.4 2382.38
  4824.3 2381.59  4911.7 2381.73  4951.1 2381.25  4951.6 2380.75  4956.6 2380.75
  4957.1 2381.25  4965.2 2381.41  5327.2 2381.62  5488.2 2381.91  5538.5 2382.65
  5629.0 2382.30  5965.2 2383.18  6642.4 2383.24  6705.4 2383.89  6712.2 2384.48
#Mann=6,-1,0
  1572.0   0.045       0  4824.3   0.035       0  4951.1   0.045       0
  4957.1   0.035       0  4965.2   0.045       0  6642.4   0.035       0
Bank Sta=4951.1,4957.1
Exp/Cntr=0.3,0.1

Type RM Length L Ch R = 1,41571,535,535,535
BEGIN DESCRIPTION:
Live Oak Creek 81.0
END DESCRIPTION:
XS GIS Cut Line= 4
      1341665.31      6871362.38      1343984.79      6873904.08
      1344269.51      6873973.53      1345320.31      6874174.08
#Sta/Elev= 30
  1348.5 2385.53  1380.8 2384.56  1918.6 2384.37  2209.0 2383.63  2428.0 2384.01
  2562.4 2383.35  2739.4 2383.64  2867.1 2382.77  3050.9 2382.93  3100.9 2382.23
  3376.5 2382.14  3426.5 2381.55  3673.8 2382.19  3765.9 2381.58  4049.4 2382.91
  4190.6 2382.08  4672.3 2381.68  4792.1 2382.15  4826.4 2381.58  4882.3 2381.97
  5047.0 2381.35  5081.4 2381.81  5105.5 2381.34  5106.0 2380.84  5111.0 2380.84
  5111.5 2381.34  5200.1 2381.91  5536.1 2381.99  5826.4 2383.48  6152.3 2383.31
#Mann=3,-1,0
  1348.5   0.045       0  5105.5   0.045       0  5111.5   0.045       0
Bank Sta=5105.5,5111.5
Exp/Cntr=0.3,0.1

Type RM Length L Ch R = 1,41036,536,536,536
BEGIN DESCRIPTION:
Live Oak Creek 80.0
END DESCRIPTION:
XS GIS Cut Line= 4
      1341408.42      6871418.00      1343998.68      6874313.80
      1344200.07      6874313.80      1345288.10      6874445.41
#Sta/Elev= 30
   908.0 2384.49  1032.9 2383.90  1295.4 2384.21  1550.3 2383.30  1897.2 2383.77
  1981.7 2383.10  2003.4 2383.50  2130.5 2383.02  2428.1 2383.32  2619.5 2382.47
  2626.2 2382.88  2647.9 2382.34  2825.1 2382.71  2839.3 2382.19  3086.8 2381.78
  3469.6 2382.37  3731.3 2382.00  3929.4 2382.96  3957.8 2382.33  4573.9 2381.75
  4673.3 2382.10  4936.6 2381.24  4937.1 2380.74  4942.1 2380.74  4942.6 2381.24
  5593.9 2382.48  5651.7 2383.00  5704.7 2382.64  5896.1 2383.51  6090.6 2383.23
#Mann=3,-1,0
   908.0   0.045       0  4936.6   0.045       0  4942.6   0.045       0
Bank Sta=4936.6,4942.6
Exp/Cntr=0.3,0.1

Type RM Length L Ch R = 1,40500,500,500,500
BEGIN DESCRIPTION:
Live Oak Creek 79.0
END DESCRIPTION:
XS GIS Cut Line= 3
      1341392.72      6871776.16      1344122.36      6874771.47
      1345038.50      6875042.19
#Sta/Elev= 30
   947.5 2383.44  1219.7 2383.83  1424.4 2383.16  1488.6 2383.60  1552.1 2382.99
  1800.1 2383.30  2564.2 2381.72  2755.4 2382.14  2819.0 2381.60  2861.5 2382.08
  2911.5 2381.69  3378.4 2382.46  3640.5 2382.13  3696.6 2382.76  3767.6 2382.32
  3873.7 2383.04  3937.8 2382.35  4383.8 2382.15  4461.5 2381.47  4468.2 2381.85
  4475.7 2381.36  4553.4 2381.36  4560.8 2381.96  4575.0 2381.46  4858.1 2381.79
  4975.3 2381.25  4975.8 2380.75  4980.9 2380.75  4981.4 2381.25  5955.3 2383.33
#Mann=3,-1,0
   947.5   0.045       0  4975.3   0.045       0  4981.4   0.045       0
Bank Sta=4975.3,4981.4
Exp/Cntr=0.3,0.1

Type RM Length L Ch R = 1,40000,651,651,651
BEGIN DESCRIPTION:
Live Oak Creek 78.0
END DESCRIPTION:
XS GIS Cut Line= 5
      1341349.30      6872079.96      1343695.73      6874648.01
      1343685.50      6874717.77      1343671.44      6874773.22
      1344989.17      6875125.45
#Sta/Elev= 30
  1450.9 2383.10  1531.2 2383.11  1581.1 2383.81  1637.9 2383.18  1892.6 2383.66
  1963.0 2382.85  2218.2 2382.96  2246.6 2382.39  2522.2 2382.43  2678.3 2381.63
  2855.3 2382.01  3003.9 2381.42  3187.7 2382.08  3407.2 2381.76  3803.8 2382.46
  4235.5 2382.16  4355.7 2382.96  4412.5 2382.18  4589.5 2382.37  4695.5 2381.49
  5021.1 2381.23  5021.6 2380.73  5026.7 2380.73  5027.2 2381.23  5671.1 2381.83
  5975.2 2383.02  6199.7 2383.40  6365.1 2383.81  6382.0 2383.30  6421.2 2383.12
#Mann=7,-1,0
  1450.9   0.045       0  5021.1   0.045       0  5027.2   0.045       0
  5671.1   0.035       0  5975.2   0.045       0  6199.7   0.035       0
  6382.0    0.07       0
Bank Sta=5021.1,5027.2
Exp/Cntr=0.3,0.1

Type RM Length L Ch R = 1,39349,201,201,201
BEGIN DESCRIPTION:
Live Oak Creek 77.0
END DESCRIPTION:
XS GIS Cut Line= 4
      1340871.90      6872850.38      1342975.24      6874626.30
      1343478.71      6874765.19      1345276.50      6875230.48
#Sta/Elev= 30
  1934.7 2383.19  2052.9 2382.65  2833.5 2381.16  2834.0 2380.66  2839.1 2380.66
  2839.6 2381.16  2971.7 2381.76  3588.1 2381.58  3823.3 2382.31  4826.4 2381.31
  4939.9 2381.93  4974.2 2381.31  5665.3 2381.90  6002.9 2381.98  6125.3 2382.96
  6145.9 2382.50  6323.9 2383.29  6403.7 2383.52  6474.7 2383.90  6479.9 2383.33
  6556.0 2383.79  6561.1 2383.33  6596.6 2383.92  6601.8 2383.26  6637.2 2383.90
  6642.4 2383.33  6730.0 2383.29  6831.5 2383.01  6848.2 2383.19  7066.8 2382.72
#Mann=10,-1,0
  1934.7   0.035       0  2052.9   0.045       0  2833.5   0.045       0
  2839.6   0.045       0  5665.3   0.035       0  6323.9   0.045       0
  6403.7   0.035       0  6730.0    0.07       0  6831.5   0.045       0
  6848.2   0.035       0
Bank Sta=2833.5,2839.6
Exp/Cntr=0.3,0.1

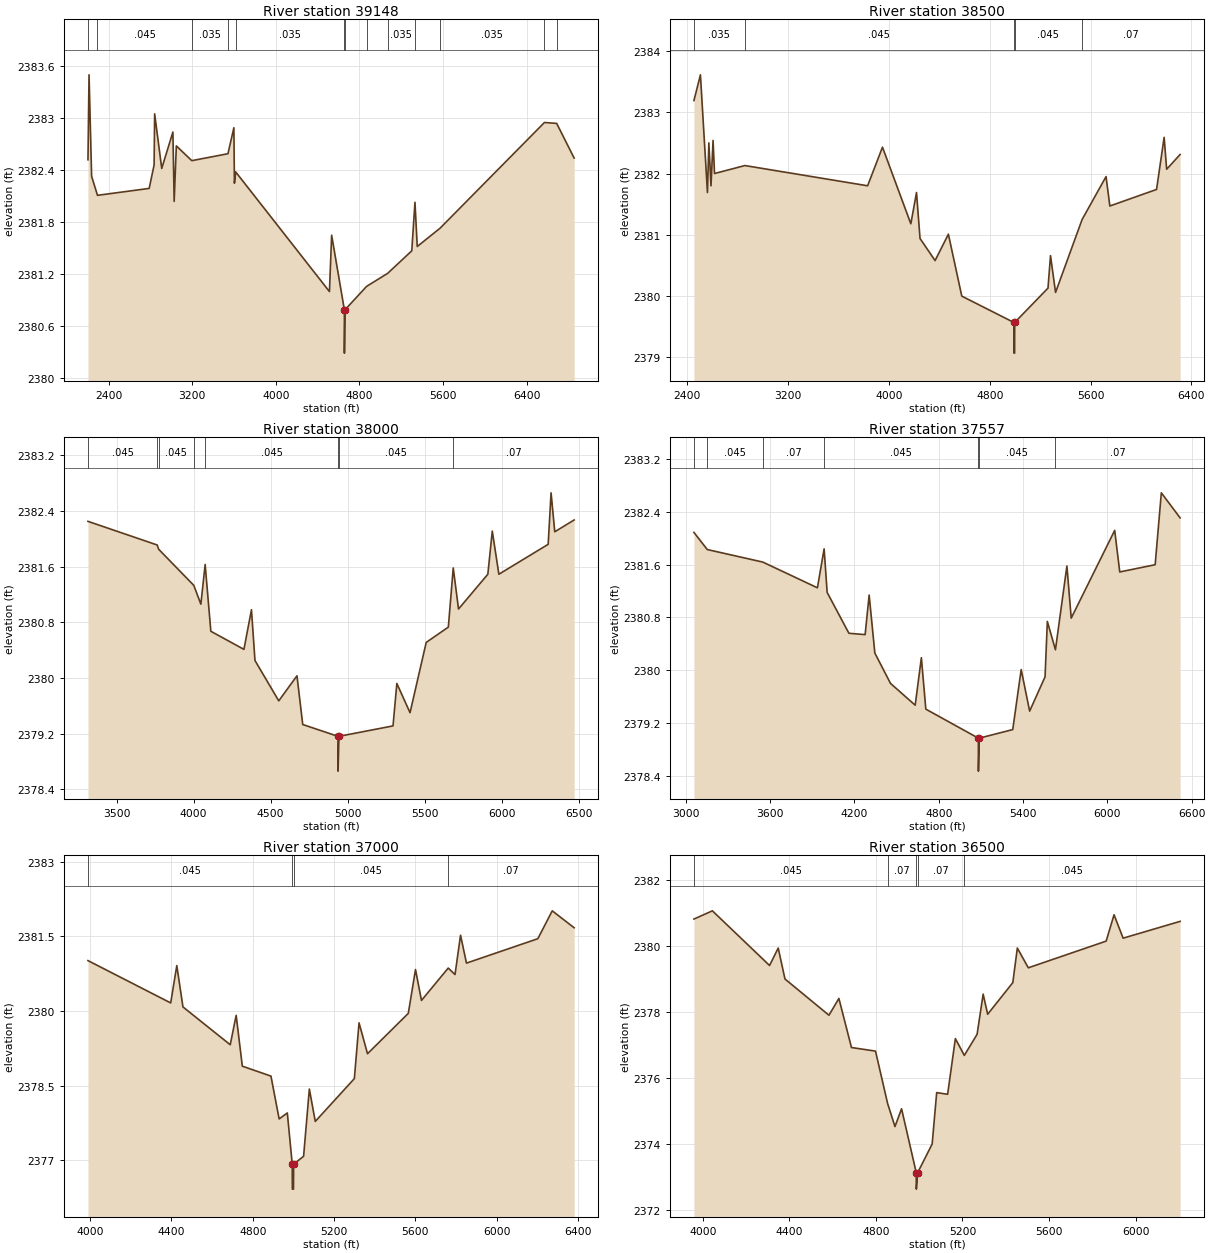
Type RM Length L Ch R = 1,39148,648,648,648
BEGIN DESCRIPTION:
Live Oak Creek 76.0
END DESCRIPTION:
XS GIS Cut Line= 3
      1340611.43      6874119.89      1343218.30      6874860.68
      1345128.03      6875220.92
#Sta/Elev= 30
  2202.2 2382.52  2212.4 2383.50  2237.1 2382.33  2293.3 2382.11  2788.1 2382.19
  2835.2 2382.46  2840.4 2383.05  2908.2 2382.42  3015.0 2382.84  3027.2 2382.04
  3048.0 2382.68  3196.0 2382.51  3542.1 2382.59  3598.8 2382.89  3604.0 2382.25
  3616.1 2382.38  4513.5 2381.00  4534.6 2381.65  4656.3 2380.79  4656.8 2380.29
  4662.4 2380.79  4869.3 2381.06  5070.5 2381.21  5301.6 2381.47  5332.1 2382.03
  5354.0 2381.52  5571.5 2381.73  6571.2 2382.95  6688.4 2382.94  6855.7 2382.54
#Mann=13,-1,0
  2202.2   0.035       0  2293.3   0.045       0  3196.0   0.035       0
  3542.1   0.045       0  3616.1   0.035       0  4656.3    0.07       0
  4662.4   0.035       0  4869.3    0.07       0  5070.5   0.035       0
  5332.1    0.07       0  5571.5   0.035       0  6571.2    0.07       0
  6688.4   0.035       0
Bank Sta=4656.3,4662.4
Exp/Cntr=0.3,0.1

Type RM Length L Ch R = 1,38500,500,500,500
BEGIN DESCRIPTION:
Live Oak Creek 75.0
END DESCRIPTION:
XS GIS Cut Line= 3
      1340578.90      6874163.29      1342863.08      6875285.82
      1344171.56      6875346.72
#Sta/Elev= 30
  2454.9 2383.19  2506.3 2383.61  2562.0 2381.69  2573.1 2382.50  2590.1 2381.80
  2606.5 2382.54  2618.1 2382.00  2858.7 2382.13  3832.0 2381.80  3949.9 2382.43
  4174.7 2381.18  4219.7 2381.69  4247.7 2380.94  4367.0 2380.58  4472.5 2381.01
  4578.7 2380.00  4992.0 2379.57  4992.5 2379.07  4997.7 2379.07  4998.2 2379.57
  5262.2 2380.13  5282.2 2380.66  5322.3 2380.06  5532.8 2381.25  5722.7 2381.95
  5752.7 2381.47  6123.1 2381.74  6183.2 2382.59  6203.2 2382.07  6309.9 2382.31
#Mann=5,-1,0
  2454.9   0.035       0  2858.7   0.045       0  4992.0   0.045       0
  4998.2   0.045       0  5532.8    0.07       0
Bank Sta=4992,4998.2
Exp/Cntr=0.3,0.1

Type RM Length L Ch R = 1,38000,443,443,443
BEGIN DESCRIPTION:
Live Oak Creek 74.0
END DESCRIPTION:
XS GIS Cut Line= 3
      1341282.57      6874860.70      1342747.91      6875694.59
      1344180.95      6875364.35
#Sta/Elev= 30
  3314.0 2382.25  3763.7 2381.91  3772.6 2381.85  4001.0 2381.33  4047.0 2381.06
  4074.8 2381.63  4111.8 2380.67  4326.6 2380.41  4375.5 2380.98  4398.3 2380.25
  4552.8 2379.67  4671.0 2380.03  4708.5 2379.33  4937.3 2379.16  4937.8 2378.66
  4943.6 2379.16  5294.6 2379.31  5319.5 2379.92  5405.1 2379.50  5510.1 2380.51
  5653.8 2380.73  5685.6 2381.58  5720.0 2380.99  5910.3 2381.49  5939.1 2382.11
  5981.9 2381.49  6302.0 2381.92  6320.8 2382.66  6344.8 2382.10  6470.6 2382.27
#Mann=8,-1,0
  3314.0   0.045       0  3763.7    0.07       0  3772.6   0.045       0
  4001.0    0.07       0  4074.8   0.045       0  4937.3   0.045       0
  4943.6   0.045       0  5685.6    0.07       0
Bank Sta=4937.3,4943.6
Exp/Cntr=0.3,0.1

Type RM Length L Ch R = 1,37557,557,557,557
BEGIN DESCRIPTION:
Live Oak Creek 73.0
END DESCRIPTION:
XS GIS Cut Line= 4
      1341030.81      6875329.44      1342714.82      6876093.32
      1342888.43      6876075.96      1344155.77      6875398.89
#Sta/Elev= 30
  3057.5 2382.09  3152.4 2381.83  3547.5 2381.64  3936.3 2381.25  3984.1 2381.84
  4005.6 2381.18  4160.6 2380.56  4276.0 2380.54  4304.6 2381.14  4345.2 2380.26
  4456.7 2379.80  4632.3 2379.47  4676.3 2380.19  4708.0 2379.41  5081.9 2378.97
  5082.4 2378.47  5088.5 2378.97  5326.7 2379.10  5386.8 2380.01  5447.0 2379.38
  5556.7 2379.90  5573.0 2380.74  5630.6 2380.31  5712.2 2381.58  5742.9 2380.79
  6052.3 2382.12  6088.4 2381.49  6340.4 2381.60  6384.3 2382.69  6518.0 2382.31
#Mann=7,-1,0
  3057.5    0.07       0  3152.4   0.045       0  3547.5    0.07       0
  3984.1   0.045       0  5081.9   0.045       0  5088.5   0.045       0
  5630.6    0.07       0
Bank Sta=5081.9,5088.5
Exp/Cntr=0.3,0.1

Type RM Length L Ch R = 1,37000,500,500,500
BEGIN DESCRIPTION:
Live Oak Creek 72.0
END DESCRIPTION:
XS GIS Cut Line= 3
      1341950.89      6876610.68      1342954.57      6876497.89
      1344065.52      6875678.39
#Sta/Elev= 30
  3990.0 2381.01  4396.7 2380.16  4426.8 2380.91  4457.0 2380.08  4689.5 2379.32
  4718.7 2379.91  4748.9 2378.89  4889.7 2378.69  4930.0 2377.83  4970.2 2377.95
  4994.4 2376.92  4994.9 2376.42  5000.5 2376.42  5001.0 2376.92  5050.2 2377.08
  5078.5 2378.43  5107.7 2377.78  5299.8 2378.64  5322.8 2379.76  5364.5 2379.14
  5565.0 2379.95  5600.5 2380.83  5629.8 2380.21  5761.4 2380.86  5794.8 2380.73
  5821.9 2381.52  5851.1 2380.96  6202.0 2381.45  6272.9 2382.01  6380.5 2381.67
#Mann=4,-1,0
  3990.0   0.045       0  4994.4   0.045       0  5001.0   0.045       0
  5761.4    0.07       0
Bank Sta=4994.4,5001
Exp/Cntr=0.3,0.1

Type RM Length L Ch R = 1,36500,500,500,500
BEGIN DESCRIPTION:
Live Oak Creek 71.0
END DESCRIPTION:
XS GIS Cut Line= 3
      1342081.17      6876761.72      1343105.17      6876950.15
      1344095.83      6876262.37
#Sta/Elev= 30
  3958.8 2380.82  4044.0 2381.07  4308.4 2379.41  4348.3 2379.94  4379.6 2379.00
  4582.9 2377.90  4628.8 2378.41  4686.9 2376.92  4798.1 2376.81  4854.0 2375.22
  4888.0 2374.52  4918.5 2375.06  4986.3 2373.12  4986.8 2372.62  4993.0 2373.12
  5059.9 2373.99  5080.8 2375.55  5131.4 2375.50  5167.2 2377.19  5208.5 2376.68
  5267.6 2377.32  5295.6 2378.54  5316.5 2377.93  5432.7 2378.89  5453.6 2379.94
  5504.3 2379.34  5864.1 2380.15  5900.6 2380.95  5942.6 2380.24  6206.0 2380.75
#Mann=5,-1,0
  3958.8   0.045       0  4854.0    0.07       0  4986.3    0.07       0
  4993.0    0.07       0  5208.5   0.045       0
Bank Sta=4986.3,4993
Exp/Cntr=0.3,0.1

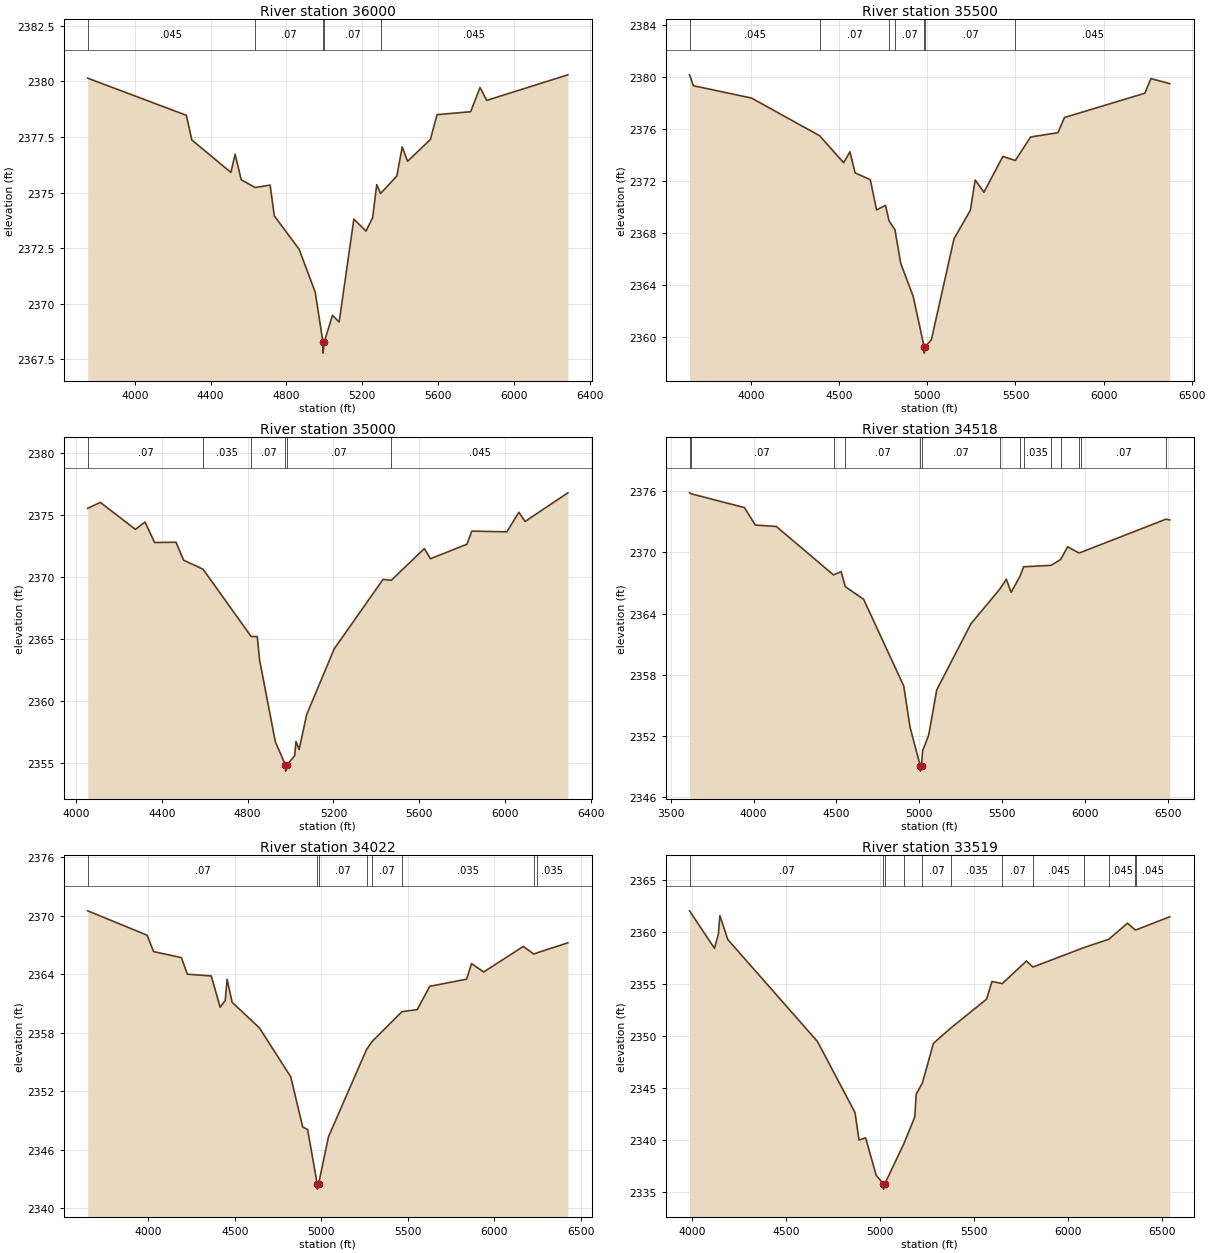
Type RM Length L Ch R = 1,36000,500,500,500
BEGIN DESCRIPTION:
Live Oak Creek 70.0
END DESCRIPTION:
XS GIS Cut Line= 3
      1342081.12      6876917.96      1343227.90      6877410.81
      1344107.18      6876475.26
#Sta/Elev= 30
  3751.8 2380.15  4272.1 2378.48  4301.0 2377.37  4507.0 2375.91  4529.3 2376.73
  4561.5 2375.58  4634.9 2375.23  4713.9 2375.34  4735.6 2373.96  4866.2 2372.46
  4951.4 2370.53  4992.3 2368.28  4992.8 2367.78  4999.1 2368.28  5042.5 2369.48
  5077.7 2369.18  5155.4 2373.81  5219.3 2373.27  5254.5 2373.88  5276.0 2375.36
  5296.1 2374.96  5382.0 2375.75  5410.3 2377.06  5438.6 2376.41  5558.8 2377.39
  5594.0 2378.51  5771.2 2378.64  5820.6 2379.73  5855.8 2379.15  6283.9 2380.30
#Mann=5,-1,0
  3751.8   0.045       0  4634.9    0.07       0  4992.3    0.07       0
  4999.1    0.07       0  5296.1   0.045       0
Bank Sta=4992.3,4999.1
Exp/Cntr=0.3,0.1

Type RM Length L Ch R = 1,35500,500,500,500
BEGIN DESCRIPTION:
Live Oak Creek 69.0
END DESCRIPTION:
XS GIS Cut Line= 3
      1342205.04      6877088.03      1343304.95      6877869.74
      1344155.02      6876787.98
#Sta/Elev= 30
  3650.6 2380.19  3672.7 2379.35  4002.3 2378.40  4389.4 2375.49  4525.0 2373.41
  4560.7 2374.26  4590.2 2372.63  4676.3 2372.11  4712.0 2369.78  4762.4 2370.13
  4782.9 2368.93  4816.2 2368.26  4848.5 2365.68  4919.8 2363.11  4981.6 2359.24
  4982.1 2358.74  4988.5 2359.24  5022.8 2359.77  5151.2 2367.55  5243.9 2369.74
  5271.4 2372.09  5321.1 2371.14  5428.6 2373.90  5499.4 2373.59  5585.9 2375.40
  5741.3 2375.73  5778.0 2376.90  6233.9 2378.77  6269.1 2379.90  6375.8 2379.51
#Mann=7,-1,0
  3650.6   0.045       0  4389.4    0.07       0  4782.9   0.035       0
  4816.2    0.07       0  4981.6    0.07       0  4988.5    0.07       0
  5499.4   0.045       0
Bank Sta=4981.6,4988.5
Exp/Cntr=0.3,0.1

Type RM Length L Ch R = 1,35000,482,482,482
BEGIN DESCRIPTION:
Live Oak Creek 68.0
END DESCRIPTION:
XS GIS Cut Line= 3
      1342505.03      6877938.02      1343354.86      6878353.61
      1344154.98      6877338.03
#Sta/Elev= 30
  4054.0 2375.55  4113.0 2376.03  4276.6 2373.85  4321.2 2374.44  4366.2 2372.79
  4465.8 2372.81  4501.3 2371.36  4591.6 2370.64  4816.3 2365.20  4844.6 2365.20
  4855.4 2363.31  4929.1 2356.69  4976.2 2354.83  4976.7 2354.33  4983.2 2354.83
  5019.0 2355.58  5025.4 2356.73  5039.8 2356.07  5075.1 2358.90  5203.3 2364.20
  5431.0 2369.81  5469.8 2369.74  5623.5 2372.30  5652.4 2371.48  5822.3 2372.65
  5844.8 2373.71  6008.3 2373.65  6064.4 2375.23  6093.3 2374.49  6292.9 2376.80
#Mann=6,-1,0
  4054.0    0.07       0  4591.6   0.035       0  4816.3    0.07       0
  4976.2    0.07       0  4983.2    0.07       0  5469.8   0.045       0
Bank Sta=4976.2,4983.2
Exp/Cntr=0.3,0.1

Type RM Length L Ch R = 1,34518,496,496,496
BEGIN DESCRIPTION:
Live Oak Creek 67.0
END DESCRIPTION:
XS GIS Cut Line= 4
      1342226.97      6878167.97      1343424.89      6878803.39
      1343513.43      6878803.39      1344414.39      6877662.87
#Sta/Elev= 30
  3614.0 2375.85  3623.0 2375.76  3945.3 2374.40  4011.2 2372.69  4137.5 2372.55
  4482.8 2367.80  4528.7 2368.13  4553.6 2366.65  4664.5 2365.41  4906.5 2356.91
  4944.8 2352.85  5006.6 2349.06  5007.1 2348.56  5013.7 2349.06  5020.1 2350.55
  5056.8 2352.07  5105.7 2356.53  5312.5 2363.02  5486.8 2366.42  5525.7 2367.38
  5554.6 2366.09  5608.9 2367.70  5630.0 2368.60  5795.8 2368.74  5853.1 2369.31
  5896.0 2370.56  5961.6 2369.97  5975.1 2370.01  6489.7 2373.27  6512.0 2373.19
#Mann=14,-1,0
  3614.0   0.045       0  3623.0    0.07       0  4482.8   0.035       0
  4553.6    0.07       0  5006.6    0.07       0  5013.7    0.07       0
  5486.8   0.035       0  5608.9   0.045       0  5630.0   0.035       0
  5795.8   0.045       0  5853.1    0.07       0  5961.6   0.045       0
  5975.1    0.07       0  6489.7   0.045       0
Bank Sta=5006.6,5013.7
Exp/Cntr=0.3,0.1

Type RM Length L Ch R = 1,34022,503,503,503
BEGIN DESCRIPTION:
Live Oak Creek 66.0
END DESCRIPTION:
XS GIS Cut Line= 4
      1342372.81      6878714.85      1343555.10      6879256.51
      1343654.06      6879246.10      1344518.62      6878178.42
#Sta/Elev= 30
  3650.3 2370.49  3993.7 2367.99  4031.1 2366.31  4191.7 2365.69  4226.1 2363.99
  4364.2 2363.81  4415.7 2360.61  4444.7 2361.29  4455.7 2363.47  4484.7 2361.11
  4642.7 2358.48  4823.2 2353.47  4892.2 2348.33  4920.7 2348.06  4976.5 2342.45
  4977.0 2341.95  4983.6 2342.45  5041.2 2347.32  5261.2 2356.27  5293.2 2357.09
  5465.3 2360.15  5554.2 2360.36  5626.1 2362.75  5838.8 2363.48  5867.5 2365.08
  5937.9 2364.22  6166.5 2366.84  6227.1 2366.06  6245.3 2366.18  6424.1 2367.21
#Mann=8,-1,0
  3650.3    0.07       0  4976.5    0.07       0  4983.6    0.07       0
  5261.2    0.16       0  5293.2    0.07       0  5465.3   0.035       0
  6227.1   0.045       0  6245.3   0.035       0
Bank Sta=4976.5,4983.6
Exp/Cntr=0.3,0.1

Type RM Length L Ch R = 1,33519,596,596,596
BEGIN DESCRIPTION:
Live Oak Creek 65.0
END DESCRIPTION:
XS GIS Cut Line= 4
      1342945.71      6879121.08      1343686.24      6879709.07
      1343810.31      6879694.01      1344877.89      6878662.88
#Sta/Elev= 30
  3985.1 2362.02  4117.6 2358.41  4138.4 2359.78  4146.4 2361.56  4188.5 2359.26
  4665.5 2349.45  4865.3 2342.61  4886.6 2339.96  4921.8 2340.18  4977.9 2336.58
  5016.5 2335.74  5017.0 2335.24  5023.7 2335.74  5126.9 2339.68  5183.5 2342.20
  5190.5 2344.36  5224.0 2345.47  5282.5 2349.27  5376.0 2350.76  5565.3 2353.52
  5593.6 2355.22  5648.8 2355.02  5777.5 2357.19  5811.8 2356.61  6085.8 2358.50
  6215.2 2359.28  6314.9 2360.83  6356.2 2360.18  6359.7 2360.18  6539.9 2361.45
#Mann=12,-1,0
  3985.1    0.07       0  5016.5    0.07       0  5023.7    0.07       0
  5126.9    0.16       0  5224.0    0.07       0  5376.0   0.035       0
  5648.8    0.07       0  5811.8   0.045       0  6085.8    0.07       0
  6215.2   0.045       0  6356.2    0.07       0  6359.7   0.045       0
Bank Sta=5016.5,5023.7
Exp/Cntr=0.3,0.1

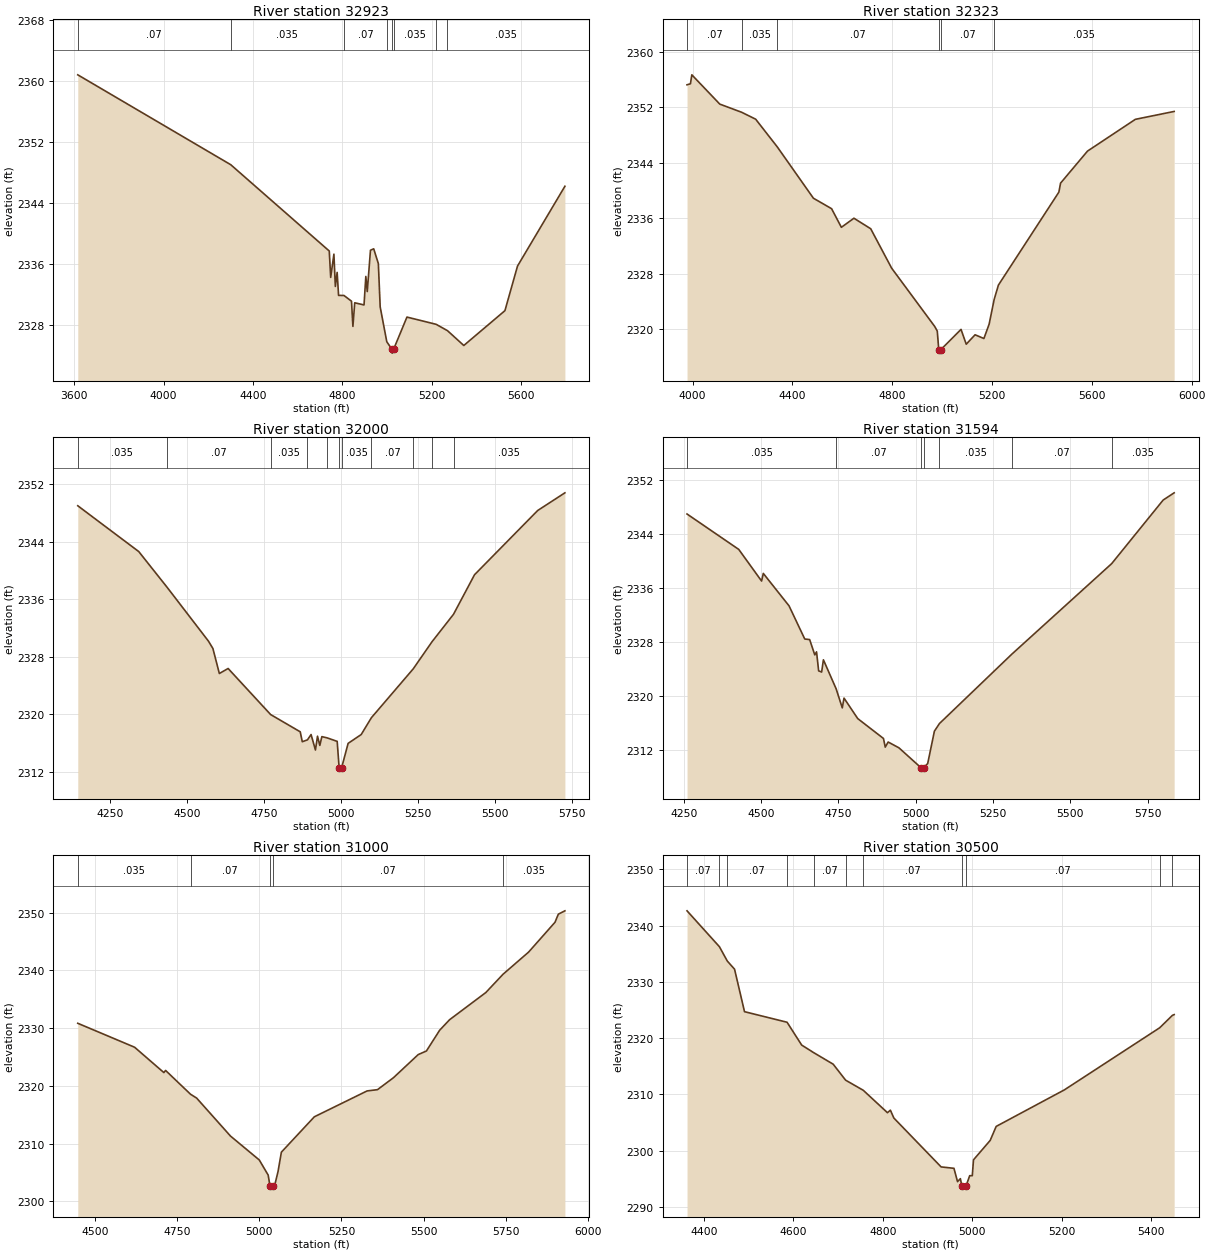
Type RM Length L Ch R = 1,32923,600,600,600
BEGIN DESCRIPTION:
Live Oak Creek 64.0
END DESCRIPTION:
XS GIS Cut Line= 3
      1342954.99      6879187.98      1343810.31      6880287.76
      1344393.63      6880819.00
#Sta/Elev= 30
  3615.3 2360.77  4300.6 2349.00  4741.9 2337.70  4748.3 2334.25  4762.7 2337.29
  4769.1 2333.06  4777.2 2334.90  4783.6 2331.89  4807.7 2331.88  4841.5 2331.13
  4847.8 2327.83  4856.0 2330.92  4897.6 2330.64  4905.7 2334.37  4912.1 2332.39
  4926.5 2337.80  4941.0 2337.99  4961.8 2336.05  4970.0 2330.38  4999.6 2325.82
  5022.8 2324.83  5023.3 2324.33  5030.1 2324.83  5089.9 2329.05  5220.9 2328.10
  5271.5 2327.27  5344.6 2325.33  5528.8 2329.89  5585.2 2335.73  5797.5 2346.18
#Mann=8,-1,0
  3615.3    0.07       0  4300.6   0.035       0  4807.7    0.07       0
  4999.6   0.035       0  5022.8   0.035       0  5030.1   0.035       0
  5220.9    0.07       0  5271.5   0.035       0
Bank Sta=5022.8,5030.1
Exp/Cntr=0.3,0.1

Type RM Length L Ch R = 1,32323,323,323,323
BEGIN DESCRIPTION:
Live Oak Creek 63.0
END DESCRIPTION:
XS GIS Cut Line= 4
      1343013.41      6879511.68      1343424.89      6880339.85
      1343430.10      6880485.68      1343955.79      6881193.54
#Sta/Elev= 30
  3977.5 2355.28  3991.2 2355.43  3996.8 2356.72  4108.8 2352.49  4196.4 2351.31
  4252.6 2350.31  4339.2 2346.31  4484.1 2338.89  4556.9 2337.38  4596.1 2334.69
  4646.5 2336.00  4713.7 2334.48  4797.7 2328.78  4970.5 2320.35  4980.5 2319.69
  4986.4 2317.01  4986.9 2316.51  4994.5 2317.01  5075.7 2319.94  5096.5 2317.80
  5132.0 2319.16  5167.4 2318.62  5188.3 2320.69  5208.4 2324.25  5225.5 2326.34
  5467.8 2339.77  5474.6 2341.07  5582.6 2345.70  5774.5 2350.29  5929.9 2351.43
#Mann=6,-1,0
  3977.5    0.07       0  4196.4   0.035       0  4339.2    0.07       0
  4986.4    0.07       0  4994.5    0.07       0  5208.4   0.035       0
Bank Sta=4986.4,4994.5
Exp/Cntr=0.3,0.1

Type RM Length L Ch R = 1,32000,406,406,406
BEGIN DESCRIPTION:
Live Oak Creek 62.0
END DESCRIPTION:
XS GIS Cut Line= 3
      1342617.62      6879996.11      1343183.56      6880637.80
      1343716.54      6881131.49
#Sta/Elev= 30
  4144.4 2349.00  4342.4 2342.63  4434.3 2337.67  4569.1 2330.15  4583.3 2329.14
  4604.2 2325.66  4632.7 2326.36  4770.8 2319.95  4866.9 2317.55  4873.6 2316.17
  4890.4 2316.43  4902.1 2317.17  4916.3 2315.02  4923.0 2316.94  4930.5 2315.66
  4937.2 2316.88  4954.8 2316.70  4986.9 2316.22  4993.2 2312.58  4993.7 2312.08
  5001.5 2312.58  5022.4 2315.94  5064.9 2317.17  5098.0 2319.51  5233.9 2326.31
  5294.9 2330.08  5364.7 2333.90  5432.9 2339.40  5638.1 2348.34  5726.5 2350.80
#Mann=11,-1,0
  4144.4   0.035       0  4434.3    0.07       0  4770.8   0.035       0
  4890.4    0.07       0  4954.8   0.035       0  4993.2   0.035       0
  5001.5   0.035       0  5098.0    0.07       0  5233.9   0.035       0
  5294.9    0.07       0  5364.7   0.035       0
Bank Sta=4993.2,5001.5
Exp/Cntr=0.3,0.1

Type RM Length L Ch R = 1,31594,594,594,594
BEGIN DESCRIPTION:
Live Oak Creek 61.0
END DESCRIPTION:
XS GIS Cut Line= 3
      1342549.88      6880199.19      1342893.64      6880871.10
      1343647.67      6881193.51
#Sta/Elev= 30
  4260.6 2346.97  4427.8 2341.72  4501.6 2337.03  4507.2 2338.16  4590.4 2333.35
  4641.2 2328.43  4657.0 2328.35  4673.6 2326.08  4679.3 2326.53  4686.1 2323.71
  4695.8 2323.53  4701.5 2325.35  4742.6 2321.05  4762.5 2318.22  4768.1 2319.67
  4812.5 2316.63  4895.7 2313.68  4901.4 2312.40  4910.8 2313.16  4945.8 2312.29
  5017.1 2309.34  5017.6 2308.84  5025.4 2309.34  5038.6 2309.96  5060.3 2314.76
  5076.7 2315.90  5310.5 2326.18  5633.4 2339.61  5799.9 2349.04  5835.4 2350.11
#Mann=7,-1,0
  4260.6   0.035       0  4742.6    0.07       0  5017.1    0.07       0
  5025.4    0.07       0  5076.7   0.035       0  5310.5    0.07       0
  5633.4   0.035       0
Bank Sta=5017.1,5025.4
Exp/Cntr=0.3,0.1

Type RM Length L Ch R = 1,31000,500,500,500
BEGIN DESCRIPTION:
Live Oak Creek 60.0
END DESCRIPTION:
XS GIS Cut Line= 3
      1342154.99      6881038.00      1342678.03      6881215.06
      1343604.96      6881288.00
#Sta/Elev= 30
  4447.8 2330.83  4620.7 2326.68  4709.7 2322.29  4715.0 2322.66  4791.0 2318.53
  4809.3 2317.88  4912.3 2311.30  5000.0 2307.15  5027.1 2304.53  5032.7 2302.60
  5033.2 2302.10  5041.0 2302.10  5041.5 2302.60  5047.1 2302.82  5057.1 2305.16
  5067.2 2308.50  5167.5 2314.63  5328.0 2319.11  5359.6 2319.33  5408.2 2321.40
  5483.6 2325.41  5508.5 2326.03  5548.7 2329.62  5578.8 2331.44  5689.1 2336.15
  5741.7 2339.33  5819.5 2343.17  5899.7 2348.33  5909.8 2349.73  5929.8 2350.31
#Mann=5,-1,0
  4447.8   0.035       0  4791.0    0.07       0  5032.7    0.07       0
  5041.5    0.07       0  5741.7   0.035       0
Bank Sta=5032.7,5041.5
Exp/Cntr=0.3,0.1

Type RM Length L Ch R = 1,30500,500,500,500
BEGIN DESCRIPTION:
Live Oak Creek 59.0
END DESCRIPTION:
XS GIS Cut Line= 3
      1342305.01      6882037.99      1342799.04      6881634.90
      1343205.00      6881438.00
#Sta/Elev= 30
  4362.4 2342.65  4434.7 2336.28  4452.5 2333.71  4468.6 2332.28  4490.9 2324.72
  4586.0 2322.84  4618.7 2318.78  4645.2 2317.45  4689.1 2315.38  4716.9 2312.54
  4756.2 2310.75  4810.4 2306.76  4816.9 2307.21  4824.8 2305.80  4930.3 2297.12
  4959.0 2296.87  4967.0 2294.50  4973.4 2295.03  4976.8 2293.67  4977.3 2293.17
  4985.8 2293.67  4994.2 2295.56  5000.0 2295.56  5002.7 2298.38  5040.0 2301.83
  5053.4 2304.32  5205.9 2310.82  5418.9 2321.86  5447.2 2324.06  5451.2 2324.20
#Mann=11,-1,0
  4362.4    0.07       0  4434.7   0.035       0  4452.5    0.07       0
  4586.0   0.035       0  4645.2    0.07       0  4716.9   0.035       0
  4756.2    0.07       0  4976.8    0.07       0  4985.8    0.07       0
  5418.9   0.035       0  5447.2    0.07       0
Bank Sta=4976.8,4985.8
Exp/Cntr=0.3,0.1