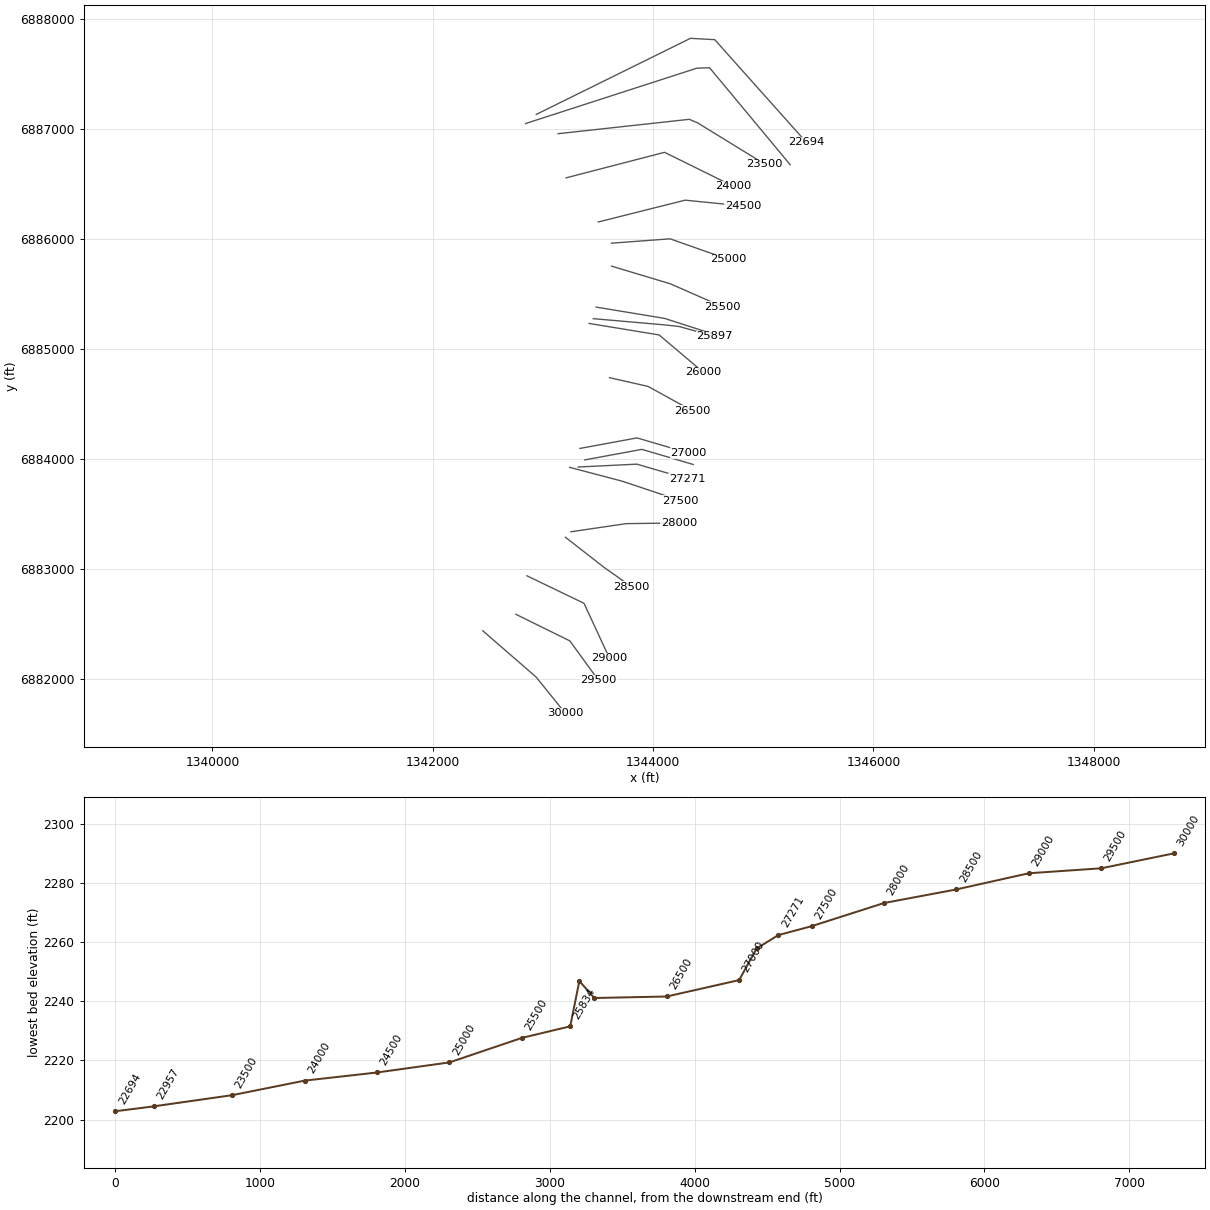
HEC-RAS study Live Oak Creek.prj: Live Oak Creek Base Level Engineering

--- Live Oak Creek.g01 (geometry) --- (continued)

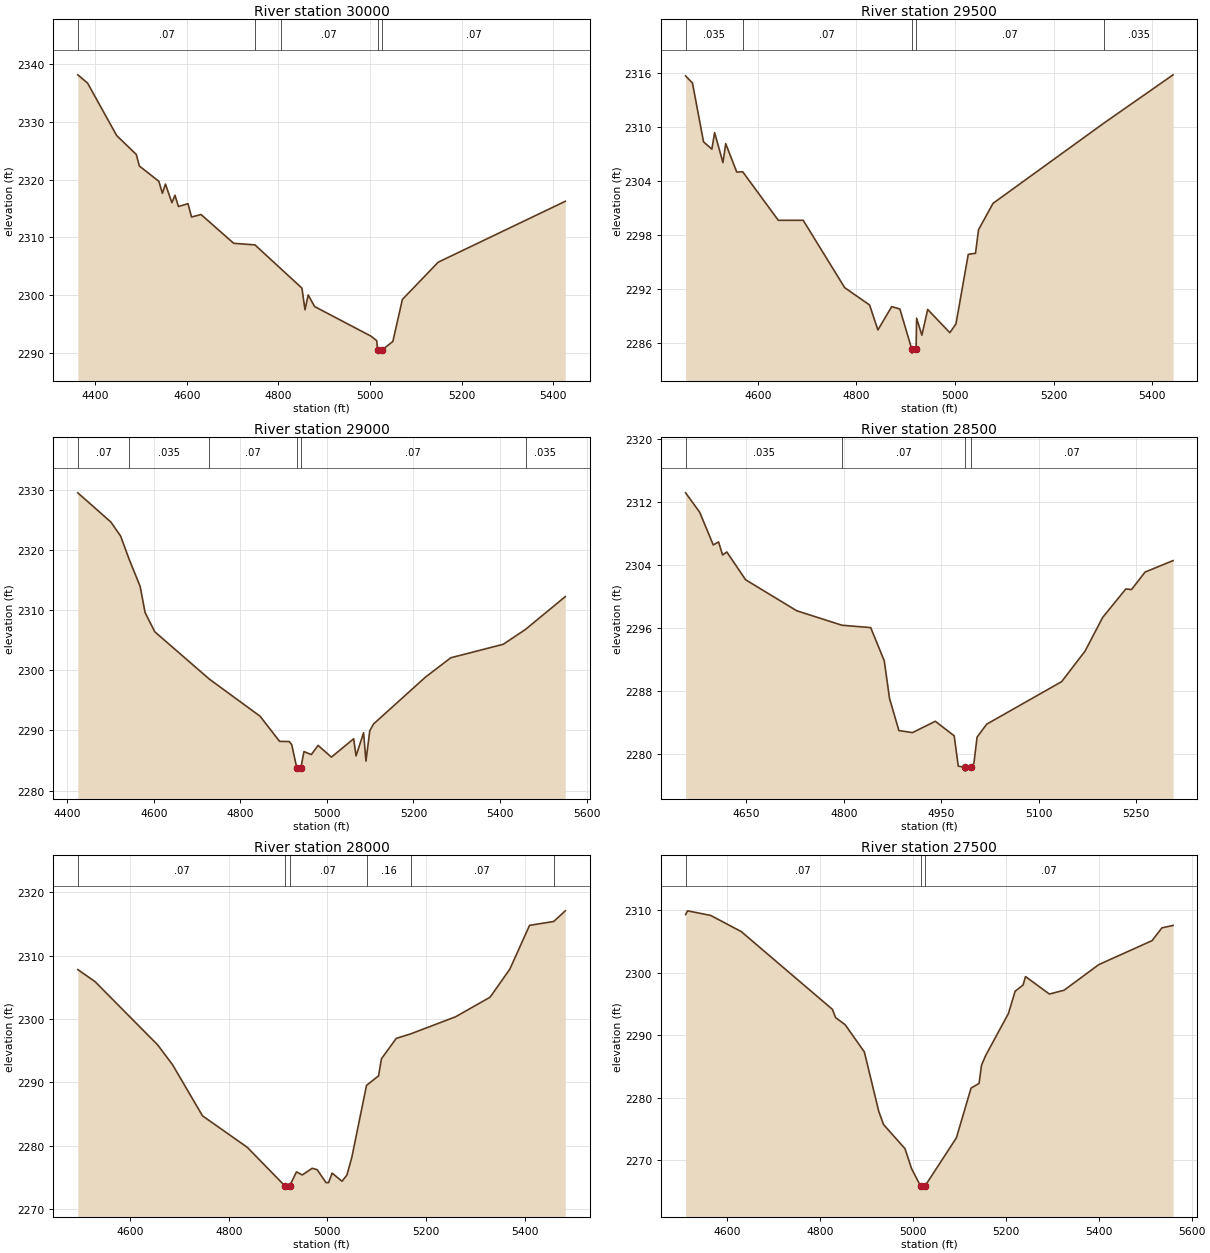
Type RM Length L Ch R = 1,30000,500,500,500
BEGIN DESCRIPTION:
Live Oak Creek 58.0
END DESCRIPTION:
XS GIS Cut Line= 3
      1342454.98      6882438.01      1342937.05      6882019.64
      1343205.03      6881687.97
#Sta/Elev= 30
  4361.7 2338.14  4383.1 2336.71  4446.7 2327.62  4489.5 2324.35  4496.1 2322.36
  4538.8 2319.70  4546.5 2317.63  4553.1 2319.23  4567.3 2315.99  4573.9 2317.29
  4581.6 2315.34  4602.4 2315.83  4610.1 2313.52  4630.9 2313.95  4702.2 2308.97
  4748.7 2308.69  4805.0 2304.58  4851.3 2301.20  4857.9 2297.46  4864.9 2300.03
  4878.8 2298.02  5002.3 2292.88  5014.6 2292.10  5016.5 2290.45  5017.0 2289.95
  5025.5 2290.45  5049.8 2291.97  5070.6 2299.24  5148.9 2305.70  5426.4 2316.24
#Mann=5,-1,0
  4361.7    0.07       0  4748.7   0.035       0  4805.0    0.07       0
  5016.5    0.07       0  5025.5    0.07       0
Bank Sta=5016.5,5025.5
Exp/Cntr=0.3,0.1

Type RM Length L Ch R = 1,29500,500,500,500
BEGIN DESCRIPTION:
Live Oak Creek 57.0
END DESCRIPTION:
XS GIS Cut Line= 3
      1342755.03      6882587.99      1343245.30      6882346.30
      1343504.99      6881988.02
#Sta/Elev= 30
  4453.4 2315.66  4467.4 2314.87  4489.8 2308.35  4506.7 2307.54  4512.3 2309.37
  4529.2 2306.05  4534.8 2308.15  4557.2 2305.00  4569.3 2305.03  4641.5 2299.65
  4692.0 2299.65  4776.2 2292.18  4826.7 2290.26  4843.6 2287.49  4871.6 2290.08
  4888.2 2289.81  4912.0 2285.42  4912.5 2284.92  4921.1 2285.42  4922.1 2288.80
  4932.8 2286.91  4944.6 2289.76  4989.5 2287.19  5002.0 2288.16  5026.9 2295.87
  5041.6 2295.99  5047.8 2298.61  5077.2 2301.53  5302.0 2310.42  5442.5 2315.78
#Mann=5,-1,0
  4453.4   0.035       0  4569.3    0.07       0  4912.0    0.07       0
  4921.1    0.07       0  5302.0   0.035       0
Bank Sta=4912,4921.1
Exp/Cntr=0.3,0.1

Type RM Length L Ch R = 1,29000,500,500,500
BEGIN DESCRIPTION:
Live Oak Creek 56.0
END DESCRIPTION:
XS GIS Cut Line= 3
      1342854.99      6882938.01      1343373.40      6882687.88
      1343604.99      6882188.02
#Sta/Elev= 30
  4424.4 2329.51  4500.8 2324.66  4523.4 2322.32  4543.3 2318.43  4568.6 2313.93
  4579.9 2309.61  4602.3 2306.41  4728.4 2298.54  4845.5 2292.38  4890.7 2288.19
  4913.0 2288.16  4918.8 2287.65  4930.6 2283.74  4931.1 2283.24  4939.8 2283.74
  4947.0 2286.49  4964.1 2285.99  4979.6 2287.52  5010.5 2285.57  5061.9 2288.62
  5067.4 2285.77  5084.8 2289.62  5090.3 2284.91  5099.1 2289.94  5107.7 2291.07
  5227.8 2298.87  5286.4 2302.09  5407.6 2304.33  5459.1 2306.81  5550.9 2312.25
#Mann=6,-1,0
  4424.4    0.07       0  4543.3   0.035       0  4728.4    0.07       0
  4930.6    0.07       0  4939.8    0.07       0  5459.1   0.035       0
Bank Sta=4930.6,4939.8
Exp/Cntr=0.3,0.1

Type RM Length L Ch R = 1,28500,500,500,500
BEGIN DESCRIPTION:
Live Oak Creek 55.0
END DESCRIPTION:
XS GIS Cut Line= 3
      1343204.96      6883288.03      1343554.63      6883014.89
      1343805.03      6882837.98
#Sta/Elev= 30
  4556.3 2313.11  4578.0 2310.65  4598.9 2306.49  4607.0 2306.88  4613.3 2305.22
  4619.8 2305.60  4648.6 2302.08  4727.3 2298.14  4797.0 2296.30  4841.2 2296.00
  4862.1 2291.78  4870.2 2287.00  4884.6 2282.93  4905.5 2282.67  4940.7 2284.11
  4969.7 2282.26  4976.0 2278.41  4985.8 2278.28  4986.3 2277.78  4995.2 2278.28
  5000.0 2278.75  5004.9 2282.09  5019.7 2283.74  5135.1 2289.14  5171.2 2293.03
  5198.2 2297.29  5233.9 2300.91  5242.6 2300.83  5263.5 2303.05  5306.6 2304.51
#Mann=4,-1,0
  4556.3   0.035       0  4797.0    0.07       0  4985.8    0.07       0
  4995.2    0.07       0
Bank Sta=4985.8,4995.2
Exp/Cntr=0.3,0.1

Type RM Length L Ch R = 1,28000,500,500,500
BEGIN DESCRIPTION:
Live Oak Creek 54.0
END DESCRIPTION:
XS GIS Cut Line= 3
      1343254.96      6883337.99      1343755.46      6883411.66
      1344237.42      6883417.97
#Sta/Elev= 30
  4494.1 2307.80  4529.0 2305.90  4655.9 2295.93  4686.2 2292.79  4746.8 2284.74
  4837.8 2279.76  4913.9 2273.68  4914.4 2273.18  4923.4 2273.68  4937.2 2275.90
  4949.0 2275.42  4969.2 2276.47  4979.3 2276.24  4997.2 2274.20  5002.3 2274.20
  5009.5 2275.71  5029.5 2274.42  5039.5 2275.40  5049.5 2278.22  5079.2 2289.54
  5103.6 2291.04  5109.5 2293.74  5139.5 2296.95  5168.4 2297.65  5259.6 2300.35
  5329.6 2303.44  5369.6 2307.86  5409.6 2314.77  5458.5 2315.38  5482.0 2317.06
#Mann=6,-1,0
  4494.1    0.07       0  4913.9    0.07       0  4923.4    0.07       0
  5079.2    0.16       0  5168.4    0.07       0  5458.5   0.035       0
Bank Sta=4913.9,4923.4
Exp/Cntr=0.3,0.1

Type RM Length L Ch R = 1,27500,229,229,229
BEGIN DESCRIPTION:
Live Oak Creek 53.0
END DESCRIPTION:
XS GIS Cut Line= 3
      1343242.59      6883923.18      1343716.64      6883798.39
      1344247.83      6883621.09
#Sta/Elev= 30
  4509.8 2309.33  4514.0 2309.93  4564.0 2309.19  4629.8 2306.60  4826.2 2294.14
  4832.9 2292.83  4853.5 2291.69  4894.9 2287.33  4925.9 2277.82  4936.3 2275.69
  4982.4 2271.84  4996.6 2268.64  5016.0 2265.85  5016.5 2265.35  5025.6 2265.85
  5093.2 2273.57  5124.8 2281.54  5142.0 2282.28  5147.3 2285.21  5156.4 2286.78
  5205.2 2293.47  5219.7 2297.05  5236.8 2298.04  5242.1 2299.40  5293.5 2296.60
  5325.1 2297.21  5400.1 2301.32  5514.8 2305.16  5535.9 2307.20  5560.0 2307.59
#Mann=3,-1,0
  4509.8    0.07       0  5016.0    0.07       0  5025.6    0.07       0
Bank Sta=5016,5025.6
Exp/Cntr=0.3,0.1

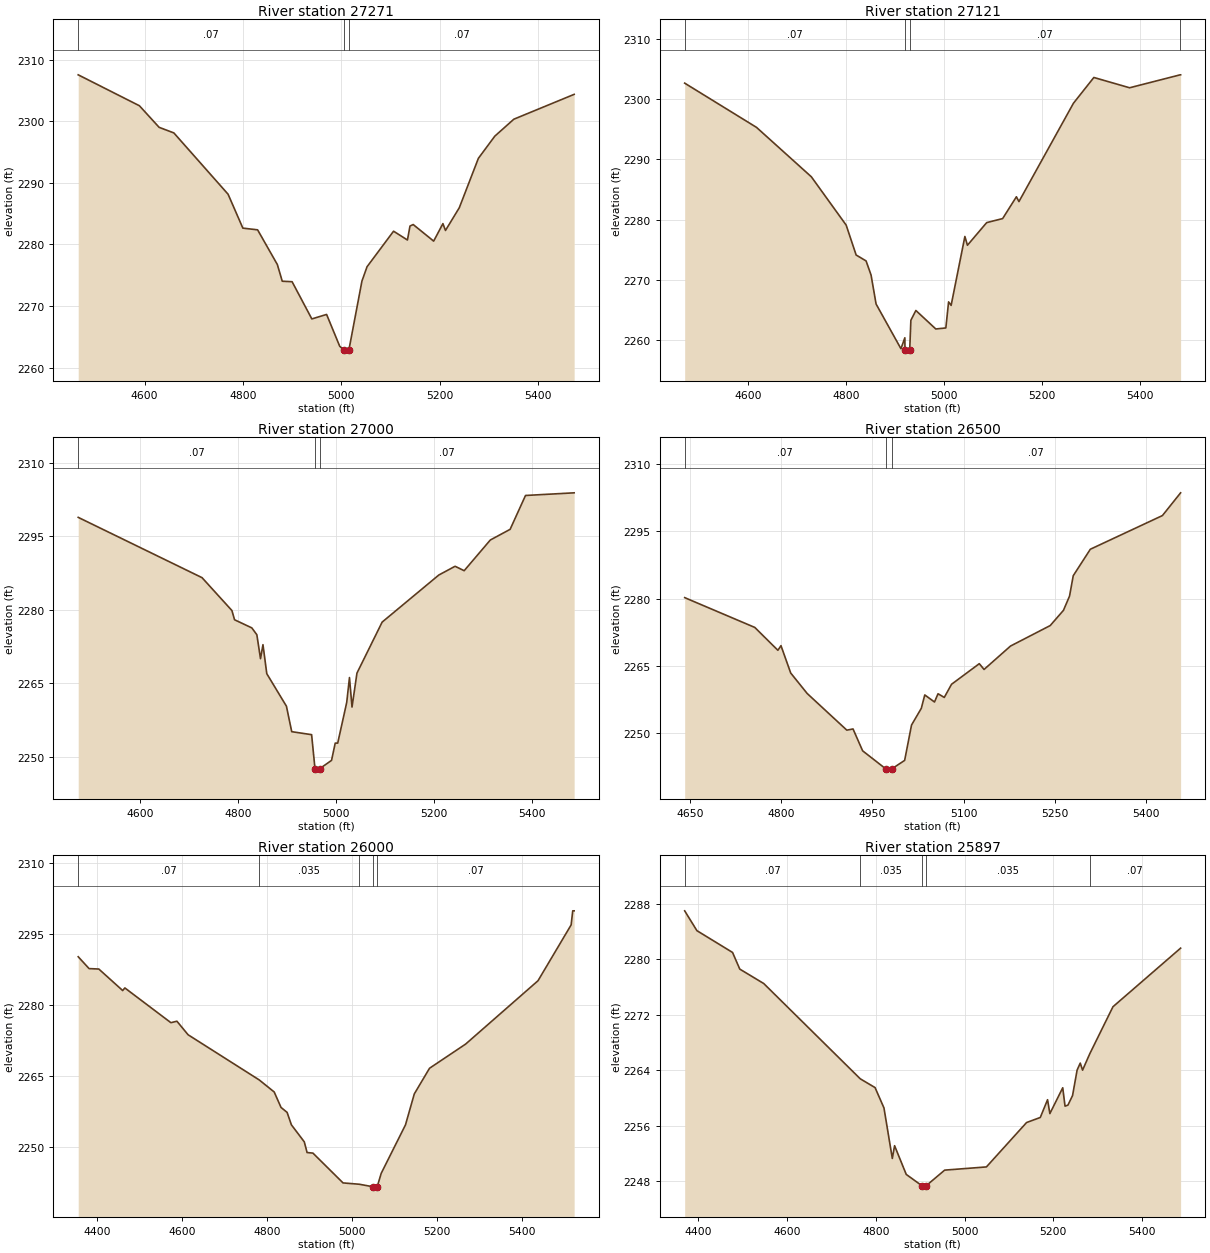
Type RM Length L Ch R = 1,27271,150,150,150
BEGIN DESCRIPTION:
Live Oak Creek 52.6
END DESCRIPTION:
XS GIS Cut Line= 3
      1343320.80      6883926.22      1343853.31      6883952.26
      1344308.98      6883819.02
#Sta/Elev= 30
  4465.1 2307.52  4589.5 2302.50  4629.5 2299.00  4659.5 2298.09  4769.7 2288.14
  4799.7 2282.64  4829.7 2282.36  4869.8 2276.73  4879.8 2274.02  4899.8 2273.94
  4939.9 2267.90  4969.9 2268.63  4996.6 2263.46  5005.6 2262.85  5006.1 2262.35
  5015.2 2262.85  5041.7 2274.04  5052.1 2276.37  5106.0 2282.14  5134.2 2280.71
  5139.4 2282.98  5145.9 2283.22  5187.5 2280.53  5206.3 2283.37  5211.5 2282.26
  5239.6 2285.95  5278.4 2293.97  5311.8 2297.57  5350.5 2300.32  5473.0 2304.35
#Mann=3,-1,0
  4465.1    0.07       0  5005.6    0.07       0  5015.2    0.07       0
Bank Sta=5005.6,5015.2
Exp/Cntr=0.3,0.1

Type RM Length L Ch R = 1,27121,121,121,121
BEGIN DESCRIPTION:
Live Oak Creek 52.5
END DESCRIPTION:
XS GIS Cut Line= 3
      1343380.63      6883990.89      1343898.89      6884086.49
      1344364.99      6883949.22
#Sta/Elev= 30
  4469.9 2302.67  4616.7 2295.32  4728.6 2287.12  4799.7 2279.10  4820.1 2274.13
  4840.4 2273.15  4850.6 2270.80  4860.8 2266.00  4911.6 2258.57  4919.6 2260.39
  4919.8 2258.34  4920.3 2257.84  4929.5 2258.34  4931.9 2263.30  4942.1 2264.92
  4982.8 2261.85  5003.3 2262.02  5008.9 2266.35  5014.1 2265.77  5042.2 2277.21
  5047.4 2275.75  5086.7 2279.51  5119.3 2280.18  5147.4 2283.80  5152.6 2283.00
  5263.9 2299.33  5305.6 2303.61  5378.6 2301.90  5481.9 2304.05  5482.8 2304.05
#Mann=4,-1,0
  4469.9    0.07       0  4919.8    0.07       0  4929.5    0.07       0
  5481.9   0.035       0
Bank Sta=4919.8,4929.5
Exp/Cntr=0.3,0.1

Type RM Length L Ch R = 1,27000,500,500,500
BEGIN DESCRIPTION:
Live Oak Creek 52.0
END DESCRIPTION:
XS GIS Cut Line= 3
      1343336.36      6884095.06      1343854.62      6884190.66
      1344320.34      6884053.50
#Sta/Elev= 30
  4473.0 2298.86  4725.8 2286.57  4786.8 2279.87  4792.2 2277.99  4827.5 2276.33
  4837.7 2274.94  4845.2 2270.06  4850.2 2272.91  4858.0 2267.00  4898.1 2260.37
  4908.9 2255.18  4949.5 2254.57  4956.4 2247.64  4956.9 2247.14  4966.1 2247.64
  4990.2 2249.33  4997.7 2252.85  5002.8 2252.85  5021.2 2261.15  5026.8 2266.21
  5032.0 2260.20  5042.1 2267.12  5093.5 2277.51  5209.1 2287.10  5242.4 2288.89
  5261.0 2287.99  5314.3 2294.24  5354.8 2296.42  5386.2 2303.32  5485.5 2303.86
#Mann=3,-1,0
  4473.0    0.07       0  4956.4    0.07       0  4966.1    0.07       0
Bank Sta=4956.4,4966.1
Exp/Cntr=0.3,0.1

Type RM Length L Ch R = 1,26500,500,500,500
BEGIN DESCRIPTION:
Live Oak Creek 51.0
END DESCRIPTION:
XS GIS Cut Line= 3
      1343604.98      6884738.00      1343954.95      6884658.40
      1344355.04      6884437.98
#Sta/Elev= 30
  4641.1 2280.22  4756.4 2273.59  4794.4 2268.50  4799.5 2269.53  4815.5 2263.44
  4842.6 2258.88  4907.8 2250.72  4918.0 2250.99  4933.8 2246.12  4971.9 2242.10
  4972.4 2241.60  4981.7 2242.10  5002.9 2243.99  5014.2 2251.85  5030.3 2255.58
  5036.0 2258.56  5052.0 2256.99  5057.8 2258.82  5068.1 2258.01  5080.0 2260.93
  5125.7 2265.52  5133.5 2264.23  5177.0 2269.44  5242.3 2274.00  5264.1 2277.39
  5274.1 2280.56  5280.2 2285.10  5308.3 2290.99  5426.9 2298.49  5456.8 2303.55
#Mann=3,-1,0
  4641.1    0.07       0  4971.9    0.07       0  4981.7    0.07       0
Bank Sta=4971.9,4981.7
Exp/Cntr=0.3,0.1

Type RM Length L Ch R = 1,26000,103,103,103
BEGIN DESCRIPTION:
Live Oak Creek 50.0
END DESCRIPTION:
XS GIS Cut Line= 3
      1343419.71      6885230.47      1344055.12      6885126.20
      1344454.98      6884788.02
#Sta/Elev= 30
  4356.1 2290.12  4381.7 2287.62  4404.6 2287.53  4460.8 2282.99  4465.9 2283.54
  4574.3 2276.21  4588.5 2276.52  4614.8 2273.66  4782.1 2264.14  4817.5 2261.59
  4833.6 2258.33  4847.9 2257.28  4858.0 2254.66  4888.4 2251.06  4894.9 2248.81
  4908.7 2248.69  4979.6 2242.40  5017.8 2242.12  5050.1 2241.59  5050.6 2241.09
  5060.0 2241.59  5069.4 2244.41  5126.6 2254.65  5147.4 2261.19  5183.2 2266.59
  5268.3 2271.70  5438.6 2285.06  5516.6 2296.84  5520.4 2299.81  5523.7 2299.81
#Mann=5,-1,0
  4356.1    0.07       0  4782.1   0.035       0  5017.8    0.07       0
  5050.1   0.035       0  5060.0    0.07       0
Bank Sta=5050.1,5060
Exp/Cntr=0.3,0.1

Type RM Length L Ch R = 1,25897,63,63,63
BEGIN DESCRIPTION:
Live Oak Creek 50.6
END DESCRIPTION:
XS GIS Cut Line= 4
      1343457.51      6885273.88      1344086.38      6885219.19
      1344233.52      6885203.57      1344559.75      6885112.94
#Sta/Elev= 30
  4369.1 2286.96  4396.7 2284.10  4477.0 2280.96  4493.3 2278.56  4547.3 2276.48
  4764.9 2262.74  4798.2 2261.48  4818.3 2258.54  4837.1 2251.26  4842.2 2253.10
  4868.5 2248.96  4903.7 2247.34  4904.2 2246.84  4913.6 2247.34  4955.1 2249.58
  5049.2 2250.04  5139.7 2256.44  5170.6 2257.17  5187.0 2259.73  5192.2 2257.73
  5221.2 2261.45  5226.4 2258.80  5232.9 2258.95  5243.3 2260.32  5253.6 2264.00
  5260.7 2265.01  5265.9 2263.99  5281.9 2266.32  5334.4 2273.13  5486.9 2281.58
#Mann=5,-1,0
  4369.1    0.07       0  4764.9   0.035       0  4903.7   0.035       0
  4913.6   0.035       0  5281.9    0.07       0
Bank Sta=4903.7,4913.6
Exp/Cntr=0.3,0.1

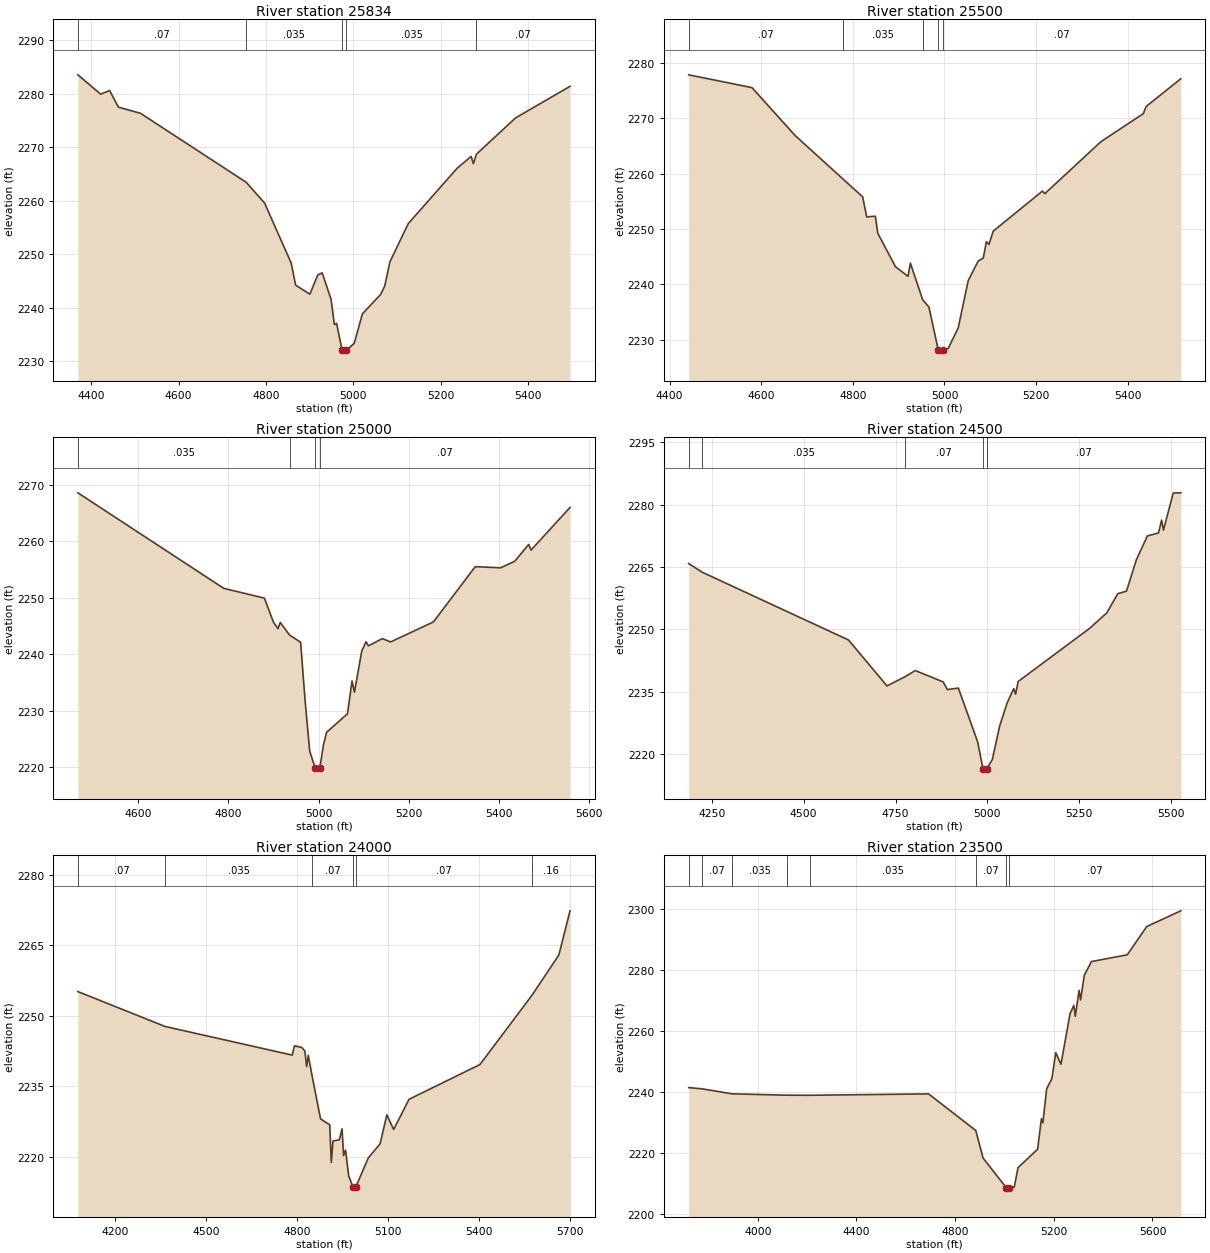
Type RM Length L Ch R = 1,25834,334,334,334
BEGIN DESCRIPTION:
Live Oak Creek 50.5
END DESCRIPTION:
XS GIS Cut Line= 3
      1343483.47      6885378.91      1344104.61      6885276.48
      1344577.23      6885124.15
#Sta/Elev= 30
  4369.6 2283.49  4421.8 2279.87  4442.1 2280.56  4462.3 2277.45  4513.0 2276.30
  4754.6 2263.43  4796.8 2259.55  4857.6 2248.35  4867.8 2244.22  4900.4 2242.53
  4918.4 2246.11  4928.6 2246.51  4948.9 2241.56  4956.5 2236.85  4961.6 2237.07
  4974.3 2232.02  4974.8 2231.52  4984.2 2232.02  5002.0 2233.37  5020.6 2238.85
  5062.6 2242.50  5071.8 2244.08  5083.6 2248.57  5125.6 2255.71  5237.3 2266.04
  5269.4 2268.25  5274.6 2266.92  5281.5 2268.66  5370.8 2275.43  5495.7 2281.34
#Mann=5,-1,0
  4369.6    0.07       0  4754.6   0.035       0  4974.3   0.035       0
  4984.2   0.035       0  5281.5    0.07       0
Bank Sta=4974.3,4984.2
Exp/Cntr=0.3,0.1

Type RM Length L Ch R = 1,25500,500,500,500
BEGIN DESCRIPTION:
Live Oak Creek 49.0
END DESCRIPTION:
XS GIS Cut Line= 3
      1343622.76      6885751.32      1344157.49      6885590.46
      1344629.93      6885382.96
#Sta/Elev= 30
  4441.6 2277.82  4579.8 2275.51  4673.6 2266.90  4778.9 2258.99  4821.4 2255.81
  4830.3 2252.19  4849.2 2252.31  4854.4 2249.25  4893.0 2243.21  4920.4 2241.46
  4925.6 2243.84  4952.4 2237.26  4966.1 2235.92  4986.7 2228.11  4987.2 2227.61
  4996.7 2228.11  5008.2 2228.46  5030.0 2232.14  5051.9 2240.69  5073.7 2244.23
  5084.7 2244.76  5091.6 2247.72  5097.1 2247.21  5106.5 2249.62  5213.9 2256.84
  5219.3 2256.39  5341.6 2265.76  5434.2 2270.82  5440.5 2272.12  5516.0 2277.11
#Mann=5,-1,0
  4441.6    0.07       0  4778.9   0.035       0  4952.4    0.07       0
  4986.7    0.07       0  4996.7    0.07       0
Bank Sta=4986.7,4996.7
Exp/Cntr=0.3,0.1

Type RM Length L Ch R = 1,25000,500,500,500
BEGIN DESCRIPTION:
Live Oak Creek 48.0
END DESCRIPTION:
XS GIS Cut Line= 3
      1343622.82      6885959.64      1344154.74      6885999.32
      1344680.05      6885813.82
#Sta/Elev= 30
  4466.6 2268.61  4789.7 2251.70  4879.9 2249.96  4900.0 2245.70  4910.0 2244.56
  4915.0 2245.66  4935.5 2243.43  4960.1 2242.16  4970.2 2231.71  4980.2 2222.90
  4992.6 2219.83  4993.1 2219.33  5002.6 2219.83  5010.9 2224.05  5017.6 2226.20
  5063.9 2229.48  5074.1 2235.29  5079.4 2233.31  5095.7 2240.62  5105.1 2242.24
  5110.4 2241.51  5141.3 2242.80  5159.4 2242.20  5254.4 2245.75  5347.1 2255.54
  5403.3 2255.33  5434.6 2256.49  5465.5 2259.48  5470.8 2258.47  5557.1 2266.02
#Mann=4,-1,0
  4466.6   0.035       0  4935.5    0.07       0  4992.6    0.07       0
  5002.6    0.07       0
Bank Sta=4992.6,5002.6
Exp/Cntr=0.3,0.1

Type RM Length L Ch R = 1,24500,500,500,500
BEGIN DESCRIPTION:
Live Oak Creek 47.0
END DESCRIPTION:
XS GIS Cut Line= 3
      1343503.05      6886152.35      1344291.54      6886350.44
      1344815.54      6886298.18
#Sta/Elev= 30
  4187.0 2265.82  4224.0 2263.73  4622.1 2247.44  4726.8 2236.40  4776.7 2238.65
  4803.9 2240.10  4879.8 2237.37  4891.3 2235.53  4921.1 2235.88  4973.6 2222.97
  4988.2 2216.42  4988.7 2215.92  4998.3 2216.42  5013.5 2218.71  5033.6 2226.78
  5053.7 2232.27  5071.9 2235.77  5076.9 2234.40  5083.9 2237.47  5278.2 2250.23
  5325.1 2253.96  5355.2 2258.59  5378.8 2259.18  5405.5 2266.70  5435.6 2272.45
  5465.8 2273.17  5474.4 2276.26  5479.4 2273.85  5506.0 2282.78  5526.6 2282.82
#Mann=5,-1,0
  4187.0    0.07       0  4224.0   0.035       0  4776.7    0.07       0
  4988.2    0.07       0  4998.3    0.07       0
Bank Sta=4988.2,4998.3
Exp/Cntr=0.3,0.1

Type RM Length L Ch R = 1,24000,500,500,500
BEGIN DESCRIPTION:
Live Oak Creek 46.0
END DESCRIPTION:
XS GIS Cut Line= 3
      1343211.31      6886553.38      1344104.53      6886785.16
      1344731.12      6886475.79
#Sta/Elev= 30
  4077.2 2255.18  4364.3 2247.77  4783.5 2241.67  4790.5 2243.64  4814.5 2243.32
  4824.9 2242.56  4831.1 2239.24  4836.3 2241.63  4850.0 2236.88  4876.8 2228.11
  4907.1 2226.84  4912.2 2218.86  4917.8 2223.41  4938.5 2223.65  4947.6 2225.99
  4952.8 2220.29  4959.2 2221.47  4969.5 2216.00  4983.2 2213.67  4983.7 2213.17
  4993.3 2213.67  5034.0 2219.81  5072.8 2222.78  5095.3 2228.97  5117.7 2225.85
  5168.2 2232.27  5402.0 2239.67  5573.4 2254.39  5662.0 2262.97  5698.8 2272.36
#Mann=6,-1,0
  4077.2    0.07       0  4364.3   0.035       0  4850.0    0.07       0
  4983.2    0.07       0  4993.3    0.07       0  5573.4    0.16       0
Bank Sta=4983.2,4993.3
Exp/Cntr=0.3,0.1

Type RM Length L Ch R = 1,23500,543,543,543
BEGIN DESCRIPTION:
Live Oak Creek 45.0
END DESCRIPTION:
XS GIS Cut Line= 4
      1343138.43      6886954.43      1344329.10      6887085.07
      1344404.51      6887052.91      1345013.45      6886678.38
#Sta/Elev= 30
  3720.2 2241.56  3775.1 2241.15  3897.1 2239.51  4118.6 2239.07  4211.9 2239.05
  4692.6 2239.49  4883.8 2227.50  4913.4 2218.46  5007.2 2208.76  5007.7 2208.26
  5017.4 2208.76  5039.8 2208.94  5055.2 2215.32  5134.5 2221.34  5149.9 2231.35
  5155.8 2230.00  5171.2 2241.16  5192.5 2244.53  5207.9 2253.06  5229.2 2249.20
  5265.9 2265.81  5281.3 2268.52  5287.2 2264.98  5302.6 2273.42  5308.5 2270.30
  5323.9 2278.44  5352.8 2282.90  5497.8 2285.12  5577.1 2294.40  5714.9 2299.54
#Mann=8,-1,0
  3720.2    0.16       0  3775.1    0.07       0  3897.1   0.035       0
  4118.6    0.07       0  4211.9   0.035       0  4883.8    0.07       0
  5007.2    0.07       0  5017.4    0.07       0
Bank Sta=5007.2,5017.4
Exp/Cntr=0.3,0.1

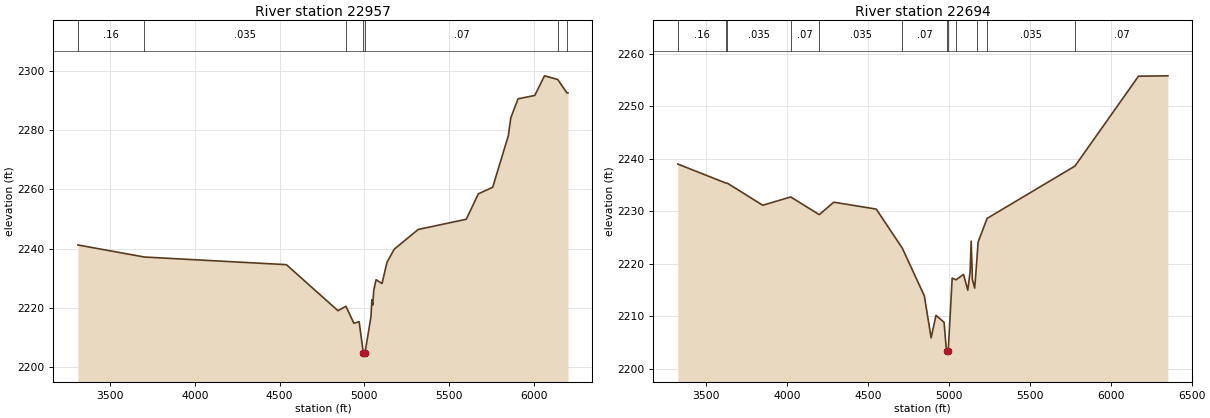
Type RM Length L Ch R = 1,22957,263,263,263
BEGIN DESCRIPTION:
Live Oak Creek 44.0
END DESCRIPTION:
XS GIS Cut Line= 4
      1342843.25      6887046.72      1344398.85      6887549.91
      1344513.43      6887553.39      1345245.40      6886672.25
#Sta/Elev= 30
  3308.6 2241.29  3701.5 2237.22  4540.1 2234.65  4844.9 2219.12  4891.8 2220.62
  4938.9 2214.88  4969.7 2215.43  4994.6 2204.97  4995.1 2204.47  5004.8 2204.97
  5039.8 2217.15  5045.1 2222.79  5050.1 2221.01  5056.5 2226.11  5070.1 2229.57
  5105.2 2228.29  5133.9 2235.37  5176.9 2239.85  5318.8 2246.52  5602.6 2249.96
  5674.3 2258.54  5758.9 2260.76  5851.3 2278.15  5865.7 2284.15  5908.6 2290.59
  6007.6 2291.72  6064.9 2298.34  6142.7 2297.12  6197.6 2292.60  6203.7 2292.57
#Mann=7,-1,0
  3308.6    0.16       0  3701.5   0.035       0  4891.8    0.07       0
  4994.6    0.07       0  5004.8    0.07       0  6142.7   0.035       0
  6197.6    0.07       0
Bank Sta=4994.6,5004.8
Exp/Cntr=0.3,0.1

Type RM Length L Ch R = 1,22694,694,694,694
BEGIN DESCRIPTION:
Live Oak Creek 43.0
END DESCRIPTION:
XS GIS Cut Line= 4
      1342940.50      6887129.77      1344339.82      6887820.75
      1344560.31      6887808.60      1345390.95      6886877.37
#Sta/Elev= 30
  3323.7 2238.99  3620.7 2235.37  3630.3 2235.34  3848.9 2231.15  4021.6 2232.73
  4197.9 2229.37  4287.9 2231.73  4550.3 2230.42  4711.3 2223.00  4847.7 2213.90
  4889.5 2205.93  4919.6 2210.21  4969.6 2208.88  4984.6 2203.33  4985.1 2202.83
  4994.8 2203.33  5019.7 2217.30  5042.8 2216.96  5089.8 2217.99  5116.2 2214.99
  5130.4 2218.48  5137.1 2224.32  5144.6 2217.04  5158.8 2215.38  5171.8 2220.54
  5179.7 2224.13  5235.6 2228.65  5778.5 2238.60  6171.3 2255.70  6353.0 2255.77
#Mann=12,-1,0
  3323.7    0.16       0  3620.7    0.07       0  3630.3   0.035       0
  4021.6    0.07       0  4197.9   0.035       0  4711.3    0.07       0
  4984.6    0.07       0  4994.8    0.07       0  5042.8   0.035       0
  5171.8    0.07       0  5235.6   0.035       0  5778.5    0.07       0
Bank Sta=4984.6,4994.8
Exp/Cntr=0.3,0.1