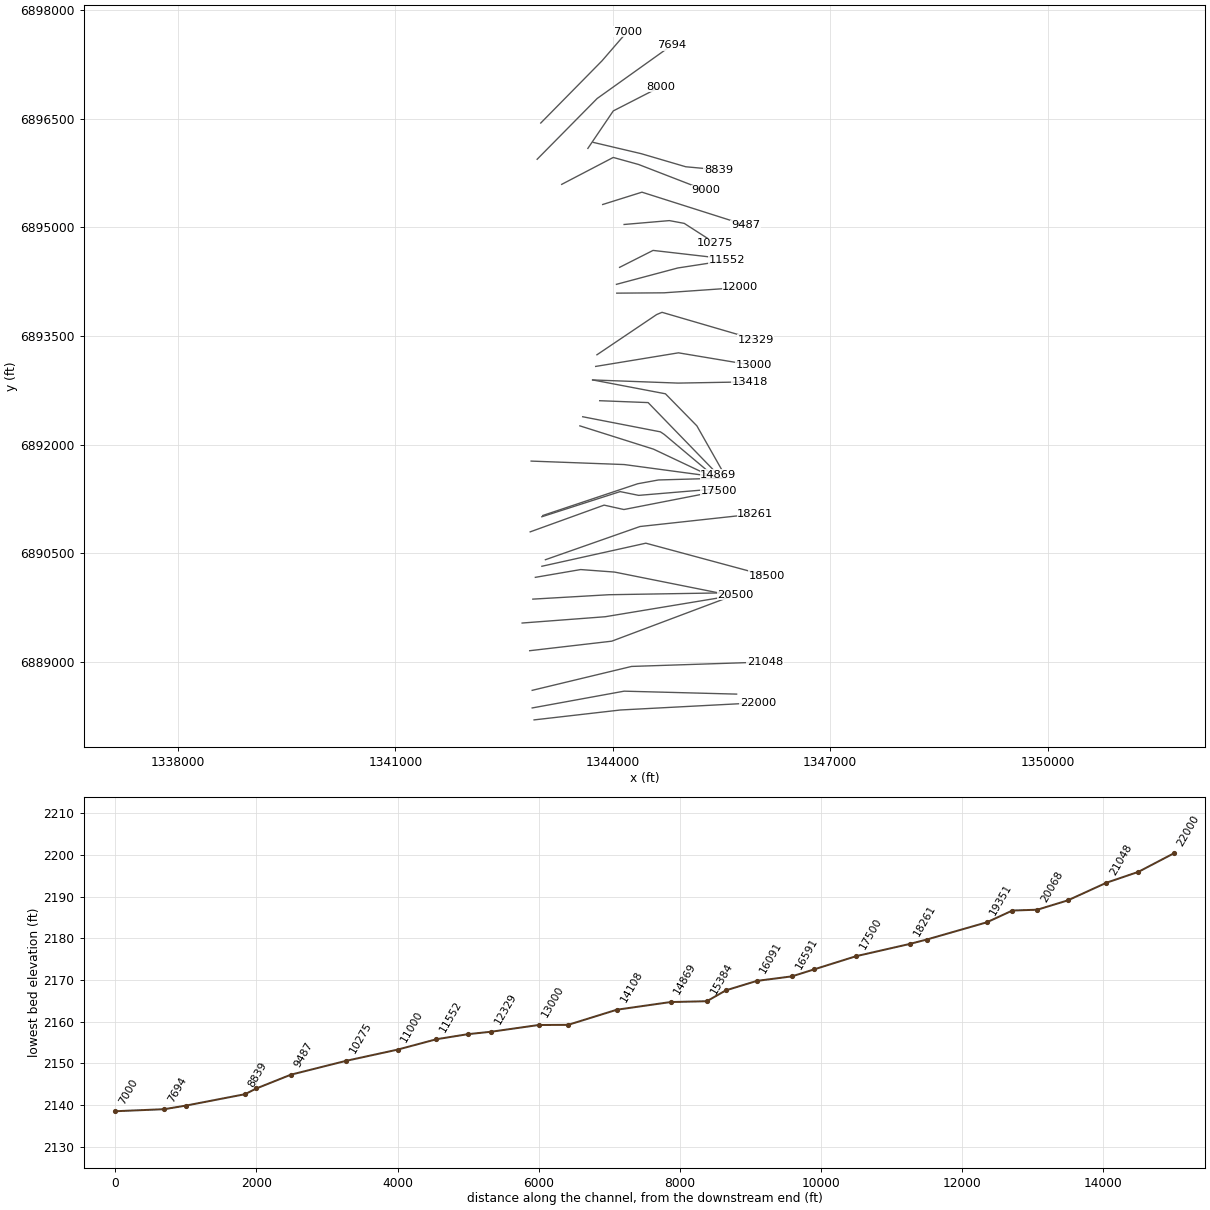
HEC-RAS study Live Oak Creek.prj: Live Oak Creek Base Level Engineering

--- Live Oak Creek.g01 (geometry) --- (continued)

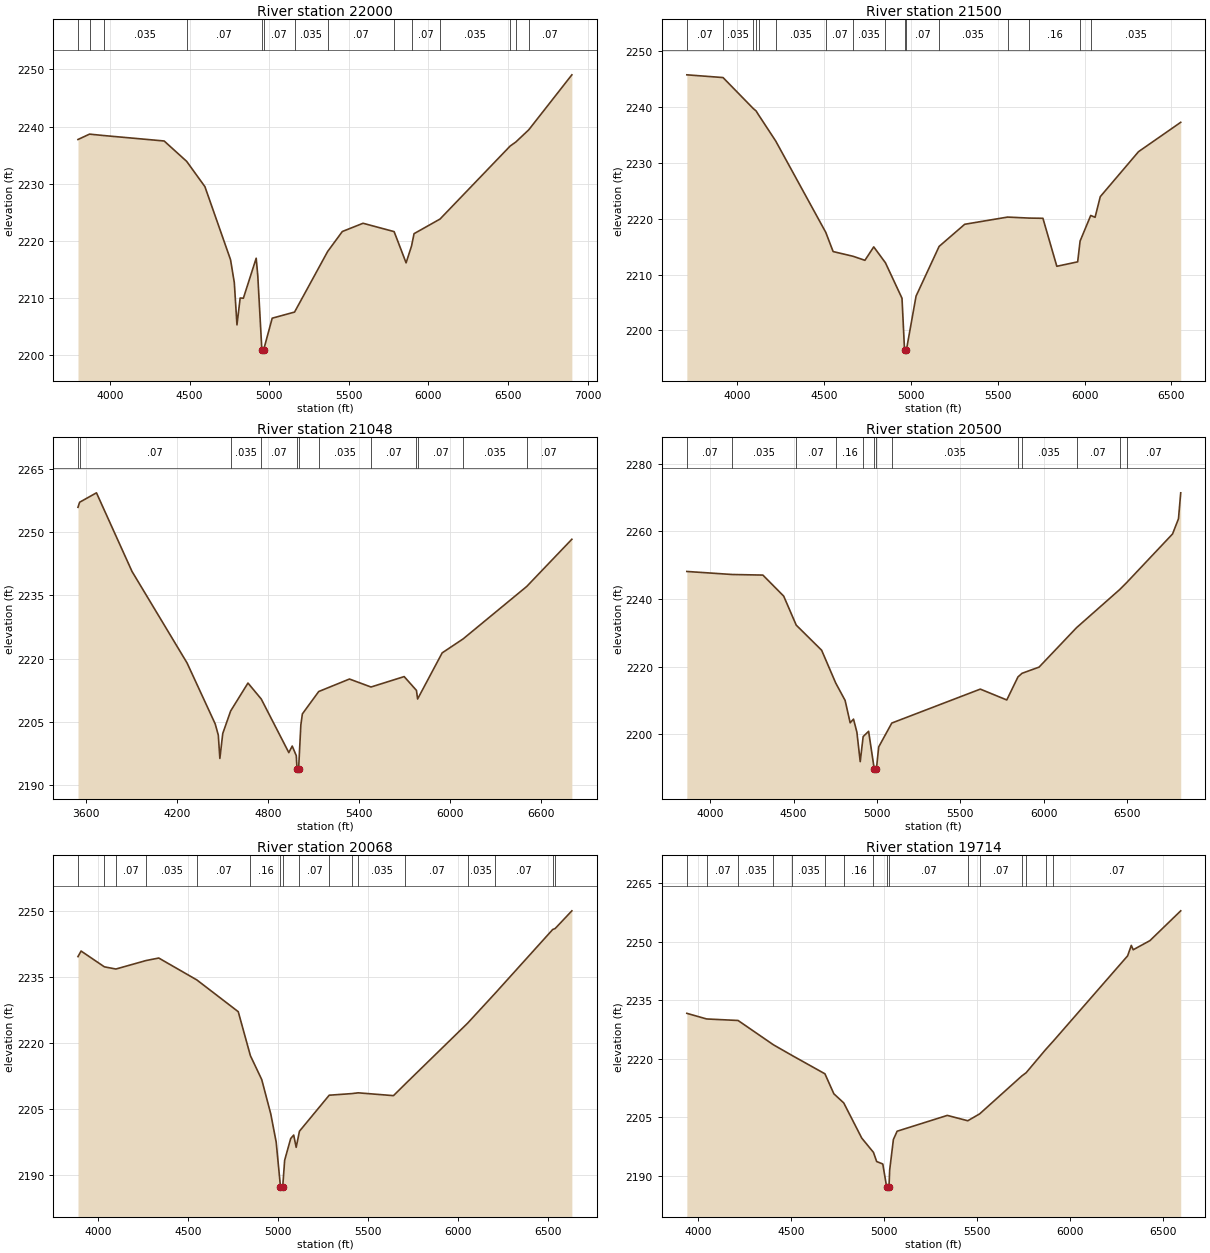
Type RM Length L Ch R = 1,22000,500,500,500
BEGIN DESCRIPTION:
Live Oak Creek 42.0
END DESCRIPTION:
XS GIS Cut Line= 3
      1342912.74      6888201.25      1344106.31      6888338.18
      1346004.99      6888438.00
#Sta/Elev= 30
  3798.6 2237.73  3871.3 2238.67  3961.1 2238.42  4339.9 2237.47  4481.6 2233.90
  4596.1 2229.48  4757.1 2216.70  4780.7 2212.70  4797.4 2205.31  4817.5 2210.01
  4837.6 2209.97  4918.2 2216.97  4928.2 2213.89  4953.9 2200.87  4954.4 2200.37
  4964.2 2200.87  5018.7 2206.48  5159.2 2207.55  5367.0 2218.14  5459.3 2221.64
  5589.5 2223.08  5784.7 2221.62  5859.9 2216.16  5894.1 2219.11  5909.9 2221.26
  6073.2 2223.82  6513.8 2236.59  6548.7 2237.28  6630.4 2239.42  6901.3 2249.04
#Mann=14,-1,0
  3798.6   0.035       0  3871.3    0.07       0  3961.1   0.035       0
  4481.6    0.07       0  4953.9    0.07       0  4964.2    0.07       0
  5159.2   0.035       0  5367.0    0.07       0  5784.7    0.16       0
  5894.1    0.07       0  6073.2   0.035       0  6513.8    0.07       0
  6548.7   0.035       0  6630.4    0.07       0
Bank Sta=4953.9,4964.2
Exp/Cntr=0.3,0.1

Type RM Length L Ch R = 1,21500,452,452,452
BEGIN DESCRIPTION:
Live Oak Creek 41.0
END DESCRIPTION:
XS GIS Cut Line= 3
      1342886.66      6888366.17      1344155.19      6888597.80
      1345707.86      6888557.15
#Sta/Elev= 30
  3710.5 2245.81  3918.8 2245.32  4093.2 2239.76  4109.1 2239.34  4123.0 2238.65
  4222.2 2233.94  4510.2 2217.58  4552.5 2214.14  4667.9 2213.29  4735.5 2212.57
  4786.3 2214.98  4853.6 2212.13  4949.0 2205.77  4963.6 2196.44  4964.1 2195.94
  4973.9 2196.44  5029.8 2206.15  5162.5 2215.06  5309.9 2219.03  5556.8 2220.32
  5679.3 2220.14  5760.1 2220.10  5840.1 2211.50  5960.1 2212.30  5974.0 2216.02
  6035.2 2220.61  6060.2 2220.28  6090.2 2223.98  6310.3 2232.04  6553.2 2237.30
#Mann=16,-1,0
  3710.5    0.07       0  3918.8   0.035       0  4093.2    0.07       0
  4109.1   0.035       0  4123.0    0.07       0  4222.2   0.035       0
  4510.2    0.07       0  4667.9   0.035       0  4853.6    0.07       0
  4963.6    0.07       0  4973.9    0.07       0  5162.5   0.035       0
  5556.8    0.07       0  5679.3    0.16       0  5974.0    0.07       0
  6035.2   0.035       0
Bank Sta=4963.6,4973.9
Exp/Cntr=0.3,0.1

Type RM Length L Ch R = 1,21048,548,548,548
BEGIN DESCRIPTION:
Live Oak Creek 40.0
END DESCRIPTION:
XS GIS Cut Line= 3
      1342886.68      6888609.23      1344258.23      6888939.09
      1346098.47      6888999.86
#Sta/Elev= 30
  3549.9 2255.85  3560.7 2257.05  3671.6 2259.28  3905.6 2240.66  4268.1 2218.97
  4453.3 2204.54  4473.8 2201.88  4484.1 2196.35  4503.2 2202.26  4555.1 2207.59
  4669.2 2214.21  4756.7 2210.42  4938.1 2197.73  4960.6 2199.28  4987.3 2197.00
  4992.2 2193.84  4992.7 2193.34  5002.5 2193.84  5017.4 2204.30  5027.4 2206.90
  5135.0 2212.20  5337.5 2215.16  5479.2 2213.27  5697.7 2215.74  5778.5 2212.47
  5786.1 2210.43  5947.9 2221.36  6085.9 2224.67  6504.2 2237.08  6801.8 2248.28
#Mann=12,-1,0
  3549.9   0.035       0  3560.7    0.07       0  4555.1   0.035       0
  4756.7    0.07       0  4992.2    0.07       0  5002.5    0.07       0
  5135.0   0.035       0  5479.2    0.07       0  5778.5   0.035       0
  5786.1    0.07       0  6085.9   0.035       0  6504.2    0.07       0
Bank Sta=4992.2,5002.5
Exp/Cntr=0.3,0.1

Type RM Length L Ch R = 1,20500,432,432,432
BEGIN DESCRIPTION:
Live Oak Creek 39.0
END DESCRIPTION:
XS GIS Cut Line= 3
      1342851.94      6889156.10      1343984.53      6889287.63
      1345690.28      6889928.59
#Sta/Elev= 30
  3859.8 2248.16  4132.1 2247.26  4315.9 2247.09  4440.7 2240.87  4515.9 2232.29
  4668.3 2224.86  4752.7 2215.17  4809.2 2210.01  4839.4 2203.40  4859.5 2204.48
  4879.7 2200.65  4899.8 2191.90  4917.4 2199.32  4950.1 2200.88  4984.3 2189.60
  4984.8 2189.10  4996.6 2189.60  5010.6 2196.26  5089.1 2203.32  5620.1 2213.36
  5778.9 2210.15  5846.0 2216.97  5870.6 2218.04  5972.6 2219.87  6197.3 2231.53
  6455.5 2242.78  6498.3 2244.89  6773.2 2259.25  6808.8 2263.75  6822.2 2271.42
#Mann=13,-1,0
  3859.8    0.07       0  4132.1   0.035       0  4515.9    0.07       0
  4752.7    0.16       0  4917.4    0.07       0  4984.3    0.07       0
  4996.6    0.07       0  5089.1   0.035       0  5846.0    0.07       0
  5870.6   0.035       0  6197.3    0.07       0  6455.5   0.035       0
  6498.3    0.07       0
Bank Sta=4984.3,4996.6
Exp/Cntr=0.3,0.1

Type RM Length L Ch R = 1,20068,354,354,354
BEGIN DESCRIPTION:
Live Oak Creek 38.0
END DESCRIPTION:
XS GIS Cut Line= 3
      1342747.83      6889538.05      1343893.64      6889624.86
      1345464.81      6889885.27
#Sta/Elev= 30
  3888.8 2239.71  3906.0 2240.98  4035.3 2237.39  4099.3 2236.89  4266.8 2238.82
  4337.2 2239.39  4548.7 2234.41  4778.5 2227.19  4845.9 2217.20  4908.9 2211.76
  4959.0 2203.96  4989.1 2197.54  5013.0 2187.36  5013.5 2186.86  5025.3 2187.36
  5036.1 2193.42  5069.7 2198.36  5086.3 2199.15  5100.1 2196.36  5118.2 2200.02
  5283.5 2208.21  5407.9 2208.57  5444.8 2208.75  5640.2 2208.11  5706.1 2210.78
  6051.5 2224.57  6204.3 2231.36  6524.0 2245.87  6537.8 2246.10  6630.5 2250.12
#Mann=17,-1,0
  3888.8    0.07       0  4035.3    0.16       0  4099.3    0.07       0
  4266.8   0.035       0  4548.7    0.07       0  4845.9    0.16       0
  5013.0    0.07       0  5025.3    0.16       0  5118.2    0.07       0
  5283.5   0.035       0  5407.9    0.07       0  5444.8   0.035       0
  5706.1    0.07       0  6051.5   0.035       0  6204.3    0.07       0
  6524.0   0.035       0  6537.8    0.07       0
Bank Sta=5013,5025.3
Exp/Cntr=0.3,0.1

Type RM Length L Ch R = 1,19714,363,363,363
BEGIN DESCRIPTION:
Live Oak Creek 37.0
END DESCRIPTION:
XS GIS Cut Line= 3
      1342895.34      6889867.91      1343945.73      6889928.68
      1345550.77      6889954.70
#Sta/Elev= 30
  3938.5 2231.63  4044.8 2230.19  4214.2 2229.80  4404.4 2223.58  4506.7 2220.80
  4681.5 2216.16  4729.5 2211.05  4782.8 2208.71  4879.7 2199.71  4942.7 2196.06
  4959.9 2193.72  4992.8 2193.09  5013.8 2187.16  5014.3 2186.66  5026.1 2187.16
  5029.9 2191.55  5049.9 2199.35  5069.9 2201.47  5340.0 2205.52  5450.1 2204.15
  5514.3 2205.92  5740.9 2215.61  5764.1 2216.43  5868.7 2222.34  5910.1 2224.52
  6310.1 2246.33  6330.1 2249.01  6340.1 2247.89  6430.1 2250.22  6595.9 2257.85
#Mann=16,-1,0
  3938.5    0.16       0  4044.8    0.07       0  4214.2   0.035       0
  4404.4    0.07       0  4506.7   0.035       0  4681.5    0.07       0
  4782.8    0.16       0  4942.7    0.07       0  5013.8    0.07       0
  5026.1    0.07       0  5450.1   0.035       0  5514.3    0.07       0
  5740.9   0.035       0  5764.1    0.07       0  5868.7   0.035       0
  5910.1    0.07       0
Bank Sta=5013.8,5026.1
Exp/Cntr=0.3,0.1

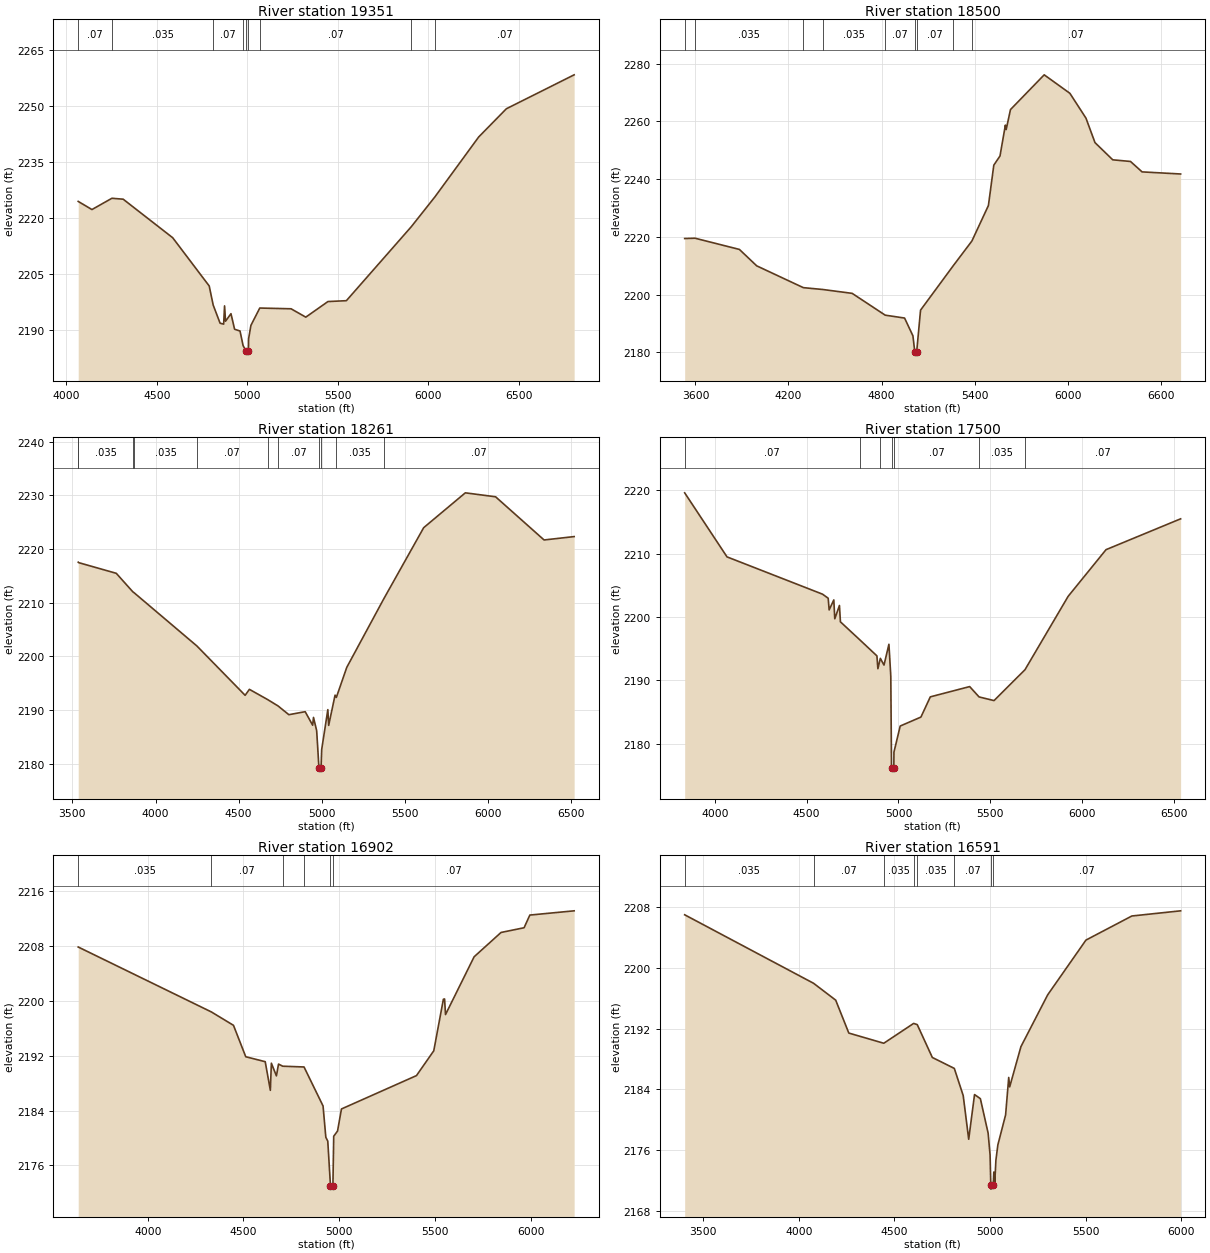
Type RM Length L Ch R = 1,19351,851,851,851
BEGIN DESCRIPTION:
Live Oak Creek 36.0
END DESCRIPTION:
XS GIS Cut Line= 4
      1342930.13      6890168.61      1343555.10      6890275.90
      1344023.85      6890241.18      1345629.80      6889919.99
#Sta/Elev= 30
  4065.7 2224.48  4141.7 2222.30  4251.9 2225.32  4314.2 2225.08  4588.1 2214.75
  4790.0 2201.82  4811.9 2196.72  4850.1 2191.85  4869.8 2191.60  4874.8 2196.49
  4880.2 2192.38  4910.3 2194.40  4930.3 2190.23  4960.4 2189.75  4977.2 2185.86
  4994.4 2184.33  4994.9 2183.83  5006.7 2184.33  5007.7 2187.66  5020.6 2191.27
  5069.5 2195.91  5242.4 2195.71  5324.0 2193.47  5446.4 2197.65  5548.3 2197.88
  5907.0 2217.69  6038.6 2225.75  6279.9 2241.75  6432.9 2249.31  6807.6 2258.40
#Mann=9,-1,0
  4065.7    0.07       0  4251.9   0.035       0  4811.9    0.07       0
  4977.2    0.16       0  4994.4    0.07       0  5006.7    0.16       0
  5069.5    0.07       0  5907.0   0.035       0  6038.6    0.07       0
Bank Sta=4994.4,5006.7
Exp/Cntr=0.3,0.1

Type RM Length L Ch R = 1,18500,239,239,239
BEGIN DESCRIPTION:
Live Oak Creek 35.0
END DESCRIPTION:
XS GIS Cut Line= 3
      1343020.36      6890321.38      1344455.02      6890639.91
      1346124.52      6890189.45
#Sta/Elev= 30
  3530.4 2219.40  3597.6 2219.50  3883.4 2215.62  3995.1 2209.93  4295.8 2202.38
  4421.5 2201.74  4610.7 2200.40  4823.8 2192.85  4948.8 2191.85  5002.6 2185.69
  5014.5 2180.20  5015.0 2179.70  5026.9 2180.20  5051.8 2194.59  5262.9 2209.99
  5382.9 2218.53  5489.6 2230.84  5524.3 2244.81  5564.2 2247.99  5598.9 2258.68
  5604.1 2257.14  5631.8 2264.06  5849.3 2276.10  6015.0 2269.70  6118.6 2261.11
  6176.9 2252.62  6291.4 2246.66  6405.9 2246.09  6480.6 2242.48  6729.2 2241.75
#Mann=9,-1,0
  3530.4    0.07       0  3597.6   0.035       0  4295.8    0.07       0
  4421.5   0.035       0  4823.8    0.07       0  5014.5    0.07       0
  5026.9    0.07       0  5262.9   0.035       0  5382.9    0.07       0
Bank Sta=5014.5,5026.9
Exp/Cntr=0.3,0.1

Type RM Length L Ch R = 1,18261,761,761,761
BEGIN DESCRIPTION:
Live Oak Creek 34.0
END DESCRIPTION:
XS GIS Cut Line= 3
      1343068.95      6890411.65      1344374.55      6890870.00
      1345964.79      6891043.60
#Sta/Elev= 30
  3535.0 2217.56  3536.5 2217.49  3764.0 2215.49  3863.4 2212.05  3872.8 2211.83
  4248.9 2201.96  4539.1 2192.77  4564.8 2193.88  4674.9 2191.97  4737.1 2190.79
  4802.2 2189.16  4900.4 2189.72  4945.4 2187.20  4950.4 2188.65  4969.5 2186.18
  4983.4 2179.15  4983.9 2178.65  4995.8 2179.15  4999.6 2182.66  5036.7 2190.10
  5041.7 2187.17  5080.1 2192.80  5087.9 2192.38  5150.5 2197.97  5373.2 2210.74
  5613.3 2223.99  5863.8 2230.48  6045.8 2229.74  6337.5 2221.70  6518.4 2222.33
#Mann=11,-1,0
  3535.0    0.07       0  3536.5   0.035       0  3863.4    0.07       0
  3872.8   0.035       0  4248.9    0.07       0  4674.9   0.035       0
  4737.1    0.07       0  4983.4    0.07       0  4995.8    0.07       0
  5087.9   0.035       0  5373.2    0.07       0
Bank Sta=4983.4,4995.8
Exp/Cntr=0.3,0.1

Type RM Length L Ch R = 1,17500,598,598,598
BEGIN DESCRIPTION:
Live Oak Creek 33.0
END DESCRIPTION:
XS GIS Cut Line= 4
      1342858.95      6890796.22      1343878.89      6891165.13
      1344152.32      6891104.37      1345461.56      6891360.15
#Sta/Elev= 30
  3836.7 2219.59  4067.1 2209.49  4586.9 2203.61  4617.6 2202.97  4622.9 2201.13
  4648.2 2202.70  4653.5 2199.73  4678.9 2201.83  4684.2 2199.25  4789.4 2196.42
  4882.8 2193.88  4888.1 2191.86  4901.4 2193.49  4921.3 2192.43  4948.1 2195.71
  4958.3 2190.68  4962.3 2176.21  4962.8 2175.71  4974.8 2176.21  4975.5 2178.71
  5009.5 2182.82  5122.2 2184.23  5173.4 2187.42  5387.5 2189.04  5438.6 2187.41
  5520.0 2186.83  5688.5 2191.70  5923.4 2203.27  6129.6 2210.63  6535.4 2215.49
#Mann=7,-1,0
  3836.7    0.07       0  4789.4   0.035       0  4901.4    0.07       0
  4962.3    0.07       0  4974.8    0.07       0  5438.6   0.035       0
  5688.5    0.07       0
Bank Sta=4962.3,4974.8
Exp/Cntr=0.3,0.1

Type RM Length L Ch R = 1,16902,311,311,311
BEGIN DESCRIPTION:
Live Oak Creek 32.0
END DESCRIPTION:
XS GIS Cut Line= 4
      1343019.48      6891004.53      1344100.24      6891351.77
      1344356.32      6891299.68      1345545.54      6891399.51
#Sta/Elev= 30
  3637.1 2207.87  4332.6 2198.39  4447.9 2196.44  4512.1 2191.85  4613.7 2191.13
  4640.5 2186.95  4645.8 2190.91  4672.2 2189.06  4683.1 2190.78  4705.2 2190.47
  4816.4 2190.36  4915.7 2184.67  4930.2 2180.10  4940.4 2179.53  4954.5 2173.03
  4955.0 2172.53  4967.2 2173.03  4971.4 2180.25  4991.4 2181.01  5011.8 2184.23
  5403.6 2189.10  5493.9 2192.72  5544.1 2200.24  5550.3 2200.29  5555.3 2198.01
  5704.6 2206.44  5845.1 2209.99  5965.5 2210.68  5995.6 2212.53  6227.0 2213.15
#Mann=6,-1,0
  3637.1   0.035       0  4332.6    0.07       0  4705.2   0.035       0
  4816.4    0.07       0  4954.5    0.07       0  4967.2    0.07       0
Bank Sta=4954.5,4967.2
Exp/Cntr=0.3,0.1

Type RM Length L Ch R = 1,16591,500,500,500
BEGIN DESCRIPTION:
Live Oak Creek 31.0
END DESCRIPTION:
XS GIS Cut Line= 4
      1343032.53      6891021.90      1344343.30      6891460.27
      1344629.75      6891512.36      1345549.90      6891538.40
#Sta/Elev= 30
  3403.5 2206.96  4077.5 2197.95  4193.4 2195.73  4261.9 2191.40  4444.9 2190.06
  4601.1 2192.67  4619.9 2192.51  4698.7 2188.19  4813.7 2186.75  4860.2 2183.18
  4889.0 2177.43  4919.5 2183.31  4950.0 2182.77  4990.6 2178.23  5000.8 2175.36
  5004.6 2171.37  5005.1 2170.87  5017.4 2171.37  5020.3 2173.12  5025.3 2171.76
  5031.3 2174.69  5041.5 2176.69  5082.0 2180.64  5098.3 2185.56  5103.3 2184.32
  5162.1 2189.61  5302.1 2196.43  5502.2 2203.63  5742.3 2206.80  5997.3 2207.48
#Mann=8,-1,0
  3403.5   0.035       0  4077.5    0.07       0  4444.9   0.035       0
  4601.1    0.07       0  4619.9   0.035       0  4813.7    0.07       0
  5004.6    0.07       0  5017.4    0.07       0
Bank Sta=5004.6,5017.4
Exp/Cntr=0.3,0.1

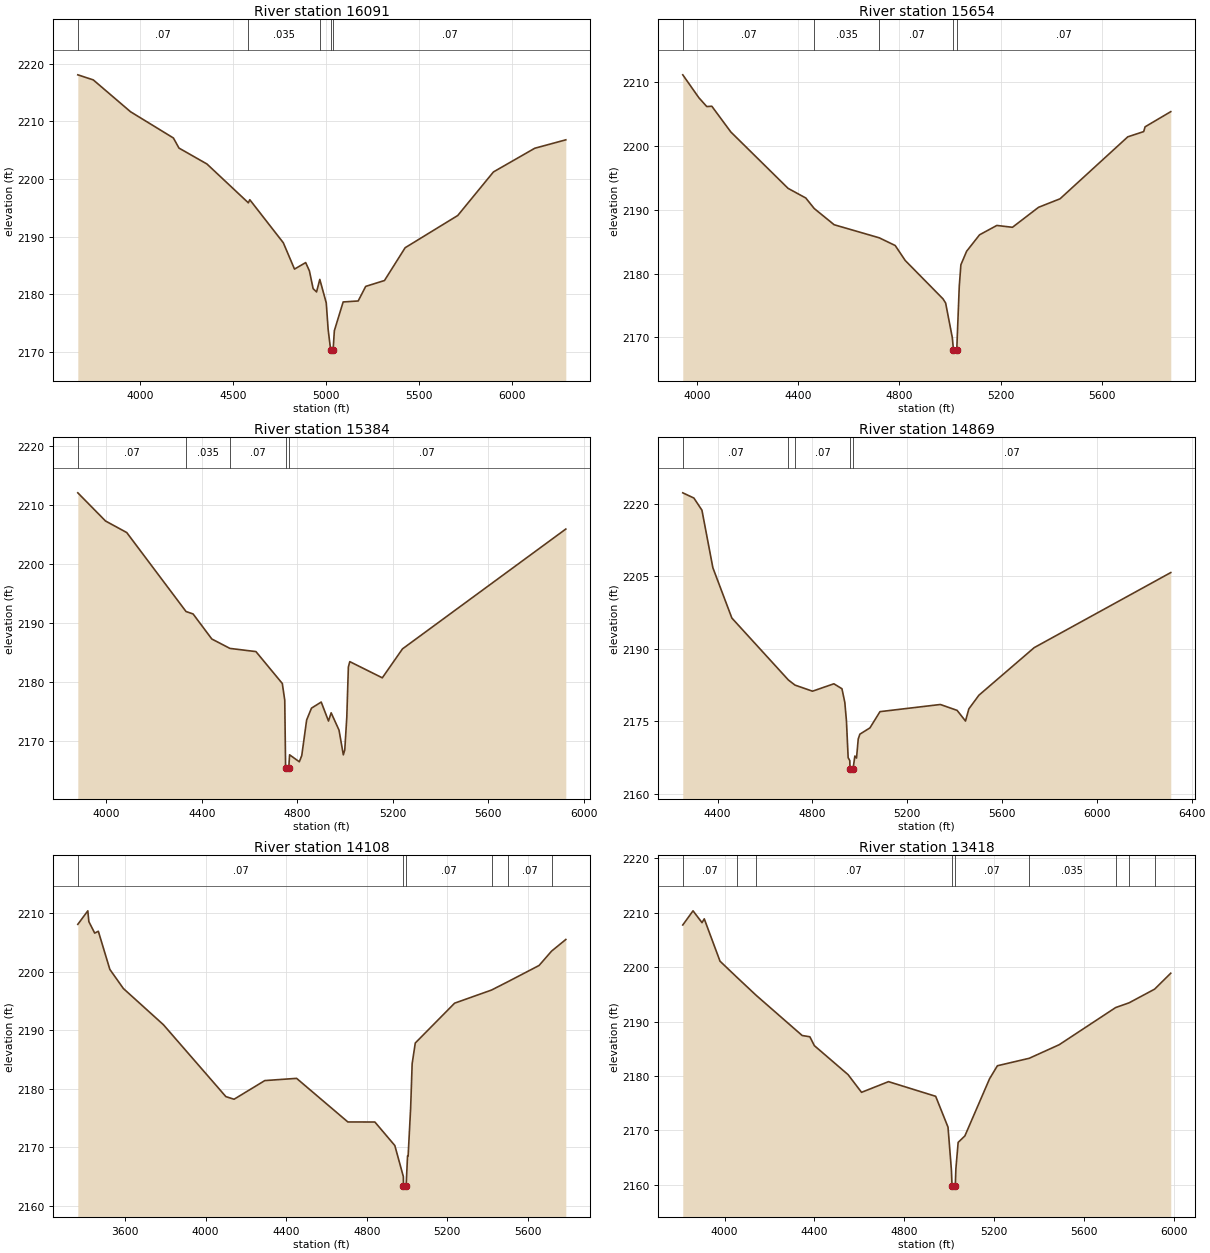
Type RM Length L Ch R = 1,16091,437,437,437
BEGIN DESCRIPTION:
Live Oak Creek 30.0
END DESCRIPTION:
XS GIS Cut Line= 3
      1342871.93      6891772.77      1344156.66      6891725.03
      1345480.24      6891547.11
#Sta/Elev= 30
  3666.0 2218.06  3749.1 2217.18  3949.3 2211.65  4179.4 2207.10  4209.4 2205.35
  4359.5 2202.59  4582.0 2195.85  4589.7 2196.39  4769.8 2188.92  4829.9 2184.35
  4889.9 2185.48  4909.9 2184.05  4929.9 2180.96  4948.3 2180.39  4965.8 2182.56
  5000.4 2178.49  5010.5 2173.90  5024.2 2170.27  5024.7 2169.77  5037.2 2170.27
  5043.9 2173.66  5091.2 2178.65  5171.9 2178.82  5212.3 2181.35  5313.2 2182.37
  5424.2 2188.06  5706.7 2193.65  5898.4 2201.21  6120.4 2205.32  6287.1 2206.78
#Mann=5,-1,0
  3666.0    0.07       0  4582.0   0.035       0  4965.8    0.07       0
  5024.2    0.07       0  5037.2    0.07       0
Bank Sta=5024.2,5037.2
Exp/Cntr=0.3,0.1

Type RM Length L Ch R = 1,15654,270,270,270
BEGIN DESCRIPTION:
Live Oak Creek 29.0
END DESCRIPTION:
XS GIS Cut Line= 3
      1343544.65      6892258.89      1344560.31      6891937.70
      1345340.74      6891569.17
#Sta/Elev= 30
  3943.8 2211.19  4007.1 2207.61  4038.6 2206.21  4058.6 2206.26  4133.7 2202.22
  4359.9 2193.37  4429.8 2191.86  4463.4 2190.20  4542.0 2187.66  4720.1 2185.61
  4783.2 2184.40  4822.8 2182.05  4972.0 2176.03  4982.5 2175.37  5008.9 2169.94
  5013.4 2168.01  5013.9 2167.51  5026.4 2168.01  5036.3 2177.96  5042.7 2181.37
  5065.4 2183.50  5116.5 2186.08  5184.8 2187.55  5246.5 2187.26  5349.7 2190.40
  5434.5 2191.73  5702.3 2201.46  5765.1 2202.28  5770.6 2203.03  5872.1 2205.41
#Mann=5,-1,0
  3943.8    0.07       0  4463.4   0.035       0  4720.1    0.07       0
  5013.4    0.07       0  5026.4    0.07       0
Bank Sta=5013.4,5026.4
Exp/Cntr=0.3,0.1

Type RM Length L Ch R = 1,15384,515,515,515
BEGIN DESCRIPTION:
Live Oak Creek 28.0
END DESCRIPTION:
XS GIS Cut Line= 4
      1343583.76      6892384.75      1344655.80      6892176.42
      1344707.88      6892141.70      1345389.34      6891568.75
#Sta/Elev= 30
  3880.1 2212.00  3996.3 2207.23  4085.1 2205.28  4333.6 2191.91  4363.2 2191.50
  4441.7 2187.26  4517.5 2185.67  4626.6 2185.13  4737.1 2179.73  4747.3 2176.90
  4750.9 2165.40  4751.4 2164.90  4764.0 2165.40  4767.6 2167.66  4808.4 2166.48
  4818.6 2167.54  4839.0 2173.55  4859.3 2175.56  4900.1 2176.59  4930.6 2173.38
  4941.8 2174.77  4974.7 2171.84  4992.8 2167.66  4998.8 2168.47  5007.3 2174.02
  5013.9 2182.53  5019.9 2183.43  5156.1 2180.69  5240.7 2185.59  5925.1 2205.87
#Mann=5,-1,0
  3880.1    0.07       0  4333.6   0.035       0  4517.5    0.07       0
  4750.9    0.07       0  4764.0    0.07       0
Bank Sta=4750.9,4764
Exp/Cntr=0.3,0.1

Type RM Length L Ch R = 1,14869,761,761,761
BEGIN DESCRIPTION:
Live Oak Creek 27.0
END DESCRIPTION:
XS GIS Cut Line= 3
      1343818.15      6892606.11      1344486.52      6892580.07
      1345453.83      6891582.39
#Sta/Elev= 30
  4253.4 2222.25  4300.3 2221.17  4334.2 2218.66  4380.4 2206.75  4460.4 2196.36
  4699.0 2183.54  4726.7 2182.49  4800.7 2181.23  4890.7 2182.76  4924.8 2181.74
  4936.9 2178.93  4943.8 2175.11  4951.0 2167.48  4958.0 2166.88  4958.6 2165.20
  4959.1 2164.70  4971.7 2165.20  4979.3 2167.82  4986.3 2167.40  4993.5 2171.34
  5000.4 2172.34  5042.9 2173.64  5085.3 2177.00  5340.0 2178.48  5410.7 2177.26
  5446.0 2175.06  5460.1 2177.57  5502.6 2180.40  5735.9 2190.24  6311.9 2205.76
#Mann=5,-1,0
  4253.4    0.07       0  4699.0   0.035       0  4726.7    0.07       0
  4958.6    0.07       0  4971.7    0.07       0
Bank Sta=4958.6,4971.7
Exp/Cntr=0.3,0.1

Type RM Length L Ch R = 1,14108,690,690,690
BEGIN DESCRIPTION:
Live Oak Creek 26.0
END DESCRIPTION:
XS GIS Cut Line= 4
      1343722.59      6892892.57      1344725.24      6892701.59
      1345159.27      6892258.88      1345545.53      6891577.50
#Sta/Elev= 30
  3364.9 2208.11  3414.6 2210.42  3419.7 2208.58  3448.8 2206.61  3466.8 2206.93
  3524.0 2200.41  3591.3 2197.14  3790.0 2190.96  4100.3 2178.67  4141.0 2178.22
  4293.7 2181.41  4451.6 2181.79  4706.2 2174.34  4840.5 2174.33  4939.5 2170.31
  4981.9 2165.00  4982.5 2163.36  4983.0 2162.86  4995.6 2163.36  5002.7 2168.53
  5005.6 2168.53  5018.1 2176.72  5025.6 2184.29  5041.1 2187.83  5236.5 2194.64
  5419.7 2196.88  5502.5 2198.33  5656.0 2201.08  5718.0 2203.53  5788.8 2205.52
#Mann=6,-1,0
  3364.9    0.07       0  4982.5    0.07       0  4995.6    0.07       0
  5419.7   0.035       0  5502.5    0.07       0  5718.0   0.035       0
Bank Sta=4982.5,4995.6
Exp/Cntr=0.3,0.1

Type RM Length L Ch R = 1,13418,418,418,418
BEGIN DESCRIPTION:
Live Oak Creek 25.0
END DESCRIPTION:
XS GIS Cut Line= 3
      1343719.34      6892892.57      1344899.94      6892849.16
      1345891.89      6892866.49
#Sta/Elev= 30
  3813.6 2207.72  3859.3 2210.32  3899.3 2208.15  3909.3 2208.85  3979.4 2201.08
  4053.7 2198.16  4139.9 2194.83  4345.4 2187.43  4379.6 2187.20  4399.7 2185.57
  4549.8 2180.25  4609.8 2177.00  4729.9 2178.96  4940.0 2176.27  4995.0 2170.60
  5010.1 2162.73  5012.9 2159.73  5013.4 2159.23  5027.2 2159.73  5030.1 2163.01
  5040.1 2167.81  5070.1 2169.00  5180.1 2179.50  5214.9 2181.88  5356.7 2183.25
  5490.1 2185.74  5741.5 2192.56  5801.4 2193.43  5915.1 2195.94  5987.1 2198.87
#Mann=9,-1,0
  3813.6    0.07       0  4053.7   0.035       0  4139.9    0.07       0
  5012.9    0.07       0  5027.2    0.07       0  5356.7   0.035       0
  5741.5    0.07       0  5801.4   0.035       0  5915.1    0.07       0
Bank Sta=5012.9,5027.2
Exp/Cntr=0.3,0.1

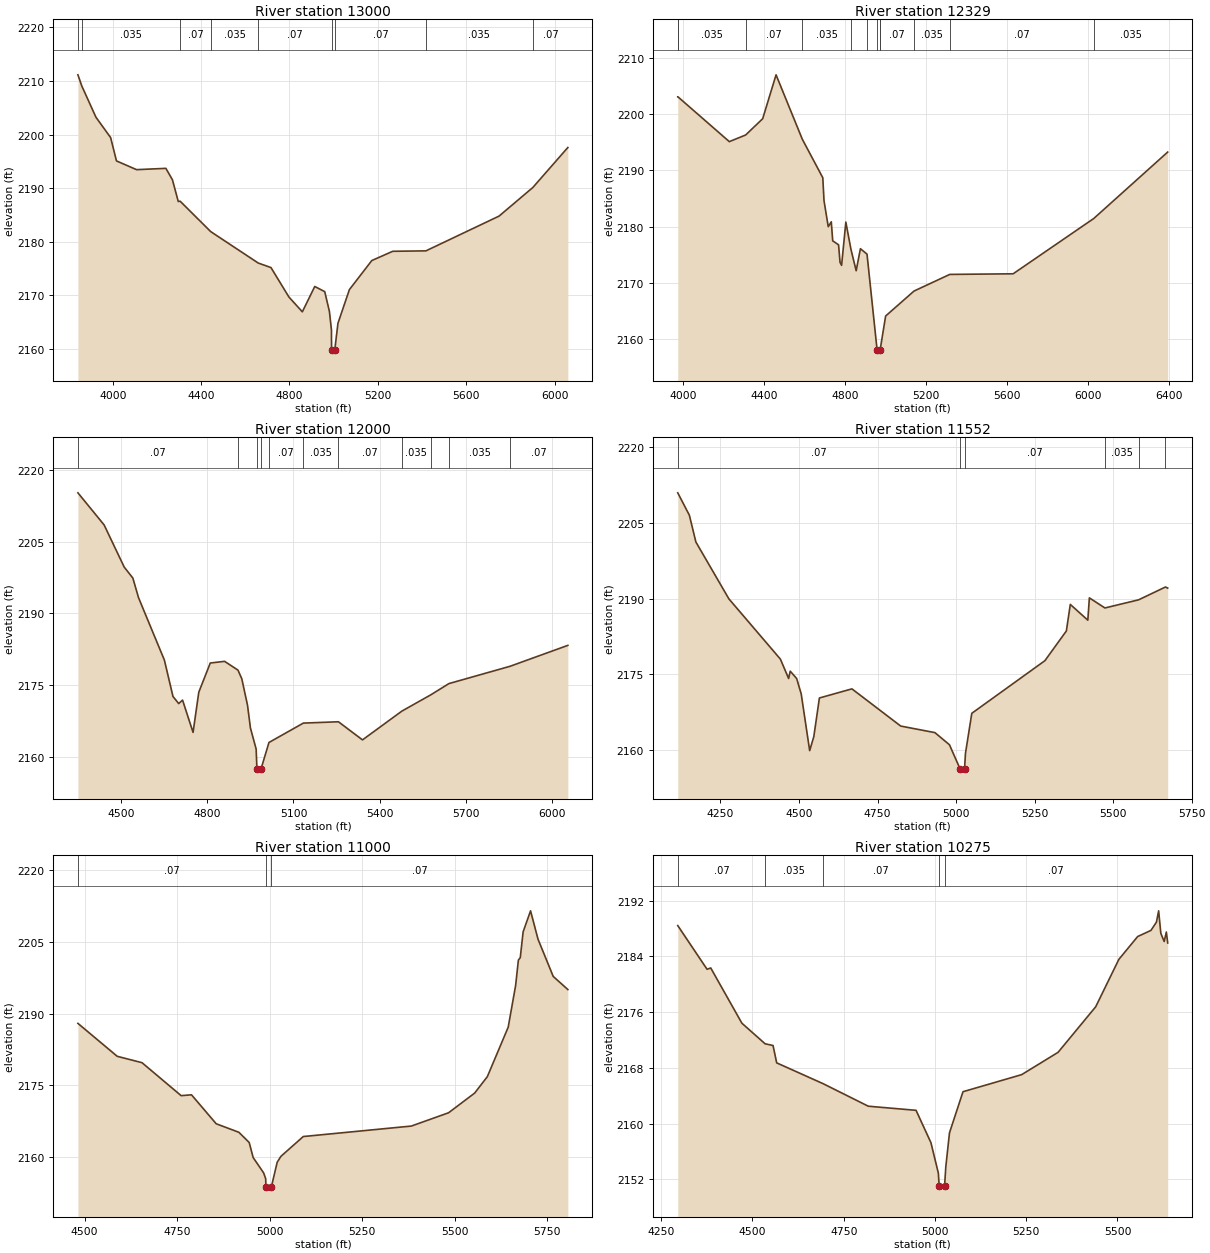
Type RM Length L Ch R = 1,13000,671,671,671
BEGIN DESCRIPTION:
Live Oak Creek 24.0
END DESCRIPTION:
XS GIS Cut Line= 3
      1343762.81      6893079.20      1344905.00      6893266.82
      1345950.12      6893092.24
#Sta/Elev= 30
  3842.5 2211.14  3860.3 2209.04  3924.2 2203.22  3990.5 2199.43  4017.0 2195.07
  4107.9 2193.44  4240.6 2193.68  4270.3 2191.54  4296.7 2187.49  4304.9 2187.56
  4443.3 2181.88  4658.4 2176.01  4716.2 2175.16  4797.3 2169.67  4858.1 2166.90
  4914.3 2171.63  4959.5 2170.67  4980.6 2166.98  4989.9 2163.50  4990.3 2159.69
  4990.8 2159.19  5004.6 2159.69  5019.2 2164.75  5071.0 2171.04  5172.4 2176.47
  5267.3 2178.20  5417.4 2178.28  5748.4 2184.77  5901.0 2190.10  6059.6 2197.57
#Mann=9,-1,0
  3842.5    0.07       0  3860.3   0.035       0  4304.9    0.07       0
  4443.3   0.035       0  4658.4    0.07       0  4990.3    0.07       0
  5004.6    0.07       0  5417.4   0.035       0  5901.0    0.07       0
Bank Sta=4990.3,5004.6
Exp/Cntr=0.3,0.1

Type RM Length L Ch R = 1,12329,329,329,329
BEGIN DESCRIPTION:
Live Oak Creek 23.0
END DESCRIPTION:
XS GIS Cut Line= 4
      1343780.14      6893239.78      1344604.80      6893795.34
      1344678.58      6893825.72      1345970.99      6893448.41
#Sta/Elev= 30
  3973.2 2203.04  3974.0 2203.04  4227.9 2195.09  4308.6 2196.27  4392.8 2199.16
  4458.8 2206.94  4588.4 2195.53  4689.7 2188.69  4695.7 2184.63  4716.7 2180.00
  4731.7 2180.87  4738.7 2177.50  4767.7 2176.79  4774.9 2173.68  4782.6 2173.15
  4803.6 2180.82  4828.7 2176.01  4854.6 2172.19  4875.6 2176.10  4908.2 2175.14
  4958.2 2158.08  4958.7 2157.58  4972.7 2158.08  4972.9 2158.14  5000.2 2164.16
  5140.4 2168.59  5317.0 2171.54  5630.1 2171.65  6028.5 2181.46  6393.7 2193.24
#Mann=12,-1,0
  3973.2    0.07       0  3974.0   0.035       0  4308.6    0.07       0
  4588.4   0.035       0  4828.7    0.07       0  4908.2   0.035       0
  4958.2    0.07       0  4972.7   0.035       0  4972.9    0.07       0
  5140.4   0.035       0  5317.0    0.07       0  6028.5   0.035       0
Bank Sta=4958.2,4972.7
Exp/Cntr=0.3,0.1

Type RM Length L Ch R = 1,12000,448,448,448
BEGIN DESCRIPTION:
Live Oak Creek 22.0
END DESCRIPTION:
XS GIS Cut Line= 3
      1344053.55      6894090.48      1344705.24      6894095.00
      1345759.27      6894168.60
#Sta/Elev= 30
  4348.3 2215.18  4439.7 2208.47  4509.8 2199.65  4539.8 2197.37  4559.8 2193.24
  4649.8 2180.22  4679.8 2172.61  4699.8 2171.12  4713.2 2171.85  4749.8 2165.10
  4769.8 2173.50  4809.8 2179.60  4859.8 2179.95  4906.4 2178.12  4919.8 2176.31
  4939.8 2170.74  4949.8 2166.04  4969.8 2161.60  4972.5 2157.50  4973.0 2157.00
  4987.0 2157.50  5014.5 2162.99  5134.4 2167.04  5256.7 2167.32  5340.6 2163.53
  5478.0 2169.55  5578.2 2172.93  5642.0 2175.30  5855.3 2178.92  6056.6 2183.29
#Mann=11,-1,0
  4348.3    0.07       0  4906.4   0.035       0  4972.5   0.035       0
  4987.0   0.035       0  5014.5    0.07       0  5134.4   0.035       0
  5256.7    0.07       0  5478.0   0.035       0  5578.2    0.07       0
  5642.0   0.035       0  5855.3    0.07       0
Bank Sta=4972.5,4987
Exp/Cntr=0.3,0.1

Type RM Length L Ch R = 1,11552,552,552,552
BEGIN DESCRIPTION:
Live Oak Creek 21.0
END DESCRIPTION:
XS GIS Cut Line= 3
      1344049.29      6894212.02      1344895.60      6894437.70
      1345571.36      6894541.67
#Sta/Elev= 30
  4114.1 2210.99  4151.1 2206.54  4171.8 2201.23  4276.8 2189.96  4440.8 2178.00
  4467.0 2174.16  4472.1 2175.61  4492.6 2174.15  4507.1 2171.09  4534.0 2159.85
  4547.2 2162.63  4565.0 2170.29  4668.5 2172.10  4823.8 2164.72  4932.7 2163.42
  4979.0 2161.01  5012.4 2156.28  5012.9 2155.78  5027.1 2156.28  5029.9 2159.28
  5050.1 2167.25  5282.8 2177.69  5351.1 2183.58  5363.7 2188.85  5419.4 2185.73
  5424.4 2190.15  5473.9 2188.15  5581.0 2189.76  5666.7 2192.31  5673.7 2192.09
#Mann=6,-1,0
  4114.1    0.07       0  5012.4    0.07       0  5027.1    0.07       0
  5473.9   0.035       0  5581.0    0.07       0  5666.7   0.035       0
Bank Sta=5012.4,5027.1
Exp/Cntr=0.3,0.1

Type RM Length L Ch R = 1,11000,725,725,725
BEGIN DESCRIPTION:
Live Oak Creek 20.0
END DESCRIPTION:
XS GIS Cut Line= 3
      1344092.61      6894446.37      1344554.63      6894680.15
      1345355.04      6894588.00
#Sta/Elev= 30
  4482.2 2187.95  4588.4 2181.06  4655.3 2179.73  4761.1 2172.83  4789.0 2173.01
  4855.8 2166.95  4917.0 2165.17  4944.9 2163.04  4955.6 2159.89  4983.9 2156.68
  4989.5 2155.45  4990.0 2153.78  4990.5 2153.28  5004.9 2153.78  5020.5 2158.89
  5030.6 2160.14  5091.0 2164.28  5382.9 2166.47  5483.5 2169.25  5554.0 2173.37
  5588.2 2176.80  5644.6 2187.15  5664.7 2195.90  5672.1 2201.18  5677.2 2201.70
  5684.9 2207.09  5705.0 2211.49  5725.1 2205.57  5766.2 2197.77  5805.7 2195.03
#Mann=3,-1,0
  4482.2    0.07       0  4990.0    0.07       0  5004.9    0.07       0
Bank Sta=4990,5004.9
Exp/Cntr=0.3,0.1

Type RM Length L Ch R = 1,10275,788,788,788
BEGIN DESCRIPTION:
Live Oak Creek 19.0
END DESCRIPTION:
XS GIS Cut Line= 4
      1344154.99      6895038.00      1344779.71      6895091.52
      1344984.57      6895053.33      1345410.82      6894779.56
#Sta/Elev= 30
  4295.5 2188.43  4375.8 2182.16  4385.8 2182.35  4471.2 2174.42  4534.7 2171.47
  4556.5 2171.22  4566.5 2168.73  4694.2 2165.73  4817.4 2162.51  4948.2 2161.92
  4988.9 2157.29  5009.3 2152.91  5011.5 2151.11  5012.0 2150.61  5026.4 2151.11
  5029.6 2153.76  5039.8 2158.69  5076.8 2164.59  5237.5 2167.04  5337.2 2170.24
  5440.3 2176.78  5503.7 2183.58  5555.2 2186.86  5591.6 2187.74  5606.7 2188.93
  5612.7 2190.55  5618.7 2187.32  5627.9 2186.15  5633.8 2187.51  5637.5 2185.94
#Mann=5,-1,0
  4295.5    0.07       0  4534.7   0.035       0  4694.2    0.07       0
  5011.5    0.07       0  5026.4    0.07       0
Bank Sta=5011.5,5026.4
Exp/Cntr=0.3,0.1

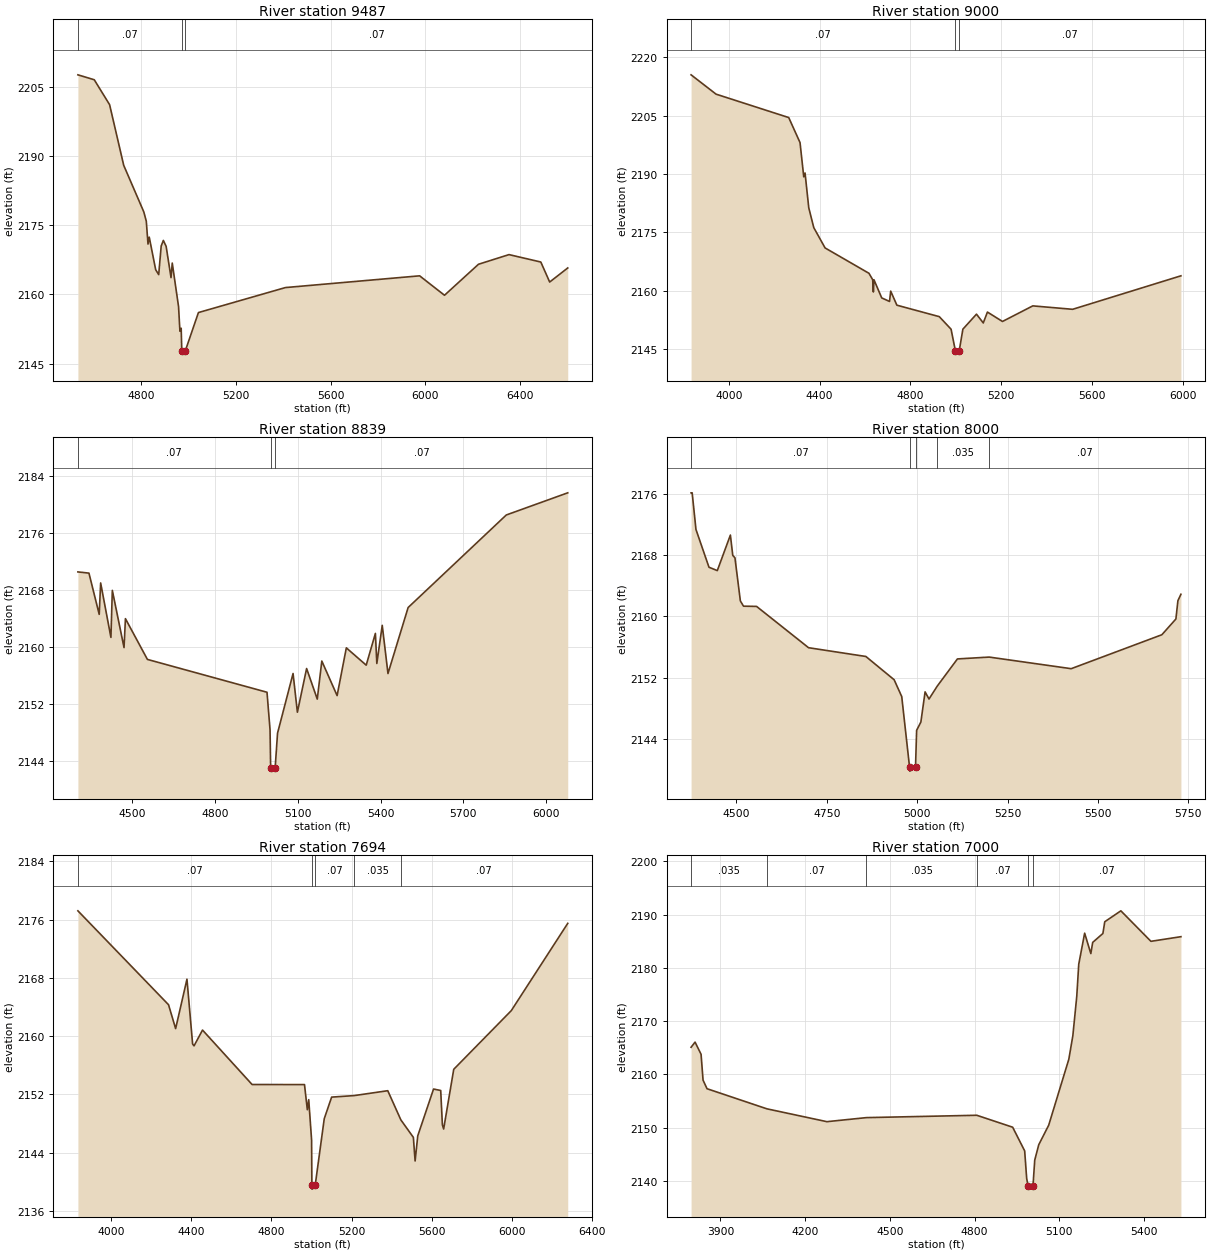
Type RM Length L Ch R = 1,9487,487,487,487
BEGIN DESCRIPTION:
Live Oak Creek 18.0
END DESCRIPTION:
XS GIS Cut Line= 3
      1343859.58      6895313.75      1344401.24      6895483.88
      1345830.86      6895029.32
#Sta/Elev= 30
  4533.0 2207.71  4602.0 2206.64  4666.8 2201.23  4726.4 2188.05  4811.2 2177.94
  4821.7 2175.91  4828.9 2170.95  4834.1 2172.46  4861.3 2165.38  4874.1 2164.31
  4884.6 2170.53  4893.7 2171.74  4905.5 2170.45  4926.1 2163.66  4931.3 2166.82
  4957.9 2157.36  4963.7 2152.01  4969.0 2152.67  4971.5 2147.76  4972.0 2147.26
  4986.4 2147.76  5041.8 2156.07  5409.0 2161.50  5975.6 2164.05  6080.6 2159.83
  6224.0 2166.56  6352.9 2168.66  6487.2 2167.05  6524.6 2162.70  6600.9 2165.76
#Mann=3,-1,0
  4533.0    0.07       0  4971.5    0.07       0  4986.4    0.07       0
Bank Sta=4971.5,4986.4
Exp/Cntr=0.3,0.1

Type RM Length L Ch R = 1,9000,161,161,161
BEGIN DESCRIPTION:
Live Oak Creek 17.0
END DESCRIPTION:
XS GIS Cut Line= 4
      1343293.63      6895591.54      1344005.40      6895963.05
      1344354.96      6895865.90      1345279.68      6895508.20
#Sta/Elev= 30
  3834.3 2215.54  3944.3 2210.57  4264.3 2204.55  4314.1 2198.12  4330.5 2189.31
  4336.2 2190.29  4352.6 2181.34  4374.7 2176.24  4424.5 2171.02  4617.7 2164.50
  4634.1 2162.84  4637.1 2159.70  4639.7 2162.84  4673.9 2158.17  4708.2 2157.26
  4713.4 2159.91  4740.6 2156.30  4927.4 2153.35  4979.3 2150.12  4998.6 2144.47
  4999.1 2143.97  5014.9 2144.47  5031.3 2150.13  5091.2 2153.99  5121.1 2151.73
  5139.4 2154.53  5205.6 2152.11  5339.2 2156.12  5514.7 2155.24  5991.5 2163.85
#Mann=3,-1,0
  3834.3    0.07       0  4998.6    0.07       0  5014.9    0.07       0
Bank Sta=4998.6,5014.9
Exp/Cntr=0.3,0.1

Type RM Length L Ch R = 1,8839,839,839,839
BEGIN DESCRIPTION:
Live Oak Creek 16.0
END DESCRIPTION:
XS GIS Cut Line= 4
      1343727.66      6896171.38      1344390.82      6896015.13
      1345005.40      6895834.58      1345456.31      6895792.96
#Sta/Elev= 30
  4303.4 2170.55  4343.4 2170.38  4380.6 2164.59  4385.8 2169.00  4423.0 2161.36
  4428.1 2167.96  4470.5 2159.93  4475.6 2163.99  4555.2 2158.27  4988.5 2153.66
  4999.5 2148.41  5001.7 2143.09  5002.2 2142.59  5018.1 2143.09  5026.7 2147.92
  5082.9 2156.29  5098.6 2150.86  5132.0 2156.99  5170.6 2152.70  5187.1 2158.04
  5242.5 2153.19  5275.9 2159.89  5347.9 2157.46  5381.2 2161.92  5386.4 2157.70
  5406.0 2163.05  5426.8 2156.29  5499.8 2165.55  5855.4 2178.54  6078.1 2181.65
#Mann=3,-1,0
  4303.4    0.07       0  5001.7    0.07       0  5018.1    0.07       0
Bank Sta=5001.7,5018.1
Exp/Cntr=0.3,0.1

Type RM Length L Ch R = 1,8000,306,306,306
BEGIN DESCRIPTION:
Live Oak Creek 15.0
END DESCRIPTION:
XS GIS Cut Line= 3
      1343655.00      6896088.00      1344005.85      6896605.35
      1344654.98      6896937.99
#Sta/Elev= 30
  4374.9 2176.09  4377.9 2176.09  4388.4 2171.32  4424.4 2166.40  4447.4 2165.96
  4483.6 2170.59  4490.2 2167.94  4496.2 2167.63  4511.2 2162.01  4519.9 2161.33
  4556.0 2161.30  4699.8 2155.92  4858.2 2154.78  4936.4 2151.75  4957.4 2149.56
  4979.1 2140.35  4979.6 2139.85  4995.5 2140.35  4998.6 2145.16  5010.3 2146.24
  5022.0 2150.17  5032.8 2149.24  5055.6 2150.92  5111.4 2154.46  5199.3 2154.70
  5426.0 2153.19  5676.7 2157.61  5715.5 2159.66  5721.1 2162.05  5729.4 2162.88
#Mann=5,-1,0
  4374.9    0.07       0  4979.1    0.07       0  4995.5    0.07       0
  5055.6   0.035       0  5199.3    0.07       0
Bank Sta=4979.1,4995.5
Exp/Cntr=0.3,0.1

Type RM Length L Ch R = 1,7694,694,694,694
BEGIN DESCRIPTION:
Live Oak Creek 14.0
END DESCRIPTION:
XS GIS Cut Line= 3
      1342955.03      6895938.03      1343783.18      6896776.71
      1344814.46      6897512.84
#Sta/Elev= 30
  3833.7 2177.22  4286.2 2164.32  4321.6 2161.04  4378.2 2167.83  4406.4 2158.93
  4413.5 2158.67  4455.9 2160.84  4703.4 2153.36  4965.0 2153.35  4979.2 2149.90
  4986.2 2151.28  5000.4 2145.76  5001.9 2139.49  5002.4 2138.99  5018.3 2139.49
  5063.7 2148.67  5100.6 2151.63  5213.4 2151.84  5380.8 2152.51  5446.2 2148.50
  5508.6 2146.10  5517.3 2142.86  5530.6 2146.32  5609.4 2152.74  5645.1 2152.54
  5653.5 2147.82  5659.8 2147.25  5710.2 2155.45  5997.5 2163.51  6279.4 2175.50
#Mann=5,-1,0
  3833.7    0.07       0  5001.9    0.07       0  5018.3    0.07       0
  5213.4   0.035       0  5446.2    0.07       0
Bank Sta=5001.9,5018.3
Exp/Cntr=0.3,0.1

Type RM Length L Ch R = 1,7000,643,643,643
BEGIN DESCRIPTION:
Live Oak Creek 13.0
END DESCRIPTION:
XS GIS Cut Line= 3
      1343004.99      6896437.99      1343849.49      6897295.87
      1344196.38      6897696.85
#Sta/Elev= 30
  3796.2 2165.10  3810.3 2166.07  3831.6 2163.78  3838.6 2158.93  3852.7 2157.33
  4064.5 2153.56  4277.0 2151.15  4416.8 2151.91  4807.5 2152.35  4934.6 2150.11
  4977.1 2145.67  4984.2 2140.50  4989.5 2139.00  4990.0 2138.50  5006.4 2139.00
  5012.7 2143.94  5027.0 2146.83  5062.1 2150.48  5133.4 2162.86  5147.6 2167.26
  5161.5 2174.65  5168.5 2180.67  5189.4 2186.50  5211.3 2182.67  5217.9 2184.77
  5254.0 2186.44  5260.6 2188.64  5317.6 2190.69  5424.0 2184.97  5530.2 2185.84
#Mann=6,-1,0
  3796.2   0.035       0  4064.5    0.07       0  4416.8   0.035       0
  4807.5    0.07       0  4989.5    0.07       0  5006.4    0.07       0
Bank Sta=4989.5,5006.4
Exp/Cntr=0.3,0.1