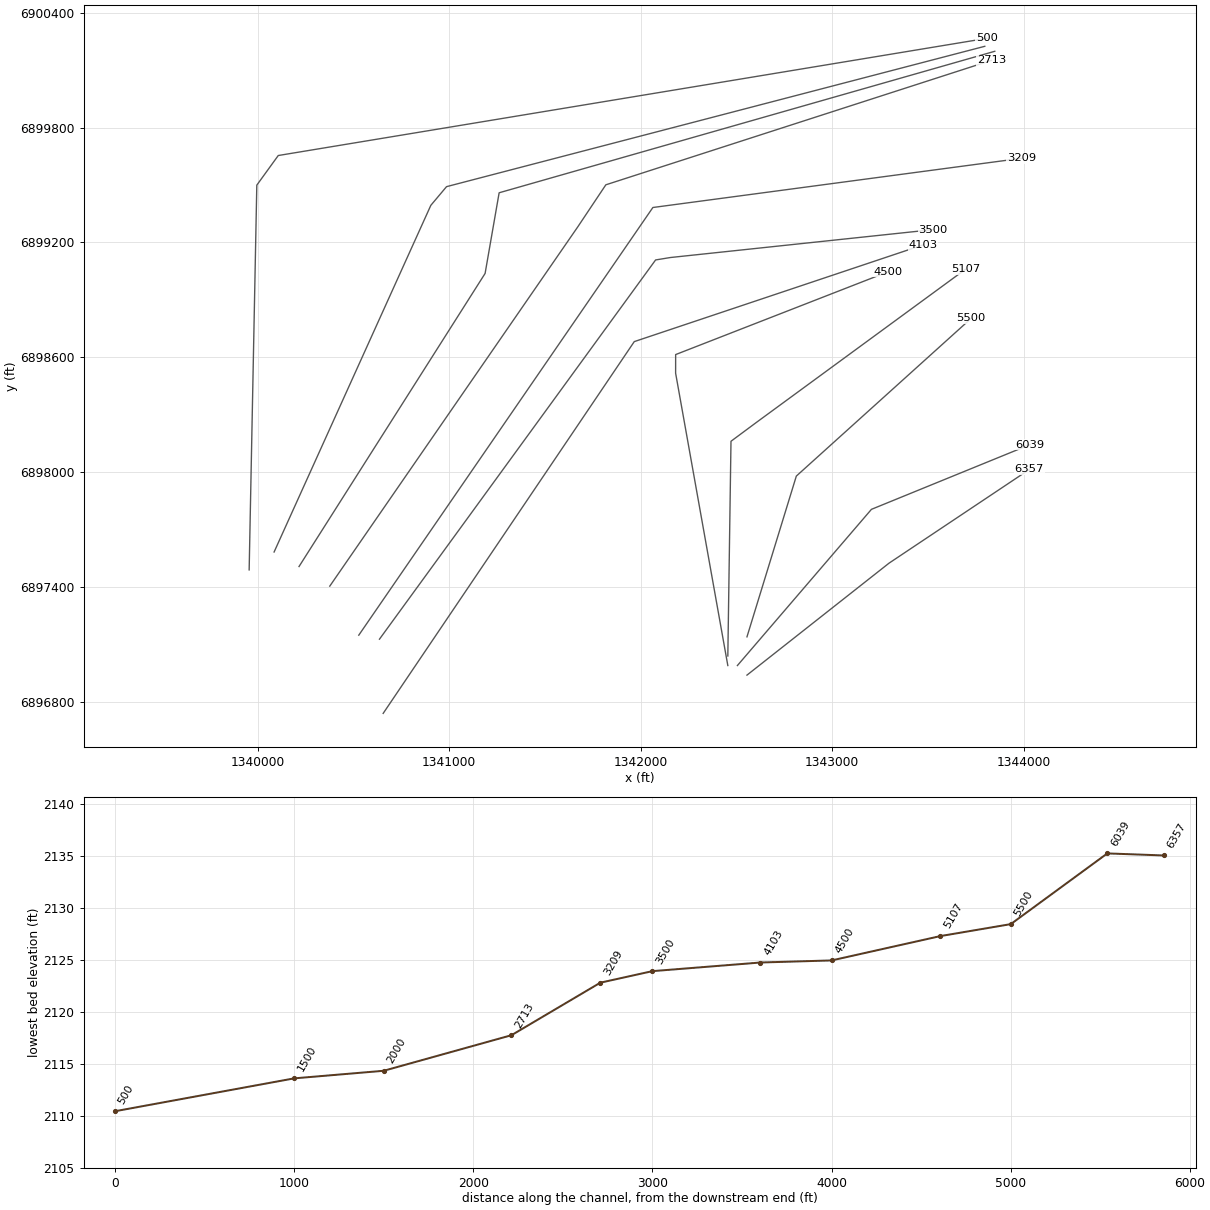
HEC-RAS study Live Oak Creek.prj: Live Oak Creek Base Level Engineering

--- Live Oak Creek.g01 (geometry) --- (continued)

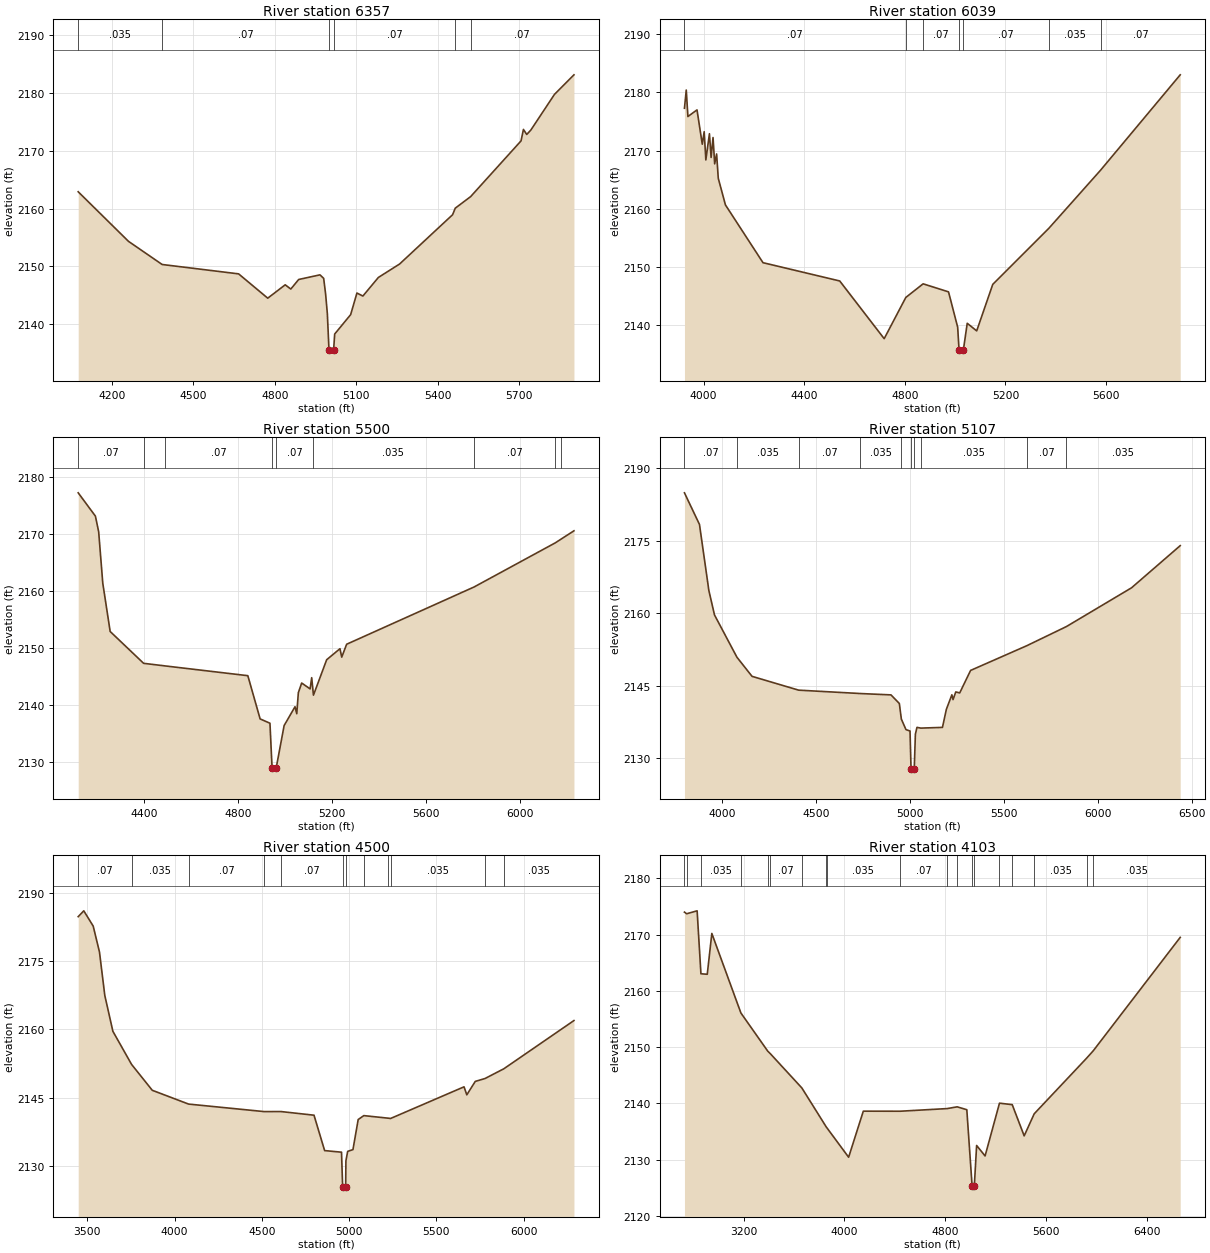
Type RM Length L Ch R = 1,6357,318,318,318
BEGIN DESCRIPTION:
Live Oak Creek 12.0
END DESCRIPTION:
XS GIS Cut Line= 3
      1342554.96      6896937.97      1343297.07      6897523.24
      1344029.72      6898012.83
#Sta/Elev= 30
  4075.3 2162.90  4260.5 2154.34  4384.5 2150.34  4666.2 2148.72  4773.6 2144.52
  4837.8 2146.83  4858.6 2146.10  4887.5 2147.75  4966.0 2148.55  4979.6 2147.94
  4986.8 2145.23  4993.2 2141.80  4999.2 2135.53  4999.7 2135.03  5016.1 2135.53
  5020.2 2138.33  5079.0 2141.68  5102.1 2145.41  5124.1 2144.89  5181.1 2148.10
  5259.2 2150.42  5454.4 2158.93  5464.4 2160.07  5520.9 2162.06  5706.7 2171.69
  5715.5 2173.67  5727.7 2172.80  5742.8 2173.56  5829.8 2179.72  5901.6 2183.10
#Mann=6,-1,0
  4075.3   0.035       0  4384.5    0.07       0  4999.2    0.07       0
  5016.1    0.07       0  5464.4   0.035       0  5520.9    0.07       0
Bank Sta=4999.2,5016.1
Exp/Cntr=0.3,0.1

Type RM Length L Ch R = 1,6039,539,539,539
BEGIN DESCRIPTION:
Live Oak Creek 11.0
END DESCRIPTION:
XS GIS Cut Line= 3
      1342505.03      6896988.03      1343205.06      6897804.49
      1344034.02      6898143.02
#Sta/Elev= 30
  3924.0 2177.28  3931.1 2180.41  3937.7 2175.86  3973.9 2177.00  3994.8 2171.11
  4002.4 2173.25  4009.0 2168.40  4023.3 2172.91  4029.9 2168.84  4037.6 2172.25
  4044.1 2167.73  4051.8 2169.43  4058.4 2165.26  4086.9 2160.68  4236.2 2150.76
  4541.3 2147.62  4718.0 2137.71  4804.0 2144.79  4872.8 2147.13  4973.8 2145.75
  5010.2 2139.68  5015.7 2135.73  5016.2 2135.23  5032.7 2135.73  5048.2 2140.35
  5085.8 2139.05  5149.7 2147.04  5372.8 2156.67  5578.4 2166.65  5894.9 2183.02
#Mann=7,-1,0
  3924.0    0.07       0  4804.0   0.035       0  4872.8    0.07       0
  5015.7    0.07       0  5032.7    0.07       0  5372.8   0.035       0
  5578.4    0.07       0
Bank Sta=5015.7,5032.7
Exp/Cntr=0.3,0.1

Type RM Length L Ch R = 1,5500,393,393,393
BEGIN DESCRIPTION:
Live Oak Creek 10.0
END DESCRIPTION:
XS GIS Cut Line= 3
      1342555.01      6897138.03      1342812.76      6897978.28
      1343725.91      6898802.77
#Sta/Elev= 30
  4121.1 2177.30  4194.3 2173.21  4208.2 2170.46  4225.7 2161.42  4257.1 2152.95
  4399.4 2147.36  4489.8 2146.91  4842.8 2145.19  4895.1 2137.60  4936.9 2136.84
  4946.0 2128.93  4946.5 2128.43  4963.2 2128.93  4997.2 2136.43  5043.5 2139.74
  5051.0 2138.51  5057.7 2142.20  5071.9 2143.90  5107.8 2142.87  5114.5 2144.84
  5118.7 2143.12  5122.0 2141.77  5178.2 2147.99  5234.8 2149.93  5242.3 2148.45
  5263.2 2150.71  5805.6 2160.77  6150.7 2168.51  6177.0 2169.21  6230.3 2170.63
#Mann=9,-1,0
  4121.1    0.07       0  4399.4   0.035       0  4489.8    0.07       0
  4946.0    0.07       0  4963.2    0.07       0  5118.7   0.035       0
  5805.6    0.07       0  6150.7   0.035       0  6177.0    0.07       0
Bank Sta=4946,4963.2
Exp/Cntr=0.3,0.1

Type RM Length L Ch R = 1,5107,607,607,607
BEGIN DESCRIPTION:
Live Oak Creek 9.0
END DESCRIPTION:
XS GIS Cut Line= 4
      1342455.00      6897037.99      1342471.55      6898160.39
      1342606.10      6898260.22      1343695.49      6899058.81
#Sta/Elev= 30
  3798.4 2184.92  3878.4 2178.37  3928.4 2164.68  3958.4 2159.63  4077.9 2150.87
  4158.4 2146.91  4406.8 2144.05  4735.5 2143.35  4898.5 2143.07  4943.0 2141.29
  4953.8 2138.05  4978.4 2135.88  4999.9 2135.59  5005.3 2127.78  5005.8 2127.28
  5022.5 2127.78  5028.5 2134.93  5036.9 2136.34  5057.8 2136.19  5172.7 2136.34
  5193.6 2140.09  5222.9 2143.09  5229.1 2142.09  5243.7 2143.68  5264.6 2143.48
  5322.7 2148.14  5622.2 2153.26  5833.0 2157.22  6180.0 2165.25  6439.2 2173.98
#Mann=10,-1,0
  3798.4    0.07       0  4077.9   0.035       0  4406.8    0.07       0
  4735.5   0.035       0  4953.8    0.07       0  5005.3    0.07       0
  5022.5    0.07       0  5057.8   0.035       0  5622.2    0.07       0
  5833.0   0.035       0
Bank Sta=5005.3,5022.5
Exp/Cntr=0.3,0.1

Type RM Length L Ch R = 1,4500,397,397,397
BEGIN DESCRIPTION:
Live Oak Creek 8.0
END DESCRIPTION:
XS GIS Cut Line= 4
      1342455.00      6896988.00      1342182.33      6898516.27
      1342182.49      6898613.51      1343291.75      6899046.17
#Sta/Elev= 30
  3447.6 2184.76  3479.6 2186.04  3533.5 2182.69  3569.5 2177.00  3600.0 2167.46
  3646.3 2159.59  3753.6 2152.31  3871.9 2146.64  4080.2 2143.61  4513.8 2141.96
  4609.4 2141.97  4798.6 2141.17  4859.5 2133.40  4956.2 2133.05  4962.7 2125.44
  4963.2 2124.94  4979.9 2125.44  4981.4 2131.17  4991.6 2133.23  5021.7 2133.61
  5051.7 2140.22  5084.1 2141.08  5225.0 2140.51  5237.3 2140.45  5658.1 2147.40
  5674.0 2145.64  5722.5 2148.59  5778.2 2149.22  5886.1 2151.36  6287.9 2161.95
#Mann=12,-1,0
  3447.6    0.07       0  3753.6   0.035       0  4080.2    0.07       0
  4513.8   0.035       0  4609.4    0.07       0  4962.7    0.07       0
  4979.9    0.07       0  5084.1   0.035       0  5225.0    0.07       0
  5237.3   0.035       0  5778.2    0.07       0  5886.1   0.035       0
Bank Sta=4962.7,4979.9
Exp/Cntr=0.3,0.1

Type RM Length L Ch R = 1,4103,603,603,603
BEGIN DESCRIPTION:
Live Oak Creek 7.0
END DESCRIPTION:
XS GIS Cut Line= 3
      1340654.98      6896737.97      1341966.34      6898681.22
      1343474.12      6899186.42
#Sta/Elev= 30
  2731.3 2173.99  2748.7 2173.70  2831.8 2174.22  2862.0 2163.03  2912.3 2162.94
  2948.5 2170.20  3179.2 2156.06  3392.8 2149.26  3413.2 2148.81  3663.3 2142.72
  3858.2 2135.74  3860.2 2135.69  4034.2 2130.41  4150.7 2138.60  4443.2 2138.59
  4816.2 2139.06  4895.6 2139.37  4972.1 2138.86  5014.4 2125.24  5014.9 2124.74
  5031.6 2125.24  5050.0 2132.50  5117.2 2130.64  5231.5 2140.02  5332.5 2139.76
  5427.5 2134.21  5506.9 2138.13  5924.6 2148.06  5976.1 2149.35  6665.8 2169.50
#Mann=19,-1,0
  2731.3   0.035       0  2748.7    0.07       0  2862.0   0.035       0
  3179.2    0.07       0  3392.8   0.035       0  3413.2    0.07       0
  3663.3   0.035       0  3858.2    0.07       0  3860.2   0.035       0
  4443.2    0.07       0  4816.2   0.035       0  4895.6    0.07       0
  5014.4    0.07       0  5031.6    0.07       0  5231.5   0.035       0
  5332.5    0.07       0  5506.9   0.035       0  5924.6    0.07       0
  5976.1   0.035       0
Bank Sta=5014.4,5031.6
Exp/Cntr=0.3,0.1

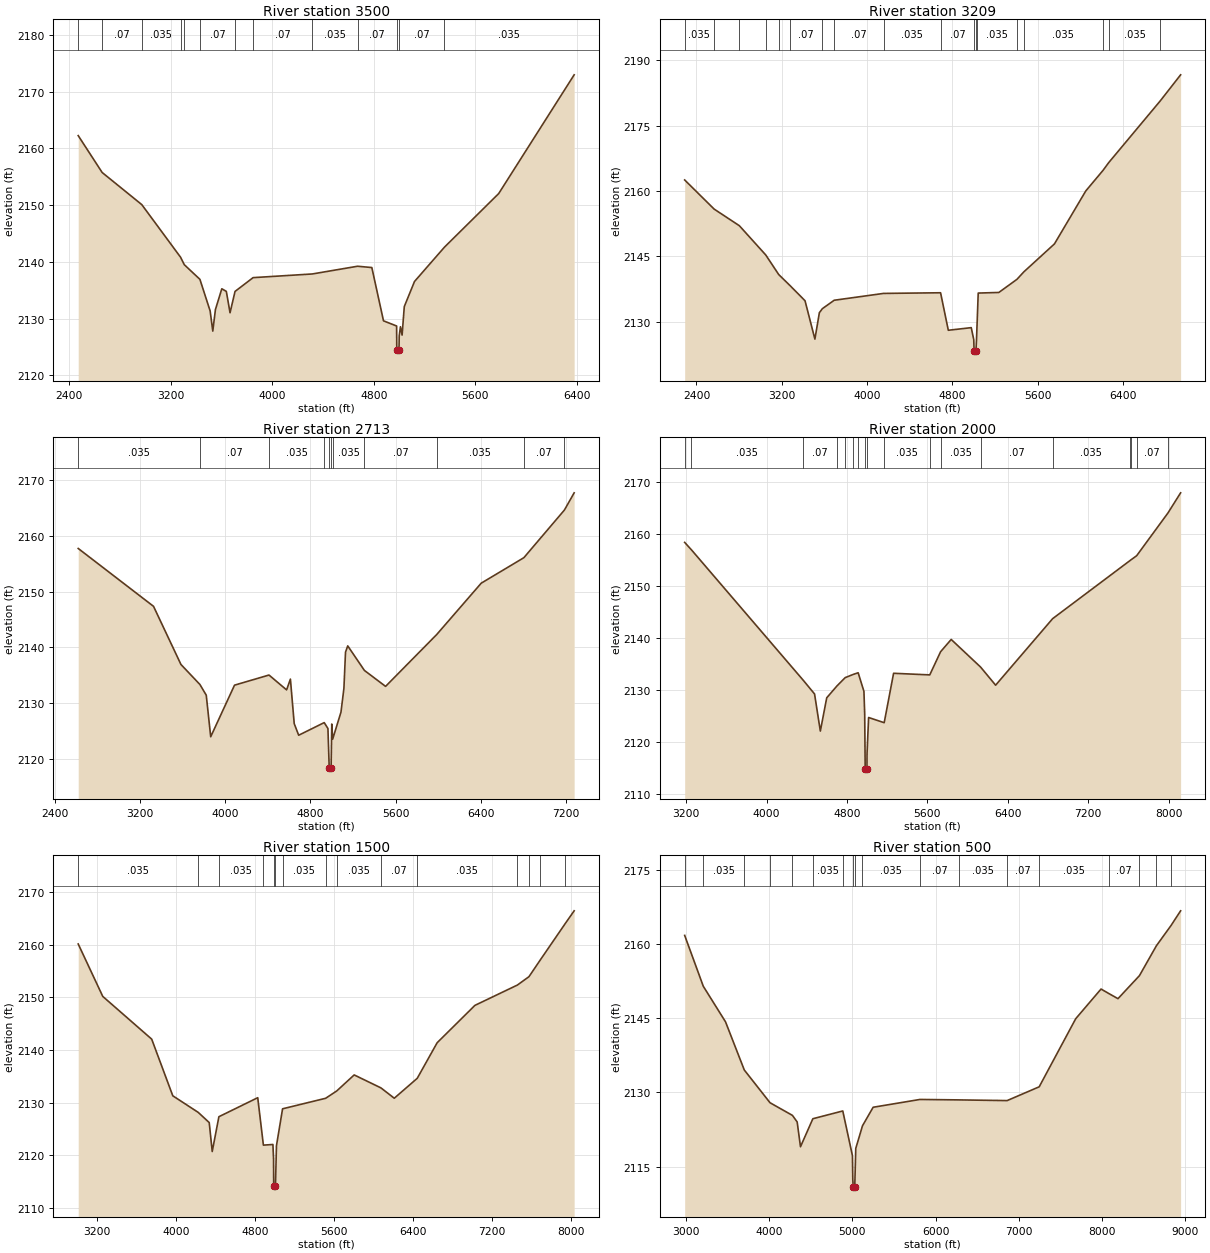
Type RM Length L Ch R = 1,3500,291,291,291
BEGIN DESCRIPTION:
Live Oak Creek 6.0
END DESCRIPTION:
XS GIS Cut Line= 4
      1340635.62      6897125.90      1342077.82      6899108.12
      1342155.23      6899120.81      1343526.21      6899266.51
#Sta/Elev= 30
  2470.2 2162.24  2658.9 2155.74  2971.2 2150.08  3276.8 2140.81  3306.4 2139.49
  3429.4 2136.91  3510.0 2131.34  3530.8 2127.79  3551.7 2131.60  3601.9 2135.25
  3637.5 2134.79  3666.8 2131.02  3706.1 2134.78  3848.4 2137.21  4315.4 2137.86
  4671.8 2139.22  4784.2 2138.99  4876.2 2129.60  4979.5 2128.69  4980.9 2124.41
  4981.4 2123.91  4998.3 2124.41  5000.0 2126.93  5009.8 2128.56  5022.8 2127.09
  5040.0 2132.11  5120.4 2136.53  5356.9 2142.59  5784.2 2152.03  6378.7 2172.95
#Mann=13,-1,0
  2470.2   0.035       0  2658.9    0.07       0  2971.2   0.035       0
  3276.8    0.07       0  3306.4   0.035       0  3429.4    0.07       0
  3706.1   0.035       0  3848.4    0.07       0  4315.4   0.035       0
  4671.8    0.07       0  4980.9    0.07       0  4998.3    0.07       0
  5356.9   0.035       0
Bank Sta=4980.9,4998.3
Exp/Cntr=0.3,0.1

Type RM Length L Ch R = 1,3209,496,496,496
BEGIN DESCRIPTION:
Live Oak Creek 5.0
END DESCRIPTION:
XS GIS Cut Line= 3
      1340527.57      6897146.75      1342063.56      6899382.25
      1343987.15      6899639.19
#Sta/Elev= 30
  2289.2 2162.56  2565.8 2155.87  2802.0 2152.06  3050.2 2145.33  3171.3 2140.85
  3276.7 2138.33  3418.3 2134.83  3511.0 2126.02  3552.9 2132.08  3581.2 2133.01
  3691.9 2134.94  4155.0 2136.51  4690.1 2136.66  4762.7 2128.05  4977.9 2128.65
  5001.5 2125.88  5004.4 2123.30  5004.9 2122.80  5021.8 2123.30  5027.3 2125.93
  5043.3 2136.59  5236.9 2136.73  5406.9 2139.75  5471.3 2141.46  5758.5 2147.88
  6052.2 2160.03  6213.8 2164.75  6267.2 2166.53  6751.2 2180.72  6942.2 2186.70
#Mann=18,-1,0
  2289.2   0.035       0  2565.8    0.07       0  2802.0   0.035       0
  3050.2    0.07       0  3171.3   0.035       0  3276.7    0.07       0
  3581.2   0.035       0  3691.9    0.07       0  4155.0   0.035       0
  4690.1    0.07       0  5004.4    0.07       0  5021.8    0.07       0
  5027.3   0.035       0  5406.9    0.07       0  5471.3   0.035       0
  6213.8    0.07       0  6267.2   0.035       0  6751.2    0.07       0
Bank Sta=5004.4,5021.8
Exp/Cntr=0.3,0.1

Type RM Length L Ch R = 1,2713,713,713,713
BEGIN DESCRIPTION:
Live Oak Creek 4.0
END DESCRIPTION:
XS GIS Cut Line= 4
      1340376.06      6897403.07      1341672.07      6899282.13
      1341817.90      6899500.88      1343831.79      6900151.37
#Sta/Elev= 30
  2617.1 2157.77  3325.1 2147.37  3582.8 2136.92  3761.2 2133.32  3820.7 2131.40
  3862.6 2123.93  4086.4 2133.20  4410.5 2135.02  4576.0 2132.35  4611.8 2134.29
  4647.6 2126.29  4689.5 2124.20  4929.5 2126.47  4964.5 2125.41  4976.8 2118.25
  4977.3 2117.75  4994.2 2118.25  5000.6 2126.22  5009.2 2123.51  5087.1 2128.35
  5114.7 2132.63  5129.8 2139.14  5150.8 2140.26  5307.4 2135.85  5506.4 2132.98
  5987.0 2142.30  6405.4 2151.53  6806.3 2156.11  7187.6 2164.68  7279.0 2167.77
#Mann=11,-1,0
  2617.1   0.035       0  3761.2    0.07       0  4410.5   0.035       0
  4929.5    0.07       0  4976.8    0.07       0  4994.2    0.07       0
  5009.2   0.035       0  5307.4    0.07       0  5987.0   0.035       0
  6806.3    0.07       0  7187.6   0.035       0
Bank Sta=4976.8,4994.2
Exp/Cntr=0.3,0.1

Type RM Length L Ch R = 1,2000,500,500,500
BEGIN DESCRIPTION:
Live Oak Creek 3.0
END DESCRIPTION:
XS GIS Cut Line= 4
      1340215.48      6897505.53      1341187.30      6899037.61
      1341260.61      6899459.22      1343849.19      6900198.81
#Sta/Elev= 30
  3185.7 2158.35  3251.6 2156.95  4367.0 2131.78  4477.9 2129.18  4535.5 2122.04
  4599.0 2128.44  4700.7 2130.72  4782.5 2132.32  4863.8 2132.95  4911.9 2133.26
  4969.3 2129.67  4976.8 2125.32  4981.7 2114.83  4982.2 2114.33  4999.2 2114.83
  5000.0 2117.65  5015.7 2124.65  5170.8 2123.65  5264.3 2133.16  5624.2 2132.85
  5732.0 2137.31  5837.5 2139.67  6129.8 2134.36  6279.5 2130.87  6846.7 2143.67
  7613.6 2154.81  7626.8 2155.00  7682.5 2155.78  7994.0 2164.01  8120.1 2167.89
#Mann=18,-1,0
  3185.7    0.07       0  3251.6   0.035       0  4367.0    0.07       0
  4700.7   0.035       0  4782.5    0.07       0  4863.8   0.035       0
  4911.9    0.07       0  4981.7    0.07       0  4999.2    0.07       0
  5170.8   0.035       0  5624.2    0.07       0  5732.0   0.035       0
  6129.8    0.07       0  6846.7   0.035       0  7613.6    0.07       0
  7626.8   0.035       0  7682.5    0.07       0  7994.0   0.035       0
Bank Sta=4981.7,4999.2
Exp/Cntr=0.3,0.1

Type RM Length L Ch R = 1,1500,1000,1000,1000
BEGIN DESCRIPTION:
Live Oak Creek 2.0
END DESCRIPTION:
XS GIS Cut Line= 4
      1340085.25      6897581.43      1340903.86      6899393.62
      1340985.87      6899491.19      1343797.05      6900224.84
#Sta/Elev= 30
  3011.5 2160.12  3260.1 2150.17  3755.6 2142.06  3969.1 2131.31  4226.7 2128.16
  4337.9 2126.23  4368.4 2120.74  4435.9 2127.34  4829.2 2130.95  4886.4 2121.95
  4982.9 2122.07  4989.5 2119.29  4990.9 2114.10  4991.4 2113.60  5008.4 2114.10
  5018.7 2121.83  5080.6 2128.84  5517.0 2130.84  5629.0 2132.23  5805.7 2135.27
  6076.5 2132.81  6211.7 2130.85  6444.2 2134.63  6645.8 2141.38  7028.2 2148.47
  7458.5 2152.33  7575.1 2153.91  7691.5 2157.13  7945.0 2164.06  8032.8 2166.41
#Mann=15,-1,0
  3011.5   0.035       0  4226.7    0.07       0  4435.9   0.035       0
  4886.4    0.07       0  4990.9    0.07       0  5008.4    0.07       0
  5080.6   0.035       0  5517.0    0.07       0  5629.0   0.035       0
  6076.5    0.07       0  6444.2   0.035       0  7458.5    0.07       0
  7575.1   0.035       0  7691.5    0.07       0  7945.0   0.035       0
Bank Sta=4990.9,5008.4
Exp/Cntr=0.3,0.1

Type RM Length L Ch R = 1,500,0,0,0
BEGIN DESCRIPTION:
Live Oak Creek 1.0
END DESCRIPTION:
XS GIS Cut Line= 4
      1339955.00      6897487.97      1339994.98      6899499.17
      1340106.97      6899653.95      1343807.46      6900266.50
#Sta/Elev= 30
  2988.4 2161.80  3211.9 2151.50  3478.5 2144.31  3704.2 2134.55  4013.4 2127.92
  4281.7 2125.37  4338.7 2124.04  4378.7 2119.02  4527.3 2124.69  4886.4 2126.26
  5002.4 2117.20  5006.6 2112.30  5012.6 2110.94  5013.1 2110.44  5030.1 2110.94
  5042.2 2118.68  5123.0 2123.26  5250.7 2127.01  5812.5 2128.59  6283.8 2128.50
  6859.2 2128.36  7244.2 2131.15  7682.5 2144.93  7986.6 2150.94  8084.3 2149.99
  8190.0 2148.99  8447.6 2153.65  8650.9 2159.69  8826.5 2163.79  8941.9 2166.77
#Mann=18,-1,0
  2988.4    0.07       0  3211.9   0.035       0  3704.2    0.07       0
  4013.4   0.035       0  4281.7    0.07       0  4527.3   0.035       0
  4886.4    0.07       0  5012.6    0.07       0  5030.1    0.07       0
  5123.0   0.035       0  5812.5    0.07       0  6283.8   0.035       0
  6859.2    0.07       0  7244.2   0.035       0  8084.3    0.07       0
  8447.6   0.035       0  8650.9    0.07       0  8826.5   0.035       0
Bank Sta=5012.6,5030.1
Exp/Cntr=0.3,0.1

Chan Stop Cuts=-1