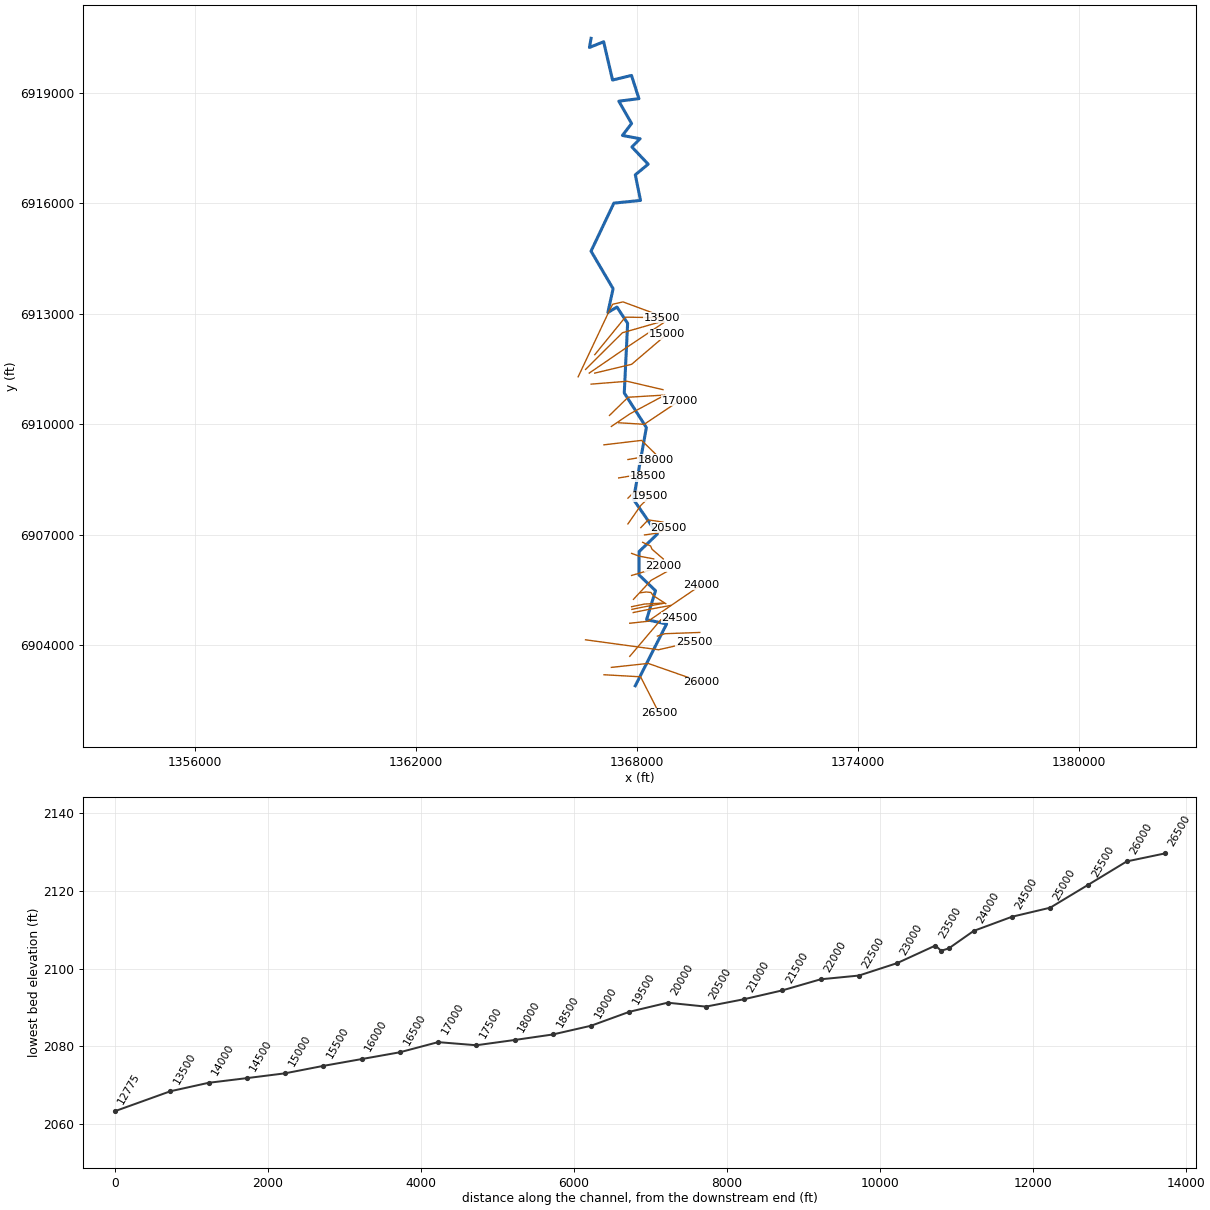
--- Plum Branch.prj (project) ---

Proj Title=Plum Branch Base Level Engineering
Current Plan=p01
Default Exp/Contr=0.3,0.1
English Units
Geom File=g01
Flow File=f01
Plan File=p01
BEGIN DESCRIPTION:
Plum Branch
END DESCRIPTION:

--- Plum Branch.p01 (plan) ---

Plan Title=Multiple Run
Short Identifier=Multiple
Geom File=g01
Flow File=f01
Subcritical Flow
K Sum by GR= 0
Std Step Tol= 0.01
Critical Tol= 0.01
Num of Std Step Trials= 20
Max Error Tol= 0.3
Flow Tol Ratio= 0.001
Split Flow NTrial= 30
Split Flow Tol= 0.02
Split Flow Ratio= 0.02
Log Output Level= 0
Friction Slope Method= 1
Unsteady Friction Slope Method= 2
Unsteady Bridges Friction Slope Method= 1
Parabolic Critical Depth
Global Vel Dist=  1 , 1 , 1
Global Log Level= 0
CheckData=True
Encroach Param= -1, 0, 0, 0
BEGIN DESCRIPTION:
Multiple Run
END DESCRIPTION:

--- Plum Branch.f01 (steady flow) ---

Flow Title=Multiple
Number of Profiles=7
Profile Names=10-year,25-year,50-year,1pct_min,100-year,1pct_plu,500-year
River Rch & RM= Plum Branch,Reach-1,26500
     367     534     679     430     857    1710    1383
River Rch & RM= Plum Branch,Reach-1,25000
     467     684     874     554    1105    2206    1795
River Rch & RM= Plum Branch,Reach-1,18000
     592     876    1124     716    1430    2852    2343
River Rch & RM= Plum Branch,Reach-1,12775
     613     907    1163     740    1477    2948    2416
River Rch & RM= Plum Branch,Reach-1,8500
     807    1203    1552     992    1980    3951    3268
Boundary for River Rch & Prof#=Plum Branch,Reach-1,1
Up Type=0
Dn Type=3
Dn Slope=0.005
Boundary for River Rch & Prof#=Plum Branch,Reach-1,2
Up Type=0
Dn Type=3
Dn Slope=0.005
Boundary for River Rch & Prof#=Plum Branch,Reach-1,3
Up Type=0
Dn Type=3
Dn Slope=0.005
Boundary for River Rch & Prof#=Plum Branch,Reach-1,4
Up Type=0
Dn Type=3
Dn Slope=0.005
Boundary for River Rch & Prof#=Plum Branch,Reach-1,5
Up Type=0
Dn Type=3
Dn Slope=0.005
Boundary for River Rch & Prof#=Plum Branch,Reach-1,6
Up Type=0
Dn Type=3
Dn Slope=0.005
Boundary for River Rch & Prof#=Plum Branch,Reach-1,7
Up Type=0
Dn Type=3
Dn Slope=0.005

--- Plum Branch.g01 (geometry) ---

Geom Title=Existing Conditions

River Reach=Plum Branch,Reach-1
Reach XY= 30
      1367955.00      6902888.00      1368804.98      6904567.78
      1368260.46      6904685.55      1368504.23      6905471.99
      1368055.19      6905903.06      1368058.54      6906536.54
      1368555.20      6907013.08      1367905.38      6907953.16
      1368255.67      6909908.08      1367656.05      6910848.43
      1367747.13      6912741.22      1367456.99      6913183.02
      1367210.47      6913034.97      1367352.95      6913682.14
      1366754.21      6914703.08      1367374.39      6916008.64
      1368097.33      6916081.47      1367955.59      6916777.39
      1368305.04      6917068.02      1367862.83      6917534.78
      1368085.99      6917758.48      1367605.86      6917848.31
      1367854.77      6918172.78      1367508.05      6918779.72
      1368054.14      6918848.31      1367851.94      6919479.73
      1367337.86      6919354.27      1367095.97      6920395.11
      1366710.82      6920239.50      1366755.00      6920488.00

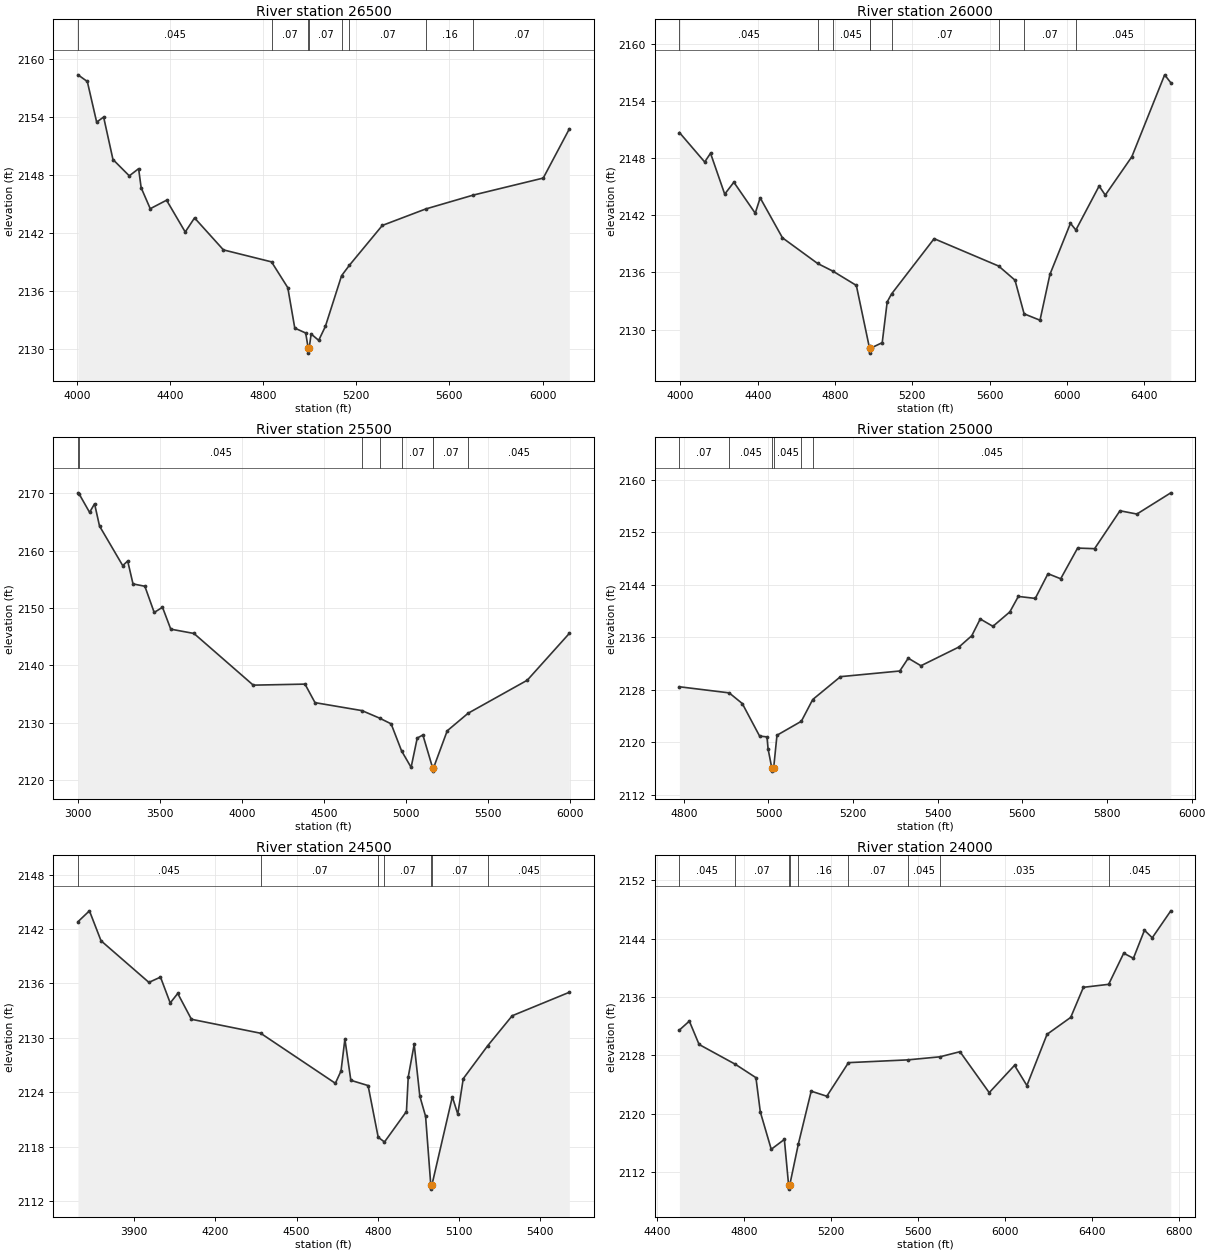
Type RM Length L Ch R = 1,26500,500,500,500
BEGIN DESCRIPTION:
Plum Branch 52.0
END DESCRIPTION:
XS GIS Cut Line= 3
      1367104.95      6903188.00      1368099.38      6903132.12
      1368604.99      6902138.01
#Sta/Elev= 30
  4004.0 2158.39  4044.1 2157.70  4084.2 2153.50  4114.2 2154.02  4154.3 2149.63
  4224.4 2147.94  4264.5 2148.68  4275.4 2146.71  4314.5 2144.54  4384.6 2145.42
  4464.8 2142.13  4504.8 2143.59  4628.9 2140.28  4835.6 2139.04  4905.5 2136.37
  4935.5 2132.19  4982.4 2131.68  4993.3 2130.10  4993.6 2129.60  4997.3 2130.10
  5005.8 2131.58  5038.3 2130.92  5066.9 2132.36  5136.6 2137.61  5170.2 2138.69
  5311.7 2142.81  5497.7 2144.51  5702.6 2145.95  6003.1 2147.71  6115.3 2152.80
#Mann=8,-1,0
  4004.0   0.045       0  4835.6    0.07       0  4993.3    0.07       0
  4997.3    0.07       0  5136.6    0.16       0  5170.2    0.07       0
  5497.7    0.16       0  5702.6    0.07       0
Bank Sta=4993.3,4997.3
Exp/Cntr=0.3,0.1

Type RM Length L Ch R = 1,26000,500,500,500
BEGIN DESCRIPTION:
Plum Branch 51.0
END DESCRIPTION:
XS GIS Cut Line= 3
      1367305.03      6903388.00      1368304.20      6903496.16
      1369754.98      6902988.01
#Sta/Elev= 30
  3995.0 2150.67  4125.7 2147.58  4155.9 2148.50  4229.3 2144.21  4276.6 2145.46
  4387.2 2142.21  4412.8 2143.82  4528.1 2139.63  4710.0 2136.94  4788.6 2136.14
  4910.3 2134.64  4978.7 2128.04  4978.9 2127.54  4982.7 2128.04  5044.2 2128.64
  5069.9 2132.91  5092.3 2133.74  5312.7 2139.54  5646.6 2136.67  5731.1 2135.19
  5778.3 2131.66  5860.5 2130.99  5911.9 2135.80  6018.0 2141.15  6046.1 2140.45
  6166.4 2145.06  6198.2 2144.11  6335.6 2148.13  6505.4 2156.72  6537.2 2155.89
#Mann=9,-1,0
  3995.0   0.045       0  4710.0    0.07       0  4788.6   0.045       0
  4978.7   0.045       0  4982.7   0.045       0  5092.3    0.07       0
  5646.6    0.16       0  5778.3    0.07       0  6046.1   0.045       0
Bank Sta=4978.7,4982.7
Exp/Cntr=0.3,0.1

Type RM Length L Ch R = 1,25500,500,500,500
BEGIN DESCRIPTION:
Plum Branch 50.0
END DESCRIPTION:
XS GIS Cut Line= 3
      1366604.97      6904138.00      1368584.15      6903867.36
      1369554.99      6904088.00
#Sta/Elev= 30
  3002.4 2170.09  3010.5 2169.84  3073.1 2166.68  3103.4 2168.18  3133.6 2164.30
  3274.9 2157.40  3305.2 2158.20  3337.6 2154.21  3409.8 2153.80  3466.7 2149.23
  3517.2 2150.14  3567.6 2146.32  3708.9 2145.57  4070.0 2136.56  4385.2 2136.74
  4446.3 2133.51  4732.4 2132.12  4840.3 2130.80  4910.0 2129.81  4973.5 2125.10
  5031.6 2122.23  5069.0 2127.34  5103.4 2127.87  5163.4 2122.07  5163.7 2121.57
  5167.4 2122.07  5251.6 2128.60  5378.8 2131.66  5739.2 2137.42  5995.6 2145.59
#Mann=8,-1,0
  3002.4   0.035       0  3010.5   0.045       0  4732.4    0.07       0
  4840.3   0.045       0  4973.5    0.07       0  5163.4    0.07       0
  5167.4    0.07       0  5378.8   0.045       0
Bank Sta=5163.4,5167.4
Exp/Cntr=0.3,0.1

Type RM Length L Ch R = 1,25000,500,500,500
BEGIN DESCRIPTION:
Plum Branch 49.0
END DESCRIPTION:
XS GIS Cut Line= 3
      1368555.02      6904238.01      1368754.95      6904303.56
      1369705.02      6904338.00
#Sta/Elev= 30
  4789.6 2128.48  4907.2 2127.55  4938.1 2125.93  4979.0 2120.98  4996.5 2120.85
  4999.1 2119.01  5007.8 2116.14  5008.1 2115.64  5012.3 2116.14  5020.1 2121.10
  5077.7 2123.23  5104.6 2126.54  5170.2 2130.02  5310.3 2130.88  5330.3 2132.83
  5360.3 2131.68  5450.3 2134.54  5480.4 2136.25  5500.4 2138.80  5530.4 2137.68
  5570.4 2139.88  5590.4 2142.23  5630.5 2141.93  5660.5 2145.69  5690.5 2144.92
  5730.5 2149.59  5770.6 2149.50  5830.6 2155.27  5870.6 2154.77  5950.7 2158.00
#Mann=6,-1,0
  4789.6    0.07       0  4907.2   0.045       0  5007.8   0.045       0
  5012.3   0.045       0  5077.7    0.07       0  5104.6   0.045       0
Bank Sta=5007.8,5012.3
Exp/Cntr=0.3,0.1

Type RM Length L Ch R = 1,24500,500,500,500
BEGIN DESCRIPTION:
Plum Branch 48.0
END DESCRIPTION:
XS GIS Cut Line= 3
      1367805.02      6903688.02      1368649.76      6904685.74
      1369154.96      6904738.00
#Sta/Elev= 30
  3692.7 2142.80  3735.0 2144.00  3777.8 2140.70  3954.7 2136.11  3997.5 2136.69
  4033.4 2133.84  4061.2 2134.89  4111.8 2132.04  4367.5 2130.50  4643.5 2124.98
  4664.4 2126.34  4678.7 2129.85  4700.7 2125.31  4764.4 2124.73  4801.7 2119.03
  4825.0 2118.51  4906.1 2121.87  4912.7 2125.68  4934.7 2129.28  4955.5 2123.56
  4976.8 2121.34  4995.9 2113.81  4996.3 2113.31  5000.5 2113.81  5075.6 2123.48
  5095.8 2121.58  5115.9 2125.49  5206.4 2129.13  5296.8 2132.43  5507.9 2135.02
#Mann=7,-1,0
  3692.7   0.045       0  4367.5    0.07       0  4801.7    0.16       0
  4825.0    0.07       0  4995.9    0.07       0  5000.5    0.07       0
  5206.4   0.045       0
Bank Sta=4995.9,5000.5
Exp/Cntr=0.3,0.1

Type RM Length L Ch R = 1,24000,326,326,326
BEGIN DESCRIPTION:
Plum Branch 47.0
END DESCRIPTION:
XS GIS Cut Line= 3
      1367804.99      6904588.00      1368300.33      6904642.21
      1369755.04      6905638.02
#Sta/Elev= 30
  4501.7 2131.47  4547.3 2132.69  4592.2 2129.49  4759.3 2126.77  4853.8 2124.94
  4873.9 2120.25  4924.2 2115.13  4984.6 2116.48  5004.3 2110.17  5004.6 2109.67
  5008.9 2110.17  5049.2 2115.88  5108.1 2123.09  5179.9 2122.40  5279.6 2127.00
  5553.0 2127.38  5700.9 2127.80  5792.7 2128.50  5927.3 2122.89  6043.8 2126.63
  6100.7 2123.86  6193.4 2130.88  6302.3 2133.20  6360.7 2137.32  6476.9 2137.73
  6546.2 2141.99  6590.9 2141.30  6641.7 2145.14  6677.6 2144.11  6762.9 2147.80
#Mann=9,-1,0
  4501.7   0.045       0  4759.3    0.07       0  5004.3    0.07       0
  5008.9    0.07       0  5049.2    0.16       0  5279.6    0.07       0
  5553.0   0.045       0  5700.9   0.035       0  6476.9   0.045       0
Bank Sta=5004.3,5008.9
Exp/Cntr=0.3,0.1

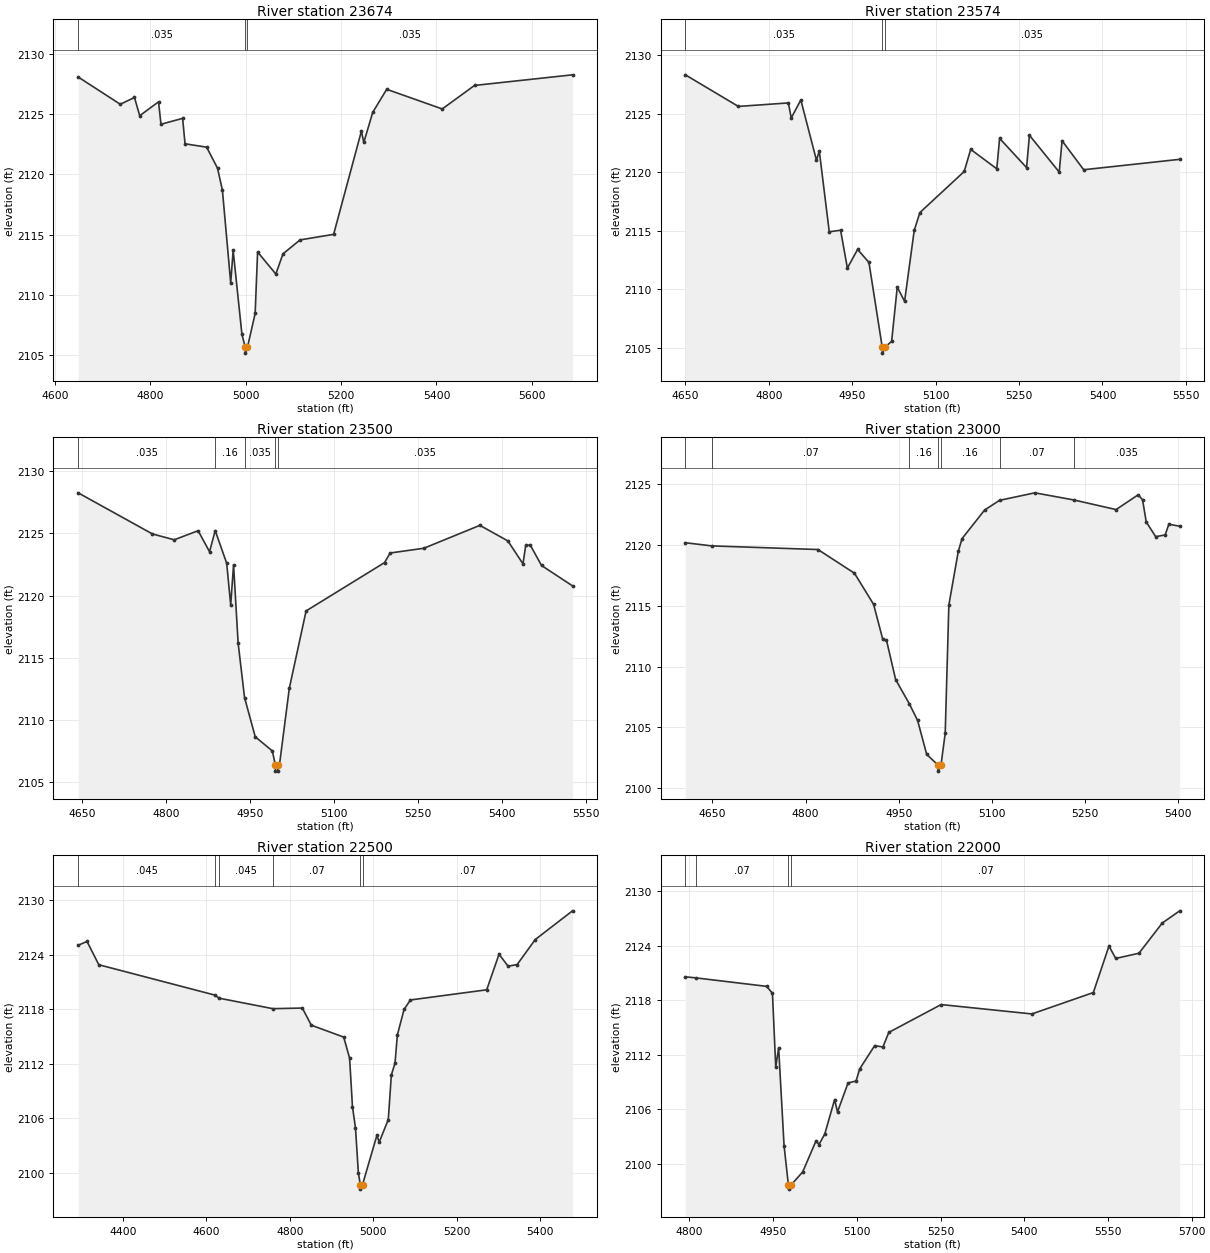
Type RM Length L Ch R = 1,23674,100,100,100
BEGIN DESCRIPTION:
Plum Branch 46.6
END DESCRIPTION:
XS GIS Cut Line= 3
      1367898.40      6904878.49      1368248.35      6904949.99
      1368917.24      6905072.55
#Sta/Elev= 30
  4648.2 2128.07  4736.6 2125.81  4766.4 2126.37  4777.4 2124.86  4816.9 2126.01
  4822.0 2124.15  4867.4 2124.64  4872.5 2122.53  4917.8 2122.25  4940.7 2120.50
  4950.9 2118.67  4968.3 2110.99  4973.4 2113.69  4991.8 2106.74  4998.7 2105.67
  4999.1 2105.17  5003.5 2105.67  5019.6 2108.46  5024.7 2113.56  5063.0 2111.73
  5077.9 2113.40  5113.8 2114.56  5184.2 2115.02  5242.5 2123.58  5247.5 2122.64
  5266.3 2125.14  5295.6 2127.05  5412.1 2125.42  5479.8 2127.37  5685.4 2128.25
#Mann=3,-1,0
  4648.2   0.035       0  4998.7   0.035       0  5003.5   0.035       0
Bank Sta=4998.7,5003.5
Exp/Cntr=0.3,0.1

Type RM Length L Ch R = 1,23574,74,74,74
BEGIN DESCRIPTION:
Plum Branch 46.5
END DESCRIPTION:
XS GIS Cut Line= 3
      1367861.48      6904965.29      1368211.46      6905036.80
      1368734.92      6905131.14
#Sta/Elev= 30
  4649.8 2128.34  4745.2 2125.64  4835.1 2125.94  4840.2 2124.65  4857.5 2126.19
  4885.6 2121.04  4890.7 2121.84  4908.6 2114.93  4929.0 2115.06  4941.2 2111.83
  4959.6 2113.42  4980.0 2112.31  5003.9 2105.06  5004.2 2104.56  5008.7 2105.06
  5020.8 2105.57  5030.9 2110.20  5044.1 2108.99  5061.4 2115.04  5071.6 2116.57
  5151.3 2120.08  5163.0 2121.97  5209.9 2120.31  5215.0 2122.91  5263.5 2120.41
  5268.6 2123.18  5322.2 2120.03  5327.3 2122.71  5366.2 2120.23  5538.9 2121.12
#Mann=3,-1,0
  4649.8   0.035       0  5003.9   0.035       0  5008.7   0.035       0
Bank Sta=5003.9,5008.7
Exp/Cntr=0.3,0.1

Type RM Length L Ch R = 1,23500,500,500,500
BEGIN DESCRIPTION:
Plum Branch 46.0
END DESCRIPTION:
XS GIS Cut Line= 3
      1367854.98      6905038.00      1368204.95      6905109.50
      1368730.30      6905137.63
#Sta/Elev= 30
  4642.8 2128.25  4775.5 2124.95  4814.5 2124.48  4857.2 2125.21  4877.6 2123.52
  4887.7 2125.22  4908.2 2122.60  4915.4 2119.25  4920.5 2122.48  4928.6 2116.22
  4940.1 2111.82  4959.2 2108.67  4989.8 2107.53  4995.1 2106.41  4995.4 2105.91
  4999.5 2105.91  4999.9 2106.41  5002.5 2106.41  5020.1 2112.56  5050.1 2118.77
  5190.3 2122.65  5200.3 2123.42  5260.4 2123.80  5360.6 2125.64  5410.6 2124.39
  5437.6 2122.55  5442.6 2124.05  5450.7 2124.05  5470.7 2122.42  5526.1 2120.78
#Mann=5,-1,0
  4642.8   0.035       0  4887.7    0.16       0  4940.1   0.035       0
  4995.1   0.035       0  4999.9   0.035       0
Bank Sta=4995.1,4999.9
Exp/Cntr=0.3,0.1

Type RM Length L Ch R = 1,23000,500,500,500
BEGIN DESCRIPTION:
Plum Branch 45.0
END DESCRIPTION:
XS GIS Cut Line= 5
      1368094.78      6905417.33      1368253.67      6905438.17
      1368378.67      6905425.15      1368442.90      6905338.61
      1368781.16      6905121.21
#Sta/Elev= 30
  4606.3 2120.20  4648.7 2119.94  4819.8 2119.64  4878.5 2117.69  4909.3 2115.13
  4923.9 2112.28  4930.1 2112.17  4944.8 2108.93  4966.7 2106.95  4980.2 2105.56
  4994.8 2102.77  5013.0 2101.89  5013.3 2101.39  5017.8 2101.89  5024.6 2104.50
  5030.5 2115.08  5045.7 2119.50  5051.7 2120.54  5088.0 2122.89  5112.0 2123.69
  5168.9 2124.31  5231.9 2123.72  5299.7 2122.93  5335.3 2124.15  5342.3 2123.73
  5348.2 2121.91  5363.4 2120.70  5378.6 2120.84  5384.6 2121.72  5402.1 2121.56
#Mann=7,-1,0
  4606.3   0.045       0  4648.7    0.07       0  4966.7    0.16       0
  5013.0    0.07       0  5017.8    0.16       0  5112.0    0.07       0
  5231.9   0.035       0
Bank Sta=5013,5017.8
Exp/Cntr=0.3,0.1

Type RM Length L Ch R = 1,22500,500,500,500
BEGIN DESCRIPTION:
Plum Branch 44.0
END DESCRIPTION:
XS GIS Cut Line= 3
      1367904.99      6905237.99      1368386.81      6905756.06
      1368805.00      6905988.00
#Sta/Elev= 30
  4292.5 2125.05  4313.8 2125.48  4342.1 2122.91  4621.0 2119.56  4630.3 2119.23
  4759.6 2118.07  4830.2 2118.14  4851.7 2116.25  4929.4 2114.94  4943.6 2112.62
  4950.4 2107.28  4957.7 2104.94  4964.6 2099.97  4969.3 2098.69  4969.7 2098.19
  4974.6 2098.69  5009.0 2104.11  5014.7 2103.37  5036.4 2105.86  5043.7 2110.76
  5052.5 2112.08  5058.2 2115.19  5074.2 2117.99  5089.4 2119.03  5272.4 2120.15
  5302.0 2124.07  5323.7 2122.75  5345.4 2122.93  5388.9 2125.69  5478.2 2128.85
#Mann=6,-1,0
  4292.5   0.045       0  4621.0    0.07       0  4630.3   0.045       0
  4759.6    0.07       0  4969.3    0.07       0  4974.6    0.07       0
Bank Sta=4969.3,4974.6
Exp/Cntr=0.3,0.1

Type RM Length L Ch R = 1,22000,500,500,500
BEGIN DESCRIPTION:
Plum Branch 43.0
END DESCRIPTION:
XS GIS Cut Line= 3
      1367854.98      6905887.99      1368054.19      6905945.33
      1368704.97      6906137.99
#Sta/Elev= 30
  4792.7 2120.56  4811.9 2120.44  4938.4 2119.51  4948.8 2118.75  4954.7 2110.63
  4959.9 2112.77  4969.6 2102.02  4977.3 2097.73  4977.7 2097.23  4982.8 2097.73
  5003.0 2099.12  5027.0 2102.55  5032.2 2102.13  5042.6 2103.29  5060.2 2107.07
  5065.4 2105.71  5084.3 2108.90  5098.7 2109.11  5105.1 2110.43  5132.0 2113.00
  5146.8 2112.85  5157.3 2114.45  5251.1 2117.51  5413.7 2116.48  5523.9 2118.83
  5551.9 2123.94  5564.0 2122.58  5605.7 2123.15  5647.4 2126.47  5678.7 2127.81
#Mann=4,-1,0
  4792.7   0.045       0  4811.9    0.07       0  4977.3    0.07       0
  4982.8    0.07       0
Bank Sta=4977.3,4982.8
Exp/Cntr=0.3,0.1

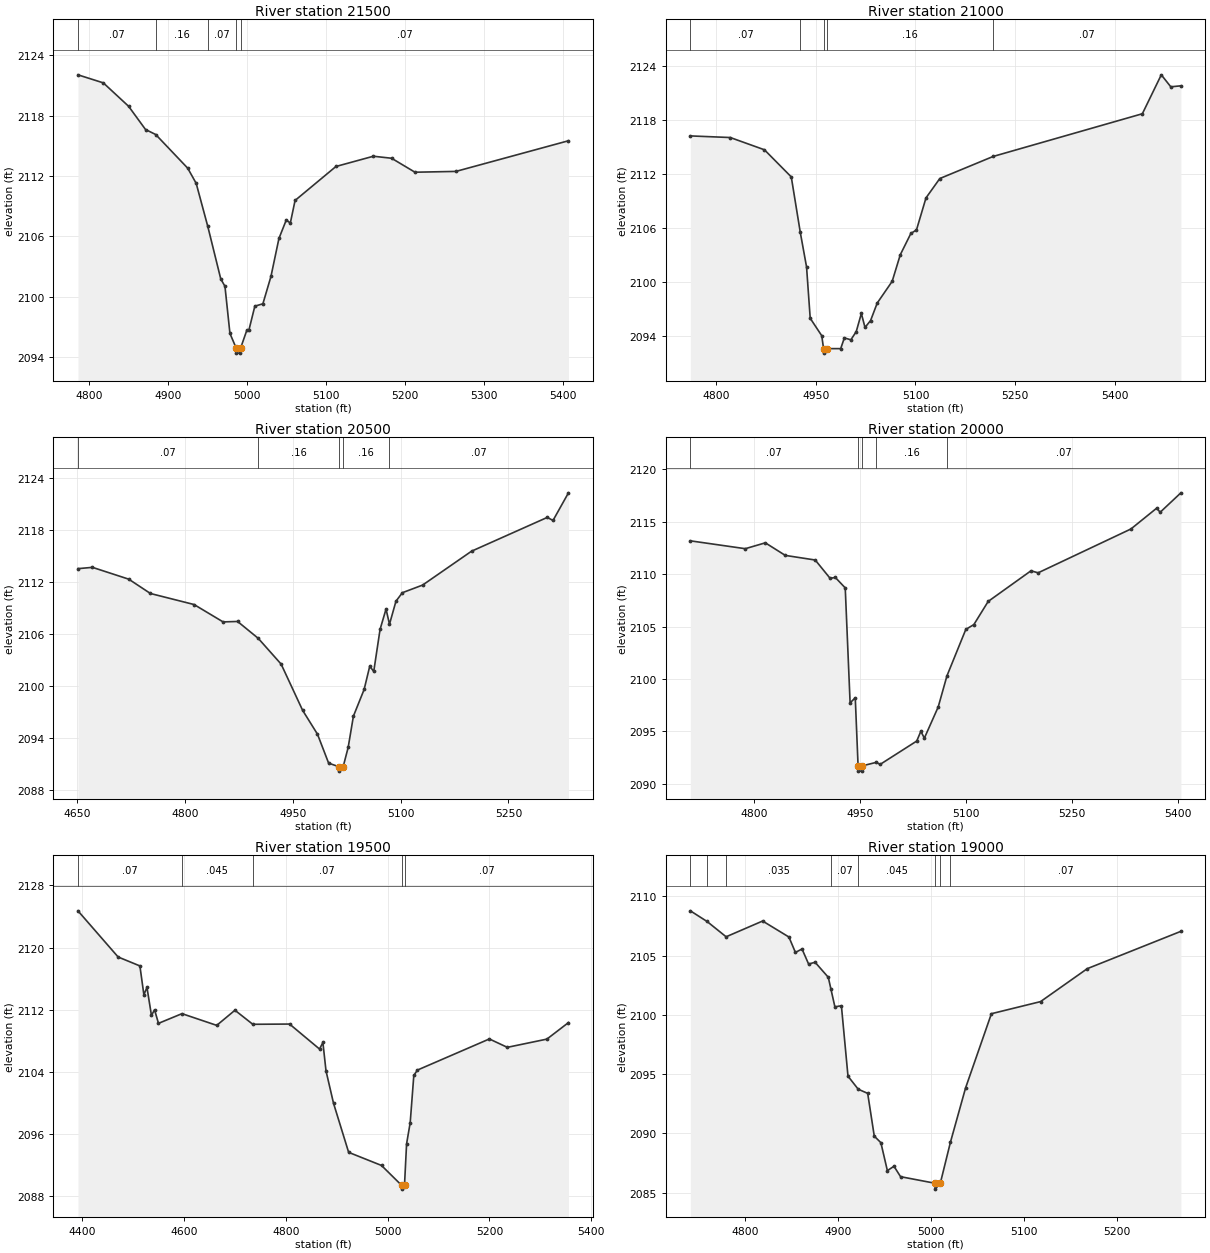
Type RM Length L Ch R = 1,21500,500,500,500
BEGIN DESCRIPTION:
Plum Branch 42.0
END DESCRIPTION:
XS GIS Cut Line= 3
      1367854.96      6906488.01      1368054.95      6906412.98
      1368454.99      6906338.00
#Sta/Elev= 30
  4786.4 2122.07  4818.5 2121.27  4850.5 2118.94  4871.9 2116.63  4884.8 2116.13
  4925.3 2112.78  4936.0 2111.27  4950.7 2106.98  4967.1 2101.76  4972.4 2101.03
  4978.7 2096.34  4986.6 2094.88  4987.0 2094.38  4991.7 2094.38  4992.2 2094.88
  5000.0 2096.64  5002.6 2096.64  5010.2 2099.05  5020.4 2099.29  5030.6 2102.01
  5040.7 2105.79  5050.0 2107.63  5055.1 2107.32  5061.1 2109.57  5112.8 2112.95
  5160.2 2113.97  5183.2 2113.77  5212.8 2112.38  5264.6 2112.46  5407.0 2115.51
#Mann=5,-1,0
  4786.4    0.07       0  4884.8    0.16       0  4950.7    0.07       0
  4986.6    0.07       0  4992.2    0.07       0
Bank Sta=4986.6,4992.2
Exp/Cntr=0.3,0.1

Type RM Length L Ch R = 1,21000,500,500,500
BEGIN DESCRIPTION:
Plum Branch 41.0
END DESCRIPTION:
XS GIS Cut Line= 4
      1368155.04      6906787.98      1368371.99      6906687.96
      1368408.06      6906601.07      1368714.40      6906335.51
#Sta/Elev= 30
  4761.1 2116.22  4821.2 2116.04  4872.6 2114.68  4913.0 2111.67  4926.6 2105.50
  4936.0 2101.68  4941.5 2095.98  4958.9 2094.04  4961.6 2092.61  4962.1 2092.11
  4967.2 2092.61  4987.4 2092.61  4992.9 2093.80  5002.7 2093.59  5010.8 2094.50
  5018.5 2096.51  5024.0 2094.96  5032.4 2095.73  5042.4 2097.67  5064.9 2100.08
  5077.1 2103.03  5093.0 2105.39  5101.5 2105.79  5115.8 2109.34  5136.6 2111.49
  5216.9 2113.94  5441.5 2118.68  5470.0 2123.00  5484.3 2121.67  5499.5 2121.78
#Mann=5,-1,0
  4761.1    0.07       0  4926.6    0.16       0  4961.6    0.07       0
  4967.2    0.16       0  5216.9    0.07       0
Bank Sta=4961.6,4967.2
Exp/Cntr=0.3,0.1

Type RM Length L Ch R = 1,20500,500,500,500
BEGIN DESCRIPTION:
Plum Branch 40.0
END DESCRIPTION:
XS GIS Cut Line= 3
      1368205.01      6906988.00      1368550.68      6907037.51
      1368851.67      6907181.14
#Sta/Elev= 30
  4650.8 2113.51  4671.0 2113.66  4721.5 2112.30  4751.7 2110.65  4812.4 2109.38
  4852.8 2107.38  4873.0 2107.43  4901.7 2105.49  4933.6 2102.52  4963.5 2097.20
  4984.2 2094.45  4999.7 2091.12  5014.2 2090.70  5014.7 2090.20  5019.9 2090.70
  5026.9 2092.93  5034.2 2096.53  5049.1 2099.60  5056.9 2102.27  5062.5 2101.68
  5071.3 2106.52  5079.6 2108.86  5084.4 2107.11  5093.4 2109.76  5102.3 2110.74
  5130.5 2111.62  5198.6 2115.52  5304.0 2119.41  5312.0 2119.06  5333.5 2122.24
#Mann=5,-1,0
  4650.8    0.07       0  4901.7    0.16       0  5014.2    0.07       0
  5019.9    0.16       0  5084.4    0.07       0
Bank Sta=5014.2,5019.9
Exp/Cntr=0.3,0.1

Type RM Length L Ch R = 1,20000,500,500,500
BEGIN DESCRIPTION:
Plum Branch 39.0
END DESCRIPTION:
XS GIS Cut Line= 3
      1368105.01      6907188.01      1368304.92      6907398.51
      1368704.97      6907338.00
#Sta/Elev= 30
  4709.7 2113.18  4787.5 2112.43  4815.9 2112.99  4844.2 2111.79  4886.6 2111.35
  4907.7 2109.60  4915.0 2109.69  4929.1 2108.69  4936.0 2097.72  4943.3 2098.21
  4947.3 2091.71  4947.8 2091.21  4952.6 2091.21  4953.1 2091.71  4973.2 2092.05
  4978.5 2091.85  5030.4 2094.08  5036.2 2095.01  5041.2 2094.36  5060.8 2097.33
  5073.2 2100.30  5099.9 2104.73  5111.3 2105.19  5131.6 2107.40  5192.2 2110.32
  5202.4 2110.13  5333.8 2114.31  5370.2 2116.29  5375.3 2115.91  5404.6 2117.76
#Mann=5,-1,0
  4709.7    0.07       0  4947.3    0.07       0  4953.1    0.07       0
  4973.2    0.16       0  5073.2    0.07       0
Bank Sta=4947.3,4953.1
Exp/Cntr=0.3,0.1

Type RM Length L Ch R = 1,19500,500,500,500
BEGIN DESCRIPTION:
Plum Branch 38.0
END DESCRIPTION:
XS GIS Cut Line= 3
      1367755.00      6907288.00      1368102.40      6907787.95
      1368354.98      6908037.98
#Sta/Elev= 30
  4391.2 2124.73  4470.2 2118.78  4513.0 2117.63  4520.8 2113.92  4526.9 2114.86
  4535.7 2111.25  4541.8 2111.98  4549.5 2110.23  4595.7 2111.48  4664.0 2109.97
  4699.8 2111.92  4734.9 2110.11  4807.2 2110.14  4866.1 2106.92  4872.7 2107.77
  4878.8 2104.11  4893.6 2099.93  4923.3 2093.61  4987.9 2091.92  5027.3 2089.37
  5027.7 2088.87  5033.1 2089.37  5037.2 2094.71  5044.3 2097.43  5051.4 2103.52
  5058.5 2104.21  5199.9 2108.22  5235.2 2107.14  5313.0 2108.20  5355.4 2110.33
#Mann=5,-1,0
  4391.2    0.07       0  4595.7   0.045       0  4734.9    0.07       0
  5027.3    0.07       0  5033.1    0.07       0
Bank Sta=5027.3,5033.1
Exp/Cntr=0.3,0.1

Type RM Length L Ch R = 1,19000,500,500,500
BEGIN DESCRIPTION:
Plum Branch 37.0
END DESCRIPTION:
XS GIS Cut Line= 3
      1367755.00      6907988.00      1367938.05      6908171.37
      1368204.98      6908138.00
#Sta/Elev= 30
  4740.9 2108.77  4758.9 2107.87  4779.4 2106.58  4818.7 2107.91  4847.0 2106.56
  4854.0 2105.26  4861.1 2105.55  4868.2 2104.28  4875.2 2104.43  4889.4 2103.16
  4892.1 2102.21  4896.5 2100.67  4903.5 2100.76  4910.6 2094.82  4921.6 2093.72
  4931.8 2093.37  4938.9 2089.76  4946.0 2089.21  4953.0 2086.85  4960.1 2087.22
  4967.2 2086.34  5004.0 2085.79  5004.5 2085.29  5010.0 2085.79  5020.9 2089.25
  5037.2 2093.83  5065.0 2100.09  5117.9 2101.11  5168.2 2103.89  5269.0 2107.04
#Mann=8,-1,0
  4740.9   0.045       0  4758.9    0.07       0  4779.4   0.035       0
  4892.1    0.07       0  4921.6   0.045       0  5004.0   0.045       0
  5010.0   0.045       0  5020.9    0.07       0
Bank Sta=5004,5010
Exp/Cntr=0.3,0.1

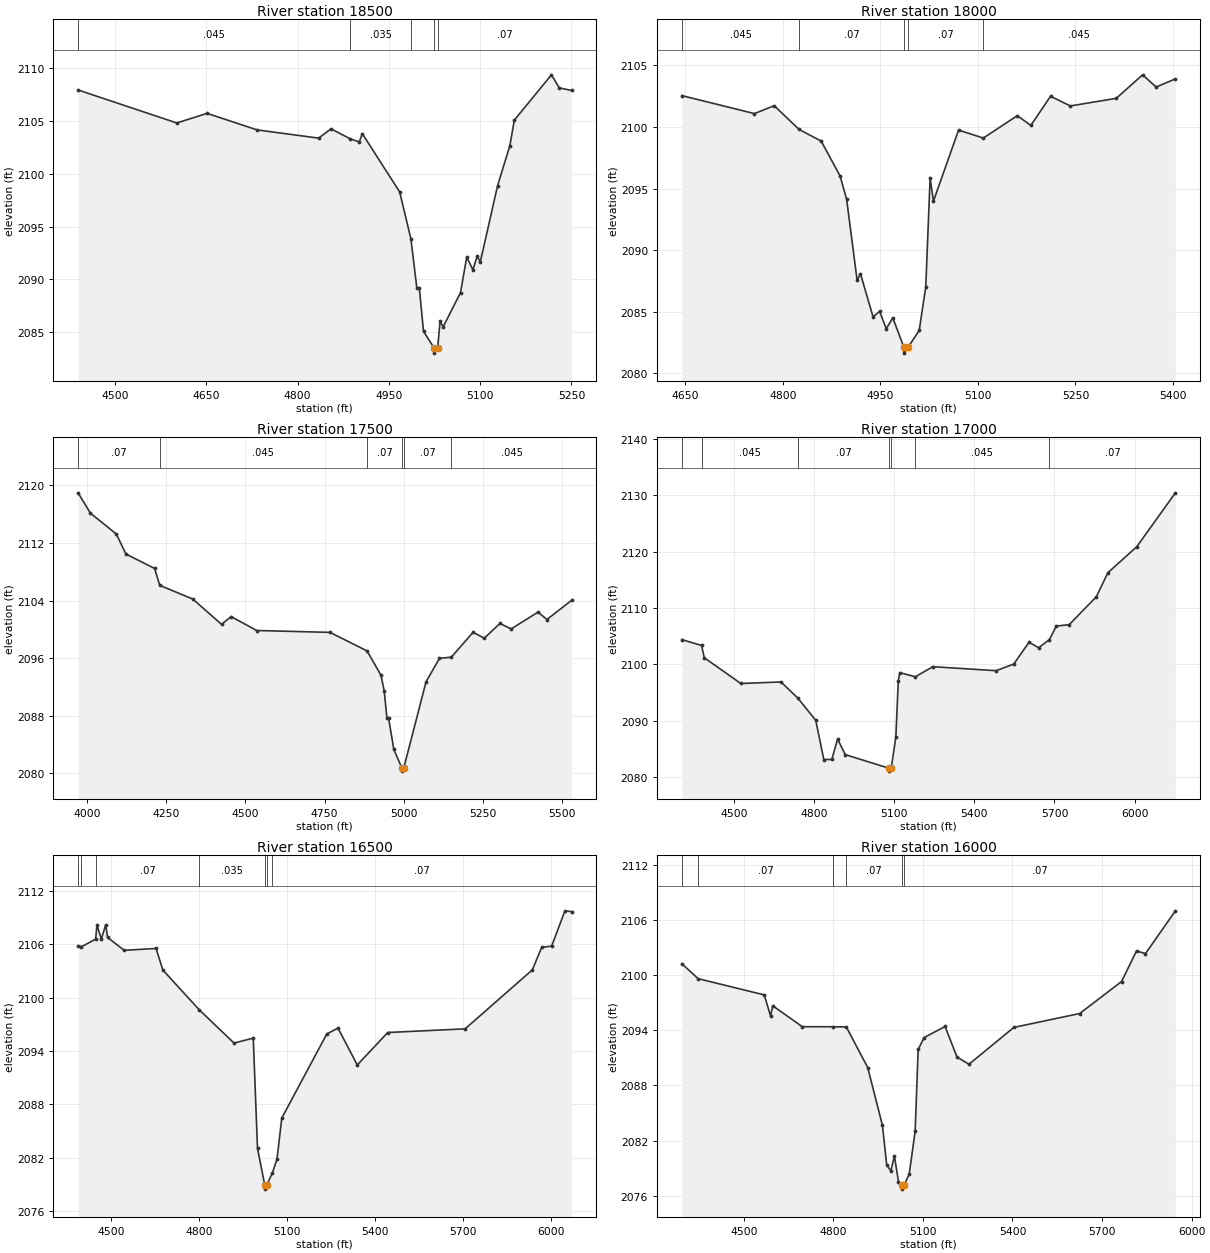
Type RM Length L Ch R = 1,18500,500,500,500
BEGIN DESCRIPTION:
Plum Branch 36.0
END DESCRIPTION:
XS GIS Cut Line= 3
      1367504.99      6908538.00      1368058.18      6908628.86
      1368305.02      6908588.00
#Sta/Elev= 30
  4439.4 2107.90  4601.6 2104.78  4651.3 2105.69  4733.3 2104.13  4834.6 2103.35
  4854.9 2104.23  4886.3 2103.29  4901.3 2102.99  4906.4 2103.77  4967.7 2098.27
  4986.2 2093.83  4995.9 2089.21  5000.0 2089.21  5006.9 2085.10  5024.1 2083.54
  5024.6 2083.04  5030.2 2083.54  5034.1 2086.06  5039.1 2085.51  5067.7 2088.76
  5077.9 2092.12  5088.0 2090.91  5095.1 2092.20  5100.2 2091.65  5128.6 2098.86
  5148.8 2102.65  5156.1 2105.05  5217.1 2109.33  5229.9 2108.10  5250.2 2107.85
#Mann=5,-1,0
  4439.4   0.045       0  4886.3   0.035       0  4986.2    0.07       0
  5024.1    0.07       0  5030.2    0.07       0
Bank Sta=5024.1,5030.2
Exp/Cntr=0.3,0.1

Type RM Length L Ch R = 1,18000,500,500,500
BEGIN DESCRIPTION:
Plum Branch 35.0
END DESCRIPTION:
XS GIS Cut Line= 3
      1367755.00      6909038.00      1368105.44      6909097.14
      1368504.99      6909038.00
#Sta/Elev= 30
  4644.6 2102.55  4756.2 2101.09  4786.6 2101.73  4825.0 2099.80  4858.8 2098.86
  4888.0 2096.02  4898.1 2094.11  4914.2 2087.53  4919.3 2088.08  4938.7 2084.57
  4948.8 2085.01  4959.0 2083.60  4969.1 2084.49  4986.0 2082.12  4986.5 2081.62
  4992.9 2082.12  5009.7 2083.46  5019.8 2086.99  5026.5 2095.85  5031.6 2093.97
  5070.3 2099.75  5108.4 2099.10  5160.6 2100.92  5181.5 2100.13  5211.8 2102.50
  5242.2 2101.71  5312.9 2102.33  5353.4 2104.24  5374.2 2103.25  5403.9 2103.91
#Mann=5,-1,0
  4644.6   0.045       0  4825.0    0.07       0  4986.0    0.07       0
  4992.9    0.07       0  5108.4   0.045       0
Bank Sta=4986,4992.9
Exp/Cntr=0.3,0.1

Type RM Length L Ch R = 1,17500,500,500,500
BEGIN DESCRIPTION:
Plum Branch 34.0
END DESCRIPTION:
XS GIS Cut Line= 3
      1367105.00      6909438.00      1368126.17      6909558.84
      1368504.98      6909188.02
#Sta/Elev= 30
  3971.7 2118.98  4010.6 2116.15  4092.5 2113.25  4122.7 2110.47  4213.4 2108.46
  4229.5 2106.11  4334.2 2104.20  4424.8 2100.68  4455.0 2101.77  4535.6 2099.83
  4767.2 2099.57  4884.1 2096.99  4928.3 2093.60  4938.4 2091.41  4946.9 2087.63
  4951.9 2087.72  4968.6 2083.30  4993.3 2080.77  4993.8 2080.27  5000.5 2080.77
  5070.4 2092.69  5112.9 2095.96  5150.3 2096.12  5219.0 2099.58  5254.3 2098.76
  5303.9 2100.81  5339.2 2100.05  5424.0 2102.39  5452.3 2101.36  5530.1 2104.03
#Mann=6,-1,0
  3971.7    0.07       0  4229.5   0.045       0  4884.1    0.07       0
  4993.3    0.07       0  5000.5    0.07       0  5150.3   0.045       0
Bank Sta=4993.3,5000.5
Exp/Cntr=0.3,0.1

Type RM Length L Ch R = 1,17000,500,500,500
BEGIN DESCRIPTION:
Plum Branch 33.0
END DESCRIPTION:
XS GIS Cut Line= 3
      1367505.03      6910038.00      1368197.66      6909996.06
      1369154.96      6910637.98
#Sta/Elev= 30
  4306.1 2104.39  4379.6 2103.35  4390.0 2101.17  4526.5 2096.61  4676.8 2096.88
  4740.3 2094.00  4807.0 2090.07  4837.0 2083.13  4867.1 2083.14  4888.7 2086.76
  4917.2 2084.00  5082.0 2081.57  5082.5 2081.07  5089.3 2081.57  5106.7 2087.15
  5115.7 2097.04  5121.7 2098.53  5179.7 2097.80  5244.7 2099.59  5481.9 2098.88
  5547.9 2100.06  5604.9 2103.93  5640.9 2102.95  5681.0 2104.38  5706.9 2106.78
  5755.3 2107.05  5857.0 2112.00  5899.8 2116.25  6008.2 2120.87  6152.6 2130.42
#Mann=7,-1,0
  4306.1    0.07       0  4379.6   0.045       0  4740.3    0.07       0
  5082.0    0.07       0  5089.3    0.07       0  5179.7   0.045       0
  5681.0    0.07       0
Bank Sta=5082,5089.3
Exp/Cntr=0.3,0.1

Type RM Length L Ch R = 1,16500,500,500,500
BEGIN DESCRIPTION:
Plum Branch 32.0
END DESCRIPTION:
XS GIS Cut Line= 3
      1367304.98      6909937.99      1367812.42      6910282.43
      1368754.99      6910788.00
#Sta/Elev= 30
  4386.7 2105.82  4398.3 2105.71  4446.5 2106.57  4451.1 2108.13  4466.1 2106.59
  4481.0 2108.19  4487.1 2106.76  4544.0 2105.31  4652.6 2105.52  4675.6 2103.10
  4799.6 2098.63  4918.5 2094.88  4984.1 2095.44  4998.5 2083.03  5023.0 2078.96
  5023.5 2078.46  5030.6 2078.96  5048.7 2080.23  5065.0 2081.84  5081.3 2086.45
  5234.7 2095.90  5272.9 2096.57  5338.7 2092.42  5442.7 2096.07  5706.5 2096.48
  5935.6 2103.11  5967.5 2105.63  6001.5 2105.79  6046.9 2109.75  6069.6 2109.66
#Mann=7,-1,0
  4386.7    0.07       0  4398.3   0.045       0  4446.5    0.07       0
  4799.6   0.035       0  5023.0   0.035       0  5030.6   0.035       0
  5048.7    0.07       0
Bank Sta=5023,5030.6
Exp/Cntr=0.3,0.1

Type RM Length L Ch R = 1,16000,500,500,500
BEGIN DESCRIPTION:
Plum Branch 31.0
END DESCRIPTION:
XS GIS Cut Line= 3
      1367255.00      6910238.00      1367761.09      6910731.96
      1368705.03      6910788.00
#Sta/Elev= 30
  4292.8 2101.27  4347.1 2099.64  4568.6 2097.87  4589.8 2095.57  4596.9 2096.69
  4695.9 2094.41  4797.3 2094.40  4843.4 2094.38  4915.1 2089.96  4964.5 2083.65
  4978.7 2079.36  4992.8 2078.69  5004.5 2080.33  5018.2 2077.50  5030.2 2077.21
  5030.7 2076.71  5037.8 2077.21  5054.0 2078.33  5074.0 2083.02  5084.1 2091.93
  5104.1 2093.22  5174.2 2094.43  5214.3 2091.09  5254.4 2090.32  5404.6 2094.33
  5625.0 2095.84  5765.3 2099.33  5815.3 2102.66  5845.4 2102.37  5945.6 2107.03
#Mann=6,-1,0
  4292.8   0.035       0  4347.1    0.07       0  4797.3   0.035       0
  4843.4    0.07       0  5030.2    0.07       0  5037.8    0.07       0
Bank Sta=5030.2,5037.8
Exp/Cntr=0.3,0.1

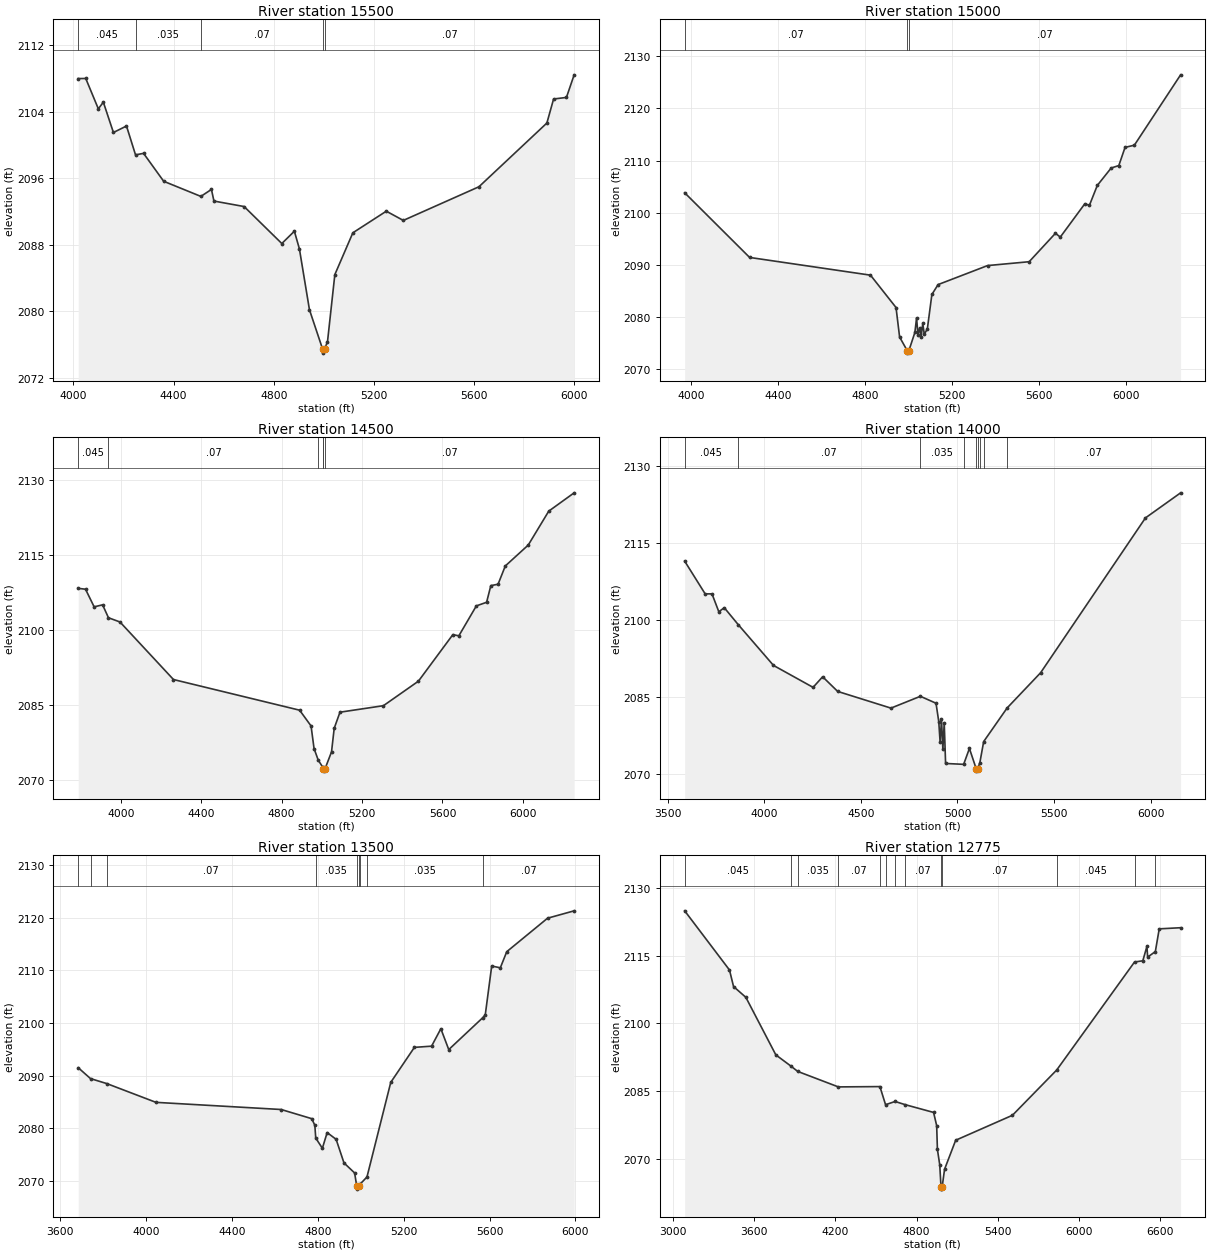
Type RM Length L Ch R = 1,15500,500,500,500
BEGIN DESCRIPTION:
Plum Branch 30.0
END DESCRIPTION:
XS GIS Cut Line= 3
      1366754.99      6911088.00      1367732.32      6911165.49
      1368704.97      6910938.01
#Sta/Elev= 30
  4019.6 2108.00  4049.7 2108.01  4099.9 2104.36  4119.9 2105.16  4160.1 2101.51
  4212.3 2102.29  4248.3 2098.82  4280.4 2099.00  4360.7 2095.64  4509.1 2093.82
  4551.3 2094.66  4561.3 2093.26  4681.7 2092.60  4832.2 2088.15  4882.3 2089.63
  4902.4 2087.50  4942.5 2080.18  4994.8 2075.46  4995.3 2074.96  5002.8 2075.46
  5014.5 2076.33  5043.8 2084.41  5115.7 2089.44  5249.2 2092.04  5317.1 2090.93
  5618.9 2094.98  5890.1 2102.65  5916.8 2105.54  5968.1 2105.73  5998.9 2108.45
#Mann=5,-1,0
  4019.6   0.045       0  4248.3   0.035       0  4509.1    0.07       0
  4994.8    0.07       0  5002.8    0.07       0
Bank Sta=4994.8,5002.8
Exp/Cntr=0.3,0.1

Type RM Length L Ch R = 1,15000,500,500,500
BEGIN DESCRIPTION:
Plum Branch 29.0
END DESCRIPTION:
XS GIS Cut Line= 3
      1366854.98      6911388.00      1367855.32      6911626.61
      1368805.00      6912438.00
#Sta/Elev= 30
  3971.6 2103.82  4269.8 2091.41  4824.9 2088.01  4942.2 2081.80  4958.6 2076.14
  4993.2 2073.55  4993.7 2073.05  5001.4 2073.55  5028.8 2077.02  5036.5 2079.81
  5043.1 2076.48  5050.8 2077.93  5057.4 2076.21  5065.1 2078.75  5071.7 2076.68
  5085.9 2077.66  5106.8 2084.30  5135.3 2086.20  5362.6 2089.85  5553.6 2090.59
  5674.4 2096.05  5696.4 2095.31  5809.4 2101.72  5830.3 2101.41  5866.5 2105.23
  5930.2 2108.57  5965.3 2109.04  5993.9 2112.53  6036.7 2112.95  6249.1 2126.45
#Mann=3,-1,0
  3971.6    0.07       0  4993.2    0.07       0  5001.4    0.07       0
Bank Sta=4993.2,5001.4
Exp/Cntr=0.3,0.1

Type RM Length L Ch R = 1,14500,500,500,500
BEGIN DESCRIPTION:
Plum Branch 28.0
END DESCRIPTION:
XS GIS Cut Line= 3
      1366704.96      6911387.98      1367703.88      6912073.46
      1368745.98      6912772.61
#Sta/Elev= 30
  3788.5 2108.35  3824.9 2108.17  3867.7 2104.65  3909.8 2105.05  3938.9 2102.47
  3996.3 2101.62  4262.2 2090.12  4889.6 2083.99  4946.5 2080.84  4961.4 2076.32
  4982.4 2073.98  5004.4 2072.62  5008.0 2072.31  5008.5 2071.81  5016.4 2072.31
  5048.3 2075.67  5061.6 2080.37  5090.3 2083.59  5306.4 2084.89  5480.4 2089.79
  5651.6 2099.09  5681.5 2098.86  5768.5 2104.84  5819.5 2105.56  5840.5 2108.89
  5876.5 2109.17  5912.5 2112.82  6026.6 2117.00  6128.6 2123.78  6254.9 2127.44
#Mann=6,-1,0
  3788.5   0.045       0  3938.9    0.07       0  4982.4    0.16       0
  5004.4    0.07       0  5008.0    0.07       0  5016.4    0.07       0
Bank Sta=5008,5016.4
Exp/Cntr=0.3,0.1

Type RM Length L Ch R = 1,14000,500,500,500
BEGIN DESCRIPTION:
Plum Branch 27.0
END DESCRIPTION:
XS GIS Cut Line= 3
      1366605.04      6911488.03      1367605.35      6912484.58
      1368715.60      6912802.98
#Sta/Elev= 30
  3588.0 2111.47  3694.0 2105.10  3729.4 2105.10  3764.7 2101.62  3793.0 2102.41
  3864.8 2099.13  4047.6 2091.18  4252.6 2086.91  4302.1 2088.97  4379.9 2086.12
  4655.7 2082.87  4808.0 2085.17  4889.0 2083.82  4903.2 2080.22  4910.2 2076.20
  4917.3 2080.66  4924.4 2074.88  4931.4 2080.04  4938.5 2072.10  5032.0 2071.93
  5061.8 2075.02  5096.6 2071.11  5097.1 2070.61  5105.0 2071.11  5115.9 2072.27
  5135.6 2076.36  5257.0 2082.90  5430.5 2089.76  5973.0 2119.88  6155.0 2124.76
#Mann=9,-1,0
  3588.0   0.045       0  3864.8    0.07       0  4808.0   0.035       0
  5032.0    0.16       0  5096.6   0.035       0  5105.0    0.16       0
  5115.9    0.07       0  5135.6    0.16       0  5257.0    0.07       0
Bank Sta=5096.6,5105
Exp/Cntr=0.3,0.1

Type RM Length L Ch R = 1,13500,725,725,725
BEGIN DESCRIPTION:
Plum Branch 26.0
END DESCRIPTION:
XS GIS Cut Line= 3
      1366855.00      6911888.00      1367685.02      6912908.47
      1368678.81      6912893.83
#Sta/Elev= 30
  3684.6 2091.49  3741.9 2089.42  3817.9 2088.47  4046.6 2084.91  4629.8 2083.55
  4772.0 2081.81  4786.4 2080.55  4790.7 2078.12  4821.5 2076.19  4843.8 2079.17
  4885.5 2077.89  4922.1 2073.41  4971.7 2071.50  4981.8 2068.93  4982.3 2068.43
  4990.3 2068.93  4998.4 2069.43  5029.2 2070.74  5140.0 2088.71  5250.0 2095.35
  5330.0 2095.58  5373.2 2098.89  5410.0 2094.93  5567.2 2100.94  5580.0 2101.52
  5610.0 2110.80  5650.1 2110.46  5680.1 2113.52  5870.1 2119.88  5993.9 2121.28
#Mann=9,-1,0
  3684.6    0.07       0  3741.9   0.035       0  3817.9    0.07       0
  4790.7   0.035       0  4981.8    0.07       0  4990.3   0.035       0
  4998.4    0.16       0  5029.2   0.035       0  5567.2    0.07       0
Bank Sta=4981.8,4990.3
Exp/Cntr=0.3,0.1

Type RM Length L Ch R = 1,12775,275,275,275
BEGIN DESCRIPTION:
Plum Branch 25.0
END DESCRIPTION:
XS GIS Cut Line= 5
      1366405.01      6911288.03      1367221.37      6913022.59
      1367339.42      6913258.70      1367621.83      6913323.81
      1368745.93      6912907.15
#Sta/Elev= 30
  3084.5 2124.91  3416.0 2111.81  3446.1 2108.15  3537.2 2105.76  3759.0 2093.02
  3871.4 2090.52  3920.7 2089.36  4221.5 2085.93  4529.1 2086.00  4570.9 2081.99
  4641.4 2082.70  4717.2 2081.99  4926.3 2080.28  4949.1 2077.36  4954.6 2072.09
  4971.9 2068.68  4981.1 2063.80  4981.6 2063.30  4989.7 2063.80  5007.6 2067.70
  5089.7 2074.12  5509.8 2079.65  5837.3 2089.67  6413.2 2113.58  6474.5 2113.85
  6504.9 2117.05  6510.2 2114.67  6567.1 2115.88  6596.0 2120.92  6754.2 2121.17
#Mann=13,-1,0
  3084.5   0.045       0  3871.4    0.07       0  3920.7   0.035       0
  4221.5    0.07       0  4529.1   0.035       0  4570.9    0.07       0
  4641.4   0.035       0  4717.2    0.07       0  4981.1    0.07       0
  4989.7    0.07       0  5837.3   0.045       0  6413.2   0.035       0
  6567.1    0.07       0
Bank Sta=4981.1,4989.7
Exp/Cntr=0.3,0.1