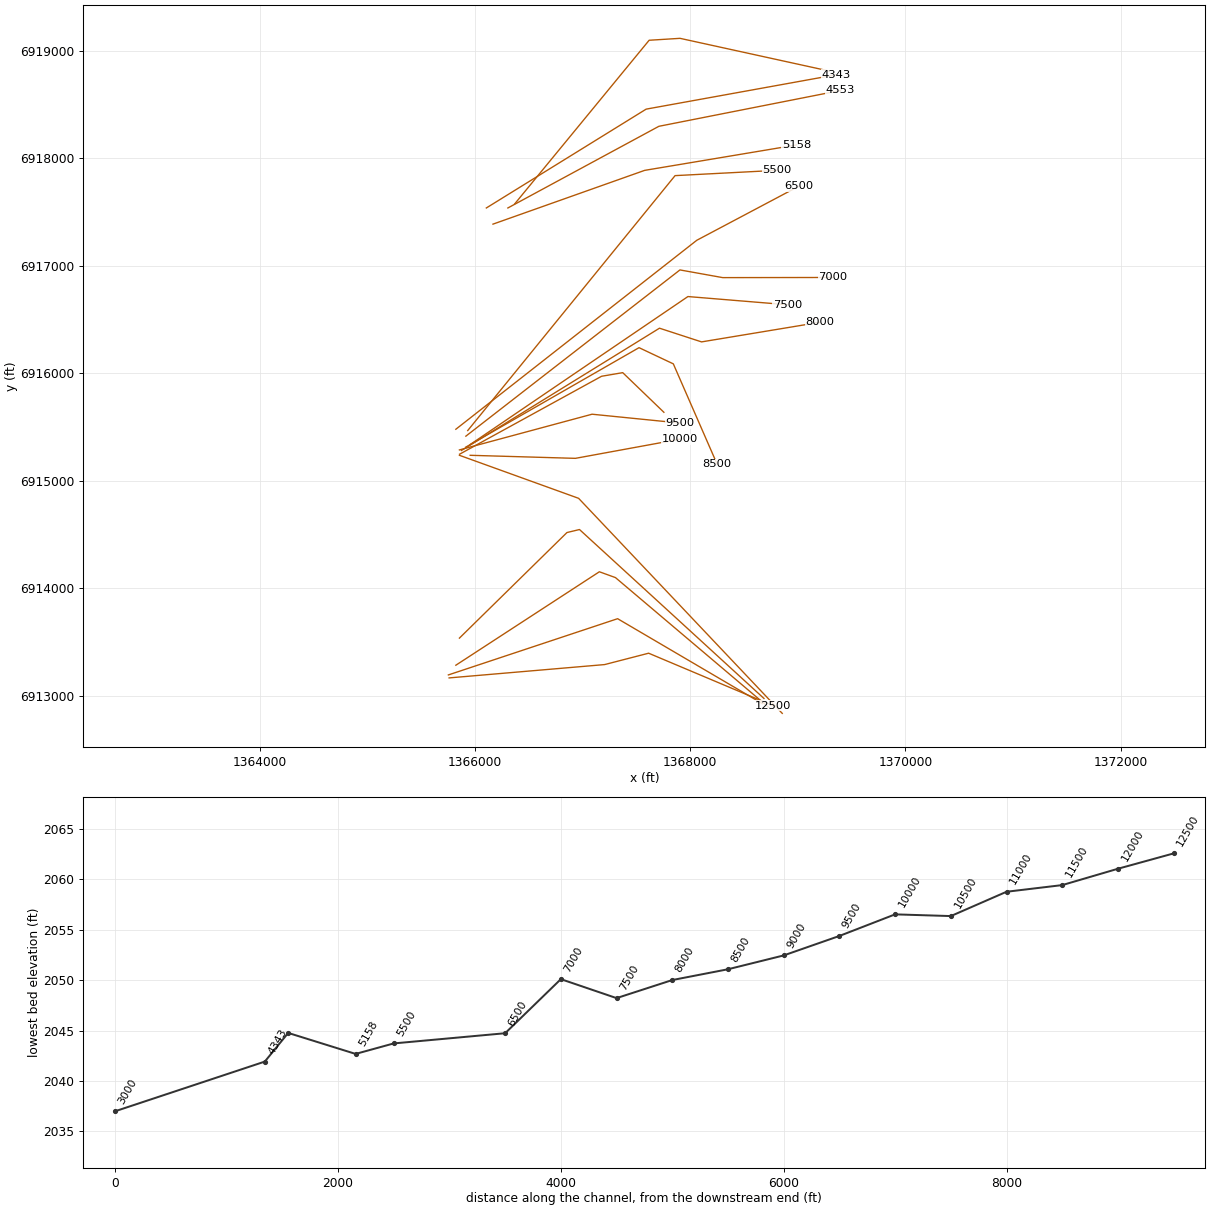
HEC-RAS study Plum Branch.prj: Plum Branch Base Level Engineering

--- Plum Branch.g01 (geometry) --- (continued)

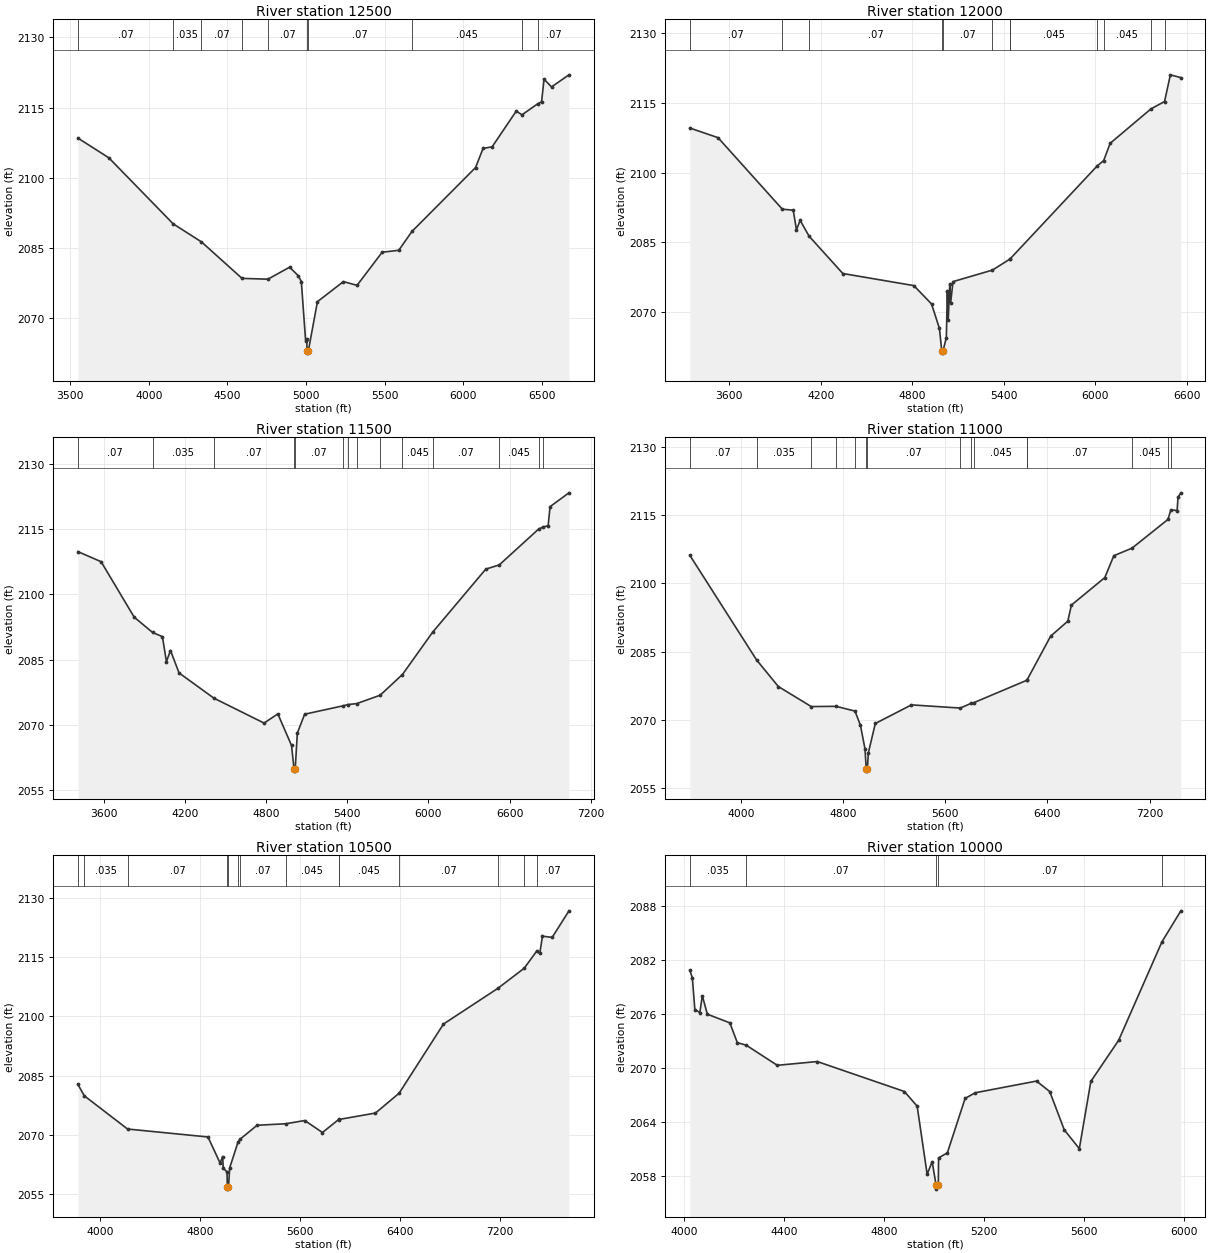
Type RM Length L Ch R = 1,12500,500,500,500
BEGIN DESCRIPTION:
Plum Branch 24.0
END DESCRIPTION:
XS GIS Cut Line= 4
      1365759.31      6913167.85      1367204.50      6913291.83
      1367613.15      6913397.59      1368765.60      6912911.21
#Sta/Elev= 30
  3549.5 2108.49  3745.9 2104.28  4155.2 2090.17  4335.0 2086.32  4593.2 2078.52
  4757.9 2078.35  4895.9 2080.91  4950.3 2079.11  4970.4 2077.85  4997.7 2065.20
  5005.2 2065.48  5006.5 2063.05  5007.0 2062.55  5015.1 2063.05  5072.8 2073.54
  5238.1 2077.83  5324.9 2077.03  5484.6 2084.11  5590.3 2084.52  5673.9 2088.54
  6078.8 2102.20  6126.3 2106.27  6184.5 2106.64  6337.7 2114.26  6374.0 2113.47
  6473.8 2115.81  6498.7 2116.24  6514.5 2121.08  6561.9 2119.42  6673.0 2122.01
#Mann=10,-1,0
  3549.5    0.07       0  4155.2   0.035       0  4335.0    0.07       0
  4593.2   0.035       0  4757.9    0.07       0  5006.5    0.07       0
  5015.1    0.07       0  5673.9   0.045       0  6374.0   0.035       0
  6473.8    0.07       0
Bank Sta=5006.5,5015.1
Exp/Cntr=0.3,0.1

Type RM Length L Ch R = 1,12000,500,500,500
BEGIN DESCRIPTION:
Plum Branch 23.0
END DESCRIPTION:
XS GIS Cut Line= 3
      1365752.28      6913195.61      1367325.02      6913718.56
      1368670.09      6912928.59
#Sta/Elev= 30
  3342.6 2109.60  3527.2 2107.52  3948.4 2092.09  4019.9 2091.87  4041.0 2087.65
  4065.3 2089.68  4123.9 2086.26  4344.9 2078.21  4810.3 2075.60  4926.2 2071.64
  4978.0 2066.35  4993.0 2061.53  4993.5 2061.03  5001.7 2061.53  5023.2 2064.40
  5029.9 2074.52  5035.6 2068.24  5045.5 2075.88  5051.3 2071.89  5067.0 2076.46
  5325.3 2078.95  5441.1 2081.35  5442.9 2081.43  6010.4 2101.38  6054.1 2102.58
  6096.5 2106.30  6364.1 2113.74  6453.1 2115.32  6491.1 2121.08  6559.9 2120.48
#Mann=12,-1,0
  3342.6    0.07       0  3948.4   0.035       0  4123.9    0.07       0
  4993.0    0.07       0  5001.7    0.07       0  5325.3   0.035       0
  5441.1    0.07       0  5442.9   0.045       0  6010.4    0.07       0
  6054.1   0.045       0  6364.1   0.035       0  6453.1    0.07       0
Bank Sta=4993,5001.7
Exp/Cntr=0.3,0.1

Type RM Length L Ch R = 1,11500,500,500,500
BEGIN DESCRIPTION:
Plum Branch 22.0
END DESCRIPTION:
XS GIS Cut Line= 4
      1365821.77      6913285.90      1367155.45      6914154.87
      1367304.99      6914100.72      1368739.61      6912885.14
#Sta/Elev= 30
  3408.2 2109.84  3579.2 2107.54  3824.0 2094.79  3960.2 2091.27  4032.7 2090.32
  4062.4 2084.58  4092.4 2087.12  4156.0 2081.97  4413.3 2076.18  4784.6 2070.45
  4886.4 2072.56  4987.5 2065.32  5006.1 2059.91  5006.6 2059.41  5014.8 2059.91
  5030.5 2068.15  5084.6 2072.49  5367.4 2074.41  5408.7 2074.72  5469.9 2074.93
  5642.8 2076.85  5807.8 2081.61  6030.5 2091.31  6423.9 2105.82  6524.1 2106.80
  6815.9 2115.06  6849.9 2115.52  6885.3 2115.81  6899.6 2120.19  7039.4 2123.36
#Mann=14,-1,0
  3408.2    0.07       0  3960.2   0.035       0  4413.3    0.07       0
  5006.1    0.07       0  5014.8    0.07       0  5367.4   0.045       0
  5408.7    0.07       0  5469.9   0.045       0  5642.8   0.035       0
  5807.8   0.045       0  6030.5    0.07       0  6524.1   0.045       0
  6815.9   0.035       0  6849.9    0.07       0
Bank Sta=5006.1,5014.8
Exp/Cntr=0.3,0.1

Type RM Length L Ch R = 1,11000,500,500,500
BEGIN DESCRIPTION:
Plum Branch 21.0
END DESCRIPTION:
XS GIS Cut Line= 4
      1365855.00      6913538.00      1366854.26      6914519.70
      1366970.79      6914547.77      1368685.17      6912976.61
#Sta/Elev= 30
  3599.2 2106.14  4121.3 2083.19  4292.2 2077.33  4550.1 2072.93  4744.5 2072.98
  4892.6 2071.94  4935.7 2068.78  4971.1 2063.62  4980.7 2059.25  4981.2 2058.75
  4989.8 2059.25  4997.0 2062.72  5051.9 2069.21  5335.0 2073.30  5717.9 2072.60
  5802.6 2073.65  5826.4 2073.82  6239.4 2078.71  6240.2 2078.77  6425.2 2088.39
  6559.6 2091.68  6588.0 2095.22  6849.4 2101.25  6920.3 2106.06  7062.7 2107.72
  7343.9 2114.02  7366.9 2116.13  7416.1 2115.98  7422.9 2118.94  7445.3 2119.87
#Mann=15,-1,0
  3599.2    0.07       0  4121.3   0.035       0  4550.1    0.07       0
  4744.5    0.16       0  4892.6    0.07       0  4980.7    0.07       0
  4989.8    0.07       0  5717.9   0.045       0  5802.6    0.07       0
  5826.4   0.045       0  6239.4   0.035       0  6240.2    0.07       0
  7062.7   0.045       0  7343.9   0.035       0  7366.9    0.07       0
Bank Sta=4980.7,4989.8
Exp/Cntr=0.3,0.1

Type RM Length L Ch R = 1,10500,500,500,500
BEGIN DESCRIPTION:
Plum Branch 20.0
END DESCRIPTION:
XS GIS Cut Line= 3
      1365855.02      6915237.99      1366962.57      6914837.90
      1368854.97      6912838.03
#Sta/Elev= 30
  3822.4 2082.80  3872.8 2079.95  4219.4 2071.54  4863.2 2069.53  4960.5 2062.91
  4980.5 2064.59  4985.8 2061.60  5015.7 2060.72  5018.3 2056.84  5018.8 2056.34
  5027.5 2056.84  5037.1 2061.72  5103.4 2068.20  5120.2 2068.97  5256.4 2072.49
  5485.1 2072.87  5638.2 2073.69  5779.8 2070.66  5909.4 2073.95  5909.6 2073.94
  6204.2 2075.58  6393.7 2080.60  6748.7 2098.09  7182.3 2107.08  7395.3 2112.21
  7494.8 2116.53  7519.7 2115.97  7541.2 2120.31  7618.8 2120.00  7753.3 2126.72
#Mann=14,-1,0
  3822.4    0.07       0  3872.8   0.035       0  4219.4    0.07       0
  5018.3    0.07       0  5027.5    0.07       0  5103.4    0.16       0
  5120.2    0.07       0  5485.1   0.045       0  5909.4    0.07       0
  5909.6   0.045       0  6393.7    0.07       0  7182.3   0.045       0
  7395.3   0.035       0  7494.8    0.07       0
Bank Sta=5018.3,5027.5
Exp/Cntr=0.3,0.1

Type RM Length L Ch R = 1,10000,500,500,500
BEGIN DESCRIPTION:
Plum Branch 19.0
END DESCRIPTION:
XS GIS Cut Line= 3
      1365955.01      6915238.00      1366932.70      6915209.67
      1367904.98      6915388.00
#Sta/Elev= 30
  4021.9 2080.82  4031.9 2080.00  4041.9 2076.47  4061.9 2076.14  4071.9 2078.00
  4091.9 2075.95  4182.0 2074.99  4212.0 2072.79  4247.5 2072.51  4372.0 2070.27
  4532.1 2070.69  4881.2 2067.36  4932.3 2065.73  4972.3 2058.16  4992.3 2059.56
  5007.9 2057.01  5008.4 2056.51  5017.1 2057.01  5018.0 2059.98  5053.2 2060.54
  5124.3 2066.59  5165.0 2067.22  5410.3 2068.52  5463.4 2067.35  5521.6 2063.09
  5581.8 2061.01  5627.9 2068.48  5739.3 2073.05  5912.6 2083.99  5988.5 2087.44
#Mann=5,-1,0
  4021.9   0.035       0  4247.5    0.07       0  5007.9    0.07       0
  5017.1    0.07       0  5912.6   0.035       0
Bank Sta=5007.9,5017.1
Exp/Cntr=0.3,0.1

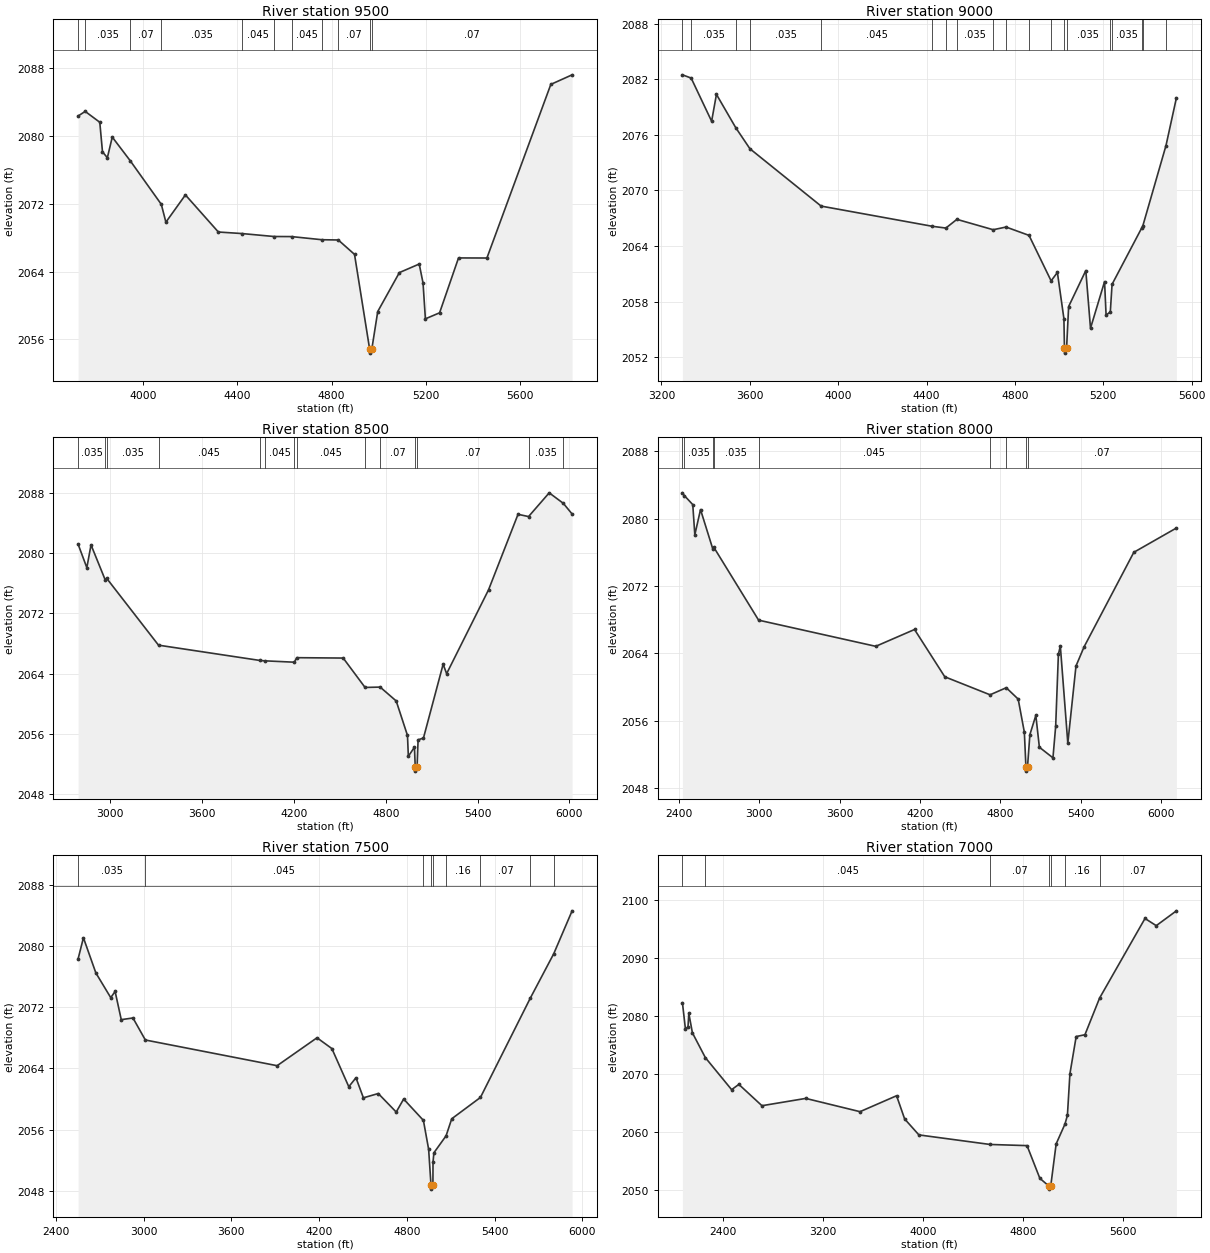
Type RM Length L Ch R = 1,9500,500,500,500
BEGIN DESCRIPTION:
Plum Branch 18.0
END DESCRIPTION:
XS GIS Cut Line= 3
      1365855.03      6915288.01      1367087.47      6915620.10
      1367904.96      6915538.00
#Sta/Elev= 30
  3723.6 2082.37  3753.7 2082.91  3815.6 2081.63  3827.1 2078.14  3847.8 2077.44
  3868.6 2079.88  3944.8 2077.09  4076.9 2071.94  4096.4 2069.83  4179.3 2073.05
  4319.2 2068.67  4418.8 2068.49  4555.4 2068.14  4630.0 2068.13  4758.9 2067.76
  4828.5 2067.73  4897.5 2066.03  4961.6 2054.87  4962.1 2054.37  4971.1 2054.87
  4996.1 2059.28  5088.0 2063.88  5172.3 2064.89  5188.5 2062.65  5198.5 2058.42
  5258.8 2059.13  5339.2 2065.61  5459.8 2065.60  5731.2 2086.10  5821.6 2087.23
#Mann=11,-1,0
  3723.6    0.07       0  3753.7   0.035       0  3944.8    0.07       0
  4076.9   0.035       0  4418.8   0.045       0  4555.4   0.035       0
  4630.0   0.045       0  4758.9   0.035       0  4828.5    0.07       0
  4961.6    0.07       0  4971.1    0.07       0
Bank Sta=4961.6,4971.1
Exp/Cntr=0.3,0.1

Type RM Length L Ch R = 1,9000,500,500,500
BEGIN DESCRIPTION:
Plum Branch 17.0
END DESCRIPTION:
XS GIS Cut Line= 4
      1365856.53      6915248.16      1367175.94      6915972.97
      1367372.50      6916006.59      1367755.01      6915637.99
#Sta/Elev= 30
  3295.2 2082.48  3334.7 2082.13  3427.3 2077.47  3449.1 2080.37  3536.6 2076.77
  3600.7 2074.50  3923.0 2068.31  4426.3 2066.13  4487.6 2065.94  4537.5 2066.88
  4701.7 2065.76  4760.0 2066.05  4864.0 2065.15  4964.0 2060.24  4992.4 2061.15
  5021.9 2056.16  5024.4 2052.94  5024.9 2052.44  5033.9 2052.94  5043.3 2057.47
  5121.0 2061.35  5142.3 2055.13  5205.9 2060.16  5212.8 2056.55  5231.9 2056.88
  5239.9 2059.87  5373.4 2065.92  5378.4 2066.12  5484.0 2074.85  5531.2 2080.00
#Mann=19,-1,0
  3295.2    0.07       0  3334.7   0.035       0  3536.6    0.07       0
  3600.7   0.035       0  3923.0   0.045       0  4426.3   0.035       0
  4487.6   0.045       0  4537.5   0.035       0  4701.7   0.045       0
  4760.0   0.035       0  4864.0    0.07       0  4964.0   0.035       0
  5024.4   0.035       0  5033.9   0.035       0  5231.9    0.07       0
  5239.9   0.035       0  5373.4    0.07       0  5378.4   0.035       0
  5484.0    0.07       0
Bank Sta=5024.4,5033.9
Exp/Cntr=0.3,0.1

Type RM Length L Ch R = 1,8500,500,500,500
BEGIN DESCRIPTION:
Plum Branch 16.0
END DESCRIPTION:
XS GIS Cut Line= 4
      1365912.91      6915313.24      1367523.96      6916238.91
      1367842.72      6916088.30      1368249.79      6915155.56
#Sta/Elev= 30
  2789.4 2081.17  2846.4 2078.06  2873.8 2081.08  2967.1 2076.41  2975.5 2076.66
  3314.8 2067.78  3978.2 2065.75  4011.6 2065.70  4202.9 2065.52  4218.1 2066.12
  4521.8 2066.07  4664.7 2062.17  4763.2 2062.22  4868.1 2060.38  4941.9 2055.80
  4947.5 2053.03  4987.5 2054.25  4992.6 2051.57  4993.1 2051.07  5004.4 2051.57
  5011.2 2055.22  5046.3 2055.46  5174.9 2065.25  5197.7 2064.00  5471.6 2075.12
  5664.3 2085.14  5733.1 2084.84  5868.0 2087.99  5960.6 2086.59  6017.7 2085.18
#Mann=14,-1,0
  2789.4   0.035       0  2967.1    0.07       0  2975.5   0.035       0
  3314.8   0.045       0  3978.2   0.035       0  4011.6   0.045       0
  4202.9   0.035       0  4218.1   0.045       0  4664.7   0.035       0
  4763.2    0.07       0  4992.6    0.07       0  5004.4    0.07       0
  5733.1   0.035       0  5960.6    0.07       0
Bank Sta=4992.6,5004.4
Exp/Cntr=0.3,0.1

Type RM Length L Ch R = 1,8000,500,500,500
BEGIN DESCRIPTION:
Plum Branch 15.0
END DESCRIPTION:
XS GIS Cut Line= 4
      1365873.84      6915282.85      1367714.13      6916420.02
      1368104.98      6916292.57      1369204.66      6916474.99
#Sta/Elev= 30
  2425.6 2083.07  2439.4 2082.75  2502.7 2081.67  2518.1 2078.08  2560.6 2081.08
  2652.7 2076.38  2660.2 2076.59  2994.4 2067.94  3869.3 2064.83  4158.9 2066.83
  4384.8 2061.21  4723.0 2059.07  4843.8 2059.91  4932.9 2058.56  4979.0 2054.63
  4990.8 2050.50  4991.3 2050.00  5002.6 2050.50  5020.3 2054.34  5064.8 2056.62
  5091.2 2052.84  5192.6 2051.58  5212.9 2055.33  5233.2 2063.87  5247.7 2064.87
  5303.6 2053.32  5364.6 2062.49  5425.5 2064.78  5796.4 2076.00  6114.7 2078.89
#Mann=9,-1,0
  2425.6    0.07       0  2439.4   0.035       0  2652.7    0.07       0
  2660.2   0.035       0  2994.4   0.045       0  4723.0   0.035       0
  4843.8    0.07       0  4990.8    0.07       0  5002.6    0.07       0
Bank Sta=4990.8,5002.6
Exp/Cntr=0.3,0.1

Type RM Length L Ch R = 1,7500,500,500,500
BEGIN DESCRIPTION:
Plum Branch 14.0
END DESCRIPTION:
XS GIS Cut Line= 3
      1365954.99      6915337.99      1367978.52      6916714.26
      1368904.99      6916638.00
#Sta/Elev= 30
  2552.8 2078.32  2589.1 2081.08  2674.1 2076.48  2775.8 2073.25  2805.7 2074.06
  2847.7 2070.37  2927.7 2070.59  3012.4 2067.71  3913.2 2064.35  4185.7 2068.00
  4287.4 2066.59  4403.1 2061.60  4452.1 2062.77  4502.9 2060.15  4604.6 2060.71
  4727.3 2058.29  4778.1 2059.99  4913.1 2057.20  4948.9 2053.42  4965.1 2048.71
  4965.6 2048.21  4978.1 2048.71  4978.8 2051.72  4984.8 2052.96  5068.1 2055.18
  5106.8 2057.41  5303.1 2060.20  5644.3 2073.20  5804.1 2078.99  5929.6 2084.60
#Mann=9,-1,0
  2552.8   0.035       0  3012.4   0.045       0  4913.1    0.07       0
  4965.1    0.07       0  4978.1    0.07       0  5068.1    0.16       0
  5303.1    0.07       0  5644.3    0.16       0  5804.1    0.07       0
Bank Sta=4965.1,4978.1
Exp/Cntr=0.3,0.1

Type RM Length L Ch R = 1,7000,500,500,500
BEGIN DESCRIPTION:
Plum Branch 13.0
END DESCRIPTION:
XS GIS Cut Line= 4
      1365914.70      6915415.94      1367904.27      6916961.84
      1368301.93      6916890.31      1369326.23      6916891.66
#Sta/Elev= 30
  2076.4 2082.26  2100.0 2077.80  2120.8 2078.07  2127.4 2080.43  2156.1 2077.07
  2259.5 2072.79  2469.4 2067.26  2527.2 2068.17  2711.8 2064.49  3062.0 2065.75
  3495.5 2063.46  3787.8 2066.21  3852.1 2062.21  3966.1 2059.45  4534.8 2057.80
  4830.4 2057.60  4932.7 2051.96  5006.6 2050.59  5007.1 2050.09  5019.6 2050.59
  5063.1 2057.90  5133.7 2061.33  5153.1 2062.83  5173.1 2070.00  5223.1 2076.43
  5293.1 2076.74  5410.2 2083.07  5773.1 2096.81  5863.1 2095.57  6024.3 2098.13
#Mann=7,-1,0
  2076.4   0.035       0  2259.5   0.045       0  4534.8    0.07       0
  5006.6    0.07       0  5019.6    0.07       0  5133.7    0.16       0
  5410.2    0.07       0
Bank Sta=5006.6,5019.6
Exp/Cntr=0.3,0.1

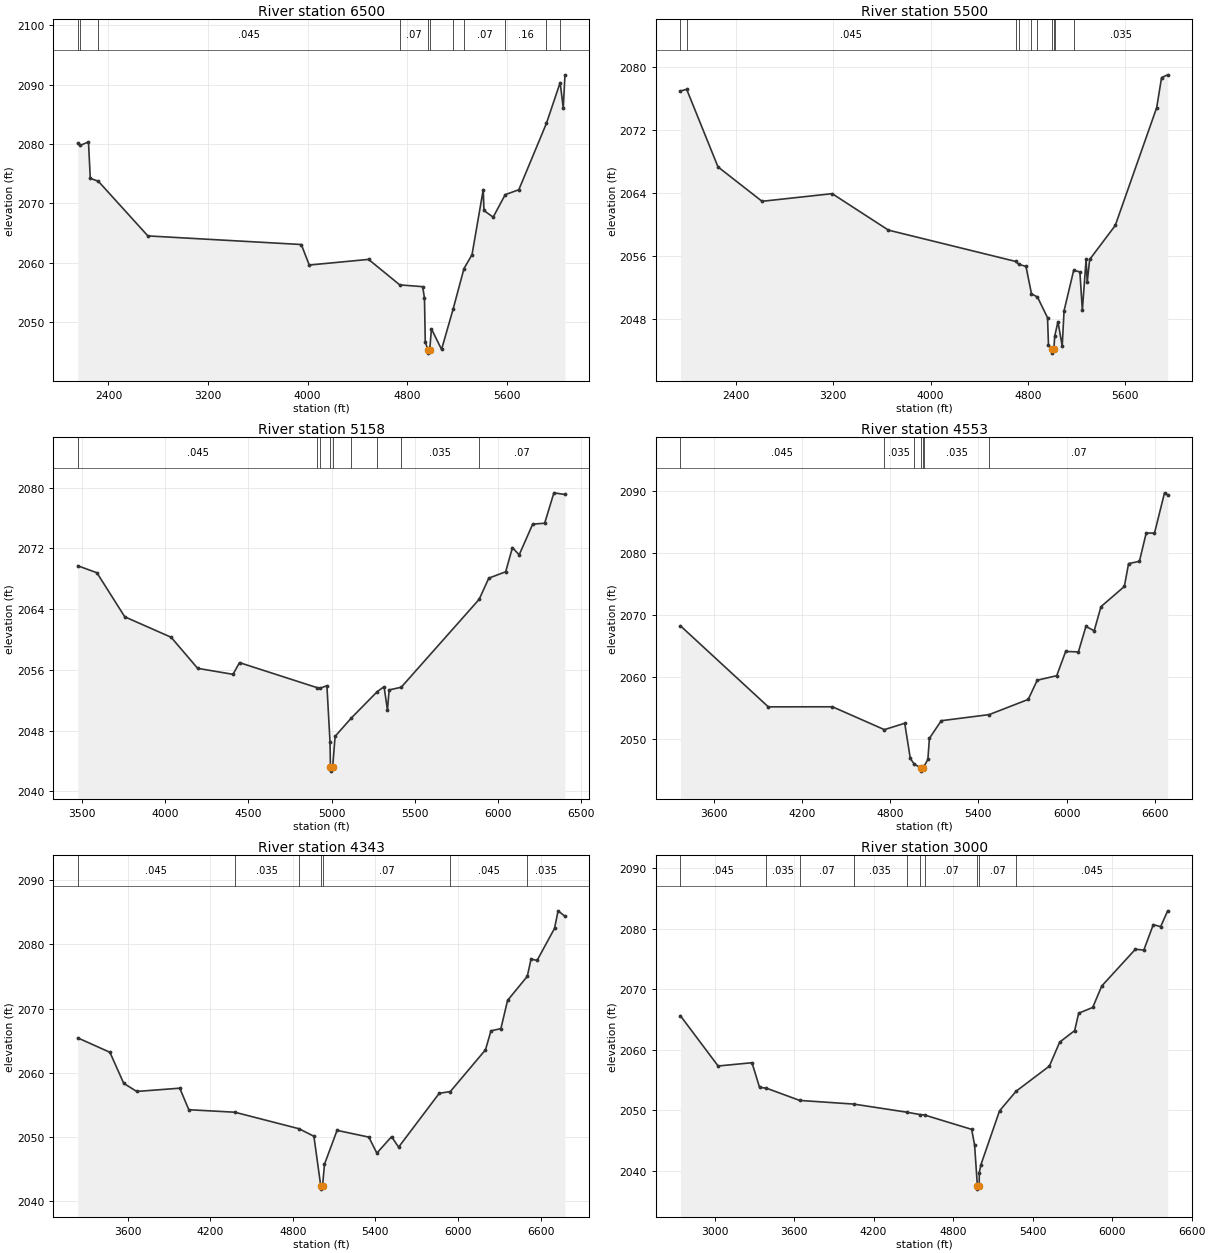
Type RM Length L Ch R = 1,6500,1000,1000,1000
BEGIN DESCRIPTION:
Plum Branch 12.0
END DESCRIPTION:
XS GIS Cut Line= 3
      1365821.78      6915480.35      1368061.03      6917237.71
      1369005.04      6917738.02
#Sta/Elev= 30
  2153.5 2080.15  2172.1 2079.76  2239.5 2080.35  2254.0 2074.21  2318.7 2073.72
  2716.9 2064.50  3949.7 2063.05  4013.5 2059.59  4490.2 2060.54  4740.9 2056.24
  4925.0 2055.94  4939.5 2053.99  4945.8 2046.61  4968.2 2045.23  4968.7 2044.73
  4981.2 2045.23  4995.5 2048.82  5076.7 2045.35  5169.8 2052.17  5257.0 2059.00
  5321.4 2061.33  5411.7 2072.31  5417.3 2068.79  5491.2 2067.66  5588.2 2071.46
  5697.6 2072.29  5919.3 2083.48  6029.7 2090.36  6054.5 2086.11  6068.4 2091.67
#Mann=11,-1,0
  2153.5    0.07       0  2172.1   0.035       0  2318.7   0.045       0
  4740.9    0.07       0  4968.2    0.07       0  4981.2    0.07       0
  5169.8    0.16       0  5257.0    0.07       0  5588.2    0.16       0
  5919.3    0.07       0  6029.7    0.16       0
Bank Sta=4968.2,4981.2
Exp/Cntr=0.3,0.1

Type RM Length L Ch R = 1,5500,342,342,342
BEGIN DESCRIPTION:
Plum Branch 11.0
END DESCRIPTION:
XS GIS Cut Line= 3
      1365932.06      6915468.01      1367858.97      6917838.80
      1368804.99      6917888.00
#Sta/Elev= 30
  1944.9 2077.01  1995.9 2077.22  2253.2 2067.37  2615.0 2063.00  3191.3 2063.97
  3653.2 2059.34  4699.5 2055.36  4726.2 2054.98  4783.0 2054.74  4828.6 2051.26
  4877.8 2050.84  4960.4 2048.22  4968.3 2044.72  4999.5 2044.22  5000.0 2043.72
  5012.6 2044.22  5019.2 2045.86  5046.1 2047.71  5081.0 2044.60  5096.2 2049.10
  5175.5 2054.25  5226.3 2054.03  5246.4 2049.17  5277.4 2055.65  5286.4 2052.73
  5306.4 2055.61  5516.7 2059.93  5857.2 2074.90  5897.2 2078.71  5947.3 2079.06
#Mann=10,-1,0
  1944.9   0.035       0  1995.9   0.045       0  4699.5    0.07       0
  4726.2   0.045       0  4828.6   0.035       0  4877.8   0.045       0
  4999.5   0.045       0  5012.6   0.045       0  5019.2    0.07       0
  5175.5   0.035       0
Bank Sta=4999.5,5012.6
Exp/Cntr=0.3,0.1

Type RM Length L Ch R = 1,5158,605,605,605
BEGIN DESCRIPTION:
Plum Branch 10.0
END DESCRIPTION:
XS GIS Cut Line= 3
      1366166.73      6917387.73      1367576.45      6917887.73
      1368986.15      6918123.84
#Sta/Elev= 30
  3476.2 2069.71  3591.1 2068.79  3758.4 2062.99  4036.7 2060.30  4195.9 2056.21
  4408.1 2055.42  4447.2 2056.96  4914.0 2053.66  4932.6 2053.60  4972.0 2053.93
  4990.8 2046.48  4993.2 2043.18  4993.7 2042.68  5006.4 2043.18  5021.2 2047.26
  5119.3 2049.69  5275.0 2053.16  5315.2 2053.79  5335.5 2050.72  5345.6 2053.37
  5418.1 2053.72  5886.0 2065.29  5943.9 2068.08  6045.3 2068.92  6085.8 2072.10
  6126.4 2071.15  6207.5 2075.19  6279.3 2075.31  6334.9 2079.31  6401.3 2079.09
#Mann=9,-1,0
  3476.2   0.045       0  4914.0   0.035       0  4932.6    0.07       0
  4993.2    0.07       0  5006.4    0.07       0  5119.3   0.045       0
  5275.0    0.07       0  5418.1   0.035       0  5886.0    0.07       0
Bank Sta=4993.2,5006.4
Exp/Cntr=0.3,0.1

Type RM Length L Ch R = 1,4553,210,210,210
BEGIN DESCRIPTION:
Plum Branch 9.0
END DESCRIPTION:
XS GIS Cut Line= 3
      1366305.03      6917538.02      1367708.40      6918297.45
      1369395.92      6918630.79
#Sta/Elev= 30
  3372.7 2068.22  3970.5 2055.14  4407.2 2055.15  4760.5 2051.46  4899.0 2052.49
  4937.0 2046.80  4963.1 2045.92  5009.3 2045.26  5009.8 2044.76  5022.5 2045.26
  5030.0 2045.52  5056.6 2046.64  5066.8 2050.05  5147.5 2052.90  5474.0 2053.89
  5739.6 2056.34  5800.8 2059.44  5933.3 2060.17  5994.4 2064.09  6080.9 2064.01
  6132.1 2068.12  6188.5 2067.43  6234.7 2071.32  6393.7 2074.58  6422.5 2078.27
  6496.2 2078.64  6542.4 2083.21  6598.8 2083.19  6667.2 2089.70  6688.5 2089.37
#Mann=7,-1,0
  3372.7   0.045       0  4760.5   0.035       0  4963.1    0.07       0
  5009.3    0.07       0  5022.5    0.07       0  5030.0   0.035       0
  5474.0    0.07       0
Bank Sta=5009.3,5022.5
Exp/Cntr=0.3,0.1

Type RM Length L Ch R = 1,4343,1343,1343,1343
BEGIN DESCRIPTION:
Plum Branch 8.0
END DESCRIPTION:
XS GIS Cut Line= 3
      1366105.02      6917538.01      1367590.34      6918457.18
      1369354.22      6918776.62
#Sta/Elev= 30
  3238.2 2065.44  3471.6 2063.20  3572.0 2058.37  3666.6 2057.11  3979.1 2057.62
  4044.8 2054.27  4379.3 2053.88  4845.8 2051.31  4953.6 2050.14  5003.4 2042.42
  5003.9 2041.92  5016.6 2042.42  5030.3 2045.78  5121.8 2051.06  5352.4 2050.01
  5410.9 2047.52  5517.8 2050.08  5568.9 2048.45  5864.0 2056.82  5944.8 2057.10
  6200.1 2063.59  6239.7 2066.53  6312.1 2066.89  6360.5 2071.27  6503.8 2075.01
  6531.0 2077.69  6575.0 2077.49  6701.6 2082.47  6727.5 2085.20  6777.5 2084.35
#Mann=7,-1,0
  3238.2   0.045       0  4379.3   0.035       0  4845.8    0.07       0
  5003.4    0.07       0  5016.6    0.07       0  5944.8   0.045       0
  6503.8   0.035       0
Bank Sta=5003.4,5016.6
Exp/Cntr=0.3,0.1

Type RM Length L Ch R = 1,3000,500,500,500
BEGIN DESCRIPTION:
Plum Branch 6.0
END DESCRIPTION:
XS GIS Cut Line= 4
      1366368.15      6917575.27      1367618.02      6919097.66
      1367904.92      6919115.55      1369290.87      6918811.53
#Sta/Elev= 30
  2742.8 2065.63  3027.0 2057.34  3282.4 2057.88  3339.8 2053.79  3389.9 2053.69
  3642.4 2051.65  4049.8 2051.05  4450.4 2049.71  4549.7 2049.32  4585.1 2049.24
  4940.0 2046.87  4962.0 2044.30  4983.4 2037.50  4983.9 2037.00  4996.8 2037.50
  4997.5 2039.69  5008.5 2040.95  5150.2 2049.93  5275.2 2053.17  5526.3 2057.32
  5604.1 2061.28  5716.9 2063.18  5747.4 2066.06  5853.5 2067.01  5921.5 2070.55
  6175.5 2076.63  6238.8 2076.48  6310.5 2080.69  6366.1 2080.36  6418.9 2082.97
#Mann=10,-1,0
  2742.8   0.045       0  3389.9   0.035       0  3642.4    0.07       0
  4049.8   0.035       0  4450.4    0.07       0  4549.7   0.035       0
  4585.1    0.07       0  4983.4    0.07       0  4996.8    0.07       0
  5275.2   0.045       0
Bank Sta=4983.4,4996.8
Exp/Cntr=0.3,0.1