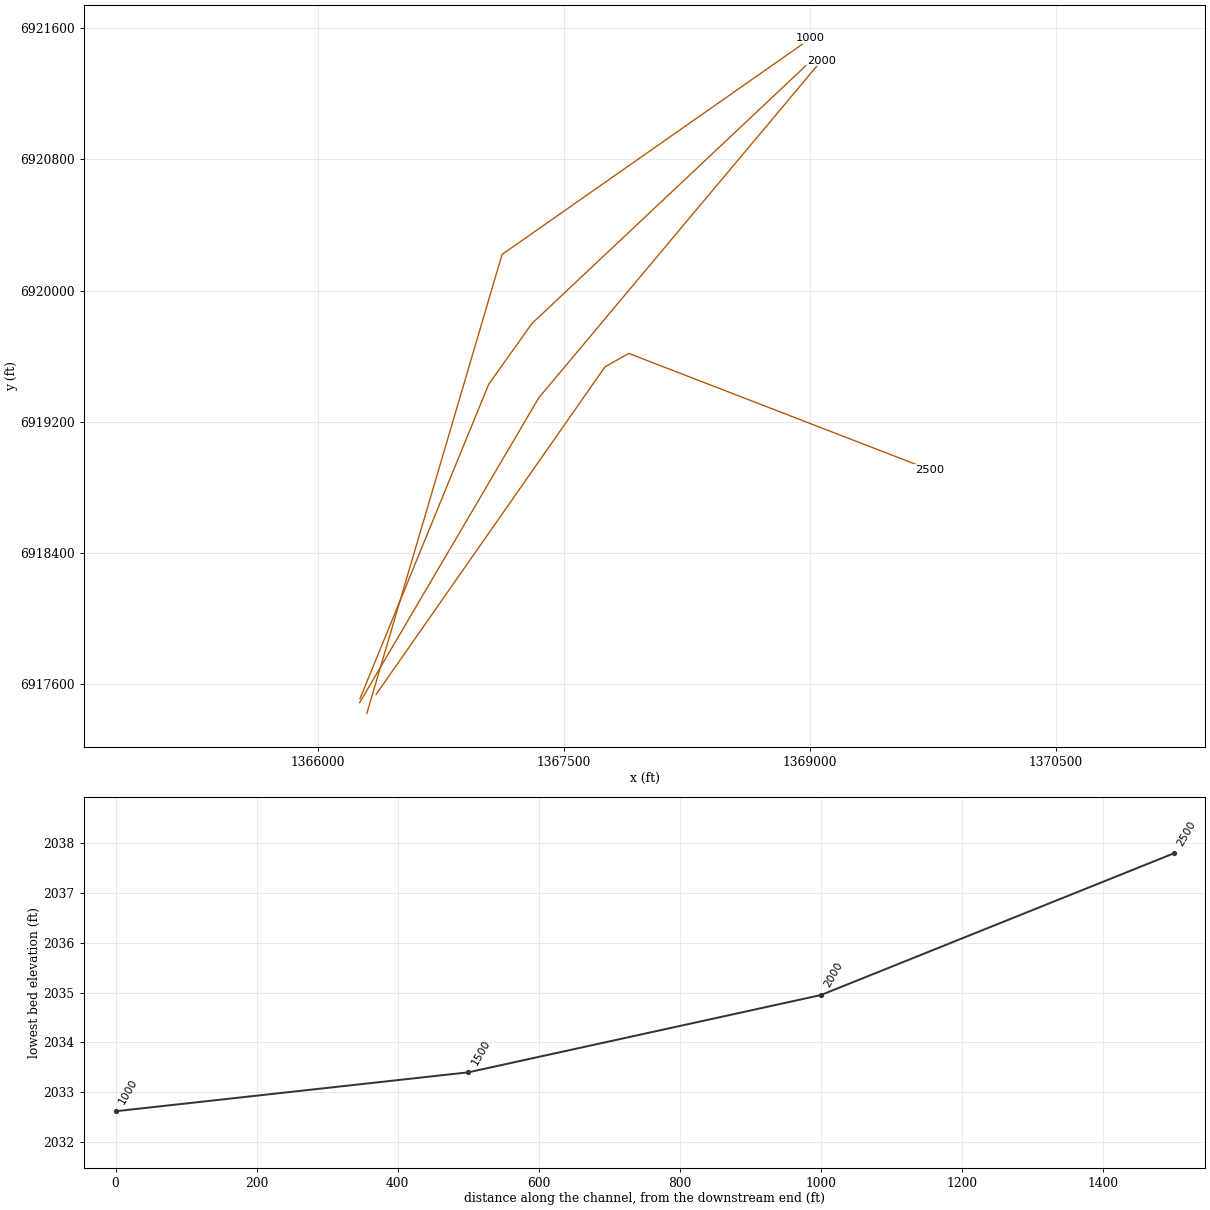
HEC-RAS study Plum Branch.prj: Plum Branch Base Level Engineering

--- Plum Branch.g01 (geometry) --- (continued)

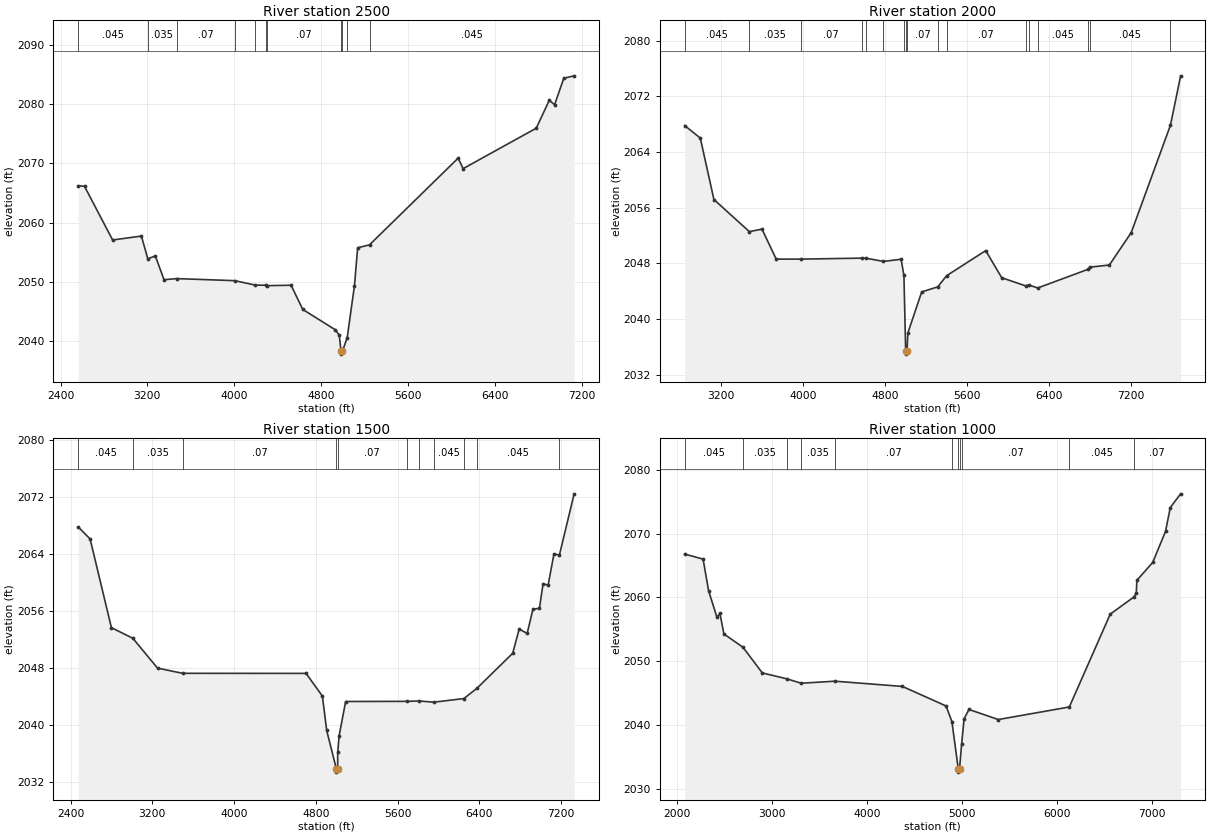
Type RM Length L Ch R = 1,2500,500,500,500
BEGIN DESCRIPTION:
Plum Branch 5.0
END DESCRIPTION:
XS GIS Cut Line= 4
      1366355.00      6917538.01      1367750.83      6919535.55
      1367895.90      6919616.90      1369729.20      6918908.58
#Sta/Elev= 30
  2563.1 2066.22  2621.1 2066.12  2880.1 2057.06  3145.3 2057.72  3204.0 2053.88
  3273.5 2054.37  3353.7 2050.35  3471.3 2050.54  4005.8 2050.19  4194.9 2049.44
  4295.2 2049.42  4306.8 2049.35  4524.1 2049.42  4631.4 2045.34  4932.3 2041.89
  4968.1 2040.97  4984.1 2038.29  4984.6 2037.79  4997.5 2038.29  5041.1 2040.57
  5108.0 2049.36  5137.3 2055.74  5246.6 2056.24  6062.8 2070.87  6108.8 2069.10
  6782.6 2075.93  6902.4 2080.63  6951.6 2079.89  7036.1 2084.36  7131.7 2084.77
#Mann=11,-1,0
  2563.1   0.045       0  3204.0   0.035       0  3471.3    0.07       0
  4005.8   0.035       0  4194.9    0.07       0  4295.2   0.035       0
  4306.8    0.07       0  4984.1    0.07       0  4997.5    0.07       0
  5041.1   0.035       0  5246.6   0.045       0
Bank Sta=4984.1,4997.5
Exp/Cntr=0.3,0.1

Type RM Length L Ch R = 1,2000,500,500,500
BEGIN DESCRIPTION:
Plum Branch 4.0
END DESCRIPTION:
XS GIS Cut Line= 3
      1366255.01      6917488.01      1367347.12      6919346.71
      1369069.52      6921401.63
#Sta/Elev= 30
  2844.2 2067.81  2996.5 2066.01  3129.4 2057.18  3475.1 2052.56  3598.1 2052.92
  3736.9 2048.61  3975.4 2048.61  4571.2 2048.75  4613.2 2048.74  4783.3 2048.28
  4955.1 2048.59  4982.6 2046.26  4999.6 2035.45  5000.1 2034.95  5013.0 2035.45
  5020.7 2037.98  5155.9 2043.89  5312.4 2044.62  5399.4 2046.23  5780.4 2049.83
  5936.6 2045.93  6170.7 2044.76  6199.2 2044.90  6287.3 2044.46  6779.4 2047.15
  6795.3 2047.45  6986.5 2047.76  7199.9 2052.43  7582.6 2067.88  7681.3 2074.96
#Mann=17,-1,0
  2844.2   0.045       0  3475.1   0.035       0  3975.4    0.07       0
  4571.2   0.035       0  4613.2    0.07       0  4783.3   0.035       0
  4982.6    0.07       0  4999.6    0.07       0  5013.0    0.07       0
  5312.4   0.045       0  5399.4    0.07       0  6170.7   0.045       0
  6199.2    0.07       0  6287.3   0.045       0  6779.4    0.07       0
  6795.3   0.045       0  7582.6    0.07       0
Bank Sta=4999.6,5013
Exp/Cntr=0.3,0.1

Type RM Length L Ch R = 1,1500,500,500,500
BEGIN DESCRIPTION:
Plum Branch 3.0
END DESCRIPTION:
XS GIS Cut Line= 4
      1366256.99      6917512.69      1367041.73      6919429.40
      1367305.07      6919799.18      1368999.12      6921393.79
#Sta/Elev= 30
  2474.9 2067.77  2591.3 2066.08  2799.5 2053.65  3009.6 2052.16  3250.7 2047.98
  3496.6 2047.25  4704.1 2047.24  4863.5 2044.06  4905.8 2039.24  4999.5 2033.90
  5000.0 2033.40  5012.9 2033.90  5013.5 2036.17  5027.4 2038.50  5091.1 2043.30
  5690.8 2043.32  5807.7 2043.37  5955.1 2043.21  6247.4 2043.71  6374.7 2045.14
  6725.3 2050.06  6788.8 2053.46  6866.9 2052.84  6923.1 2056.22  6987.1 2056.37
  7022.3 2059.80  7072.0 2059.61  7128.6 2063.96  7182.7 2063.85  7326.5 2072.41
#Mann=11,-1,0
  2474.9   0.045       0  3009.6   0.035       0  3496.6    0.07       0
  4999.5    0.07       0  5012.9    0.07       0  5690.8   0.045       0
  5807.7    0.07       0  5955.1   0.045       0  6247.4    0.07       0
  6374.7   0.045       0  7182.7    0.07       0
Bank Sta=4999.5,5012.9
Exp/Cntr=0.3,0.1

Type RM Length L Ch R = 1,1000,0,0,0
BEGIN DESCRIPTION:
Plum Branch 2.0
END DESCRIPTION:
XS GIS Cut Line= 3
      1366298.67      6917422.43      1367123.09      6920220.30
      1369005.02      6921538.02
#Sta/Elev= 30
  2083.2 2066.79  2276.7 2066.00  2334.8 2061.04  2422.6 2056.87  2453.9 2057.49
  2495.6 2054.27  2695.9 2052.19  2899.3 2048.17  3161.8 2047.22  3307.9 2046.55
  3661.9 2046.87  4372.1 2046.05  4830.8 2042.99  4892.8 2040.55  4959.6 2033.12
  4960.1 2032.62  4973.0 2033.12  4994.8 2037.01  5021.4 2040.99  5072.0 2042.44
  5380.8 2040.86  6127.2 2042.83  6557.6 2057.38  6807.0 2060.07  6831.4 2060.73
  6837.5 2062.68  7004.0 2065.48  7138.7 2070.34  7188.8 2074.08  7297.4 2076.23
#Mann=11,-1,0
  2083.2   0.045       0  2695.9   0.035       0  3161.8    0.07       0
  3307.9   0.035       0  3661.9    0.07       0  4892.8   0.035       0
  4959.6    0.07       0  4973.0   0.035       0  4994.8    0.07       0
  6127.2   0.045       0  6807.0    0.07       0
Bank Sta=4959.6,4973
Exp/Cntr=0.3,0.1

Chan Stop Cuts=-1