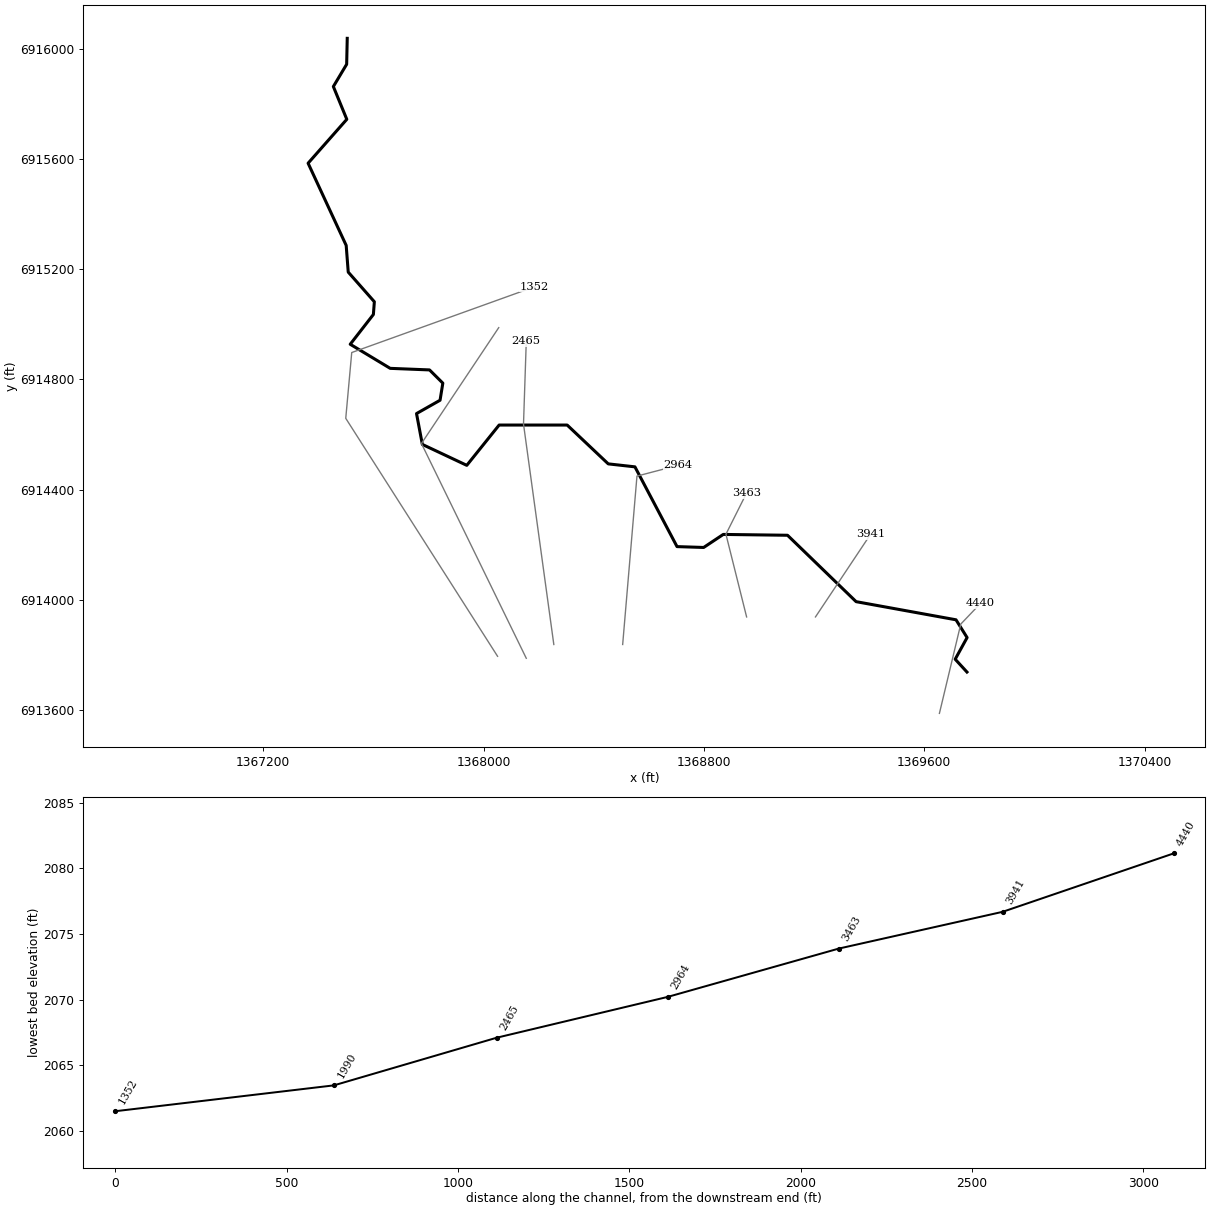
--- Plum Branch Trib01.prj (project) ---

Proj Title=Plum Branch Trib01 Base Level Engineering
Current Plan=p01
Default Exp/Contr=0.3,0.1
English Units
Geom File=g01
Flow File=f01
Plan File=p01
BEGIN DESCRIPTION:
Plum Branch Trib01
END DESCRIPTION:

--- Plum Branch Trib01.p01 (plan) ---

Plan Title=Multiple Run
Short Identifier=Multiple
Geom File=g01
Flow File=f01
Subcritical Flow
K Sum by GR= 0
Std Step Tol= 0.01
Critical Tol= 0.01
Num of Std Step Trials= 20
Max Error Tol= 0.3
Flow Tol Ratio= 0.001
Split Flow NTrial= 30
Split Flow Tol= 0.02
Split Flow Ratio= 0.02
Log Output Level= 0
Friction Slope Method= 1
Unsteady Friction Slope Method= 2
Unsteady Bridges Friction Slope Method= 1
Parabolic Critical Depth
Global Vel Dist=  1 , 1 , 1
Global Log Level= 0
CheckData=True
Encroach Param= -1, 0, 0, 0
BEGIN DESCRIPTION:
Multiple Run
END DESCRIPTION:

--- Plum Branch Trib01.f01 (steady flow) ---

Flow Title=Multiple
Number of Profiles=7
Profile Names=10-year,25-year,50-year,1pct_min,100-year,1pct_plu,500-year
River Rch & RM= Plum Branch Trib,Reach-1,4440
     238     333     412     253     505    1008     771
Boundary for River Rch & Prof#=Plum Branch Trib,Reach-1,1
Up Type=0
Dn Type=3
Dn Slope=0.005
Boundary for River Rch & Prof#=Plum Branch Trib,Reach-1,2
Up Type=0
Dn Type=3
Dn Slope=0.005
Boundary for River Rch & Prof#=Plum Branch Trib,Reach-1,3
Up Type=0
Dn Type=3
Dn Slope=0.005
Boundary for River Rch & Prof#=Plum Branch Trib,Reach-1,4
Up Type=0
Dn Type=3
Dn Slope=0.005
Boundary for River Rch & Prof#=Plum Branch Trib,Reach-1,5
Up Type=0
Dn Type=3
Dn Slope=0.005
Boundary for River Rch & Prof#=Plum Branch Trib,Reach-1,6
Up Type=0
Dn Type=3
Dn Slope=0.005
Boundary for River Rch & Prof#=Plum Branch Trib,Reach-1,7
Up Type=0
Dn Type=3
Dn Slope=0.005

--- Plum Branch Trib01.g01 (geometry) ---

Geom Title=Existing Conditions

River Reach=Plum Branch Trib,Reach-1
Reach XY= 30
      1369755.00      6913738.00      1369712.27      6913784.56
      1369755.49      6913863.10      1369715.23      6913927.65
      1369352.55      6913993.47      1369103.54      6914234.46
      1368870.22      6914237.48      1368799.02      6914190.16
      1368702.32      6914193.29      1368549.56      6914482.75
      1368452.63      6914493.55      1368303.54      6914634.46
      1368056.45      6914634.47      1367938.98      6914488.23
      1367777.68      6914564.12      1367756.53      6914676.11
      1367841.97      6914724.48      1367852.02      6914786.57
      1367803.81      6914834.54      1367660.93      6914840.25
      1367515.83      6914927.68      1367599.90      6915035.71
      1367603.41      6915081.95      1367508.62      6915189.50
      1367501.17      6915286.41      1367362.87      6915584.78
      1367503.38      6915744.03      1367454.59      6915863.00
      1367502.87      6915943.86      1367505.00      6916038.00

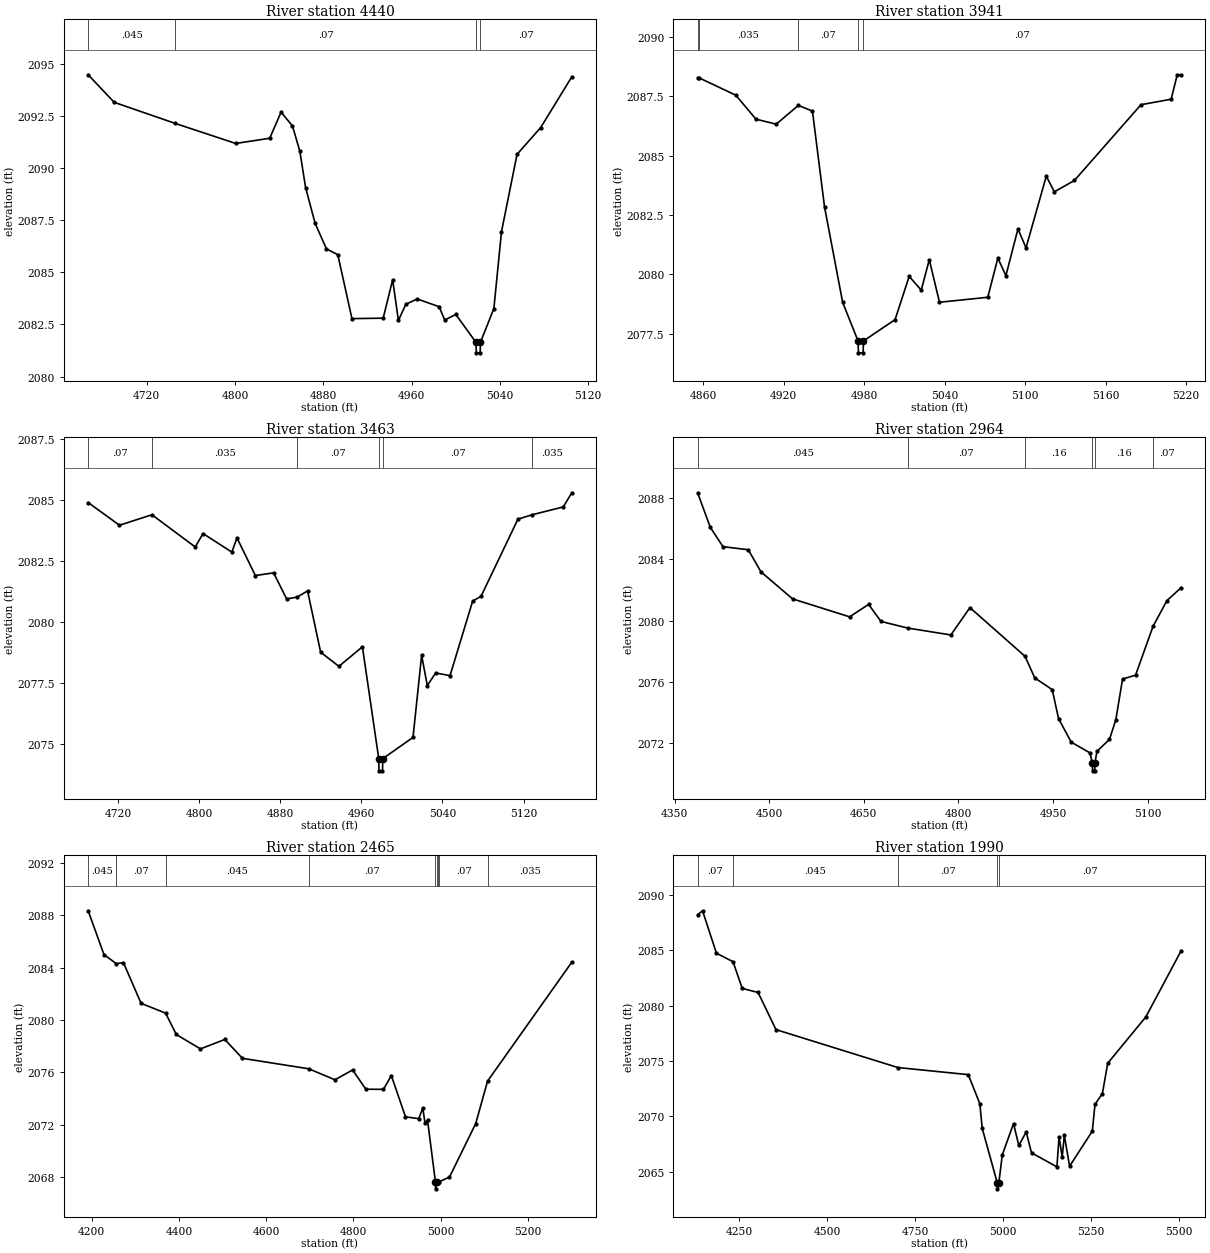
Type RM Length L Ch R = 1,4440,499,499,499
BEGIN DESCRIPTION:
Plum Branch Trib01 6.0
END DESCRIPTION:
XS GIS Cut Line= 3
      1369655.00      6913588.01      1369732.49      6913911.97
      1369805.03      6913988.03
#Sta/Elev= 30
  4666.9 2094.46  4690.5 2093.14  4745.8 2092.13  4800.6 2091.17  4831.4 2091.42
  4841.7 2092.67  4852.0 2092.01  4858.7 2090.80  4863.9 2089.06  4872.5 2087.35
  4882.8 2086.12  4893.1 2085.84  4905.9 2082.78  4934.2 2082.80  4942.8 2084.64
  4948.0 2082.69  4954.8 2083.47  4965.1 2083.72  4984.9 2083.35  4990.0 2082.71
  5000.0 2082.98  5018.3 2081.64  5018.6 2081.14  5022.1 2081.14  5022.3 2081.64
  5034.5 2083.26  5041.4 2086.94  5055.5 2090.65  5076.9 2091.93  5105.1 2094.36
#Mann=4,-1,0
  4666.9   0.045       0  4745.8    0.07       0  5018.3    0.07       0
  5022.3    0.07       0
Bank Sta=5018.3,5022.3
Exp/Cntr=0.3,0.1

Type RM Length L Ch R = 1,3941,478,478,478
BEGIN DESCRIPTION:
Plum Branch Trib01 5.0
END DESCRIPTION:
XS GIS Cut Line= 3
      1369205.02      6913938.03      1369284.97      6914057.92
      1369404.99      6914237.98
#Sta/Elev= 30
  4855.9 2088.28  4856.6 2088.28  4884.4 2087.54  4899.4 2086.53  4914.5 2086.32
  4931.0 2087.11  4941.5 2086.87  4950.5 2082.84  4964.0 2078.82  4975.5 2077.19
  4975.8 2076.69  4979.3 2076.69  4979.5 2077.19  5003.1 2078.09  5013.6 2079.91
  5022.6 2079.33  5028.6 2080.61  5036.2 2078.82  5072.2 2079.03  5079.7 2080.68
  5085.7 2079.94  5094.7 2081.91  5100.7 2081.11  5115.8 2084.13  5121.8 2083.47
  5136.8 2083.95  5186.4 2087.14  5208.9 2087.37  5213.4 2088.40  5216.4 2088.40
#Mann=5,-1,0
  4855.9    0.07       0  4856.6   0.035       0  4931.0    0.07       0
  4975.5    0.07       0  4979.5    0.07       0
Bank Sta=4975.5,4979.5
Exp/Cntr=0.3,0.1

Type RM Length L Ch R = 1,3463,499,499,499
BEGIN DESCRIPTION:
Plum Branch Trib01 4.0
END DESCRIPTION:
XS GIS Cut Line= 3
      1368954.99      6913938.05      1368879.92      6914238.20
      1368955.02      6914388.03
#Sta/Elev= 30
  4690.6 2084.88  4721.5 2083.95  4753.5 2084.38  4796.2 2083.06  4803.9 2083.61
  4832.3 2082.85  4837.4 2083.43  4855.5 2081.89  4873.5 2082.00  4886.4 2080.93
  4896.8 2081.01  4907.0 2081.26  4919.9 2078.75  4937.9 2078.17  4961.1 2078.97
  4977.2 2074.39  4977.4 2073.89  4980.9 2073.89  4981.2 2074.39  5011.0 2075.26
  5019.5 2078.62  5025.1 2077.38  5033.3 2077.90  5047.5 2077.79  5069.8 2080.84
  5078.1 2081.04  5114.5 2084.20  5128.5 2084.38  5159.2 2084.70  5167.6 2085.28
#Mann=6,-1,0
  4690.6    0.07       0  4753.5   0.035       0  4896.8    0.07       0
  4977.2    0.07       0  4981.2    0.07       0  5128.5   0.035       0
Bank Sta=4977.2,4981.2
Exp/Cntr=0.3,0.1

Type RM Length L Ch R = 1,2964,499,499,499
BEGIN DESCRIPTION:
Plum Branch Trib01 3.0
END DESCRIPTION:
XS GIS Cut Line= 3
      1368505.00      6913837.99      1368556.90      6914449.19
      1368705.00      6914488.00
#Sta/Elev= 30
  4386.6 2088.32  4406.7 2086.07  4426.8 2084.81  4466.9 2084.61  4487.0 2083.17
  4537.1 2081.41  4627.5 2080.24  4657.6 2081.05  4677.3 2079.94  4719.5 2079.51
  4788.0 2079.06  4818.2 2080.84  4905.5 2077.67  4921.0 2076.26  4948.6 2075.50
  4958.7 2073.61  4978.7 2072.08  5008.4 2071.38  5012.3 2070.71  5012.5 2070.21
  5016.0 2070.21  5016.3 2070.71  5019.5 2071.48  5039.4 2072.26  5049.5 2073.55
  5060.1 2076.19  5080.7 2076.44  5108.4 2079.62  5130.3 2081.29  5153.1 2082.15
#Mann=6,-1,0
  4386.6   0.045       0  4719.5    0.07       0  4905.5    0.16       0
  5012.3    0.07       0  5016.3    0.16       0  5108.4    0.07       0
Bank Sta=5012.3,5016.3
Exp/Cntr=0.3,0.1

Type RM Length L Ch R = 1,2465,475,475,475
BEGIN DESCRIPTION:
Plum Branch Trib01 2.0
END DESCRIPTION:
XS GIS Cut Line= 3
      1368255.01      6913837.96      1368144.95      6914638.12
      1368155.00      6914937.96
#Sta/Elev= 30
  4192.3 2088.34  4228.4 2085.00  4256.7 2084.30  4273.1 2084.38  4313.5 2081.27
  4369.7 2080.52  4394.2 2078.89  4449.5 2077.79  4505.3 2078.51  4545.6 2077.07
  4697.6 2076.27  4757.6 2075.43  4798.0 2076.18  4828.3 2074.71  4868.7 2074.70
  4886.7 2075.75  4919.1 2072.60  4949.4 2072.46  4958.7 2073.26  4963.8 2072.14
  4969.6 2072.34  4987.8 2067.60  4988.0 2067.10  4991.8 2067.60  4992.9 2067.61
  4996.9 2067.65  5019.9 2068.00  5079.9 2072.08  5107.1 2075.33  5300.0 2084.41
#Mann=9,-1,0
  4192.3   0.045       0  4256.7    0.07       0  4369.7   0.045       0
  4697.6    0.07       0  4987.8    0.07       0  4991.8    0.07       0
  4992.9    0.16       0  4996.9    0.07       0  5107.1   0.035       0
Bank Sta=4987.8,4991.8
Exp/Cntr=0.3,0.1

Type RM Length L Ch R = 1,1990,638,638,638
BEGIN DESCRIPTION:
Plum Branch Trib01 1.0
END DESCRIPTION:
XS GIS Cut Line= 3
      1368154.99      6913788.02      1367774.41      6914567.48
      1368054.98      6914987.97
#Sta/Elev= 30
  4132.6 2088.19  4146.6 2088.55  4186.1 2084.72  4233.1 2083.96  4259.2 2081.55
  4304.3 2081.18  4355.1 2077.83  4701.3 2074.41  4901.0 2073.77  4933.8 2071.14
  4940.5 2068.93  4983.6 2063.97  4983.8 2063.47  4987.6 2063.97  4997.5 2066.53
  5029.4 2069.36  5044.4 2067.38  5065.4 2068.60  5080.5 2066.72  5152.6 2065.45
  5158.6 2068.17  5167.6 2066.34  5173.6 2068.30  5188.6 2065.51  5253.1 2068.68
  5260.7 2071.10  5281.7 2072.06  5296.8 2074.80  5404.9 2078.97  5505.5 2084.96
#Mann=5,-1,0
  4132.6    0.07       0  4233.1   0.045       0  4701.3    0.07       0
  4983.6    0.07       0  4987.6    0.07       0
Bank Sta=4983.6,4987.6
Exp/Cntr=0.3,0.1

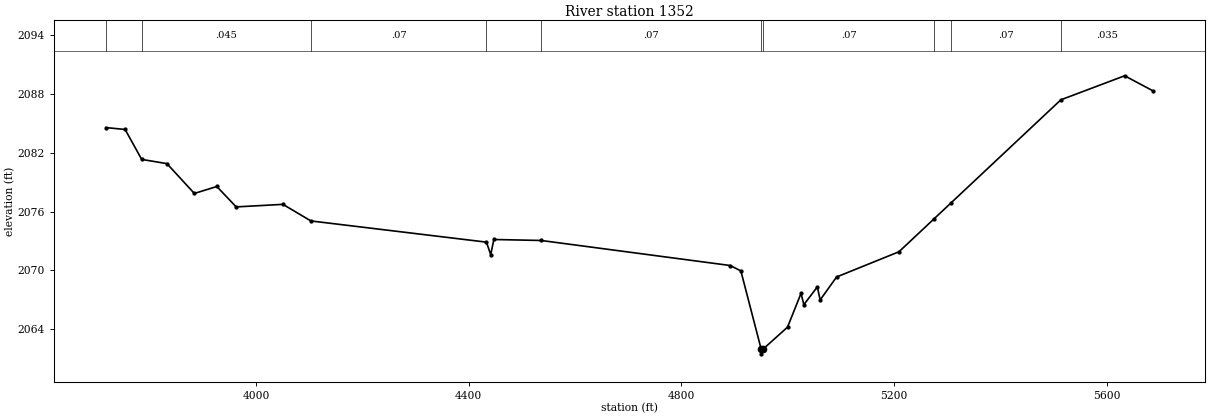
Type RM Length L Ch R = 1,1352,0,0,0
BEGIN DESCRIPTION:
Plum Branch Trib01 0.5
END DESCRIPTION:
XS GIS Cut Line= 4
      1368050.79      6913795.20      1367499.59      6914658.90
      1367521.29      6914897.62      1368185.38      6915136.35
#Sta/Elev= 30
  3717.5 2084.55  3753.3 2084.36  3784.5 2081.31  3832.0 2080.88  3883.6 2077.84
  3925.9 2078.55  3962.3 2076.47  4050.3 2076.73  4102.9 2075.04  4433.2 2072.88
  4441.2 2071.61  4447.2 2073.15  4536.1 2073.05  4891.8 2070.50  4911.9 2069.95
  4950.0 2062.00  4950.3 2061.50  4954.1 2062.00  4999.7 2064.22  5025.1 2067.66
  5030.4 2066.51  5055.8 2068.32  5061.1 2066.99  5092.0 2069.33  5209.4 2071.90
  5275.7 2075.27  5306.6 2076.84  5514.0 2087.38  5634.0 2089.83  5687.5 2088.29
#Mann=10,-1,0
  3717.5    0.07       0  3784.5   0.045       0  4102.9    0.07       0
  4433.2   0.045       0  4536.1    0.07       0  4950.0    0.07       0
  4954.1    0.07       0  5275.7   0.035       0  5306.6    0.07       0
  5514.0   0.035       0
Bank Sta=4950,4954.1
Exp/Cntr=0.3,0.1

Chan Stop Cuts=-1