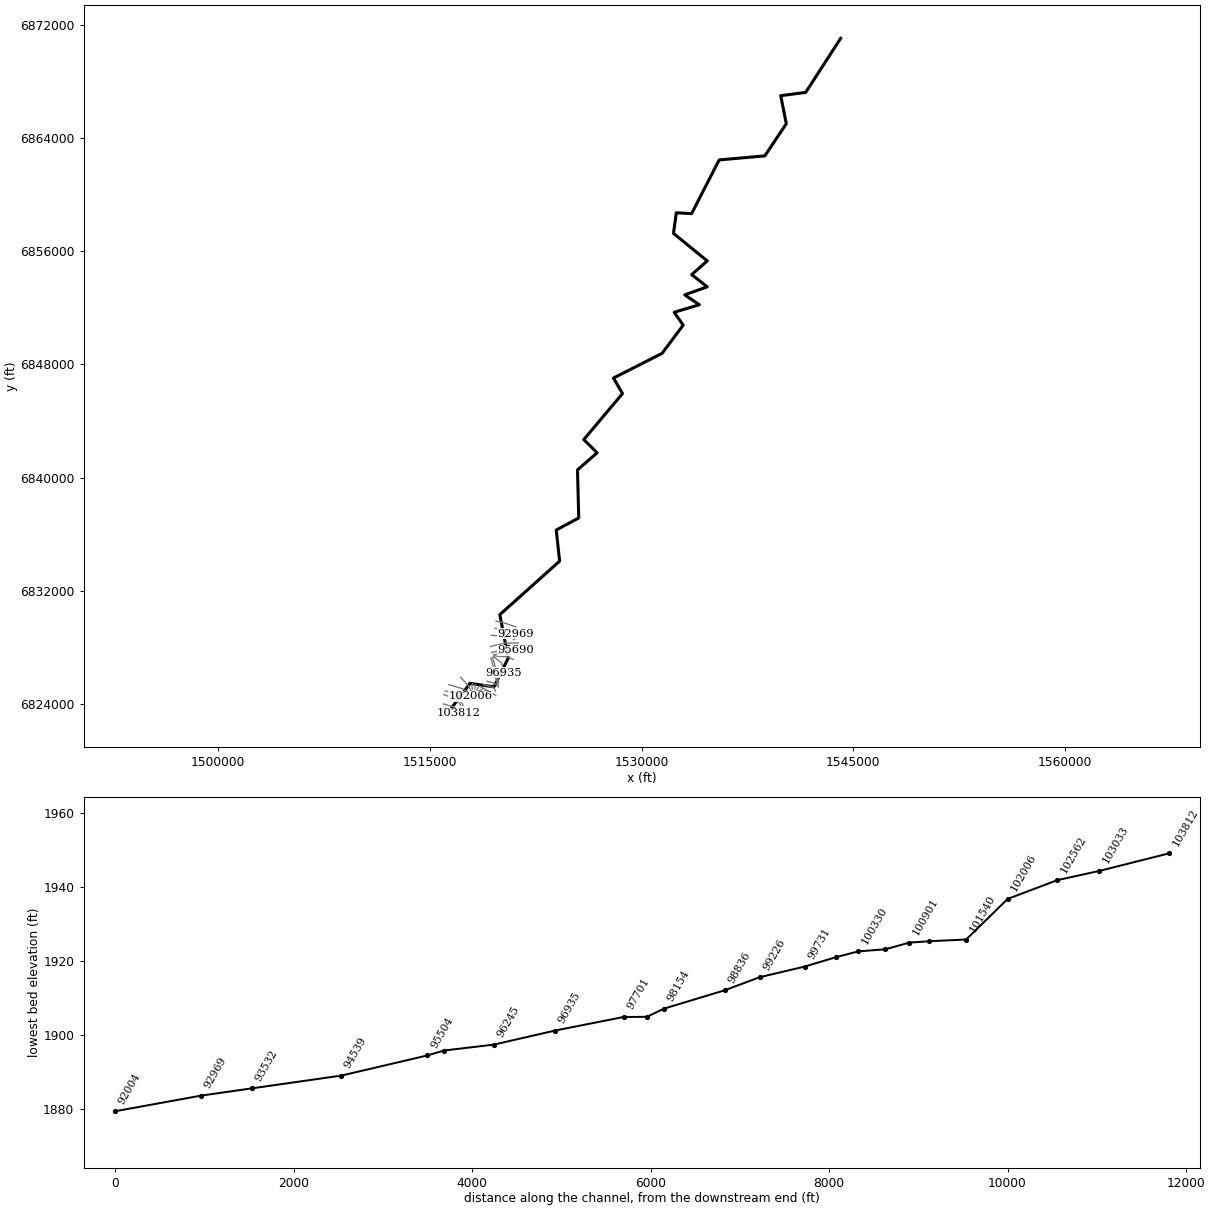
--- BULL WAGON CREEK.prj (project) ---

Proj Title=BULL WAGON CREEK Base Level Engineering
Current Plan=p01
Default Exp/Contr=0.3,0.1
English Units
Geom File=g01
Flow File=f01
Plan File=p01
Y Axis Title=Elevation
X Axis Title(PF)=Main Channel Distance
X Axis Title(XS)=Station
BEGIN DESCRIPTION:
BULL WAGON CREEK
END DESCRIPTION:
DSS Export Rating Curves= 0
DSS Export Rating Curve Sorted= 0
DSS Export Volume Flow Curves= 0
DXF OffsetX= 0
DXF OffsetY= 0
DXF ScaleX= 1
DXF ScaleY= 10

--- BULL WAGON CREEK.p01 (plan) ---

Plan Title=Multiple Run
Short Identifier=Multiple
Geom File=g01
Flow File=f01
Subcritical Flow
K Sum by GR= 0
Std Step Tol= 0.01
Critical Tol= 0.01
Num of Std Step Trials= 20
Max Error Tol= 0.3
Flow Tol Ratio= 0.001
Split Flow NTrial= 30
Split Flow Tol= 0.02
Split Flow Ratio= 0.02
Log Output Level= 0
Friction Slope Method= 1
Unsteady Friction Slope Method= 2
Unsteady Bridges Friction Slope Method= 1
Parabolic Critical Depth
Global Vel Dist=  1 , 1 , 1
Global Log Level= 0
CheckData=True
Encroach Param= -1, 0, 0, 0
BEGIN DESCRIPTION:
Multiple Run
END DESCRIPTION:

--- BULL WAGON CREEK.f01 (steady flow) ---

Flow Title=Multiple
Program Version=4.10
Number of Profiles= 7
Profile Names=10-year,25-year,50-year,1pct_min,100-year,1pct_plu,500-year
River Rch & RM=BULL WAGON CREEK,Reach-1         ,103812
     360     524     668     424     847    1690    1380
River Rch & RM=BULL WAGON CREEK,Reach-1         ,100901
     562     837    1081     696    1388    2770    2321
River Rch & RM=BULL WAGON CREEK,Reach-1         ,96245
     896    1355    1769    1148    2291    4571    3897
River Rch & RM=BULL WAGON CREEK,Reach-1         ,92004
     862    1294    1679    1083    2161    4312    3630
River Rch & RM=BULL WAGON CREEK,Reach-1         ,84552
    1152    1746    2280    1479    2950    5887    5010
River Rch & RM=BULL WAGON CREEK,Reach-1         ,82023
    1342    2038    2668    1732    3455    6894    5881
River Rch & RM=BULL WAGON CREEK,Reach-1         ,69953
    1464    2224    2911    1889    3769    7519    6407
River Rch & RM=BULL WAGON CREEK,Reach-1         ,62654
    1483    2251    2944    1909    3808    7598    6463
River Rch & RM=BULL WAGON CREEK,Reach-1         ,57523
    1540    2338    3057    1982    3954    7889    6708
River Rch & RM=BULL WAGON CREEK,Reach-1         ,54253
    1571    2384    3116    2018    4027    8036    6826
River Rch & RM=BULL WAGON CREEK,Reach-1         ,49402
    1903    2906    3815    2482    4952    9880    8458
River Rch & RM=BULL WAGON CREEK,Reach-1         ,46980
    1971    3012    3958    2575    5139   10253    8787
River Rch & RM=BULL WAGON CREEK,Reach-1         ,45129
    1991    3040    3992    2596    5180   10336    8847
River Rch & RM=BULL WAGON CREEK,Reach-1         ,41815
    2024    3088    4052    2633    5254   10483    8959
River Rch & RM=BULL WAGON CREEK,Reach-1         ,36334
    2017    3070    4022    2609    5206   10387    8845
River Rch & RM=BULL WAGON CREEK,Reach-1         ,29116
    2054    3127    4097    2658    5304   10584    9014
River Rch & RM=BULL WAGON CREEK,Reach-1         ,26898
    2072    3152    4127    2676    5339   10652    9059
River Rch & RM=BULL WAGON CREEK,Reach-1         ,22601
    2064    3137    4104    2659    5305   10584    8986
River Rch & RM=BULL WAGON CREEK,Reach-1         ,18712
    2055    3118    4077    2639    5265   10505    8904
River Rch & RM=BULL WAGON CREEK,Reach-1         ,13610
    2102    3192    4175    2703    5394   10762    9128
River Rch & RM=BULL WAGON CREEK,Reach-1         ,12661
    2208    3356    4392    2845    5677   11327    9618
River Rch & RM=BULL WAGON CREEK,Reach-1         ,9317
    2255    3428    4487    2907    5800   11572    9827
River Rch & RM=BULL WAGON CREEK,Reach-1         ,7185
    2254    3424    4480    2901    5787   11547    9794
River Rch & RM=BULL WAGON CREEK,Reach-1         ,1718
    2274    3455    4520    2926    5838   11649    9878
Boundary for River Rch & Prof#=BULL WAGON CREEK,Reach-1         , 1
Up Type= 0
Dn Type= 3
Dn Slope=0.0019
Boundary for River Rch & Prof#=BULL WAGON CREEK,Reach-1         , 2
Up Type= 0
Dn Type= 3
Dn Slope=0.0019
Boundary for River Rch & Prof#=BULL WAGON CREEK,Reach-1         , 3
Up Type= 0
Dn Type= 3
Dn Slope=0.0019
Boundary for River Rch & Prof#=BULL WAGON CREEK,Reach-1         , 4
Up Type= 0
Dn Type= 3
Dn Slope=0.0019
Boundary for River Rch & Prof#=BULL WAGON CREEK,Reach-1         , 5
Up Type= 0
Dn Type= 3
Dn Slope=0.0019
Boundary for River Rch & Prof#=BULL WAGON CREEK,Reach-1         , 6
Up Type= 0
Dn Type= 3
Dn Slope=0.0019
Boundary for River Rch & Prof#=BULL WAGON CREEK,Reach-1         , 7
Up Type= 0
Dn Type= 3
Dn Slope=0.0019
DSS Import GetInterval= 0
DSS Import GetPeak= 0
DSS Import FillOption= 0

--- BULL WAGON CREEK.g01 (geometry) ---

Geom Title=Existing Conditions
Program Version=4.10

River Reach=BULL WAGON CREEK,Reach-1
Reach XY= 30
        1516505.        6823638.       1517852.7      6825432.94
      1519544.05      6825177.98      1520555.36       6827212.8
      1519960.68      6830290.39      1524196.23      6834081.15
      1523956.78      6836281.87      1525549.94       6837135.7
      1525462.77      6840541.41      1526854.24      6841748.69
      1525908.37      6842686.26      1528653.03      6845943.67
      1528010.28      6847040.71        1531455.        6848788.
      1532947.52      6850784.43      1532315.18       6851697.7
      1534096.11      6852231.49       1533056.2       6852927.5
      1534652.06      6853496.56      1533554.49      6854362.96
      1534653.38      6855331.96      1532262.67      6857281.47
      1532460.68      6858740.52      1533544.82      6858678.29
      1535498.92      6862480.53      1538735.79      6862768.06
      1540253.56      6865044.43      1539857.93      6867030.03
      1541628.47      6867261.01        1544105.        6871088.

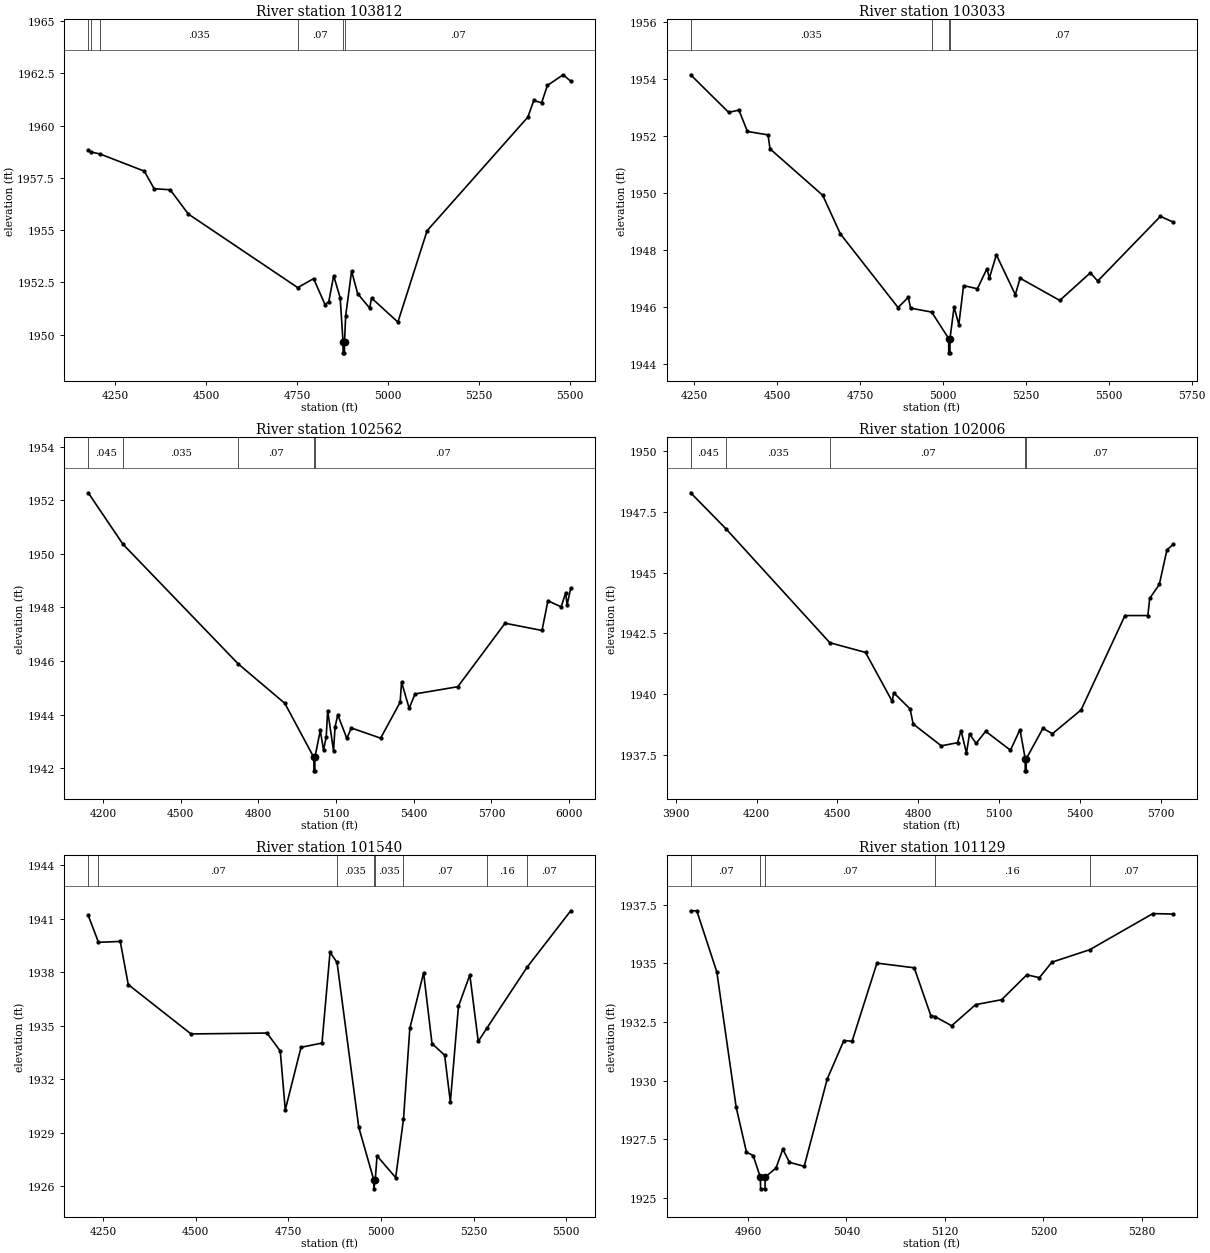
Type RM Length L Ch R = 1 ,103812  ,779,779,779
BEGIN DESCRIPTION:
BULL WAGON CREEK 94.0
END DESCRIPTION:
XS GIS Cut Line= 3
      1515961.39      6823977.28        1516755.        6823738.
      1516999.62      6823303.65
#Sta/Elev= 30
  4175.4 1958.81  4182.7 1958.74  4208.2 1958.64  4329.7 1957.82  4356.7 1956.98
  4400.9 1956.93  4450.7 1955.77  4751.7 1952.25  4795.4 1952.68  4826.7 1951.44
  4837.2 1951.58  4850.6 1952.82  4868.5 1951.76  4876.4 1949.63  4876.6 1949.13
  4880.1 1949.13  4880.4 1949.63  4883.6  1950.9  4899.9 1953.04  4916.6 1951.96
  4949.6 1951.27  4954.8 1951.75  5027.3  1950.6  5107.6 1954.97    5385 1960.41
    5401  1961.2  5422.6 1961.09  5438.6 1961.92  5481.9 1962.43  5502.8 1962.12
#Mann= 6 ,-1 , 0
  4175.4    .035       0  4182.7     .07       0  4208.2    .035       0
  4751.7     .07       0  4876.4     .07       0  4880.4     .07       0
Bank Sta=4876.4,4880.4
XS Rating Curve= 0 ,0
Exp/Cntr=0.3,0.1

Type RM Length L Ch R = 1 ,103033  ,471,471,471
BEGIN DESCRIPTION:
Mapping XS 5332e6e8
END DESCRIPTION:
XS GIS Cut Line= 4
      1515989.16      6824630.06        1516701.      6824380.05
      1517096.83      6824046.71      1517180.08      6823883.69
#Sta/Elev= 30
  4239.2 1954.16  4353.9 1952.84  4384.8 1952.92  4410.5 1952.17  4472.5 1952.05
  4478.6 1951.56  4637.5 1949.93  4690.5 1948.58  4864.7 1945.99  4895.7 1946.35
  4902.5 1945.97  4966.1 1945.83  5017.3  1944.9  5017.6  1944.4  5021.1  1944.4
  5021.3  1944.9  5033.6 1946.01  5047.9 1945.39  5062.2 1946.76  5103.9 1946.65
  5132.5 1947.35  5140.2 1947.03  5161.1 1947.84  5218.3 1946.44  5232.6 1947.02
  5352.3 1946.24  5444.6 1947.21  5466.7 1946.92  5655.7 1949.19  5694.2 1948.99
#Mann= 4 ,-1 , 0
  4239.2    .035       0  4966.1     .07       0  5017.3     .07       0
  5021.3     .07       0
Bank Sta=5017.3,5021.3
XS Rating Curve= 0 ,0
Exp/Cntr=0.3,0.1

Type RM Length L Ch R = 1 ,102562  ,556,556,556
BEGIN DESCRIPTION:
BULL WAGON CREEK 93.0
END DESCRIPTION:
XS GIS Cut Line= 3
      1516082.98      6824883.51      1516931.62      6824764.82
      1517357.07      6823852.66
#Sta/Elev= 30
  4143.1 1952.28  4277.2 1950.36  4722.6 1945.89  4902.4 1944.42  5014.4  1942.4
  5014.7  1941.9  5018.2  1941.9  5018.4  1942.4  5039.3 1943.41  5051.7 1942.67
  5062.2 1943.17  5067.7 1944.15  5090.5 1942.64  5096.1 1943.53  5106.8 1943.99
  5141.8 1943.11  5159.1  1943.5  5272.3 1943.12  5347.6 1944.46  5353.1 1945.21
  5382.7 1944.23  5404.8 1944.77  5570.3 1945.04  5752.8 1947.41  5895.5 1947.14
  5918.3 1948.25  5969.6 1948.02  5986.9 1948.55  5992.4 1948.09  6006.5 1948.73
#Mann= 5 ,-1 , 0
  4143.1    .045       0  4277.2    .035       0  4722.6     .07       0
  5014.4     .07       0  5018.4     .07       0
Bank Sta=5014.4,5018.4
XS Rating Curve= 0 ,0
Exp/Cntr=0.3,0.1

Type RM Length L Ch R = 1 ,102006  ,466,466,466
BEGIN DESCRIPTION:
BULL WAGON CREEK 92.0
END DESCRIPTION:
XS GIS Cut Line= 3
      1516355.01        6825338.        1517355.        6825038.
      1517874.64      6824505.02
#Sta/Elev= 30
  3955.8 1948.29  4087.2  1946.8  4471.7 1942.11    4604 1941.71  4703.1 1939.69
  4708.4 1940.05  4769.3 1939.38  4780.6 1938.76    4885 1937.86    4945 1937.99
  4958.1 1938.49  4978.1 1937.56  4989.4 1938.35  5013.9 1937.96  5049.3 1938.46
  5141.2 1937.68  5176.6 1938.53  5195.8 1937.33    5196 1936.83  5199.5 1936.83
  5199.8 1937.33  5261.5 1938.58  5296.8 1938.36    5403 1939.34  5565.6 1943.23
  5650.4 1943.23  5657.4 1943.94  5692.9 1944.51  5721.2 1945.94  5744.2 1946.16
#Mann= 5 ,-1 , 0
  3955.8    .045       0  4087.2    .035       0  4471.7     .07       0
  5195.8     .07       0  5199.8     .07       0
Bank Sta=5195.8,5199.8
XS Rating Curve= 0 ,0
Exp/Cntr=0.3,0.1

Type RM Length L Ch R = 1 ,101540  ,411,411,411
BEGIN DESCRIPTION:
BULL WAGON CREEK 91.0
END DESCRIPTION:
XS GIS Cut Line= 3
      1517174.27      6825869.72      1517716.96      6825279.82
      1517954.99      6824838.02
#Sta/Elev= 30
  4209.3 1941.19    4237 1939.68  4295.8 1939.73  4317.4 1937.31  4486.9 1934.54
  4692.2 1934.59    4728 1933.58  4741.6 1930.28  4784.1 1933.79  4840.8 1934.03
  4862.4 1939.12  4881.4 1938.55  4940.1  1929.3  4980.6 1926.35  4980.8 1925.85
  4984.6 1926.35  4989.4  1927.7  5039.8 1926.48  5060.9 1929.76    5078 1934.85
  5115.2 1937.97  5137.9    1934    5172 1933.35  5187.5 1930.72  5209.4 1936.09
  5240.1 1937.85  5262.8 1934.12  5286.9 1934.89  5394.6 1938.28  5512.7 1941.45
#Mann= 8 ,-1 , 0
  4209.3    .035       0    4237     .07       0  4881.4    .035       0
  4980.6    .035       0  4984.6    .035       0  5060.9     .07       0
  5286.9     .16       0  5394.6     .07       0
Bank Sta=4980.6,4984.6
XS Rating Curve= 0 ,0
Exp/Cntr=0.3,0.1

Type RM Length L Ch R = 1 ,101129  ,228,228,228
BEGIN DESCRIPTION:
Mapping XS 4b90b977
END DESCRIPTION:
XS GIS Cut Line= 4
       1518038.2      6825422.29      1518004.82      6825340.11
      1517983.99      6825194.28      1518017.57      6825041.85
#Sta/Elev= 30
  4913.4 1937.24  4918.4 1937.24  4934.7 1934.63  4950.4 1928.87  4958.8 1926.95
  4964.2 1926.81    4970 1925.89  4970.3 1925.39  4973.8 1925.39    4974 1925.89
  4982.8 1926.28  4988.3 1927.08  4993.7 1926.52  5005.7 1926.35  5024.4 1930.07
  5037.9 1931.71  5044.6 1931.68  5064.8 1935.01  5095.1 1934.81  5108.6 1932.77
    5112 1932.73  5125.5 1932.34    5145 1933.24  5166.1 1933.45  5186.6 1934.51
  5196.8 1934.39    5207 1935.05  5237.7 1935.58    5289 1937.12  5305.5  1937.1
#Mann= 5 ,-1 , 0
  4913.4     .07       0    4970     .07       0    4974     .07       0
    5112     .16       0  5237.7     .07       0
Bank Sta=4970,4974
XS Rating Curve= 0 ,0
Exp/Cntr=0.3,0.1

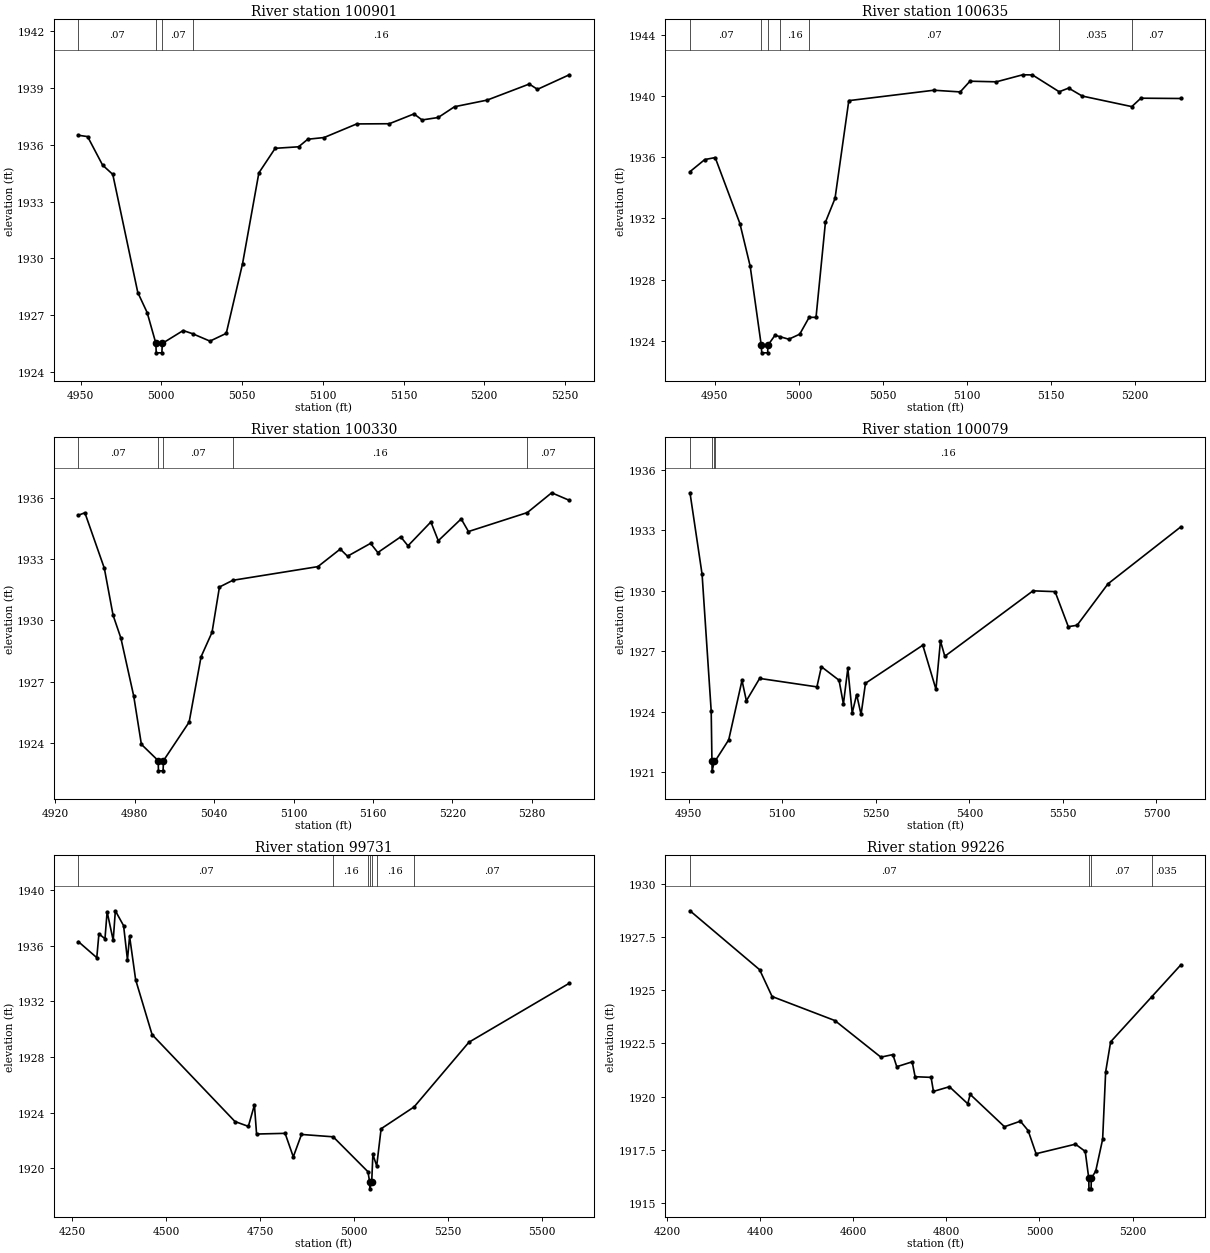
Type RM Length L Ch R = 1 ,100901  ,266,266,266
BEGIN DESCRIPTION:
Mapping XS 81b19c78
END DESCRIPTION:
XS GIS Cut Line= 3
      1518241.13      6825320.87      1518210.55       6825269.8
      1518176.69      6825027.58
#Sta/Elev= 30
  4948.6 1936.51  4954.3 1936.44  4963.6 1934.93  4969.9 1934.44  4985.4 1928.19
  4991.2 1927.13  4996.6  1925.5  4996.8    1925  5000.3    1925  5000.6  1925.5
  5013.5 1926.18  5019.4 1926.01  5030.1 1925.62  5040.2 1926.03  5050.3 1929.72
  5060.4 1934.52  5070.5 1935.82    5085  1935.9  5090.7  1936.3  5100.8 1936.39
    5121 1937.11  5141.2 1937.12  5156.5 1937.64  5161.5 1937.32  5171.5 1937.45
  5181.6 1938.02  5201.8 1938.37  5227.9 1939.22    5233 1938.94  5252.7 1939.71
#Mann= 4 ,-1 , 0
  4948.6     .07       0  4996.6     .07       0  5000.6     .07       0
  5019.4     .16       0
Bank Sta=4996.6,5000.6
XS Rating Curve= 0 ,0
Exp/Cntr=0.3,0.1

Type RM Length L Ch R = 1 ,100635  ,305,305,305
BEGIN DESCRIPTION:
Mapping XS a4d1797f
END DESCRIPTION:
XS GIS Cut Line= 3
      1518478.34      6825205.71      1518434.51       6825144.8
      1518325.14      6824957.31
#Sta/Elev= 30
  4935.3 1935.05  4944.1 1935.84  4950.3 1935.97    4965 1931.66  4971.1 1928.88
  4977.7 1923.71    4978 1923.21  4981.5 1923.21  4981.7 1923.71  4985.9 1924.36
    4989 1924.26  4994.1  1924.1  5000.6 1924.43  5006.2 1925.53  5010.3 1925.53
  5015.9 1931.75  5021.6  1933.3  5029.8 1939.69  5080.4 1940.37  5096.1 1940.26
  5101.9 1940.96  5117.6 1940.92  5133.3 1941.38  5139.1 1941.37    5155 1940.27
  5160.6 1940.51  5168.7 1939.99  5198.2  1939.3  5203.6 1939.85  5227.4 1939.83
#Mann= 7 ,-1 , 0
  4935.3     .07       0  4977.7     .07       0  4981.7     .07       0
    4989     .16       0  5006.2     .07       0    5155    .035       0
  5198.2     .07       0
Bank Sta=4977.7,4981.7
XS Rating Curve= 0 ,0
Exp/Cntr=0.3,0.1

Type RM Length L Ch R = 1 ,100330  ,251,251,251
BEGIN DESCRIPTION:
Mapping XS d34debeb
END DESCRIPTION:
XS GIS Cut Line= 3
      1518723.94      6825054.79      1518690.87      6824999.84
      1518412.92       6824869.8
#Sta/Elev= 30
  4937.4 1935.16  4942.3 1935.28    4957 1932.56  4963.6 1930.26  4969.5 1929.14
  4979.2  1926.3    4985 1923.93  4997.7 1923.13  4997.9 1922.63  5001.4 1922.63
  5001.7 1923.13  5021.1 1925.02  5030.1 1928.22  5038.4 1929.42    5044 1931.64
  5054.1 1931.97  5118.4 1932.64  5135.3  1933.5  5140.8 1933.15  5158.2 1933.78
  5163.7 1933.33    5181  1934.1  5186.5 1933.66  5203.8 1934.83  5209.4 1933.91
  5226.7 1934.98  5232.2 1934.36  5276.7 1935.29  5295.1 1936.26  5308.4 1935.89
#Mann= 5 ,-1 , 0
  4937.4     .07       0  4997.7     .07       0  5001.7     .07       0
  5054.1     .16       0  5276.7     .07       0
Bank Sta=4997.7,5001.7
XS Rating Curve= 0 ,0
Exp/Cntr=0.3,0.1

Type RM Length L Ch R = 1 ,100079  ,348,348,348
BEGIN DESCRIPTION:
Mapping XS c046702d
END DESCRIPTION:
XS GIS Cut Line= 3
      1518931.29      6824929.02      1518907.89      6824897.84
      1518375.54      6824372.22
#Sta/Elev= 30
  4952.1 1934.87  4971.5 1930.82  4986.1 1924.03  4987.3 1921.56  4987.6 1921.06
  4991.3 1921.56  4992.7 1921.56  5014.2  1922.6  5035.5 1925.55  5042.5 1924.54
  5063.8 1925.65  5155.6 1925.23  5162.8 1926.23  5191.1 1925.56  5198.1 1924.38
  5205.2 1926.15  5212.2 1923.93  5219.3 1924.85  5226.4 1923.86  5233.5 1925.41
  5325.4  1927.3  5346.5 1925.11  5353.7 1927.51  5360.7 1926.75  5502.1    1930
  5537.5 1929.96  5558.7 1928.22  5572.8 1928.29  5622.4 1930.35  5739.2 1933.18
#Mann= 4 ,-1 , 0
  4952.1     .07       0  4987.3     .07       0  4991.3     .07       0
  4992.7     .16       0
Bank Sta=4987.3,4991.3
XS Rating Curve= 0 ,0
Exp/Cntr=0.3,0.1

Type RM Length L Ch R = 1 ,99731   ,505,505,505
BEGIN DESCRIPTION:
Mapping XS 850bba03
END DESCRIPTION:
XS GIS Cut Line= 3
      1518539.48      6825217.77      1519184.25      6824865.43
      1519675.99      6824574.92
#Sta/Elev= 30
  4266.8  1936.3  4315.7 1935.15  4321.4 1936.86  4337.5 1936.51  4343.2 1938.45
  4359.4 1936.39  4365.1 1938.52    4387 1937.45  4397.3    1935    4403 1936.68
  4419.1 1933.56  4462.8 1929.62  4683.3 1923.37  4718.9 1923.02  4735.1 1924.56
  4740.8 1922.47  4816.7 1922.52  4838.5 1920.83  4860.3 1922.44  4944.6 1922.27
  5037.1 1919.76  5041.6 1919.03  5042.1 1918.53  5047.1 1919.03  5050.2    1921
  5060.4 1920.18  5072.1 1922.85  5159.9 1924.42  5305.7 1929.07  5572.7 1933.31
#Mann= 7 ,-1 , 0
  4266.8     .07       0  4944.6     .16       0  5037.1     .07       0
  5041.6     .07       0  5047.1     .07       0  5060.4     .16       0
  5159.9     .07       0
Bank Sta=5041.6,5047.1
XS Rating Curve= 0 ,0
Exp/Cntr=0.3,0.1

Type RM Length L Ch R = 1 ,99226   ,390,390,390
BEGIN DESCRIPTION:
Mapping XS a4fb28b0
END DESCRIPTION:
XS GIS Cut Line= 4
      1518785.03      6825342.85      1519502.94      6825143.28
      1519581.07      6825058.65      1519650.27        6824877.
#Sta/Elev= 30
  4249.1 1928.73  4398.7 1925.96  4425.5  1924.7  4560.4 1923.57  4659.2 1921.85
    4685 1921.97  4693.4  1921.4  4726.5 1921.63  4732.8 1920.93  4767.1  1920.9
  4772.2 1920.24  4806.5 1920.46  4845.9 1919.66  4851.1  1920.1  4924.8 1918.58
    4959 1918.84  4975.6  1918.4  4992.7 1917.31  5077.3 1917.76  5098.3 1917.42
  5105.9 1916.16  5106.3 1915.66  5110.9 1915.66  5111.4 1916.16  5120.8 1916.49
  5135.7 1917.99  5142.2 1921.16  5152.9 1922.57  5241.3 1924.69  5303.8 1926.19
#Mann= 4 ,-1 , 0
  4249.1     .07       0  5105.9     .07       0  5111.4     .07       0
  5241.3    .035       0
Bank Sta=5105.9,5111.4
XS Rating Curve= 0 ,0
Exp/Cntr=0.3,0.1

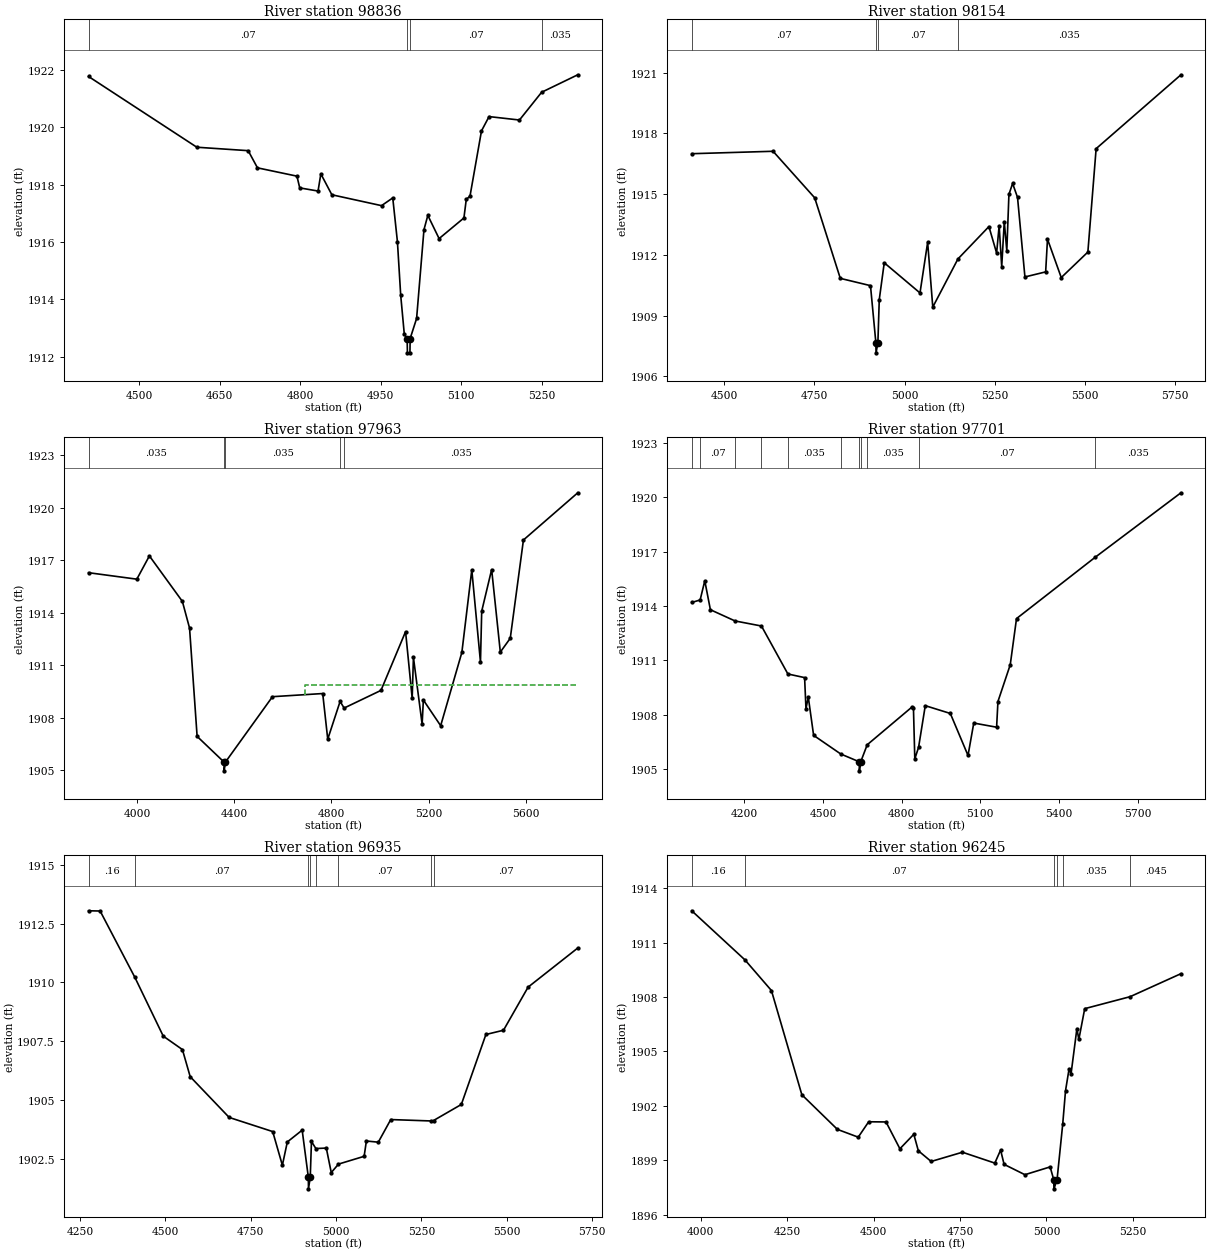
Type RM Length L Ch R = 1 ,98836   ,682,682,682
BEGIN DESCRIPTION:
Mapping XS 70573959
END DESCRIPTION:
XS GIS Cut Line= 4
      1519048.77      6825578.11      1519548.51      6825438.42
      1519693.91      6825336.43      1519843.33      6825182.68
#Sta/Elev= 30
  4405.9 1921.78  4607.5 1919.31  4703.1 1919.19  4720.4 1918.59  4793.9  1918.3
  4799.1 1917.89  4833.2 1917.78  4838.4 1918.38  4858.9 1917.65  4951.4 1917.27
  4972.3 1917.54    4981 1916.01  4987.1 1914.14  4993.8 1912.78  4999.1 1912.63
  4999.6 1912.13  5004.3 1912.13  5004.7 1912.63  5016.7 1913.33  5030.4 1916.43
  5037.6 1916.93  5058.6 1916.12  5104.8 1916.84  5109.2 1917.49  5116.1  1917.6
  5137.5 1919.88  5151.6 1920.38  5208.2 1920.26  5249.5 1921.23  5316.8 1921.84
#Mann= 4 ,-1 , 0
  4405.9     .07       0  4999.1     .07       0  5004.7     .07       0
  5249.5    .035       0
Bank Sta=4999.1,5004.7
XS Rating Curve= 0 ,0
Exp/Cntr=0.3,0.1

Type RM Length L Ch R = 1 ,98154   ,191,191,191
BEGIN DESCRIPTION:
Mapping XS cad9330c
END DESCRIPTION:
XS GIS Cut Line= 4
      1518968.61      6826175.42      1519453.03      6825982.69
      1519708.24      6825727.48       1519812.4      6825266.57
#Sta/Elev= 30
  4410.7    1917  4635.9 1917.12  4751.2 1914.82  4822.1 1910.84  4905.7 1910.48
  4920.6 1907.66  4921.1 1907.16  4926.2 1907.66    4930 1909.79  4943.8 1911.61
  5042.8 1910.12    5064 1912.62  5078.2 1909.42  5147.9  1911.8  5233.7  1913.4
    5255 1912.09    5262 1913.44  5269.1 1911.42  5276.2 1913.64  5283.2  1912.2
  5289.1 1914.99  5299.3 1915.53  5312.9 1914.84  5333.4 1910.91  5390.8 1911.16
  5395.9 1912.78    5434 1910.88  5507.7 1912.14  5530.6 1917.25  5765.5  1920.9
#Mann= 4 ,-1 , 0
  4410.7     .07       0  4920.6     .07       0  4926.2     .07       0
  5147.9    .035       0
#XS Ineff= 2 , 0
       0                    5064       0 1912.62
Permanent Ineff=
       F       F
Bank Sta=4920.6,4926.2
XS Rating Curve= 0 ,0
Exp/Cntr=0.3,0.1

Type RM Length L Ch R = 1 ,97963   ,262,262,262
BEGIN DESCRIPTION:
Mapping XS 3b10a16f
END DESCRIPTION:
XS GIS Cut Line= 3
      1519333.23       6827230.1      1519637.92      6826066.03
        1519838.      6825281.32
#Sta/Elev= 30
  3800.6 1916.28  3999.2 1915.91  4050.9 1917.24  4186.6 1914.64  4216.2 1913.11
  4247.3 1906.92  4358.2 1905.45  4358.6 1904.95  4363.8 1905.45  4557.4 1909.19
  4764.1 1909.37  4784.8 1906.76  4835.7 1908.92  4852.2 1908.54  5003.9 1909.55
  5105.1 1912.91  5132.3  1909.1  5137.4 1911.44  5173.2 1907.62  5178.3    1909
  5249.5 1907.53  5336.7 1911.72  5377.6 1916.44  5413.3 1911.17  5418.4 1914.08
  5459.3 1916.46    5495 1911.74  5535.9 1912.53  5590.1 1918.15  5813.7 1920.85
#Mann= 5 ,-1 , 0
  3800.6    .035       0  4358.2    .035       0  4363.8    .035       0
  4835.7     .07       0  4852.2    .035       0
#XS Ineff= 2 , 0
       0                  4691.4       0 1909.86
Permanent Ineff=
       F       F
Bank Sta=4358.2,4363.8
XS Rating Curve= 0 ,0
Exp/Cntr=0.3,0.1

Type RM Length L Ch R = 1 ,97701   ,766,766,766
BEGIN DESCRIPTION:
Mapping XS 66733c88
END DESCRIPTION:
XS GIS Cut Line= 3
      1519455.63      6827266.57      1519716.05      6826318.63
      1519882.56      6825452.24
#Sta/Elev= 30
  3999.8  1914.2  4031.8 1914.34  4049.5  1915.4  4070.9  1913.8  4164.8 1913.18
  4265.6  1912.9  4366.4 1910.25  4430.1 1910.05  4435.3 1908.34  4444.2 1908.97
  4464.5 1906.86    4568 1905.83  4638.5  1905.4  4638.9  1904.9  4644.1  1905.4
  4668.8 1906.34  4838.3 1908.41  4845.1 1908.39  4850.3 1905.56  4864.7  1906.2
  4890.2  1908.5  4985.7 1908.07  5053.2 1905.75  5075.1 1907.54  5162.2 1907.31
  5167.3 1908.73  5214.2 1910.76  5238.1 1913.31  5537.4 1916.69  5865.1 1920.26
#Mann= 11 ,-1 , 0
  3999.8    .035       0  4031.8     .07       0  4164.8    .035       0
  4265.6     .07       0  4366.4    .035       0    4568     .07       0
  4638.5     .07       0  4644.1     .07       0  4668.8    .035       0
  4864.7     .07       0  5537.4    .035       0
Bank Sta=4638.5,4644.1
XS Rating Curve= 0 ,0
Exp/Cntr=0.3,0.1

Type RM Length L Ch R = 1 ,96935   ,690,690,690
BEGIN DESCRIPTION:
Mapping XS 89af4706
END DESCRIPTION:
XS GIS Cut Line= 3
      1519517.28      6827316.88      1520090.18      6826876.79
      1520259.45      6826186.67
#Sta/Elev= 30
  4274.9 1913.04  4308.8 1913.03  4410.7 1910.21  4493.7 1907.72  4549.8 1907.15
  4572.6    1906  4686.8 1904.27  4814.3 1903.67  4842.6 1902.24  4857.1 1903.23
  4900.6 1903.73  4918.6 1901.74  4919.1 1901.24  4924.3 1901.74  4927.8 1903.25
  4940.7 1902.95  4971.3 1902.97  4985.8 1901.93    5007 1902.29  5082.1 1902.62
  5088.7 1903.27  5123.6 1903.22  5160.1 1904.18  5278.8 1904.12  5285.5 1904.14
  5366.8 1904.82  5438.8 1907.79  5490.3 1907.97  5562.4  1909.8  5707.9 1911.46
#Mann= 8 ,-1 , 0
  4274.9     .16       0  4410.7     .07       0  4918.6    .035       0
  4924.3     .07       0  4940.7    .035       0    5007     .07       0
  5278.8    .035       0  5285.5     .07       0
Bank Sta=4918.6,4924.3
XS Rating Curve= 0 ,0
Exp/Cntr=0.3,0.1

Type RM Length L Ch R = 1 ,96245   ,555,555,555
BEGIN DESCRIPTION:
Mapping XS fec62ec7
END DESCRIPTION:
XS GIS Cut Line= 3
      1519535.52        6827382.       1520540.7      6827290.85
      1520905.27      6827113.78
#Sta/Elev= 30
  3974.2 1912.76  4128.1 1910.05  4204.6 1908.36  4292.6 1902.61  4395.4  1900.7
  4455.6 1900.27  4485.8 1901.12    4536 1901.11  4576.1 1899.63  4616.3 1900.43
  4629.4 1899.52  4666.5 1898.93  4756.9 1899.44  4850.6 1898.84  4867.3 1899.56
  4877.4 1898.77  4937.6  1898.2  5010.5 1898.63    5021 1897.92  5021.5 1897.42
  5030.5 1897.92    5047 1901.01    5055 1902.83  5065.3 1904.04  5070.9 1903.75
  5087.9 1906.26  5093.5 1905.66  5110.5 1907.36  5241.7 1908.02  5388.8 1909.29
#Mann= 6 ,-1 , 0
  3974.2     .16       0  4128.1     .07       0    5021     .07       0
  5030.5     .07       0    5047    .035       0  5241.7    .045       0
Bank Sta=5021,5030.5
XS Rating Curve= 0 ,0
Exp/Cntr=0.3,0.1

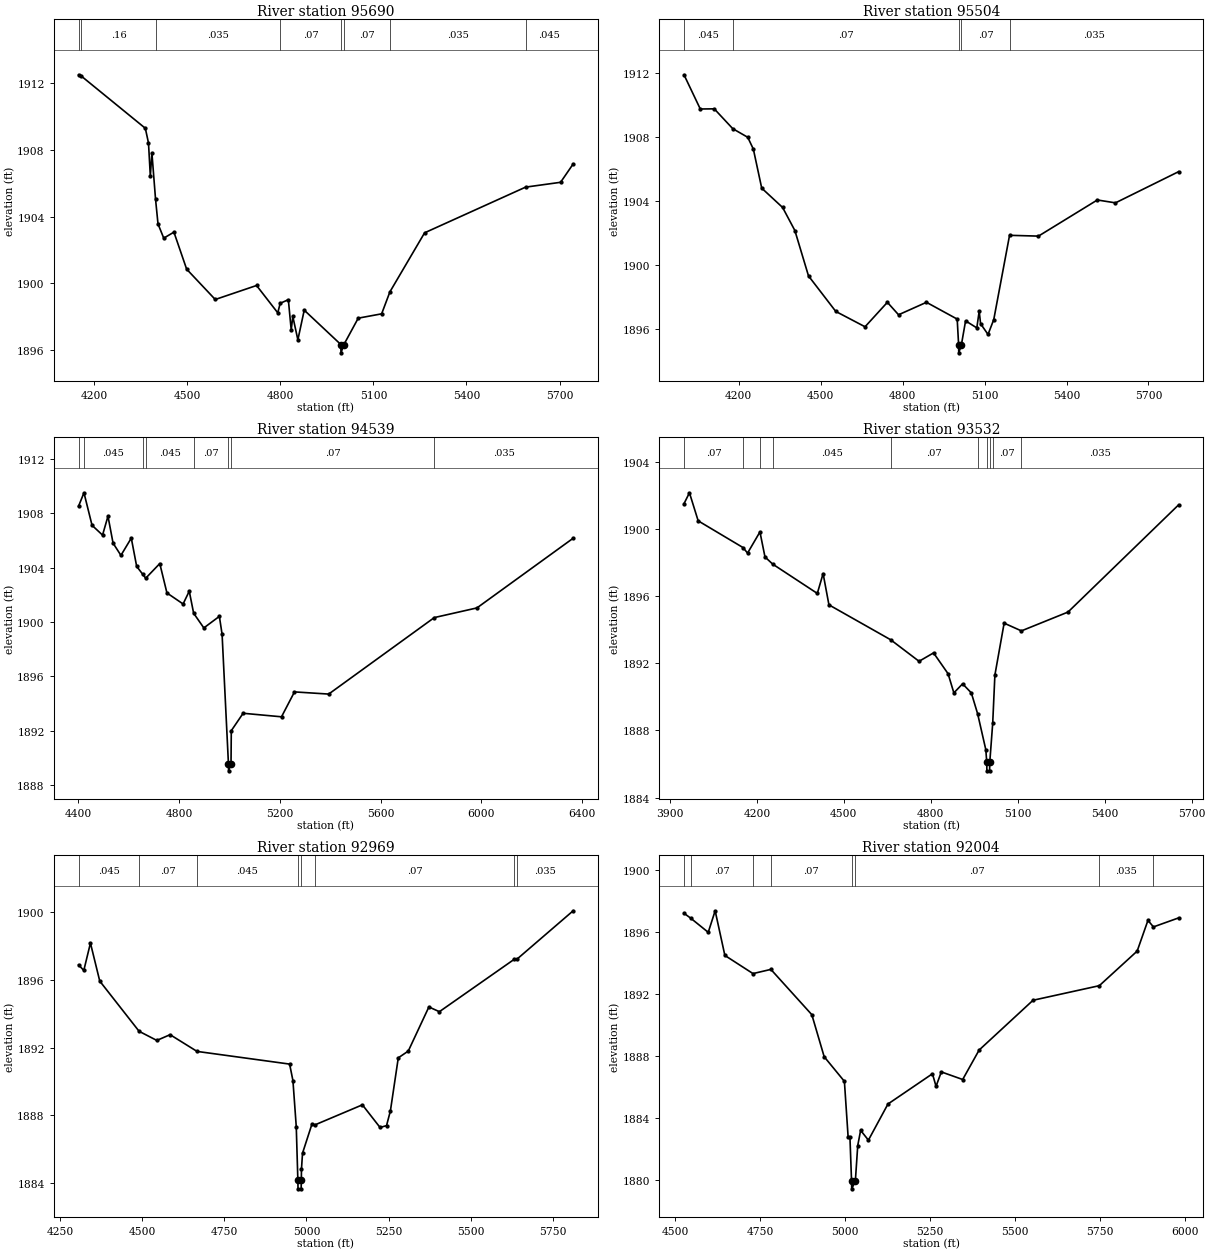
Type RM Length L Ch R = 1 ,95690   ,186,186,186
BEGIN DESCRIPTION:
Mapping XS ba55cdc2
END DESCRIPTION:
XS GIS Cut Line= 3
      1519525.05       6827452.3      1520374.03      6827642.42
      1521084.85      6827783.02
#Sta/Elev= 30
  4149.4 1912.52  4158.3 1912.44  4364.6 1909.31  4374.8 1908.43  4380.7 1906.45
  4385.8 1907.83  4397.5 1905.06  4405.5 1903.57    4424 1902.72  4456.8 1903.08
  4497.8 1900.86    4590 1899.04  4723.2 1899.88  4791.6 1898.24  4799.4 1898.81
  4825.7 1899.03  4834.9 1897.22  4840.1 1898.02  4856.4 1896.62  4876.9  1898.4
  4994.9 1896.34  4995.4 1895.84  5004.9 1896.34    5051 1897.92  5126.5 1898.18
  5153.2  1899.5    5265 1903.04  5590.6 1905.78  5703.4 1906.07    5744 1907.17
#Mann= 8 ,-1 , 0
  4149.4    .035       0  4158.3     .16       0  4397.5    .035       0
  4799.4     .07       0  4994.9     .07       0  5004.9     .07       0
  5153.2    .035       0  5590.6    .045       0
Bank Sta=4994.9,5004.9
XS Rating Curve= 0 ,0
Exp/Cntr=0.3,0.1

Type RM Length L Ch R = 1 ,95504   ,965,965,965
BEGIN DESCRIPTION:
Mapping XS 8f4c5ccf
END DESCRIPTION:
XS GIS Cut Line= 3
      1519376.64      6827618.98      1520345.39       6827822.1
      1521144.85      6828004.39
#Sta/Elev= 30
  4000.3  1911.9  4059.9 1909.76    4111 1909.77  4178.7 1908.53  4233.6 1907.99
  4254.1 1907.25  4284.7 1904.81  4361.2  1903.6    4406 1902.16  4455.9 1899.32
  4555.7  1897.1  4662.8 1896.14  4744.5 1897.67  4785.4 1896.89  4887.5 1897.67
    5000 1896.62  5005.2 1895.01  5005.7 1894.51  5015.3 1895.01  5030.7 1896.51
  5071.8 1896.07  5080.5 1897.12  5085.6 1896.33  5112.8 1895.66  5133.8 1896.59
  5191.6 1901.86  5297.4 1901.81  5512.8 1904.07  5579.2 1903.89  5810.1 1905.84
#Mann= 5 ,-1 , 0
  4000.3    .045       0  4178.7     .07       0  5005.2     .07       0
  5015.3     .07       0  5191.6    .035       0
Bank Sta=5005.2,5015.3
XS Rating Curve= 0 ,0
Exp/Cntr=0.3,0.1

Type RM Length L Ch R = 1 ,94539   ,1007,1007,1007
BEGIN DESCRIPTION:
Mapping XS 41bbf3cb
END DESCRIPTION:
XS GIS Cut Line= 4
       1519321.5      6828039.55      1519929.16      6828187.12
      1520324.12      6828282.61      1521257.32      6828291.29
#Sta/Elev= 30
  4400.4 1908.51  4421.8 1909.49  4453.9  1907.1  4495.6 1906.38  4517.2 1907.77
  4537.4 1905.79  4568.6 1904.89  4609.8 1906.16  4631.2 1904.08  4655.8 1903.49
    4667 1903.21    4723 1904.29  4751.4 1902.13  4815.6 1901.32  4840.1 1902.26
  4857.5 1900.64    4898 1899.56  4959.7 1900.41  4970.5  1899.1  4995.8 1889.56
  4996.3 1889.06    5006 1889.56  5007.1 1892.01  5054.1 1893.29  5206.6 1893.03
  5258.1 1894.86  5394.1  1894.7  5813.6 1900.32    5983 1901.03  6365.3 1906.15
#Mann= 8 ,-1 , 0
  4400.4     .07       0  4421.8    .045       0  4655.8     .07       0
    4667    .045       0  4857.5     .07       0  4995.8     .07       0
    5006     .07       0  5813.6    .035       0
Bank Sta=4995.8,5006
XS Rating Curve= 0 ,0
Exp/Cntr=0.3,0.1

Type RM Length L Ch R = 1 ,93532   ,563,563,563
BEGIN DESCRIPTION:
Mapping XS f5e458b2
END DESCRIPTION:
XS GIS Cut Line= 3
      1519356.26      6828829.48      1520406.59       6828755.7
      1521021.42      6828534.88
#Sta/Elev= 30
  3948.8 1901.49  3967.6 1902.14  3997.7 1900.47  4152.3 1898.88  4168.1 1898.55
  4210.8 1899.81  4228.2 1898.32  4255.1 1897.89  4408.7 1896.15  4428.7 1897.33
  4448.8 1895.47  4661.9 1893.39  4759.7 1892.11  4809.7 1892.61  4859.8 1891.37
  4879.8 1890.23  4909.9 1890.77    4940 1890.23  4961.7 1888.99  4990.1 1886.84
  4993.2 1886.09  4993.7 1885.59  5003.1 1885.59  5003.6 1886.09  5013.8 1888.43
  5021.3 1891.29  5053.2 1894.38  5112.8 1893.92  5273.5 1895.04    5655 1901.42
#Mann= 10 ,-1 , 0
  3948.8     .07       0  4152.3    .045       0  4210.8     .07       0
  4255.1    .045       0  4661.9     .07       0  4961.7    .045       0
  4993.2    .045       0  5003.6    .045       0  5013.8     .07       0
  5112.8    .035       0
Bank Sta=4993.2,5003.6
XS Rating Curve= 0 ,0
Exp/Cntr=0.3,0.1

Type RM Length L Ch R = 1 ,92969   ,965,965,965
BEGIN DESCRIPTION:
Mapping XS 1f3b3827
END DESCRIPTION:
XS GIS Cut Line= 3
       1519619.3      6829332.95      1520296.34      6829232.26
      1521067.15      6828947.55
#Sta/Elev= 30
  4306.1  1896.9    4322 1896.57  4342.2 1898.19  4370.6 1895.94  4490.4 1892.97
  4544.4 1892.43  4584.8 1892.77  4666.9 1891.78  4948.8 1891.03  4958.9 1890.05
    4969 1887.33  4973.9 1884.15  4974.4 1883.65  4983.9 1883.65  4984.4 1884.15
  4984.9 1884.82  4988.1 1885.76  5016.6 1887.47  5026.7 1887.44  5170.4 1888.62
  5224.2 1887.28  5243.9 1887.39  5255.7 1888.26  5279.7  1891.4  5310.1  1891.8
  5372.9 1894.41  5404.9 1894.13  5632.9 1897.23  5641.9 1897.25  5812.3  1900.1
#Mann= 8 ,-1 , 0
  4306.1    .045       0  4490.4     .07       0  4666.9    .045       0
  4973.9    .045       0  4984.4    .045       0  5026.7     .07       0
  5632.9    .045       0  5641.9    .035       0
Bank Sta=4973.9,4984.4
XS Rating Curve= 0 ,0
Exp/Cntr=0.3,0.1

Type RM Length L Ch R = 1 ,92004   ,454,454,454
BEGIN DESCRIPTION:
Mapping XS cf8c7165
END DESCRIPTION:
XS GIS Cut Line= 3
      1519694.75      6829824.28      1520170.47      6829740.94
      1521090.31      6829428.54
#Sta/Elev= 30
  4525.9 1897.19  4545.8 1896.87  4597.2 1895.96  4617.5 1897.35  4646.1 1894.47
  4728.8  1893.3  4781.4 1893.57  4901.8 1890.65  4938.1 1887.94  4997.6 1886.35
  5008.6 1882.74  5013.9 1882.74  5018.6 1879.92  5019.1 1879.42  5029.8 1879.92
  5036.8 1882.21  5045.3 1883.19  5068.2 1882.56  5125.7 1884.89  5256.5 1886.84
  5267.1 1886.03  5282.6 1886.96  5345.4 1886.47  5393.8 1888.37  5552.3 1891.58
  5747.2 1892.52  5858.5 1894.75  5890.2 1896.73  5906.4 1896.31  5980.3 1896.89
#Mann= 8 ,-1 , 0
  4525.9    .045       0  4545.8     .07       0  4728.8    .045       0
  4781.4     .07       0  5018.6     .07       0  5029.8     .07       0
  5747.2    .035       0  5906.4     .07       0
Bank Sta=5018.6,5029.8
XS Rating Curve= 0 ,0
Exp/Cntr=0.3,0.1