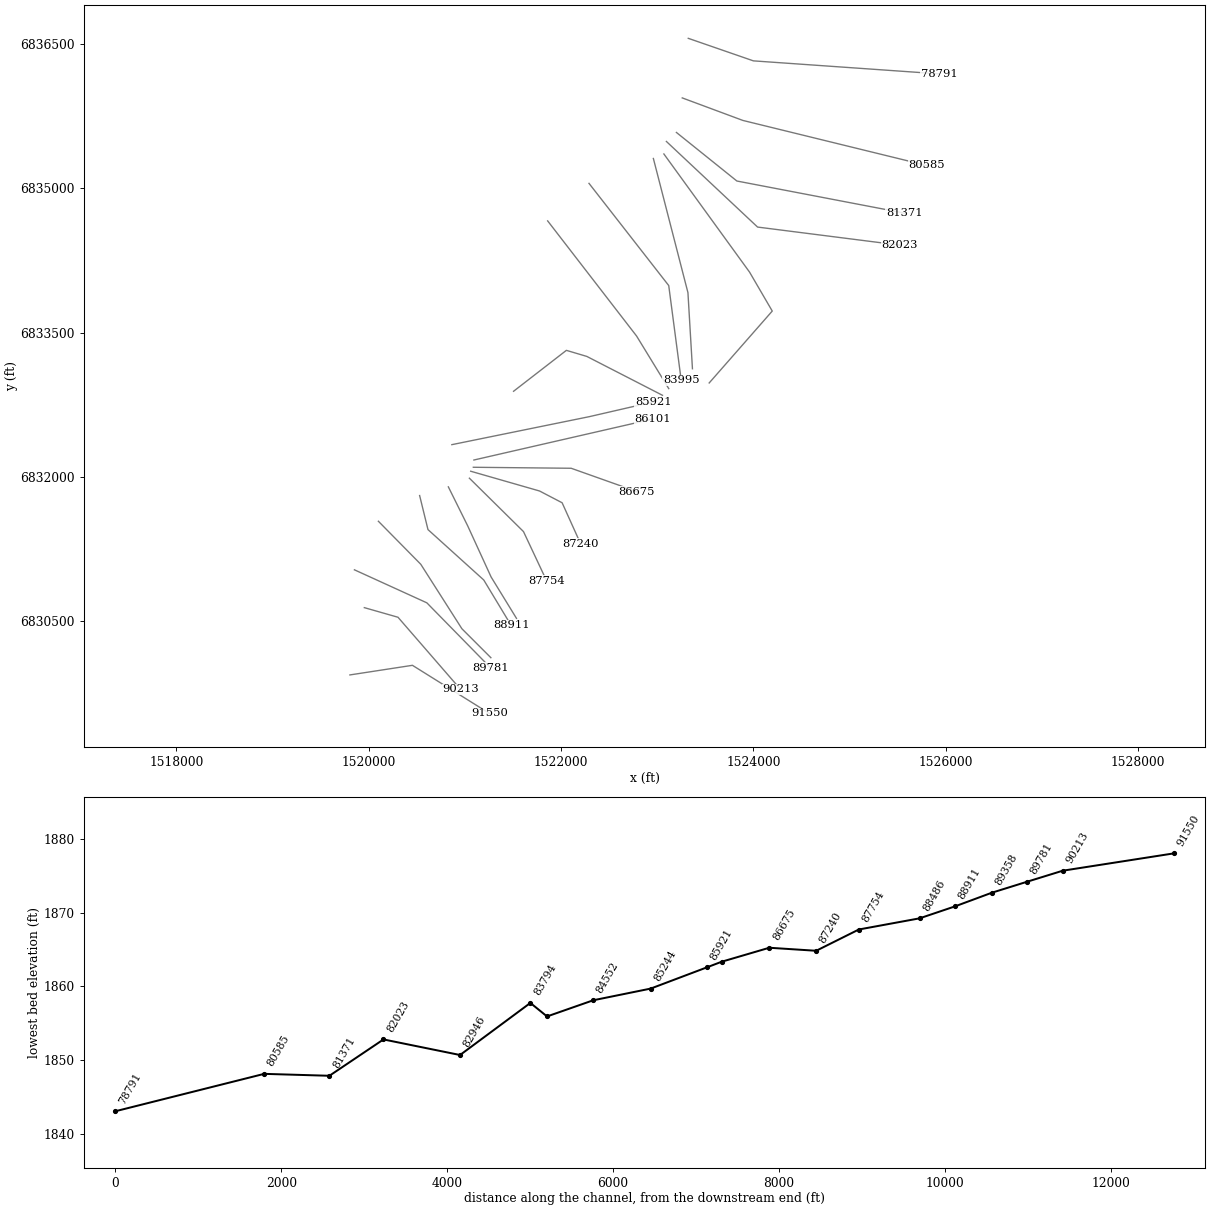
HEC-RAS study BULL WAGON CREEK.prj: BULL WAGON CREEK Base Level Engineering

--- BULL WAGON CREEK.g01 (geometry) --- (continued)

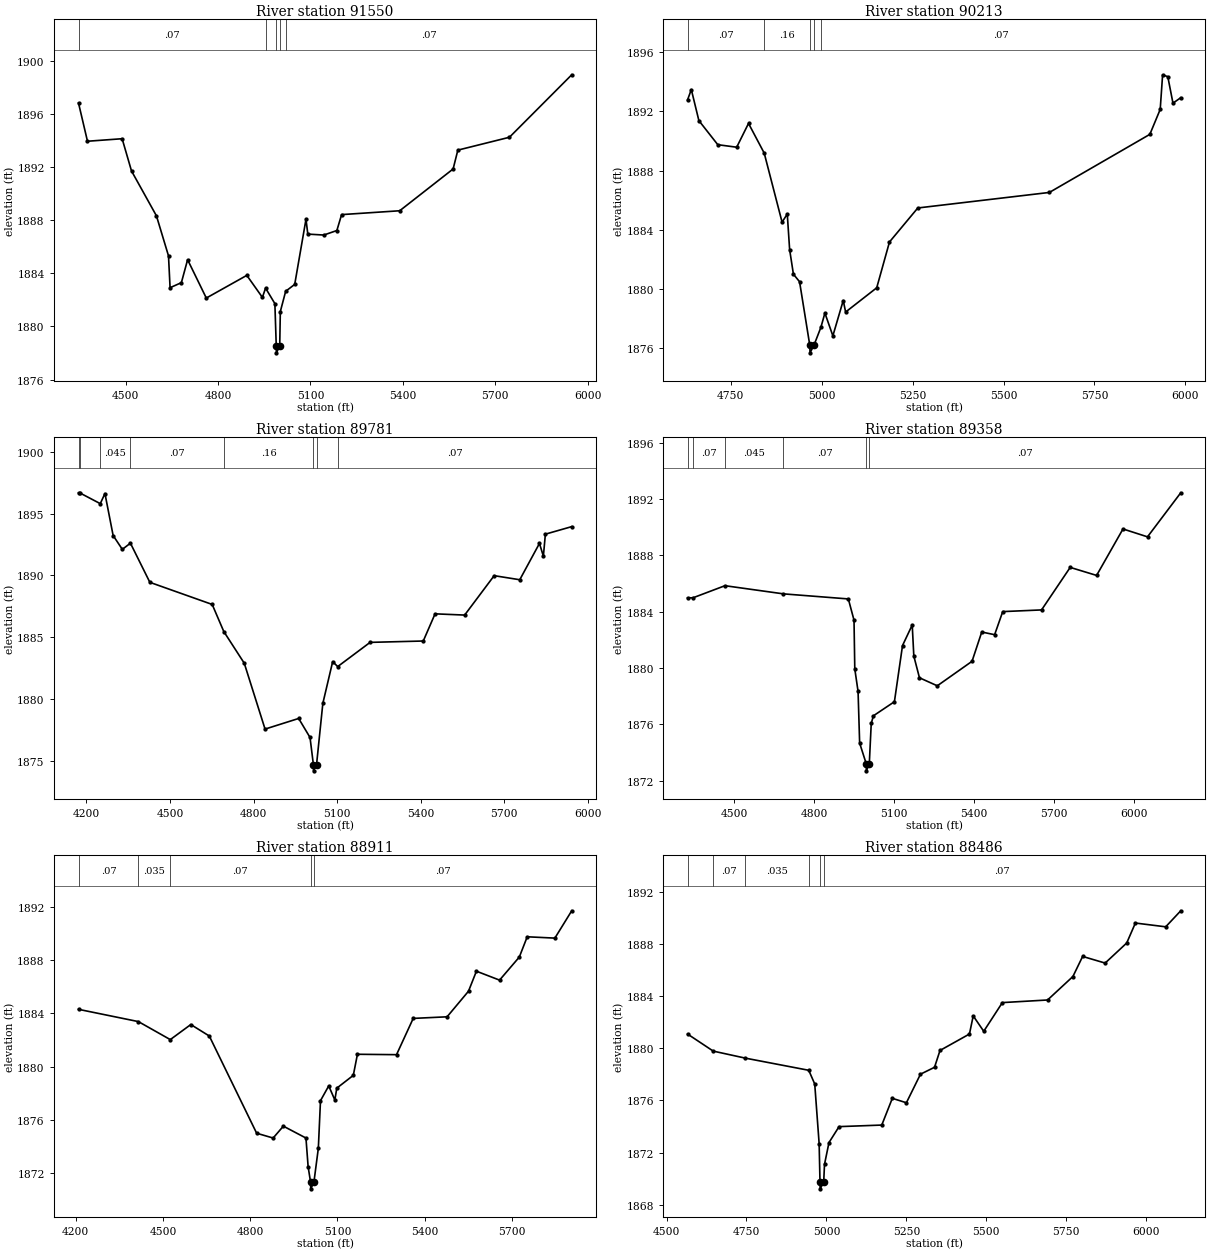
Type RM Length L Ch R = 1 ,91550   ,1337,1337,1337
BEGIN DESCRIPTION:
BULL WAGON CREEK 74.0
END DESCRIPTION:
XS GIS Cut Line= 3
      1519805.02        6829938.        1520455.        6830038.
      1521254.98      6829538.01
#Sta/Elev= 30
  4347.3 1896.84  4376.4 1893.96  4488.9 1894.15  4519.3 1891.72  4600.2 1888.34
  4639.4 1885.32  4644.5 1882.92  4681.2  1883.3  4701.4 1885.03  4762.1 1882.14
  4893.6 1883.85  4944.2 1882.19  4954.5 1882.89  4984.7 1881.72  4989.2 1878.51
  4989.7 1878.01  5000.4 1878.51  5002.4 1881.12  5019.7 1882.65  5049.1 1883.17
  5085.7 1888.08  5091.6 1886.96  5143.5 1886.89  5185.9 1887.23  5201.3 1888.43
  5389.9 1888.72  5563.3 1891.87  5578.6 1893.29  5746.1 1894.26  5948.3 1898.97
#Mann= 5 ,-1 , 0
  4347.3     .07       0  4954.5     .16       0  4989.2     .07       0
  5000.4     .16       0  5019.7     .07       0
Bank Sta=4989.2,5000.4
XS Rating Curve= 0 ,0
Exp/Cntr=0.3,0.1

Type RM Length L Ch R = 1 ,90213   ,432,432,432
BEGIN DESCRIPTION:
BULL WAGON CREEK 73.0
END DESCRIPTION:
XS GIS Cut Line= 3
      1519954.97      6830638.01        1520305.        6830538.
        1520955.        6829788.
#Sta/Elev= 30
  4630.9 1892.78  4641.3 1893.48  4662.1 1891.38  4714.1 1889.75  4766.1 1889.58
  4798.6 1891.19  4841.8 1889.18  4890.9 1884.51  4905.2 1885.06  4911.7 1882.65
  4922.1 1880.99    4939 1880.48  4967.2 1876.17  4967.7 1875.67  4978.4 1876.17
  4997.6 1877.39  5008.7 1878.36  5030.6 1876.82  5059.1 1879.21  5065.7 1878.43
  5151.2 1880.07  5186.3 1883.17  5264.2 1885.47    5626 1886.52  5902.4 1890.45
  5930.9 1892.14  5937.5 1894.48  5951.8 1894.35    5966 1892.56  5987.4 1892.93
#Mann= 5 ,-1 , 0
  4630.9     .07       0  4841.8     .16       0  4967.2     .07       0
  4978.4     .16       0  4997.6     .07       0
Bank Sta=4967.2,4978.4
XS Rating Curve= 0 ,0
Exp/Cntr=0.3,0.1

Type RM Length L Ch R = 1 ,89781   ,423,423,423
BEGIN DESCRIPTION:
BULL WAGON CREEK 72.0
END DESCRIPTION:
XS GIS Cut Line= 3
      1519851.87      6831031.58        1520605.        6830688.
      1521265.06      6830014.24
#Sta/Elev= 30
  4171.5 1896.68  4175.3 1896.68  4249.6  1895.8  4266.4 1896.62  4295.8 1893.22
  4328.8  1892.1  4357.9  1892.6  4427.7 1889.43  4651.5 1887.64  4693.1 1885.45
  4766.7 1882.88  4841.3 1877.55    4962 1878.41  5002.8 1876.87  5014.9 1874.67
  5015.4 1874.17  5026.2 1874.67  5048.8 1879.63  5084.1 1883.01  5102.2 1882.61
  5218.5 1884.57  5409.4 1884.68  5451.8 1886.88    5558 1886.78    5664 1889.97
  5755.9 1889.64  5826.6 1892.58  5840.7 1891.55  5847.9 1893.33  5942.5 1893.94
#Mann= 8 ,-1 , 0
  4171.5    .045       0  4175.3     .07       0  4249.6    .045       0
  4357.9     .07       0  4693.1     .16       0  5014.9     .07       0
  5026.2     .16       0  5102.2     .07       0
Bank Sta=5014.9,5026.2
XS Rating Curve= 0 ,0
Exp/Cntr=0.3,0.1

Type RM Length L Ch R = 1 ,89358   ,447,447,447
BEGIN DESCRIPTION:
Mapping XS ef59eebf
END DESCRIPTION:
XS GIS Cut Line= 4
        1520101.       6831536.8        1520542.      6831088.86
      1520969.09      6830418.72      1521270.56      6830117.25
#Sta/Elev= 30
  4325.3 1884.98  4345.6 1884.98  4465.7 1885.84    4685 1885.26  4928.3  1884.9
  4949.6 1883.39  4952.5 1879.93  4964.8 1878.33  4970.7 1874.66  4995.5 1873.19
    4996 1872.69  5006.9 1873.19  5014.2 1876.06  5022.4  1876.6  5101.1  1877.6
  5131.5 1881.59  5167.9 1883.05  5173.9 1880.84    5195  1879.3  5261.9 1878.73
  5392.2 1880.47  5428.6 1882.55  5476.9 1882.36  5507.3    1884  5652.9 1884.12
  5760.3 1887.14  5859.3 1886.57  5958.3 1889.87  6050.2 1889.31  6174.9 1892.44
#Mann= 6 ,-1 , 0
  4325.3    .045       0  4345.6     .07       0  4465.7    .045       0
    4685     .07       0  4995.5     .07       0  5006.9     .07       0
Bank Sta=4995.5,5006.9
XS Rating Curve= 0 ,0
Exp/Cntr=0.3,0.1

Type RM Length L Ch R = 1 ,88911   ,425,425,425
BEGIN DESCRIPTION:
Mapping XS 7c071df8
END DESCRIPTION:
XS GIS Cut Line= 4
      1520529.84      6831804.18      1520616.66      6831449.97
      1521196.52      6830925.66      1521480.64      6830454.44
#Sta/Elev= 30
  4209.3 1884.29  4415.3 1883.37    4525 1882.02  4595.6 1883.15  4659.2 1882.29
  4822.1    1875  4878.8 1874.64    4914 1875.53  4991.7 1874.64  4999.2 1872.49
  5007.6 1871.33  5008.1 1870.83  5019.1 1871.33  5034.3 1873.87  5041.7 1877.44
  5070.1 1878.55  5091.1 1877.49  5097.8 1878.38  5154.6 1879.34  5168.8 1880.92
  5303.3 1880.89  5360.7 1883.61  5477.2 1883.73  5550.9 1885.65  5578.1 1887.15
  5657.7 1886.48  5725.7 1888.21  5752.9 1889.73    5848 1889.63    5906 1891.68
#Mann= 5 ,-1 , 0
  4209.3     .07       0  4415.3    .035       0    4525     .07       0
  5007.6     .07       0  5019.1     .07       0
Bank Sta=5007.6,5019.1
XS Rating Curve= 0 ,0
Exp/Cntr=0.3,0.1

Type RM Length L Ch R = 1 ,88486   ,732,732,732
BEGIN DESCRIPTION:
Mapping XS 6a59b4ca
END DESCRIPTION:
XS GIS Cut Line= 4
      1520828.47      6831894.38      1521029.85      6831488.16
      1521272.91      6830956.91      1521536.79      6830526.36
#Sta/Elev= 30
  4565.7 1881.09  4646.1 1879.78  4746.8 1879.24  4944.8 1878.31  4963.5 1877.26
  4977.3 1872.69    4980 1869.72  4980.5 1869.22  4991.5 1869.72  4994.1  1871.1
  5008.1 1872.77  5039.6 1873.99  5173.2 1874.11  5206.2 1876.16  5250.2 1875.82
  5294.2 1878.01  5338.2 1878.54  5355.3 1879.83  5447.4 1881.09  5459.2 1882.48
  5492.1  1881.3  5550.4  1883.5  5691.7  1883.7    5771  1885.5  5801.4 1887.04
  5871.8 1886.53  5939.3 1888.07  5966.4  1889.6  6061.2 1889.31  6108.3 1890.54
#Mann= 6 ,-1 , 0
  4565.7    .035       0  4646.1     .07       0  4746.8    .035       0
  4944.8     .07       0    4980     .07       0  4991.5     .07       0
Bank Sta=4980,4991.5
XS Rating Curve= 0 ,0
Exp/Cntr=0.3,0.1

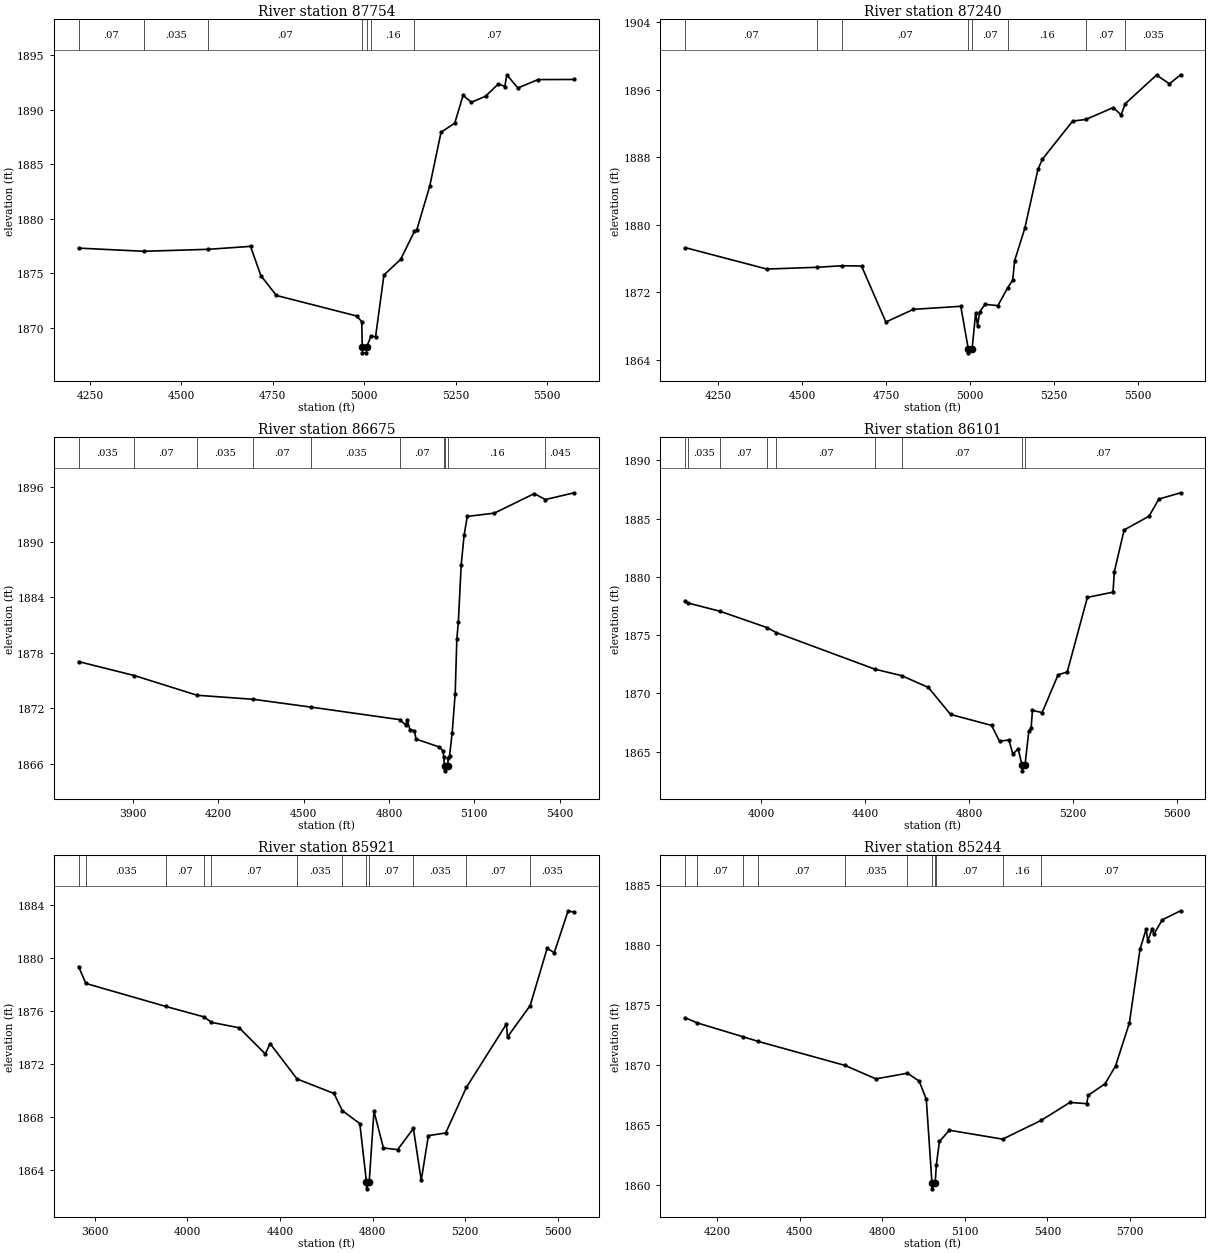
Type RM Length L Ch R = 1 ,87754   ,514,514,514
BEGIN DESCRIPTION:
Mapping XS fc80ae09
END DESCRIPTION:
XS GIS Cut Line= 3
      1521047.18      6831984.71      1521609.71      6831429.13
       1521849.3       6830918.7
#Sta/Elev= 30
  4219.1 1877.31  4397.2 1877.02  4573.2  1877.2    4689 1877.47  4717.3 1874.78
  4759.7 1872.97  4978.9 1871.09    4993 1870.57  4994.4 1868.21  4994.9 1867.71
  5005.5 1867.71    5006 1868.21  5018.2 1869.24  5030.8 1869.19  5053.6 1874.85
  5099.2 1876.27  5136.9 1878.84  5143.6    1879  5178.7 1882.98  5209.8 1887.94
  5247.1 1888.76  5269.9 1891.31  5292.8 1890.68  5331.3 1891.23  5366.7 1892.37
    5384 1892.12  5389.5  1893.2  5419.7 1891.99    5475 1892.76  5573.6 1892.77
#Mann= 7 ,-1 , 0
  4219.1     .07       0  4397.2    .035       0  4573.2     .07       0
  4994.4     .07       0    5006     .07       0  5018.2     .16       0
  5136.9     .07       0
Bank Sta=4994.4,5006
XS Rating Curve= 0 ,0
Exp/Cntr=0.3,0.1

Type RM Length L Ch R = 1 ,87240   ,565,565,565
BEGIN DESCRIPTION:
Mapping XS 1f472295
END DESCRIPTION:
XS GIS Cut Line= 4
      1521060.71      6832057.16      1521776.81      6831851.44
      1522011.19      6831729.05      1522203.68      6831302.44
#Sta/Elev= 30
  4150.5 1877.29  4394.3 1874.75  4545.1 1874.96  4617.4 1875.14  4676.5 1875.11
  4749.1 1868.48  4831.3 1869.98  4972.5 1870.34  4994.7 1865.33  4995.2 1864.83
  5006.3 1865.33  5016.9 1869.56  5022.5 1868.06  5028.9 1869.68  5044.6 1870.57
  5083.1 1870.42  5111.8  1872.5  5127.3 1873.43    5133 1875.74  5163.3 1879.56
  5202.6 1886.56    5216 1887.77  5306.1 1892.27  5345.5 1892.46  5427.2 1893.87
  5450.4    1893  5462.7 1894.32  5556.1 1897.72  5594.6 1896.68    5628 1897.75
#Mann= 8 ,-1 , 0
  4150.5     .07       0  4545.1    .035       0  4617.4     .07       0
  4994.7     .07       0  5006.3     .07       0  5111.8     .16       0
  5345.5     .07       0  5462.7    .035       0
Bank Sta=4994.7,5006.3
XS Rating Curve= 0 ,0
Exp/Cntr=0.3,0.1

Type RM Length L Ch R = 1 ,86675   ,574,574,574
BEGIN DESCRIPTION:
Mapping XS aea0a485
END DESCRIPTION:
XS GIS Cut Line= 3
      1521087.98       6832098.4      1522105.37      6832087.99
      1522789.43      6831844.92
#Sta/Elev= 30
  3708.2 1877.06  3904.4 1875.55    4125 1873.42    4323 1872.98  4527.3 1872.13
  4838.2 1870.78    4859  1870.2  4864.3 1870.74  4873.8 1869.71  4889.8 1869.56
  4895.1 1868.68  4977.1 1867.82  4990.6 1867.39  4992.6  1866.7  4995.4 1865.74
  4995.9 1865.24    5007 1865.74  5007.9 1866.58  5013.2 1866.88  5022.4 1869.36
    5033  1873.6  5038.8 1879.51  5044.1 1881.35  5054.2 1887.54  5064.3 1890.73
  5075.5 1892.77    5171 1893.13  5311.1 1895.24  5350.5  1894.6  5451.6 1895.33
#Mann= 10 ,-1 , 0
  3708.2    .035       0  3904.4     .07       0    4125    .035       0
    4323     .07       0  4527.3    .035       0  4838.2     .07       0
  4992.6     .16       0  4995.4     .07       0    5007     .16       0
  5350.5    .045       0
Bank Sta=4995.4,5007
XS Rating Curve= 0 ,0
Exp/Cntr=0.3,0.1

Type RM Length L Ch R = 1 ,86101   ,180,180,180
BEGIN DESCRIPTION:
Mapping XS e5870ce6
END DESCRIPTION:
XS GIS Cut Line= 2
      1521094.06      6832173.92      1522955.18        6832601.
#Sta/Elev= 30
  3706.4 1877.95  3719.1 1877.75  3841.9 1877.04  4021.9 1875.65  4058.5 1875.21
  4437.4 1872.08    4541 1871.52  4643.7 1870.51  4729.4 1868.19  4887.3 1867.25
    4918 1865.89  4954.1    1866  4969.3  1864.8  4989.9 1865.23  5004.5 1863.85
    5005 1863.35  5016.2 1863.85  5030.9 1866.77  5039.8 1867.03  5044.9 1868.54
  5082.2 1868.35  5143.8  1871.6  5178.7 1871.83  5256.6 1878.24  5355.3 1878.69
  5360.5 1880.45  5398.2 1884.03  5494.2 1885.21    5532 1886.68  5615.9 1887.22
#Mann= 9 ,-1 , 0
  3706.4     .07       0  3719.1    .035       0  3841.9     .07       0
  4021.9    .035       0  4058.5     .07       0  4437.4    .035       0
    4541     .07       0  5004.5     .07       0  5016.2     .07       0
Bank Sta=5004.5,5016.2
XS Rating Curve= 0 ,0
Exp/Cntr=0.3,0.1

Type RM Length L Ch R = 1 ,85921   ,677,677,677
BEGIN DESCRIPTION:
Mapping XS 1829363c
END DESCRIPTION:
XS GIS Cut Line= 3
      1520864.89      6832333.64      1522295.47      6832625.31
      1522958.69       6832778.1
#Sta/Elev= 30
  3530.3 1879.37  3561.4  1878.1    3907 1876.36  4072.3 1875.57  4103.9 1875.16
  4223.6 1874.75  4336.7 1872.77  4357.1 1873.56  4474.1 1870.88    4633 1869.79
  4669.9 1868.48  4744.9 1867.51  4773.7 1863.08  4774.2 1862.58  4785.4 1863.08
  4806.1 1868.44  4846.9 1865.67  4908.2 1865.54  4976.3 1867.14  5010.3 1863.22
  5041.1  1866.6  5115.9  1866.8  5205.1 1870.24  5377.8 1875.02  5382.9 1874.06
  5480.9 1876.43  5554.1 1880.75    5585 1880.43  5644.8 1883.59  5670.9 1883.47
#Mann= 12 ,-1 , 0
  3530.3     .07       0  3561.4    .035       0    3907     .07       0
  4072.3    .035       0  4103.9     .07       0  4474.1    .035       0
  4669.9     .07       0  4773.7    .035       0  4785.4     .07       0
  4976.3    .035       0  5205.1     .07       0  5480.9    .035       0
Bank Sta=4773.7,4785.4
XS Rating Curve= 0 ,0
Exp/Cntr=0.3,0.1

Type RM Length L Ch R = 1 ,85244   ,692,692,692
BEGIN DESCRIPTION:
Mapping XS 39309b9e
END DESCRIPTION:
XS GIS Cut Line= 4
      1521506.41      6832889.04      1522055.44      6833314.71
      1522268.04      6833251.55      1523054.41      6832847.28
#Sta/Elev= 30
  4083.5 1873.93  4127.8  1873.5  4295.4 1872.34  4349.7 1871.96  4664.1 1869.97
  4776.8 1868.85  4891.6 1869.32  4934.2 1868.66    4960 1867.15  4980.5 1860.21
    4981 1859.71  4992.3 1860.21  4996.4 1861.68  5007.8 1863.65  5043.9 1864.58
  5237.4 1863.84  5377.4  1865.4  5481.8 1866.89  5542.8 1866.79  5548.4 1867.49
  5609.3 1868.43    5648 1869.94    5698  1873.5  5736.8 1879.65  5758.9 1881.29
  5764.6 1880.31  5781.1 1881.34  5786.7 1880.87  5817.4 1882.07  5884.2 1882.82
#Mann= 11 ,-1 , 0
  4083.5    .035       0  4127.8     .07       0  4295.4    .035       0
  4349.7     .07       0  4664.1    .035       0  4891.6     .07       0
  4980.5     .07       0  4992.3     .07       0  4996.4     .07       0
  5237.4     .16       0  5377.4     .07       0
Bank Sta=4980.5,4992.3
XS Rating Curve= 0 ,0
Exp/Cntr=0.3,0.1

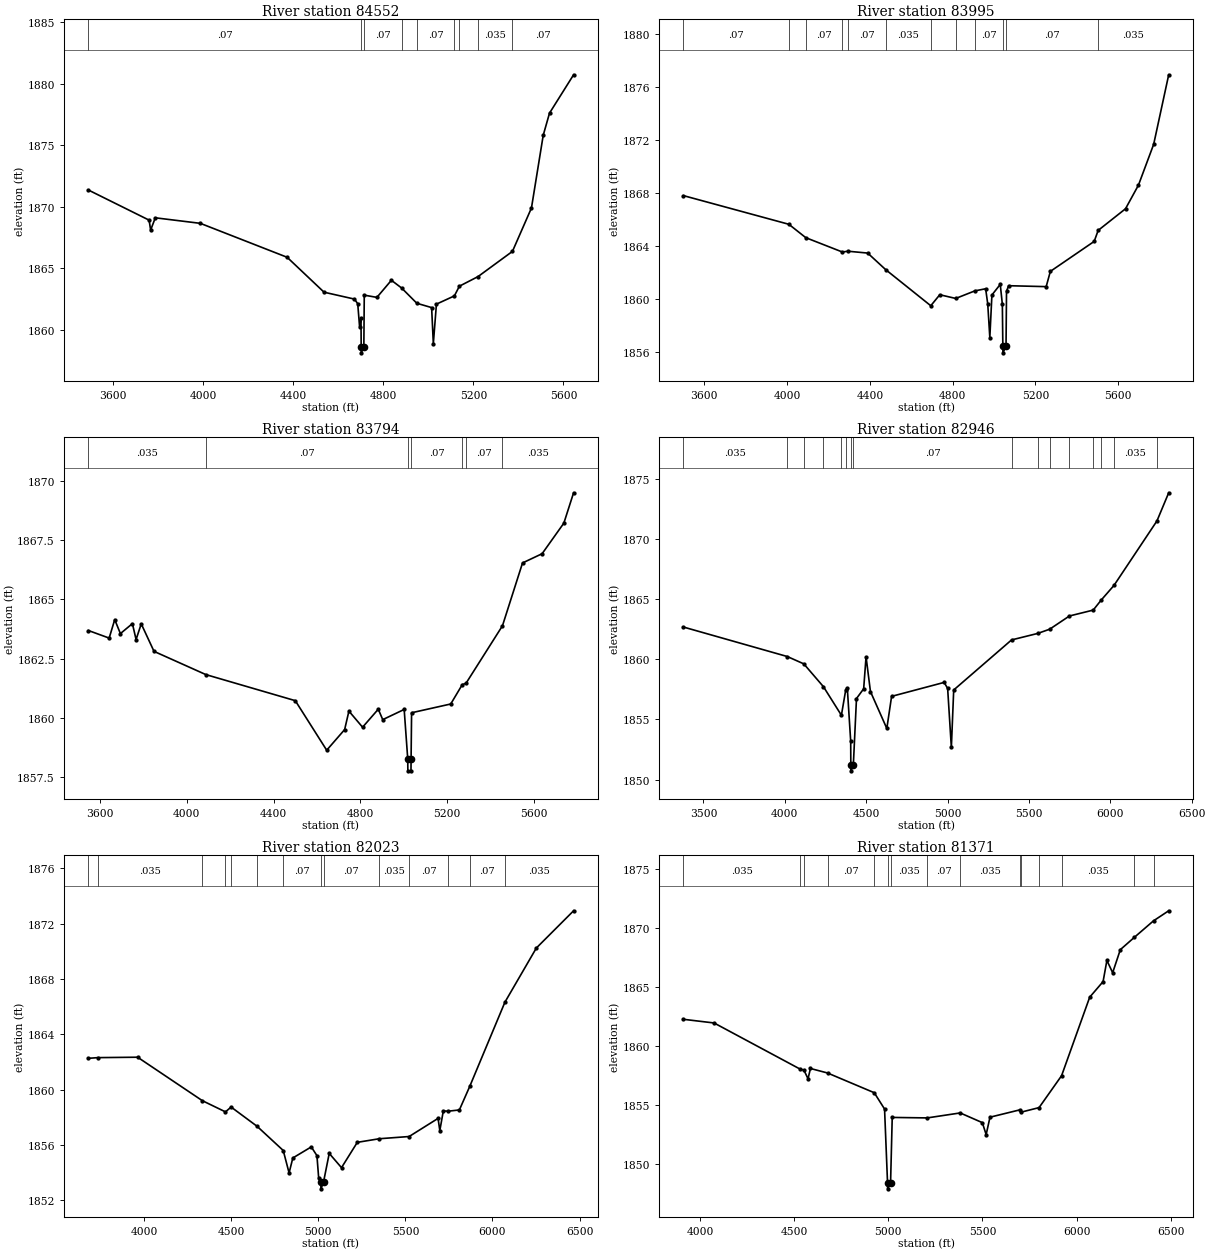
Type RM Length L Ch R = 1 ,84552   ,557,557,557
BEGIN DESCRIPTION:
Mapping XS 67e2a39c
END DESCRIPTION:
XS GIS Cut Line= 3
      1521860.87      6834661.47      1522785.32       6833463.6
      1523119.51      6832916.74
#Sta/Elev= 30
  3490.9 1871.37  3760.6 1868.92  3767.3 1868.11  3788.1 1869.11  3987.9 1868.66
  4373.3  1865.9  4537.2 1863.06  4672.2  1862.5  4686.7 1862.12  4694.8 1860.27
  4701.2 1860.98    4702 1858.63  4702.5 1858.13  4713.8 1858.63  4715.7 1862.82
  4771.8 1862.64  4836.1 1864.03  4881.6  1863.4  4949.1 1862.16  5014.7 1861.81
  5022.3 1858.88    5036 1862.09  5115.7 1862.76    5138 1863.55  5220.7 1864.33
  5373.5 1866.38  5457.9 1869.91  5510.1 1875.82    5538 1877.62  5644.9 1880.74
#Mann= 9 ,-1 , 0
  3490.9     .07       0    4702     .07       0  4713.8     .07       0
  4881.6     .16       0  4949.1     .07       0  5115.7     .16       0
    5138     .07       0  5220.7    .035       0  5373.5     .07       0
Bank Sta=4702,4713.8
XS Rating Curve= 0 ,0
Exp/Cntr=0.3,0.1

Type RM Length L Ch R = 1 ,83995   ,201,201,201
BEGIN DESCRIPTION:
Mapping XS f8bd3604
END DESCRIPTION:
XS GIS Cut Line= 3
      1522290.53      6835052.13      1523119.52      6833988.77
      1523249.48       6833001.1
#Sta/Elev= 30
  3499.2 1867.79  4008.4 1865.63  4090.3 1864.62  4266.9 1863.54  4293.7  1863.6
  4389.3 1863.46  4476.3 1862.21  4694.1 1859.49  4737.6 1860.32  4814.6 1860.04
    4907 1860.61  4959.2 1860.77  4969.3 1859.63  4979.4 1857.09  4989.5  1860.3
  5029.8  1861.1  5039.9 1859.61  5042.3 1856.44  5042.8 1855.94  5057.7 1856.44
  5060.1 1860.58  5070.2    1861  5251.7 1860.93  5271.9 1862.08  5483.7 1864.34
  5502.9 1865.17    5635  1866.8  5697.5 1868.58  5771.1 1871.66  5843.7  1876.9
#Mann= 12 ,-1 , 0
  3499.2     .07       0  4008.4    .035       0  4090.3     .07       0
  4266.9    .035       0  4293.7     .07       0  4476.3    .035       0
  4694.1     .07       0  4814.6     .16       0    4907     .07       0
  5042.3     .07       0  5057.7     .07       0  5502.9    .035       0
Bank Sta=5042.3,5057.7
XS Rating Curve= 0 ,0
Exp/Cntr=0.3,0.1

Type RM Length L Ch R = 1 ,83794   ,848,848,848
BEGIN DESCRIPTION:
Mapping XS ff9e7a17
END DESCRIPTION:
XS GIS Cut Line= 3
       1522959.8       6835310.8      1523319.17      6833914.98
      1523366.05      6833123.31
#Sta/Elev= 30
  3547.2 1863.69    3643 1863.37  3668.6 1864.15  3694.7 1863.56    3750 1863.98
  3766.9 1863.31  3790.7 1863.97  3849.5 1862.81  4088.2 1861.83  4500.1 1860.73
  4644.7 1858.64  4727.3 1859.51    4747 1860.29  4809.9 1859.61  4882.2 1860.37
  4902.8 1859.93  5001.5 1860.36  5017.9 1858.27  5018.4 1857.77  5032.8 1857.77
  5033.3 1858.27  5035.6 1860.22  5215.9 1860.59  5269.2 1861.41    5286 1861.46
  5454.1 1863.89  5546.5 1866.54  5636.7 1866.93  5736.8 1868.22  5781.6  1869.5
#Mann= 7 ,-1 , 0
  3547.2    .035       0  4088.2     .07       0  5017.9     .07       0
  5033.3     .07       0  5269.2    .035       0    5286     .07       0
  5454.1    .035       0
Bank Sta=5017.9,5033.3
XS Rating Curve= 0 ,0
Exp/Cntr=0.3,0.1

Type RM Length L Ch R = 1 ,82946   ,923,923,923
BEGIN DESCRIPTION:
Mapping XS 2618e492
END DESCRIPTION:
XS GIS Cut Line= 4
      1523069.15      6835357.73       1523959.8      6834128.53
      1524195.72       6833723.5      1523540.07      6832975.58
#Sta/Elev= 30
  3377.6 1862.67  4015.6 1860.22    4117 1859.61  4237.7 1857.71  4347.9 1855.34
  4374.2 1857.42  4384.2  1857.6    4405 1853.18  4405.8 1851.22  4406.3 1850.72
  4421.3 1851.22  4440.6 1856.73  4484.7 1857.54  4499.4  1860.2  4526.4 1857.31
    4627 1854.24  4656.3 1856.91  4979.2 1858.07  5000.7 1857.57  5023.5 1852.66
  5037.9 1857.44  5393.3  1861.6  5554.1 1862.14  5627.4 1862.49  5748.9 1863.59
  5895.1 1864.08    5944 1864.91  6022.7 1866.13  6286.7 1871.49  6358.9 1873.83
#Mann= 16 ,-1 , 0
  3377.6    .035       0  4015.6     .07       0    4117    .035       0
  4237.7     .07       0  4347.9    .035       0  4374.2     .07       0
  4405.8     .07       0  4421.3     .07       0  5393.3     .16       0
  5554.1     .07       0  5627.4     .16       0  5748.9     .07       0
  5895.1    .035       0    5944     .07       0  6022.7    .035       0
  6286.7     .07       0
Bank Sta=4405.8,4421.3
XS Rating Curve= 0 ,0
Exp/Cntr=0.3,0.1

Type RM Length L Ch R = 1 ,82023   ,652,652,652
BEGIN DESCRIPTION:
Mapping XS 581b28fc
END DESCRIPTION:
XS GIS Cut Line= 3
      1523095.23      6835487.89      1524043.13      6834597.28
       1525517.1      6834409.78
#Sta/Elev= 30
  3679.4 1862.26  3734.1 1862.31  3962.2 1862.34  4333.9  1859.2  4466.8 1858.39
  4499.1 1858.74  4648.2 1857.35  4798.5  1855.6  4832.1 1853.98  4853.6 1855.06
  4959.6 1855.86    4992 1855.23  5002.1  1853.6  5014.5 1853.33    5015 1852.83
    5030 1853.33  5062.6 1855.39  5133.1 1854.36  5223.9 1856.19  5350.3 1856.45
  5521.5 1856.61  5687.6 1857.92  5697.7 1857.04  5717.8 1858.46  5745.6 1858.44
    5810 1858.53  5869.5 1860.23  6071.7 1866.32  6252.1 1870.23  6465.9 1872.92
#Mann= 14 ,-1 , 0
  3679.4     .07       0  3734.1    .035       0  4333.9     .07       0
  4466.8    .035       0  4499.1     .07       0  4648.2    .035       0
  4798.5     .07       0  5014.5     .07       0    5030     .07       0
  5350.3    .035       0  5521.5     .07       0  5745.6    .035       0
  5869.5     .07       0  6071.7    .035       0
Bank Sta=5014.5,5030
XS Rating Curve= 0 ,0
Exp/Cntr=0.3,0.1

Type RM Length L Ch R = 1 ,81371   ,786,786,786
BEGIN DESCRIPTION:
Mapping XS d25d5729
END DESCRIPTION:
XS GIS Cut Line= 3
      1523199.35      6835581.67      1523827.85      6835076.44
      1525567.41      6834743.11
#Sta/Elev= 30
  3911.9 1862.25  4074.5 1861.94  4528.9 1858.06  4551.8 1857.95  4573.5 1857.22
  4586.4 1858.09    4677 1857.71  4925.3 1856.04  4980.1 1854.66  4995.9 1848.41
  4996.4 1847.91    5012 1848.41  5020.8 1853.95  5206.9 1853.91  5381.9 1854.33
  5499.4 1853.51  5519.8  1852.5  5540.1 1853.97  5698.6 1854.59  5706.2  1854.4
  5800.8 1854.78  5920.5 1857.48  6069.8 1864.12  6140.9 1865.44  6161.2 1867.23
  6191.8 1866.19  6232.5 1868.14  6307.5 1869.19  6408.8 1870.58  6489.5 1871.43
#Mann= 15 ,-1 , 0
  3911.9    .035       0  4528.9     .07       0  4551.8    .035       0
    4677     .07       0  4925.3    .035       0  4995.9    .035       0
    5012    .035       0  5206.9     .07       0  5381.9    .035       0
  5698.6     .07       0  5706.2    .035       0  5800.8     .07       0
  5920.5    .035       0  6307.5     .07       0  6408.8    .035       0
Bank Sta=4995.9,5012
XS Rating Curve= 0 ,0
Exp/Cntr=0.3,0.1

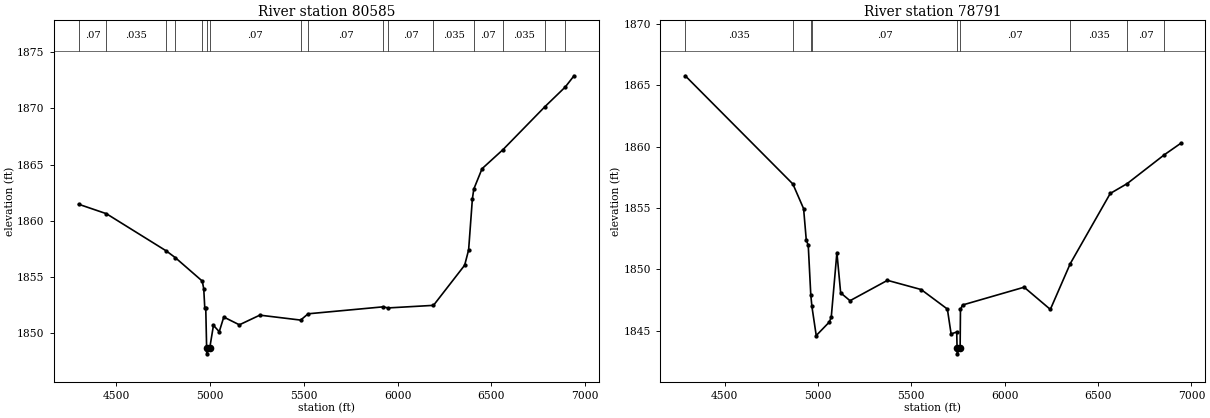
Type RM Length L Ch R = 1 ,80585   ,1794,1794,1794
BEGIN DESCRIPTION:
Mapping XS 48c88846
END DESCRIPTION:
XS GIS Cut Line= 3
       1523260.1      6835941.04      1523890.35      6835706.65
      1525800.92      6835238.12
#Sta/Elev= 30
  4300.4 1861.47  4448.2 1860.63  4767.4 1857.32  4815.7 1856.72  4959.1 1854.64
  4967.1 1853.95  4972.6 1852.24  4977.8 1852.24  4982.5 1848.67    4983 1848.17
  4998.8 1848.67  5018.8  1850.7  5049.7 1850.14  5073.8 1851.44  5156.9 1850.75
  5265.9 1851.61  5483.4 1851.17  5523.3 1851.73    5924 1852.35  5947.8 1852.25
  6191.2 1852.48  6357.3 1856.05  6378.4 1857.41  6398.5 1861.96    6406 1862.82
    6450 1864.63  6561.8 1866.33  6785.3 1870.15  6893.2 1871.89    6940 1872.89
#Mann= 16 ,-1 , 0
  4300.4     .07       0  4448.2    .035       0  4767.4     .07       0
  4815.7    .035       0  4959.1     .07       0  4982.5     .07       0
  4998.8     .07       0  5483.4     .16       0  5523.3     .07       0
    5924    .035       0  5947.8     .07       0  6191.2    .035       0
    6406     .07       0  6561.8    .035       0  6785.3     .07       0
  6893.2    .035       0
Bank Sta=4982.5,4998.8
XS Rating Curve= 0 ,0
Exp/Cntr=0.3,0.1

Type RM Length L Ch R = 1 ,78791   ,1227,1227,1227
BEGIN DESCRIPTION:
Mapping XS 0bfd67df
END DESCRIPTION:
XS GIS Cut Line= 3
      1523322.64      6836560.82      1523999.73      6836326.44
      1525930.98       6836191.1
#Sta/Elev= 30
  4289.5 1865.77  4865.8 1856.95  4923.2 1854.94  4937.5 1852.39  4948.1 1851.95
  4961.7 1847.91  4967.7 1846.97  4990.8  1844.6  5061.4 1845.71  5071.4 1846.12
  5101.5 1851.36  5121.6 1848.08  5171.7 1847.44  5372.2  1849.1  5552.6 1848.35
    5693 1846.76    5713 1844.73  5743.1 1844.89  5744.9 1843.61  5745.4 1843.11
  5761.3 1843.61  5763.1 1846.73  5774.3 1847.09    6104 1848.54  6244.3 1846.73
    6351 1850.46  6565.1 1856.18  6655.5 1856.98  6854.4 1859.33    6942 1860.26
#Mann= 9 ,-1 , 0
  4289.5    .035       0  4865.8     .07       0  4961.7    .035       0
  4967.7     .07       0  5744.9     .07       0  5761.3     .07       0
    6351    .035       0  6655.5     .07       0  6854.4    .035       0
#XS Ineff= 2 , 0
       0  5101.5 1851.36               0
Permanent Ineff=
       F       F
Bank Sta=5744.9,5761.3
XS Rating Curve= 0 ,0
Exp/Cntr=0.3,0.1