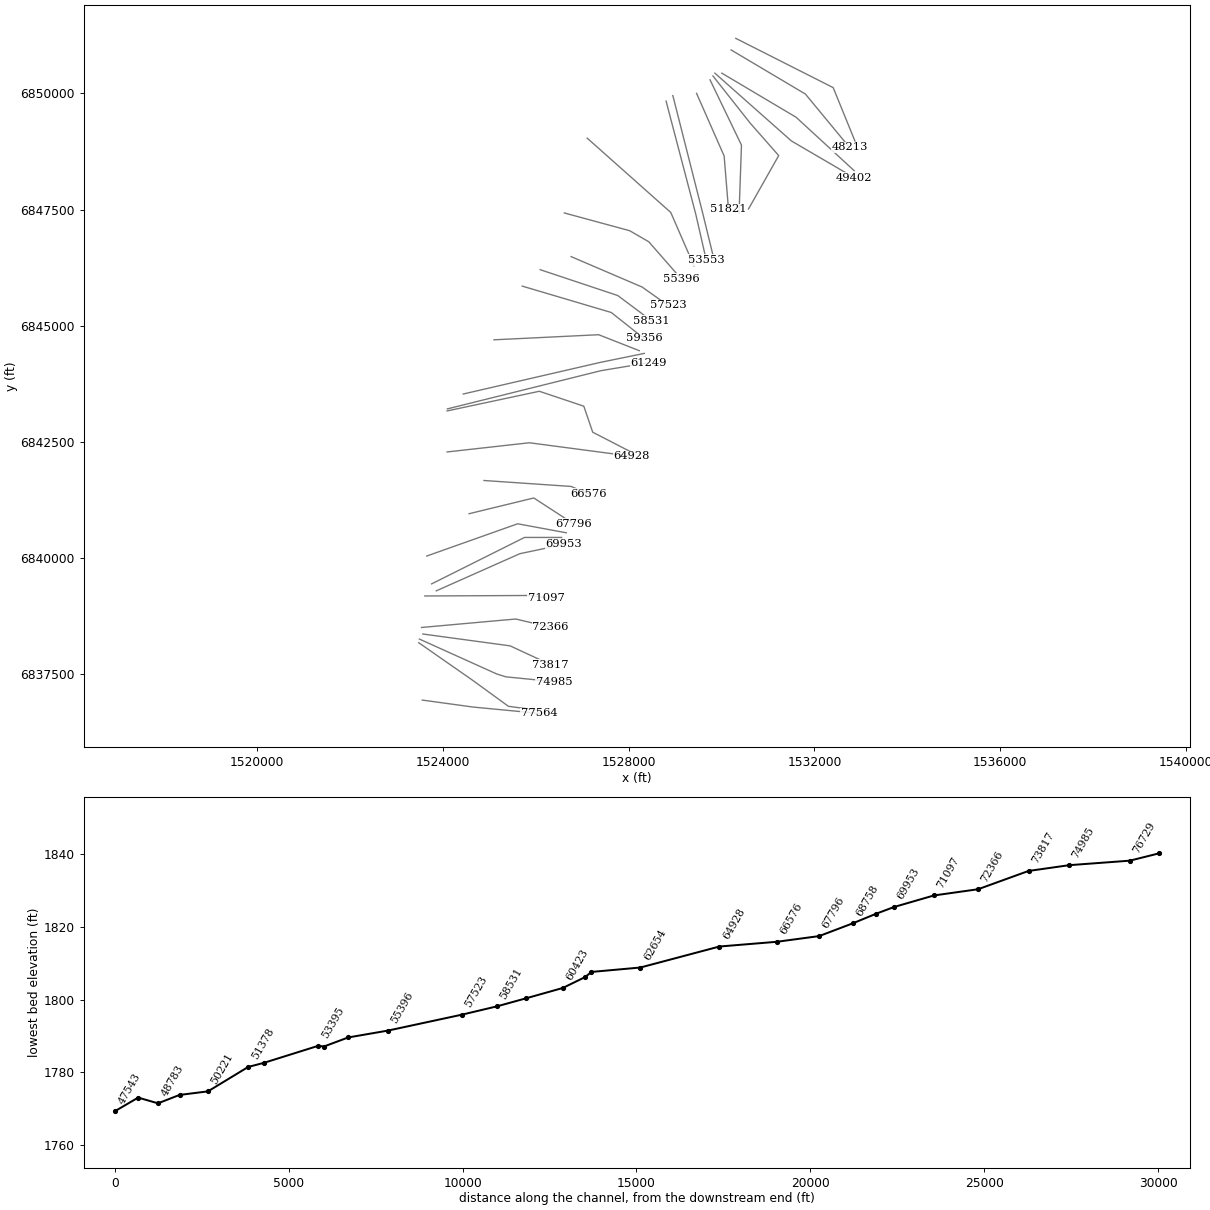
HEC-RAS study BULL WAGON CREEK.prj: BULL WAGON CREEK Base Level Engineering

--- BULL WAGON CREEK.g01 (geometry) --- (continued)

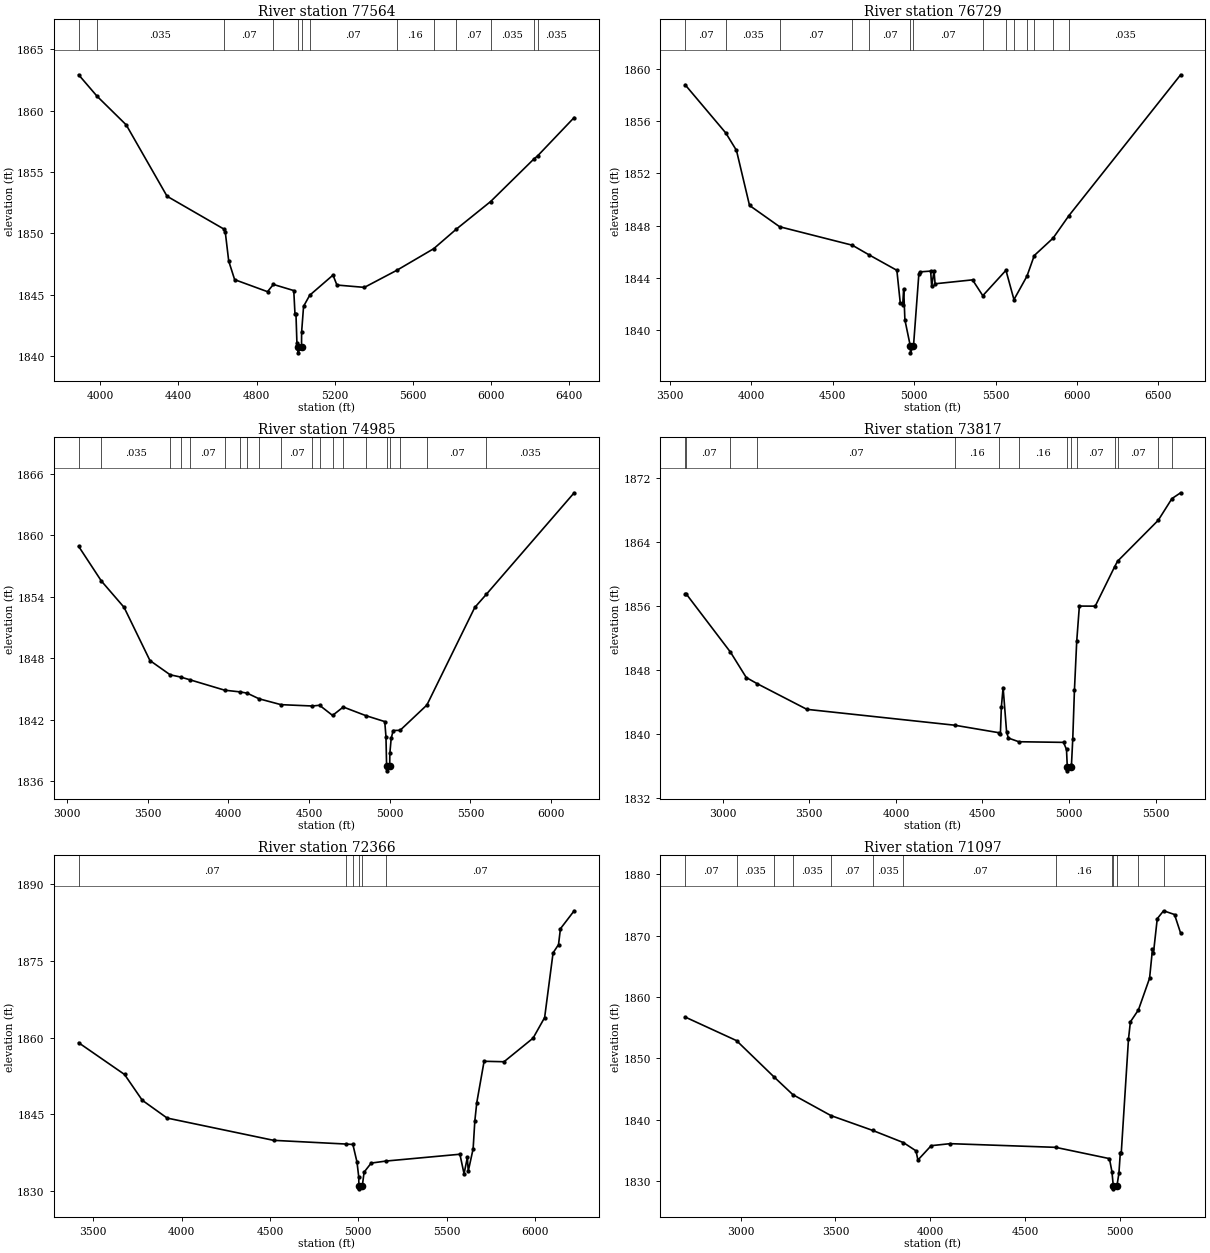
Type RM Length L Ch R = 1 ,77564   ,835,835,835
BEGIN DESCRIPTION:
Mapping XS 7cfdf875
END DESCRIPTION:
XS GIS Cut Line= 3
      1523553.58      6836934.94      1524652.51      6836783.91
      1526074.42      6836648.49
#Sta/Elev= 30
  3888.8 1862.91  3982.8 1861.17  4132.5 1858.83  4341.6 1853.02  4632.4 1850.35
  4639.9 1850.08  4657.4 1847.74  4687.7 1846.23    4856 1845.25  4886.1 1845.84
  4990.5 1845.34  4996.8  1843.4  5001.8  1843.4  5006.6 1841.09  5011.1 1840.77
  5011.6 1840.27  5030.2 1840.77  5030.7 1841.96  5040.7 1844.06  5072.2 1844.96
  5191.4  1846.6  5211.5 1845.79  5352.1  1845.6  5519.3    1847  5707.1 1848.75
  5823.5 1850.35  5998.6 1852.59  6220.5 1856.06  6238.8  1856.3  6426.4 1859.43
#Mann= 13 ,-1 , 0
  3888.8     .07       0  3982.8    .035       0  4632.4     .07       0
  4886.1    .035       0  5011.1    .035       0  5030.2    .035       0
  5072.2     .07       0  5519.3     .16       0  5707.1    .035       0
  5823.5     .07       0  5998.6    .035       0  6220.5     .07       0
  6238.8    .035       0
Bank Sta=5011.1,5030.2
XS Rating Curve= 0 ,0
Exp/Cntr=0.3,0.1

Type RM Length L Ch R = 1 ,76729   ,1744,1744,1744
BEGIN DESCRIPTION:
Mapping XS 893149f0
END DESCRIPTION:
XS GIS Cut Line= 4
      1523476.49      6838170.35      1524627.51      6837368.28
      1525408.76      6836800.57      1526080.31      6836712.08
#Sta/Elev= 30
  3591.9 1858.77  3842.1 1855.08  3907.6 1853.75  3987.9 1849.54  4173.2 1847.91
  4619.5  1846.5  4722.9 1845.76  4893.6 1844.58  4914.6 1842.07  4929.4 1841.92
  4935.5 1843.17    4943 1840.79  4976.6 1838.77  4977.1 1838.27  4995.7 1838.77
  5028.8  1844.3  5036.4 1844.46  5101.3 1844.52  5107.5 1843.35  5122.2 1844.55
  5128.4 1843.55  5358.7 1843.85  5421.8 1842.64  5564.1 1844.58  5613.3 1842.34
  5693.2 1844.13  5738.2 1845.71  5853.8 1847.04  5950.5 1848.75  6637.9 1859.53
#Mann= 14 ,-1 , 0
  3591.9     .07       0  3842.1    .035       0  4173.2     .07       0
  4619.5    .035       0  4722.9     .07       0  4976.6     .07       0
  4995.7     .07       0  5421.8     .16       0  5564.1     .07       0
  5613.3     .16       0  5693.2     .07       0  5738.2    .035       0
  5853.8     .16       0  5950.5    .035       0
Bank Sta=4976.6,4995.7
XS Rating Curve= 0 ,0
Exp/Cntr=0.3,0.1

Type RM Length L Ch R = 1 ,74985   ,1168,1168,1168
BEGIN DESCRIPTION:
Mapping XS 0017cf08
END DESCRIPTION:
XS GIS Cut Line= 4
      1523492.07       6838248.5      1525153.55      6837498.49
      1525351.46      6837435.99      1526387.88      6837331.83
#Sta/Elev= 30
  3070.9 1858.91  3211.9 1855.53  3352.8 1852.96    3513 1847.78  3638.4 1846.39
  3703.5 1846.17  3763.9 1845.89  3976.3 1844.89  4073.9 1844.72  4115.8  1844.6
  4189.7 1844.05  4325.5 1843.48  4519.7 1843.35  4564.6 1843.42  4645.2 1842.43
  4711.6 1843.25  4849.8 1842.42  4968.7 1841.83  4976.2 1840.36  4980.1 1837.53
  4980.6 1837.03  4999.4 1837.53  5000.2 1838.72  5008.6  1840.2  5021.2 1840.96
  5063.9 1840.98  5229.8 1843.44  5526.6 1852.95  5598.8 1854.24    6143 1864.13
#Mann= 20 ,-1 , 0
  3070.9    .045       0  3211.9    .035       0  3638.4     .07       0
  3703.5    .035       0  3763.9     .07       0  3976.3    .035       0
  4073.9     .07       0  4115.8    .035       0  4189.7     .07       0
  4325.5     .07       0  4519.7     .16       0  4564.6     .07       0
  4645.2     .16       0  4711.6     .07       0  4849.8     .16       0
  4980.1     .07       0  4999.4     .07       0  5063.9     .16       0
  5229.8     .07       0  5598.8    .035       0
Bank Sta=4980.1,4999.4
XS Rating Curve= 0 ,0
Exp/Cntr=0.3,0.1

Type RM Length L Ch R = 1 ,73817   ,1451,1451,1451
BEGIN DESCRIPTION:
Mapping XS 4c0edb3b
END DESCRIPTION:
XS GIS Cut Line= 3
      1523565.03      6838357.86      1525445.21      6838102.66
       1526320.1      6837696.46
#Sta/Elev= 30
  2782.4 1857.52  2790.1 1857.47  3044.6 1850.24  3135.6 1847.08  3197.1 1846.33
  3485.7 1843.11  4339.6 1841.13  4593.5  1840.2  4603.4 1840.07    4609 1843.41
  4619.1 1845.83  4639.2  1840.3  4649.3 1839.53  4709.7 1839.07  4967.9 1838.99
  4985.2 1838.11  4989.7 1835.94  4990.2 1835.44    5009 1835.94  5013.7 1836.11
  5021.4 1839.45    5031 1845.48  5044.2 1851.59  5059.5 1855.99  5151.1 1855.98
  5263.3  1860.9  5279.9 1861.58    5515 1866.69  5594.3  1869.4  5644.4 1870.12
#Mann= 14 ,-1 , 0
  2782.4    .045       0  2790.1     .07       0  3044.6    .035       0
  3197.1     .07       0  4339.6     .16       0  4593.5     .07       0
  4709.7     .16       0  4989.7     .07       0    5009     .16       0
  5044.2     .07       0  5263.3    .035       0  5279.9     .07       0
    5515    .035       0  5594.3     .07       0
Bank Sta=4989.7,5009
XS Rating Curve= 0 ,0
Exp/Cntr=0.3,0.1

Type RM Length L Ch R = 1 ,72366   ,1269,1269,1269
BEGIN DESCRIPTION:
Mapping XS d19cd038
END DESCRIPTION:
XS GIS Cut Line= 4
      1523536.36      6838498.49      1525036.36      6838633.91
      1525567.61      6838680.78      1526311.17      6838503.99
#Sta/Elev= 30
  3417.5    1859  3677.2 1852.79  3777.6 1847.74  3918.2 1844.26  4520.6  1839.9
  4927.7 1839.18  4969.2 1839.09  4992.5 1835.64  5002.5 1832.68  5002.9 1830.91
  5003.4 1830.41  5022.2 1830.91  5032.7 1833.68  5072.8 1835.45  5157.4 1835.85
  5574.7 1837.18  5598.1 1833.36  5616.9 1836.55    5622 1833.88  5649.5 1838.24
  5659.1 1843.68  5670.1 1847.27  5711.5 1855.37  5824.3 1855.28  5988.7  1859.9
  6054.1 1863.93  6101.8 1876.58  6132.6  1878.2  6143.5 1881.31  6221.2 1884.82
#Mann= 6 ,-1 , 0
  3417.5     .07       0  4927.7    .035       0  4969.2     .16       0
  5002.9     .07       0  5022.2     .16       0  5157.4     .07       0
Bank Sta=5002.9,5022.2
XS Rating Curve= 0 ,0
Exp/Cntr=0.3,0.1

Type RM Length L Ch R = 1 ,71097   ,1144,1144,1144
BEGIN DESCRIPTION:
BULL WAGON CREEK 61.0
END DESCRIPTION:
XS GIS Cut Line= 3
      1523607.53      6839177.31        1525905.        6839188.
      1526216.96      6839140.85
#Sta/Elev= 30
  2707.1 1856.73  2978.2 1852.88  3176.2 1846.95  3275.1 1844.07  3476.1 1840.65
  3695.3 1838.24  3858.5 1836.24  3924.6  1834.9  3934.7  1833.4  4004.6 1835.74
  4104.6 1836.07  4660.9 1835.47  4944.6 1833.63  4957.8 1831.51  4964.9  1829.2
  4965.4  1828.7  4984.3  1829.2  4994.6 1831.23  5002.1 1834.62  5007.1 1834.62
  5045.1 1853.13  5055.2 1855.94  5097.5 1857.89  5156.3 1863.06  5171.7  1867.8
  5176.7 1867.15  5196.8 1872.77  5230.2 1874.06  5287.8 1873.45  5320.1 1870.41
#Mann= 13 ,-1 , 0
  2707.1     .07       0  2978.2    .035       0  3176.2     .07       0
  3275.1    .035       0  3476.1     .07       0  3695.3    .035       0
  3858.5     .07       0  4660.9     .16       0  4957.8     .07       0
  4964.9     .07       0  4984.3     .07       0  5097.5    .035       0
  5230.2     .07       0
Bank Sta=4964.9,4984.3
XS Rating Curve= 0 ,0
Exp/Cntr=0.3,0.1

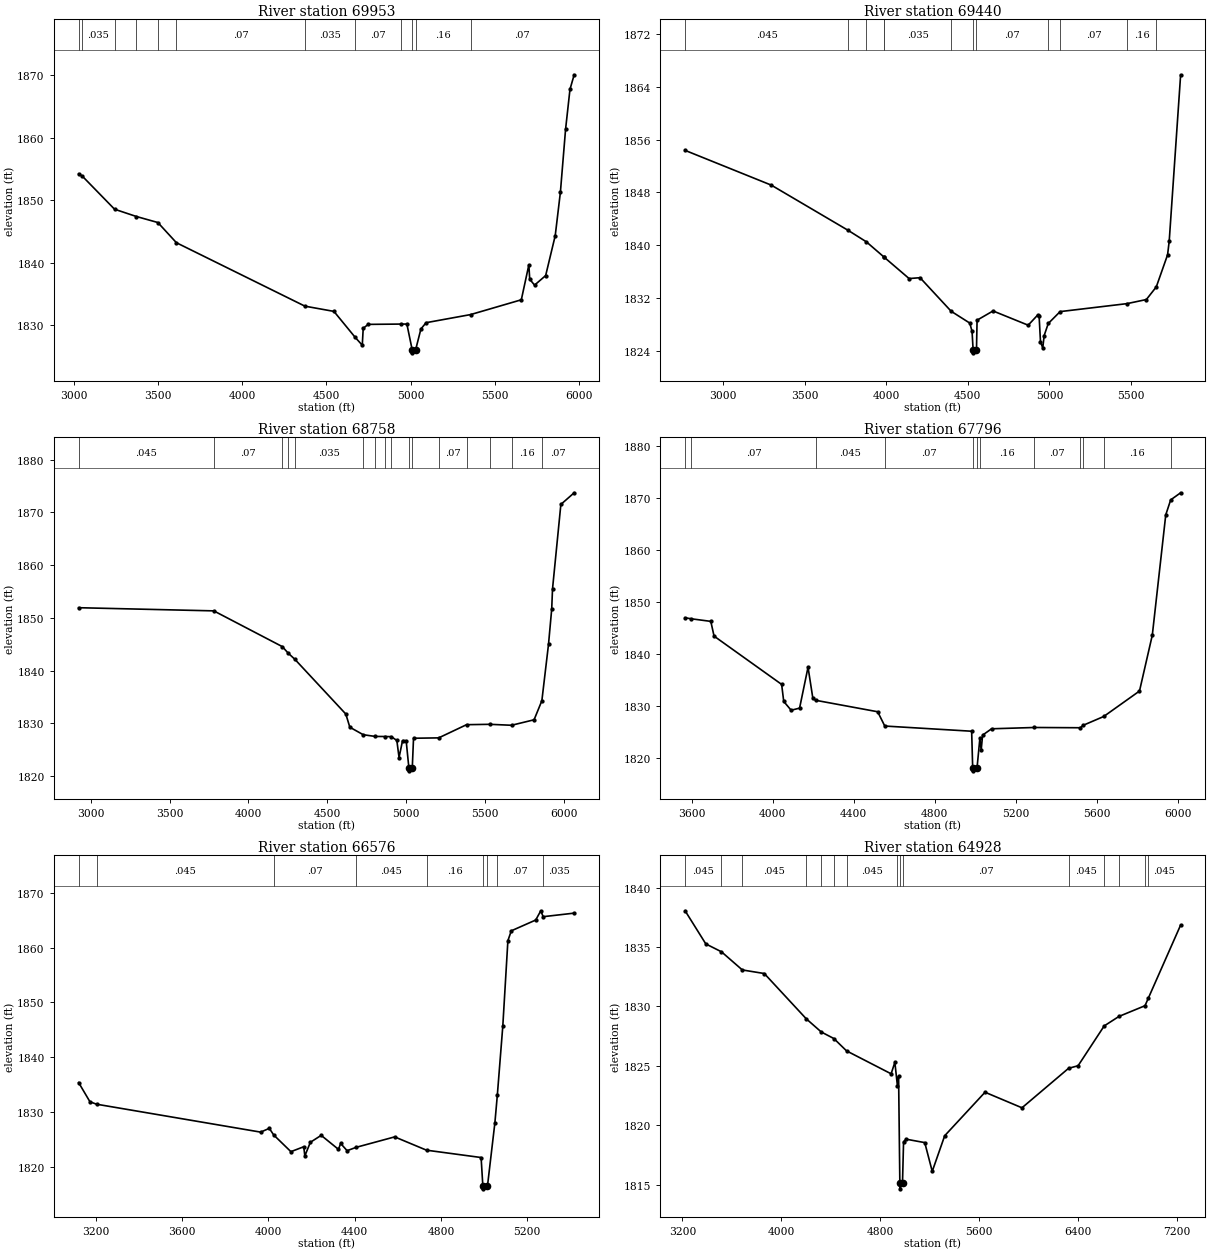
Type RM Length L Ch R = 1 ,69953   ,513,513,513
BEGIN DESCRIPTION:
BULL WAGON CREEK 59.0
END DESCRIPTION:
XS GIS Cut Line= 3
      1523854.98      6839287.99        1525655.        6840088.
      1526604.98        6840288.
#Sta/Elev= 30
  3030.2 1854.21  3052.4 1853.83  3243.4 1848.54  3373.4 1847.37  3500.3 1846.41
  3610.6 1843.17    4373 1833.01  4545.2 1832.17    4671 1828.02  4713.4 1826.75
  4718.9 1829.46  4748.3 1830.09  4944.5 1830.14  4978.1 1830.14  5009.4 1826.03
  5009.9 1825.53  5030.1 1826.03  5061.3 1829.35    5092 1830.36  5356.3 1831.66
  5657.2 1834.03  5701.9 1839.63    5707 1837.32  5735.8 1836.38  5801.6 1837.91
  5858.4 1844.31  5889.1 1851.28  5919.7 1861.33  5945.9 1867.75  5970.8 1870.08
#Mann= 12 ,-1 , 0
  3030.2     .07       0  3052.4    .035       0  3243.4     .07       0
  3373.4    .035       0  3500.3    .045       0  3610.6     .07       0
    4373    .035       0    4671     .07       0  4944.5     .16       0
  5009.4     .07       0  5030.1     .16       0  5356.3     .07       0
Bank Sta=5009.4,5030.1
XS Rating Curve= 0 ,0
Exp/Cntr=0.3,0.1

Type RM Length L Ch R = 1 ,69440   ,682,682,682
BEGIN DESCRIPTION:
BULL WAGON CREEK 58.0
END DESCRIPTION:
XS GIS Cut Line= 3
      1523754.96      6839437.98        1525755.        6840438.
      1526554.98        6840438.
#Sta/Elev= 30
  2767.5 1854.38  3295.8 1849.11  3767.6 1842.24    3878 1840.52  3987.2 1838.19
  3987.9 1838.17  4139.9 1834.95    4207 1835.08  4397.7 1829.99  4511.7  1828.2
  4525.7 1826.94    4532 1824.19  4532.5 1823.69  4552.8 1824.19  4556.4 1828.64
  4654.2 1830.04  4869.5 1827.88  4928.1 1829.43  4936.5 1829.27  4944.9 1825.36
  4958.9 1824.43  4967.3  1826.3  4992.6 1828.14  5065.2 1829.94  5475.4 1831.15
  5593.6 1831.77  5654.5 1833.69  5723.6 1838.55  5733.6 1840.63  5803.6 1865.84
#Mann= 12 ,-1 , 0
  2767.5    .045       0  3767.6     .07       0    3878    .035       0
  3987.2     .07       0  3987.9    .035       0  4397.7     .07       0
    4532     .07       0  4552.8     .07       0  4992.6     .16       0
  5065.2     .07       0  5475.4     .16       0  5654.5     .07       0
Bank Sta=4532,4552.8
XS Rating Curve= 0 ,0
Exp/Cntr=0.3,0.1

Type RM Length L Ch R = 1 ,68758   ,962,962,962
BEGIN DESCRIPTION:
BULL WAGON CREEK 57.0
END DESCRIPTION:
XS GIS Cut Line= 3
      1523650.04      6840037.54      1525607.46      6840732.13
      1526655.02        6840538.
#Sta/Elev= 30
    2923 1851.94    3780 1851.34  4214.7 1844.56    4252 1843.32  4293.5 1842.18
  4617.3 1831.78  4642.8 1829.28  4727.7 1827.86  4804.1 1827.53  4863.9 1827.52
  4905.7 1827.49  4940.9 1826.77  4954.9 1823.53  4977.1 1826.74    5000 1826.72
  5017.4 1821.51  5017.9 1821.01  5038.7 1821.51  5046.7 1827.19  5206.2 1827.26
  5382.9 1829.76  5530.6 1829.83  5668.2 1829.65  5811.1 1830.69  5860.5  1834.3
  5902.7    1845    5923 1851.71  5928.1 1855.51    5981 1871.52  6065.4 1873.73
#Mann= 16 ,-1 , 0
    2923    .045       0    3780     .07       0  4214.7    .035       0
    4252     .07       0  4293.5    .035       0  4727.7     .07       0
  4804.1     .16       0  4863.9    .035       0  4905.7     .16       0
  5017.4     .07       0  5038.7     .16       0  5206.2     .07       0
  5382.9     .16       0  5530.6     .07       0  5668.2     .16       0
  5860.5     .07       0
Bank Sta=5017.4,5038.7
XS Rating Curve= 0 ,0
Exp/Cntr=0.3,0.1

Type RM Length L Ch R = 1 ,67796   ,1220,1220,1220
BEGIN DESCRIPTION:
BULL WAGON CREEK 56.0
END DESCRIPTION:
XS GIS Cut Line= 3
      1524561.56      6840949.02        1525955.        6841288.
      1526805.49      6840735.45
#Sta/Elev= 30
    3567    1847  3597.1 1846.81    3694 1846.31  3710.1 1843.47    4044 1834.17
  4054.3 1830.89  4090.9 1829.19  4132.6  1829.6  4174.4 1837.48  4198.3 1831.47
  4213.3  1831.1  4518.5  1828.9  4553.5 1826.15  4982.8 1825.15  4987.9 1818.02
  4988.4 1817.52  5009.2 1818.02  5023.4 1823.77  5029.8 1821.52  5036.9  1824.4
  5081.1 1825.62  5292.6 1825.87  5520.1 1825.82  5533.1 1826.28  5635.3 1827.99
    5812 1832.89  5875.3 1843.65  5941.8 1866.83  5966.1 1869.71  6015.3 1871.08
#Mann= 12 ,-1 , 0
    3567    .045       0  3597.1     .07       0  4213.3    .045       0
  4553.5     .07       0  4987.9     .07       0  5009.2     .07       0
  5023.4     .16       0  5292.6     .07       0  5520.1     .16       0
  5533.1     .07       0  5635.3     .16       0  5966.1     .07       0
Bank Sta=4987.9,5009.2
XS Rating Curve= 0 ,0
Exp/Cntr=0.3,0.1

Type RM Length L Ch R = 1 ,66576   ,1648,1648,1648
BEGIN DESCRIPTION:
BULL WAGON CREEK 55.0
END DESCRIPTION:
XS GIS Cut Line= 3
      1524882.74      6841664.29      1526758.79      6841536.43
      1527143.13      6841372.62
#Sta/Elev= 30
  3119.6 1835.36    3172 1831.86  3202.5 1831.41  3963.8 1826.31  4003.9    1827
  4024.3 1825.79  4104.1 1822.74  4163.7 1823.64  4168.7 1821.96  4194.3 1824.45
  4244.5 1825.72  4324.7 1823.16  4334.7 1824.24  4364.7 1822.92  4406.5 1823.53
  4585.3 1825.44    4733 1823.01  4986.2 1821.67  4994.3 1816.45  4994.8 1815.95
  5015.7 1816.45  5050.2 1828.05  5061.4 1833.05  5086.8 1845.68  5110.4 1861.28
  5126.3 1863.08  5239.4 1865.05    5263 1866.74    5274 1865.66  5417.8 1866.31
#Mann= 9 ,-1 , 0
  3119.6     .07       0  3202.5    .045       0  4024.3     .07       0
  4406.5    .045       0    4733     .16       0  4994.3     .07       0
  5015.7     .16       0  5061.4     .07       0    5274    .035       0
Bank Sta=4994.3,5015.7
XS Rating Curve= 0 ,0
Exp/Cntr=0.3,0.1

Type RM Length L Ch R = 1 ,64928   ,2274,2274,2274
BEGIN DESCRIPTION:
BULL WAGON CREEK 54.0
END DESCRIPTION:
XS GIS Cut Line= 3
      1524088.29       6842279.3      1525859.17      6842477.22
      1528067.48      6842185.56
#Sta/Elev= 30
  3221.8 1838.05  3389.5 1835.26  3515.9  1834.6  3684.9 1833.07  3862.5 1832.77
    4202 1828.96  4323.6 1827.85  4425.2  1827.3  4528.1 1826.26  4888.8 1824.33
    4919  1825.3  4939.9  1823.3  4949.2 1824.14  4959.3 1815.15  4959.8 1814.65
  4980.8 1815.15  4989.4  1818.6  5009.6 1818.83  5160.9 1818.54  5221.4 1816.12
  5322.3 1819.12  5648.5 1822.78  5947.5 1821.47  6324.1 1824.79  6401.6 1825.01
  6612.7 1828.36  6732.4 1829.16  6942.9 1830.06  6968.7 1830.67  7231.2 1836.85
#Mann= 15 ,-1 , 0
  3221.8    .045       0  3515.9     .07       0  3684.9    .045       0
    4202    .035       0  4323.6    .045       0  4425.2     .07       0
  4528.1    .045       0  4939.9     .07       0  4959.3     .07       0
  4980.8     .07       0  6324.1    .045       0  6612.7    .035       0
  6732.4    .045       0  6942.9     .07       0  6968.7    .045       0
Bank Sta=4959.3,4980.8
XS Rating Curve= 0 ,0
Exp/Cntr=0.3,0.1

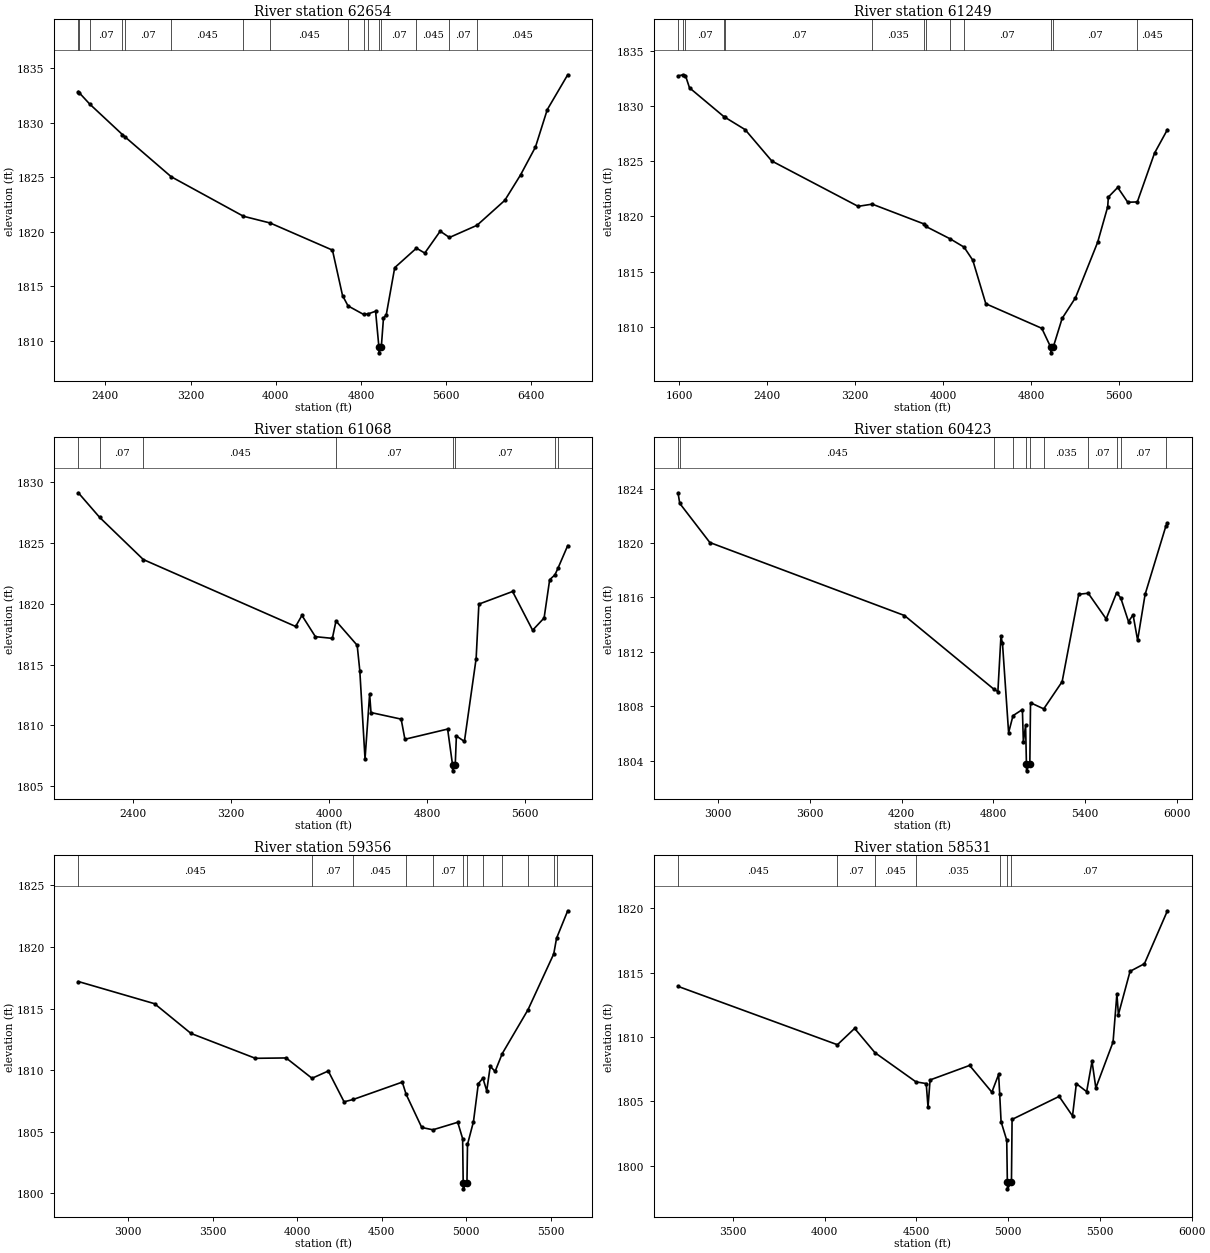
Type RM Length L Ch R = 1 ,62654   ,1405,1405,1405
BEGIN DESCRIPTION:
Mapping XS 59ba645b
END DESCRIPTION:
XS GIS Cut Line= 5
      1524087.94      6843162.56      1526074.01      6843586.17
      1527032.13      6843264.98      1527224.08      6842704.74
      1528078.28      6842263.75
#Sta/Elev= 30
  2146.1 1832.86  2156.7 1832.73  2252.1 1831.72  2560.2 1828.91  2586.6 1828.68
  3017.8 1825.04  3696.6 1821.41  3947.6 1820.79  4532.1  1818.3  4626.7 1814.13
  4678.4 1813.18  4823.7  1812.4  4868.2 1812.45    4937 1812.69  4968.5 1809.37
    4969 1808.87  4990.5 1809.37  5011.1 1812.06  5036.9 1812.34  5116.6 1816.69
  5320.5 1818.48  5398.8 1818.03  5543.6 1820.04  5630.3 1819.46  5889.3 1820.58
  6150.2 1822.87  6298.3 1825.21  6438.2 1827.77  6548.9  1831.2  6740.9  1834.4
#Mann= 16 ,-1 , 0
  2146.1     .07       0  2156.7    .045       0  2252.1     .07       0
  2560.2    .045       0  2586.6     .07       0  3017.8    .045       0
  3696.6     .07       0  3947.6    .045       0  4678.4     .07       0
  4823.7    .045       0  4868.2     .07       0  4968.5     .07       0
  4990.5     .07       0  5320.5    .045       0  5630.3     .07       0
  5889.3    .045       0
Bank Sta=4968.5,4990.5
XS Rating Curve= 0 ,0
Exp/Cntr=0.3,0.1

Type RM Length L Ch R = 1 ,61249   ,181,181,181
BEGIN DESCRIPTION:
Mapping XS a1aa0ba9
END DESCRIPTION:
XS GIS Cut Line= 3
      1524093.36      6843206.62      1527400.62      6844029.52
      1528430.91      6844201.24
#Sta/Elev= 30
  1587.5 1832.71  1634.5 1832.81    1655 1832.74  1691.9 1831.63  2006.7 1829.01
  2015.5 1828.96    2198 1827.85  2440.8 1825.01  3225.8 1820.91  3354.4 1821.11
  3824.8 1819.32  3842.9 1819.09  4065.4 1817.96    4190 1817.22  4269.1 1816.04
  4387.9  1812.1  4897.1 1809.88  4978.8 1808.16  4979.3 1807.66  5000.9 1808.16
  5081.9 1810.77  5203.5 1812.64  5405.6 1817.67  5496.8 1820.87  5502.6 1821.75
    5588 1822.62  5679.3 1821.28  5766.2 1821.31  5922.6 1825.72  6040.1 1827.85
#Mann= 13 ,-1 , 0
  1587.5     .07       0  1634.5    .045       0    1655     .07       0
  2006.7    .045       0  2015.5     .07       0  3354.4    .035       0
  3824.8    .045       0  3842.9    .035       0  4065.4    .045       0
    4190     .07       0  4978.8     .07       0  5000.9     .07       0
  5766.2    .045       0
Bank Sta=4978.8,5000.9
XS Rating Curve= 0 ,0
Exp/Cntr=0.3,0.1

Type RM Length L Ch R = 1 ,61068   ,645,645,645
BEGIN DESCRIPTION:
Mapping XS 67152aad
END DESCRIPTION:
XS GIS Cut Line= 3
      1524435.06      6843527.21      1527393.38       6844209.5
      1528336.11      6844402.21
#Sta/Elev= 30
  1952.4 1829.15  2126.1 1827.13  2483.5 1823.65  3727.8 1818.14  3779.1 1819.05
  3889.2  1817.3  4027.8 1817.16  4057.5 1818.59  4230.6 1816.59  4251.9 1814.51
  4294.7 1807.23  4332.3 1812.57  4343.5 1811.05  4589.8 1810.51  4620.6 1808.85
  4969.5 1809.69  5009.6 1806.75  5010.1 1806.25  5031.7 1806.75  5041.1 1809.12
  5106.6 1808.67  5202.4  1815.5  5224.8 1819.98  5500.2 1821.02  5663.7 1817.83
  5757.7 1818.84  5803.1 1821.99    5846 1822.39  5870.7 1822.93  5950.6  1824.8
#Mann= 8 ,-1 , 0
  1952.4    .045       0  2126.1     .07       0  2483.5    .045       0
  4057.5     .07       0  5009.6     .07       0  5031.7     .07       0
    5846     .16       0  5870.7     .07       0
Bank Sta=5009.6,5031.7
XS Rating Curve= 0 ,0
Exp/Cntr=0.3,0.1

Type RM Length L Ch R = 1 ,60423   ,1067,1067,1067
BEGIN DESCRIPTION:
Mapping XS a25bd7a5
END DESCRIPTION:
XS GIS Cut Line= 3
      1525097.37      6844694.74      1527352.59      6844804.12
      1528227.62      6844460.36
#Sta/Elev= 30
  2739.4  1823.7  2750.6 1822.92  2947.3 1820.04  4218.8 1814.67  4804.2 1809.24
  4829.5 1809.07  4849.5 1813.13  4859.5 1812.64  4899.6 1806.05  4928.4  1807.3
  4989.7 1807.75    4996 1805.36  5010.6 1806.58  5016.1 1803.74  5016.6 1803.24
  5038.3 1803.74  5042.8 1808.25  5129.2  1807.8  5249.4  1809.8  5357.8 1816.23
  5419.7 1816.31  5537.1 1814.42  5605.7 1816.35  5632.8 1815.95  5683.1 1814.22
  5712.9 1814.72  5742.6 1812.85  5791.5 1816.22  5926.8 1821.23  5937.4 1821.44
#Mann= 11 ,-1 , 0
  2739.4     .07       0  2750.6    .045       0  4804.2     .07       0
  4928.4    .045       0  5016.1    .045       0  5038.3    .045       0
  5129.2    .035       0  5419.7     .07       0  5605.7     .16       0
  5632.8     .07       0  5926.8     .16       0
Bank Sta=5016.1,5038.3
XS Rating Curve= 0 ,0
Exp/Cntr=0.3,0.1

Type RM Length L Ch R = 1 ,59356   ,825,825,825
BEGIN DESCRIPTION:
Mapping XS d1977bdf
END DESCRIPTION:
XS GIS Cut Line= 3
      1525706.71      6845851.01      1527623.42      6845283.29
      1528326.53      6844726.01
#Sta/Elev= 30
  2705.6 1817.19  3156.9 1815.39  3372.1 1812.98  3753.5 1810.96  3935.3 1810.99
  4088.5 1809.34  4184.8 1809.93  4278.3 1807.43  4332.3 1807.62  4622.8 1809.03
  4645.5 1808.04  4737.9 1805.35  4803.9 1805.16    4951 1805.77  4979.9 1804.44
  4983.2 1800.87  4983.7 1800.37  5005.5 1800.87  5008.7 1803.97    5044 1805.82
  5072.8  1808.9  5099.8 1809.35  5122.5 1808.33  5143.3 1810.31  5172.2  1809.9
  5214.3 1811.34  5366.7  1814.9  5519.1 1819.43  5535.7  1820.7  5601.8 1822.93
#Mann= 12 ,-1 , 0
  2705.6    .045       0  4088.5     .07       0  4332.3    .045       0
  4645.5     .16       0  4803.9     .07       0  4983.2     .07       0
  5005.5     .07       0  5099.8     .16       0  5214.3     .07       0
  5366.7    .035       0  5519.1     .16       0  5535.7     .07       0
Bank Sta=4983.2,5005.5
XS Rating Curve= 0 ,0
Exp/Cntr=0.3,0.1

Type RM Length L Ch R = 1 ,58531   ,1008,1008,1008
BEGIN DESCRIPTION:
Mapping XS 7382793f
END DESCRIPTION:
XS GIS Cut Line= 3
      1526092.14      6846205.17      1527764.04      6845647.87
        1528488.      6845106.21
#Sta/Elev= 30
  3201.4 1813.94  4069.8  1809.4  4163.6 1810.67  4274.5 1808.78  4497.9 1806.51
  4553.7 1806.38  4563.5 1804.55  4574.7 1806.66  4790.1 1807.79  4911.3 1805.71
  4948.2 1807.09    4954 1805.57  4961.6 1803.41  4992.4 1801.97  4995.8 1798.69
  4996.3 1798.19  5018.1 1798.69  5021.5 1803.59  5277.9 1805.38  5350.8 1803.86
  5371.7 1806.37  5427.9 1805.75  5457.1 1808.11  5477.9 1806.04  5571.7 1809.61
  5592.6 1813.35  5600.9 1811.75  5664.3 1815.11  5742.6  1815.7  5867.9 1819.82
#Mann= 7 ,-1 , 0
  3201.4    .045       0  4069.8     .07       0  4274.5    .045       0
  4497.9    .035       0    4954     .07       0  4995.8     .07       0
  5018.1     .07       0
Bank Sta=4995.8,5018.1
XS Rating Curve= 0 ,0
Exp/Cntr=0.3,0.1

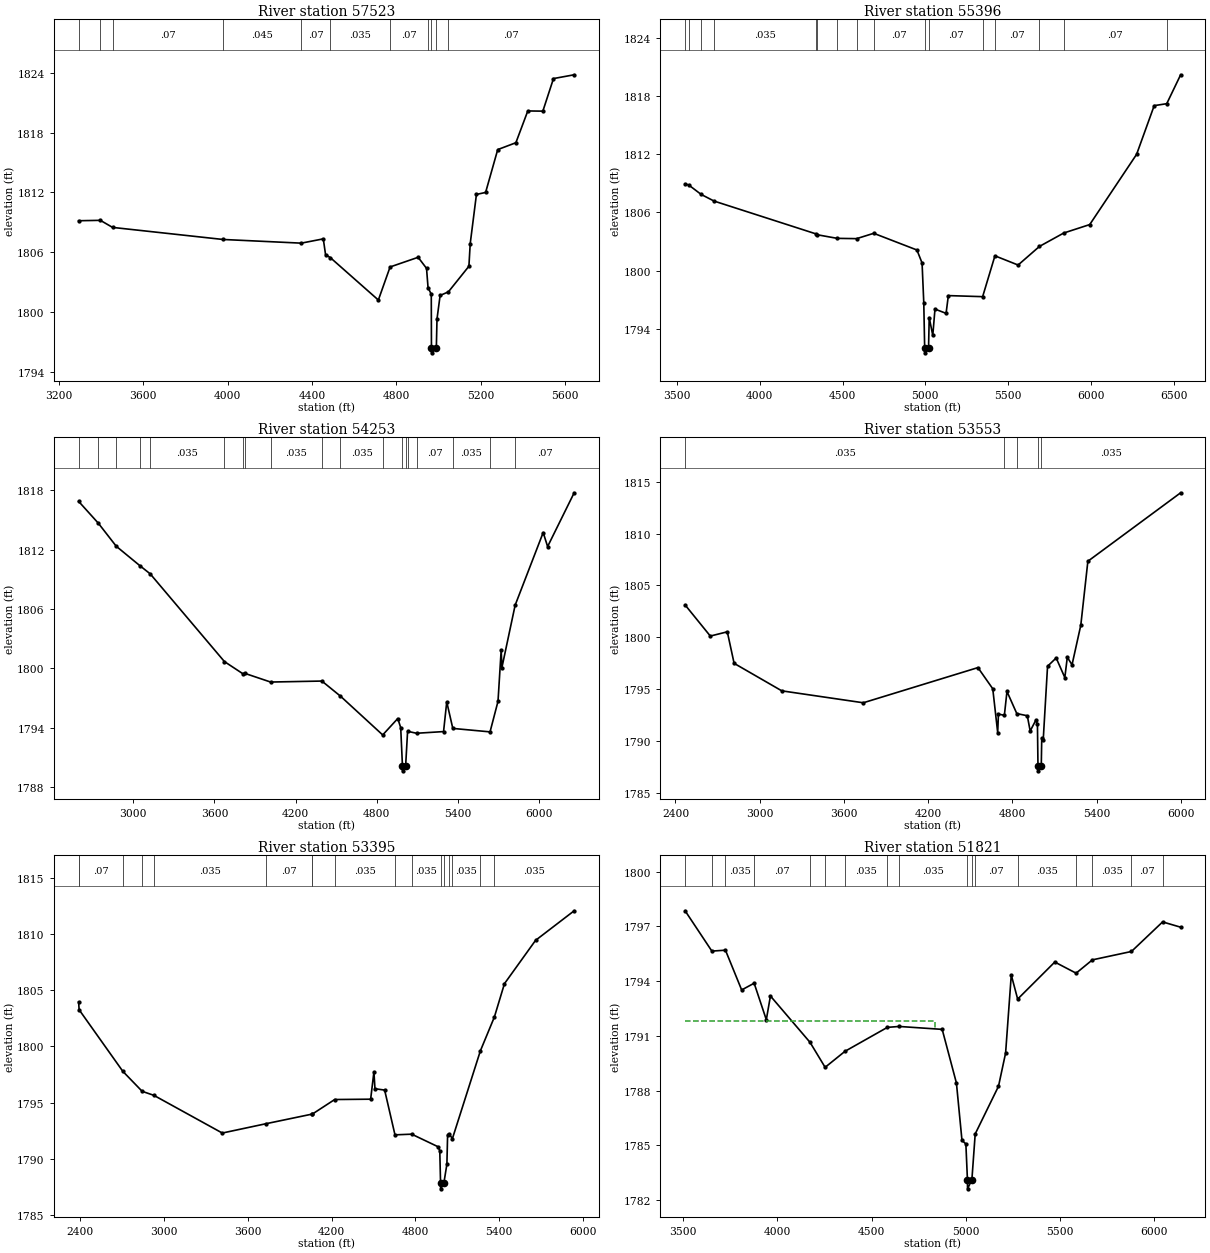
Type RM Length L Ch R = 1 ,57523   ,2127,2127,2127
BEGIN DESCRIPTION:
Mapping XS ed192094
END DESCRIPTION:
XS GIS Cut Line= 3
      1526758.83      6846486.41      1528290.09      6845830.16
      1528847.36      6845434.34
#Sta/Elev= 30
    3294 1809.16  3396.9  1809.2    3455 1808.49    3978 1807.28  4349.6 1806.91
    4454 1807.34  4464.8 1805.75  4487.2 1805.46  4715.1  1801.2  4770.7 1804.52
  4903.7 1805.49  4943.5 1804.38  4950.7 1802.44    4966 1801.78  4966.8  1796.4
  4967.3  1795.9    4990  1796.4  4993.1 1799.29  5007.9 1801.66  5047.1 1802.02
  5144.4 1804.59  5150.6 1806.86  5180.1  1811.8  5223.6    1812    5281  1816.3
  5367.1 1816.99  5423.6 1820.18    5495 1820.16  5545.4 1823.43  5643.5 1823.81
#Mann= 11 ,-1 , 0
    3294     .07       0  3396.9    .045       0    3455     .07       0
    3978    .045       0  4349.6     .07       0  4487.2    .035       0
  4770.7     .07       0  4950.7     .16       0  4966.8     .07       0
    4990     .16       0  5047.1     .07       0
Bank Sta=4966.8,4990
XS Rating Curve= 0 ,0
Exp/Cntr=0.3,0.1

Type RM Length L Ch R = 1 ,55396   ,1143,1143,1143
BEGIN DESCRIPTION:
Mapping XS d1a2063c
END DESCRIPTION:
XS GIS Cut Line= 4
      1526613.09       6847426.8      1528019.32      6847044.86
      1528431.65      6846806.14      1529130.24      6846007.75
#Sta/Elev= 30
  3548.4 1808.92  3569.5 1808.83  3645.2 1807.85  3723.9 1807.16  4339.4 1803.78
  4344.1  1803.7  4467.5 1803.32  4584.9 1803.29  4688.3 1803.84  4949.3 1802.12
  4980.4 1800.78  4990.7  1796.7  4996.1 1792.02  4996.6 1791.52  5019.5 1792.02
  5023.6 1795.16  5045.1 1793.31  5058.4 1796.03  5125.5 1795.59  5139.2 1797.42
  5346.4 1797.31  5420.7 1801.52  5560.7 1800.57  5689.8 1802.49  5836.5 1803.87
  5993.5 1804.74  6276.8 1811.98  6383.1    1817  6458.9  1817.2  6542.9 1820.18
#Mann= 16 ,-1 , 0
  3548.4     .07       0  3569.5    .035       0  3645.2     .07       0
  3723.9    .035       0  4339.4     .07       0  4344.1    .035       0
  4467.5     .07       0  4584.9    .035       0  4688.3     .07       0
  4996.1     .07       0  5019.5     .07       0  5346.4     .16       0
  5420.7     .07       0  5689.8     .16       0  5836.5     .07       0
  6458.9    .035       0
Bank Sta=4996.1,5019.5
XS Rating Curve= 0 ,0
Exp/Cntr=0.3,0.1

Type RM Length L Ch R = 1 ,54253   ,700,700,700
BEGIN DESCRIPTION:
BULL WAGON CREEK 45.0
END DESCRIPTION:
XS GIS Cut Line= 3
        1527105.        6849038.        1528905.        6847438.
        1529405.      6846288.01
#Sta/Elev= 30
  2596.6 1816.88  2741.7 1814.68  2874.8 1812.34  3051.7 1810.35  3125.6 1809.55
    3674 1800.68  3809.2 1799.46  3826.5 1799.48  4015.4 1798.61  4394.3 1798.71
  4531.9 1797.18  4843.8 1793.26  4955.2 1794.92  4976.9    1794  4989.8 1790.13
  4990.3 1789.63  5013.3 1790.13  5027.8 1793.63  5093.7 1793.43  5293.6  1793.6
  5317.1  1796.6    5362 1793.92  5637.2 1793.57    5696 1796.66  5719.4 1801.84
  5724.9 1800.08  5822.6 1806.38  6029.9 1813.73  6062.6 1812.31  6258.9 1817.75
#Mann= 19 ,-1 , 0
  2596.6    .035       0  2741.7     .07       0  2874.8    .035       0
  3051.7     .07       0  3125.6    .035       0    3674     .07       0
  3809.2    .035       0  3826.5     .07       0  4015.4    .035       0
  4394.3     .07       0  4531.9    .035       0  4843.8     .07       0
  4989.8     .07       0  5013.3     .07       0  5027.8    .035       0
  5093.7     .07       0    5362    .035       0  5637.2     .16       0
  5822.6     .07       0
Bank Sta=4989.8,5013.3
XS Rating Curve= 0 ,0
Exp/Cntr=0.3,0.1

Type RM Length L Ch R = 1 ,53553   ,158,158,158
BEGIN DESCRIPTION:
Mapping XS c4fa3b05
END DESCRIPTION:
XS GIS Cut Line= 3
      1528804.15      6849835.75      1529445.54      6847392.95
      1529669.51      6846413.74
#Sta/Elev= 30
  2468.8 1803.12  2648.4 1800.12  2769.5 1800.53    2818 1797.49  3157.6 1794.84
  3738.2 1793.69  4554.9 1797.08  4660.5 1795.04  4695.7 1790.81  4700.9  1792.6
  4743.2 1792.48  4761.7 1794.78  4831.7 1792.65  4906.5 1792.44  4927.1 1790.97
    4968 1792.03  4978.8 1791.62  4982.6 1787.63  4983.1 1787.13  5006.1 1787.63
  5009.5 1790.29    5020 1790.11  5050.8 1797.21  5112.3 1798.01  5173.9 1796.12
  5191.5 1798.08  5225.2 1797.35  5287.7 1801.17    5338 1807.33  5998.9 1813.93
#Mann= 5 ,-1 , 0
  2468.8    .035       0  4743.2     .07       0  4831.7    .035       0
  4982.6    .035       0  5006.1    .035       0
#XS Ineff= 2 , 0
       0  4554.9 1797.08               0
Permanent Ineff=
       F       F
Bank Sta=4982.6,5006.1
XS Rating Curve= 0 ,0
Exp/Cntr=0.3,0.1

Type RM Length L Ch R = 1 ,53395   ,1574,1574,1574
BEGIN DESCRIPTION:
Mapping XS 9edd8d9e
END DESCRIPTION:
XS GIS Cut Line= 3
      1528950.01      6849955.45      1529591.37      6847429.41
       1529815.3      6846512.86
#Sta/Elev= 30
  2388.5 1803.95  2392.1 1803.26  2705.5 1797.78  2843.5 1796.01  2927.8 1795.65
  3417.6  1792.3  3730.8 1793.13    4063 1793.99  4063.1 1793.99  4222.8 1795.28
  4480.3 1795.31  4503.8 1797.74  4511.2 1796.24  4580.5 1796.12  4654.6 1792.14
  4774.3  1792.2  4965.2 1791.07  4975.5  1790.7  4981.1 1787.84  4981.6 1787.34
  5004.6 1787.84  5026.5 1789.53  5031.6 1792.14    5042 1792.22  5066.1 1791.81
  5266.4 1799.61  5366.5 1802.61  5438.8 1805.58  5661.6 1809.43  5938.2 1812.06
#Mann= 17 ,-1 , 0
  2388.5    .035       0  2392.1     .07       0  2705.5    .035       0
  2843.5     .07       0  2927.8    .035       0  3730.8     .07       0
    4063    .035       0  4063.1     .07       0  4222.8    .035       0
  4654.6     .07       0  4774.3    .035       0  4981.1    .035       0
  5004.6    .035       0    5042     .07       0  5066.1    .035       0
  5266.4     .07       0  5366.5    .035       0
#XS Ineff= 2 , 0
       0  4503.8 1797.74               0
Permanent Ineff=
       F       F
Bank Sta=4981.1,5004.6
XS Rating Curve= 0 ,0
Exp/Cntr=0.3,0.1

Type RM Length L Ch R = 1 ,51821   ,443,443,443
BEGIN DESCRIPTION:
Mapping XS 1fecd4a7
END DESCRIPTION:
XS GIS Cut Line= 3
      1529461.18      6850002.29      1530054.91      6848653.37
      1530148.64      6847502.69
#Sta/Elev= 30
  3510.7 1797.86  3652.7 1795.65  3724.8  1795.7  3810.7 1793.52  3876.9 1793.89
  3941.5 1791.89  3963.3 1793.19  4173.3 1790.65  4253.4 1789.28  4359.1 1790.16
  4583.5 1791.47  4645.9 1791.52  4874.3 1791.36  4949.8 1788.42  4979.2 1785.28
  4999.9 1785.08  5008.2 1783.12  5008.7 1782.62  5031.8 1783.12  5049.4 1785.63
  5172.9 1788.24  5210.6 1790.06  5240.7 1794.34  5274.6 1793.02  5471.5 1795.05
  5584.6 1794.44    5671 1795.17  5878.2 1795.63  6043.4 1797.25    6139 1796.96
#Mann= 17 ,-1 , 0
  3510.7    .035       0  3652.7     .07       0  3724.8    .035       0
  3876.9     .07       0  4173.3    .035       0  4253.4     .07       0
  4359.1    .035       0  4583.5     .07       0  4645.9    .035       0
  5008.2    .035       0  5031.8    .035       0  5049.4     .07       0
  5274.6    .035       0  5584.6     .07       0    5671    .035       0
  5878.2     .07       0  6043.4    .035       0
#XS Ineff= 2 , 0
       0  4837.4 1791.81               0
Permanent Ineff=
       F       F
Bank Sta=5008.2,5031.8
XS Rating Curve= 0 ,0
Exp/Cntr=0.3,0.1

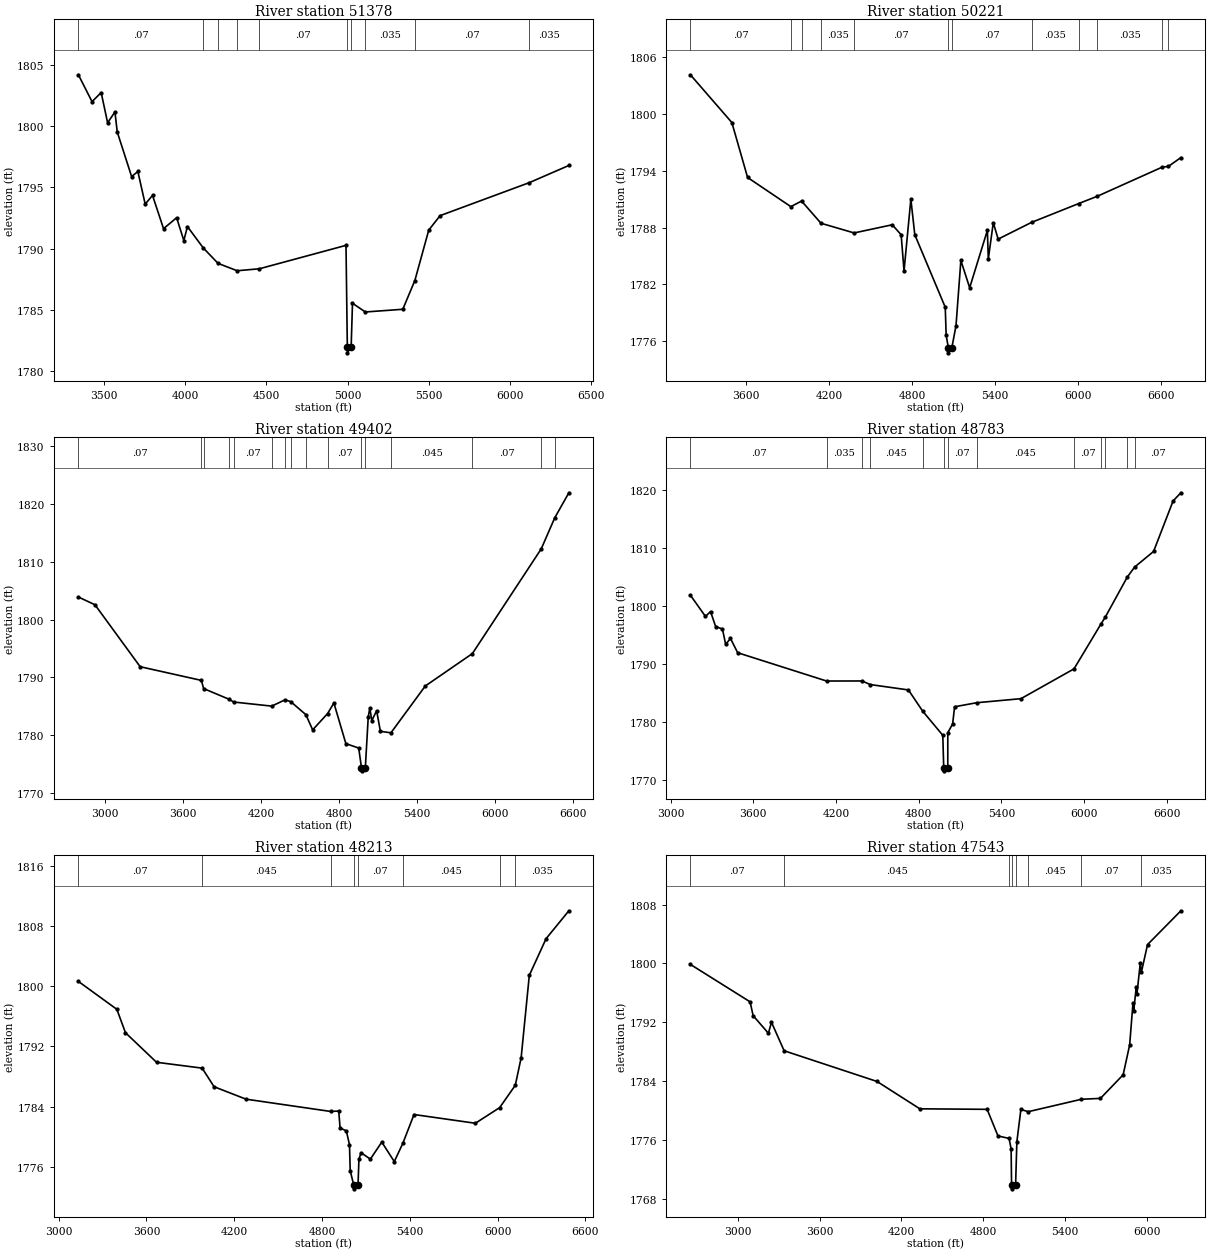
Type RM Length L Ch R = 1 ,51378   ,1157,1157,1157
BEGIN DESCRIPTION:
Mapping XS 45a8a54b
END DESCRIPTION:
XS GIS Cut Line= 3
      1529751.09      6850293.99      1530428.18      6848887.74
       1530376.1      6847424.23
#Sta/Elev= 30
  3339.9 1804.18  3424.1 1801.99  3480.5 1802.73  3520.2 1800.27  3565.4 1801.15
  3579.6 1799.52  3668.4 1795.88  3706.7  1796.3    3752 1793.64  3797.2 1794.35
  3865.1 1791.64  3945.9 1792.53  3990.3 1790.67  4012.5 1791.81  4110.7 1790.06
  4201.5 1788.81  4319.1 1788.21  4455.9 1788.37  4990.5 1790.28  4998.7 1782.02
  4999.2 1781.52  5022.3 1782.02  5030.5 1785.56  5109.8 1784.85  5340.7 1785.07
  5415.1 1787.41  5500.8 1791.52  5570.8  1792.7  6121.1 1795.39  6365.1 1796.79
#Mann= 10 ,-1 , 0
  3339.9     .07       0  4110.7    .035       0  4201.5     .07       0
  4319.1    .035       0  4455.9     .07       0  4998.7     .07       0
  5022.3     .07       0  5109.8    .035       0  5415.1     .07       0
  6121.1    .035       0
#XS Ineff= 2 , 0
       0  4990.5 1790.28               0
Permanent Ineff=
       F       F
Bank Sta=4998.7,5022.3
XS Rating Curve= 0 ,0
Exp/Cntr=0.3,0.1

Type RM Length L Ch R = 1 ,50221   ,819,819,819
BEGIN DESCRIPTION:
Mapping XS 86fab2ec
END DESCRIPTION:
XS GIS Cut Line= 4
      1529813.58      6850377.35      1530615.68       6849361.7
        1531230.        6848663.      1530580.01      6847513.02
#Sta/Elev= 30
  3197.9 1804.09  3497.6 1799.06  3611.4 1793.27  3924.1  1790.2  4001.6 1790.79
  4141.8 1788.45  4381.4 1787.43  4656.8 1788.29  4721.3 1787.24  4742.1 1783.43
  4791.5 1790.99    4820 1787.24  5040.1  1779.6  5046.7 1776.65    5063  1775.3
  5063.5  1774.8  5087.3  1775.3  5117.9 1777.67    5153 1784.53  5216.6 1781.66
  5344.6  1787.7  5351.3 1784.69  5387.3 1788.51  5422.4 1786.78  5663.7 1788.54
  6003.9 1790.52  6140.2  1791.3  6609.5 1794.37    6652 1794.43  6743.4 1795.37
#Mann= 12 ,-1 , 0
  3197.9     .07       0  3924.1    .035       0  4001.6     .07       0
  4141.8    .035       0  4381.4     .07       0    5063     .07       0
  5087.3     .07       0  5663.7    .035       0  6003.9     .07       0
  6140.2    .035       0  6609.5     .07       0    6652    .035       0
Bank Sta=5063,5087.3
XS Rating Curve= 0 ,0
Exp/Cntr=0.3,0.1

Type RM Length L Ch R = 1 ,49402   ,619,619,619
BEGIN DESCRIPTION:
BULL WAGON CREEK 41.0
END DESCRIPTION:
XS GIS Cut Line= 3
      1529855.01      6850437.99      1531504.06      6848977.52
      1532854.98      6848188.01
#Sta/Elev= 30
  2797.2 1803.89  2924.7 1802.55  3271.8 1791.83  3742.3 1789.46  3758.9 1788.05
  3957.4 1786.17  3989.1 1785.72  4282.3 1785.01  4383.7 1786.09    4428 1785.79
  4544.6 1783.53  4596.7  1780.9  4711.4 1783.72  4759.8 1785.55  4851.8 1778.52
  4950.5 1777.75  4971.8 1774.31  4972.3 1773.81  5001.2 1774.31  5023.6 1783.14
  5035.8 1784.69  5050.9  1782.5  5088.1 1784.22  5116.9 1780.65    5198 1780.39
  5461.7 1788.49  5823.5  1794.1  6352.8 1812.24    6456 1817.59  6564.7 1821.93
#Mann= 16 ,-1 , 0
  2797.2     .07       0  3742.3    .035       0  3758.9     .07       0
  3957.4    .035       0  3989.1     .07       0  4282.3    .035       0
  4383.7     .07       0    4428    .035       0  4544.6    .045       0
  4711.4     .07       0  4971.8     .07       0  5001.2     .07       0
    5198    .045       0  5823.5     .07       0  6352.8    .035       0
    6456     .07       0
Bank Sta=4971.8,5001.2
XS Rating Curve= 0 ,0
Exp/Cntr=0.3,0.1

Type RM Length L Ch R = 1 ,48783   ,570,570,570
BEGIN DESCRIPTION:
BULL WAGON CREEK 40.0
END DESCRIPTION:
XS GIS Cut Line= 3
      1530004.98      6850438.01        1531605.        6849488.
      1532854.98      6848338.02
#Sta/Elev= 30
  3143.2 1801.86  3252.3  1798.2  3289.4 1799.03  3326.4 1796.45  3375.8 1796.01
  3399.1 1793.37    3434 1794.39  3486.2 1791.92  4131.6 1787.03  4388.8 1787.04
  4448.3 1786.42  4725.3 1785.49  4829.2 1781.81  4974.8 1777.65  4981.5 1772.01
    4982 1771.51  5010.9 1772.01  5011.1 1778.11  5046.2 1779.62  5060.4 1782.58
  5220.6 1783.28  5541.9 1783.98  5926.9 1789.13  6122.9  1796.9  6152.3 1798.01
  6313.7    1805  6366.6 1806.72  6504.3 1809.42  6646.1 1818.16  6702.5 1819.56
#Mann= 13 ,-1 , 0
  3143.2     .07       0  4131.6    .035       0  4388.8     .07       0
  4448.3    .045       0  4829.2     .07       0  4981.5     .07       0
  5010.9     .07       0  5220.6    .045       0  5926.9     .07       0
  6122.9    .035       0  6152.3     .07       0  6313.7    .035       0
  6366.6     .07       0
Bank Sta=4981.5,5010.9
XS Rating Curve= 0 ,0
Exp/Cntr=0.3,0.1

Type RM Length L Ch R = 1 ,48213   ,670,670,670
BEGIN DESCRIPTION:
BULL WAGON CREEK 39.0
END DESCRIPTION:
XS GIS Cut Line= 3
      1530204.96      6850938.02        1531805.        6849988.
      1532755.02      6848837.98
#Sta/Elev= 30
    3135 1800.63  3398.1 1796.92  3456.6 1793.82    3669 1789.89    3981 1789.11
  4062.5 1786.64  4280.7 1784.99  4858.4 1783.36  4914.4 1783.41  4923.8 1781.17
  4966.6 1780.77    4988 1778.94  4992.9 1775.49    5017 1773.58  5017.5 1773.08
  5046.4 1773.58  5052.5 1776.99  5066.8 1777.88  5130.7 1777.03  5208.8 1779.29
  5294.2  1776.7  5352.6 1779.12    5429 1782.95  5848.5 1781.79  6014.6 1783.87
  6121.2 1786.83  6161.2 1790.48  6217.1 1801.44  6331.8 1806.31  6487.5 1810.01
#Mann= 8 ,-1 , 0
    3135     .07       0    3981    .045       0  4858.4     .07       0
    5017     .07       0  5046.4     .07       0  5352.6    .045       0
  6014.6     .07       0  6121.2    .035       0
Bank Sta=5017,5046.4
XS Rating Curve= 0 ,0
Exp/Cntr=0.3,0.1

Type RM Length L Ch R = 1 ,47543   ,563,563,563
BEGIN DESCRIPTION:
BULL WAGON CREEK 38.0
END DESCRIPTION:
XS GIS Cut Line= 3
      1530304.99        6851188.      1532403.24      6850126.51
      1532871.99      6848976.33
#Sta/Elev= 30
    2654 1799.87  3091.3 1794.78  3113.6  1792.9  3225.6  1790.5    3248    1792
  3340.7 1788.12  4021.6 1783.94    4335 1780.22  4828.1 1780.15  4907.3 1776.53
  4988.8 1776.19  5003.7 1774.77    5007 1769.83  5007.5 1769.33  5036.4 1769.83
  5045.8 1775.74  5075.2 1780.13  5129.4 1779.83  5518.8 1781.52  5658.2 1781.64
  5824.5 1784.85  5872.2 1788.92  5896.3 1794.58  5901.7 1793.55  5920.3 1796.73
  5925.7 1795.89  5949.7    1800  5958.4 1798.85  6003.2 1802.57  6247.5 1807.17
#Mann= 8 ,-1 , 0
    2654     .07       0  3340.7    .045       0  4988.8     .07       0
    5007     .07       0  5036.4     .07       0  5129.4    .045       0
  5518.8     .07       0  5958.4    .035       0
Bank Sta=5007,5036.4
XS Rating Curve= 0 ,0
Exp/Cntr=0.3,0.1