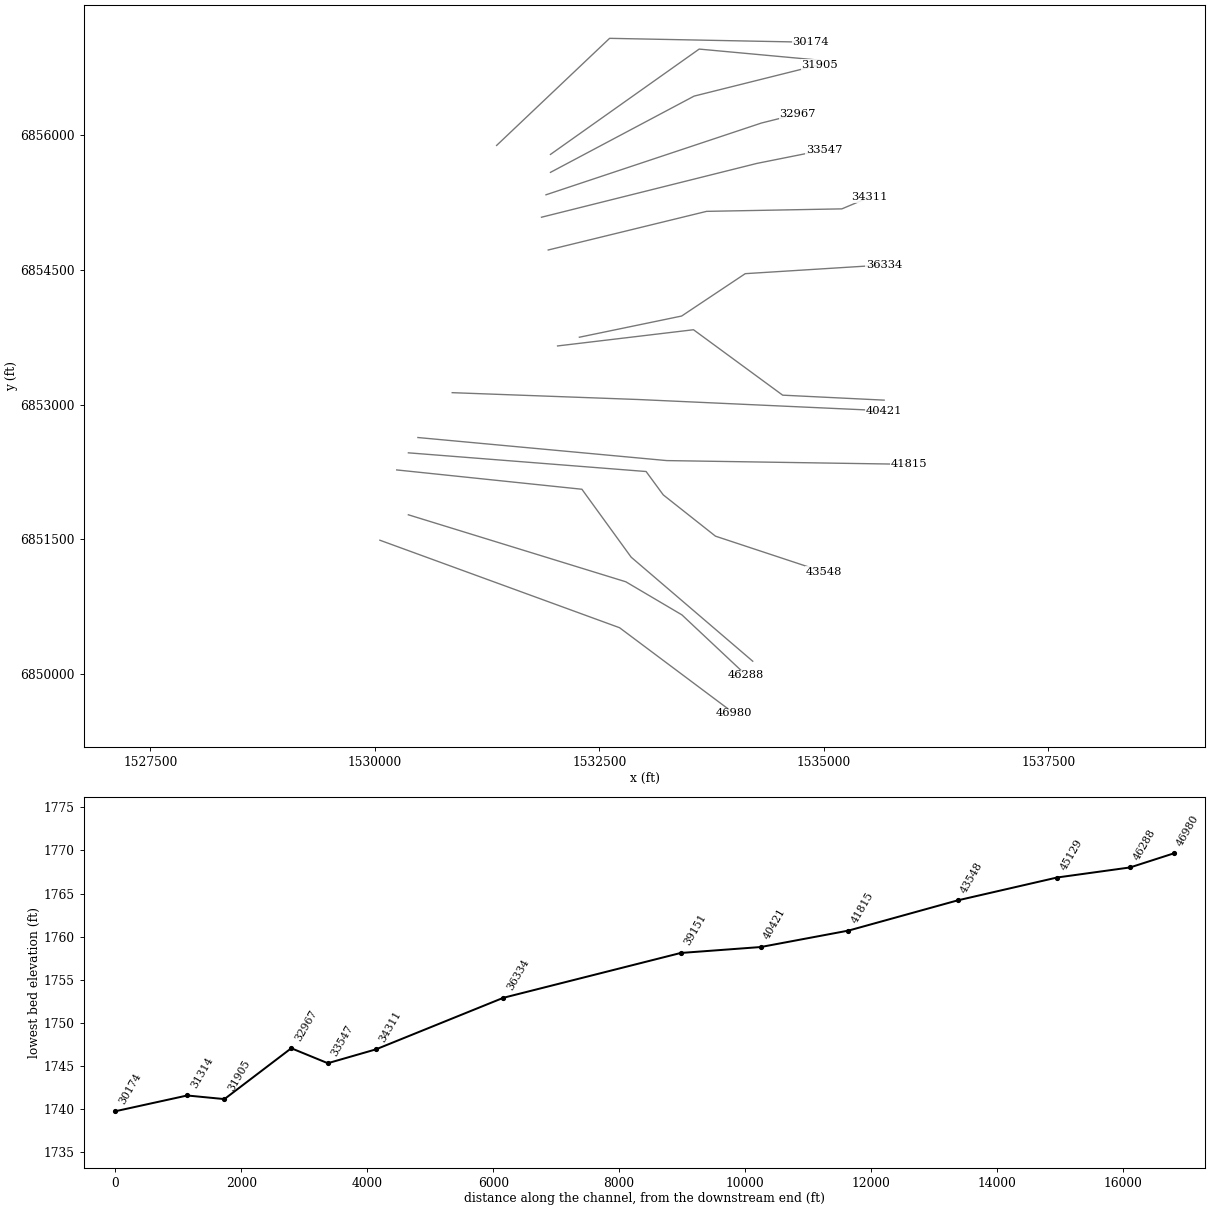
HEC-RAS study BULL WAGON CREEK.prj: BULL WAGON CREEK Base Level Engineering

--- BULL WAGON CREEK.g01 (geometry) --- (continued)

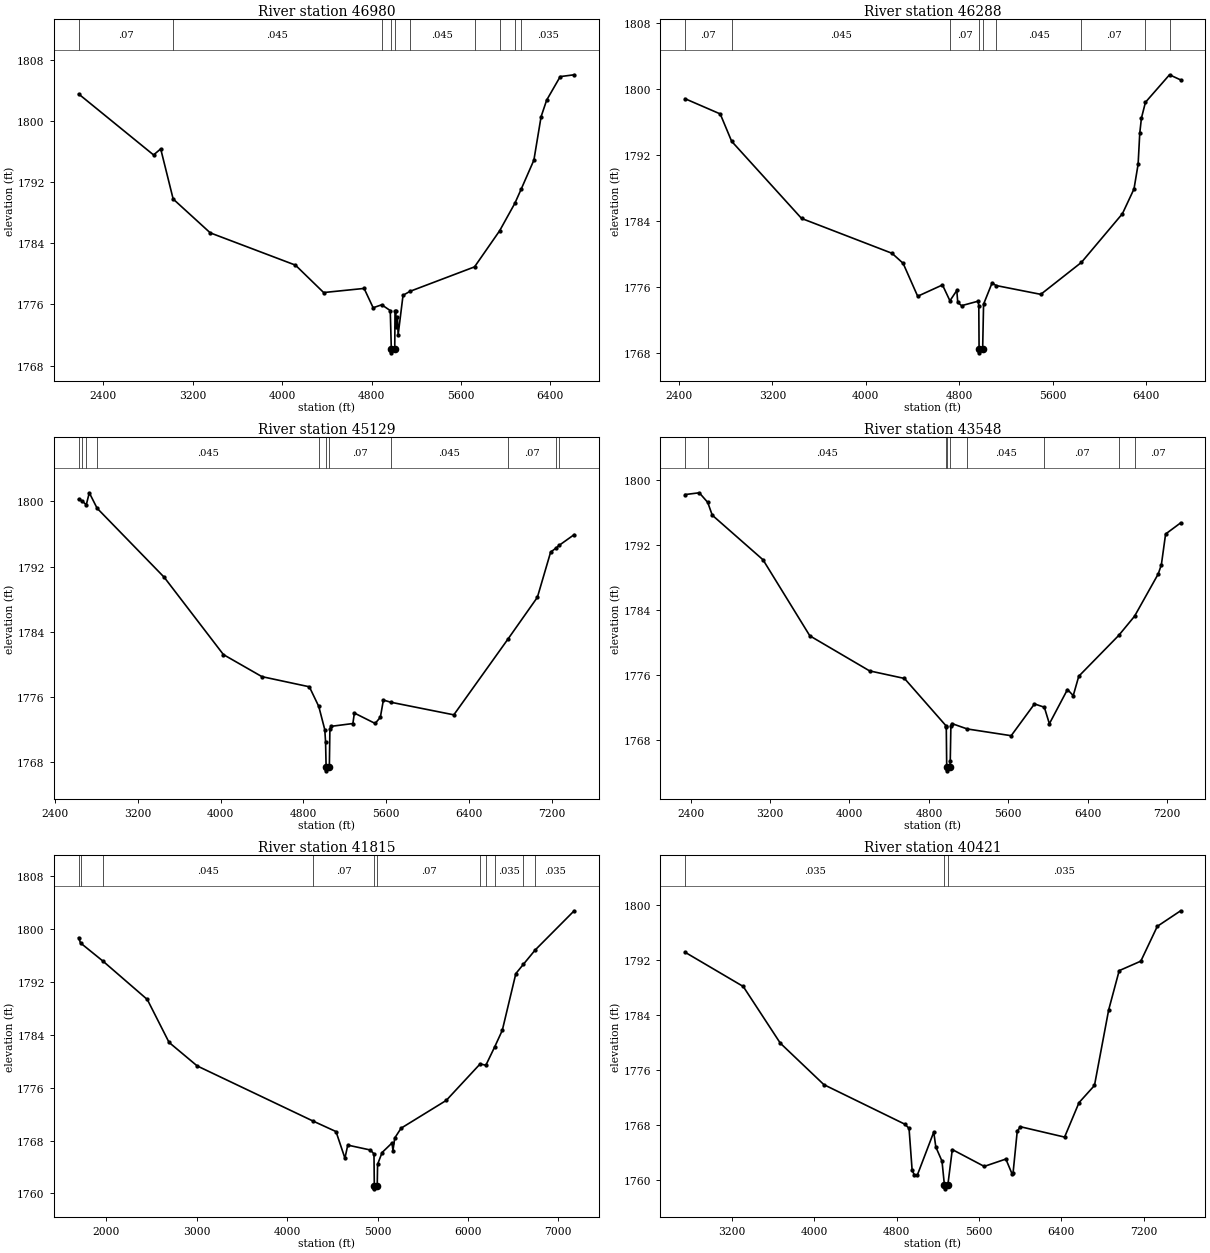
Type RM Length L Ch R = 1 ,46980   ,692,692,692
BEGIN DESCRIPTION:
BULL WAGON CREEK 37.0
END DESCRIPTION:
XS GIS Cut Line= 3
      1530055.04      6851487.98      1532724.42      6850512.79
      1534000.23       6849558.1
#Sta/Elev= 30
  2178.6 1803.54  2849.3 1795.56  2913.2 1796.35  3024.7 1789.79  3356.9 1785.36
    4119 1781.14  4371.7 1777.55  4733.8 1778.09  4814.7 1775.56  4891.5 1775.95
  4967.9 1775.19  4977.4 1770.16  4977.9 1769.66    5008 1770.16  5010.5  1775.1
  5017.9 1775.17  5020.2 1773.02  5032.2 1774.36  5038.4 1772.01  5082.2 1777.19
  5144.7 1777.71  5722.2 1780.91  5946.6 1785.63  6083.4 1789.24  6139.9 1791.09
  6253.4 1794.88    6318 1800.57    6368 1802.74  6488.9 1805.81    6614 1806.05
#Mann= 10 ,-1 , 0
  2178.6     .07       0  3024.7    .045       0  4891.5     .07       0
  4977.4     .07       0    5008     .07       0  5144.7    .045       0
  5722.2     .07       0  5946.6    .035       0  6083.4     .07       0
  6139.9    .035       0
Bank Sta=4977.4,5008
XS Rating Curve= 0 ,0
Exp/Cntr=0.3,0.1

Type RM Length L Ch R = 1 ,46288   ,1159,1159,1159
BEGIN DESCRIPTION:
Mapping XS c3df35d3
END DESCRIPTION:
XS GIS Cut Line= 4
      1530372.02      6851771.46      1532793.86      6851024.94
      1533418.86      6850656.02        1534135.      6849983.29
#Sta/Elev= 30
  2452.5 1798.79  2753.3 1796.95  2850.9 1793.64  3449.7  1784.3  4224.1 1780.08
    4319 1778.87  4443.8 1774.88  4656.1 1776.25  4719.9 1774.33  4778.7 1775.58
  4786.8 1774.13  4819.5 1773.74  4960.6 1774.28    4967 1773.75  4969.5 1768.53
    4970 1768.03  5000.1 1768.53  5007.9 1773.92    5081  1776.5  5114.2 1776.18
  5497.7 1775.11  5845.7 1778.98  6196.6 1784.87  6295.8 1787.87    6331 1790.85
  6345.1 1794.61  6359.3 1796.44  6393.8 1798.36  6599.8 1801.69  6695.1 1801.07
#Mann= 9 ,-1 , 0
  2452.5     .07       0  2850.9    .045       0  4719.9     .07       0
  4969.5     .07       0  5000.1     .07       0  5114.2    .045       0
  5845.7     .07       0  6393.8    .035       0  6599.8     .07       0
Bank Sta=4969.5,5000.1
XS Rating Curve= 0 ,0
Exp/Cntr=0.3,0.1

Type RM Length L Ch R = 1 ,45129   ,1581,1581,1581
BEGIN DESCRIPTION:
Mapping XS 0362842f
END DESCRIPTION:
XS GIS Cut Line= 4
      1530242.41      6852271.42      1532304.91      6852056.14
      1532853.53       6851299.2      1534207.72      6850139.45
#Sta/Elev= 30
  2626.9 1800.28  2662.6 1800.05  2700.6 1799.58  2730.1 1801.07  2805.4 1799.17
    3454 1790.68  4027.1 1781.16  4399.1 1778.45  4857.7  1777.2    4949 1774.78
  5007.1 1771.92  5014.6 1770.42  5019.8 1767.36  5020.3 1766.86  5051.2 1767.36
  5056.5 1772.04  5071.1 1772.34  5278.8 1772.68    5293 1773.97    5494 1772.69
  5544.3 1773.45  5573.7 1775.57  5645.4  1775.3  6254.8 1773.75  6777.6 1783.06
  7062.6 1788.21    7191 1793.78  7242.6 1794.26  7272.8  1794.6  7418.4 1795.92
#Mann= 11 ,-1 , 0
  2626.9     .07       0  2662.6    .045       0  2700.6     .07       0
  2805.4    .045       0    4949     .07       0  5019.8     .07       0
  5051.2     .07       0  5645.4    .045       0  6777.6     .07       0
  7242.6    .035       0  7272.8     .07       0
Bank Sta=5019.8,5051.2
XS Rating Curve= 0 ,0
Exp/Cntr=0.3,0.1

Type RM Length L Ch R = 1 ,43548   ,1733,1733,1733
BEGIN DESCRIPTION:
Mapping XS b70cb6ce
END DESCRIPTION:
XS GIS Cut Line= 5
      1530372.52      6852462.05       1533020.1      6852253.72
      1533211.07       6851993.3      1533792.67      6851533.23
      1534999.25      6851133.93
#Sta/Elev= 30
  2344.4 1798.17  2487.3 1798.39  2572.3 1797.21  2617.7 1795.64  3129.3 1790.15
  3600.8  1780.8  4202.6 1776.49  4553.7 1775.56  4970.2 1769.77    4975 1769.65
  4979.4  1764.7  4979.9  1764.2  5010.8  1764.7  5015.2 1765.45  5021.4 1769.66
  5029.8 1770.02  5186.2 1769.35  5628.8 1768.52  5863.6 1772.43  5962.7 1772.02
  6013.5 1769.99  6195.8  1774.2  6253.9 1773.45  6309.4 1775.83  6711.8 1780.85
  6871.3 1783.21  7109.9 1788.41  7141.5 1789.54  7184.2 1793.32  7335.6 1794.69
#Mann= 9 ,-1 , 0
  2344.4     .07       0  2572.3    .045       0  4970.2     .07       0
  4979.4     .07       0  5010.8     .07       0  5186.2    .045       0
  5962.7     .07       0  6711.8     .16       0  6871.3     .07       0
Bank Sta=4979.4,5010.8
XS Rating Curve= 0 ,0
Exp/Cntr=0.3,0.1

Type RM Length L Ch R = 1 ,41815   ,1394,1394,1394
BEGIN DESCRIPTION:
Mapping XS 9288c356
END DESCRIPTION:
XS GIS Cut Line= 3
      1530478.49      6852632.54      1533249.36      6852375.59
      1535950.38      6852333.93
#Sta/Elev= 30
  1691.6 1798.72  1712.3 1797.92  1958.9 1795.19  2451.4 1789.36  2692.4 1782.86
  3003.7  1779.3    4283 1770.97    4540 1769.36  4638.6 1765.33    4670 1767.31
  4920.1 1766.57  4960.1 1765.98  4963.9 1761.19  4964.5 1760.69  4996.2 1761.19
  5000.1  1764.4  5050.1 1766.19  5160.1 1767.64  5170.1 1766.48  5190.1 1768.39
  5260.1 1769.87  5760.2 1774.08  6135.5 1779.61  6198.3  1779.4  6297.4 1782.22
  6380.2 1784.69  6530.2 1793.28  6612.1 1794.66  6744.7 1796.86  7175.7 1802.79
#Mann= 11 ,-1 , 0
  1691.6    .094       0  1712.3     .07       0  1958.9    .045       0
    4283     .07       0  4963.9     .07       0  4996.2     .07       0
  6135.5    .035       0  6198.3     .07       0  6297.4    .035       0
  6612.1     .07       0  6744.7    .035       0
Bank Sta=4963.9,4996.2
XS Rating Curve= 0 ,0
Exp/Cntr=0.3,0.1

Type RM Length L Ch R = 1 ,40421   ,1270,1270,1270
BEGIN DESCRIPTION:
Mapping XS e1f8fe49
END DESCRIPTION:
XS GIS Cut Line= 3
      1530860.44      6853132.53      1532936.86      6853056.14
      1535671.48      6852931.21
#Sta/Elev= 30
  2743.3 1793.16  3308.2 1788.19  3668.5 1779.95  4092.2 1773.92  4879.3 1768.17
  4919.4 1767.57  4949.4 1761.49  4969.4 1760.85  4999.5 1760.76  5159.6 1767.03
  5179.6 1764.86  5239.7  1762.8  5263.5 1759.28    5264 1758.78    5296 1759.28
  5339.8 1764.49  5650.1 1762.04  5860.3 1763.11  5920.4 1760.95  5930.4  1761.1
  5970.5 1767.12  6000.5 1767.81  6430.9  1766.3  6571.1 1771.31  6721.2  1773.8
  6859.2 1784.78  6961.5 1790.49  7171.7 1791.87  7331.9 1796.93  7558.6 1799.19
#Mann= 3 ,-1 , 0
  2743.3    .035       0  5263.5    .035       0    5296    .035       0
Bank Sta=5263.5,5296
XS Rating Curve= 0 ,0
Exp/Cntr=0.3,0.1

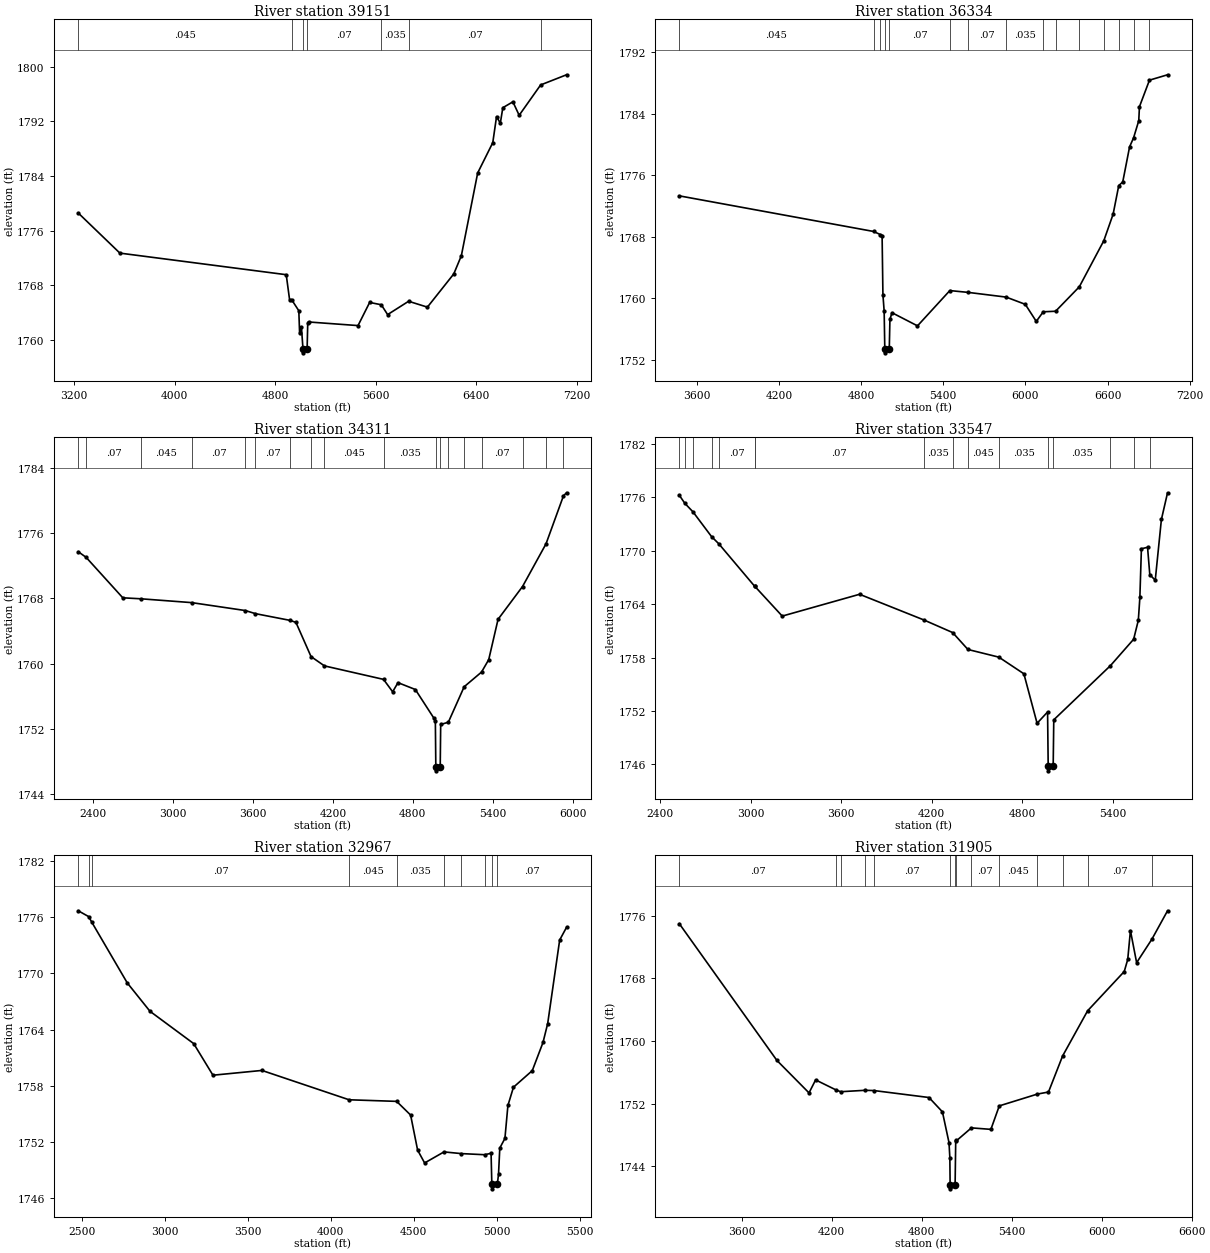
Type RM Length L Ch R = 1 ,39151   ,2817,2817,2817
BEGIN DESCRIPTION:
Mapping XS 80d07f8b
END DESCRIPTION:
XS GIS Cut Line= 4
      1532034.07      6853653.37      1533547.97      6853833.92
      1534541.03      6853104.76      1535671.52      6853049.27
#Sta/Elev= 30
  3231.7 1778.56  3563.2 1772.69    4888 1769.53    4915 1765.83  4930.7 1765.88
  4988.3 1764.25  4994.5 1760.96  5009.2 1761.82  5021.7 1758.59  5022.2 1758.09
  5054.3 1758.59  5059.3 1762.43  5065.5 1762.61  5459.8 1762.08  5552.4 1765.47
    5645 1765.13  5695.5 1763.69  5862.8 1765.64  6012.3 1764.78  6222.6 1769.65
  6282.7 1772.31  6412.8 1784.43    6533 1788.86    6563 1792.68    6593 1791.71
  6613.1 1793.98  6693.2 1794.84  6743.2 1792.87  6914.1 1797.31  7120.2  1798.8
#Mann= 7 ,-1 , 0
  3231.7    .045       0  4930.7     .07       0  5021.7     .07       0
  5054.3     .07       0    5645    .035       0  5862.8     .07       0
  6914.1    .045       0
Bank Sta=5021.7,5054.3
XS Rating Curve= 0 ,0
Exp/Cntr=0.3,0.1

Type RM Length L Ch R = 1 ,36334   ,2023,2023,2023
BEGIN DESCRIPTION:
Mapping XS 09870b92
END DESCRIPTION:
XS GIS Cut Line= 4
      1532277.17       6853750.6      1533416.03       6853986.7
      1534124.36      6854458.92      1535671.53      6854556.05
#Sta/Elev= 30
    3473  1773.3    4891 1768.67  4940.3 1768.27  4953.6 1768.14  4959.6 1760.44
  4968.6 1758.31  4973.3 1753.38  4973.9 1752.88    5006 1753.38  5010.7 1757.24
  5025.7  1758.1    5212 1756.39  5448.2 1760.98  5583.4 1760.74  5859.4 1760.13
    5999 1759.19  6079.2 1756.97  6130.2 1758.22  6220.2 1758.29  6393.4 1761.47
  6572.2 1767.46  6640.3 1770.92  6681.4 1774.64  6710.4  1775.1  6760.5 1779.68
  6789.5 1780.84  6827.5 1783.08  6832.5  1784.9  6905.6 1788.35  7037.6 1789.05
#Mann= 15 ,-1 , 0
    3473    .045       0    4891    .035       0  4940.3     .07       0
  4973.3     .07       0    5006     .07       0  5448.2    .035       0
  5583.4     .07       0  5859.4    .035       0  6130.2     .07       0
  6220.2    .035       0  6393.4     .07       0  6572.2    .035       0
  6681.4     .07       0  6789.5    .035       0  6905.6     .07       0
Bank Sta=4973.3,5006
XS Rating Curve= 0 ,0
Exp/Cntr=0.3,0.1

Type RM Length L Ch R = 1 ,34311   ,764,764,764
BEGIN DESCRIPTION:
Mapping XS 6d3413ae
END DESCRIPTION:
XS GIS Cut Line= 4
      1531929.95      6854722.82       1533693.8      6855153.37
      1535200.75      6855181.14      1535511.54      6855312.37
#Sta/Elev= 30
  2291.7  1773.7  2350.6 1773.01  2625.5 1768.06  2760.9 1767.94  3142.5 1767.47
  3544.6  1766.5  3620.3 1766.12    3876 1765.31  3923.3 1765.06  4036.7 1760.87
  4137.2 1759.73  4580.1 1758.08  4648.6 1756.56  4688.6 1757.68  4818.7 1756.84
  4958.7 1753.31  4968.7 1752.97  4972.2 1747.39  4972.8 1746.89  5005.2 1747.39
  5008.7 1752.56  5066.1 1752.84  5184.8 1757.18  5314.7 1758.97  5368.7 1760.49
  5438.8 1765.43  5622.2 1769.44  5798.5 1774.67  5929.1 1780.54  5951.9 1780.91
#Mann= 18 ,-1 , 0
  2291.7    .045       0  2350.6     .07       0  2760.9    .045       0
  3142.5     .07       0  3544.6    .045       0  3620.3     .07       0
    3876    .035       0  4036.7     .07       0  4137.2    .045       0
  4580.1    .035       0  4972.2    .035       0  5005.2    .035       0
  5066.1     .07       0  5184.8    .035       0  5314.7     .07       0
  5622.2    .035       0  5798.5     .07       0  5929.1    .045       0
Bank Sta=4972.2,5005.2
XS Rating Curve= 0 ,0
Exp/Cntr=0.3,0.1

Type RM Length L Ch R = 1 ,33547   ,580,580,580
BEGIN DESCRIPTION:
BULL WAGON CREEK 32.0
END DESCRIPTION:
XS GIS Cut Line= 3
      1531855.04      6855088.01        1534255.        6855688.
      1535005.03      6855838.01
#Sta/Elev= 30
  2526.4 1776.23  2563.4 1775.32    2617 1774.37  2740.2 1771.59  2787.9 1770.79
  3025.2 1766.03  3025.8 1766.03  3209.2 1762.66  3722.1 1765.11  4148.2 1762.23
  4339.6 1760.81    4441 1758.91    4646 1758.05  4812.1 1756.18  4899.7 1750.62
  4969.3 1751.89  4973.4 1745.78    4974 1745.28  5006.5 1745.78  5010.4 1751.01
  5386.6  1757.1  5540.2 1760.06  5571.3 1762.19  5581.5 1764.75  5591.7 1770.22
  5632.5 1770.39  5647.4 1767.31  5683.5 1766.69  5724.3 1773.51  5765.1 1776.51
#Mann= 16 ,-1 , 0
  2526.4     .07       0  2563.4    .035       0    2617     .07       0
  2740.2    .035       0  2787.9     .07       0  3025.2    .045       0
  3025.8     .07       0  4148.2    .035       0  4339.6     .07       0
    4441    .045       0    4646    .035       0  4973.4    .035       0
  5006.5    .035       0  5386.6     .07       0  5540.2    .035       0
  5647.4     .07       0
Bank Sta=4973.4,5006.5
XS Rating Curve= 0 ,0
Exp/Cntr=0.3,0.1

Type RM Length L Ch R = 1 ,32967   ,1062,1062,1062
BEGIN DESCRIPTION:
BULL WAGON CREEK 31.0
END DESCRIPTION:
XS GIS Cut Line= 3
      1531905.05      6855338.02        1534305.        6856138.
      1534705.01        6856238.
#Sta/Elev= 30
  2478.1 1776.68  2540.6 1776.06  2560.6 1775.43  2773.2 1768.99  2910.2 1765.96
  3173.8 1762.51  3289.7 1759.14  3584.8 1759.65    4110 1756.52  4396.6 1756.35
  4480.8 1754.89    4523 1751.15  4565.2 1749.78    4682 1750.96  4785.4 1750.78
  4926.3 1750.66  4965.7 1750.81  4970.2 1747.52  4970.8 1747.02  5003.4 1747.52
  5010.5 1748.57  5018.2 1751.37  5049.1  1752.4  5067.1 1755.91  5100.6 1757.86
    5214 1759.63  5278.5 1762.63  5306.8 1764.65    5379 1773.56  5420.2 1774.91
#Mann= 10 ,-1 , 0
  2478.1     .07       0  2540.6    .035       0  2560.6     .07       0
    4110    .045       0  4396.6    .035       0    4682     .07       0
  4785.4    .035       0  4926.3     .07       0  4970.2     .07       0
  5003.4     .07       0
Bank Sta=4970.2,5003.4
XS Rating Curve= 0 ,0
Exp/Cntr=0.3,0.1

Type RM Length L Ch R = 1 ,31905   ,591,591,591
BEGIN DESCRIPTION:
BULL WAGON CREEK 30.0
END DESCRIPTION:
XS GIS Cut Line= 3
      1531955.03      6855588.01        1533555.        6856438.
      1534954.98      6856787.99
#Sta/Elev= 30
  3184.4 1774.99    3835 1757.52  4049.1 1753.37  4093.1 1755.03  4230.9 1753.73
  4260.4 1753.52  4421.7  1753.7  4481.2 1753.67  4848.9 1752.78  4938.4 1750.95
  4982.3 1747.02    4988 1745.08  4989.8 1741.61  4990.4 1741.11    5023 1741.61
  5027.1 1747.29  5030.4 1747.23  5131.7  1748.9  5261.6 1748.71  5317.5 1751.71
  5571.7 1753.22  5645.5 1753.48  5739.7 1758.09  5906.3 1763.86  6150.6 1768.88
  6173.8 1770.42  6191.8 1774.11  6233.1 1770.01  6334.9 1773.01  6439.2 1776.64
#Mann= 14 ,-1 , 0
  3184.4     .07       0  4230.9    .045       0  4260.4     .07       0
  4421.7    .045       0  4481.2     .07       0  4989.8     .07       0
    5023     .07       0  5030.4    .035       0  5131.7     .07       0
  5317.5    .045       0  5571.7     .07       0  5739.7    .045       0
  5906.3     .07       0  6334.9    .045       0
Bank Sta=4989.8,5023
XS Rating Curve= 0 ,0
Exp/Cntr=0.3,0.1

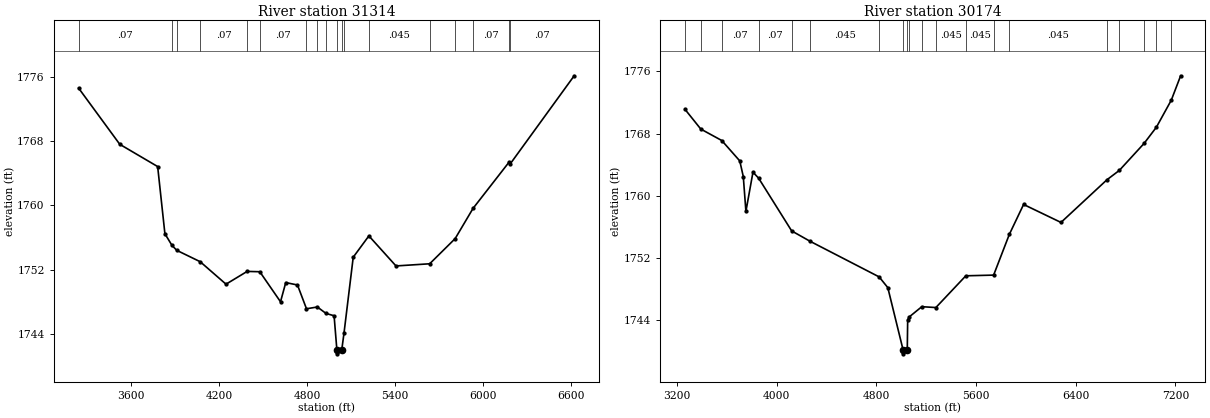
Type RM Length L Ch R = 1 ,31314   ,1140,1140,1140
BEGIN DESCRIPTION:
BULL WAGON CREEK 29.0
END DESCRIPTION:
XS GIS Cut Line= 3
      1531954.97      6855787.98      1533611.25      6856962.05
      1534955.04        6856838.
#Sta/Elev= 30
  3242.3  1774.6  3522.9 1767.61  3781.3 1764.84  3830.7 1756.48  3878.5 1755.04
  3911.9 1754.41  4071.1    1753  4247.5  1750.2  4391.6 1751.79  4477.8 1751.75
  4619.2 1748.01  4654.9  1750.4  4734.9  1750.1  4796.3 1747.14  4870.5 1747.36
  4929.5 1746.56  4984.6 1746.27  5003.6 1742.03  5004.3 1741.53  5036.9 1742.03
  5052.3 1744.12  5115.1 1753.56  5221.9 1756.21  5406.8 1752.47  5636.6 1752.74
  5810.2 1755.87  5932.5 1759.64  6176.6 1765.36  6186.2 1765.18    6622 1776.14
#Mann= 18 ,-1 , 0
  3242.3     .07       0  3878.5    .035       0  3911.9    .045       0
  4071.1     .07       0  4391.6    .045       0  4477.8     .07       0
  4796.3    .035       0  4870.5     .07       0  4929.5    .035       0
  5003.6    .035       0  5036.9    .035       0  5052.3     .07       0
  5221.9    .045       0  5636.6     .07       0  5810.2    .045       0
  5932.5     .07       0  6176.6    .045       0  6186.2     .07       0
Bank Sta=5003.6,5036.9
XS Rating Curve= 0 ,0
Exp/Cntr=0.3,0.1

Type RM Length L Ch R = 1 ,30174   ,1058,1058,1058
BEGIN DESCRIPTION:
BULL WAGON CREEK 28.0
END DESCRIPTION:
XS GIS Cut Line= 3
      1531355.02      6855888.02      1532613.46      6857081.82
      1534855.03        6857038.
#Sta/Elev= 30
  3265.4 1771.11  3391.4 1768.59  3559.7 1767.12  3704.1  1764.5  3732.4 1762.49
  3753.4 1758.01    3810 1763.05  3855.4 1762.28  4120.6  1755.5  4269.3 1754.16
  4822.6 1749.59  4892.1 1748.21  5014.8  1740.2  5015.4  1739.7  5048.3  1740.2
  5051.6 1744.08  5065.9 1744.47    5165 1745.76  5277.8 1745.65  5518.2 1749.73
  5741.3 1749.82  5867.2 1755.05  5981.7  1758.9  6281.8 1756.59  6651.1 1762.08
  6750.2 1763.28  6948.3 1766.74  7047.4 1768.83  7167.1 1772.31    7242 1775.44
#Mann= 20 ,-1 , 0
  3265.4    .035       0  3391.4    .035       0  3559.7     .07       0
  3855.4     .07       0  4120.6    .035       0  4269.3    .045       0
  4822.6    .035       0  5014.8    .035       0  5048.3    .035       0
  5065.9     .07       0    5165    .035       0  5277.8    .045       0
  5518.2    .045       0  5741.3     .07       0  5867.2    .045       0
  6651.1     .07       0  6750.2    .035       0  6948.3    .045       0
  7047.4     .07       0  7167.1    .045       0
Bank Sta=5014.8,5048.3
XS Rating Curve= 0 ,0
Exp/Cntr=0.3,0.1