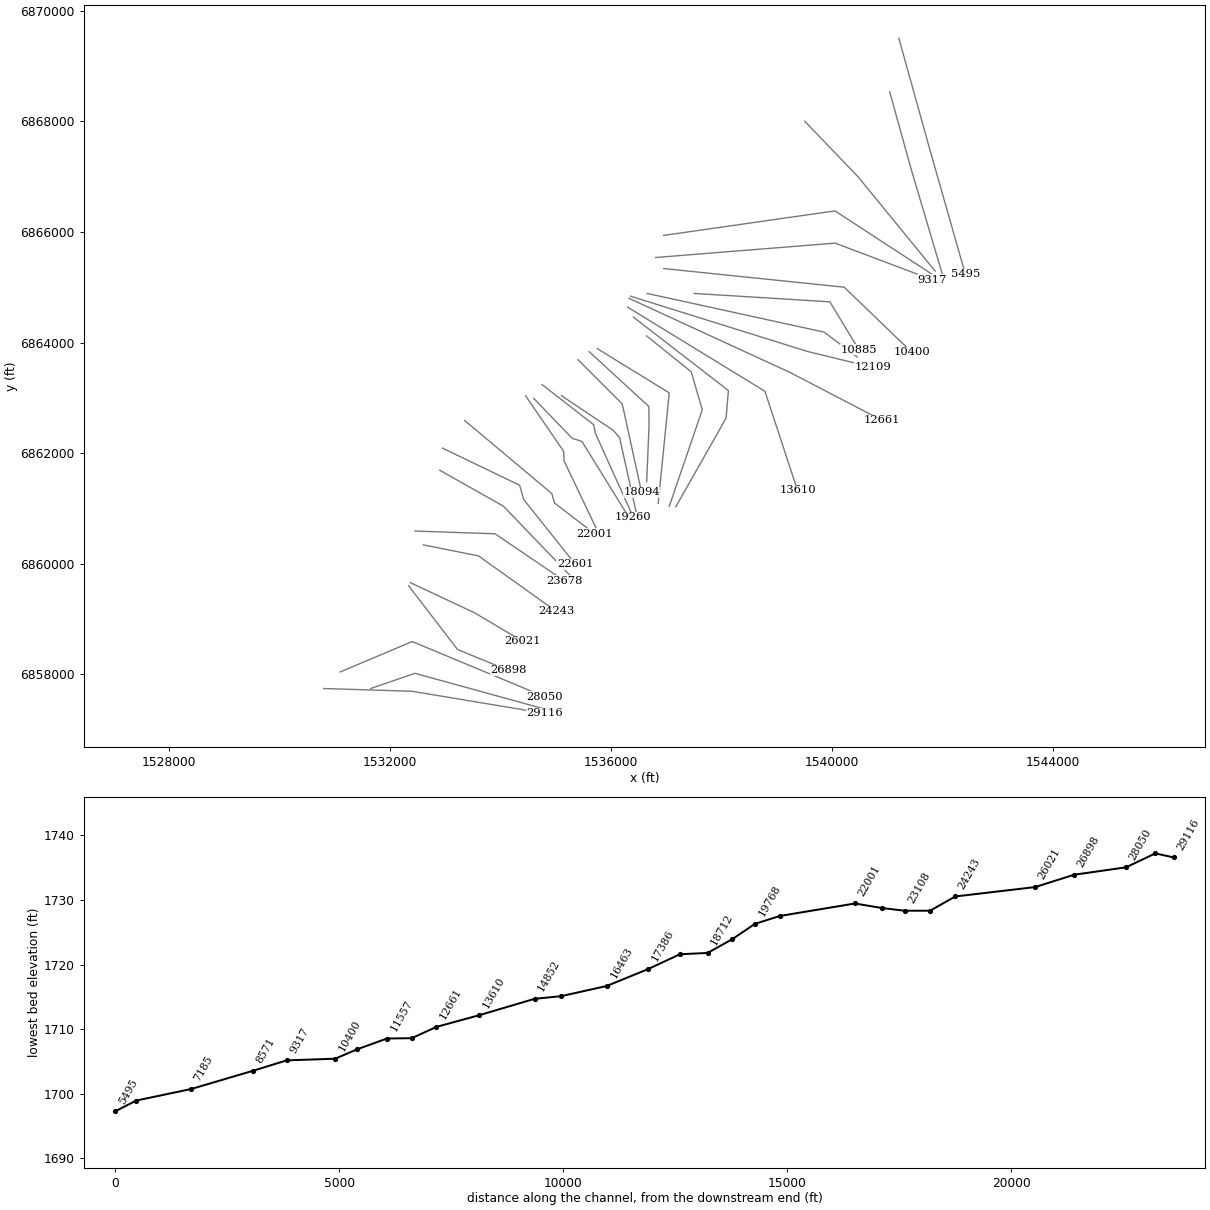
HEC-RAS study BULL WAGON CREEK.prj: BULL WAGON CREEK Base Level Engineering

--- BULL WAGON CREEK.g01 (geometry) --- (continued)

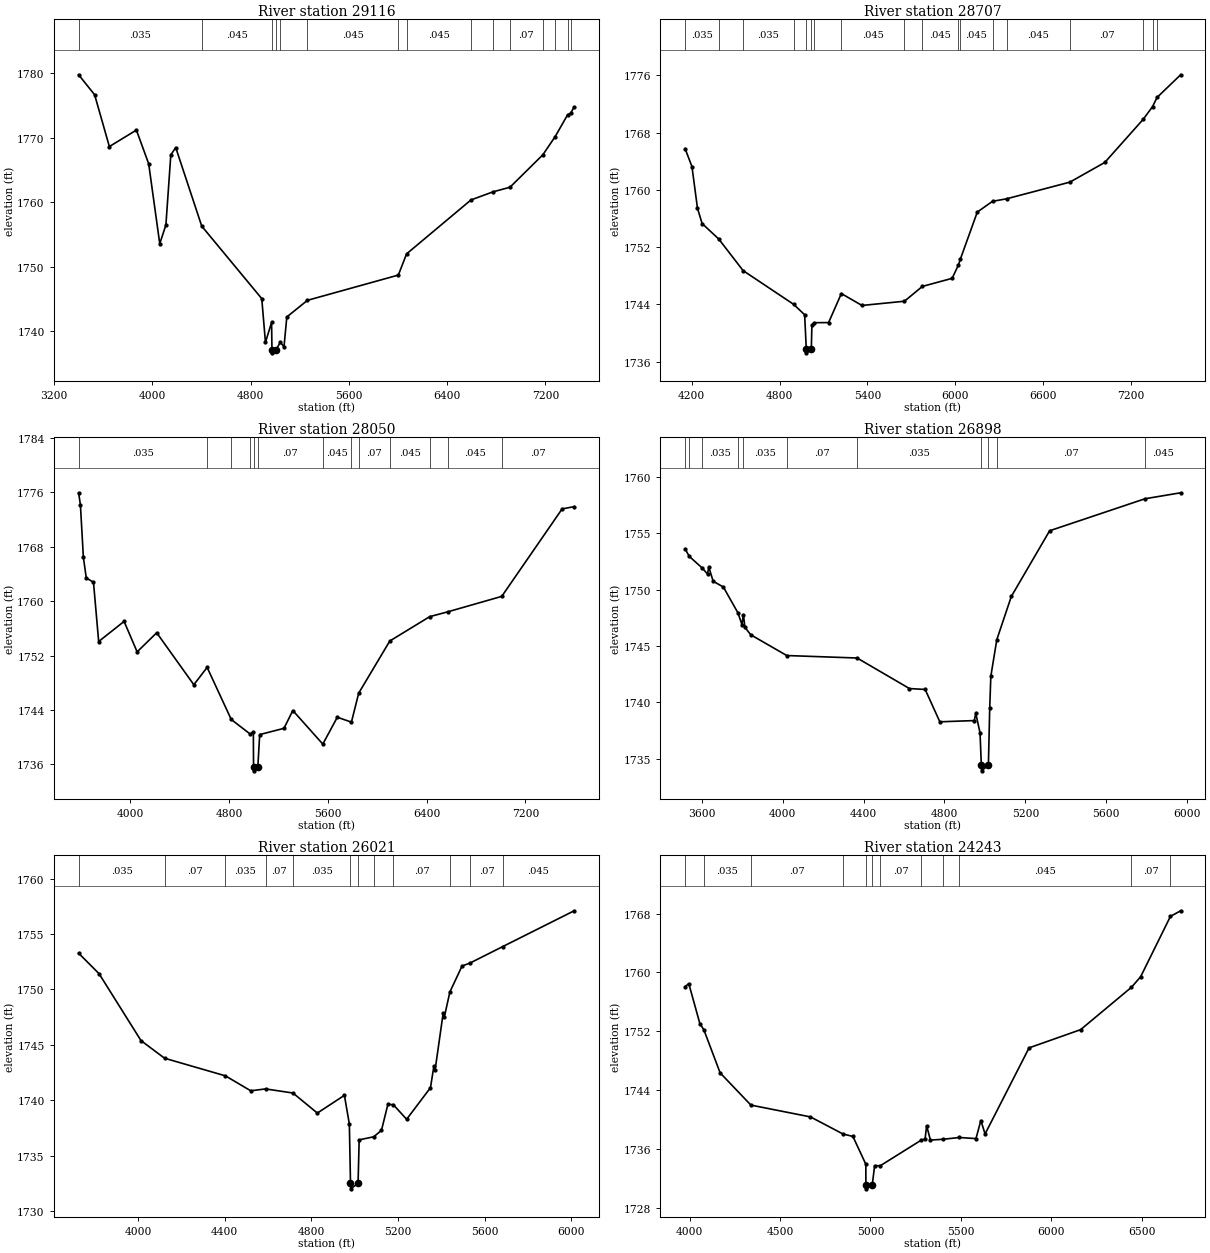
Type RM Length L Ch R = 1 ,29116   ,409,409,409
BEGIN DESCRIPTION:
BULL WAGON CREEK 27.0
END DESCRIPTION:
XS GIS Cut Line= 3
      1530804.96        6857738.        1532405.        6857688.
      1534804.97        6857288.
#Sta/Elev= 30
    3400 1779.79  3530.1 1776.69  3650.2 1768.64  3870.3  1771.2  3970.3 1765.96
  4060.4 1753.55  4110.4 1756.46  4150.4 1767.34  4190.4 1768.49  4402.1 1756.28
  4890.8 1745.02  4920.8 1738.23  4970.8 1741.33  4973.7  1737.1  4974.4  1736.6
    5008  1737.1  5041.9 1738.25  5071.8 1737.52  5094.6 1742.17  5262.9 1744.76
  6002.6 1748.68  6069.6 1751.97  6593.9 1760.35  6775.4 1761.62  6911.2 1762.32
  7178.8 1767.36  7279.6  1770.2  7380.5 1773.58  7405.3 1773.82  7433.9 1774.79
#Mann= 15 ,-1 , 0
    3400    .035       0  4402.1    .045       0  4973.7    .045       0
    5008    .045       0  5041.9    .035       0  5262.9    .045       0
  6002.6     .07       0  6069.6    .045       0  6593.9     .07       0
  6775.4    .045       0  6911.2     .07       0  7178.8    .035       0
  7279.6     .07       0  7380.5    .035       0  7405.3     .07       0
Bank Sta=4973.7,5008
XS Rating Curve= 0 ,0
Exp/Cntr=0.3,0.1

Type RM Length L Ch R = 1 ,28707   ,657,657,657
BEGIN DESCRIPTION:
BULL WAGON CREEK 26.0
END DESCRIPTION:
XS GIS Cut Line= 3
      1531654.96      6857737.99      1532454.59        6858013.
      1534905.02        6857338.
#Sta/Elev= 30
  4154.4 1765.75  4201.3 1763.24    4239 1757.42  4270.8 1755.28  4384.1 1753.13
  4550.9 1748.71  4896.8 1743.99  4971.6 1742.54  4982.8 1737.72  4983.5 1737.22
  5017.1 1737.72  5021.2 1741.13  5038.2 1741.43  5135.3 1741.45  5222.5  1745.5
  5363.5 1743.84  5653.6 1744.43  5776.3  1746.5  5979.8 1747.63  6023.1 1749.51
  6035.4 1750.28  6151.8 1756.89  6255.9 1758.39  6351.5 1758.74  6784.7 1761.07
  7023.1 1763.82  7285.1 1769.83  7349.4 1771.61  7380.8 1772.91  7541.7 1776.07
#Mann= 18 ,-1 , 0
  4154.4    .035       0  4384.1    .045       0  4550.9    .035       0
  4896.8    .045       0  4982.8    .045       0  5017.1    .045       0
  5038.2     .07       0  5222.5    .045       0  5653.6     .07       0
  5776.3    .045       0  6023.1     .07       0  6035.4    .045       0
  6255.9     .07       0  6351.5    .045       0  6784.7     .07       0
  7285.1    .035       0  7349.4     .07       0  7380.8    .035       0
Bank Sta=4982.8,5017.1
XS Rating Curve= 0 ,0
Exp/Cntr=0.3,0.1

Type RM Length L Ch R = 1 ,28050   ,1152,1152,1152
BEGIN DESCRIPTION:
BULL WAGON CREEK 25.0
END DESCRIPTION:
XS GIS Cut Line= 3
      1531104.97      6858037.99        1532405.        6858588.
      1534805.01        6857588.
#Sta/Elev= 30
  3582.6 1775.94  3597.2 1774.14  3620.9 1766.46  3644.6 1763.41  3702.8 1762.79
  3744.8 1754.07  3950.6 1757.03  4056.2 1752.55  4214.6 1755.36  4515.2 1747.72
  4622.9 1750.27  4818.1 1742.61  4973.4 1740.44  4996.9  1740.8  4998.7 1735.56
  4999.4 1735.06  5033.1 1735.56  5048.4 1740.39    5245 1741.31  5316.5 1743.93
  5559.3 1738.99  5676.7 1742.94    5791 1742.22  5849.8 1746.48  6101.7 1754.15
  6424.9 1757.73  6569.4 1758.43  7007.9 1760.71  7496.7 1773.57  7594.2  1773.9
#Mann= 13 ,-1 , 0
  3582.6    .035       0  4622.9    .045       0  4818.1    .035       0
  4973.4     .07       0  4998.7     .07       0  5033.1     .07       0
  5559.3    .045       0    5791    .035       0  5849.8     .07       0
  6101.7    .045       0  6424.9     .07       0  6569.4    .045       0
  7007.9     .07       0
Bank Sta=4998.7,5033.1
XS Rating Curve= 0 ,0
Exp/Cntr=0.3,0.1

Type RM Length L Ch R = 1 ,26898   ,877,877,877
BEGIN DESCRIPTION:
Mapping XS ab45005b
END DESCRIPTION:
XS GIS Cut Line= 3
      1532340.41      6859598.05      1533225.85       6858443.5
      1534145.99      6858065.89
#Sta/Elev= 30
  3518.1 1753.62  3538.5 1752.95  3603.1 1751.91  3628.9 1751.38  3635.2 1752.01
  3656.8 1750.74  3707.2 1750.23  3779.2 1747.94  3799.2  1746.9  3806.4 1747.78
  3813.8 1746.65  3842.8 1745.99  4020.6 1744.15  4368.5 1743.93  4627.2 1741.22
  4704.8 1741.14  4777.4 1738.27  4947.8 1738.38  4954.8 1739.03    4976  1737.3
  4982.5 1734.42  4983.3 1733.92  5017.4 1734.42  5023.9 1739.47  5029.4 1742.31
    5059 1745.56  5130.7 1749.39  5320.1 1755.22  5791.6 1758.06  5967.7 1758.59
#Mann= 11 ,-1 , 0
  3518.1    .035       0  3538.5    .045       0  3603.1    .035       0
  3779.2    .045       0  3806.4    .035       0  4020.6     .07       0
  4368.5    .035       0  4982.5    .035       0  5017.4    .035       0
    5059     .07       0  5791.6    .045       0
Bank Sta=4982.5,5017.4
XS Rating Curve= 0 ,0
Exp/Cntr=0.3,0.1

Type RM Length L Ch R = 1 ,26021   ,1778,1778,1778
BEGIN DESCRIPTION:
Mapping XS ff661ab0
END DESCRIPTION:
XS GIS Cut Line= 3
      1532374.24      6859653.01      1533537.48      6859106.11
      1534400.57      6858594.33
#Sta/Elev= 30
  3725.3 1753.27  3819.7 1751.42  4013.4 1745.38  4122.2 1743.79  4403.2  1742.2
  4520.3 1740.85  4588.6 1741.02  4715.2 1740.65  4827.8 1738.84  4952.9 1740.44
  4975.7 1737.85    4981  1732.5  4981.7    1732    5016  1732.5    5021 1736.42
  5088.4  1736.7  5124.1 1737.28  5153.6 1739.62  5178.5  1739.6  5240.3 1738.28
  5350.4 1741.13    5366 1743.06  5371.9 1742.75  5408.9 1747.84  5414.7 1747.54
    5440 1749.77  5496.1 1752.11  5534.8  1752.4  5684.4 1753.87  6014.1  1757.1
#Mann= 12 ,-1 , 0
  3725.3    .035       0  4122.2     .07       0  4403.2    .035       0
  4588.6     .07       0  4715.2    .035       0    4981     .07       0
    5016    .035       0  5088.4    .035       0  5178.5     .07       0
    5440    .035       0  5534.8     .07       0  5684.4    .045       0
Bank Sta=4981,5016
XS Rating Curve= 0 ,0
Exp/Cntr=0.3,0.1

Type RM Length L Ch R = 1 ,24243   ,565,565,565
BEGIN DESCRIPTION:
BULL WAGON CREEK 23.0
END DESCRIPTION:
XS GIS Cut Line= 3
      1532605.03      6860337.99        1533605.        6860138.
      1535004.97      6859138.02
#Sta/Elev= 30
  3975.4 1758.08  3995.8 1758.48    4057 1753.05  4079.6 1752.17  4169.1 1746.34
  4339.2 1741.95  4668.8 1740.34  4848.2 1738.02  4903.4 1737.68  4974.8  1733.9
  4975.1 1731.05  4975.8 1730.55  5010.2 1731.05  5023.4  1733.7  5055.1  1733.7
  5281.9 1737.19  5302.4 1737.33    5311 1739.14  5331.9 1737.19  5399.4 1737.29
  5491.8 1737.54  5583.8 1737.39  5610.9 1739.85  5634.2 1738.02  5877.5 1749.74
  6162.6 1752.22  6443.8 1757.99  6494.4 1759.42  6659.2 1767.64  6715.6  1768.4
#Mann= 12 ,-1 , 0
  3975.4     .07       0  4079.6    .035       0  4339.2     .07       0
  4848.2    .045       0  4975.1    .045       0  5010.2    .045       0
  5055.1     .07       0  5281.9    .045       0  5399.4     .07       0
  5491.8    .045       0  6443.8     .07       0  6659.2    .045       0
Bank Sta=4975.1,5010.2
XS Rating Curve= 0 ,0
Exp/Cntr=0.3,0.1

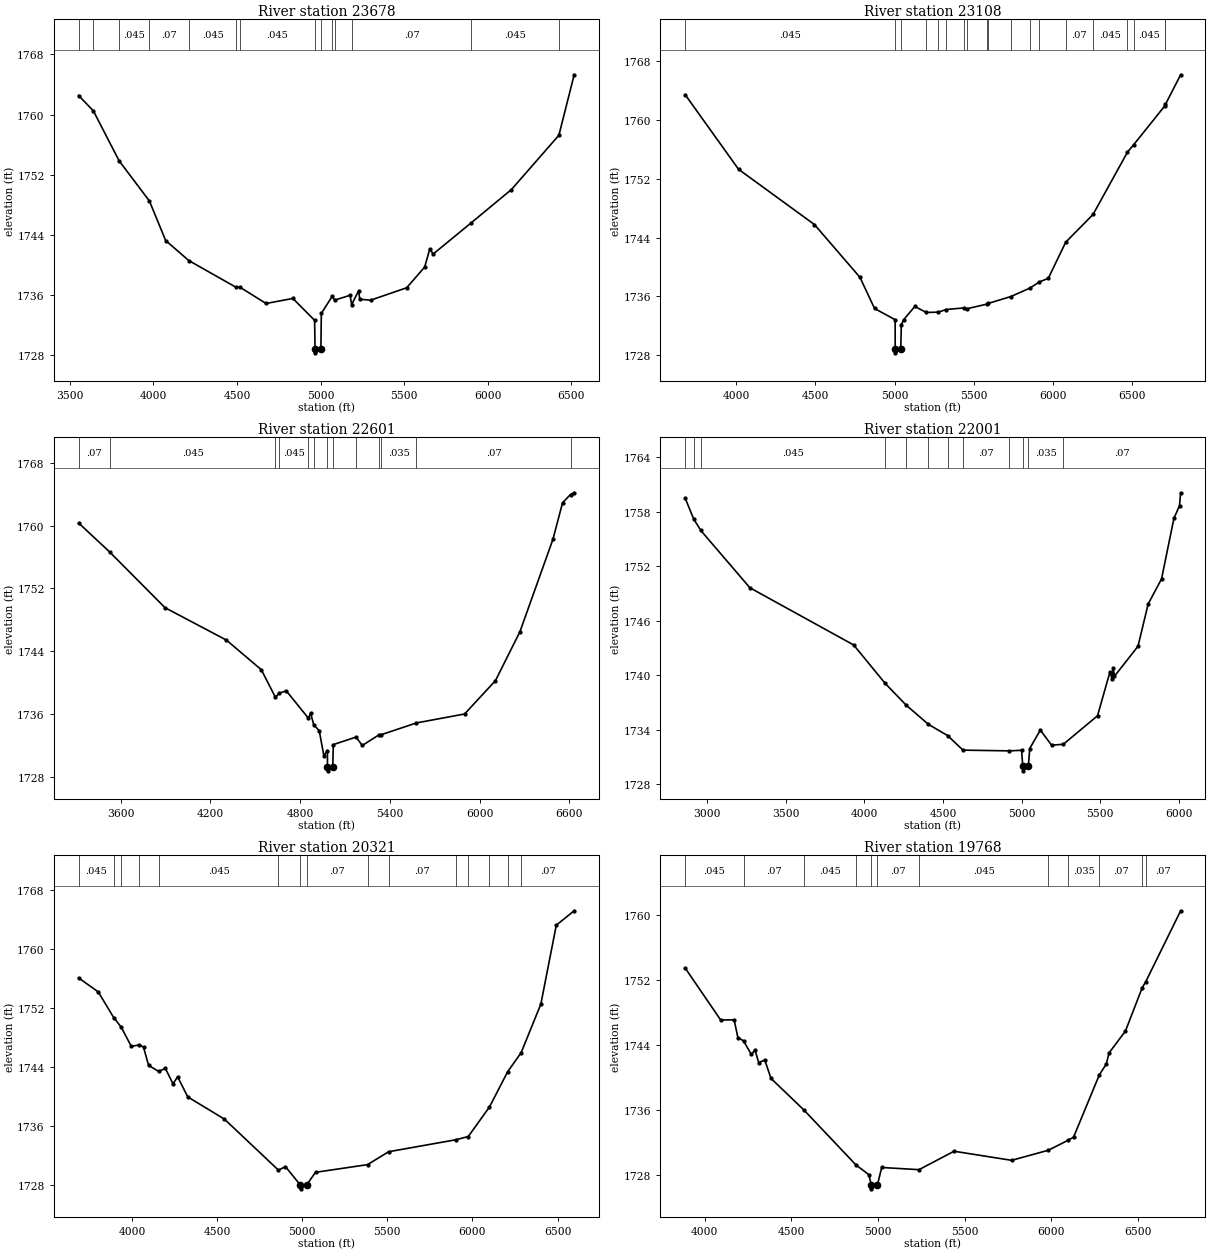
Type RM Length L Ch R = 1 ,23678   ,570,570,570
BEGIN DESCRIPTION:
BULL WAGON CREEK 22.0
END DESCRIPTION:
XS GIS Cut Line= 3
      1532455.01        6860588.        1533905.        6860538.
      1535155.02      6859687.99
#Sta/Elev= 30
  3553.6 1762.54  3641.5 1760.51  3795.5 1753.87  3976.8 1748.52  4073.9 1743.27
    4212 1740.61  4496.6 1737.03  4516.2 1737.09  4674.3  1734.9  4834.4 1735.57
  4964.4 1732.66  4966.9 1728.84  4967.6 1728.34    5002 1728.84  5004.5 1733.58
  5069.3 1735.85  5084.4 1735.35  5176.6 1735.99  5185.8 1734.75  5227.5 1736.59
  5234.2 1735.46  5299.3 1735.34  5514.8 1736.99  5622.6 1739.75  5652.5 1742.13
  5673.5 1741.48  5902.1 1745.65  6141.2 1750.05  6424.7 1757.26  6516.1  1765.3
#Mann= 14 ,-1 , 0
  3553.6    .045       0  3641.5    .035       0  3795.5    .045       0
  3976.8     .07       0    4212    .045       0  4496.6     .07       0
  4516.2    .045       0  4966.9    .035       0    5002    .045       0
  5069.3     .07       0  5084.4    .035       0  5185.8     .07       0
  5902.1    .045       0  6424.7    .035       0
Bank Sta=4966.9,5002
XS Rating Curve= 0 ,0
Exp/Cntr=0.3,0.1

Type RM Length L Ch R = 1 ,23108   ,507,507,507
BEGIN DESCRIPTION:
BULL WAGON CREEK 21.0
END DESCRIPTION:
XS GIS Cut Line= 3
      1532904.98      6861688.01        1534055.        6861038.
      1535305.02      6859737.98
#Sta/Elev= 30
  3679.4 1763.45  4016.5 1753.29    4495 1745.78  4781.7 1738.61    4874 1734.37
  5003.9 1732.84    5004 1728.84  5004.7 1728.34  5039.3 1728.84  5042.7 1732.13
  5056.9 1732.83  5127.6 1734.64  5200.3 1733.83  5276.3 1733.87  5324.9 1734.23
  5438.6 1734.45  5457.3 1734.34  5585.8 1734.98  5589.7 1735.05  5732.9 1735.99
  5854.4 1737.15  5912.2 1737.97  5969.4 1738.47    6079 1743.37  6251.5 1747.15
  6468.6 1755.62  6507.6 1756.63  6702.6 1761.87    6708 1762.11  6803.9 1766.14
#Mann= 19 ,-1 , 0
  3679.4    .045       0    5004    .045       0  5039.3    .045       0
  5200.3     .07       0  5276.3    .045       0  5324.9     .07       0
  5438.6    .035       0  5457.3     .07       0  5585.8    .035       0
  5589.7     .07       0  5732.9    .035       0  5854.4     .07       0
  5912.2    .045       0    6079     .07       0  6251.5    .045       0
  6468.6     .07       0  6507.6    .045       0  6702.6    .035       0
    6708    .045       0
Bank Sta=5004,5039.3
XS Rating Curve= 0 ,0
Exp/Cntr=0.3,0.1

Type RM Length L Ch R = 1 ,22601   ,600,600,600
BEGIN DESCRIPTION:
BULL WAGON CREEK 20.0
END DESCRIPTION:
XS GIS Cut Line= 4
      1532955.01        6862088.      1534349.11      6861416.59
      1534422.03      6861158.77      1535354.98      6859988.03
#Sta/Elev= 30
    3319 1760.32  3526.5 1756.63  3896.2 1749.54  4306.8 1745.41  4539.9 1741.64
  4634.6 1738.12  4657.2 1738.61  4706.4 1738.96  4855.2 1735.46  4869.9  1736.1
  4890.3 1734.64  4927.2 1733.87  4958.4 1730.67  4982.1 1731.35  4982.3 1729.26
    4983 1728.76  5017.7 1729.26  5021.3  1732.1  5173.2 1733.06  5214.8 1731.99
  5328.3 1733.36  5337.9 1733.34  5576.7 1734.86  5898.7    1736  6105.3 1740.25
  6268.6 1746.47  6489.6 1758.26  6553.7  1762.9  6606.8 1763.95  6631.3 1764.17
#Mann= 13 ,-1 , 0
    3319     .07       0  3526.5    .045       0  4634.6    .035       0
  4657.2    .045       0  4855.2     .07       0  4890.3    .045       0
  4982.3    .045       0  5017.7    .045       0  5173.2    .035       0
  5328.3     .07       0  5337.9    .035       0  5576.7     .07       0
  6606.8    .045       0
Bank Sta=4982.3,5017.7
XS Rating Curve= 0 ,0
Exp/Cntr=0.3,0.1

Type RM Length L Ch R = 1 ,22001   ,1680,1680,1680
BEGIN DESCRIPTION:
BULL WAGON CREEK 19.0
END DESCRIPTION:
XS GIS Cut Line= 4
      1533355.03      6862587.97      1534930.71      6861266.41
      1534979.32      6861096.27      1535704.96      6860538.03
#Sta/Elev= 30
  2861.9 1759.51  2915.7 1757.22  2961.6 1755.93  3273.6 1749.62  3933.2 1743.32
  4133.3 1739.09  4265.7 1736.71    4408 1734.58  4530.3 1733.34    4628 1731.74
    4922 1731.66    5000 1731.72  5007.8 1729.96  5008.6 1729.46  5043.3 1729.96
    5052 1731.92  5119.3 1733.95  5190.9 1732.28  5265.7 1732.39  5482.6 1735.52
  5561.5 1740.34    5576 1739.53  5582.3  1740.8  5590.5 1739.88    5740 1743.18
  5804.4 1747.83  5889.5 1750.59  5968.4 1757.28  6003.7 1758.65  6010.9 1760.08
#Mann= 12 ,-1 , 0
  2861.9    .045       0  2915.7     .07       0  2961.6    .045       0
  4133.3     .07       0  4265.7    .045       0    4408     .07       0
  4530.3    .035       0    4628     .07       0    4922    .035       0
  5007.8    .035       0  5043.3    .035       0  5265.7     .07       0
Bank Sta=5007.8,5043.3
XS Rating Curve= 0 ,0
Exp/Cntr=0.3,0.1

Type RM Length L Ch R = 1 ,20321   ,553,553,553
BEGIN DESCRIPTION:
BULL WAGON CREEK 18.0
END DESCRIPTION:
XS GIS Cut Line= 4
      1534454.98      6863038.03      1535146.21      6862028.35
      1535152.72      6861857.78      1535805.01      6860487.98
#Sta/Elev= 30
  3686.2 1756.11  3801.3 1754.22  3892.1 1750.74  3936.3 1749.44  3995.7 1746.83
  4042.9 1747.03  4067.4 1746.72  4097.2 1744.26  4156.2 1743.44    4196 1743.84
  4240.8 1741.75  4267.9 1742.71  4327.4 1739.98  4542.7 1736.97    4860 1730.06
  4901.5 1730.53  4989.4 1728.02  4990.2 1727.52  5025.1 1728.02  5077.9 1729.76
  5383.8  1730.8  5507.5 1732.55  5901.9 1734.17  5975.5 1734.61  6099.6  1738.6
  6206.6 1743.38  6286.2 1745.98  6401.9 1752.56  6492.7 1763.26  6597.7 1765.21
#Mann= 15 ,-1 , 0
  3686.2    .045       0  3892.1     .07       0  3936.3    .045       0
  4042.9     .07       0  4156.2    .045       0    4860     .07       0
  4989.4     .07       0  5025.1     .07       0  5383.8    .035       0
  5507.5     .07       0  5901.9    .035       0  5975.5     .07       0
  6099.6    .035       0  6206.6    .045       0  6286.2     .07       0
Bank Sta=4989.4,5025.1
XS Rating Curve= 0 ,0
Exp/Cntr=0.3,0.1

Type RM Length L Ch R = 1 ,19768   ,508,508,508
BEGIN DESCRIPTION:
BULL WAGON CREEK 17.0
END DESCRIPTION:
XS GIS Cut Line= 4
      1534604.99      6862988.01      1535295.95      6862268.58
      1535476.93      6862207.39      1536355.01      6860787.99
#Sta/Elev= 30
  3887.4  1753.5  4092.6 1747.09  4170.3 1747.11  4191.7 1744.93  4224.2 1744.53
  4269.3 1742.85  4290.4  1743.4  4311.8 1741.85    4347 1742.16  4382.6  1739.9
  4572.6 1736.01  4872.4 1729.25  4947.2 1728.04  4961.1  1726.8  4961.9  1726.3
  4996.8  1726.8  5021.1 1728.93  5235.9 1728.66  5438.4 1730.93  5770.5 1729.81
  5981.6 1731.05  6094.9 1732.27  6127.4 1732.66    6276 1740.33  6316.5 1741.68
  6331.9 1743.03  6426.5 1745.72  6523.6 1751.08  6542.8 1751.76    6745 1760.54
#Mann= 12 ,-1 , 0
  3887.4    .045       0  4224.2     .07       0  4572.6    .045       0
  4872.4     .07       0  4961.1     .07       0  4996.8     .07       0
  5235.9    .045       0  5981.6     .07       0  6094.9    .035       0
    6276     .07       0  6523.6    .035       0  6542.8     .07       0
Bank Sta=4961.1,4996.8
XS Rating Curve= 0 ,0
Exp/Cntr=0.3,0.1

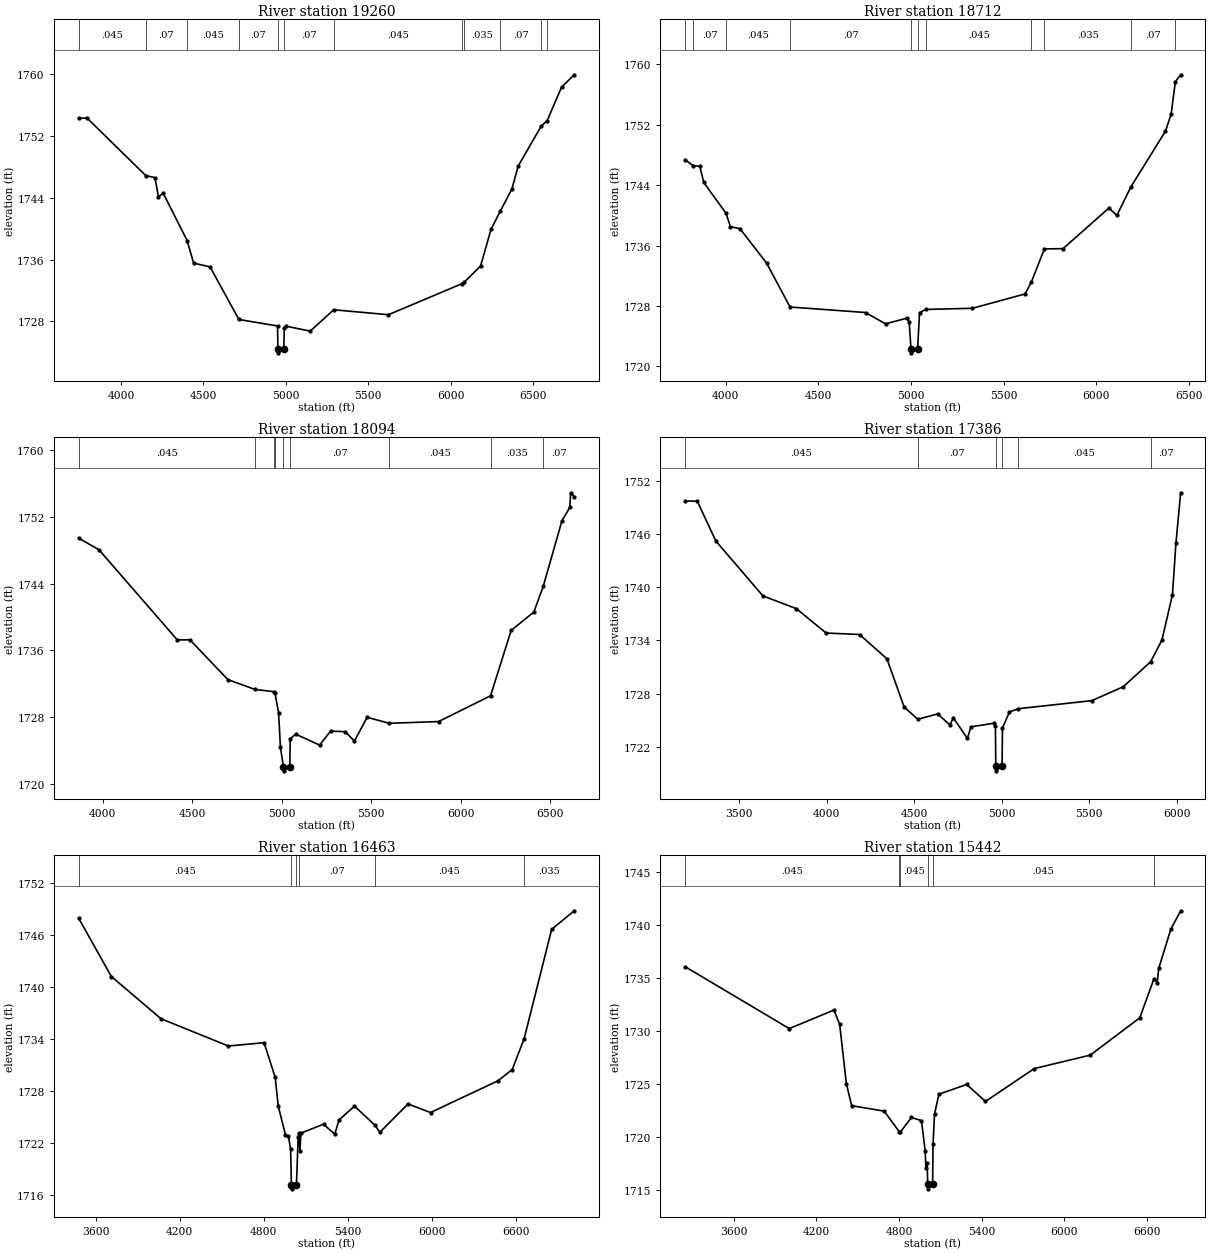
Type RM Length L Ch R = 1 ,19260   ,548,548,548
BEGIN DESCRIPTION:
BULL WAGON CREEK 16.0
END DESCRIPTION:
XS GIS Cut Line= 4
      1534754.98      6863238.02      1535687.87      6862512.72
      1535718.25      6862358.64      1536404.98      6860838.04
#Sta/Elev= 30
  3742.5  1754.3  3793.2 1754.34  4149.8 1746.88  4205.9 1746.61  4226.7 1744.12
  4255.6  1744.6  4400.9 1738.46  4440.2 1735.54  4540.5 1735.04    4715 1728.23
  4949.4 1727.39  4951.9 1724.41  4952.7 1723.91  4987.6 1724.41    4991 1727.19
  5000.3 1727.37  5147.8 1726.72  5290.4 1729.49  5622.5 1728.85  6066.5 1732.85
  6081.7 1733.05  6181.7 1735.16    6245 1739.91  6302.1  1742.3  6372.2 1745.16
  6409.6  1748.1  6549.8 1753.29  6585.9 1753.99  6672.9 1758.33  6749.7 1759.94
#Mann= 12 ,-1 , 0
  3742.5    .045       0  4149.8     .07       0  4400.9    .045       0
    4715     .07       0  4951.9     .07       0  4987.6     .07       0
  5290.4    .045       0  6066.5     .07       0  6081.7    .035       0
  6302.1     .07       0  6549.8    .035       0  6585.9     .07       0
Bank Sta=4951.9,4987.6
XS Rating Curve= 0 ,0
Exp/Cntr=0.3,0.1

Type RM Length L Ch R = 1 ,18712   ,618,618,618
BEGIN DESCRIPTION:
BULL WAGON CREEK 15.0
END DESCRIPTION:
XS GIS Cut Line= 4
      1535104.97      6863038.02       1536041.6      6862410.73
      1536156.62      6862278.35        1536455.      6860938.01
#Sta/Elev= 30
  3780.3 1747.37  3823.4  1746.6  3859.9  1746.5  3880.9 1744.37  4001.4 1740.28
    4025 1738.51    4076 1738.26  4220.1  1733.7  4346.8 1727.87  4754.5 1727.14
  4862.5 1725.64  4976.1 1726.38  4990.3 1725.89    5000  1722.3  5000.8  1721.8
  5035.7  1722.3  5046.3 1727.14  5080.9 1727.55  5331.5  1727.7    5616  1729.6
  5650.3  1731.2  5720.7 1735.57  5820.9  1735.6  6068.4 1740.97  6111.9 1740.01
    6188  1743.8  6374.2 1751.16  6404.9 1753.44  6427.5 1757.71  6456.1 1758.63
#Mann= 11 ,-1 , 0
  3780.3    .045       0  3823.4     .07       0  4001.4    .045       0
  4346.8     .07       0    5000     .07       0  5035.7     .07       0
  5080.9    .045       0  5650.3     .07       0  5720.7    .035       0
    6188     .07       0  6427.5    .035       0
Bank Sta=5000,5035.7
XS Rating Curve= 0 ,0
Exp/Cntr=0.3,0.1

Type RM Length L Ch R = 1 ,18094   ,708,708,708
BEGIN DESCRIPTION:
BULL WAGON CREEK 14.0
END DESCRIPTION:
XS GIS Cut Line= 3
      1535405.03      6863687.97        1536205.        6862888.
      1536555.01      6861287.96
#Sta/Elev= 30
  3864.8 1749.44  3977.9 1748.06  4416.3 1737.26    4487 1737.27  4699.1  1732.5
  4851.3 1731.33    4956 1731.06  4962.1 1730.86    4982 1728.57  4992.6  1724.4
  5008.9 1722.09  5009.7 1721.59  5044.7 1722.09  5047.3 1725.44    5078 1725.98
  5211.5 1724.67  5272.5 1726.34  5354.4 1726.28  5405.6 1725.15  5477.2    1728
    5600 1727.28  5876.5 1727.49  6166.6 1730.57  6281.9  1738.4  6408.8  1740.6
  6461.1 1743.66  6565.6 1751.52  6609.5 1753.11  6614.6 1754.87    6634 1754.41
#Mann= 9 ,-1 , 0
  3864.8    .045       0  4851.3     .07       0    4956    .045       0
  4962.1     .07       0  5008.9     .07       0  5044.7     .07       0
    5600    .045       0  6166.6    .035       0  6461.1     .07       0
Bank Sta=5008.9,5044.7
XS Rating Curve= 0 ,0
Exp/Cntr=0.3,0.1

Type RM Length L Ch R = 1 ,17386   ,923,923,923
BEGIN DESCRIPTION:
Mapping XS 7e136e36
END DESCRIPTION:
XS GIS Cut Line= 4
      1535604.99      6863836.06       1536685.7      6862842.15
      1536690.04      6862503.61      1536646.72      6861481.15
#Sta/Elev= 30
  3192.4  1749.7  3261.6 1749.69  3368.2 1745.19    3637 1739.01  3828.1 1737.57
  3997.7 1734.83  4188.8 1734.66  4344.8 1731.93  4443.5 1726.49  4521.3 1725.11
  4634.6 1725.71  4704.8 1724.48  4724.8 1725.26  4804.8 1722.95  4824.8 1724.26
  4954.8 1724.66  4964.8 1724.34  4966.9  1719.8  4967.7  1719.3  5002.7  1719.8
    5005 1724.13  5044.9 1725.93    5095  1726.3  5515.3 1727.21  5695.5 1728.78
  5851.5  1731.6  5915.7 1734.03  5975.7 1739.12  5995.7 1744.92  6022.6 1750.63
#Mann= 6 ,-1 , 0
  3192.4    .045       0  4521.3     .07       0  4966.9     .07       0
  5002.7     .07       0    5095    .045       0  5851.5     .07       0
Bank Sta=4966.9,5002.7
XS Rating Curve= 0 ,0
Exp/Cntr=0.3,0.1

Type RM Length L Ch R = 1 ,16463   ,1021,1021,1021
BEGIN DESCRIPTION:
BULL WAGON CREEK 13.0
END DESCRIPTION:
XS GIS Cut Line= 3
        1535755.        6863888.        1537055.        6863088.
        1536855.        6861088.
#Sta/Elev= 30
  3478.3 1747.92    3712 1741.19  4065.8 1736.32  4546.8 1733.17  4801.8 1733.55
  4881.1 1729.55  4902.4 1726.26  4954.5 1722.89  4975.7 1722.74  4991.2 1721.23
  4996.8 1717.18  4997.6 1716.68  5032.8 1717.18  5044.9 1722.65  5049.9 1723.13
  5057.5  1721.1    5065 1723.11  5225.8 1724.14  5306.2 1722.98  5336.4 1724.63
  5446.9 1726.23  5590.7 1724.06  5627.8 1723.21  5828.8 1726.48  5989.6 1725.49
    6472 1729.16  6572.5 1730.45  6657.8 1734.02  6853.9 1746.63  7014.7 1748.78
#Mann= 6 ,-1 , 0
  3478.3    .045       0  4996.8    .045       0  5032.8    .045       0
  5049.9     .07       0  5590.7    .045       0  6657.8    .035       0
Bank Sta=4996.8,5032.8
XS Rating Curve= 0 ,0
Exp/Cntr=0.3,0.1

Type RM Length L Ch R = 1 ,15442   ,590,590,590
BEGIN DESCRIPTION:
BULL WAGON CREEK 12.0
END DESCRIPTION:
XS GIS Cut Line= 4
      1536644.86      6864120.57      1537452.16      6863469.52
      1537652.69      6862782.19      1537056.37      6861037.48
#Sta/Elev= 30
  3246.9 1736.05  4003.1 1730.21  4327.3 1731.96  4368.9 1730.61  4417.5 1725.01
  4456.1 1722.94  4691.9 1722.43  4802.1 1720.47    4809 1720.45  4889.8 1721.83
  4962.7 1721.53  4989.6 1718.67  4994.8 1717.04  5004.2  1717.5  5007.6  1715.6
  5008.4  1715.1  5043.6  1715.6  5046.7 1719.35  5057.3 1722.14    5089 1724.02
  5290.8 1724.94  5427.1 1723.34  5781.2 1726.44  6188.3 1727.71  6547.3 1731.23
  6650.2 1734.91  6673.4 1734.54  6684.7 1735.89  6772.6 1739.58  6843.8 1741.32
#Mann= 6 ,-1 , 0
  3246.9    .045       0  4802.1     .07       0    4809    .045       0
  5007.6    .045       0  5043.6    .045       0  6650.2    .035       0
Bank Sta=5007.6,5043.6
XS Rating Curve= 0 ,0
Exp/Cntr=0.3,0.1

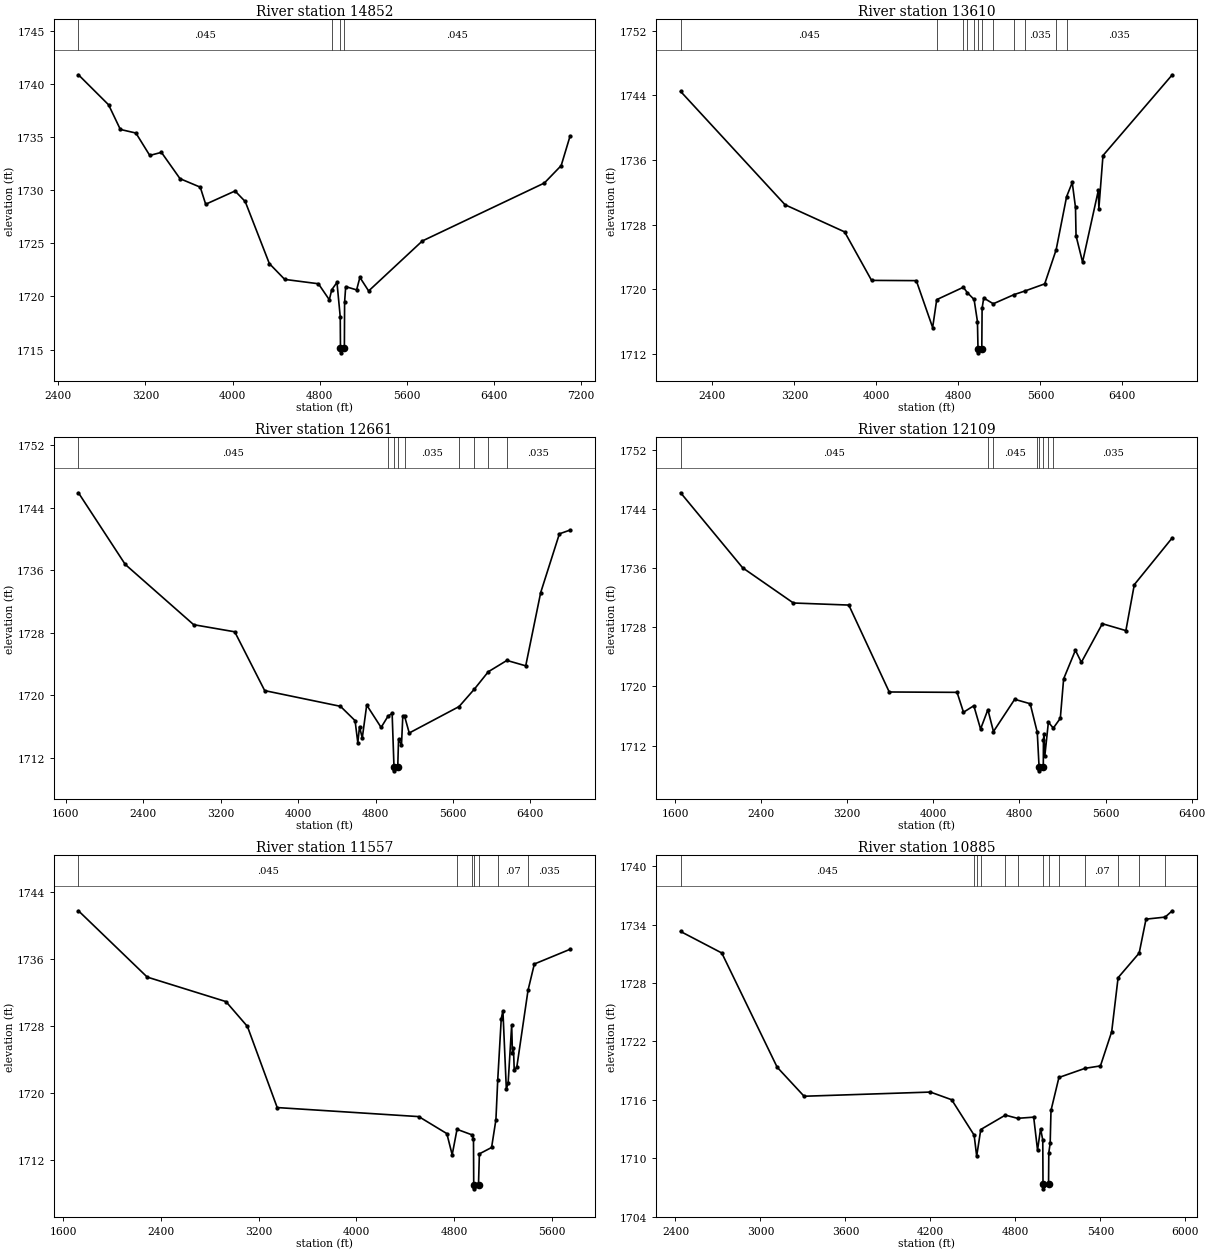
Type RM Length L Ch R = 1 ,14852   ,1242,1242,1242
BEGIN DESCRIPTION:
Mapping XS 0f34ce77
END DESCRIPTION:
XS GIS Cut Line= 4
      1536406.43      6864459.26       1538124.9      6863130.98
      1538083.24      6862630.98       1537173.5      6861026.79
#Sta/Elev= 30
  2584.2 1740.89  2861.4 1738.06  2969.2 1735.74  3112.3  1735.4  3239.6 1733.29
  3346.8 1733.58  3517.7  1731.1  3703.7  1730.3  3753.5 1728.69  4023.3 1729.94
  4116.6 1728.95  4338.5  1723.1  4479.7 1721.61  4789.3  1721.2  4889.6 1719.69
  4911.8 1720.63  4959.9 1721.33    4990 1718.08    4992 1715.19  4992.9 1714.69
    5028 1715.19  5030.1 1719.46  5040.1 1720.93  5140.5 1720.62  5170.6  1721.8
  5250.9 1720.52  5744.2 1725.23  6865.5 1730.69  7020.2 1732.33  7102.1 1735.12
#Mann= 4 ,-1 , 0
  2584.2    .045       0  4911.8     .07       0    4992     .07       0
    5028    .045       0
Bank Sta=4992,5028
XS Rating Curve= 0 ,0
Exp/Cntr=0.3,0.1

Type RM Length L Ch R = 1 ,13610   ,949,949,949
BEGIN DESCRIPTION:
BULL WAGON CREEK 11.0
END DESCRIPTION:
XS GIS Cut Line= 3
      1536304.97      6864638.02       1538785.4      6863117.84
      1539374.77      6861325.97
#Sta/Elev= 30
  2090.8 1744.47    3110 1730.45  3690.3  1727.1  3953.3  1721.1  4389.6 1721.07
    4549 1715.27  4588.7 1718.72  4848.4 1720.25  4888.1 1719.57  4953.3 1718.74
    4986 1716.01  4991.4 1712.64  4992.3 1712.14  5028.4 1712.64  5031.4 1717.64
    5047 1718.92  5140.6 1718.21  5344.9 1719.35  5447.1 1719.78    5642 1720.67
  5753.5 1724.88  5855.7 1731.46  5910.6 1733.21  5942.4 1730.12  5947.7 1726.62
  6011.3 1723.37    6165 1732.22  6170.3 1729.99  6210.4 1736.54  6886.3 1746.53
#Mann= 12 ,-1 , 0
  2090.8    .045       0  4588.7     .07       0  4848.4    .045       0
  4888.1     .07       0  4953.3    .035       0  4991.4    .035       0
  5028.4    .035       0  5140.6    .045       0  5344.9     .07       0
  5447.1    .035       0  5753.5    .045       0  5855.7    .035       0
Bank Sta=4991.4,5028.4
XS Rating Curve= 0 ,0
Exp/Cntr=0.3,0.1

Type RM Length L Ch R = 1 ,12661   ,552,552,552
BEGIN DESCRIPTION:
Mapping XS edec4c4c
END DESCRIPTION:
XS GIS Cut Line= 3
      1536325.89      6864800.18      1539249.48      6863452.97
      1540900.04      6862593.02
#Sta/Elev= 30
  1729.7  1745.9  2213.2 1736.74  2920.5 1729.03  3344.8 1728.12  3654.2  1720.6
  4437.3 1718.59  4588.1 1716.76  4616.6 1713.92    4634 1715.99  4662.5 1714.54
  4708.4 1718.75  4857.2 1715.89  4929.1 1717.34  4971.1 1717.68  4990.3 1710.84
  4991.3 1710.34  5029.1 1710.84  5037.4 1714.39  5067.7 1713.62  5081.6 1717.39
  5099.7 1717.32  5147.9 1715.18  5662.8 1718.56  5822.2 1720.81  5964.6 1723.01
    6157 1724.46  6351.5 1723.77  6506.2 1733.14  6699.4 1740.65  6809.9 1741.13
#Mann= 9 ,-1 , 0
  1729.7    .045       0  4929.1     .07       0  4990.3     .07       0
  5029.1     .07       0  5099.7    .035       0  5662.8     .07       0
  5822.2    .035       0  5964.6     .07       0    6157    .035       0
Bank Sta=4990.3,5029.1
XS Rating Curve= 0 ,0
Exp/Cntr=0.3,0.1

Type RM Length L Ch R = 1 ,12109   ,552,552,552
BEGIN DESCRIPTION:
BULL WAGON CREEK 10.0
END DESCRIPTION:
XS GIS Cut Line= 3
      1536355.02      6864837.99        1539555.        6863838.
      1540735.64      6863550.18
#Sta/Elev= 30
  1651.6 1746.18  2227.8 1736.04  2699.3 1731.28  3214.2    1731  3589.8 1719.25
    4220  1719.2  4279.7 1716.51  4375.6 1717.39  4438.4 1714.24  4506.3 1716.86
  4558.1  1713.9  4755.4 1718.26  4899.4 1717.66  4965.1  1713.8    4982 1709.09
    4983 1708.59  5021.1 1709.09  5022.5 1712.73  5027.6 1713.63  5035.1 1710.59
  5068.4 1715.16  5114.2 1714.37  5179.2 1715.69    5210 1721.02  5319.5 1724.89
  5374.7 1723.26  5569.7 1728.48  5788.4 1727.55  5866.7 1733.76  6219.4 1740.09
#Mann= 8 ,-1 , 0
  1651.6    .045       0  4506.3     .07       0  4558.1    .045       0
  4965.1    .035       0    4982    .035       0  5021.1    .035       0
  5068.4     .07       0  5114.2    .035       0
Bank Sta=4982,5021.1
XS Rating Curve= 0 ,0
Exp/Cntr=0.3,0.1

Type RM Length L Ch R = 1 ,11557   ,672,672,672
BEGIN DESCRIPTION:
BULL WAGON CREEK 9.0
END DESCRIPTION:
XS GIS Cut Line= 3
      1536655.01        6864888.        1539855.        6864188.
      1540455.03      6863737.98
#Sta/Elev= 30
  1723.7 1741.76  2286.7 1733.84  2931.6 1730.91  3107.4 1727.94  3351.3 1718.25
  4510.6 1717.17  4740.2 1715.14    4784 1712.61  4823.7 1715.65    4948 1714.98
  4958.4 1714.49  4960.4 1709.04  4961.4 1708.54  4999.5 1709.04  5006.7 1712.72
  5106.7 1713.48  5142.1  1716.8  5156.9 1721.53  5185.8 1728.87  5199.4 1729.82
  5227.5 1720.45  5242.1 1721.18  5271.2 1728.13  5277.5 1724.74  5285.8 1725.33
  5292.1 1722.71  5312.9 1723.06    5405 1732.26  5456.7  1735.4  5749.4 1737.16
#Mann= 7 ,-1 , 0
  1723.7    .045       0  4823.7     .07       0    4948    .035       0
  4960.4    .035       0  4999.5    .035       0  5156.9     .07       0
    5405    .035       0
Bank Sta=4960.4,4999.5
XS Rating Curve= 0 ,0
Exp/Cntr=0.3,0.1

Type RM Length L Ch R = 1 ,10885   ,485,485,485
BEGIN DESCRIPTION:
BULL WAGON CREEK 8.0
END DESCRIPTION:
XS GIS Cut Line= 3
      1537505.04        6864888.      1539959.99       6864736.1
      1540484.31      6863871.62
#Sta/Elev= 30
  2436.4 1733.31  2726.9  1731.1  3117.7 1719.36    3308 1716.37  4199.7  1716.8
    4350 1716.01  4508.4 1712.37  4526.4 1710.21  4555.2 1712.95  4728.7 1714.43
  4814.8  1714.1  4928.8 1714.22    4956 1710.83  4977.4 1713.03  4992.9 1711.87
  4994.6 1707.35  4995.6 1706.85  5033.7 1707.35  5035.5 1710.57  5045.2 1711.54
    5051 1714.91    5107  1718.3  5291.1 1719.24    5400 1719.49  5479.5 1723.01
  5524.6 1728.56  5673.4 1731.09  5721.8 1734.58  5856.8 1734.79  5907.1 1735.44
#Mann= 13 ,-1 , 0
  2436.4    .045       0  4508.4     .07       0  4526.4    .045       0
  4555.2     .07       0  4728.7    .045       0  4814.8     .07       0
  4994.6     .07       0  5033.7     .07       0    5107    .035       0
  5291.1     .07       0  5524.6    .035       0  5673.4     .07       0
  5856.8    .035       0
Bank Sta=4994.6,5033.7
XS Rating Curve= 0 ,0
Exp/Cntr=0.3,0.1

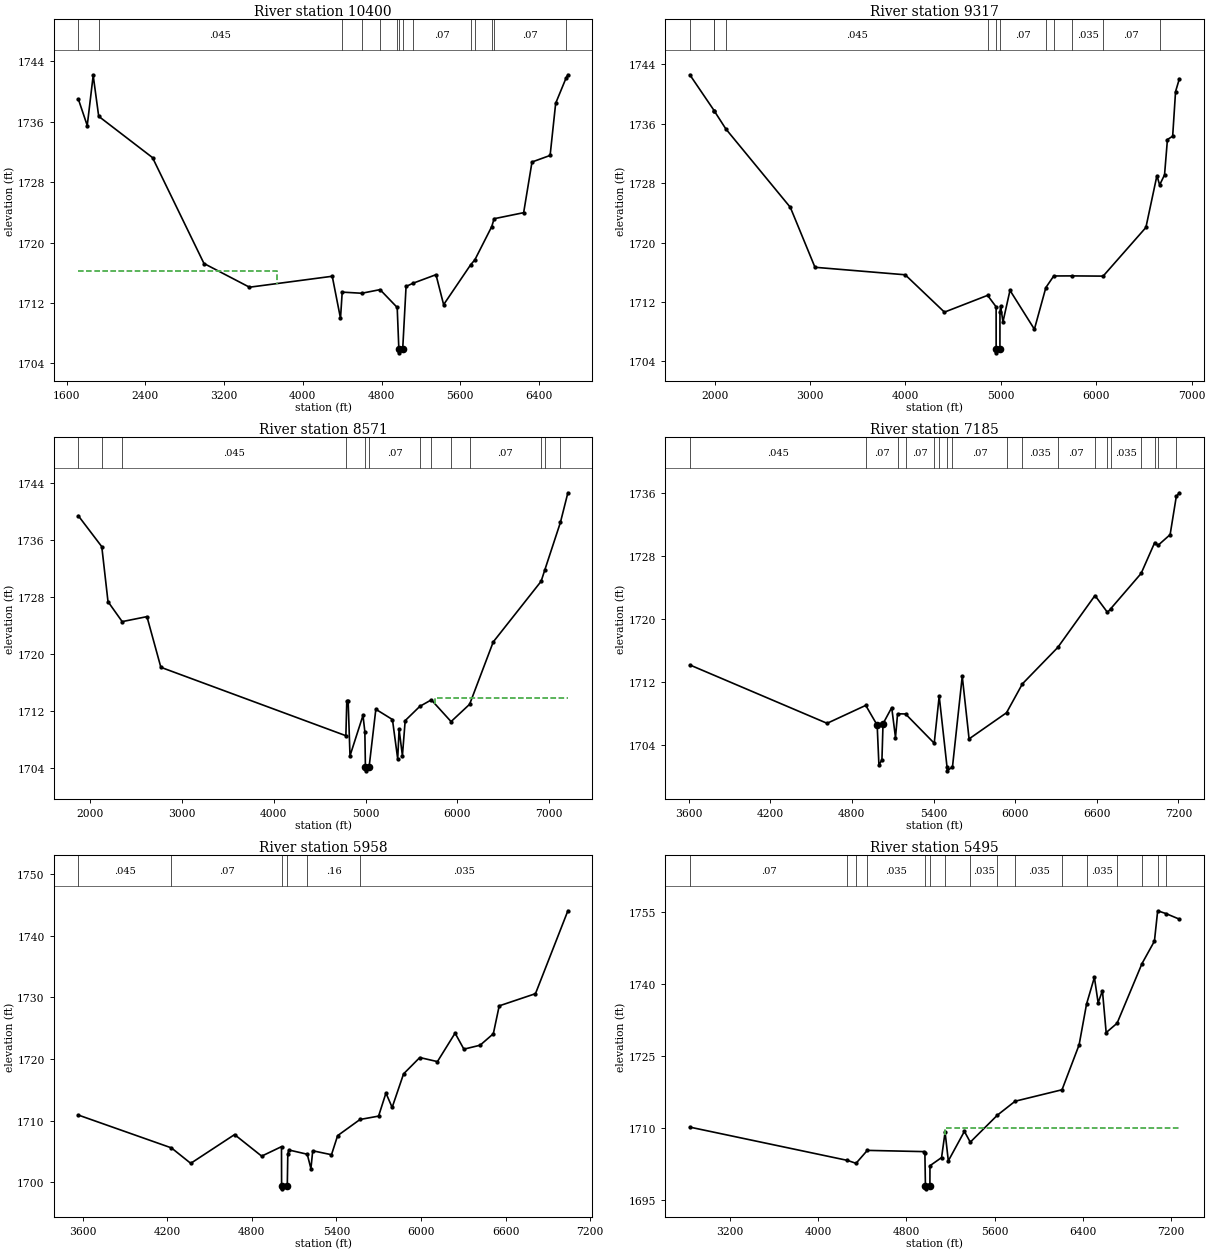
Type RM Length L Ch R = 1 ,10400   ,1083,1083,1083
BEGIN DESCRIPTION:
BULL WAGON CREEK 7.0
END DESCRIPTION:
XS GIS Cut Line= 3
      1536954.95      6865338.01      1540218.62      6865001.25
      1541438.95      6863826.62
#Sta/Elev= 30
    1719 1739.01  1809.5 1735.51    1870 1742.14    1926 1736.73    2473 1731.26
  2995.8 1717.24  3458.2  1714.1  4299.3 1715.55  4383.1 1709.98  4400.5 1713.45
  4599.4  1713.3  4785.1 1713.78  4959.3 1711.42  4976.1 1705.91  4977.1 1705.41
  5015.2 1705.91  5049.4  1714.2  5118.8 1714.62  5353.4 1715.76  5431.1 1711.79
  5706.7 1717.09  5748.2 1717.72  5919.8 1722.12  5944.2 1723.17  6244.3 1723.97
  6329.2 1730.68  6513.2 1731.55  6569.8 1738.46  6676.9 1741.85  6693.8 1742.23
#Mann= 14 ,-1 , 0
    1719     .07       0    1926    .045       0  4400.5     .07       0
  4599.4    .045       0  4785.1     .07       0  4959.3    .035       0
  4976.1    .035       0  5015.2    .035       0  5118.8     .07       0
  5706.7    .035       0  5748.2     .07       0  5919.8    .035       0
  5944.2     .07       0  6676.9    .035       0
#XS Ineff= 2 , 0
       0  3739.7 1716.29  5353.4       0 1715.76
Permanent Ineff=
       F       F
Bank Sta=4976.1,5015.2
XS Rating Curve= 0 ,0
Exp/Cntr=0.3,0.1

Type RM Length L Ch R = 1 ,9317    ,746,746,746
BEGIN DESCRIPTION:
BULL WAGON CREEK 6.0
END DESCRIPTION:
XS GIS Cut Line= 3
      1536804.96        6865538.      1540053.94      6865798.44
      1541805.03      6865137.99
#Sta/Elev= 30
  1740.6 1742.59  1995.8 1737.76  1996.1 1737.74  2118.6 1735.29    2794 1724.74
  3052.3 1716.67  3997.9 1715.66  4409.2 1710.63  4861.5 1712.89  4950.9 1711.34
  4951.1 1705.65  4952.1 1705.15  4990.8 1705.65    4991 1710.61    4998 1711.45
  5022.5 1709.32  5096.2 1713.56    5352 1708.33  5472.2 1713.94  5554.9  1715.5
  5747.5 1715.51  6072.5 1715.48  6520.7 1722.03  6636.3 1729.01  6664.6 1727.75
  6716.1 1729.12  6746.3 1733.87  6801.3 1734.32  6831.5 1740.33  6871.5 1742.05
#Mann= 12 ,-1 , 0
  1740.6     .07       0  1995.8    .045       0  1996.1     .07       0
  2118.6    .045       0  4861.5     .07       0  4951.1     .07       0
  4990.8     .07       0  5472.2    .035       0  5554.9     .07       0
  5747.5    .035       0  6072.5     .07       0  6664.6    .035       0
Bank Sta=4951.1,4990.8
XS Rating Curve= 0 ,0
Exp/Cntr=0.3,0.1

Type RM Length L Ch R = 1 ,8571    ,1386,1386,1386
BEGIN DESCRIPTION:
BULL WAGON CREEK 5.0
END DESCRIPTION:
XS GIS Cut Line= 3
      1536955.01        6865938.      1540052.46      6866381.95
      1541898.65      6865177.02
#Sta/Elev= 30
  1870.9 1739.34  2126.4 1735.01  2194.2 1727.29  2348.7 1724.49  2618.5 1725.19
    2770 1718.08  4785.9 1708.48  4795.7 1713.34  4810.6 1713.32  4830.8 1705.66
  4972.3 1711.33  4992.5 1709.05  4998.8 1704.05  4999.8 1703.55  5038.5 1704.05
  5112.2 1712.19  5293.2 1710.75  5350.5 1705.23  5365.6 1709.37  5401.8 1705.68
  5432.1  1710.6  5591.7  1712.6  5716.9 1713.51  5931.9 1710.46    6134 1712.89
  6391.4 1721.64  6913.2 1730.15  6951.6 1731.68  7123.4 1738.42  7204.6 1742.57
#Mann= 13 ,-1 , 0
  1870.9    .045       0  2126.4     .07       0  2348.7    .045       0
  4785.9     .07       0  4998.8     .07       0  5038.5     .07       0
  5591.7    .035       0  5716.9     .07       0  5931.9    .035       0
    6134     .07       0  6913.2    .035       0  6951.6     .07       0
  7123.4    .035       0
#XS Ineff= 2 , 0
       0                  5755.3       0 1713.72
Permanent Ineff=
       F       F
Bank Sta=4998.8,5038.5
XS Rating Curve= 0 ,0
Exp/Cntr=0.3,0.1

Type RM Length L Ch R = 1 ,7185    ,1227,1227,1227
BEGIN DESCRIPTION:
Mapping XS 93a63eda
END DESCRIPTION:
XS GIS Cut Line= 3
      1539505.36      6868005.06      1540468.31      6867001.39
      1541864.67      6865292.29
#Sta/Elev= 30
  3609.1 1714.17    4618 1706.75    4902 1709.03    4986 1706.52  4998.9 1701.42
  5021.1 1702.13    5029  1706.7  5092.9 1708.75  5120.6 1704.94    5136 1707.96
  5194.4 1707.94  5405.3 1704.22  5441.8 1710.21  5499.3 1701.21  5500.3 1700.71
  5539.5 1701.21  5611.3 1712.73  5661.5 1704.77  5936.5 1708.09  6053.6 1711.77
  6313.2 1716.39  6586.7 1722.99  6678.6 1720.85  6701.8  1721.3  6925.9  1725.8
    7026 1729.73  7049.6 1729.36    7139 1730.73  7184.4 1735.58    7207 1736.05
#Mann= 18 ,-1 , 0
  3609.1    .045       0    4902     .07       0    5136     .16       0
  5194.4     .07       0  5405.3     .16       0  5441.8     .07       0
  5499.3     .07       0  5539.5     .07       0  5936.5     .16       0
  6053.6    .035       0  6313.2     .07       0  6586.7    .035       0
  6678.6     .07       0  6701.8    .035       0  6925.9     .07       0
    7026    .035       0  7049.6     .07       0  7184.4    .035       0
#XS Ineff= 2 , 0
       0                  5611.3       0 1712.73
Permanent Ineff=
       F       F
Bank Sta=4986,5029
XS Rating Curve= 0 ,0
Exp/Cntr=0.3,0.1

Type RM Length L Ch R = 1 ,5958    ,463,463,463
BEGIN DESCRIPTION:
BULL WAGON CREEK 4.0
END DESCRIPTION:
XS GIS Cut Line= 3
      1541042.53      6868535.97      1541424.84      6867158.22
      1542004.87      6865201.17
#Sta/Elev= 30
  3570.2  1710.9  4230.1 1705.57  4367.2 1703.06    4678 1707.73  4870.1 1704.23
  5010.7 1705.77  5011.4 1699.42  5012.4 1698.92  5051.7 1699.42  5055.5  1704.6
  5062.8 1705.23  5193.2 1704.54  5219.3  1702.2  5232.1  1705.1  5365.1 1704.46
  5408.7 1707.56  5567.4 1710.18    5699 1710.73  5751.2 1714.47  5795.2 1712.14
  5876.3 1717.59  5991.1 1720.24  6116.2 1719.58  6241.4  1724.2    6304  1721.6
  6418.7 1722.24  6512.6  1724.1  6554.3 1728.63  6811.4 1730.61  7041.2 1744.07
#Mann= 6 ,-1 , 0
  3570.2    .045       0  4230.1     .07       0  5011.4     .07       0
  5051.7     .07       0  5193.2     .16       0  5567.4    .035       0
Bank Sta=5011.4,5051.7
XS Rating Curve= 0 ,0
Exp/Cntr=0.3,0.1

Type RM Length L Ch R = 1 ,5495    ,1068,1068,1068
BEGIN DESCRIPTION:
Mapping XS cd53692f
END DESCRIPTION:
XS GIS Cut Line= 3
      1541208.36      6869504.76      1541788.42       6867421.3
      1542411.51      6865234.01
#Sta/Elev= 30
  2837.3 1710.14  4266.1  1703.2  4343.7 1702.59  4446.1 1705.29  4961.9 1705.03
  4967.8 1704.76  4972.8 1697.77  4973.8 1697.27  5013.2 1697.77  5013.8 1702.09
  5119.1 1703.79  5150.8  1709.1  5180.2  1703.1  5325.8 1709.25  5379.2    1707
  5625.1 1712.64  5785.9 1715.54  6210.8 1717.93  6365.5 1727.29    6433  1735.8
  6504.1 1741.37  6537.9 1736.07    6577 1738.58  6610.8 1729.85  6709.7  1731.8
  6935.8 1744.25  7048.2 1748.92  7077.7 1755.25  7152.4 1754.67  7274.3  1753.5
#Mann= 16 ,-1 , 0
  2837.3     .07       0  4266.1    .035       0  4343.7     .07       0
  4446.1    .035       0  4972.8    .035       0  5013.2    .035       0
  5150.8     .07       0  5379.2    .035       0  5625.1     .07       0
  5785.9    .035       0  6210.8     .07       0    6433    .035       0
  6709.7     .07       0  6935.8    .035       0  7077.7     .07       0
  7152.4    .035       0
#XS Ineff= 2 , 0
       0                  5147.8       0 1710.05
Permanent Ineff=
       F       F
Bank Sta=4972.8,5013.2
XS Rating Curve= 0 ,0
Exp/Cntr=0.3,0.1