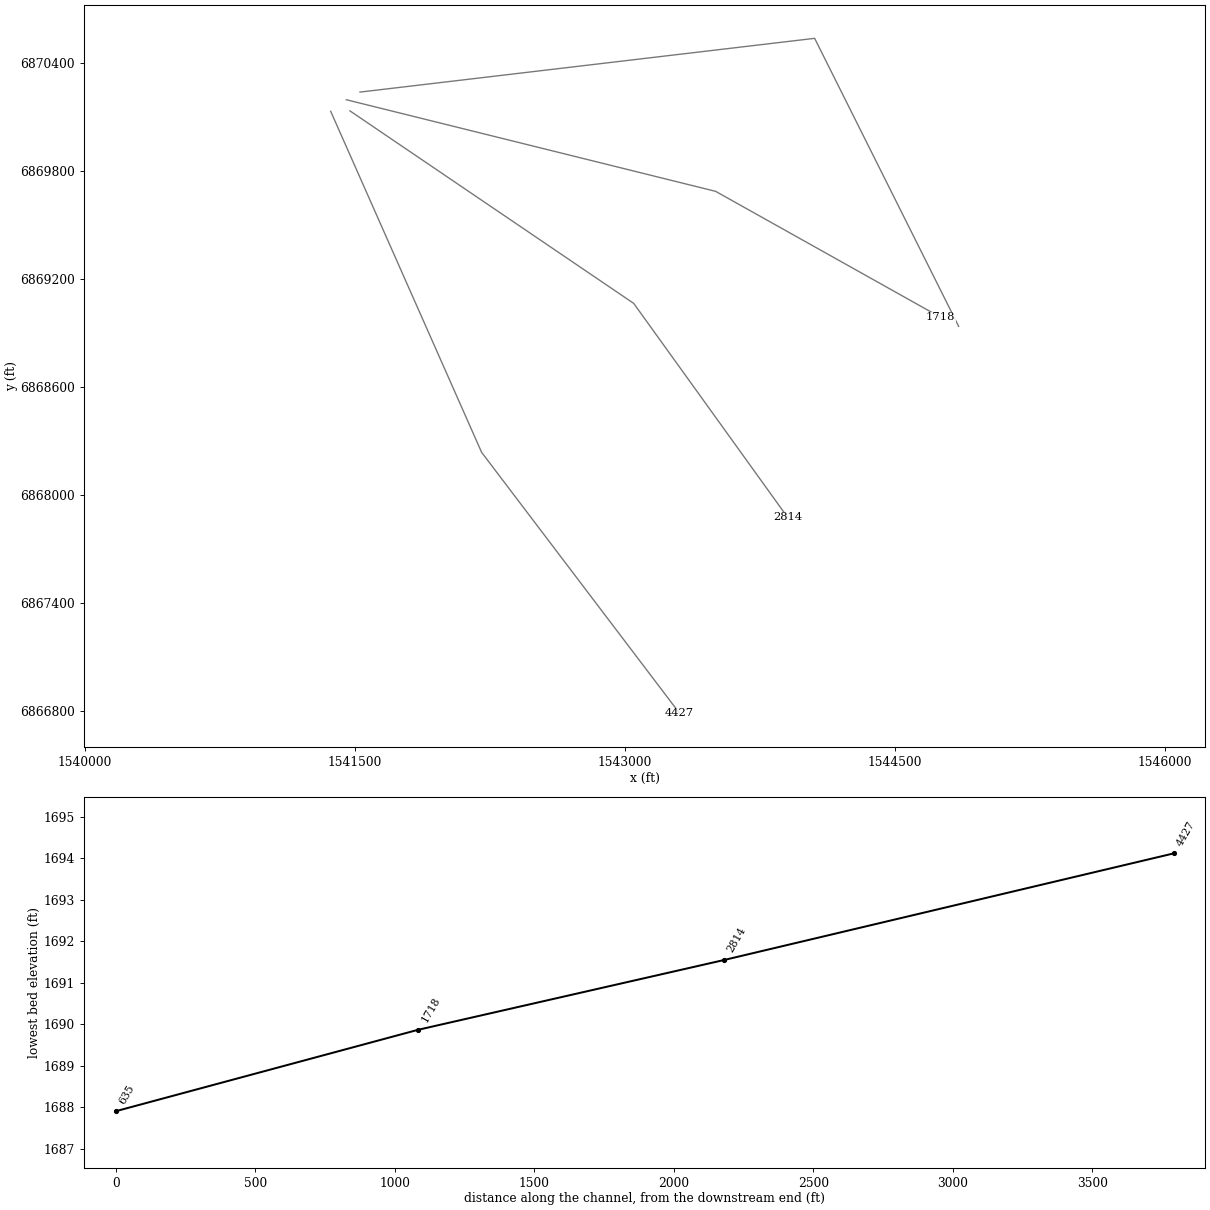
HEC-RAS study BULL WAGON CREEK.prj: BULL WAGON CREEK Base Level Engineering

--- BULL WAGON CREEK.g01 (geometry) --- (continued)

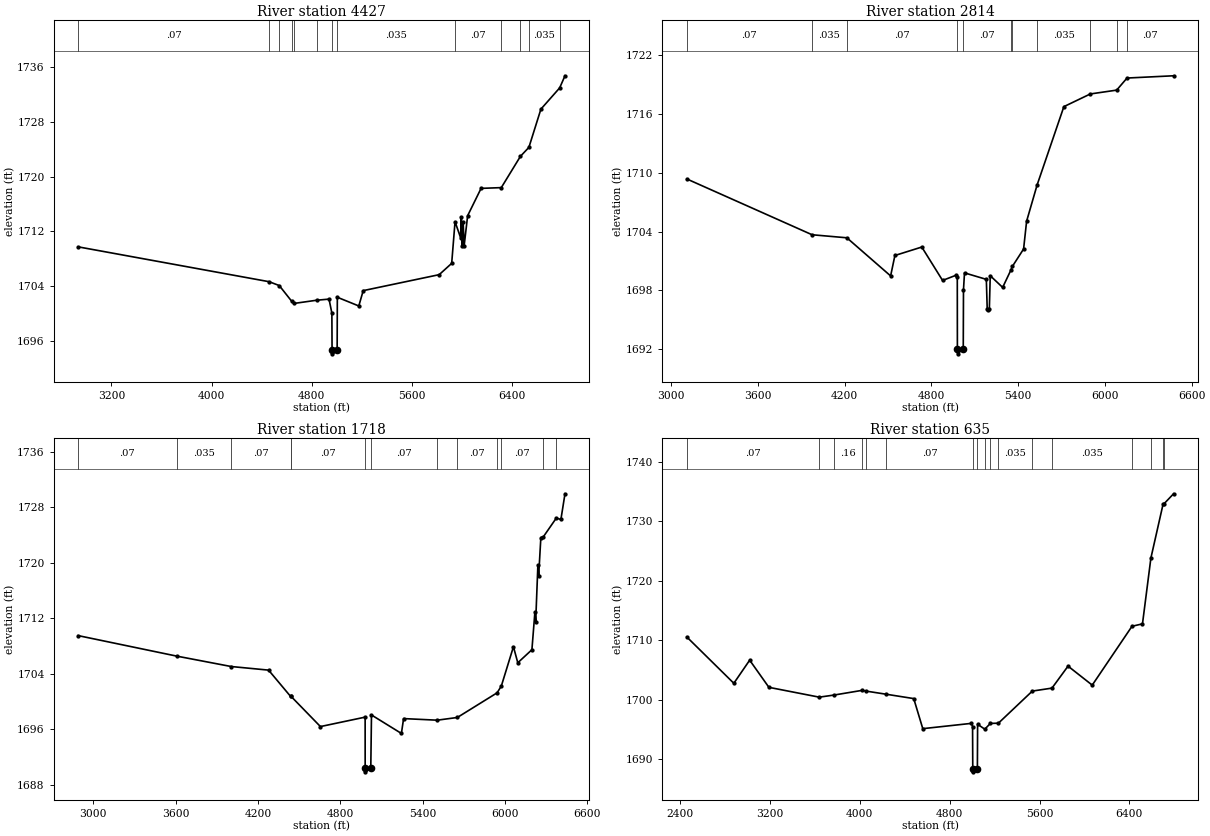
Type RM Length L Ch R = 1 ,4427    ,1613,1613,1613
BEGIN DESCRIPTION:
BULL WAGON CREEK 3.0
END DESCRIPTION:
XS GIS Cut Line= 3
      1541366.49      6870132.67        1542205.        6868238.
      1543305.03      6866787.96
#Sta/Elev= 30
  2933.9 1709.74    4461 1704.65  4541.5 1704.09    4642 1701.77  4659.7 1701.48
  4841.5 1701.95  4939.4 1702.11  4962.1 1700.07  4963.7 1694.62  4964.7 1694.12
  5004.3 1694.62  5005.8 1702.38  5177.4 1701.11  5212.8 1703.35  5820.1 1705.68
    5920 1707.33  5946.9 1713.42  5990.7  1711.1  5997.4 1714.13  6005.3 1709.83
  6011.5 1713.38  6019.8 1709.92  6047.6 1714.29    6155 1718.28  6316.7 1718.39
  6470.1 1722.97  6537.2 1724.26  6633.4 1729.85  6783.3 1732.95  6825.9 1734.72
#Mann= 13 ,-1 , 0
  2933.9     .07       0    4461    .035       0  4541.5     .07       0
    4642    .035       0  4659.7     .07       0  4841.5    .035       0
  4963.7    .035       0  5004.3    .035       0  5946.9     .07       0
  6316.7    .035       0  6470.1     .07       0  6537.2    .035       0
  6783.3     .07       0
Bank Sta=4963.7,5004.3
XS Rating Curve= 0 ,0
Exp/Cntr=0.3,0.1

Type RM Length L Ch R = 1 ,2814    ,1096,1096,1096
BEGIN DESCRIPTION:
Mapping XS 8f6dc540
END DESCRIPTION:
XS GIS Cut Line= 3
      1541473.47      6870135.03      1543049.89      6869065.56
      1543904.03       6867878.1
#Sta/Elev= 30
  3107.2 1709.35    3974 1703.67  4214.7 1703.36  4517.4 1699.48    4547 1701.56
    4733 1702.42  4876.8 1699.02    4970 1699.55  4978.6 1699.39  4979.3 1692.05
  4980.3 1691.55  5019.9 1692.05  5021.5 1698.07  5028.5 1699.79  5179.5 1699.13
  5185.7 1696.09  5193.9 1696.02  5200.4 1696.13  5206.6  1699.5  5292.5 1698.31
  5348.3 1700.04  5359.4 1700.44  5437.3 1702.22  5458.2 1705.05  5530.9 1708.74
    5716 1716.71    5899    1718  6081.2 1718.39  6152.9 1719.62  6474.9 1719.85
#Mann= 11 ,-1 , 0
  3107.2     .07       0    3974    .035       0  4214.7     .07       0
  4979.3     .07       0  5019.9     .07       0  5348.3     .16       0
  5359.4     .07       0  5530.9    .035       0    5899     .07       0
  6081.2    .035       0  6152.9     .07       0
#XS Ineff= 2 , 0
       0  4704.1 1702.27               0
Permanent Ineff=
       F       F
Bank Sta=4979.3,5019.9
XS Rating Curve= 0 ,0
Exp/Cntr=0.3,0.1

Type RM Length L Ch R = 1 ,1718    ,1083,1083,1083
BEGIN DESCRIPTION:
BULL WAGON CREEK 2.0
END DESCRIPTION:
XS GIS Cut Line= 3
      1541453.51      6870196.89        1543505.        6869688.
      1544754.99      6868988.01
#Sta/Elev= 30
    2891 1709.49  3608.2 1706.54  4005.3 1705.04    4278 1704.52    4438 1700.74
  4440.7 1700.76  4655.6 1696.39  4981.4 1697.75  4981.6 1690.37  4982.6 1689.87
  5022.5 1690.37  5027.6 1698.06  5245.6  1695.4  5261.5 1697.54  5506.6 1697.31
    5653  1697.7  5942.7 1701.25  5973.6 1702.23  6061.8 1707.89  6093.5 1705.58
  6196.4 1707.46  6218.1 1712.87  6223.9 1711.52  6239.8  1719.6  6245.5  1718.1
  6261.5 1723.61  6280.2 1723.74  6374.1 1726.42  6407.6 1726.22  6437.3 1729.92
#Mann= 13 ,-1 , 0
    2891     .07       0  3608.2    .035       0  4005.3     .07       0
    4438     .16       0  4440.7     .07       0  4981.6     .07       0
  5022.5     .07       0  5506.6    .035       0    5653     .07       0
  5942.7    .035       0  5973.6     .07       0  6280.2    .035       0
  6374.1     .07       0
Bank Sta=4981.6,5022.5
XS Rating Curve= 0 ,0
Exp/Cntr=0.3,0.1

Type RM Length L Ch R = 1 ,635     ,0,0,0
BEGIN DESCRIPTION:
BULL WAGON CREEK 1.0
END DESCRIPTION:
XS GIS Cut Line= 3
      1541529.16      6870239.35        1544055.        6870538.
        1544855.      6868937.99
#Sta/Elev= 30
  2460.9 1710.56  2879.6 1702.78  3020.6 1706.66  3191.8  1702.1  3639.8 1700.45
    3767 1700.79    4024  1701.6  4052.3 1701.48    4236 1700.94  4480.7 1700.21
  4561.3 1695.16  4994.3 1696.05  5004.3 1695.51  5006.1 1688.41  5007.1 1687.91
  5047.2 1688.41  5049.1  1695.9  5113.2 1695.07  5162.4 1696.04  5234.3 1696.08
  5536.2 1701.47  5711.1 1701.97    5854 1705.66  6069.3 1702.47  6423.1 1712.35
  6516.5 1712.76  6591.3  1723.8  6699.3 1732.82    6704 1732.84  6793.2  1734.6
#Mann= 17 ,-1 , 0
  2460.9     .07       0  3639.8    .035       0    3767     .16       0
    4024     .07       0  4052.3     .16       0    4236     .07       0
  5006.1     .07       0  5047.2     .07       0  5113.2    .035       0
  5162.4     .07       0  5234.3    .035       0  5536.2     .07       0
  5711.1    .035       0  6423.1     .07       0  6591.3    .035       0
  6699.3     .07       0    6704    .035       0
Bank Sta=5006.1,5047.2
XS Rating Curve= 0 ,0
Exp/Cntr=0.3,0.1

Chan Stop Cuts=-1
Use User Specified Reach Order=0
Composite Channel Slope=5