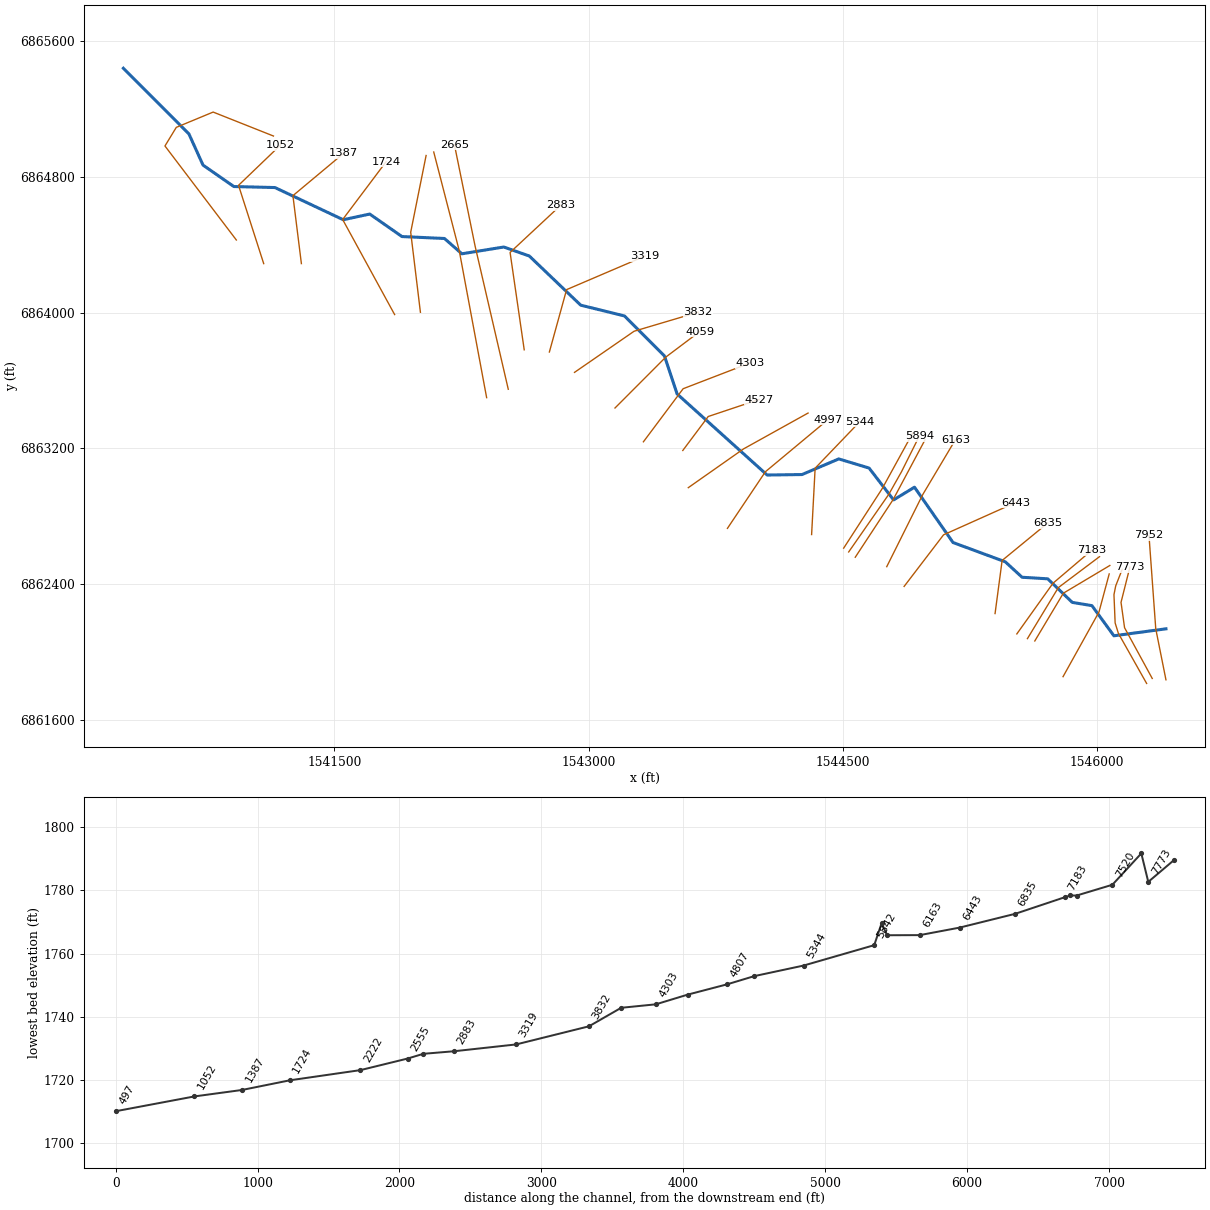
--- BULL WAGON CREEK TRIBUTARY 1.prj (project) ---

Proj Title=BULL WAGON CREEK TRIBUTARY 1 Base Level Engineering
Current Plan=p01
Default Exp/Contr=0.3,0.1
English Units
Geom File=g01
Flow File=f01
Plan File=p01
BEGIN DESCRIPTION:
BULL WAGON CREEK TRIBUTARY 1
END DESCRIPTION:

--- BULL WAGON CREEK TRIBUTARY 1.p01 (plan) ---

Plan Title=Multiple Run
Short Identifier=Multiple
Geom File=g01
Flow File=f01
Subcritical Flow
K Sum by GR= 0
Std Step Tol= 0.01
Critical Tol= 0.01
Num of Std Step Trials= 20
Max Error Tol= 0.3
Flow Tol Ratio= 0.001
Split Flow NTrial= 30
Split Flow Tol= 0.02
Split Flow Ratio= 0.02
Log Output Level= 0
Friction Slope Method= 1
Unsteady Friction Slope Method= 2
Unsteady Bridges Friction Slope Method= 1
Parabolic Critical Depth
Global Vel Dist=  1 , 1 , 1
Global Log Level= 0
CheckData=True
Encroach Param= -1, 0, 0, 0
BEGIN DESCRIPTION:
Multiple Run
END DESCRIPTION:

--- BULL WAGON CREEK TRIBUTARY 1.f01 (steady flow) ---

Flow Title=Multiple
Number of Profiles=7
Profile Names=10-year,25-year,50-year,1pct_min,100-year,1pct_plu,500-year
River Rch & RM= BULL WAGON CREEK,Reach-1,7952
      53      66      77      44      88     177     119
River Rch & RM= BULL WAGON CREEK,Reach-1,5894
     143     192     232     140     280     559     411
Boundary for River Rch & Prof#=BULL WAGON CREEK,Reach-1,1
Up Type=0
Dn Type=3
Dn Slope=0.005
Boundary for River Rch & Prof#=BULL WAGON CREEK,Reach-1,2
Up Type=0
Dn Type=3
Dn Slope=0.005
Boundary for River Rch & Prof#=BULL WAGON CREEK,Reach-1,3
Up Type=0
Dn Type=3
Dn Slope=0.005
Boundary for River Rch & Prof#=BULL WAGON CREEK,Reach-1,4
Up Type=0
Dn Type=3
Dn Slope=0.005
Boundary for River Rch & Prof#=BULL WAGON CREEK,Reach-1,5
Up Type=0
Dn Type=3
Dn Slope=0.005
Boundary for River Rch & Prof#=BULL WAGON CREEK,Reach-1,6
Up Type=0
Dn Type=3
Dn Slope=0.005
Boundary for River Rch & Prof#=BULL WAGON CREEK,Reach-1,7
Up Type=0
Dn Type=3
Dn Slope=0.005

--- BULL WAGON CREEK TRIBUTARY 1.g01 (geometry) ---

Geom Title=Existing Conditions

River Reach=BULL WAGON CREEK,Reach-1
Reach XY= 30
      1546405.00      6862138.00      1546097.98      6862097.01
      1545968.33      6862274.61      1545852.57      6862293.52
      1545707.45      6862432.53      1545556.47      6862441.56
      1545457.42      6862532.46      1545148.93      6862646.13
      1544921.67      6862971.80      1544798.32      6862896.96
      1544653.72      6863084.48      1544475.18      6863138.28
      1544258.22      6863046.28      1544052.57      6863043.40
      1543521.30      6863520.87      1543446.86      6863744.06
      1543211.06      6863979.86      1542952.55      6864043.47
      1542649.52      6864332.71      1542499.07      6864385.74
      1542251.59      6864345.81      1542149.14      6864435.92
      1541898.34      6864447.31      1541708.23      6864579.77
      1541551.78      6864546.27      1541149.07      6864735.76
      1540906.55      6864741.75      1540724.77      6864867.87
      1540641.46      6865051.54      1540255.00      6865438.00

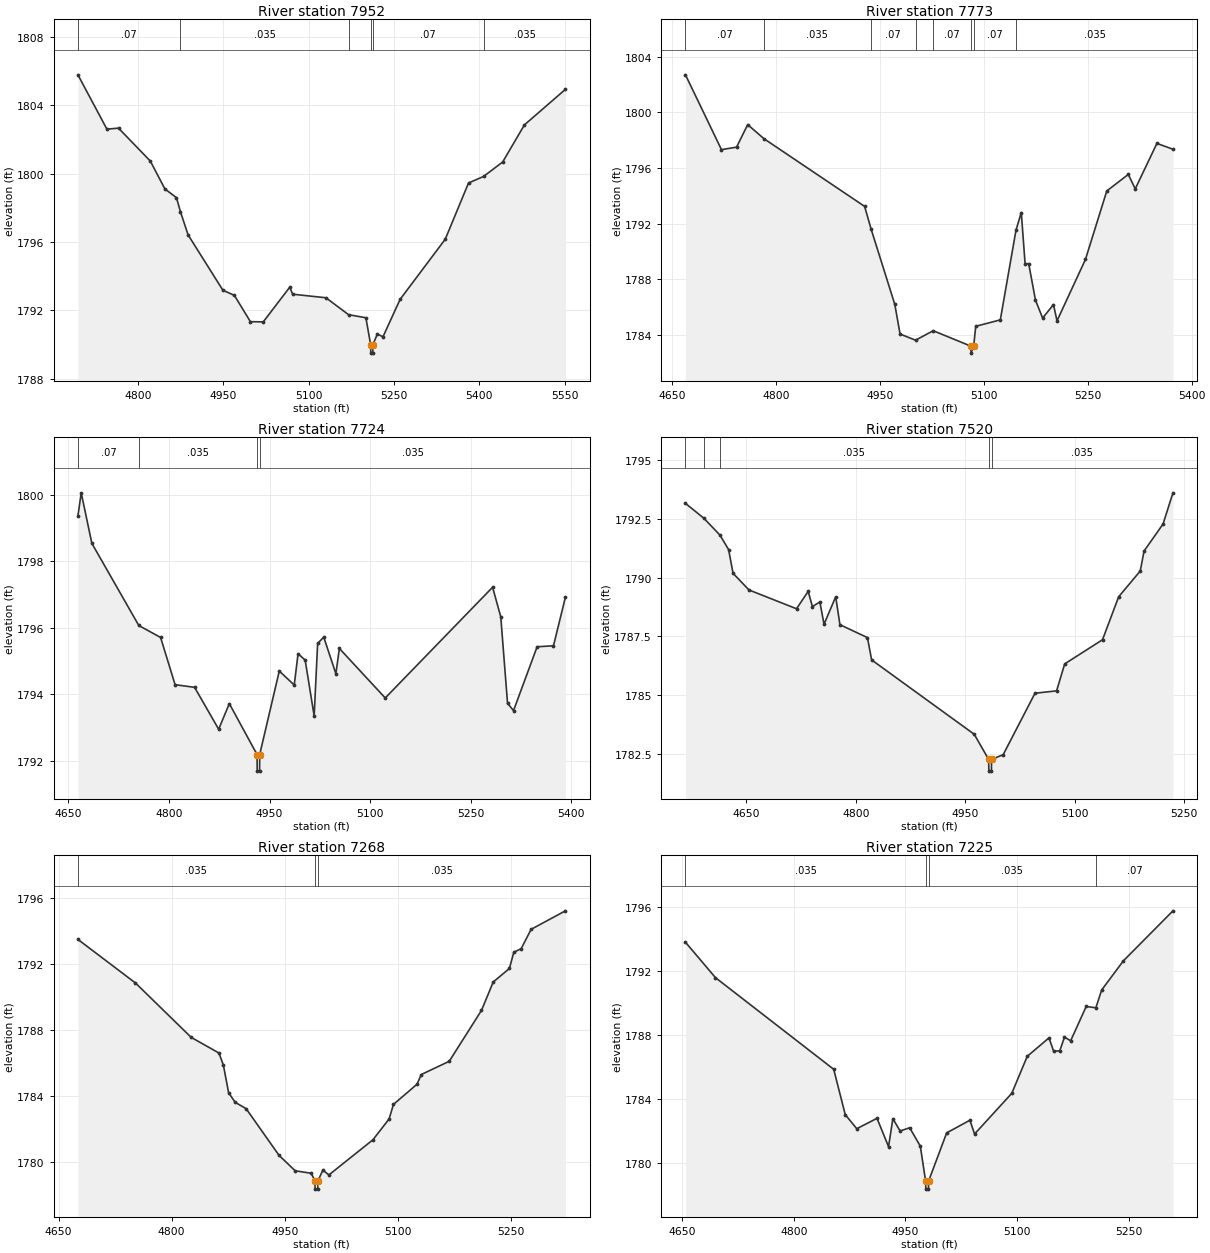
Type RM Length L Ch R = 1,7952,179,179,179
BEGIN DESCRIPTION:
BULL WAGON CREEK TRIBUTARY 1 16.0
END DESCRIPTION:
XS GIS Cut Line= 3
      1546405.00      6861837.98      1546344.92      6862138.02
      1546305.00      6862687.97
#Sta/Elev= 30
  4694.0 1805.78  4745.0 1802.60  4765.4 1802.66  4821.4 1800.73  4847.0 1799.10
  4867.3 1798.59  4874.3 1797.77  4887.8 1796.41  4949.0 1793.17  4969.2 1792.87
  4997.4 1791.33  5020.0 1791.32  5066.6 1793.35  5071.6 1792.94  5130.3 1792.73
  5170.0 1791.74  5200.5 1791.56  5208.8 1789.99  5209.1 1789.49  5212.6 1789.49
  5212.8 1789.99  5220.6 1790.60  5230.6 1790.45  5260.7 1792.64  5340.1 1796.16
  5381.0 1799.45  5407.4 1799.83  5441.1 1800.68  5479.3 1802.85  5551.4 1804.93
#Mann=6,-1,0
  4694.0    0.07       0  4874.3   0.035       0  5170.0    0.07       0
  5208.8   0.035       0  5212.8    0.07       0  5407.4   0.035       0
Bank Sta=5208.8,5212.8
Exp/Cntr=0.3,0.1

Type RM Length L Ch R = 1,7773,49,49,49
BEGIN DESCRIPTION:
Mapping XS 2ea2064f
END DESCRIPTION:
XS GIS Cut Line= 4
      1546324.11      6861845.94      1546160.89      6862144.60
      1546140.06      6862293.90      1546192.15      6862500.54
#Sta/Elev= 30
  4668.8 1802.69  4720.8 1797.31  4742.6 1797.49  4758.7 1799.11  4782.1 1798.10
  4927.6 1793.23  4936.7 1791.64  4971.2 1786.18  4978.8 1784.05  5001.2 1783.61
  5026.7 1784.29  5081.1 1783.18  5081.3 1782.68  5085.1 1783.18  5088.1 1784.61
  5123.6 1785.07  5146.3 1791.53  5153.9 1792.79  5159.4 1789.11  5164.6 1789.11
  5174.4 1786.49  5184.7 1785.20  5200.4 1786.17  5205.5 1785.00  5246.6 1789.42
  5277.4 1794.34  5308.5 1795.53  5318.5 1794.49  5349.8 1797.76  5373.0 1797.34
#Mann=8,-1,0
  4668.8    0.07       0  4782.1   0.035       0  4936.7    0.07       0
  5001.2   0.035       0  5026.7    0.07       0  5081.1    0.07       0
  5085.1    0.07       0  5146.3   0.035       0
Bank Sta=5081.1,5085.1
Exp/Cntr=0.3,0.1

Type RM Length L Ch R = 1,7724,204,204,204
BEGIN DESCRIPTION:
Mapping XS 94f2876e
END DESCRIPTION:
XS GIS Cut Line= 6
      1546291.10      6861816.48      1546124.43      6862111.61
      1546105.34      6862172.38      1546098.39      6862339.04
      1546108.81      6862391.13      1546147.00      6862488.33
#Sta/Elev= 30
  4664.2 1799.36  4669.1 1800.06  4685.0 1798.54  4755.0 1796.07  4787.5 1795.71
  4809.1 1794.29  4838.2 1794.21  4874.1 1792.95  4890.0 1793.72  4931.3 1792.19
  4931.6 1791.69  4935.1 1791.69  4935.3 1792.19  4964.5 1794.70  4986.8 1794.28
  4992.5 1795.22  5003.1 1795.03  5016.5 1793.35  5021.7 1795.53  5030.8 1795.72
  5048.9 1794.62  5054.1 1795.38  5122.5 1793.89  5282.6 1797.22  5294.8 1796.33
  5304.9 1793.73  5313.8 1793.51  5349.0 1795.43  5373.4 1795.46  5391.2 1796.92
#Mann=4,-1,0
  4664.2    0.07       0  4755.0   0.035       0  4931.3   0.035       0
  4935.3   0.035       0
Bank Sta=4931.3,4935.3
Exp/Cntr=0.3,0.1

Type RM Length L Ch R = 1,7520,252,252,252
BEGIN DESCRIPTION:
Mapping XS 199c8e9c
END DESCRIPTION:
XS GIS Cut Line= 3
      1545798.03      6861856.38      1546009.85      6862236.61
      1546070.31      6862461.17
#Sta/Elev= 30
  4566.8 1793.17  4591.9 1792.54  4614.0 1791.82  4625.9 1791.20  4632.0 1790.19
  4653.8 1789.48  4718.9 1788.68  4734.9 1789.42  4740.7 1788.77  4750.9 1788.97
  4756.6 1788.02  4772.6 1789.19  4778.4 1788.00  4816.1 1787.45  4821.8 1786.50
  4962.4 1783.33  4982.1 1782.26  4982.4 1781.76  4985.9 1781.76  4986.1 1782.26
  5002.0 1782.46  5045.6 1785.08  5075.2 1785.18  5086.3 1786.33  5138.1 1787.36
  5160.2 1789.19  5189.8 1790.29  5195.0 1791.14  5221.0 1792.29  5234.6 1793.62
#Mann=5,-1,0
  4566.8   0.035       0  4591.9    0.07       0  4614.0   0.035       0
  4982.1   0.035       0  4986.1   0.035       0
Bank Sta=4982.1,4986.1
Exp/Cntr=0.3,0.1

Type RM Length L Ch R = 1,7268,43,43,43
BEGIN DESCRIPTION:
Mapping XS ac1e2cd6
END DESCRIPTION:
XS GIS Cut Line= 3
      1545631.36      6862066.45      1545799.78      6862347.72
      1546074.07      6862510.91
#Sta/Elev= 30
  4675.6 1793.47  4752.0 1790.83  4825.9 1787.54  4862.8 1786.59  4868.7 1785.85
  4875.6 1784.19  4884.2 1783.61  4898.9 1783.22  4942.6 1780.39  4964.0 1779.46
  4985.3 1779.31  4990.1 1778.85  4990.4 1778.35  4993.9 1778.35  4994.1 1778.85
  5000.7 1779.50  5008.7 1779.21  5067.2 1781.34  5088.6 1782.60  5094.4 1783.48
  5125.6 1784.70  5131.4 1785.29  5168.4 1786.09  5211.2 1789.17  5226.8 1790.89
  5248.3 1791.71  5254.1 1792.69  5263.9 1792.91  5277.1 1794.08  5322.6 1795.20
#Mann=3,-1,0
  4675.6   0.035       0  4990.1   0.035       0  4994.1   0.035       0
Bank Sta=4990.1,4994.1
Exp/Cntr=0.3,0.1

Type RM Length L Ch R = 1,7225,42,42,42
BEGIN DESCRIPTION:
Mapping XS 7d3dbdcb
END DESCRIPTION:
XS GIS Cut Line= 3
      1545588.00      6862080.40      1545770.27      6862380.71
      1546013.31      6862562.99
#Sta/Elev= 30
  4654.4 1793.78  4694.7 1791.57  4853.6 1785.85  4869.1 1783.02  4884.6 1782.14
  4911.8 1782.79  4927.3 1781.02  4933.1 1782.77  4942.8 1782.00  4955.7 1782.20
  4970.0 1781.05  4977.1 1778.87  4977.4 1778.37  4980.9 1778.37  4981.1 1778.87
  5005.4 1781.88  5036.6 1782.67  5042.9 1781.81  5092.9 1784.35  5113.7 1786.66
  5142.9 1787.81  5149.1 1786.98  5157.4 1787.00  5163.7 1787.86  5172.0 1787.63
  5192.9 1789.77  5205.9 1789.69  5213.7 1790.80  5242.9 1792.62  5309.5 1795.74
#Mann=4,-1,0
  4654.4   0.035       0  4977.1   0.035       0  4981.1   0.035       0
  5205.9    0.07       0
Bank Sta=4977.1,4981.1
Exp/Cntr=0.3,0.1

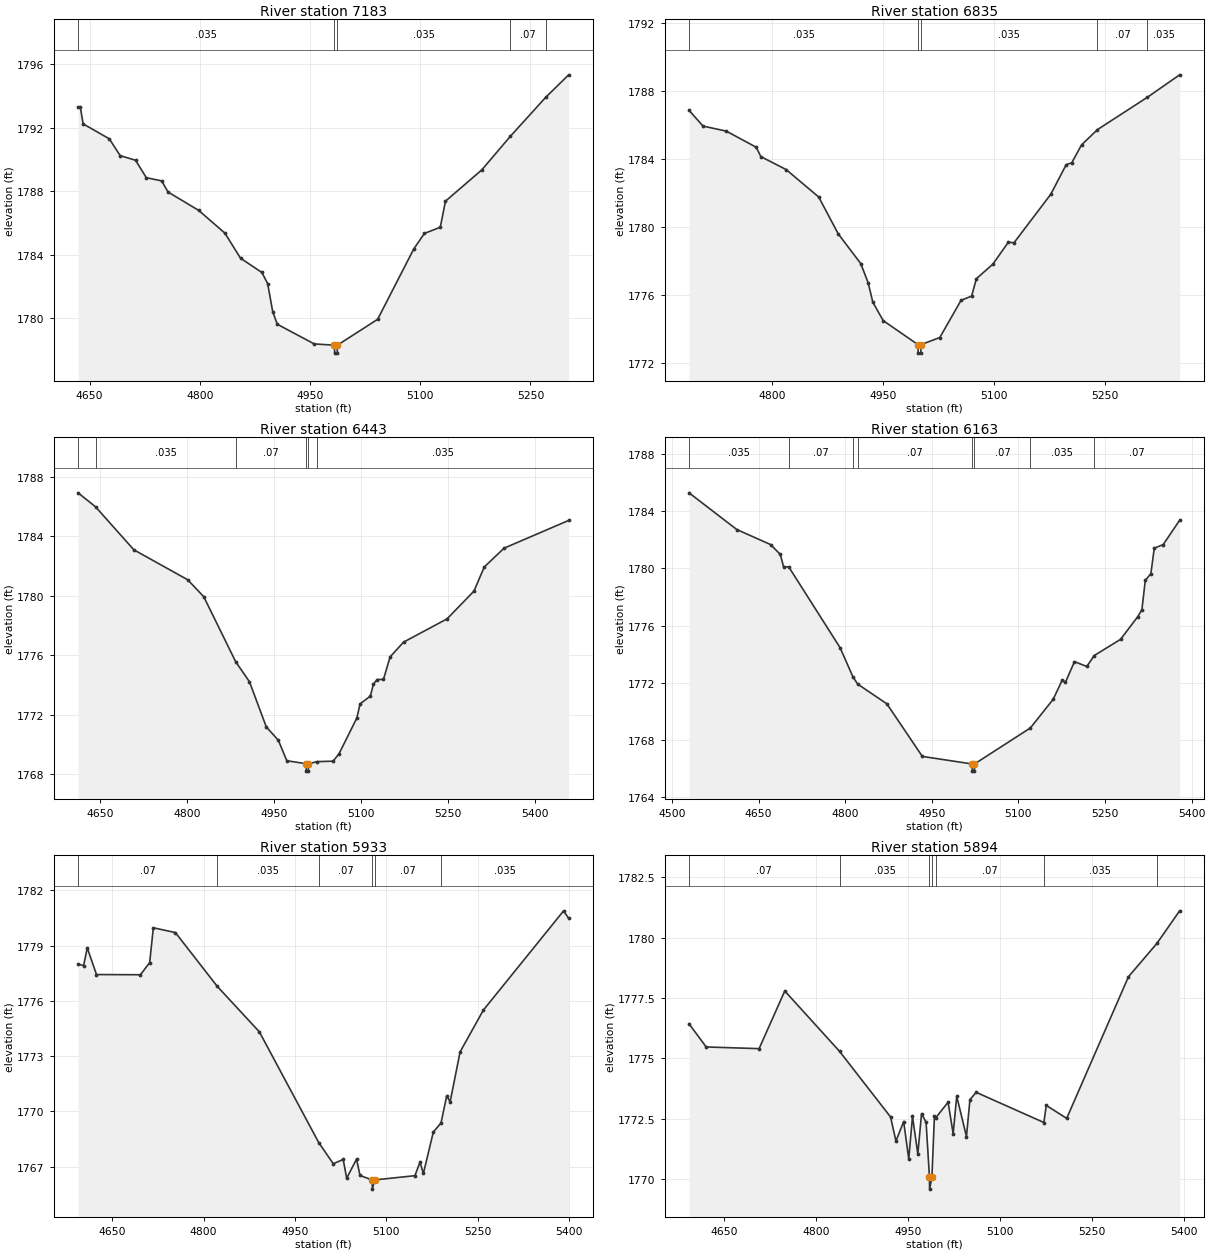
Type RM Length L Ch R = 1,7183,348,348,348
BEGIN DESCRIPTION:
Mapping XS 36bad47e
END DESCRIPTION:
XS GIS Cut Line= 3
      1545525.47      6862108.13      1545739.02      6862406.75
      1545968.21      6862601.22
#Sta/Elev= 30
  4634.4 1793.30  4637.4 1793.30  4641.3 1792.23  4676.9 1791.29  4691.7 1790.23
  4712.6 1789.94  4727.3 1788.84  4748.2 1788.64  4756.8 1787.94  4798.6 1786.78
  4834.2 1785.35  4855.5 1783.77  4884.6 1782.87  4892.4 1782.17  4899.3 1780.41
  4905.5 1779.61  4955.8 1778.37  4983.3 1778.29  4983.6 1777.79  4987.1 1777.79
  4987.3 1778.29  5042.1 1779.92  5091.5 1784.37  5105.8 1785.33  5127.4 1785.72
  5134.4 1787.36  5183.8 1789.33  5222.6 1791.44  5271.0 1793.91  5302.1 1795.32
#Mann=5,-1,0
  4634.4   0.035       0  4983.3   0.035       0  4987.3   0.035       0
  5222.6    0.07       0  5271.0   0.035       0
Bank Sta=4983.3,4987.3
Exp/Cntr=0.3,0.1

Type RM Length L Ch R = 1,6835,392,392,392
BEGIN DESCRIPTION:
Mapping XS 91052dd4
END DESCRIPTION:
XS GIS Cut Line= 3
      1545397.00      6862227.94      1545438.67      6862540.43
      1545707.81      6862760.95
#Sta/Elev= 30
  4687.6 1786.87  4706.5 1785.94  4738.1 1785.64  4778.5 1784.69  4784.7 1784.14
  4818.8 1783.38  4862.9 1781.76  4889.4 1779.58  4919.7 1777.84  4929.8 1776.70
  4936.0 1775.57  4950.0 1774.48  4997.1 1773.06  4997.4 1772.56  5000.9 1772.56
  5001.1 1773.06  5026.6 1773.48  5055.3 1775.67  5069.6 1775.92  5076.1 1776.95
  5098.3 1777.80  5119.1 1779.09  5127.0 1779.07  5176.6 1781.92  5197.4 1783.66
  5205.0 1783.78  5218.2 1784.83  5239.7 1785.73  5307.3 1787.64  5350.8 1788.96
#Mann=5,-1,0
  4687.6   0.035       0  4997.1   0.035       0  5001.1   0.035       0
  5239.7    0.07       0  5307.3   0.035       0
Bank Sta=4997.1,5001.1
Exp/Cntr=0.3,0.1

Type RM Length L Ch R = 1,6443,280,280,280
BEGIN DESCRIPTION:
Mapping XS 642b2a01
END DESCRIPTION:
XS GIS Cut Line= 3
      1544860.56      6862387.67      1545093.18      6862691.47
      1545516.80      6862880.71
#Sta/Elev= 30
  4611.6 1786.94  4641.7 1786.00  4707.9 1783.10  4800.9 1781.08  4828.5 1779.94
  4883.6 1775.56  4907.4 1774.21  4936.4 1771.17  4957.2 1770.27  4971.8 1768.89
  5005.2 1768.69  5005.4 1768.19  5008.9 1768.19  5009.2 1768.69  5024.2 1768.83
  5051.7 1768.86  5061.9 1769.36  5092.7 1771.77  5098.2 1772.72  5115.9 1773.24
  5121.4 1774.06  5127.7 1774.36  5138.6 1774.37  5150.1 1775.89  5173.3 1776.88
  5248.4 1778.45  5294.8 1780.32  5312.5 1781.94  5346.7 1783.21  5458.2 1785.08
#Mann=6,-1,0
  4611.6    0.07       0  4641.7   0.035       0  4883.6    0.07       0
  5005.2    0.07       0  5009.2    0.07       0  5024.2   0.035       0
Bank Sta=5005.2,5009.2
Exp/Cntr=0.3,0.1

Type RM Length L Ch R = 1,6163,230,230,230
BEGIN DESCRIPTION:
Mapping XS a182471b
END DESCRIPTION:
XS GIS Cut Line= 3
      1544758.11      6862503.96      1544969.92      6862927.58
      1545162.64      6863250.52
#Sta/Elev= 30
  4529.5 1785.29  4612.3 1782.72  4670.8 1781.67  4687.6 1780.98  4693.2 1780.12
  4702.2 1780.11  4791.2 1774.45  4813.1 1772.44  4821.5 1771.91  4872.1 1770.53
  4933.6 1766.85  5019.9 1766.32  5020.2 1765.82  5023.7 1765.82  5023.9 1766.32
  5120.7 1768.84  5160.1 1770.84  5175.7 1772.17  5181.5 1772.04  5197.1 1773.48
  5218.5 1773.14  5231.1 1773.90  5276.9 1775.04  5306.4 1776.61  5313.9 1777.12
  5319.7 1779.16  5329.4 1779.64  5335.3 1781.42  5350.8 1781.67  5379.2 1783.37
#Mann=8,-1,0
  4529.5   0.035       0  4702.2    0.07       0  4813.1   0.035       0
  4821.5    0.07       0  5019.9    0.07       0  5023.9    0.07       0
  5120.7   0.035       0  5231.1    0.07       0
Bank Sta=5019.9,5023.9
Exp/Cntr=0.3,0.1

Type RM Length L Ch R = 1,5933,39,39,39
BEGIN DESCRIPTION:
Mapping XS 35b20a28
END DESCRIPTION:
XS GIS Cut Line= 3
      1544572.32      6862559.49      1544796.31      6862899.81
      1544983.82      6863250.51
#Sta/Elev= 30
  4594.0 1778.00  4603.1 1777.92  4609.1 1778.88  4624.2 1777.43  4696.4 1777.42
  4711.5 1778.08  4717.5 1779.97  4753.7 1779.71  4822.4 1776.79  4891.5 1774.32
  4988.9 1768.31  5012.8 1767.16  5029.1 1767.39  5034.8 1766.37  5051.0 1767.41
  5056.7 1766.52  5076.7 1766.28  5077.0 1765.78  5080.7 1766.28  5146.8 1766.51
  5155.1 1767.24  5160.7 1766.63  5177.0 1768.88  5189.6 1769.37  5199.0 1770.85
  5204.6 1770.52  5220.9 1773.23  5259.1 1775.50  5390.8 1780.89  5399.1 1780.48
#Mann=6,-1,0
  4594.0    0.07       0  4822.4   0.035       0  4988.9    0.07       0
  5076.7    0.07       0  5080.7    0.07       0  5189.6   0.035       0
Bank Sta=5076.7,5080.7
Exp/Cntr=0.3,0.1

Type RM Length L Ch R = 1,5894,52,52,52
BEGIN DESCRIPTION:
Mapping XS 0584119d
END DESCRIPTION:
XS GIS Cut Line= 4
      1544533.55      6862590.60      1544769.64      6862929.11
      1544846.03      6863064.53      1544950.10      6863272.67
#Sta/Elev= 30
  4592.1 1776.43  4620.1 1775.47  4706.5 1775.40  4748.4 1777.79  4837.8 1775.29
  4921.1 1772.57  4929.9 1771.57  4942.5 1772.38  4950.8 1770.83  4956.9 1772.59
  4965.6 1771.04  4971.7 1772.71  4979.1 1772.35  4984.6 1770.08  4984.8 1769.58
  4988.6 1770.08  4992.7 1772.59  4995.0 1772.54  5015.0 1773.18  5023.3 1771.88
  5029.1 1773.43  5045.0 1771.76  5050.7 1773.29  5060.9 1773.59  5171.4 1772.34
  5175.3 1773.05  5208.6 1772.51  5309.5 1778.38  5355.9 1779.76  5393.0 1781.11
#Mann=7,-1,0
  4592.1    0.07       0  4837.8   0.035       0  4984.6    0.07       0
  4988.6   0.035       0  4995.0    0.07       0  5171.4   0.035       0
  5355.9    0.07       0
Bank Sta=4984.6,4988.6
Exp/Cntr=0.3,0.1

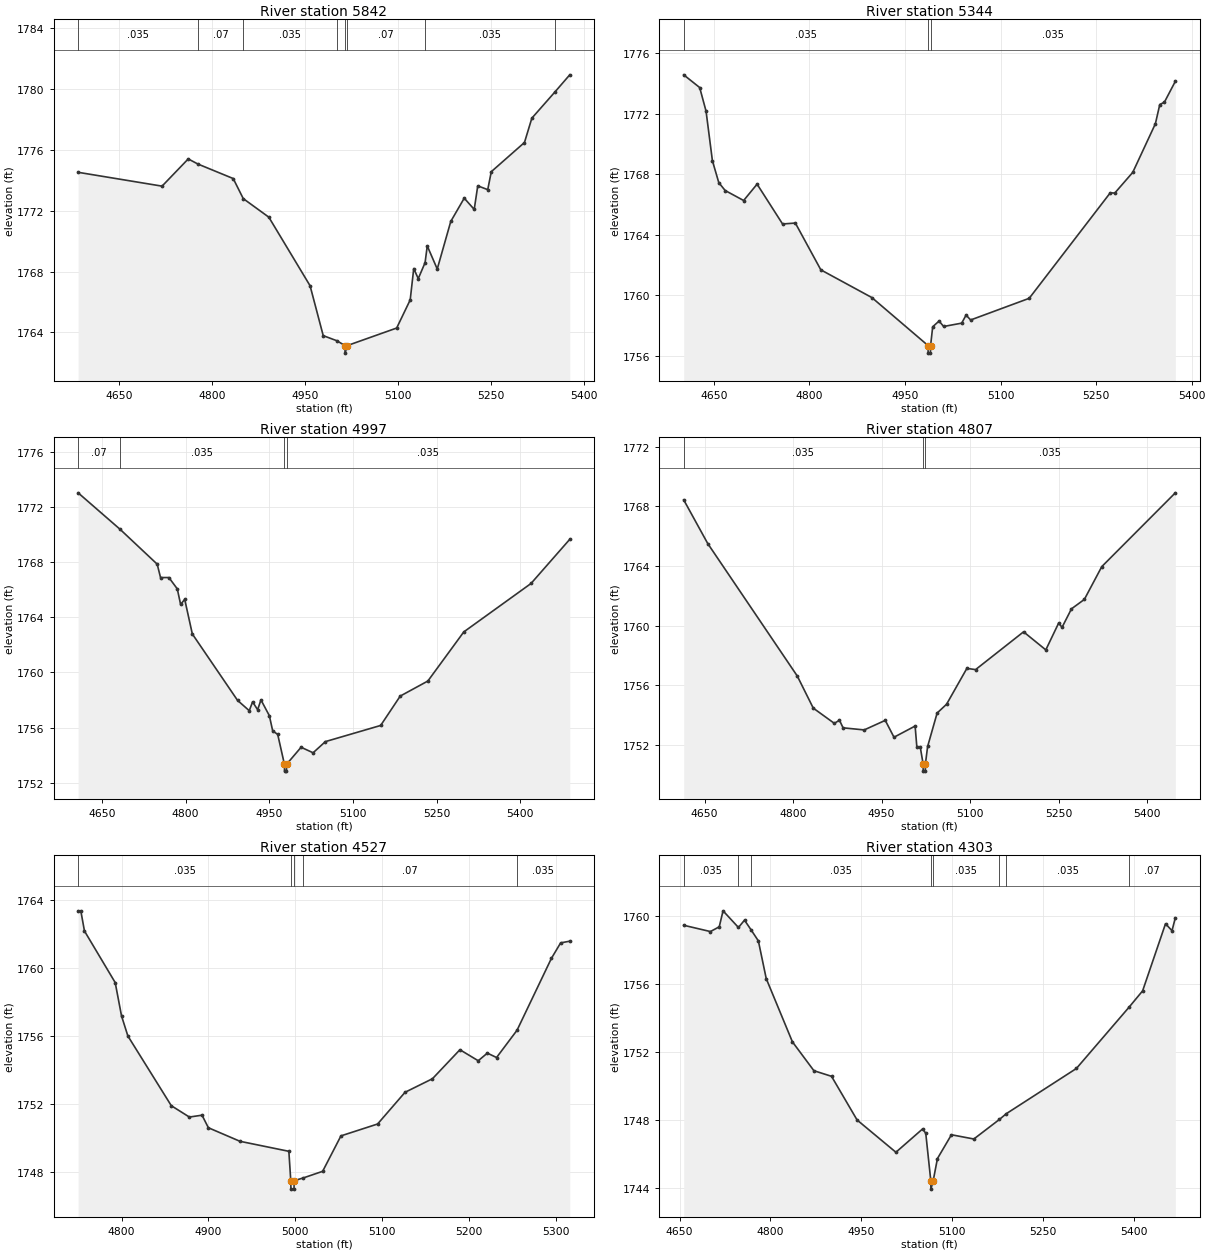
Type RM Length L Ch R = 1,5842,498,498,498
BEGIN DESCRIPTION:
Mapping XS f4e44503
END DESCRIPTION:
XS GIS Cut Line= 3
      1544504.02      6862613.14      1544731.45      6862963.83
      1544912.00      6863291.95
#Sta/Elev= 30
  4584.1 1774.53  4719.4 1773.62  4761.6 1775.41  4777.4 1775.07  4834.1 1774.12
  4850.3 1772.80  4891.5 1771.58  4958.0 1767.07  4979.2 1763.79  5000.8 1763.46
  5014.2 1763.14  5014.4 1762.64  5018.2 1763.14  5097.6 1764.29  5119.4 1766.14
  5125.1 1768.20  5132.4 1767.54  5143.4 1768.59  5146.9 1769.69  5163.0 1768.17
  5184.8 1771.30  5206.5 1772.83  5222.6 1772.09  5228.3 1773.64  5244.4 1773.39
  5250.1 1774.57  5303.6 1776.49  5315.5 1778.09  5352.2 1779.79  5376.6 1780.94
#Mann=8,-1,0
  4584.1   0.035       0  4777.4    0.07       0  4850.3   0.035       0
  5000.8    0.07       0  5014.2   0.035       0  5018.2    0.07       0
  5143.4   0.035       0  5352.2    0.07       0
Bank Sta=5014.2,5018.2
Exp/Cntr=0.3,0.1

Type RM Length L Ch R = 1,5344,347,347,347
BEGIN DESCRIPTION:
Mapping XS df363f67
END DESCRIPTION:
XS GIS Cut Line= 3
      1544314.78      6862692.98      1544335.62      6863083.63
      1544599.48      6863357.91
#Sta/Elev= 30
  4602.6 1774.56  4627.7 1773.72  4637.7 1772.16  4647.7 1768.88  4657.7 1767.44
  4667.7 1766.92  4696.7 1766.26  4717.8 1767.34  4757.8 1764.71  4777.9 1764.77
  4817.9 1761.68  4898.0 1759.85  4986.2 1756.68  4986.4 1756.18  4989.9 1756.18
  4990.2 1756.68  4993.5 1757.92  5003.5 1758.30  5010.7 1757.94  5039.0 1758.16
  5045.9 1758.69  5053.1 1758.37  5145.0 1759.80  5272.3 1766.77  5279.3 1766.75
  5307.6 1768.12  5343.1 1771.33  5350.0 1772.60  5357.2 1772.75  5374.4 1774.13
#Mann=3,-1,0
  4602.6   0.035       0  4986.2   0.035       0  4990.2   0.035       0
Bank Sta=4986.2,4990.2
Exp/Cntr=0.3,0.1

Type RM Length L Ch R = 1,4997,190,190,190
BEGIN DESCRIPTION:
Mapping XS fe862a5f
END DESCRIPTION:
XS GIS Cut Line= 3
      1543818.27      6862729.48      1544042.21      6863062.79
      1544411.04      6863369.28
#Sta/Elev= 30
  4607.4 1773.01  4682.5 1770.37  4749.1 1767.84  4755.1 1766.87  4770.1 1766.87
  4785.1 1766.05  4791.1 1764.92  4798.4 1765.29  4812.1 1762.78  4893.1 1757.97
  4914.1 1757.22  4920.1 1757.86  4929.1 1757.29  4935.1 1758.00  4950.1 1756.86
  4956.1 1755.76  4965.1 1755.50  4977.1 1753.34  4977.3 1752.84  4980.8 1752.84
  4981.1 1753.34  5007.0 1754.57  5028.5 1754.17  5050.6 1754.98  5149.6 1756.15
  5184.7 1758.28  5234.2 1759.37  5298.6 1762.93  5419.1 1766.44  5488.5 1769.64
#Mann=4,-1,0
  4607.4    0.07       0  4682.5   0.035       0  4977.1   0.035       0
  4981.1   0.035       0
Bank Sta=4977.1,4981.1
Exp/Cntr=0.3,0.1

Type RM Length L Ch R = 1,4807,280,280,280
BEGIN DESCRIPTION:
Mapping XS aab31a8a
END DESCRIPTION:
XS GIS Cut Line= 3
      1543587.32      6862969.02      1543912.00      6863196.47
      1544293.98      6863408.30
#Sta/Elev= 30
  4614.7 1768.43  4655.5 1765.50  4807.2 1756.63  4834.3 1754.48  4870.0 1753.46
  4878.7 1753.67  4884.8 1753.16  4920.6 1753.02  4956.3 1753.66  4971.1 1752.53
  5006.9 1753.28  5009.9 1751.85  5015.7 1751.85  5020.4 1750.76  5020.7 1750.26
  5024.2 1750.26  5024.4 1750.76  5028.1 1751.91  5044.2 1754.15  5060.2 1754.74
  5094.6 1757.14  5109.4 1757.06  5190.7 1759.59  5228.4 1758.38  5250.2 1760.18
  5255.9 1759.89  5271.9 1761.13  5293.7 1761.76  5323.3 1763.96  5447.9 1768.90
#Mann=3,-1,0
  4614.7   0.035       0  5020.4   0.035       0  5024.4   0.035       0
Bank Sta=5020.4,5024.4
Exp/Cntr=0.3,0.1

Type RM Length L Ch R = 1,4527,224,224,224
BEGIN DESCRIPTION:
BULL WAGON CREEK TRIBUTARY 1 9.0
END DESCRIPTION:
XS GIS Cut Line= 3
      1543555.01      6863188.01      1543705.00      6863388.00
      1544004.99      6863488.00
#Sta/Elev= 30
  4750.0 1763.38  4753.1 1763.38  4757.3 1762.19  4792.7 1759.15  4800.0 1757.18
  4807.3 1756.00  4857.3 1751.89  4878.1 1751.22  4892.7 1751.33  4900.0 1750.59
  4936.4 1749.79  4992.7 1749.20  4994.9 1747.47  4995.1 1746.97  4998.6 1746.97
  4998.9 1747.47  5009.3 1747.63  5031.6 1748.02  5052.7 1750.11  5094.9 1750.81
  5126.5 1752.68  5158.1 1753.48  5189.7 1755.19  5210.8 1754.54  5221.3 1754.99
  5231.9 1754.73  5255.5 1756.34  5295.1 1760.58  5305.7 1761.49  5316.2 1761.59
#Mann=5,-1,0
  4750.0   0.035       0  4994.9   0.035       0  4998.9   0.035       0
  5009.3    0.07       0  5255.5   0.035       0
Bank Sta=4994.9,4998.9
Exp/Cntr=0.3,0.1

Type RM Length L Ch R = 1,4303,244,244,244
BEGIN DESCRIPTION:
Mapping XS 5b7cb596
END DESCRIPTION:
XS GIS Cut Line= 3
      1543322.57      6863238.98      1543556.97      6863551.51
      1543950.10      6863702.51
#Sta/Elev= 30
  4656.9 1759.44  4701.0 1759.07  4715.6 1759.35  4721.9 1760.29  4747.3 1759.31
  4757.3 1759.74  4768.0 1759.18  4780.2 1758.52  4793.2 1756.30  4836.4 1752.58
  4871.9 1750.88  4901.0 1750.55  4943.2 1747.98  5007.3 1746.08  5051.3 1747.45
  5056.6 1747.20  5064.9 1744.41  5065.1 1743.91  5068.9 1744.41  5075.9 1745.71
  5099.0 1747.11  5136.0 1746.86  5178.2 1748.01  5189.6 1748.35  5305.3 1751.01
  5392.1 1754.61  5414.7 1755.58  5452.5 1759.53  5463.2 1759.12  5468.7 1759.88
#Mann=8,-1,0
  4656.9   0.035       0  4747.3    0.07       0  4768.0   0.035       0
  5064.9   0.035       0  5068.9   0.035       0  5178.2    0.07       0
  5189.6   0.035       0  5392.1    0.07       0
Bank Sta=5064.9,5068.9
Exp/Cntr=0.3,0.1

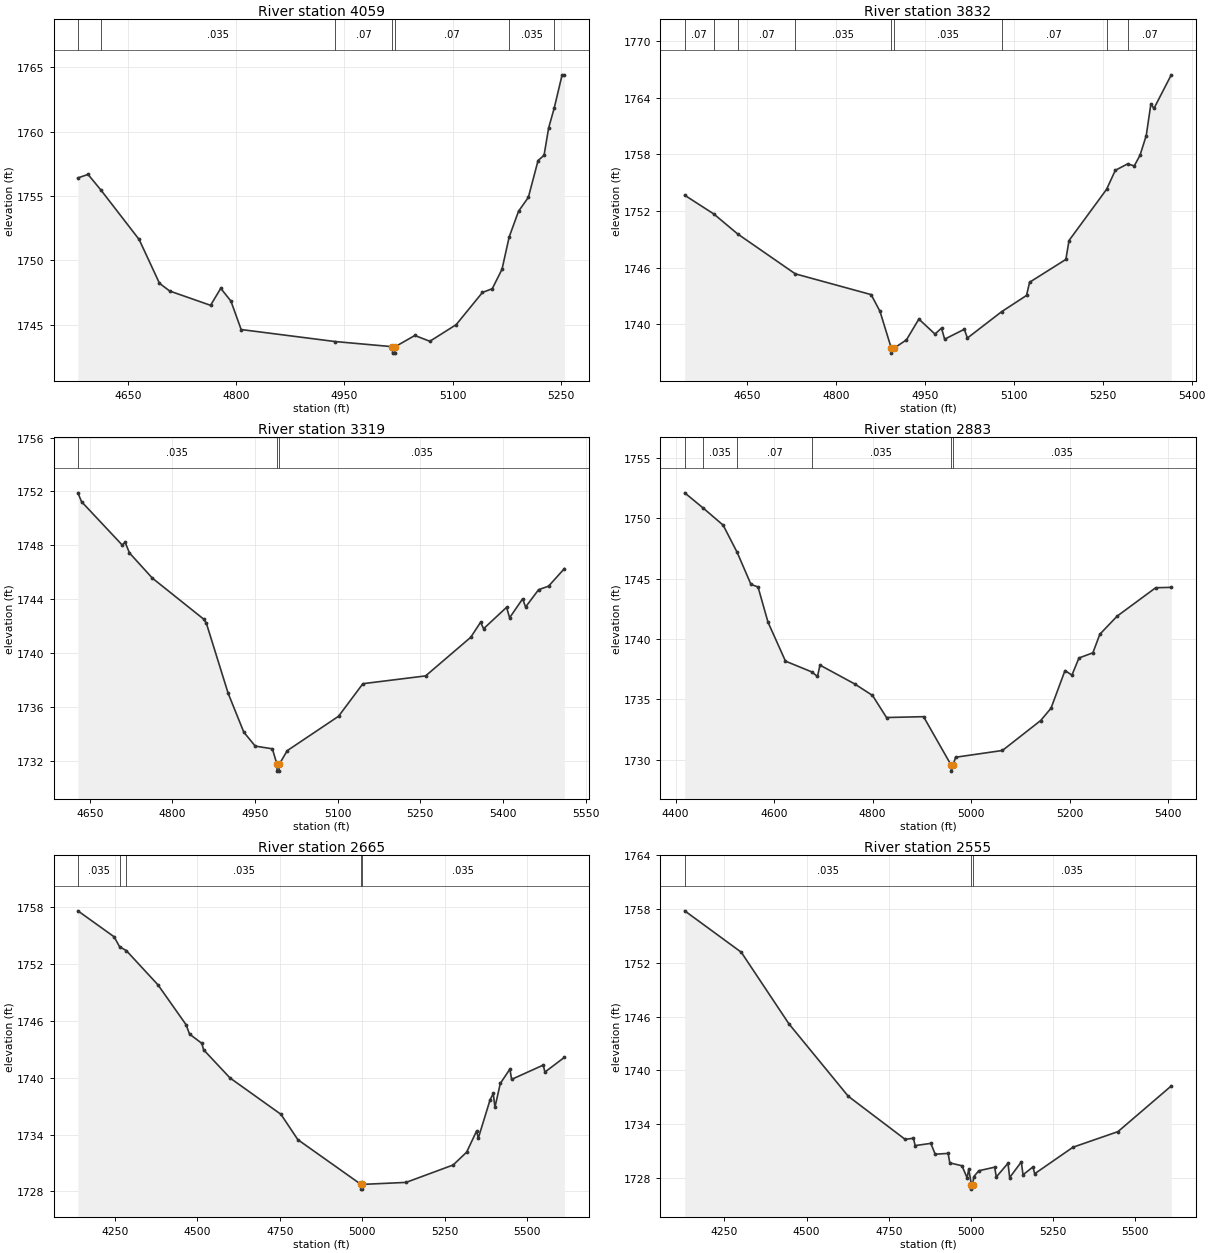
Type RM Length L Ch R = 1,4059,227,227,227
BEGIN DESCRIPTION:
BULL WAGON CREEK TRIBUTARY 1 8.0
END DESCRIPTION:
XS GIS Cut Line= 3
      1543155.00      6863438.00      1543455.00      6863738.00
      1543655.03      6863888.02
#Sta/Elev= 30
  4580.5 1756.41  4594.6 1756.68  4612.7 1755.45  4665.4 1751.63  4693.6 1748.23
  4707.8 1747.63  4764.4 1746.52  4778.5 1747.84  4792.6 1746.85  4806.8 1744.64
  4936.9 1743.71  5016.3 1743.31  5016.6 1742.81  5020.1 1742.81  5020.3 1743.31
  5047.5 1744.18  5068.3 1743.73  5104.8 1745.02  5141.2 1747.52  5154.8 1747.81
  5168.3 1749.32  5178.2 1751.82  5191.2 1753.82  5204.8 1754.90  5218.3 1757.76
  5226.6 1758.17  5232.9 1760.28  5240.8 1761.86  5251.6 1764.41  5254.8 1764.41
#Mann=7,-1,0
  4580.5    0.07       0  4612.7   0.035       0  4936.9    0.07       0
  5016.3    0.07       0  5020.3    0.07       0  5178.2   0.035       0
  5240.8    0.07       0
Bank Sta=5016.3,5020.3
Exp/Cntr=0.3,0.1

Type RM Length L Ch R = 1,3832,513,513,513
BEGIN DESCRIPTION:
Mapping XS 1737bdd8
END DESCRIPTION:
XS GIS Cut Line= 3
      1542916.30      6863647.83      1543267.91      6863890.05
      1543645.50      6864002.02
#Sta/Elev= 30
  4544.8 1753.68  4593.8 1751.70  4634.1 1749.58  4731.4 1745.35  4859.3 1743.15
  4874.2 1741.38  4893.4 1737.45  4893.6 1736.95  4897.4 1737.45  4918.8 1738.35
  4939.8 1740.56  4967.0 1738.97  4978.0 1739.60  4983.3 1738.43  5016.5 1739.48
  5021.7 1738.55  5079.4 1741.34  5121.4 1743.06  5126.6 1744.46  5187.8 1746.88
  5193.1 1748.88  5256.5 1754.31  5271.2 1756.32  5291.8 1757.00  5303.2 1756.79
  5312.9 1757.92  5323.4 1760.01  5331.2 1763.35  5336.4 1762.88  5365.6 1766.44
#Mann=9,-1,0
  4544.8    0.07       0  4593.8   0.035       0  4634.1    0.07       0
  4731.4   0.035       0  4893.4   0.035       0  4897.4   0.035       0
  5079.4    0.07       0  5256.5   0.035       0  5291.8    0.07       0
Bank Sta=4893.4,4897.4
Exp/Cntr=0.3,0.1

Type RM Length L Ch R = 1,3319,436,436,436
BEGIN DESCRIPTION:
Mapping XS 213065a9
END DESCRIPTION:
XS GIS Cut Line= 3
      1542767.92      6863767.69      1542869.47      6864134.84
      1543331.48      6864332.10
#Sta/Elev= 30
  4628.3 1751.90  4635.0 1751.24  4708.8 1748.02  4714.0 1748.23  4722.0 1747.43
  4763.5 1745.56  4856.4 1742.52  4861.6 1742.20  4901.1 1737.00  4929.5 1734.11
  4950.3 1733.07  4981.4 1732.87  4989.8 1731.71  4990.0 1731.21  4993.5 1731.21
  4993.8 1731.71  5008.3 1732.73  5101.6 1735.29  5145.7 1737.71  5259.6 1738.29
  5341.5 1741.16  5359.4 1742.28  5364.9 1741.80  5406.6 1743.39  5412.1 1742.61
  5435.7 1744.02  5441.1 1743.41  5464.7 1744.70  5482.8 1744.96  5511.6 1746.27
#Mann=3,-1,0
  4628.3   0.035       0  4989.8   0.035       0  4993.8   0.035       0
Bank Sta=4989.8,4993.8
Exp/Cntr=0.3,0.1

Type RM Length L Ch R = 1,2883,218,218,218
BEGIN DESCRIPTION:
Mapping XS 4d8c4dd8
END DESCRIPTION:
XS GIS Cut Line= 3
      1542619.47      6863780.70      1542536.14      6864353.59
      1542835.63      6864632.25
#Sta/Elev= 30
  4418.5 1752.11  4456.3 1750.84  4496.6 1749.43  4525.1 1747.17  4553.0 1744.53
  4567.4 1744.31  4587.6 1741.40  4623.1 1738.17  4676.4 1737.28  4688.1 1736.90
  4693.2 1737.84  4763.3 1736.29  4799.8 1735.33  4828.3 1733.50  4903.5 1733.57
  4959.5 1729.56  4959.7 1729.06  4963.5 1729.56  4968.5 1730.21  5063.6 1730.77
  5141.3 1733.25  5162.3 1734.27  5190.7 1737.39  5204.8 1737.01  5219.0 1738.43
  5247.3 1738.86  5261.5 1740.40  5296.7 1741.90  5374.9 1744.25  5406.5 1744.28
#Mann=6,-1,0
  4418.5    0.07       0  4456.3   0.035       0  4525.1    0.07       0
  4676.4   0.035       0  4959.5   0.035       0  4963.5   0.035       0
Bank Sta=4959.5,4963.5
Exp/Cntr=0.3,0.1

Type RM Length L Ch R = 1,2665,110,110,110
BEGIN DESCRIPTION:
Mapping XS fccc7d5e
END DESCRIPTION:
XS GIS Cut Line= 3
      1542525.38      6863548.36      1542330.06      6864389.53
      1542207.66      6864988.51
#Sta/Elev= 30
  4137.9 1757.63  4247.7 1754.89  4264.5 1753.83  4284.8 1753.43  4380.8 1749.81
  4466.0 1745.60  4476.3 1744.62  4513.8 1743.63  4518.9 1742.96  4599.1 1739.98
  4753.5 1736.14  4804.8 1733.46  4996.1 1728.74  4996.3 1728.24  4999.8 1728.24
  5000.1 1728.74  5132.6 1728.95  5275.5 1730.79  5316.3 1732.14  5346.6 1734.38
  5351.7 1733.62  5387.7 1737.70  5397.1 1738.34  5402.2 1736.88  5418.4 1739.40
  5447.6 1740.92  5452.7 1739.83  5548.6 1741.34  5553.7 1740.60  5612.8 1742.16
#Mann=5,-1,0
  4137.9   0.035       0  4264.5    0.07       0  4284.8   0.035       0
  4996.1   0.035       0  5000.1   0.035       0
Bank Sta=4996.1,5000.1
Exp/Cntr=0.3,0.1

Type RM Length L Ch R = 1,2555,333,333,333
BEGIN DESCRIPTION:
Mapping XS ac794720
END DESCRIPTION:
XS GIS Cut Line= 3
      1542397.76      6863498.93      1542236.31      6864363.49
      1542085.76      6864944.91
#Sta/Elev= 30
  4129.5 1757.82  4301.5 1753.20  4446.6 1745.20  4627.0 1737.12  4800.0 1732.31
  4825.4 1732.43  4830.5 1731.61  4878.1 1731.86  4891.5 1730.65  4930.8 1730.74
  4935.9 1729.68  4972.9 1729.36  4988.5 1728.01  4993.6 1728.99  5001.4 1727.25
  5001.7 1726.75  5005.4 1727.25  5008.8 1728.14  5024.0 1728.80  5072.3 1729.20
  5077.4 1728.11  5112.9 1729.64  5118.0 1728.04  5153.5 1729.79  5158.6 1728.35
  5188.9 1729.23  5194.1 1728.47  5310.7 1731.43  5447.5 1733.17  5609.6 1738.27
#Mann=3,-1,0
  4129.5   0.035       0  5001.4   0.035       0  5005.4   0.035       0
Bank Sta=5001.4,5005.4
Exp/Cntr=0.3,0.1

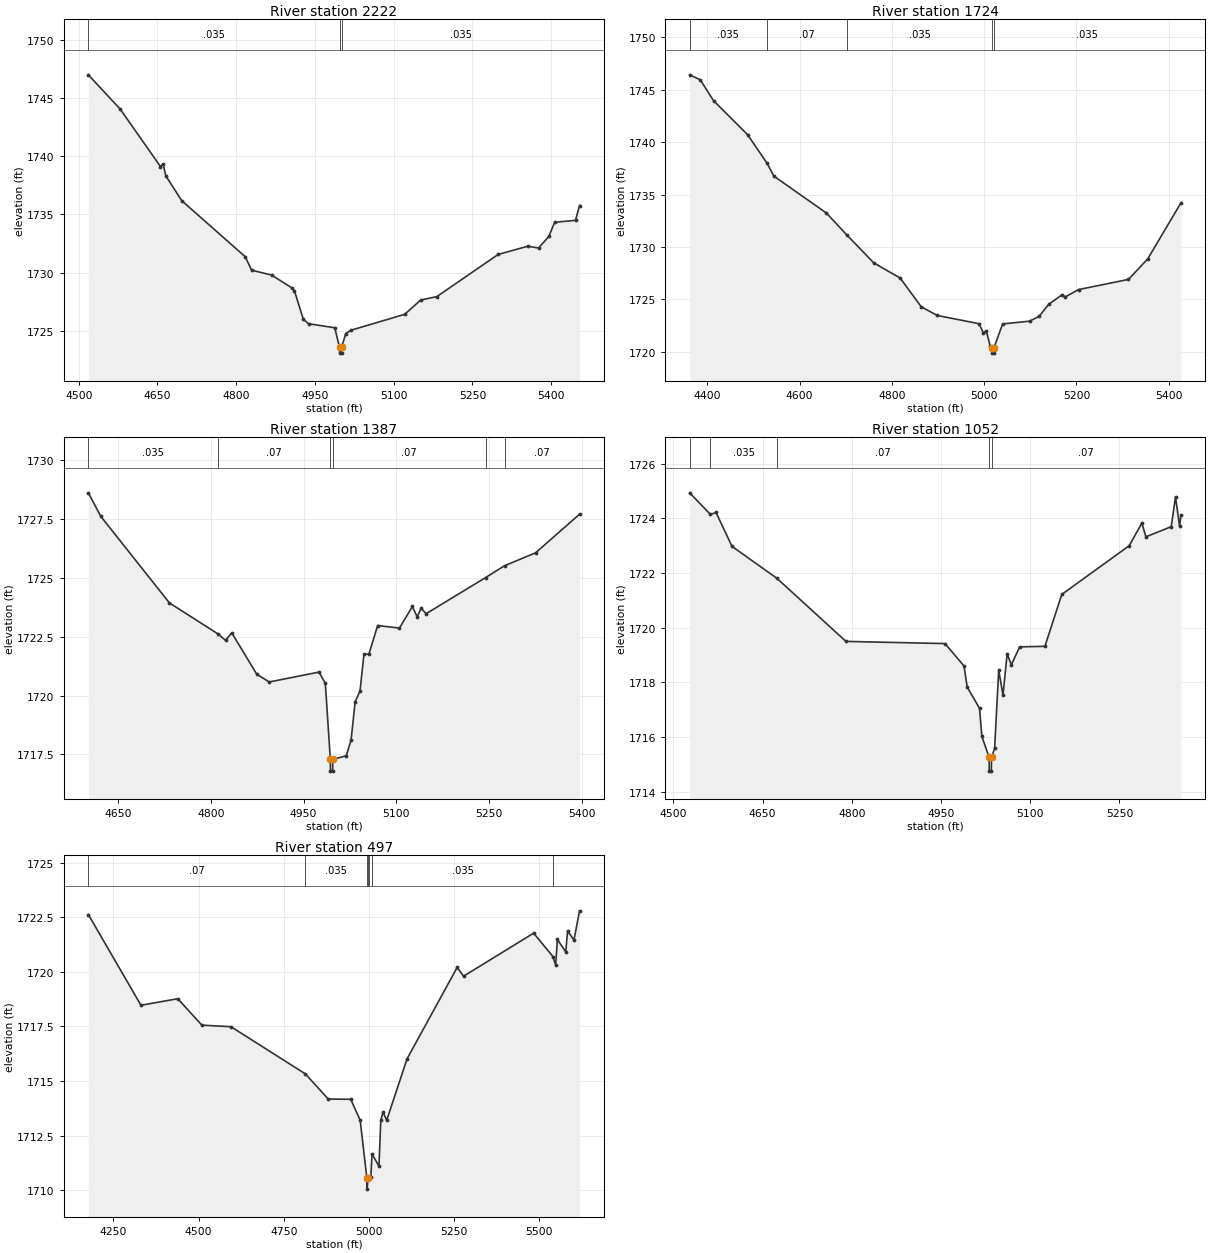
Type RM Length L Ch R = 1,2222,498,498,498
BEGIN DESCRIPTION:
Mapping XS cff454dc
END DESCRIPTION:
XS GIS Cut Line= 3
      1542007.15      6864001.46      1541949.85      6864472.86
      1542040.69      6864924.45
#Sta/Elev= 30
  4518.4 1746.97  4579.0 1744.03  4655.7 1739.10  4660.8 1739.31  4666.0 1738.30
  4696.2 1736.17  4817.1 1731.36  4829.3 1730.20  4867.5 1729.78  4906.0 1728.68
  4911.0 1728.42  4927.9 1725.98  4938.0 1725.60  4987.7 1725.26  4996.8 1723.58
  4997.1 1723.08  5000.6 1723.08  5000.8 1723.58  5008.7 1724.76  5018.9 1725.05
  5120.9 1726.41  5151.5 1727.64  5182.1 1727.93  5298.9 1731.55  5355.5 1732.26
  5375.9 1732.10  5395.5 1733.10  5406.5 1734.31  5446.3 1734.48  5453.9 1735.75
#Mann=3,-1,0
  4518.4   0.035       0  4996.8   0.035       0  5000.8   0.035       0
Bank Sta=4996.8,5000.8
Exp/Cntr=0.3,0.1

Type RM Length L Ch R = 1,1724,337,337,337
BEGIN DESCRIPTION:
BULL WAGON CREEK TRIBUTARY 1 3.0
END DESCRIPTION:
XS GIS Cut Line= 3
      1541855.02      6863987.97      1541548.47      6864547.62
      1541804.98      6864887.98
#Sta/Elev= 30
  4361.9 1746.43  4384.7 1745.96  4413.6 1743.96  4487.4 1740.71  4529.5 1737.99
  4544.5 1736.75  4658.2 1733.23  4702.3 1731.14  4761.0 1728.46  4818.0 1727.02
  4863.6 1724.28  4898.1 1723.45  4989.0 1722.66  4998.4 1721.75  5004.6 1721.97
  5013.0 1720.54  5017.2 1720.35  5017.5 1719.85  5021.0 1719.85  5021.2 1720.35
  5040.0 1722.64  5098.3 1722.90  5119.1 1723.36  5140.0 1724.52  5169.1 1725.43
  5175.8 1725.22  5204.5 1725.92  5312.7 1726.89  5354.4 1728.85  5426.2 1734.19
#Mann=5,-1,0
  4361.9   0.035       0  4529.5    0.07       0  4702.3   0.035       0
  5017.2   0.035       0  5021.2   0.035       0
Bank Sta=5017.2,5021.2
Exp/Cntr=0.3,0.1

Type RM Length L Ch R = 1,1387,335,335,335
BEGIN DESCRIPTION:
BULL WAGON CREEK TRIBUTARY 1 2.0
END DESCRIPTION:
XS GIS Cut Line= 3
      1541304.99      6864288.04      1541255.00      6864688.00
      1541555.01      6864938.01
#Sta/Elev= 30
  4602.3 1728.62  4622.4 1727.62  4733.3 1723.94  4811.9 1722.62  4824.0 1722.35
  4834.0 1722.67  4874.4 1720.91  4894.5 1720.58  4975.1 1721.00  4985.2 1720.52
  4993.3 1717.29  4993.5 1716.79  4997.0 1716.79  4997.3 1717.29  5019.0 1717.44
  5026.8 1718.11  5033.4 1719.74  5041.2 1720.19  5047.7 1721.77  5055.5 1721.76
  5069.8 1722.98  5105.0 1722.87  5125.8 1723.79  5133.6 1723.35  5140.1 1723.72
  5147.9 1723.48  5244.3 1725.02  5274.7 1725.52  5324.9 1726.07  5395.9 1727.71
#Mann=6,-1,0
  4602.3   0.035       0  4811.9    0.07       0  4993.3    0.07       0
  4997.3    0.07       0  5244.3   0.035       0  5274.7    0.07       0
Bank Sta=4993.3,4997.3
Exp/Cntr=0.3,0.1

Type RM Length L Ch R = 1,1052,555,555,555
BEGIN DESCRIPTION:
Mapping XS 175f8d9d
END DESCRIPTION:
XS GIS Cut Line= 3
      1541082.67      6864287.96      1540934.23      6864748.90
      1541180.80      6864985.10
#Sta/Elev= 30
  4527.6 1724.94  4562.4 1724.15  4571.9 1724.22  4598.7 1722.98  4674.2 1721.81
  4790.3 1719.50  4956.8 1719.42  4988.8 1718.60  4994.1 1717.83  5014.8 1717.05
  5018.8 1716.02  5031.0 1715.25  5031.2 1714.75  5034.7 1714.75  5035.0 1715.25
  5040.2 1715.58  5047.1 1718.45  5054.3 1717.53  5061.3 1719.05  5068.3 1718.64
  5082.3 1719.30  5124.8 1719.32  5153.1 1721.22  5266.3 1723.00  5287.7 1723.83
  5294.6 1723.33  5337.1 1723.70  5344.3 1724.79  5351.2 1723.71  5353.3 1724.11
#Mann=5,-1,0
  4527.6    0.07       0  4562.4   0.035       0  4674.2    0.07       0
  5031.0    0.07       0  5035.0    0.07       0
Bank Sta=5031,5035
Exp/Cntr=0.3,0.1

Type RM Length L Ch R = 1,497,0,0,0
BEGIN DESCRIPTION:
BULL WAGON CREEK TRIBUTARY 1 1.0
END DESCRIPTION:
XS GIS Cut Line= 5
      1540921.19      6864427.08      1540500.18      6864980.46
      1540567.08      6865090.14      1540784.47      6865180.11
      1541140.18      6865039.13
#Sta/Elev= 30
  4176.2 1722.62  4330.6 1718.47  4438.7 1718.77  4509.4 1717.56  4594.7 1717.49
  4813.4 1715.33  4880.4 1714.18  4946.4 1714.17  4974.1 1713.21  4993.8 1710.56
  4994.1 1710.06  4997.8 1710.56  4999.9 1710.56  5005.3 1710.62  5009.0 1711.67
  5029.2 1711.11  5034.6 1713.20  5041.0 1713.59  5051.9 1713.21  5111.7 1716.02
  5258.7 1720.20  5277.6 1719.80  5483.3 1721.77  5539.6 1720.70  5547.8 1720.32
  5553.1 1721.48  5577.5 1720.91  5582.9 1721.87  5601.6 1721.45  5617.9 1722.79
#Mann=7,-1,0
  4176.2    0.07       0  4813.4   0.035       0  4993.8    0.07       0
  4997.8   0.035       0  4999.9    0.07       0  5009.0   0.035       0
  5539.6    0.07       0
Bank Sta=4993.8,4997.8
Exp/Cntr=0.3,0.1

Chan Stop Cuts=-1