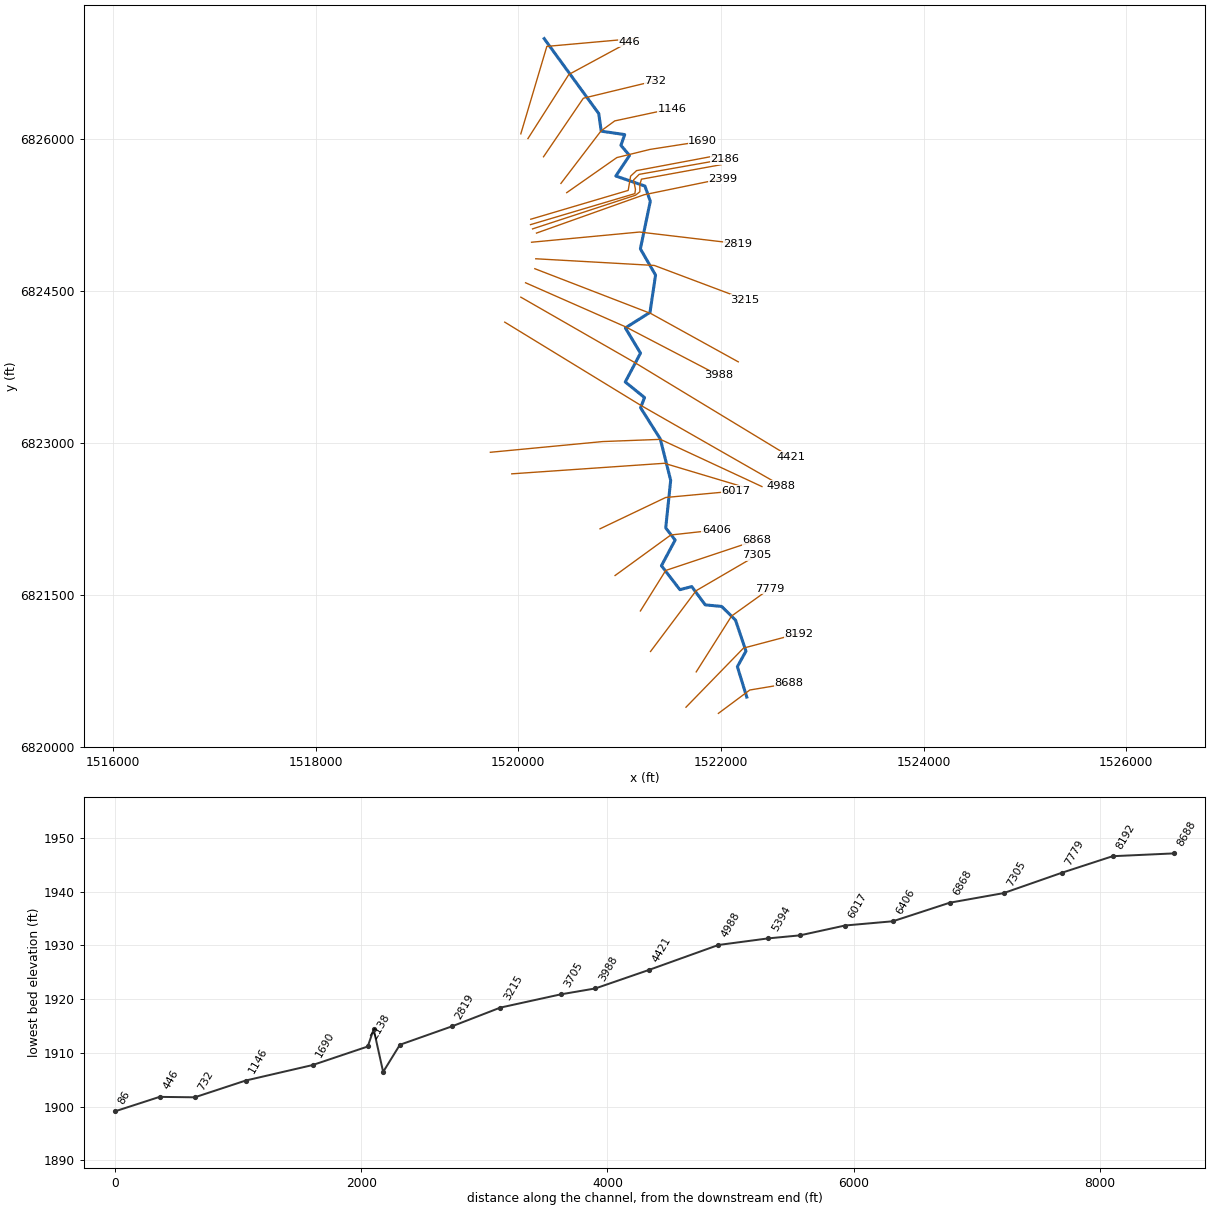
--- BULL WAGON CREEK TRIBUTARY 10.prj (project) ---

Proj Title=BULL WAGON CREEK TRIBUTARY 10 Base Level Engineering
Current Plan=p01
Default Exp/Contr=0.3,0.1
English Units
Geom File=g01
Flow File=f01
Plan File=p01
BEGIN DESCRIPTION:
BULL WAGON CREEK TRIBUTARY 10
END DESCRIPTION:

--- BULL WAGON CREEK TRIBUTARY 10.p01 (plan) ---

Plan Title=Multiple Run
Short Identifier=Multiple
Geom File=g01
Flow File=f01
Subcritical Flow
K Sum by GR= 0
Std Step Tol= 0.01
Critical Tol= 0.01
Num of Std Step Trials= 20
Max Error Tol= 0.3
Flow Tol Ratio= 0.001
Split Flow NTrial= 30
Split Flow Tol= 0.02
Split Flow Ratio= 0.02
Log Output Level= 0
Friction Slope Method= 1
Unsteady Friction Slope Method= 2
Unsteady Bridges Friction Slope Method= 1
Parabolic Critical Depth
Global Vel Dist=  1 , 1 , 1
Global Log Level= 0
CheckData=True
Encroach Param= -1, 0, 0, 0
BEGIN DESCRIPTION:
Multiple Run
END DESCRIPTION:

--- BULL WAGON CREEK TRIBUTARY 10.f01 (steady flow) ---

Flow Title=Multiple
Number of Profiles=7
Profile Names=10-year,25-year,50-year,1pct_min,100-year,1pct_plu,500-year
River Rch & RM= BULL WAGON CREEK,Reach-1,8688
     314     452     571     360     718    1433    1150
River Rch & RM= BULL WAGON CREEK,Reach-1,4421
     460     673     861     548    1094    2182    1789
Boundary for River Rch & Prof#=BULL WAGON CREEK,Reach-1,1
Up Type=0
Dn Type=3
Dn Slope=0.005
Boundary for River Rch & Prof#=BULL WAGON CREEK,Reach-1,2
Up Type=0
Dn Type=3
Dn Slope=0.005
Boundary for River Rch & Prof#=BULL WAGON CREEK,Reach-1,3
Up Type=0
Dn Type=3
Dn Slope=0.005
Boundary for River Rch & Prof#=BULL WAGON CREEK,Reach-1,4
Up Type=0
Dn Type=3
Dn Slope=0.005
Boundary for River Rch & Prof#=BULL WAGON CREEK,Reach-1,5
Up Type=0
Dn Type=3
Dn Slope=0.005
Boundary for River Rch & Prof#=BULL WAGON CREEK,Reach-1,6
Up Type=0
Dn Type=3
Dn Slope=0.005
Boundary for River Rch & Prof#=BULL WAGON CREEK,Reach-1,7
Up Type=0
Dn Type=3
Dn Slope=0.005

--- BULL WAGON CREEK TRIBUTARY 10.g01 (geometry) ---

Geom Title=Existing Conditions

River Reach=BULL WAGON CREEK,Reach-1
Reach XY= 30
      1522255.00      6820488.00      1522162.30      6820787.92
      1522247.23      6820941.41      1522143.77      6821248.00
      1522007.45      6821382.53      1521844.88      6821398.35
      1521711.75      6821578.86      1521595.00      6821548.07
      1521412.61      6821784.67      1521547.89      6822037.99
      1521454.97      6822157.98      1521503.90      6822627.45
      1521401.24      6823036.44      1521206.84      6823344.12
      1521245.86      6823444.75      1521055.53      6823598.47
      1521205.87      6823882.97      1521056.50      6824132.13
      1521299.64      6824285.30      1521354.62      6824653.28
      1521204.85      6824912.87      1521302.84      6825382.03
      1521249.74      6825532.53      1520962.34      6825631.58
      1521097.39      6825834.67      1521012.85      6825934.59
      1521050.00      6826040.58      1520818.52      6826074.27
      1520793.76      6826248.00      1520255.00      6826988.00

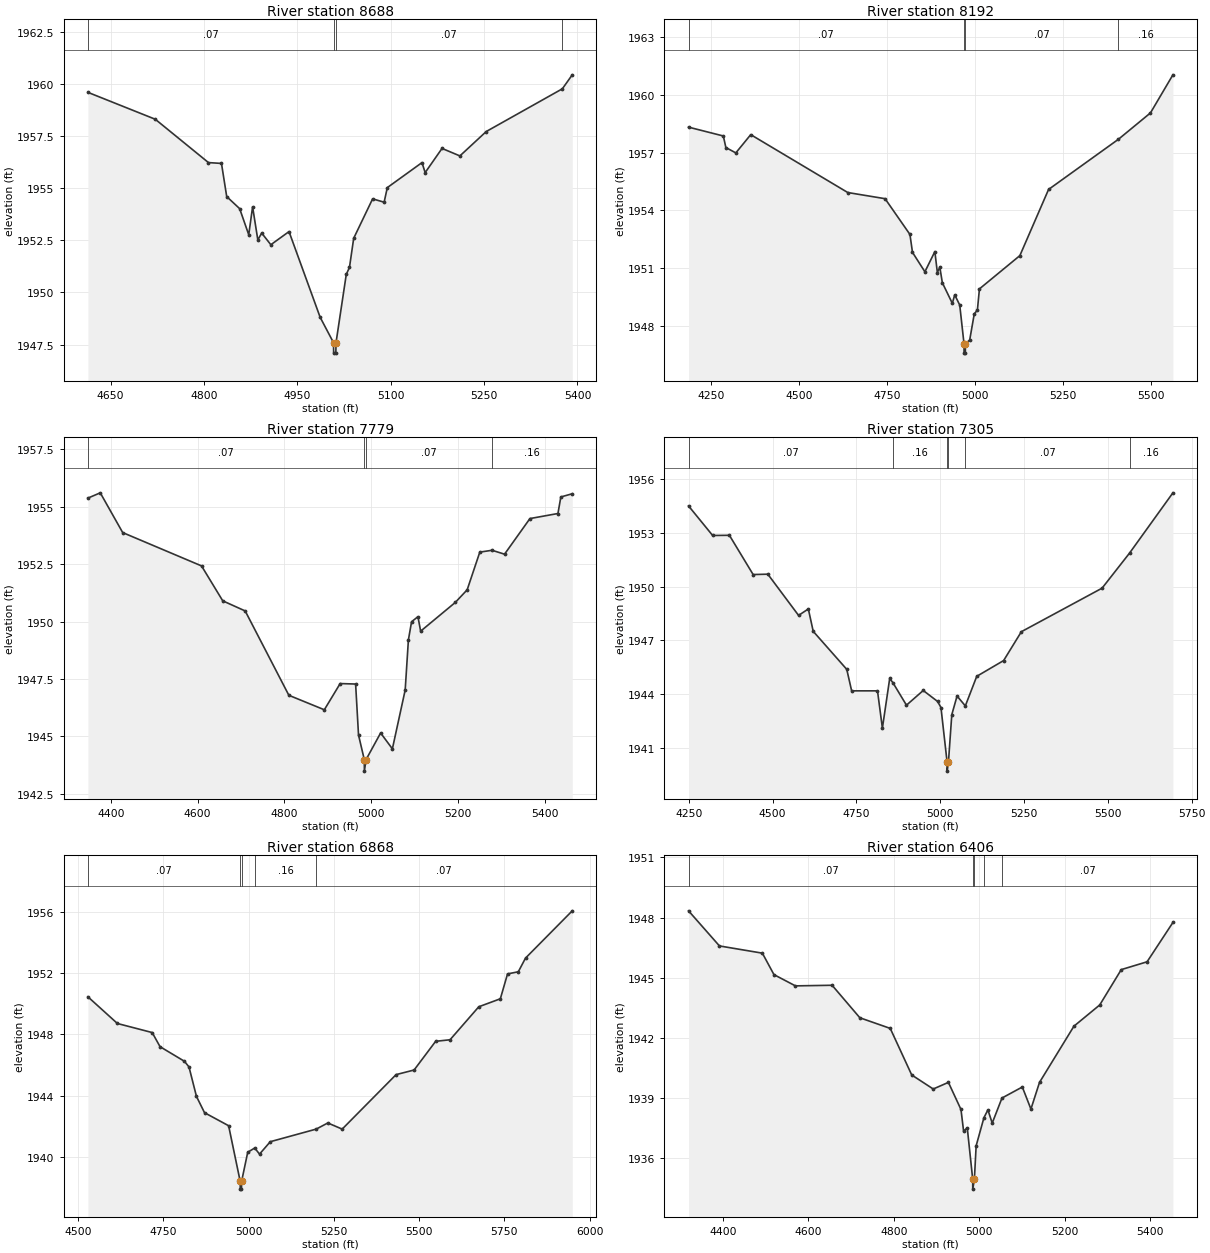
Type RM Length L Ch R = 1,8688,496,496,496
BEGIN DESCRIPTION:
BULL WAGON CREEK TRIBUTARY 10 14.0
END DESCRIPTION:
XS GIS Cut Line= 3
      1521974.94      6820327.09      1522285.06      6820557.75
      1522671.33      6820622.15
#Sta/Elev= 30
  4613.5 1959.60  4721.7 1958.31  4807.2 1956.23  4828.1 1956.19  4836.5 1954.60
  4857.3 1954.02  4871.9 1952.77  4878.1 1954.11  4886.5 1952.52  4892.7 1952.85
  4907.4 1952.29  4936.6 1952.92  4986.6 1948.81  5008.1 1947.59  5008.3 1947.09
  5011.8 1947.09  5012.1 1947.59  5028.6 1950.87  5033.7 1951.20  5040.5 1952.60
  5070.9 1954.49  5089.4 1954.33  5094.5 1955.03  5150.2 1956.23  5155.3 1955.75
  5182.4 1956.91  5211.1 1956.55  5253.4 1957.72  5375.7 1959.77  5391.6 1960.44
#Mann=4,-1,0
  4613.5    0.07       0  5008.1    0.07       0  5012.1    0.07       0
  5375.7    0.16       0
Bank Sta=5008.1,5012.1
Exp/Cntr=0.3,0.1

Type RM Length L Ch R = 1,8192,413,413,413
BEGIN DESCRIPTION:
BULL WAGON CREEK TRIBUTARY 10 13.0
END DESCRIPTION:
XS GIS Cut Line= 3
      1521654.99      6820387.99      1522222.55      6820971.35
      1522766.64      6821115.28
#Sta/Elev= 30
  4186.1 1958.32  4285.0 1957.86  4292.2 1957.26  4320.5 1956.98  4362.9 1957.93
  4638.7 1954.92  4744.7 1954.60  4815.4 1952.74  4822.6 1951.81  4857.9 1950.80
  4886.2 1951.85  4893.3 1950.76  4900.3 1951.04  4907.5 1950.23  4935.8 1949.16
  4942.7 1949.60  4956.9 1949.07  4969.0 1947.07  4969.3 1946.57  4972.8 1946.57
  4973.0 1947.07  4985.2 1947.25  4998.2 1948.61  5007.1 1948.81  5012.9 1949.91
  5127.8 1951.64  5209.4 1955.08  5408.0 1957.69  5499.0 1959.06  5562.8 1961.04
#Mann=4,-1,0
  4186.1    0.07       0  4969.0    0.07       0  4973.0    0.07       0
  5408.0    0.16       0
Bank Sta=4969,4973
Exp/Cntr=0.3,0.1

Type RM Length L Ch R = 1,7779,474,474,474
BEGIN DESCRIPTION:
BULL WAGON CREEK TRIBUTARY 10 12.0
END DESCRIPTION:
XS GIS Cut Line= 3
      1521756.16      6820736.77      1522105.00      6821288.00
      1522481.84      6821557.96
#Sta/Elev= 30
  4347.3 1955.37  4375.8 1955.60  4427.5 1953.87  4609.1 1952.42  4658.0 1950.90
  4709.7 1950.46  4810.3 1946.79  4892.0 1946.16  4928.5 1947.30  4964.1 1947.28
  4970.8 1945.06  4984.1 1943.99  4984.3 1943.49  4988.1 1943.99  5021.7 1945.15
  5048.8 1944.46  5078.3 1947.02  5085.7 1949.20  5093.0 1949.99  5107.7 1950.21
  5113.9 1949.58  5193.7 1950.83  5221.1 1951.38  5250.2 1953.02  5278.4 1953.10
  5307.2 1952.93  5365.7 1954.48  5430.2 1954.70  5436.9 1955.42  5463.2 1955.56
#Mann=4,-1,0
  4347.3    0.07       0  4984.1    0.07       0  4988.1    0.07       0
  5278.4    0.16       0
Bank Sta=4984.1,4988.1
Exp/Cntr=0.3,0.1

Type RM Length L Ch R = 1,7305,437,437,437
BEGIN DESCRIPTION:
BULL WAGON CREEK TRIBUTARY 10 11.0
END DESCRIPTION:
XS GIS Cut Line= 3
      1521304.98      6820937.98      1521755.00      6821538.00
      1522355.04      6821888.02
#Sta/Elev= 30
  4249.4 1954.50  4321.3 1952.85  4371.3 1952.86  4442.1 1950.67  4485.9 1950.69
  4577.6 1948.39  4606.7 1948.75  4621.3 1947.50  4721.3 1945.38  4735.9 1944.18
  4813.0 1944.18  4827.6 1942.10  4849.4 1944.87  4858.8 1944.64  4899.4 1943.38
  4949.4 1944.20  4992.1 1943.59  5002.3 1943.25  5020.6 1940.20  5020.8 1939.70
  5024.6 1940.20  5034.6 1942.85  5050.3 1943.89  5075.0 1943.34  5109.0 1944.99
  5189.2 1945.87  5242.1 1947.48  5482.8 1949.91  5564.9 1951.87  5694.1 1955.23
#Mann=6,-1,0
  4249.4    0.07       0  4858.8    0.16       0  5020.6    0.07       0
  5024.6    0.16       0  5075.0    0.07       0  5564.9    0.16       0
Bank Sta=5020.6,5024.6
Exp/Cntr=0.3,0.1

Type RM Length L Ch R = 1,6868,462,462,462
BEGIN DESCRIPTION:
BULL WAGON CREEK TRIBUTARY 10 10.0
END DESCRIPTION:
XS GIS Cut Line= 3
      1521205.02      6821338.03      1521455.00      6821738.00
      1522355.05      6822038.02
#Sta/Elev= 30
  4528.7 1950.45  4615.3 1948.71  4717.3 1948.12  4740.3 1947.20  4811.7 1946.25
  4825.2 1945.88  4847.1 1943.96  4870.7 1942.90  4941.4 1942.05  4975.4 1938.42
  4975.6 1937.92  4979.1 1937.92  4979.4 1938.42  4997.4 1940.32  5018.0 1940.60
  5032.0 1940.20  5063.6 1941.01  5198.2 1941.83  5232.3 1942.23  5274.4 1941.83
  5432.5 1945.38  5485.3 1945.68  5548.5 1947.55  5590.7 1947.65  5675.0 1949.80
  5738.2 1950.32  5759.3 1951.94  5790.9 1952.08  5812.0 1952.97  5949.1 1956.05
#Mann=5,-1,0
  4528.7    0.07       0  4975.4    0.07       0  4979.4    0.07       0
  5018.0    0.16       0  5198.2    0.07       0
Bank Sta=4975.4,4979.4
Exp/Cntr=0.3,0.1

Type RM Length L Ch R = 1,6406,389,389,389
BEGIN DESCRIPTION:
BULL WAGON CREEK TRIBUTARY 10 9.0
END DESCRIPTION:
XS GIS Cut Line= 3
      1520954.99      6821687.99      1521505.00      6822088.00
      1521955.05      6822138.01
#Sta/Elev= 30
  4319.8 1948.34  4392.1 1946.59  4492.5 1946.23  4519.6 1945.16  4569.8 1944.60
  4655.6 1944.63  4720.5 1943.01  4791.6 1942.48  4841.8 1940.16  4892.1 1939.46
  4927.6 1939.79  4957.0 1938.44  4963.2 1937.35  4971.7 1937.53  4984.4 1934.97
  4984.6 1934.47  4988.4 1934.97  4992.5 1936.63  5010.7 1938.03  5020.0 1938.42
  5030.1 1937.76  5052.9 1939.01  5100.5 1939.56  5120.6 1938.46  5140.7 1939.79
  5221.2 1942.59  5281.6 1943.65  5331.9 1945.41  5392.3 1945.80  5452.7 1947.76
#Mann=5,-1,0
  4319.8    0.07       0  4984.4    0.07       0  4988.4    0.07       0
  5010.7    0.16       0  5052.9    0.07       0
Bank Sta=4984.4,4988.4
Exp/Cntr=0.3,0.1

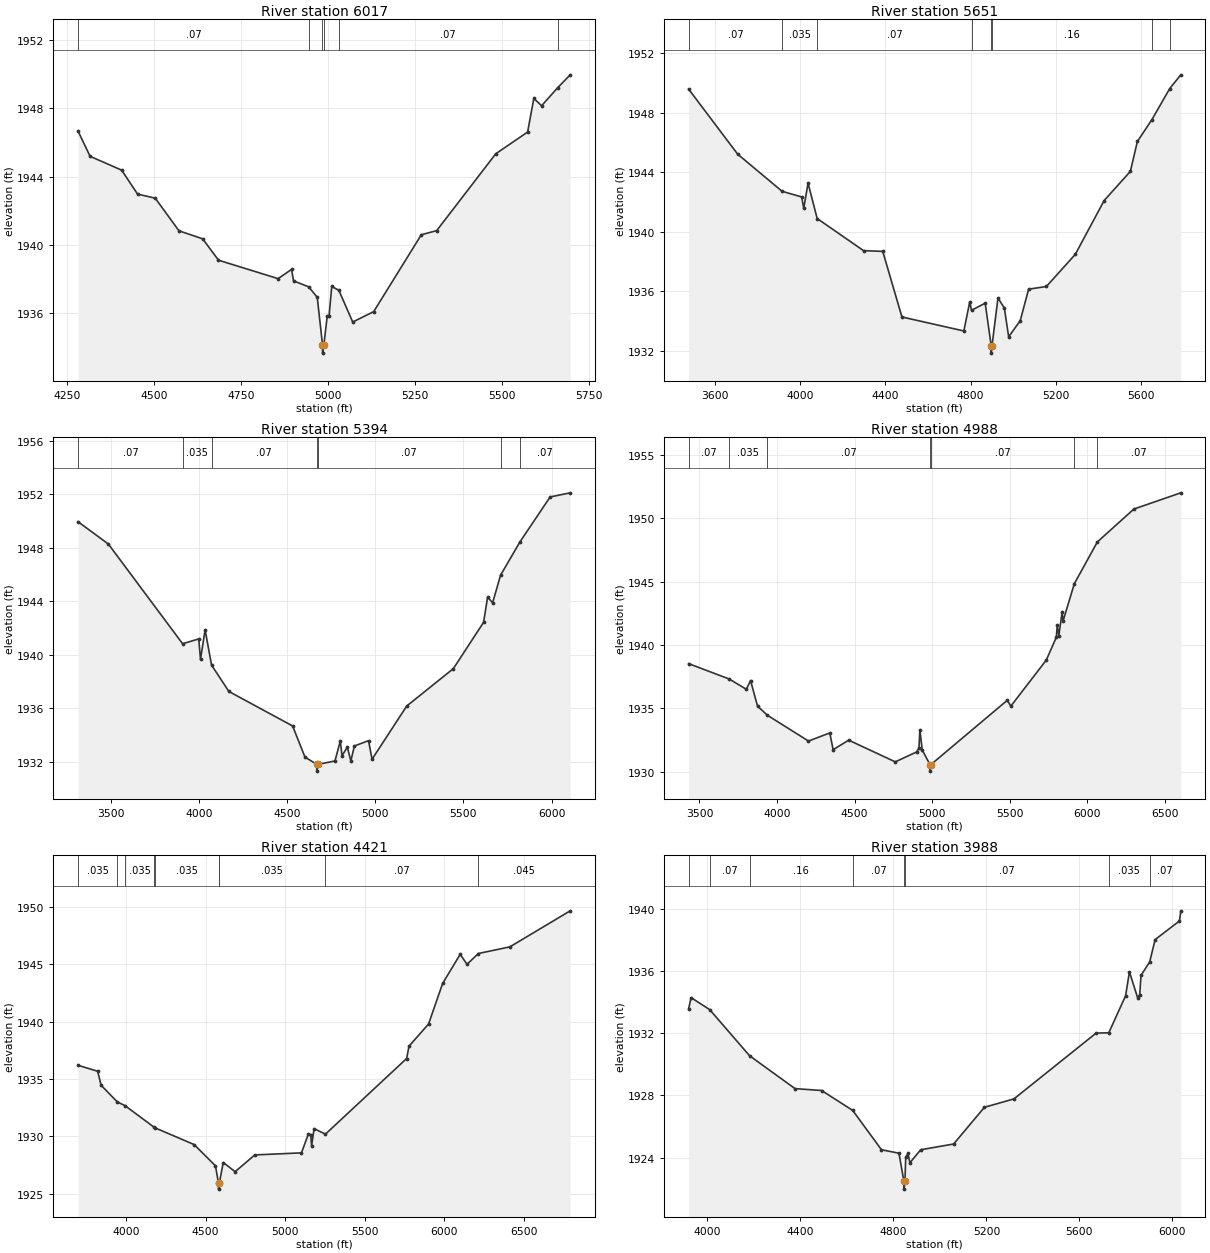
Type RM Length L Ch R = 1,6017,366,366,366
BEGIN DESCRIPTION:
BULL WAGON CREEK TRIBUTARY 10 8.0
END DESCRIPTION:
XS GIS Cut Line= 3
      1520806.54      6822149.13      1521454.64      6822458.15
      1522146.77      6822522.39
#Sta/Elev= 30
  4282.0 1946.68  4316.6 1945.20  4407.4 1944.39  4452.8 1942.99  4503.7 1942.75
  4571.8 1940.84  4639.9 1940.37  4685.3 1939.12  4856.4 1938.04  4895.1 1938.58
  4900.7 1937.91  4944.2 1937.56  4968.8 1936.95  4983.9 1934.18  4984.2 1933.68
  4987.9 1934.18  4997.4 1935.83  5002.7 1935.83  5010.4 1937.58  5030.8 1937.36
  5070.7 1935.50  5130.9 1936.11  5267.7 1940.61  5311.7 1940.85  5481.4 1945.35
  5572.8 1946.62  5590.7 1948.59  5613.0 1948.16  5659.3 1949.22  5695.1 1949.97
#Mann=6,-1,0
  4282.0    0.07       0  4944.2    0.16       0  4983.9    0.07       0
  4987.9    0.16       0  5030.8    0.07       0  5659.3    0.16       0
Bank Sta=4983.9,4987.9
Exp/Cntr=0.3,0.1

Type RM Length L Ch R = 1,5651,257,257,257
BEGIN DESCRIPTION:
Mapping XS 9c21826a
END DESCRIPTION:
XS GIS Cut Line= 3
      1519935.45      6822691.73      1521441.51      6822795.90
      1522209.75      6822565.86
#Sta/Elev= 30
  3475.9 1949.60  3706.0 1945.23  3914.7 1942.73  4006.7 1942.35  4016.7 1941.59
  4036.8 1943.28  4079.6 1940.90  4297.4 1938.74  4387.6 1938.69  4477.8 1934.28
  4768.5 1933.34  4796.1 1935.29  4804.6 1934.73  4868.8 1935.21  4896.8 1932.35
  4897.1 1931.85  4900.8 1932.35  4928.9 1935.56  4959.0 1934.87  4979.0 1932.95
  5033.3 1934.03  5072.7 1936.15  5156.2 1936.33  5291.9 1938.49  5427.6 1942.11
  5550.6 1944.07  5583.6 1946.08  5651.9 1947.55  5735.6 1949.64  5787.5 1950.56
#Mann=8,-1,0
  3475.9    0.07       0  3914.7   0.035       0  4079.6    0.07       0
  4804.6    0.16       0  4896.8    0.07       0  4900.8    0.16       0
  5651.9    0.16       0  5735.6    0.07       0
Bank Sta=4896.8,4900.8
Exp/Cntr=0.3,0.1

Type RM Length L Ch R = 1,5394,406,406,406
BEGIN DESCRIPTION:
Mapping XS f7a285df
END DESCRIPTION:
XS GIS Cut Line= 4
      1519723.92      6822904.40      1520832.44      6823010.31
      1521402.75      6823032.07      1522405.04      6822565.87
#Sta/Elev= 30
  3315.7 1949.95  3487.6 1948.28  3908.5 1940.82  3999.9 1941.18  4009.9 1939.66
  4036.0 1941.86  4072.6 1939.22  4170.7 1937.25  4531.9 1934.67  4602.0 1932.34
  4670.0 1931.79  4670.3 1931.29  4674.0 1931.79  4772.1 1932.05  4802.1 1933.54
  4812.1 1932.45  4842.1 1933.08  4862.1 1932.06  4882.2 1933.17  4962.2 1933.57
  4982.2 1932.18  5178.9 1936.16  5443.2 1938.96  5614.4 1942.42  5637.3 1944.31
  5665.7 1943.88  5710.7 1945.95  5821.5 1948.46  5991.6 1951.80  6105.4 1952.11
#Mann=7,-1,0
  3315.7    0.07       0  3908.5   0.035       0  4072.6    0.07       0
  4670.0    0.07       0  4674.0    0.07       0  5710.7    0.16       0
  5821.5    0.07       0
Bank Sta=4670,4674
Exp/Cntr=0.3,0.1

Type RM Length L Ch R = 1,4988,567,567,567
BEGIN DESCRIPTION:
Mapping XS b3f3f685
END DESCRIPTION:
XS GIS Cut Line= 3
      1519866.02      6824189.11      1521207.13      6823368.82
      1522595.98      6822574.57
#Sta/Elev= 30
  3430.4 1938.53  3691.7 1937.32  3802.3 1936.51  3829.5 1937.20  3874.6 1935.18
  3938.4 1934.46  4202.9 1932.43  4340.3 1933.07  4361.6 1931.75  4462.2 1932.50
  4762.1 1930.79  4899.5 1931.57  4914.9 1931.87  4920.8 1933.31  4936.2 1931.72
  4986.3 1930.56  4986.5 1930.06  4990.3 1930.56  5483.9 1935.64  5506.9 1935.18
  5735.5 1938.81  5800.2 1940.61  5806.4 1941.58  5816.1 1940.73  5837.7 1942.60
  5843.4 1941.88  5916.2 1944.83  6064.6 1948.12  6299.7 1950.71  6602.4 1951.99
#Mann=7,-1,0
  3430.4    0.07       0  3691.7   0.035       0  3938.4    0.07       0
  4986.3    0.07       0  4990.3    0.07       0  5916.2    0.16       0
  6064.6    0.07       0
Bank Sta=4986.3,4990.3
Exp/Cntr=0.3,0.1

Type RM Length L Ch R = 1,4421,433,433,433
BEGIN DESCRIPTION:
Mapping XS ba8bd061
END DESCRIPTION:
XS GIS Cut Line= 3
      1520024.86      6824435.65      1521149.84      6823789.82
      1522686.33      6822857.51
#Sta/Elev= 30
  3697.7 1936.19  3821.2 1935.67  3842.8 1934.45  3945.2 1932.99  3992.5 1932.68
  4177.3 1930.78  4180.2 1930.75  4428.1 1929.28  4561.8 1927.43  4581.1 1925.90
  4581.4 1925.40  4585.6 1925.90  4610.7 1927.72  4685.5 1926.92  4809.2 1928.38
  5102.4 1928.56  5145.1 1930.17  5160.5 1930.16  5166.4 1929.18  5181.9 1930.67
  5253.1 1930.19  5763.5 1936.78  5778.9 1937.86  5901.6 1939.79  5990.2 1943.33
  6100.4 1945.86  6143.4 1944.99  6214.8 1945.93  6412.8 1946.51  6792.1 1949.65
#Mann=9,-1,0
  3697.7   0.035       0  3945.2    0.07       0  3992.5   0.035       0
  4177.3    0.07       0  4180.2   0.035       0  4581.1   0.035       0
  4585.6   0.035       0  5253.1    0.07       0  6214.8   0.045       0
Bank Sta=4581.1,4585.6
Exp/Cntr=0.3,0.1

Type RM Length L Ch R = 1,3988,283,283,283
BEGIN DESCRIPTION:
Mapping XS d7ca76e0
END DESCRIPTION:
XS GIS Cut Line= 3
      1520071.47      6824577.82      1521056.76      6824143.77
      1521979.70      6823662.80
#Sta/Elev= 30
  3918.9 1933.57  3929.5 1934.29  4009.5 1933.52  4181.4 1930.55  4376.8 1928.44
  4491.0 1928.32  4624.8 1927.04  4748.6 1924.51  4823.8 1924.29  4845.1 1922.48
  4845.4 1921.98  4849.6 1922.48  4852.8 1924.02  4862.5 1924.28  4870.7 1923.67
  4917.1 1924.51  5058.9 1924.88  5191.4 1927.24  5318.4 1927.78  5671.9 1932.01
  5726.5 1932.03  5798.8 1934.41  5815.3 1935.95  5850.6 1934.28  5859.5 1934.48
  5865.1 1935.72  5902.5 1936.59  5925.8 1938.02  6030.6 1939.22  6036.3 1939.87
#Mann=8,-1,0
  3918.9   0.035       0  4009.5    0.07       0  4181.4    0.16       0
  4624.8    0.07       0  4845.1    0.07       0  4849.6    0.07       0
  5726.5   0.035       0  5902.5    0.07       0
Bank Sta=4845.1,4849.6
Exp/Cntr=0.3,0.1

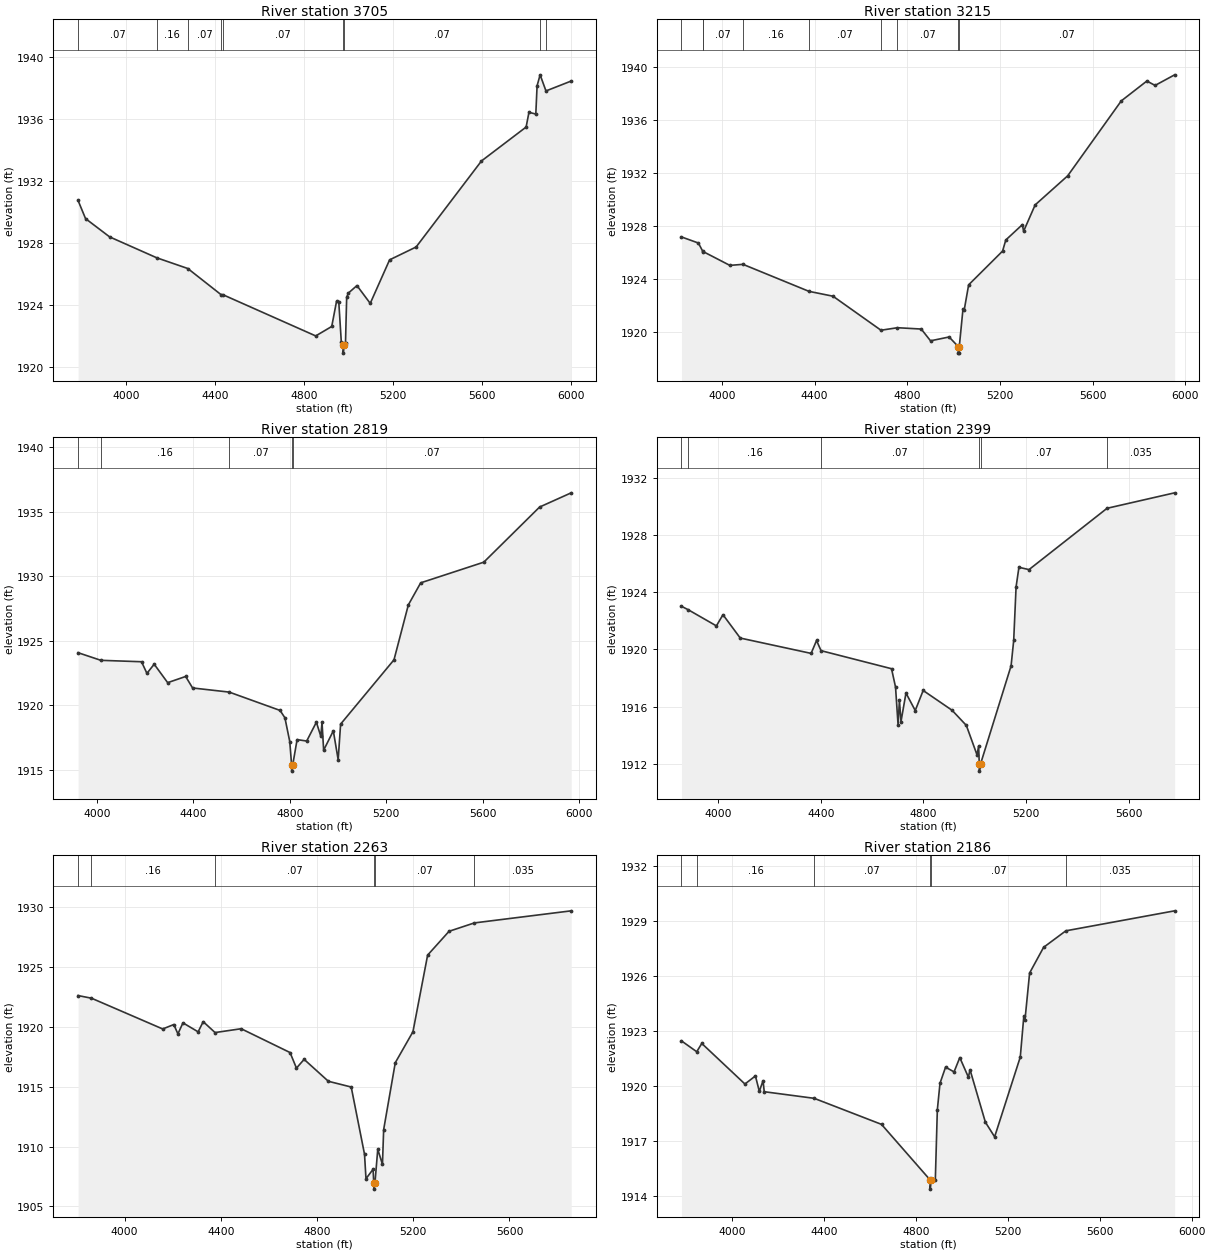
Type RM Length L Ch R = 1,3705,490,490,490
BEGIN DESCRIPTION:
Mapping XS 6423ca40
END DESCRIPTION:
XS GIS Cut Line= 3
      1520162.69      6824716.68      1521308.49      6824273.98
      1522171.13      6823797.15
#Sta/Elev= 30
  3785.6 1930.72  3819.2 1929.55  3927.4 1928.37  4139.2 1927.02  4278.3 1926.33
  4426.9 1924.65  4435.9 1924.64  4852.5 1921.98  4924.4 1922.59  4945.9 1924.21
  4956.2 1924.14  4967.3 1921.60  4975.8 1921.37  4976.1 1920.87  4980.3 1921.37
  4986.2 1921.54  4991.5 1924.48  4999.5 1924.75  5037.6 1925.23  5097.2 1924.08
  5184.2 1926.89  5303.3 1927.72  5596.6 1933.27  5797.1 1935.46  5809.8 1936.41
  5840.6 1936.30  5846.3 1938.12  5859.9 1938.83  5886.2 1937.79  5999.6 1938.43
#Mann=9,-1,0
  3785.6    0.07       0  4139.2    0.16       0  4278.3    0.07       0
  4426.9    0.16       0  4435.9    0.07       0  4975.8    0.07       0
  4980.3    0.07       0  5859.9   0.035       0  5886.2   0.045       0
Bank Sta=4975.8,4980.3
Exp/Cntr=0.3,0.1

Type RM Length L Ch R = 1,3215,396,396,396
BEGIN DESCRIPTION:
Mapping XS fb7c2c31
END DESCRIPTION:
XS GIS Cut Line= 3
      1520172.19      6824814.78      1521342.35      6824748.81
      1522236.81      6824412.52
#Sta/Elev= 30
  3825.9 1927.19  3898.8 1926.73  3918.2 1926.09  3920.9 1926.07  4034.6 1925.04
  4091.2 1925.12  4375.7 1923.08  4479.7 1922.71  4686.6 1920.14  4757.6 1920.33
  4860.3 1920.23  4900.4 1919.34  4980.5 1919.63  5019.7 1918.91  5020.1 1918.41
  5024.2 1918.41  5024.5 1918.91  5040.5 1921.76  5045.8 1921.68  5064.8 1923.57
  5211.2 1926.12  5225.1 1926.96  5296.6 1928.12  5301.9 1927.62  5351.7 1929.61
  5492.2 1931.81  5723.3 1937.47  5833.6 1938.97  5869.2 1938.64  5953.5 1939.44
#Mann=9,-1,0
  3825.9    0.07       0  3918.2    0.16       0  3920.9    0.07       0
  4091.2    0.16       0  4375.7    0.07       0  4686.6   0.035       0
  4757.6    0.07       0  5019.7    0.07       0  5024.5    0.07       0
Bank Sta=5019.7,5024.5
Exp/Cntr=0.3,0.1

Type RM Length L Ch R = 1,2819,420,420,420
BEGIN DESCRIPTION:
Mapping XS 4a9bb588
END DESCRIPTION:
XS GIS Cut Line= 3
      1520130.57      6824977.98      1521196.52      6825078.67
      1522165.27      6824964.08
#Sta/Elev= 30
  3921.1 1924.07  4015.7 1923.48  4184.4 1923.37  4206.8 1922.47  4236.9 1923.18
  4292.9 1921.75  4367.5 1922.23  4396.2 1921.34  4548.1 1921.02  4759.2 1919.60
  4779.3 1919.03  4799.4 1917.19  4807.0 1915.40  4807.4 1914.90  4811.9 1915.40
  4829.9 1917.34  4869.7 1917.23  4909.9 1918.69  4928.3 1917.59  4933.3 1918.69
  4940.0 1916.52  4980.2 1918.02  5000.3 1915.78  5010.4 1918.54  5231.9 1923.52
  5291.4 1927.77  5342.7 1929.48  5604.5 1931.08  5836.1 1935.35  5967.3 1936.45
#Mann=5,-1,0
  3921.1    0.07       0  4015.7    0.16       0  4548.1    0.07       0
  4807.0    0.07       0  4811.9    0.07       0
Bank Sta=4807,4811.9
Exp/Cntr=0.3,0.1

Type RM Length L Ch R = 1,2399,136,136,136
BEGIN DESCRIPTION:
Mapping XS 70e7d1e5
END DESCRIPTION:
XS GIS Cut Line= 3
      1520179.14      6825068.24      1521241.65      6825446.72
      1522019.41      6825606.44
#Sta/Elev= 30
  3857.2 1923.01  3884.2 1922.76  3993.3 1921.64  4018.9 1922.42  4086.3 1920.79
  4362.4 1919.72  4383.6 1920.62  4401.1 1919.91  4675.8 1918.65  4691.4 1917.37
  4701.3 1914.73  4706.6 1916.45  4712.7 1914.96  4732.1 1916.95  4768.2 1915.73
  4799.1 1917.13  4911.7 1915.75  4967.4 1914.69  5008.9 1912.64  5015.2 1913.24
  5017.8 1912.00  5018.2 1911.50  5022.7 1912.00  5141.7 1918.85  5151.9 1920.62
  5161.2 1924.36  5172.3 1925.73  5211.6 1925.57  5515.7 1929.85  5779.1 1930.93
#Mann=6,-1,0
  3857.2    0.07       0  3884.2    0.16       0  4401.1    0.07       0
  5017.8    0.07       0  5022.7    0.07       0  5515.7   0.035       0
Bank Sta=5017.8,5022.7
Exp/Cntr=0.3,0.1

Type RM Length L Ch R = 1,2263,77,77,77
BEGIN DESCRIPTION:
Mapping XS 25b02bd9
END DESCRIPTION:
XS GIS Cut Line= 6
      1520140.50      6825109.69      1521156.15      6825441.73
      1521199.55      6825476.45      1521199.55      6825543.73
      1521214.74      6825600.15      1522002.49      6825743.38
#Sta/Elev= 30
  3806.4 1922.62  3862.2 1922.40  4158.3 1919.83  4204.4 1920.20  4221.5 1919.42
  4242.5 1920.34  4305.6 1919.59  4326.7 1920.44  4376.0 1919.53  4484.5 1919.85
  4687.8 1917.86  4714.4 1916.56  4746.3 1917.29  4847.1 1915.46  4942.1 1914.98
  4997.4 1909.37  5003.5 1907.32  5033.1 1908.11  5035.8 1906.95  5036.1 1906.45
  5040.7 1906.95  5052.5 1909.78  5072.0 1908.52  5077.0 1911.42  5125.3 1917.01
  5198.8 1919.60  5259.8 1926.00  5348.9 1927.99  5454.2 1928.69  5856.9 1929.70
#Mann=6,-1,0
  3806.4    0.07       0  3862.2    0.16       0  4376.0    0.07       0
  5035.8    0.07       0  5040.7    0.07       0  5454.2   0.035       0
Bank Sta=5035.8,5040.7
Exp/Cntr=0.3,0.1

Type RM Length L Ch R = 1,2186,48,48,48
BEGIN DESCRIPTION:
Mapping XS e572e7a2
END DESCRIPTION:
XS GIS Cut Line= 6
      1520120.15      6825151.59      1521150.73      6825458.01
      1521156.15      6825500.33      1521137.49      6825592.56
      1521193.04      6825648.11      1522036.84      6825797.43
#Sta/Elev= 30
  3778.5 1922.47  3844.9 1921.88  3867.0 1922.33  4054.8 1920.12  4100.5 1920.56
  4117.4 1919.72  4133.7 1920.30  4138.9 1919.70  4356.2 1919.34  4649.5 1917.92
  4861.3 1914.89  4861.6 1914.39  4866.2 1914.89  4883.9 1914.91  4892.6 1918.71
  4904.2 1920.16  4928.5 1921.04  4965.4 1920.78  4990.4 1921.56  5027.9 1920.49
  5034.9 1920.90  5101.8 1918.04  5142.1 1917.24  5253.8 1921.59  5269.1 1923.80
  5274.2 1923.61  5294.4 1926.17  5355.3 1927.57  5452.2 1928.47  5925.9 1929.56
#Mann=6,-1,0
  3778.5    0.07       0  3844.9    0.16       0  4356.2    0.07       0
  4861.3    0.07       0  4866.2    0.07       0  5452.2   0.035       0
Bank Sta=4861.3,4866.2
Exp/Cntr=0.3,0.1

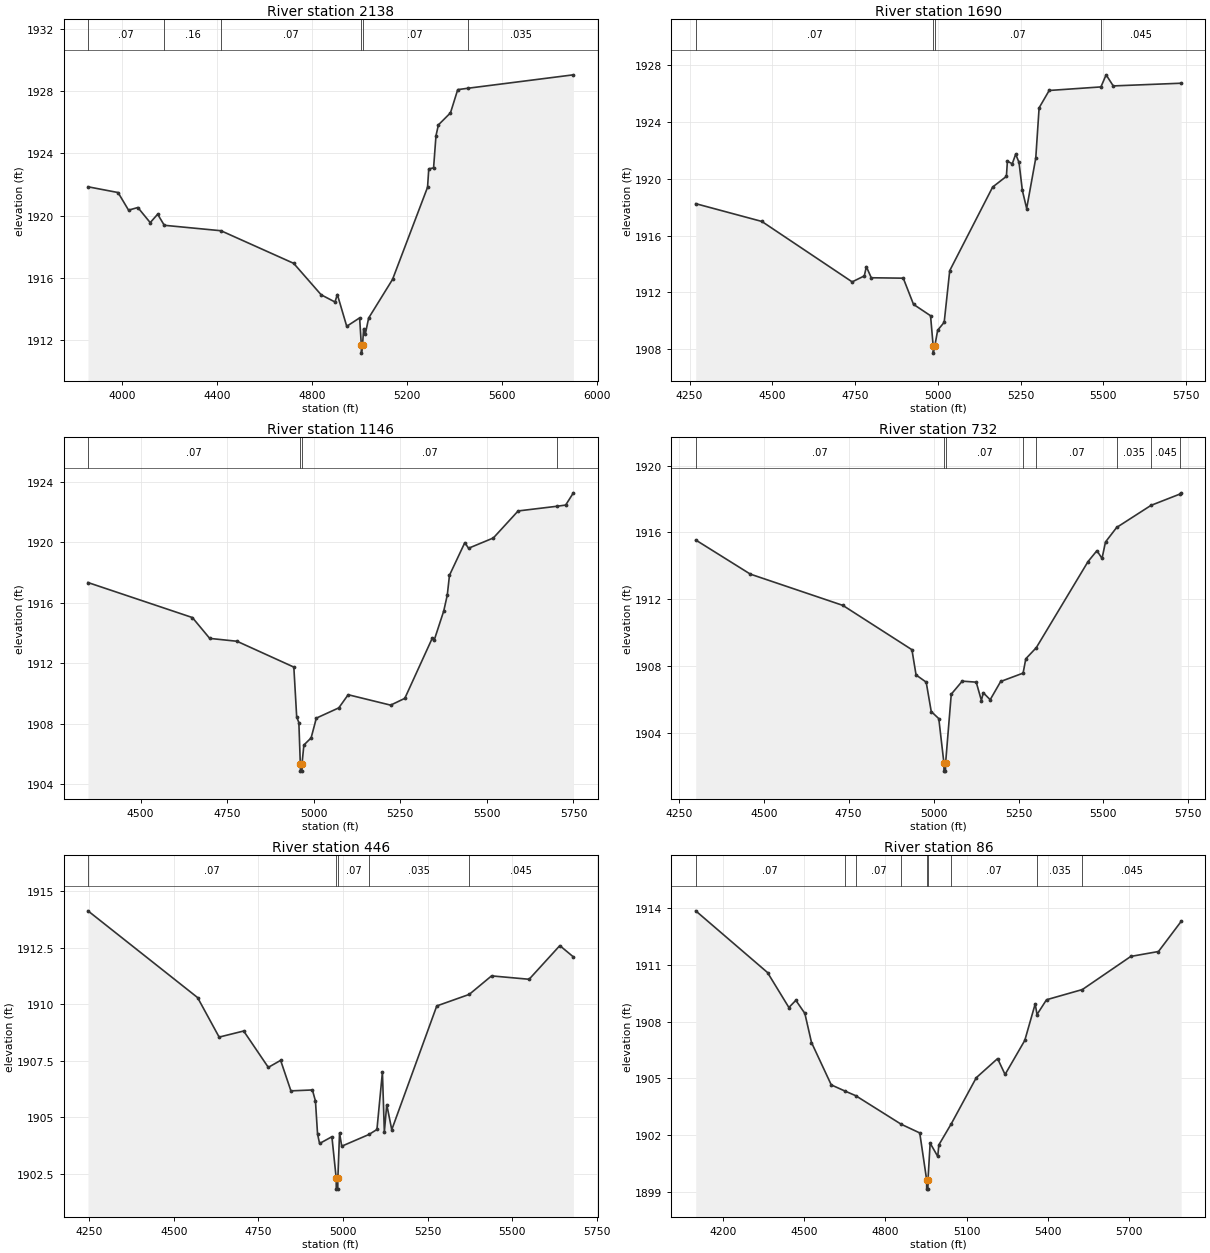
Type RM Length L Ch R = 1,2138,448,448,448
BEGIN DESCRIPTION:
Mapping XS 8424b51b
END DESCRIPTION:
XS GIS Cut Line= 5
      1520123.19      6825205.19      1521084.54      6825489.48
      1521108.41      6825630.53      1521167.00      6825684.79
      1521974.31      6825836.70
#Sta/Elev= 30
  3854.8 1921.85  3981.8 1921.48  4026.1 1920.35  4065.3 1920.52  4117.4 1919.55
  4148.7 1920.09  4176.7 1919.38  4415.7 1919.03  4722.2 1916.94  4838.3 1914.92
  4896.4 1914.46  4906.5 1914.94  4946.0 1912.90  5000.4 1913.44  5007.6 1911.68
  5008.0 1911.18  5012.5 1911.68  5017.4 1912.75  5024.3 1912.40  5038.4 1913.43
  5139.2 1915.91  5286.8 1921.82  5291.9 1923.00  5312.2 1923.06  5322.4 1925.13
  5332.6 1925.82  5383.4 1926.59  5414.0 1928.08  5457.3 1928.17  5901.7 1929.03
#Mann=6,-1,0
  3854.8    0.07       0  4176.7    0.16       0  4415.7    0.07       0
  5007.6    0.07       0  5012.5    0.07       0  5457.3   0.035       0
Bank Sta=5007.6,5012.5
Exp/Cntr=0.3,0.1

Type RM Length L Ch R = 1,1690,544,544,544
BEGIN DESCRIPTION:
Mapping XS dc405138
END DESCRIPTION:
XS GIS Cut Line= 4
      1520477.79      6825467.36      1520972.56      6825813.69
      1521300.68      6825894.42      1521818.89      6825975.15
#Sta/Elev= 30
  4268.7 1918.24  4468.5 1916.99  4741.3 1912.74  4778.0 1913.16  4784.2 1913.81
  4799.0 1913.03  4895.7 1913.00  4926.6 1911.16  4978.1 1910.36  4986.0 1908.23
  4986.3 1907.73  4990.9 1908.23  4999.6 1909.34  5019.3 1909.90  5036.0 1913.53
  5165.7 1919.41  5207.2 1920.16  5210.2 1921.22  5225.0 1921.05  5235.2 1921.72
  5245.3 1921.14  5255.4 1919.17  5268.4 1917.90  5295.9 1921.45  5306.0 1924.98
  5336.4 1926.20  5492.7 1926.45  5508.4 1927.30  5529.9 1926.52  5735.0 1926.71
#Mann=4,-1,0
  4268.7    0.07       0  4986.0    0.07       0  4990.9    0.07       0
  5492.7   0.045       0
Bank Sta=4986,4990.9
Exp/Cntr=0.3,0.1

Type RM Length L Ch R = 1,1146,414,414,414
BEGIN DESCRIPTION:
Mapping XS 45014d06
END DESCRIPTION:
XS GIS Cut Line= 4
      1520420.49      6825558.51      1520816.31      6826076.71
      1520951.72      6826175.67      1521521.06      6826297.86
#Sta/Elev= 30
  4347.7 1917.34  4649.4 1915.02  4699.4 1913.64  4778.2 1913.45  4942.4 1911.74
  4950.6 1908.45  4956.9 1908.06  4961.1 1905.35  4961.5 1904.85  4965.8 1904.85
  4966.1 1905.35  4971.4 1906.58  4992.3 1907.05  5007.4 1908.36  5072.3 1909.04
  5099.3 1909.91  5222.0 1909.22  5262.9 1909.67  5342.5 1913.67  5347.6 1913.51
  5375.4 1915.46  5385.6 1916.51  5391.9 1917.82  5436.2 1919.98  5447.0 1919.61
  5518.6 1920.29  5590.2 1922.08  5702.2 1922.39  5727.5 1922.47  5749.8 1923.28
#Mann=4,-1,0
  4347.7    0.07       0  4961.1    0.07       0  4966.1    0.07       0
  5702.2   0.045       0
Bank Sta=4961.1,4966.1
Exp/Cntr=0.3,0.1

Type RM Length L Ch R = 1,732,286,286,286
BEGIN DESCRIPTION:
Mapping XS 40908e89
END DESCRIPTION:
XS GIS Cut Line= 3
      1520248.61      6825821.52      1520641.83      6826399.63
      1521351.42      6826571.18
#Sta/Elev= 30
  4299.6 1915.55  4460.4 1913.51  4732.8 1911.64  4936.2 1908.99  4948.4 1907.48
  4978.2 1907.05  4993.1 1905.29  5015.3 1904.87  5030.3 1902.23  5030.7 1901.73
  5035.0 1901.73  5035.4 1902.23  5052.0 1906.33  5084.3 1907.11  5125.5 1907.05
  5140.8 1905.95  5146.1 1906.42  5166.6 1906.00  5197.5 1907.09  5263.5 1907.59
  5271.5 1908.45  5302.3 1909.11  5454.7 1914.26  5480.8 1914.91  5495.9 1914.45
  5506.1 1915.43  5539.0 1916.30  5640.1 1917.62  5725.7 1918.30  5728.8 1918.37
#Mann=8,-1,0
  4299.6    0.07       0  5030.3    0.07       0  5035.4    0.07       0
  5263.5   0.035       0  5302.3    0.07       0  5539.0   0.035       0
  5640.1   0.045       0  5725.7   0.035       0
Bank Sta=5030.3,5035.4
Exp/Cntr=0.3,0.1

Type RM Length L Ch R = 1,446,360,360,360
BEGIN DESCRIPTION:
Mapping XS 417f210a
END DESCRIPTION:
XS GIS Cut Line= 3
      1520094.94      6826001.18      1520498.60      6826634.01
      1521100.08      6826959.48
#Sta/Elev= 30
  4246.5 1914.13  4570.5 1910.29  4634.2 1908.54  4706.7 1908.81  4779.5 1907.20
  4815.9 1907.51  4846.3 1906.16  4909.8 1906.20  4918.8 1905.71  4925.0 1904.25
  4931.0 1903.83  4967.4 1904.13  4980.0 1902.31  4980.4 1901.81  4984.7 1901.81
  4985.1 1902.31  4990.0 1904.30  4996.5 1903.71  5077.0 1904.23  5100.5 1904.45
  5116.7 1906.99  5122.4 1904.34  5129.5 1905.55  5144.3 1904.44  5277.3 1909.92
  5373.2 1910.43  5439.2 1911.25  5550.2 1911.10  5640.9 1912.59  5681.0 1912.09
#Mann=5,-1,0
  4246.5    0.07       0  4980.0    0.07       0  4985.1    0.07       0
  5077.0   0.035       0  5373.2   0.045       0
Bank Sta=4980,4985.1
Exp/Cntr=0.3,0.1

Type RM Length L Ch R = 1,86,0,0,0
BEGIN DESCRIPTION:
BULL WAGON CREEK TRIBUTARY 10 1.0
END DESCRIPTION:
XS GIS Cut Line= 3
      1520024.64      6826048.07      1520281.35      6826911.20
      1521170.20      6826990.75
#Sta/Elev= 30
  4099.5 1913.85  4364.7 1910.59  4443.7 1908.74  4469.4 1909.12  4502.6 1908.43
  4527.2 1906.89  4600.2 1904.65  4649.9 1904.33  4690.4 1904.08  4858.4 1902.57
  4927.0 1902.11  4952.4 1899.64  4952.7 1899.14  4957.1 1899.14  4957.5 1899.64
  4965.4 1901.57  4993.4 1900.87  4997.6 1901.48  5043.7 1902.60  5135.8 1905.03
  5214.5 1906.04  5242.1 1905.20  5314.9 1907.00  5353.4 1908.93  5360.1 1908.37
  5395.2 1909.15  5527.7 1909.69  5706.5 1911.44  5808.7 1911.70  5892.4 1913.29
#Mann=9,-1,0
  4099.5    0.07       0  4649.9   0.035       0  4690.4    0.07       0
  4858.4   0.035       0  4952.4   0.035       0  4957.5   0.035       0
  5043.7    0.07       0  5360.1   0.035       0  5527.7   0.045       0
Bank Sta=4952.4,4957.5
Exp/Cntr=0.3,0.1

Chan Stop Cuts=-1