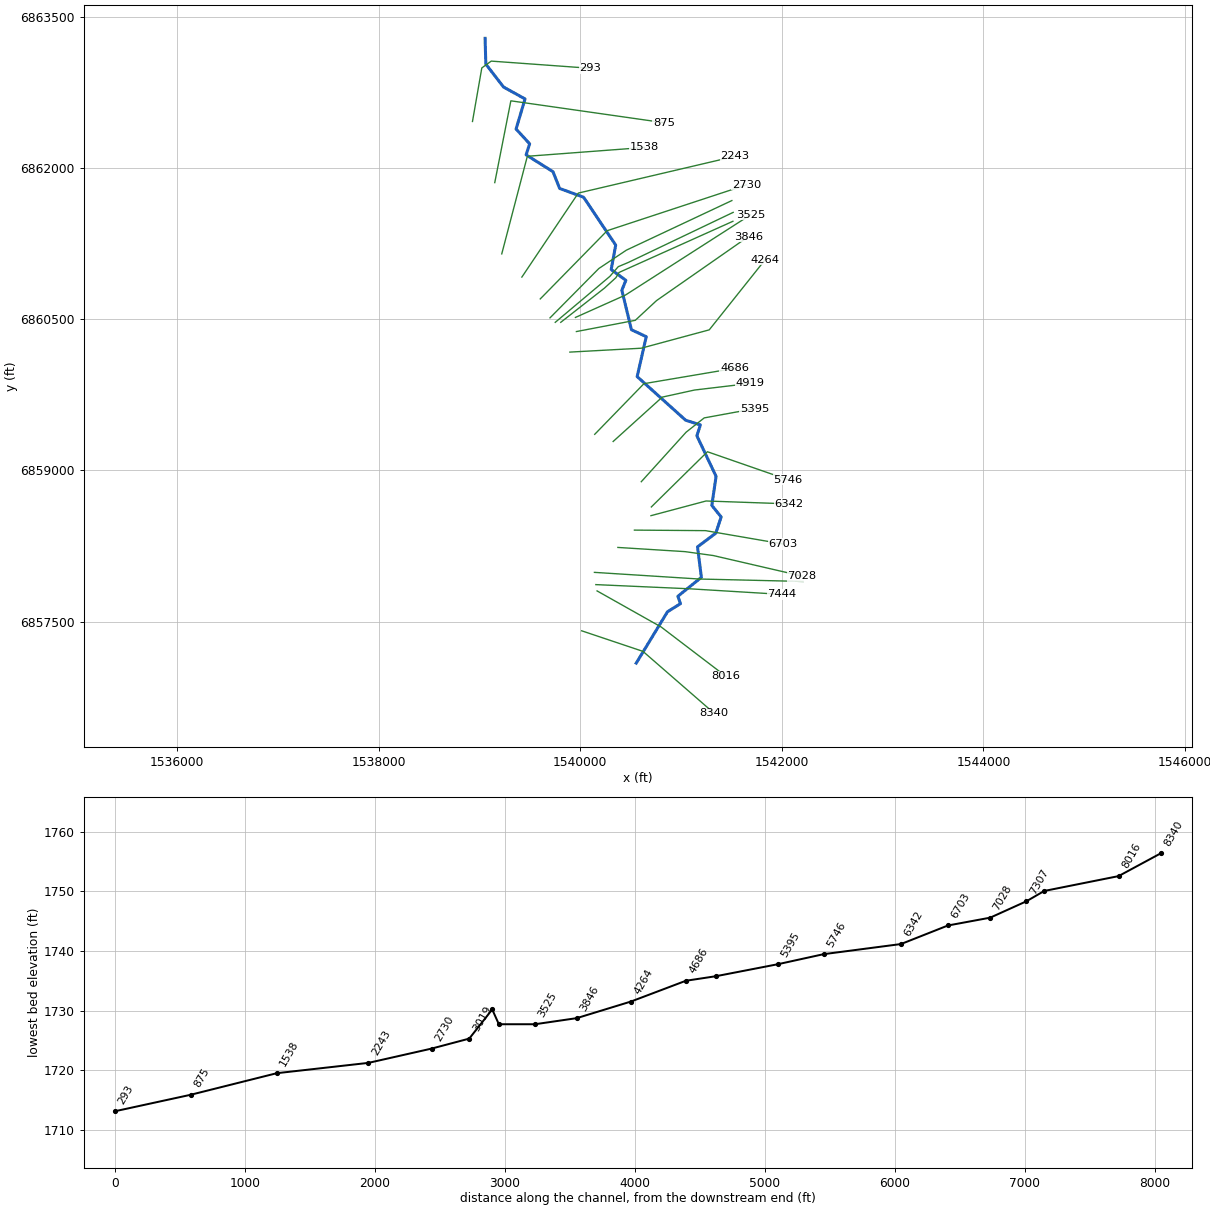
--- BULL WAGON CREEK TRIBUTARY 2.prj (project) ---

Proj Title=BULL WAGON CREEK TRIBUTARY 2 Base Level Engineering
Current Plan=p01
Default Exp/Contr=0.3,0.1
English Units
Geom File=g01
Flow File=f01
Plan File=p01
Y Axis Title=Elevation
X Axis Title(PF)=Main Channel Distance
X Axis Title(XS)=Station
BEGIN DESCRIPTION:
BULL WAGON CREEK TRIBUTARY 2
END DESCRIPTION:
DSS Export Rating Curves= 0
DSS Export Rating Curve Sorted= 0
DSS Export Volume Flow Curves= 0
DXF OffsetX= 0
DXF OffsetY= 0
DXF ScaleX= 1
DXF ScaleY= 10

--- BULL WAGON CREEK TRIBUTARY 2.p01 (plan) ---

Plan Title=Multiple Run
Short Identifier=Multiple
Geom File=g01
Flow File=f01
Subcritical Flow
K Sum by GR= 0
Std Step Tol= 0.01
Critical Tol= 0.01
Num of Std Step Trials= 20
Max Error Tol= 0.3
Flow Tol Ratio= 0.001
Split Flow NTrial= 30
Split Flow Tol= 0.02
Split Flow Ratio= 0.02
Log Output Level= 0
Friction Slope Method= 1
Unsteady Friction Slope Method= 2
Unsteady Bridges Friction Slope Method= 1
Parabolic Critical Depth
Global Vel Dist=  1 , 1 , 1
Global Log Level= 0
CheckData=True
Encroach Param= -1, 0, 0, 0
BEGIN DESCRIPTION:
Multiple Run
END DESCRIPTION:

--- BULL WAGON CREEK TRIBUTARY 2.f01 (steady flow) ---

Flow Title=Multiple
Program Version=4.10
Number of Profiles= 7
Profile Names=10-year,25-year,50-year,1pct_min,100-year,1pct_plu,500-year
River Rch & RM=BULL WAGON CREEK,Reach-1         ,8340
     103     135     160      95     190     378     269
River Rch & RM=BULL WAGON CREEK,Reach-1         ,6342
     145     194     234     140     280     559     407
River Rch & RM=BULL WAGON CREEK,Reach-1         ,4264
     293     409     505     311     620    1237     945
Boundary for River Rch & Prof#=BULL WAGON CREEK,Reach-1         , 1
Up Type= 0
Dn Type= 3
Dn Slope=0.005
Boundary for River Rch & Prof#=BULL WAGON CREEK,Reach-1         , 2
Up Type= 0
Dn Type= 3
Dn Slope=0.005
Boundary for River Rch & Prof#=BULL WAGON CREEK,Reach-1         , 3
Up Type= 0
Dn Type= 3
Dn Slope=0.005
Boundary for River Rch & Prof#=BULL WAGON CREEK,Reach-1         , 4
Up Type= 0
Dn Type= 3
Dn Slope=0.005
Boundary for River Rch & Prof#=BULL WAGON CREEK,Reach-1         , 5
Up Type= 0
Dn Type= 3
Dn Slope=0.005
Boundary for River Rch & Prof#=BULL WAGON CREEK,Reach-1         , 6
Up Type= 0
Dn Type= 3
Dn Slope=0.005
Boundary for River Rch & Prof#=BULL WAGON CREEK,Reach-1         , 7
Up Type= 0
Dn Type= 3
Dn Slope=0.005
DSS Import GetInterval= 0
DSS Import GetPeak= 0
DSS Import FillOption= 0

--- BULL WAGON CREEK TRIBUTARY 2.g01 (geometry) ---

Geom Title=Existing Conditions
Program Version=4.10

River Reach=BULL WAGON CREEK,Reach-1
Reach XY= 30
        1540555.        6857088.      1540865.39       6857598.1
      1540993.88      6857677.69      1540968.51      6857751.68
      1541201.47      6857939.47      1541162.98      6858241.35
      1541344.62       6858377.9      1541397.67       6858538.1
      1541305.26      6858653.22      1541347.17       6858941.4
      1541156.67      6859344.05      1541191.63      6859451.79
       1541045.2      6859498.51       1540564.1      6859931.25
      1540654.47      6860327.55      1540507.54      6860396.17
      1540412.26      6860787.91      1540451.93      6860886.57
      1540306.54      6860993.85      1540351.26      6861236.44
      1540032.15      6861711.58      1539794.83      6861798.33
      1539728.84      6861964.93      1539462.38      6862131.67
      1539497.18      6862241.41      1539362.54        6862388.
      1539451.63      6862686.72      1539238.29      6862804.63
      1539062.52      6863031.96        1539055.        6863288.

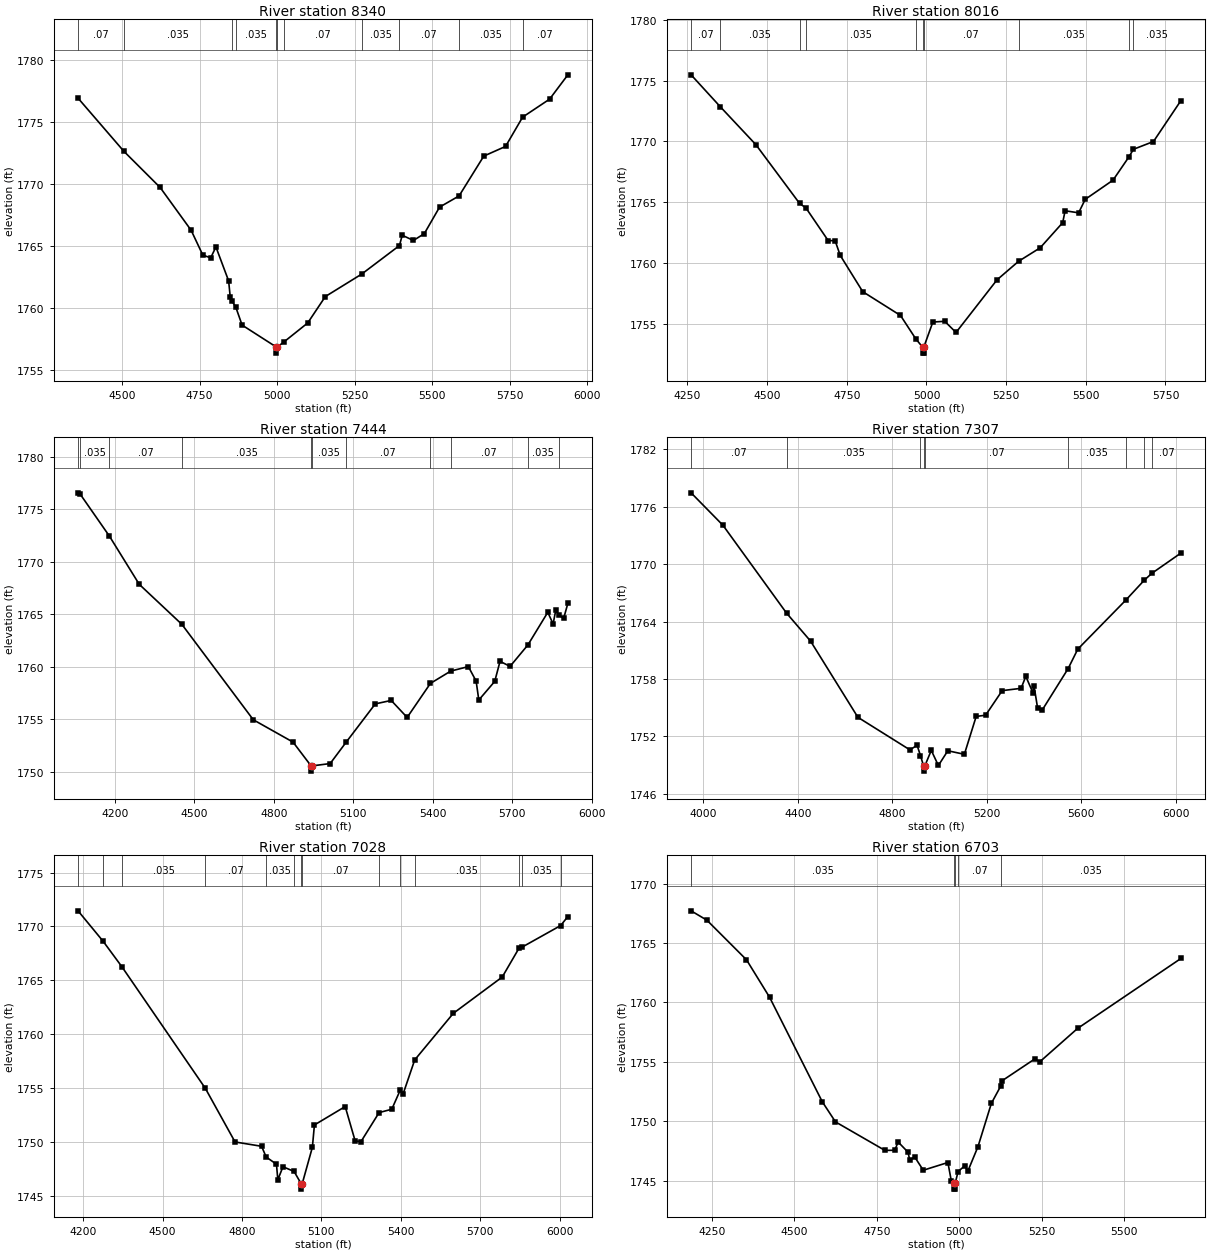
Type RM Length L Ch R = 1 ,8340    ,324,324,324
BEGIN DESCRIPTION:
BULL WAGON CREEK TRIBUTARY 2 15.0
END DESCRIPTION:
XS GIS Cut Line= 3
      1540013.47      6857408.78      1540622.01      6857204.53
      1541329.44      6856589.34
#Sta/Elev= 30
  4358.1 1776.93  4505.8 1772.65  4622.9 1769.73  4722.8 1766.28  4760.5 1764.28
  4785.9 1764.06  4802.7 1764.94  4843.7  1762.2  4848.9 1760.89  4854.4 1760.58
  4866.7 1760.09  4887.1 1758.64  4996.9 1756.88  4997.2 1756.38  5000.9 1756.88
  5023.4 1757.31  5098.6 1758.81  5155.5 1760.94  5272.7 1762.75  5394.5 1765.05
  5403.4 1765.88  5439.5 1765.46  5474.6 1766.01  5523.9 1768.15  5586.7 1769.05
  5666.4 1772.26  5736.6 1773.04  5791.6  1775.4  5878.6 1776.85  5937.5 1778.81
#Mann= 11 ,-1 , 0
  4358.1     .07       0  4505.8    .035       0  4854.4     .07       0
  4866.7    .035       0  4996.9    .035       0  5000.9    .035       0
  5023.4     .07       0  5272.7    .035       0  5394.5     .07       0
  5586.7    .035       0  5791.6     .07       0
Bank Sta=4996.9,5000.9
XS Rating Curve= 0 ,0
Exp/Cntr=0.3,0.1

Type RM Length L Ch R = 1 ,8016    ,572,572,572
BEGIN DESCRIPTION:
Mapping XS 778ce7b4
END DESCRIPTION:
XS GIS Cut Line= 3
      1540166.25      6857804.61      1540801.68      6857446.96
      1541444.02       6856957.4
#Sta/Elev= 30
  4261.6 1775.48  4352.6 1772.87  4464.9 1769.73  4602.1 1764.89    4622 1764.52
  4691.8 1761.83  4713.4 1761.83  4729.4 1760.62  4800.1 1757.63  4918.6 1755.67
  4966.9 1753.73  4987.8 1753.07  4988.1 1752.57  4991.6 1752.57  4991.8 1753.07
  5020.1 1755.13  5057.4 1755.19  5092.8 1754.27  5221.3  1758.6  5289.1 1760.13
  5356.8 1761.24  5427.5 1763.31    5435 1764.29  5477.4 1764.12  5498.2 1765.23
  5585.4 1766.81  5634.4 1768.69  5649.4 1769.35  5712.3 1769.99  5798.4 1773.36
#Mann= 10 ,-1 , 0
  4261.6     .07       0  4352.6    .035       0  4602.1     .07       0
    4622    .035       0  4966.9     .07       0  4987.8     .07       0
  4991.8     .07       0  5289.1    .035       0  5634.4     .07       0
  5649.4    .035       0
Bank Sta=4987.8,4991.8
XS Rating Curve= 0 ,0
Exp/Cntr=0.3,0.1

Type RM Length L Ch R = 1 ,7444    ,137,137,137
BEGIN DESCRIPTION:
Mapping XS d8122f94
END DESCRIPTION:
XS GIS Cut Line= 3
      1540154.14       6857867.1      1541088.14      6857825.44
      1542000.63      6857769.92
#Sta/Elev= 30
  4060.6 1776.57    4068 1776.47    4179 1772.45  4291.7 1767.86  4452.6 1764.05
  4722.1 1754.97  4872.3 1752.84  4940.3 1750.58  4940.6 1750.08  4944.3 1750.58
  5012.4  1750.8    5072 1752.81  5182.7 1756.48  5242.8 1756.81    5303 1755.19
  5390.8 1758.43  5467.3  1759.6    5534 1760.03  5563.4 1758.65  5573.5 1756.85
  5633.6 1758.62  5653.6 1760.53  5691.5 1760.05  5758.8 1762.09  5833.9  1765.2
    5854 1764.09    5864  1765.4  5874.8 1764.94    5894 1764.64  5909.7 1766.05
#Mann= 11 ,-1 , 0
  4060.6     .07       0    4068    .035       0    4179     .07       0
  4452.6    .035       0  4940.3    .035       0  4944.3    .035       0
    5072     .07       0  5390.8    .035       0  5467.3     .07       0
  5758.8    .035       0  5874.8     .07       0
Bank Sta=4940.3,4944.3
XS Rating Curve= 0 ,0
Exp/Cntr=0.3,0.1

Type RM Length L Ch R = 1 ,7307    ,279,279,279
BEGIN DESCRIPTION:
Mapping XS eab8ae7e
END DESCRIPTION:
XS GIS Cut Line= 3
       1540140.2      6857988.63      1541178.42      6857922.66
      1542211.52      6857898.39
#Sta/Elev= 30
  3948.5 1777.46  4083.6 1774.06  4352.6 1764.88  4454.3 1761.95  4654.7 1753.98
  4875.2 1750.57  4905.2 1751.06  4919.5 1749.98  4933.3 1748.85  4933.5 1748.35
  4937.3 1748.85  4965.3 1750.52  4995.4 1748.94  5035.4 1750.48  5105.4 1750.11
  5155.4 1754.07  5195.4  1754.2  5265.5 1756.77  5345.5 1757.01  5365.5 1758.26
  5395.3 1756.57  5400.3 1757.26  5415.5 1754.94  5435.5 1754.76  5544.6 1759.07
  5585.6 1761.11  5788.2 1766.22  5866.3  1768.3  5898.5 1769.03  6022.2 1771.16
#Mann= 9 ,-1 , 0
  3948.5     .07       0  4352.6    .035       0  4919.5     .07       0
  4933.3     .07       0  4937.3     .07       0  5544.6    .035       0
  5788.2     .07       0  5866.3    .035       0  5898.5     .07       0
Bank Sta=4933.3,4937.3
XS Rating Curve= 0 ,0
Exp/Cntr=0.3,0.1

Type RM Length L Ch R = 1 ,7028    ,325,325,325
BEGIN DESCRIPTION:
Mapping XS f540464e
END DESCRIPTION:
XS GIS Cut Line= 4
       1540372.9      6858236.02      1541039.53      6858194.36
      1541320.78       6858155.3      1542196.64      6857952.58
#Sta/Elev= 30
  4180.6 1771.45  4275.8 1768.61  4346.2 1766.26  4661.7 1754.96  4773.9 1749.98
  4874.2 1749.58  4891.3 1748.59  4930.4 1747.91  4935.5 1746.47    4955 1747.68
    4997 1747.24  5023.7  1746.1  5023.9  1745.6  5027.7  1746.1  5066.1 1749.49
  5073.8 1751.56  5190.1 1753.27  5227.7 1750.08  5249.7 1750.01  5318.2 1752.71
  5366.1 1753.02  5398.7 1754.83  5408.8 1754.43  5452.7  1757.6  5598.7 1761.93
  5783.5  1765.3  5847.6 1768.01  5857.9 1768.07  6004.1 1770.08  6031.5 1770.92
#Mann= 14 ,-1 , 0
  4180.6    .035       0  4275.8     .07       0  4346.2    .035       0
  4661.7     .07       0  4891.3    .035       0    4997     .07       0
  5023.7     .07       0  5027.7     .07       0  5318.2    .035       0
  5398.7     .07       0  5452.7    .035       0  5847.6     .07       0
  5857.9    .035       0  6004.1     .07       0
Bank Sta=5023.7,5027.7
XS Rating Curve= 0 ,0
Exp/Cntr=0.3,0.1

Type RM Length L Ch R = 1 ,6703    ,361,361,361
BEGIN DESCRIPTION:
Mapping XS 34510f6a
END DESCRIPTION:
XS GIS Cut Line= 3
      1540536.88       6858407.9      1541242.66      6858402.69
      1542011.73      6858270.18
#Sta/Elev= 30
  4186.3 1767.71  4234.4 1766.92  4354.4 1763.59  4424.4 1760.44  4584.4 1751.64
  4624.4 1749.95  4774.4 1747.55  4804.4 1747.56  4814.4 1748.26  4844.4  1747.4
    4850 1746.71  4864.4 1747.01  4890.8 1745.88  4965.5 1746.53  4975.7    1745
  4983.8 1744.79    4984 1744.29  4987.5 1744.29  4987.8 1744.79  4996.3 1745.77
  5016.2 1746.24  5026.4 1745.83  5056.8 1747.87  5097.4 1751.51  5125.7 1752.96
  5129.4  1753.4  5229.3 1755.25  5244.1    1755  5358.8 1757.81  5672.5  1763.7
#Mann= 5 ,-1 , 0
  4186.3    .035       0  4983.8     .07       0  4987.8    .035       0
  4996.3     .07       0  5125.7    .035       0
Bank Sta=4983.8,4987.8
XS Rating Curve= 0 ,0
Exp/Cntr=0.3,0.1

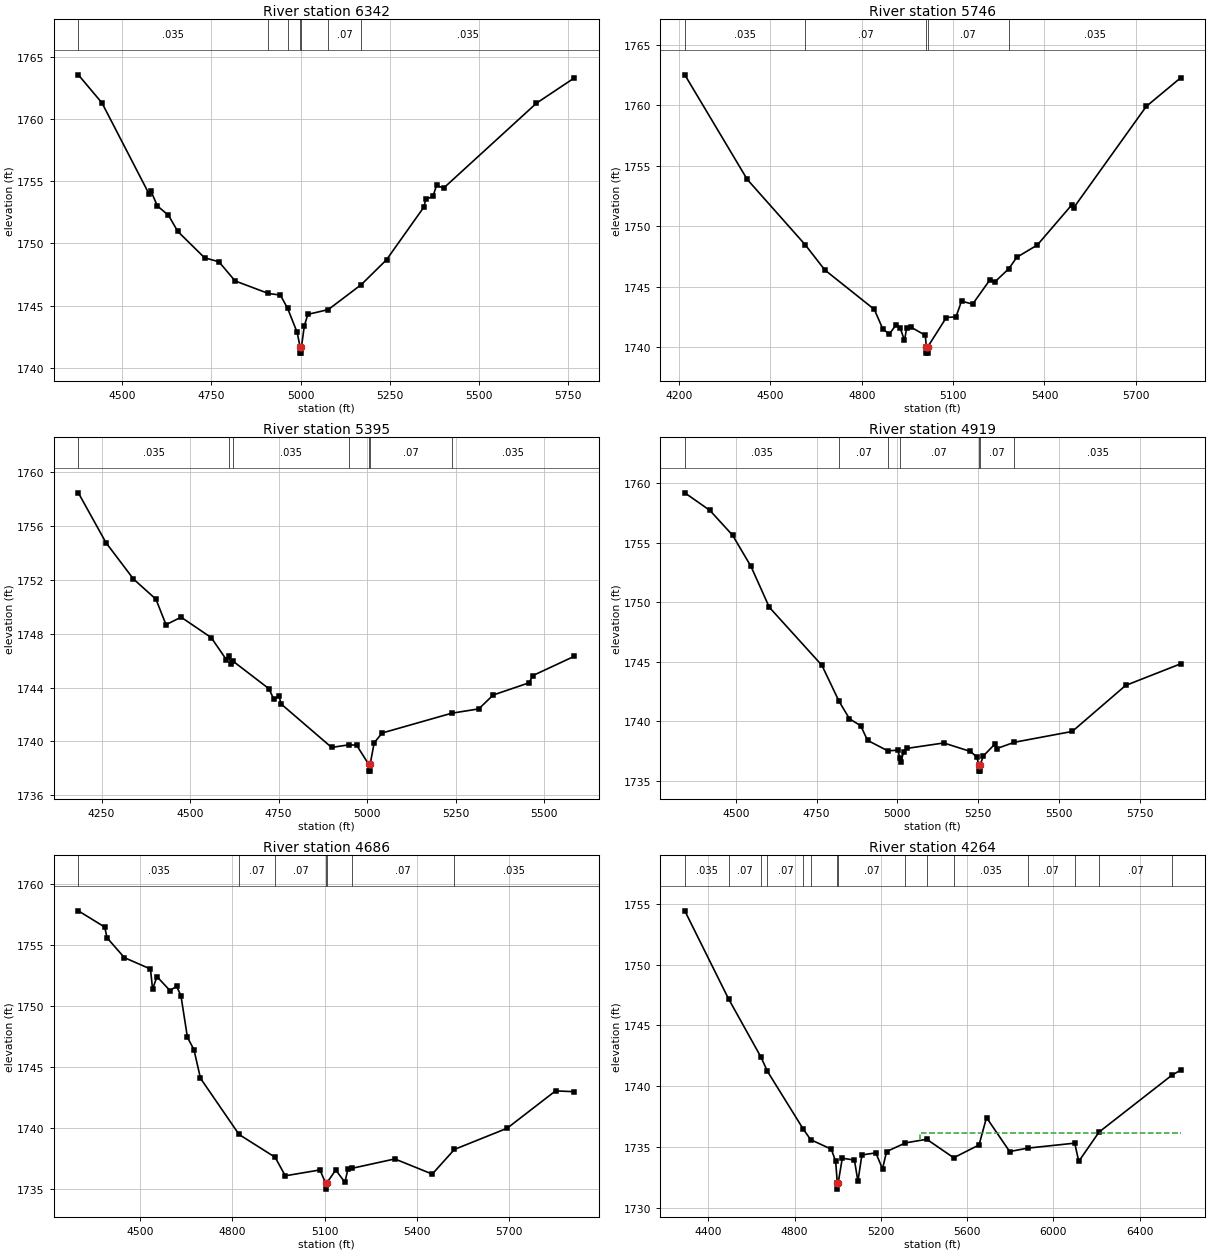
Type RM Length L Ch R = 1 ,6342    ,596,596,596
BEGIN DESCRIPTION:
Mapping XS 23b8c6bd
END DESCRIPTION:
XS GIS Cut Line= 3
      1540701.02      6858551.14      1541247.86      6858696.96
      1542070.41      6858668.33
#Sta/Elev= 30
  4377.6 1763.57  4443.8 1761.31    4576 1753.97  4581.2  1754.2  4599.1 1753.02
  4630.1 1752.27  4656.2 1750.97  4731.3 1748.85  4771.4 1748.53  4816.7 1746.99
  4909.9 1745.98  4943.6 1745.85  4963.9 1744.78  4990.7 1742.84  4998.7 1741.68
    4999 1741.18  5002.5 1741.18  5002.7 1741.68  5010.7 1743.38  5020.7  1744.3
  5077.7 1744.68  5170.6  1746.7  5240.9 1748.69  5345.4 1752.92  5350.9 1753.55
    5371 1753.79    5381 1754.67    5401 1754.46  5661.1 1761.29  5766.6 1763.31
#Mann= 7 ,-1 , 0
  4377.6    .035       0  4909.9     .07       0  4963.9    .035       0
  4998.7    .035       0  5002.7    .035       0  5077.7     .07       0
  5170.6    .035       0
Bank Sta=4998.7,5002.7
XS Rating Curve= 0 ,0
Exp/Cntr=0.3,0.1

Type RM Length L Ch R = 1 ,5746    ,351,351,351
BEGIN DESCRIPTION:
BULL WAGON CREEK TRIBUTARY 2 10.0
END DESCRIPTION:
XS GIS Cut Line= 3
      1540704.97      6858637.97      1541261.41      6859185.72
      1542061.56      6858907.62
#Sta/Elev= 30
  4219.2 1762.54  4424.3 1753.87  4614.5 1748.46  4678.9 1746.37  4841.5  1743.1
  4869.8 1741.45  4891.1 1741.07  4912.2  1741.8  4926.4 1741.56  4940.5 1740.53
  4947.6 1741.56  4961.8 1741.63  5008.7 1740.96  5012.4 1739.98  5012.6 1739.48
  5016.1 1739.48  5016.4 1739.98  5077.9 1742.43  5109.7 1742.49  5127.8 1743.79
  5164.2 1743.54  5221.2 1745.56  5236.7 1745.37  5282.8 1746.47  5309.2 1747.42
  5376.7 1748.44  5490.6 1751.79  5495.9 1751.52  5734.2 1759.92  5847.1 1762.29
#Mann= 5 ,-1 , 0
  4219.2    .035       0  4614.5     .07       0  5012.4     .07       0
  5016.4     .07       0  5282.8    .035       0
Bank Sta=5012.4,5016.4
XS Rating Curve= 0 ,0
Exp/Cntr=0.3,0.1

Type RM Length L Ch R = 1 ,5395    ,476,476,476
BEGIN DESCRIPTION:
BULL WAGON CREEK TRIBUTARY 2 9.0
END DESCRIPTION:
XS GIS Cut Line= 4
        1540605.        6858888.      1541049.86      6859379.52
      1541229.55      6859521.44      1541730.02        6859613.
#Sta/Elev= 30
  4184.4 1758.46  4262.5 1754.76  4340.2 1752.06  4403.7 1750.56  4432.1 1748.67
  4474.7 1749.23  4559.9 1747.71  4602.4 1746.08  4609.3 1746.32    4616 1745.74
    4622 1745.95  4722.7 1743.92  4736.9 1743.12  4750.9 1743.37  4757.9 1742.77
  4899.9 1739.56  4948.1 1739.75  4970.4 1739.73  5004.8  1738.3  5005.1  1737.8
  5008.6  1737.8  5008.8  1738.3  5020.1  1739.9  5042.6 1740.63  5239.2  1742.1
  5315.7 1742.42  5356.3 1743.45    5458 1744.36  5468.2 1744.89  5585.1 1746.32
#Mann= 7 ,-1 , 0
  4184.4    .035       0  4609.3     .07       0    4622    .035       0
  4948.1     .07       0  5004.8     .07       0  5008.8     .07       0
  5239.2    .035       0
Bank Sta=5004.8,5008.8
XS Rating Curve= 0 ,0
Exp/Cntr=0.3,0.1

Type RM Length L Ch R = 1 ,4919    ,233,233,233
BEGIN DESCRIPTION:
Mapping XS 8d9ed543
END DESCRIPTION:
XS GIS Cut Line= 4
        1540326.      6859287.55      1540812.97      6859727.65
      1541133.28      6859797.96      1541680.02        6859863.
#Sta/Elev= 30
    4342 1759.21  4419.7 1757.73    4490 1755.64  4546.8 1753.02  4603.6 1749.58
  4766.5 1744.69  4819.6 1741.66  4851.7  1740.2  4886.8  1739.6  4907.7 1738.38
  4970.2  1737.5    5002 1737.55  5007.3 1736.93  5010.7 1736.53  5019.6 1737.44
  5031.2 1737.71  5143.8 1738.16  5225.7 1737.45  5246.2 1736.98  5251.9 1736.29
  5252.2 1735.79  5255.7 1735.79  5255.9 1736.29  5266.6 1737.08  5302.8 1738.09
  5307.9 1737.69  5362.5 1738.22  5541.4 1739.13  5706.6    1743  5876.9 1744.82
#Mann= 7 ,-1 , 0
    4342    .035       0  4819.6     .07       0  4970.2    .035       0
  5007.3     .07       0  5251.9     .07       0  5255.9     .07       0
  5362.5    .035       0
Bank Sta=5251.9,5255.9
XS Rating Curve= 0 ,0
Exp/Cntr=0.3,0.1

Type RM Length L Ch R = 1 ,4686    ,422,422,422
BEGIN DESCRIPTION:
Mapping XS de686d53
END DESCRIPTION:
XS GIS Cut Line= 3
        1540143.      6859358.46      1540631.43      6859861.01
      1541529.96      6860012.99
#Sta/Elev= 30
  4299.2 1757.79  4385.1 1756.46  4392.3 1755.59  4448.9 1753.96  4533.7 1753.03
  4540.7 1751.38  4554.8 1752.41  4597.3 1751.26  4618.6 1751.62  4632.8 1750.85
  4653.9 1747.44  4675.1 1746.43  4696.3 1744.09  4821.9 1739.49  4938.9 1737.63
  4972.1 1736.11  5084.8 1736.59    5103 1735.52  5103.3 1735.02    5107 1735.52
  5136.2 1736.59  5165.9 1735.57    5176 1736.69  5188.3 1736.72  5328.2 1737.49
  5449.9 1736.25  5522.1 1738.27  5693.3    1740  5850.9 1743.06  5911.3 1742.99
#Mann= 7 ,-1 , 0
  4299.2    .035       0  4821.9     .07       0  4938.9     .07       0
    5103     .07       0    5107     .07       0  5188.3     .07       0
  5522.1    .035       0
Bank Sta=5103,5107
XS Rating Curve= 0 ,0
Exp/Cntr=0.3,0.1

Type RM Length L Ch R = 1 ,4264    ,418,418,418
BEGIN DESCRIPTION:
Mapping XS 15408acc
END DESCRIPTION:
XS GIS Cut Line= 4
      1539896.47      6860174.43      1540604.62        6860213.
      1541279.66      6860395.26      1541834.97       6861091.9
#Sta/Elev= 30
  4290.8 1754.42  4493.5 1747.19  4644.1 1742.39  4674.2 1741.22    4840 1736.48
  4874.3 1735.61  4970.3 1734.82  4990.4 1733.82    4998 1732.04  4998.2 1731.54
    5002 1732.04  5021.1 1734.08  5077.4 1733.93  5093.6 1732.19  5112.1 1734.35
  5176.5 1734.52  5207.6 1733.21  5226.6 1734.63    5314 1735.34  5412.7 1735.64
  5537.7 1734.12  5655.2 1735.17  5689.9 1737.42  5797.3 1734.63    5881 1734.91
  6099.1 1735.32  6117.6 1733.82  6211.7 1736.23  6549.1  1740.9  6590.1 1741.32
#Mann= 15 ,-1 , 0
  4290.8    .035       0  4493.5     .07       0  4644.1    .035       0
  4674.2     .07       0    4840    .035       0  4874.3     .07       0
    4998     .07       0    5002     .07       0    5314    .035       0
  5412.7     .07       0  5537.7    .035       0    5881     .07       0
  6099.1    .035       0  6211.7     .07       0  6549.1    .035       0
#XS Ineff= 2 , 0
       0                  5381.1       0 1736.13
Permanent Ineff=
       F       F
Bank Sta=4998,5002
XS Rating Curve= 0 ,0
Exp/Cntr=0.3,0.1

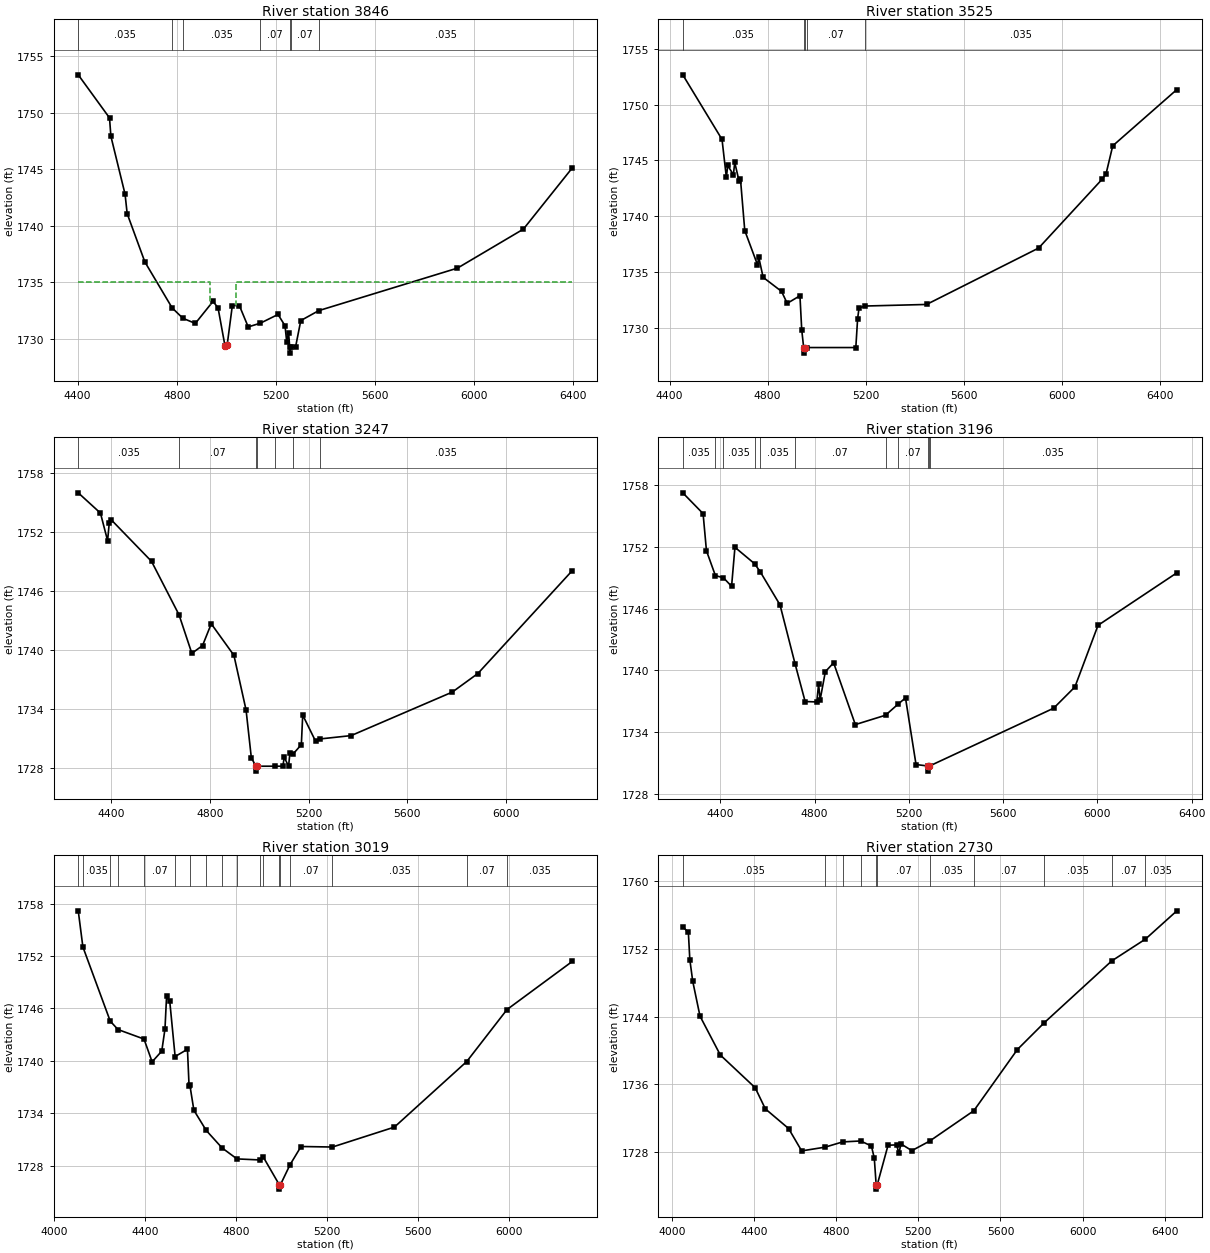
Type RM Length L Ch R = 1 ,3846    ,321,321,321
BEGIN DESCRIPTION:
Mapping XS e1416801
END DESCRIPTION:
XS GIS Cut Line= 4
      1539961.18      6860378.25      1540545.61       6860489.8
       1540756.9      6860685.94      1541666.86      6861320.08
#Sta/Elev= 30
  4402.9 1753.37    4529 1749.56  4534.5 1747.94  4591.7 1742.81  4600.2 1741.09
  4671.5 1736.82  4781.6 1732.75    4825 1731.83  4875.1 1731.38  4946.4 1733.33
  4966.7 1732.75    4995 1729.35  5003.2 1729.43  5024.3 1732.96  5052.6 1732.96
  5088.3 1731.07  5137.4  1731.4  5208.5 1732.17  5236.8 1731.17  5243.6 1729.74
    5251 1730.55  5255.8 1729.25    5256 1728.75  5259.8 1729.25  5279.3  1729.3
  5300.3 1731.63  5372.8 1732.51  5932.1 1736.27    6198 1739.72  6395.3 1745.14
#Mann= 7 ,-1 , 0
  4402.9    .035       0  4781.6     .07       0    4825    .035       0
  5137.4     .07       0  5255.8    .035       0  5259.8     .07       0
  5372.8    .035       0
#XS Ineff= 2 , 0
       0  4936.2    1735  5038.4       0    1735
Permanent Ineff=
       F       F
Bank Sta=4995,5003.2
XS Rating Curve= 0 ,0
Exp/Cntr=0.3,0.1

Type RM Length L Ch R = 1 ,3525    ,278,278,278
BEGIN DESCRIPTION:
Mapping XS 827a0529
END DESCRIPTION:
XS GIS Cut Line= 3
      1539951.82      6860518.43      1540448.39      6860740.67
      1541687.95       6861535.8
#Sta/Elev= 30
  4453.7 1752.66  4613.9 1746.87  4631.6 1743.47  4637.1 1744.54  4660.3 1743.71
  4665.8 1744.81  4683.5 1743.13    4689 1743.37  4706.7 1738.71  4758.6 1735.65
    4764  1736.3  4781.7 1734.52  4856.8 1733.26    4880 1732.19  4931.9 1732.87
  4939.2 1729.82  4947.1 1728.23  4947.5 1727.73  4952.1 1728.23  4960.7 1728.23
    5160 1728.23  5167.4 1730.83  5173.3 1731.79  5199.4 1731.95  5448.8 1732.09
  5906.1 1737.14  6166.4 1743.33  6181.6 1743.81  6208.7  1746.3  6470.4 1751.34
#Mann= 5 ,-1 , 0
  4453.7    .035       0  4947.1     .07       0  4952.1    .035       0
  4960.7     .07       0  5199.4    .035       0
Bank Sta=4947.1,4952.1
XS Rating Curve= 0 ,0
Exp/Cntr=0.3,0.1

Type RM Length L Ch R = 1 ,3247    ,51,51,51
BEGIN DESCRIPTION:
Mapping XS 1503f3ed
END DESCRIPTION:
XS GIS Cut Line= 5
      1539806.05      6860469.86      1540238.32      6860808.38
       1540352.9      6860912.55      1540384.15      6860964.63
      1541514.37      6861472.45
#Sta/Elev= 30
  4265.2 1756.01  4355.3 1753.95  4384.2 1751.15  4390.9 1752.93  4398.6 1753.28
  4562.3 1749.05    4674 1743.61  4725.9  1739.7  4769.3 1740.49  4804.6  1742.7
  4896.5  1739.5  4945.8 1733.94  4967.1  1729.1  4985.4 1728.23  4985.8 1727.73
  4990.4 1728.23  5064.9 1728.23  5095.1 1728.23  5100.5 1729.14  5118.2 1728.23
  5123.7 1729.59  5135.4 1729.44    5170 1730.42  5175.5 1733.43  5228.1 1730.75
  5245.6    1731  5371.8 1731.34    5782 1735.76  5885.9 1737.65  6268.9 1748.11
#Mann= 7 ,-1 , 0
  4265.2    .035       0    4674     .07       0  4985.4     .07       0
  4990.4     .07       0  5064.9    .035       0  5135.4     .07       0
  5245.6    .035       0
Bank Sta=4985.4,4990.4
XS Rating Curve= 0 ,0
Exp/Cntr=0.3,0.1

Type RM Length L Ch R = 1 ,3196    ,177,177,177
BEGIN DESCRIPTION:
Mapping XS 83bacfe8
END DESCRIPTION:
XS GIS Cut Line= 5
      1539751.33      6860469.83        1540293.      6860925.57
      1540376.34      6861021.92      1540475.29      6861063.59
      1541516.98      6861560.99
#Sta/Elev= 30
  4240.2 1757.24  4326.4 1755.22  4340.7 1751.61  4378.7  1749.2  4412.8 1748.99
  4447.3 1748.16  4461.6 1751.95  4544.7 1750.36    4569 1749.57  4652.8 1746.36
  4716.7 1740.64  4759.5 1736.97  4808.9 1736.93  4816.7 1738.66  4823.2 1737.14
  4845.3 1739.87  4880.4 1740.73  4972.6 1734.73  5100.7 1735.64  5155.7 1736.75
  5185.5 1737.32  5230.2 1730.85  5279.8 1730.71  5280.1 1730.21  5284.8 1730.71
  5288.6 1730.72  5814.2 1736.32  5904.6 1738.39  6002.6 1744.37  6337.2 1749.47
#Mann= 11 ,-1 , 0
  4240.2    .035       0  4378.7     .07       0  4412.8    .035       0
  4544.7     .07       0    4569    .035       0  4716.7     .07       0
  5100.7    .035       0  5155.7     .07       0  5279.8     .07       0
  5284.8     .07       0  5288.6    .035       0
Bank Sta=5279.8,5284.8
XS Rating Curve= 0 ,0
Exp/Cntr=0.3,0.1

Type RM Length L Ch R = 1 ,3019    ,289,289,289
BEGIN DESCRIPTION:
Mapping XS 60b75e4c
END DESCRIPTION:
XS GIS Cut Line= 4
      1539699.24       6860514.1      1540183.63      6861003.69
      1540457.07      6861185.98      1541503.98      6861678.19
#Sta/Elev= 30
  4104.9 1757.18  4125.3 1753.05  4245.7 1744.55  4279.8 1743.59  4394.3  1742.5
    4430 1739.89  4472.4 1741.12  4486.5 1743.64  4493.6 1747.39  4507.7  1746.8
  4531.2  1740.5  4585.5 1741.33  4592.6 1737.13  4596.2 1737.21  4613.8 1734.35
  4668.1 1732.04  4737.7 1730.04  4803.3 1728.78    4905 1728.66  4920.1 1728.95
  4989.6 1725.82    4990 1725.32  4994.6 1725.82  5036.9 1728.11  5085.3  1730.2
  5223.6 1730.14  5496.2 1732.42  5814.6 1739.93  5991.8 1745.88  6279.1 1751.39
#Mann= 18 ,-1 , 0
  4104.9     .07       0  4125.3    .035       0  4245.7     .07       0
  4279.8    .035       0  4394.3     .07       0  4531.2    .035       0
  4596.2     .07       0  4668.1    .035       0  4737.7     .07       0
  4803.3    .035       0    4905     .07       0  4920.1    .035       0
  4989.6    .035       0  4994.6    .035       0  5036.9     .07       0
  5223.6    .035       0  5814.6     .07       0  5991.8    .035       0
Bank Sta=4989.6,4994.6
XS Rating Curve= 0 ,0
Exp/Cntr=0.3,0.1

Type RM Length L Ch R = 1 ,2730    ,487,487,487
BEGIN DESCRIPTION:
Mapping XS 999f7b37
END DESCRIPTION:
XS GIS Cut Line= 3
       1539602.5      6860702.03      1540266.53      6861379.08
      1541650.55      6861834.64
#Sta/Elev= 30
  4053.2  1754.6  4080.4 1753.94  4087.5 1750.72  4101.7 1748.16    4137 1744.06
    4236 1739.47  4405.7 1735.61  4455.1 1733.12  4568.3  1730.8    4632 1728.16
  4745.7  1728.6  4831.6 1729.22  4918.9 1729.33  4971.5 1728.74  4985.6 1727.31
  4994.7 1724.15  4995.1 1723.65  4999.8 1724.15  5052.6 1728.83  5094.7 1728.87
    5105 1727.87  5115.7 1728.98  5168.4 1728.19  5254.6 1729.31  5470.2  1732.9
  5682.3 1740.12  5811.8 1743.25  6141.5 1750.57  6305.5 1753.14  6458.6 1756.48
#Mann= 11 ,-1 , 0
  4053.2    .035       0  4745.7     .07       0  4831.6    .035       0
  4918.9     .07       0  4994.7     .07       0  4999.8     .07       0
  5254.6    .035       0  5470.2     .07       0  5811.8    .035       0
  6141.5     .07       0  6305.5    .035       0
Bank Sta=4994.7,4999.8
XS Rating Curve= 0 ,0
Exp/Cntr=0.3,0.1

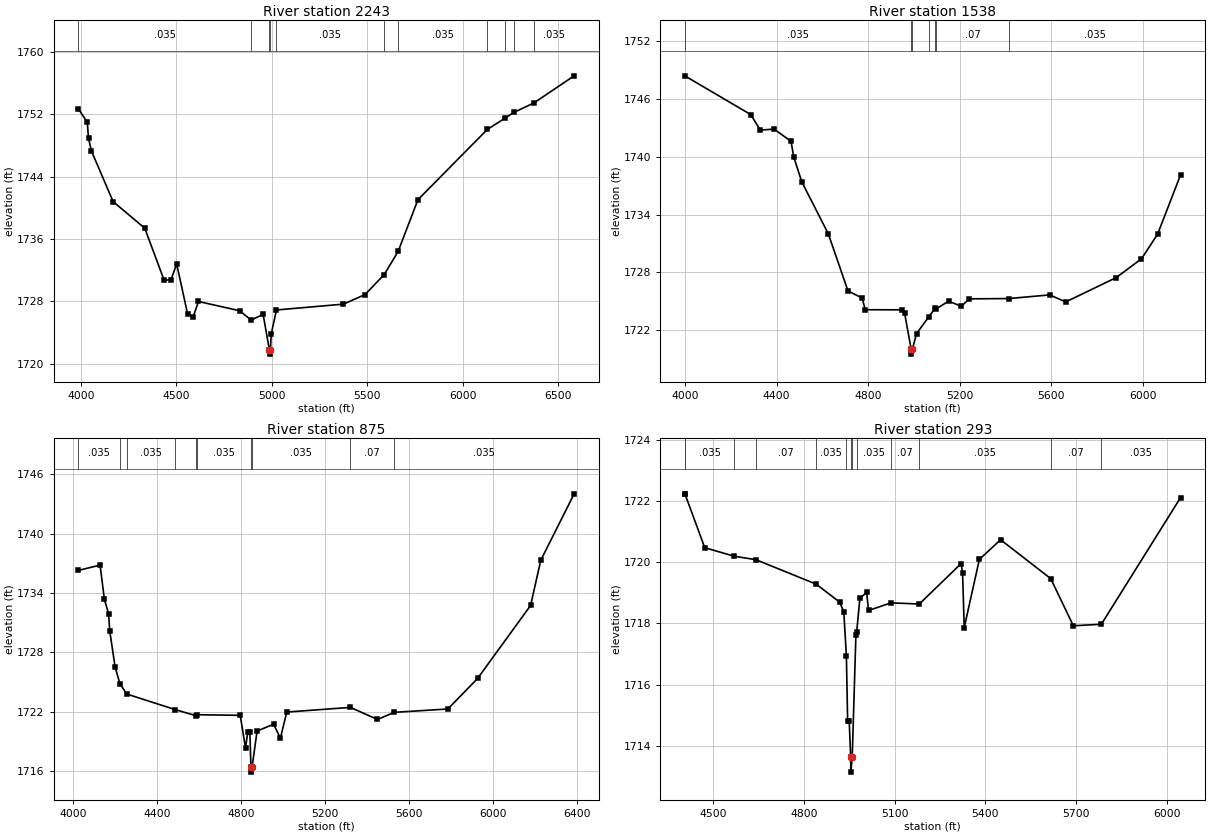
Type RM Length L Ch R = 1 ,2243    ,705,705,705
BEGIN DESCRIPTION:
Mapping XS 555002fa
END DESCRIPTION:
XS GIS Cut Line= 3
      1539420.16        6860919.      1539980.07      6861752.35
      1541531.95      6862116.47
#Sta/Elev= 30
  3986.6 1752.72  4033.6 1750.95  4039.9 1748.95  4054.8 1747.32  4168.9  1740.8
  4334.8 1737.39  4435.9 1730.74  4471.9 1730.77  4501.9 1732.81  4558.9 1726.42
  4587.8 1725.98  4615.9    1728  4831.9 1726.81    4892 1725.62  4954.9 1726.34
    4988 1721.75  4988.4 1721.25  4993.1 1721.75  4997.1 1723.82  5024.8 1726.91
  5375.7 1727.66  5488.7 1728.88  5589.2 1731.45  5662.2 1734.41    5766 1741.05
  6129.9 1750.06  6220.3 1751.47  6267.6 1752.23  6372.8 1753.44  6584.6 1756.93
#Mann= 11 ,-1 , 0
  3986.6    .035       0    4892     .07       0    4988     .07       0
  4993.1     .07       0  5024.8    .035       0  5589.2     .07       0
  5662.2    .035       0  6129.9     .07       0  6220.3    .035       0
  6267.6     .07       0  6372.8    .035       0
Bank Sta=4988,4993.1
XS Rating Curve= 0 ,0
Exp/Cntr=0.3,0.1

Type RM Length L Ch R = 1 ,1538    ,663,663,663
BEGIN DESCRIPTION:
Mapping XS a38b6bc9
END DESCRIPTION:
XS GIS Cut Line= 3
      1539220.51      6861149.02      1539474.27      6862117.52
      1540635.38      6862205.09
#Sta/Elev= 30
  3998.8 1748.42  4287.2 1744.39  4328.6 1742.78  4388.4 1742.89  4462.9 1741.62
  4474.3 1740.02  4509.6 1737.42  4625.6 1732.01  4711.6 1726.08  4773.1 1725.35
  4787.2 1724.13  4948.8 1724.12  4959.1 1723.74  4987.6 1720.02    4988 1719.52
  4992.8 1720.02  5010.8 1721.65  5064.9  1723.4  5091.9 1724.29    5098 1724.24
  5151.2 1725.02    5206 1724.49  5241.4 1725.26  5413.9 1725.29  5592.4 1725.67
  5662.6 1724.94  5883.2 1727.47  5993.5 1729.42  6063.7 1731.97  6164.4 1738.15
#Mann= 7 ,-1 , 0
  3998.8    .035       0  4987.6    .035       0  4992.8    .035       0
  5064.9     .07       0  5091.9    .035       0    5098     .07       0
  5413.9    .035       0
Bank Sta=4987.6,4992.8
XS Rating Curve= 0 ,0
Exp/Cntr=0.3,0.1

Type RM Length L Ch R = 1 ,875     ,582,582,582
BEGIN DESCRIPTION:
Mapping XS 5d244904
END DESCRIPTION:
XS GIS Cut Line= 3
       1539151.1      6861856.32      1539310.82      6862667.93
      1540830.42      6862450.97
#Sta/Elev= 30
  4026.3 1736.28  4129.9 1736.82  4150.3 1733.37  4170.7 1731.89  4175.9 1730.19
  4201.3 1726.54  4224.6 1724.82  4257.1 1723.79  4488.8 1722.21  4589.1 1721.59
  4591.2  1721.7  4797.5 1721.64    4823 1718.34  4833.2 1719.92  4843.4 1719.92
  4848.8  1716.4  4849.2  1715.9    4854  1716.4  4877.9 1720.05  4956.4 1720.74
    4989 1719.33  5019.3 1721.97  5322.8 1722.44  5451.5 1721.22  5530.9 1721.94
    5787 1722.28  5928.5 1725.37    6181 1732.74  6229.5 1737.31  6388.5 1744.02
#Mann= 10 ,-1 , 0
  4026.3    .035       0  4224.6     .07       0  4257.1    .035       0
  4488.8     .07       0  4589.1    .045       0  4591.2    .035       0
  4848.8    .035       0    4854    .035       0  5322.8     .07       0
  5530.9    .035       0
Bank Sta=4848.8,4854
XS Rating Curve= 0 ,0
Exp/Cntr=0.3,0.1

Type RM Length L Ch R = 1 ,293     ,0,0,0
BEGIN DESCRIPTION:
BULL WAGON CREEK TRIBUTARY 2 1.0
END DESCRIPTION:
XS GIS Cut Line= 4
      1538929.99      6862462.97      1539022.62      6862994.32
      1539116.37      6863062.03      1540098.98      6862990.85
#Sta/Elev= 30
    4406 1722.23  4406.4 1722.23    4472 1720.47    4570 1720.19  4640.9 1720.08
  4840.6 1719.28  4918.6 1718.69    4932 1718.37  4940.5 1716.94  4944.7  1714.8
  4949.9  1714.8  4954.7 1713.64  4955.1 1713.14  4959.9 1713.64    4972 1717.61
  4974.5 1717.71  4985.3 1718.82  5007.6 1719.01  5013.8 1718.42  5088.6 1718.67
  5181.7 1718.63  5319.9 1719.95  5324.9 1719.65  5330.3 1717.86  5380.5 1720.09
  5450.7 1720.73  5616.6 1719.46  5691.3 1717.92    5784 1717.97  6046.2 1722.11
#Mann= 13 ,-1 , 0
    4406    .045       0  4406.4    .035       0    4570    .045       0
  4640.9     .07       0  4840.6    .035       0  4940.5    .045       0
  4954.7    .035       0  4959.9    .045       0  4974.5    .035       0
  5088.6     .07       0  5181.7    .035       0  5616.6     .07       0
    5784    .035       0
Bank Sta=4954.7,4959.9
XS Rating Curve= 0 ,0
Exp/Cntr=0.3,0.1

Chan Stop Cuts=-1
Use User Specified Reach Order=0
Composite Channel Slope=5