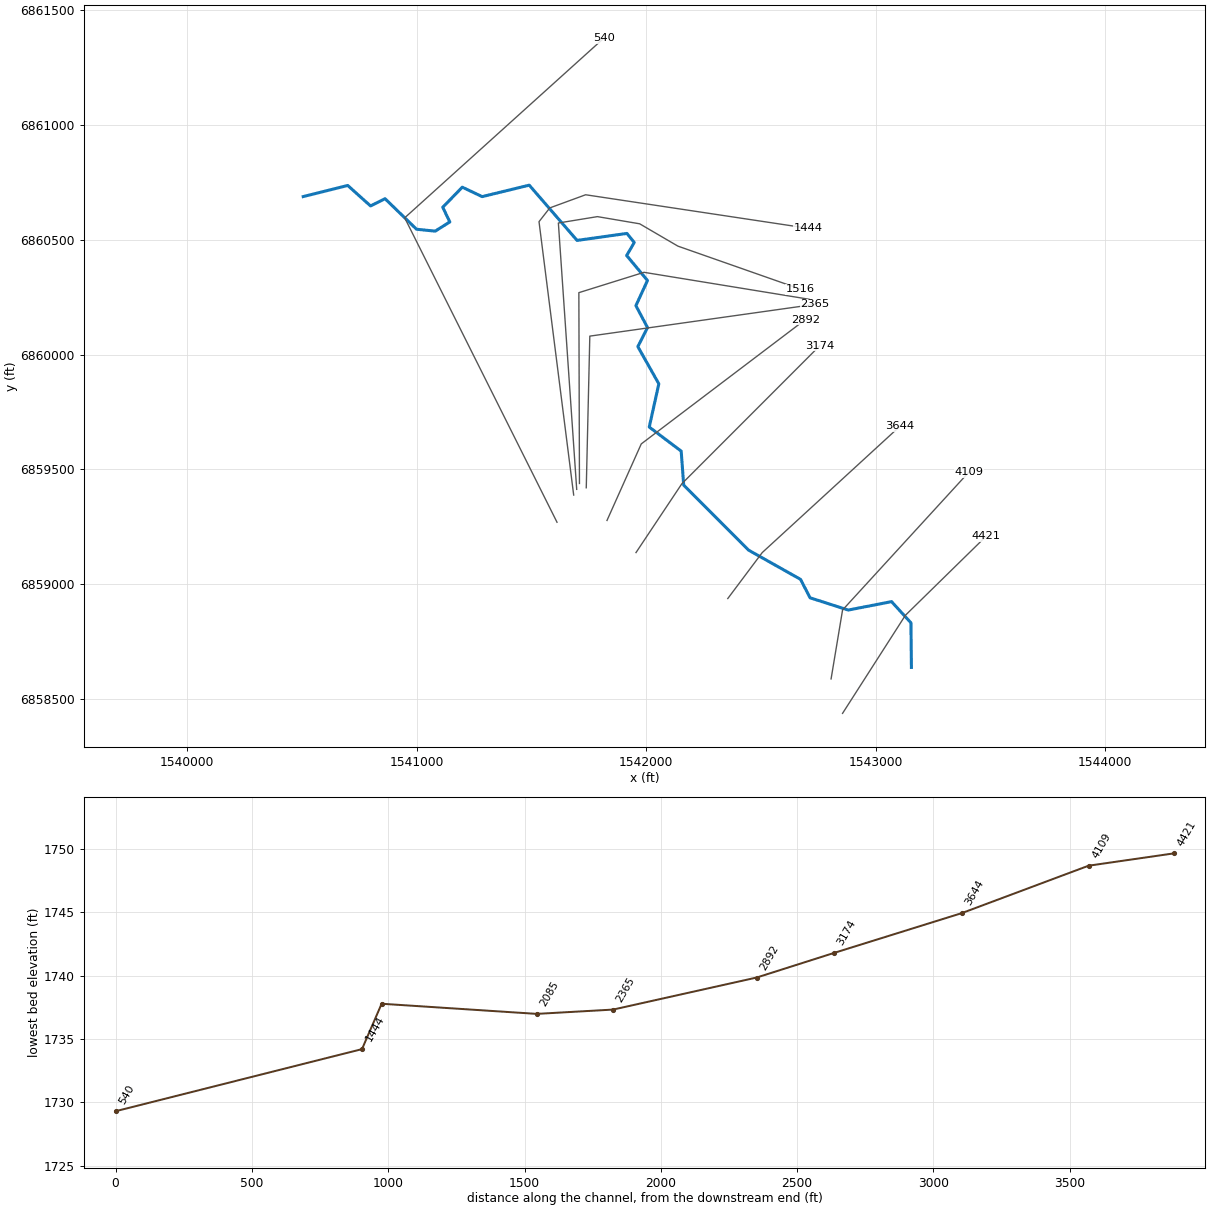
--- BULL WAGON CREEK TRIBUTARY 2_1.prj (project) ---

Proj Title=BULL WAGON CREEK TRIBUTARY 2_1 Base Level Engineering
Current Plan=p01
Default Exp/Contr=0.3,0.1
English Units
Geom File=g01
Flow File=f01
Plan File=p01
Y Axis Title=Elevation
X Axis Title(PF)=Main Channel Distance
X Axis Title(XS)=Station
BEGIN DESCRIPTION:
BULL WAGON CREEK TRIBUTARY 2_1
END DESCRIPTION:
DSS Export Rating Curves= 0
DSS Export Rating Curve Sorted= 0
DSS Export Volume Flow Curves= 0
DXF OffsetX= 0
DXF OffsetY= 0
DXF ScaleX= 1
DXF ScaleY= 10

--- BULL WAGON CREEK TRIBUTARY 2_1.p01 (plan) ---

Plan Title=Multiple Run
Short Identifier=Multiple
Geom File=g01
Flow File=f01
Subcritical Flow
K Sum by GR= 0
Std Step Tol= 0.01
Critical Tol= 0.01
Num of Std Step Trials= 20
Max Error Tol= 0.3
Flow Tol Ratio= 0.001
Split Flow NTrial= 30
Split Flow Tol= 0.02
Split Flow Ratio= 0.02
Log Output Level= 0
Friction Slope Method= 1
Unsteady Friction Slope Method= 2
Unsteady Bridges Friction Slope Method= 1
Parabolic Critical Depth
Global Vel Dist=  1 , 1 , 1
Global Log Level= 0
CheckData=True
Encroach Param= -1, 0, 0, 0
BEGIN DESCRIPTION:
Multiple Run
END DESCRIPTION:

--- BULL WAGON CREEK TRIBUTARY 2_1.f01 (steady flow) ---

Flow Title=Multiple
Number of Profiles=7
Profile Names=10-year,25-year,50-year,1pct_min,100-year,1pct_plu,500-year
River Rch & RM= BULL WAGON CREEK,Reach-1,4421
     139     186     224     134     268     534     389
River Rch & RM= BULL WAGON CREEK,Reach-1,2365
     193     263     319     194     387     772     574
Boundary for River Rch & Prof#=BULL WAGON CREEK,Reach-1,1
Up Type=0
Dn Type=3
Dn Slope=0.005
Boundary for River Rch & Prof#=BULL WAGON CREEK,Reach-1,2
Up Type=0
Dn Type=3
Dn Slope=0.005
Boundary for River Rch & Prof#=BULL WAGON CREEK,Reach-1,3
Up Type=0
Dn Type=3
Dn Slope=0.005
Boundary for River Rch & Prof#=BULL WAGON CREEK,Reach-1,4
Up Type=0
Dn Type=3
Dn Slope=0.005
Boundary for River Rch & Prof#=BULL WAGON CREEK,Reach-1,5
Up Type=0
Dn Type=3
Dn Slope=0.005
Boundary for River Rch & Prof#=BULL WAGON CREEK,Reach-1,6
Up Type=0
Dn Type=3
Dn Slope=0.005
Boundary for River Rch & Prof#=BULL WAGON CREEK,Reach-1,7
Up Type=0
Dn Type=3
Dn Slope=0.005

--- BULL WAGON CREEK TRIBUTARY 2_1.g01 (geometry) ---

Geom Title=Existing Conditions
Program Version=4.10

River Reach=BULL WAGON CREEK,Reach-1
Reach XY= 30
        1543155.        6858638.      1543152.95      6858832.17
      1543068.41      6858924.48      1542879.93      6858887.77
      1542713.35      6858941.19      1542672.01      6859021.42
      1542445.32      6859148.78      1542162.82      6859431.81
      1542151.92      6859579.69      1542012.79      6859684.57
      1542054.51      6859872.78      1541963.07      6860034.69
       1542005.2       6860117.8      1541954.62        6860213.
      1542005.03      6860322.66      1541914.33      6860431.35
      1541947.54      6860488.25      1541915.51      6860527.53
      1541698.26      6860497.13      1541489.96      6860737.69
      1541284.79      6860687.79      1541198.23      6860728.85
      1541113.01      6860641.35      1541143.91      6860577.62
      1541080.22      6860537.49      1540998.83      6860545.76
      1540861.67       6860678.7      1540798.34      6860647.32
      1540698.97      6860736.37        1540505.        6860688.

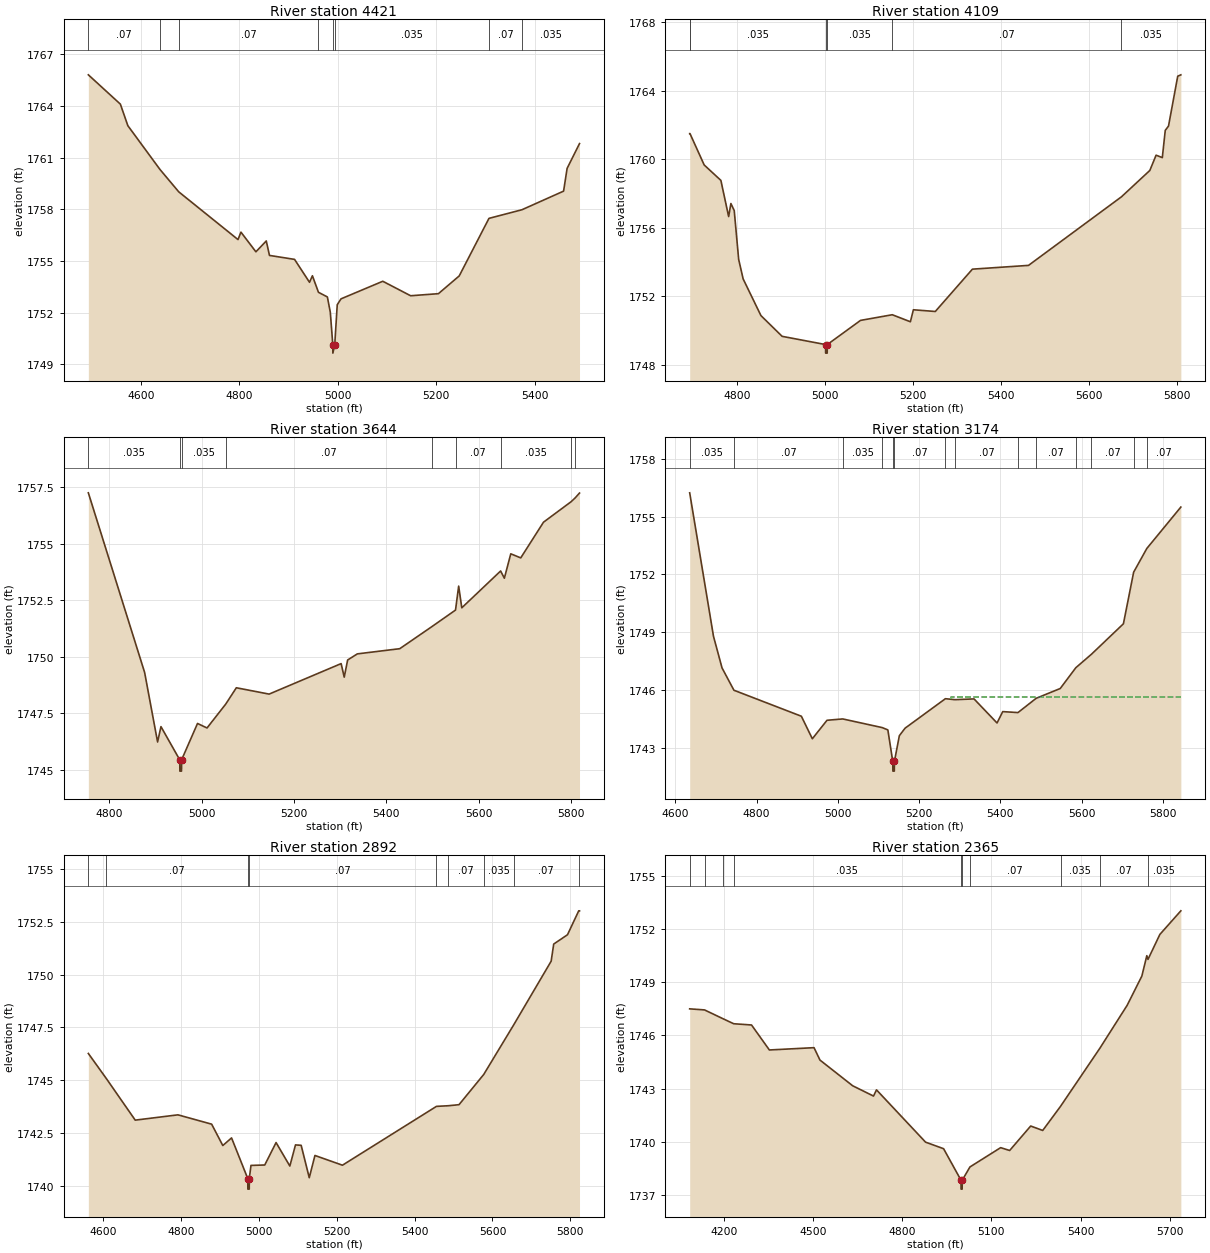
Type RM Length L Ch R = 1 ,4421    ,312,312,312
BEGIN DESCRIPTION:
BULL WAGON CREEK TRIBUTARY 2_1 5.0
END DESCRIPTION:
XS GIS Cut Line= 3
      1542854.98      6858437.97      1543128.84      6858865.01
      1543480.03      6859208.72
#Sta/Elev= 30
  4492.7  1765.8  4557.8  1764.1    4573 1762.85  4638.3 1760.31  4676.5 1759.01
    4797 1756.24    4803 1756.67  4833.4 1755.53  4854.5 1756.16    4861 1755.32
    4912 1755.09  4942.4 1753.76  4948.3 1754.14  4960.6 1753.18  4978.7 1752.91
  4984.7 1752.02  4989.7 1750.15  4989.9 1749.65  4993.7 1750.15  4998.8 1752.46
  5006.5  1752.8  5091.4 1753.82    5148 1752.98  5204.5  1753.1  5246.8 1754.13
  5307.3 1757.47  5374.3 1757.97    5459 1759.05  5466.2 1760.37  5491.4 1761.81
#Mann= 8 ,-1 , 0
  4492.7     .07       0  4638.3    .035       0  4676.5     .07       0
  4960.6    .035       0  4989.7    .035       0  4993.7    .035       0
  5307.3     .07       0  5374.3    .035       0
#XS Ineff= 2 , 0
       0                  5091.4       0 1753.82
Permanent Ineff=
       F       F
Bank Sta=4989.7,4993.7
XS Rating Curve= 0 ,0
Exp/Cntr=0.3,0.1

Type RM Length L Ch R = 1 ,4109    ,465,465,465
BEGIN DESCRIPTION:
BULL WAGON CREEK TRIBUTARY 2_1 4.0
END DESCRIPTION:
XS GIS Cut Line= 3
        1542805.      6858587.98        1542855.        6858888.
        1543405.        6859488.
#Sta/Elev= 30
  4691.4 1761.49  4692.1 1761.49  4724.4 1759.66  4762.4 1758.76  4780.1 1756.65
  4785.2 1757.41  4792.8    1757  4802.9 1754.15  4813.1 1753.01  4853.6 1750.87
  4901.8 1749.66  5000.7 1749.18  5000.9 1748.68  5004.4 1748.68  5004.7 1749.18
  5080.3 1750.59  5152.6 1750.92  5193.8 1750.51  5200.6 1751.21  5250.5 1751.11
    5335 1753.58  5462.7  1753.8  5674.2  1757.8  5738.9 1759.34  5753.1 1760.23
  5767.3 1760.09    5774 1761.68  5781.4 1761.93  5802.4 1764.84  5809.5 1764.92
#Mann= 6 ,-1 , 0
  4691.4     .07       0  4692.1    .035       0  5000.7    .035       0
  5004.7    .035       0  5152.6     .07       0  5674.2    .035       0
Bank Sta=5000.7,5004.7
XS Rating Curve= 0 ,0
Exp/Cntr=0.3,0.1

Type RM Length L Ch R = 1 ,3644    ,470,470,470
BEGIN DESCRIPTION:
BULL WAGON CREEK TRIBUTARY 2_1 3.0
END DESCRIPTION:
XS GIS Cut Line= 3
      1542354.97      6858937.97        1542505.        6859138.
      1543105.01      6859688.01
#Sta/Elev= 30
  4754.5 1757.26  4876.4 1749.31  4904.5 1746.23  4911.8 1746.91  4952.5 1745.44
  4952.8 1744.94  4956.3 1744.94  4956.5 1745.44    4991 1747.05  5011.6 1746.85
  5052.2 1747.91  5075.1 1748.63  5146.1 1748.35  5302.1  1749.7  5308.8  1749.1
  5316.2 1749.86  5337.2 1750.13  5429.1 1750.36  5498.2 1751.33  5549.9 1752.07
  5556.7 1753.13  5563.5 1752.17  5647.6  1753.8  5655.7 1753.48  5669.6 1754.56
  5691.2 1754.38  5740.5 1755.96  5800.5 1756.87  5808.8 1757.03  5818.5 1757.25
#Mann= 9 ,-1 , 0
  4754.5    .035       0  4952.5    .035       0  4956.5    .035       0
  5052.2     .07       0  5498.2    .035       0  5549.9     .07       0
  5647.6    .035       0  5800.5     .07       0  5808.8    .035       0
Bank Sta=4952.5,4956.5
XS Rating Curve= 0 ,0
Exp/Cntr=0.3,0.1

Type RM Length L Ch R = 1 ,3174    ,282,282,282
BEGIN DESCRIPTION:
BULL WAGON CREEK TRIBUTARY 2_1 2.0
END DESCRIPTION:
XS GIS Cut Line= 3
      1541955.02      6859138.03        1542155.        6859438.
      1542754.96      6860037.96
#Sta/Elev= 30
  4635.2 1756.24  4693.8 1748.79  4714.8 1747.15  4744.1 1745.99  4910.1 1744.64
  4937.1 1743.47  4973.2 1744.43  5011.9  1744.5  5109.1 1744.05    5123 1743.93
  5135.1 1742.29  5135.4 1741.79  5138.9 1741.79  5139.1 1742.29  5151.3 1743.63
  5165.4 1744.02  5264.6 1745.55  5288.4  1745.5  5335.1 1745.54  5391.7 1744.29
  5405.8 1744.88  5443.3 1744.83    5488 1745.57  5547.3 1746.08  5585.7 1747.16
  5624.2 1747.86  5702.8 1749.44    5728 1752.12  5760.4 1753.35  5844.2  1755.5
#Mann= 14 ,-1 , 0
  4635.2    .035       0  4744.1     .07       0  5011.9    .035       0
  5109.1     .07       0  5135.1     .07       0  5139.1     .07       0
  5264.6    .035       0  5288.4     .07       0  5443.3    .035       0
    5488     .07       0  5585.7    .035       0  5624.2     .07       0
    5728    .035       0  5760.4     .07       0
#XS Ineff= 2 , 0
       0                  5278.6       0 1745.63
Permanent Ineff=
       F       F
Bank Sta=5135.1,5139.1
XS Rating Curve= 0 ,0
Exp/Cntr=0.3,0.1

Type RM Length L Ch R = 1 ,2892    ,527,527,527
BEGIN DESCRIPTION:
Mapping XS 4c19274e
END DESCRIPTION:
XS GIS Cut Line= 3
      1541828.62      6859277.81      1541977.92      6859611.12
      1542693.15      6860152.76
#Sta/Elev= 30
  4561.3 1746.27  4607.7 1745.08  4681.8 1743.12  4791.6 1743.37  4878.2 1742.93
  4906.9 1741.92  4929.4 1742.28    4971 1740.36  4971.3 1739.86  4974.8 1739.86
    4975 1740.36  4979.3 1740.98  5014.7    1741  5043.8 1742.06  5079.2 1740.95
  5093.7 1741.95  5108.3 1741.93  5129.1  1740.4  5143.7 1741.45  5214.4 1740.99
    5456 1743.77  5486.3  1743.8    5514 1743.85  5577.6 1745.28  5654.5 1747.62
  5750.8 1750.63  5757.4 1751.44  5792.8 1751.88  5821.7 1753.01  5823.7 1753.01
#Mann= 9 ,-1 , 0
  4561.3    .035       0  4607.7     .07       0    4971     .07       0
    4975     .07       0    5456    .035       0  5486.3     .07       0
  5577.6    .035       0  5654.5     .07       0  5821.7    .035       0
Bank Sta=4971,4975
XS Rating Curve= 0 ,0
Exp/Cntr=0.3,0.1

Type RM Length L Ch R = 1 ,2365    ,280,280,280
BEGIN DESCRIPTION:
Mapping XS 832fd473
END DESCRIPTION:
XS GIS Cut Line= 3
      1541738.33      6859420.14      1541753.81      6860080.45
      1542734.82      6860218.76
#Sta/Elev= 30
  4085.6  1747.5  4135.5 1747.44    4198 1746.94  4233.5 1746.66  4293.5 1746.59
  4353.5 1745.18  4503.6 1745.31  4523.6 1744.61  4633.6 1743.16  4703.6 1742.58
  4713.6 1742.93  4878.6 1739.98  4939.2 1739.61  4997.8 1737.83    4998 1737.33
  5001.5 1737.33  5001.8 1737.83  5027.7 1738.58    5131 1739.67  5161.3 1739.51
    5232 1740.89  5272.4 1740.64  5332.3    1742  5464.2 1745.27  5556.3  1747.7
  5605.7 1749.35  5622.4  1750.5  5626.3 1750.29  5666.3  1751.7  5736.8 1753.03
#Mann= 10 ,-1 , 0
  4085.6     .07       0  4135.5    .035       0    4198     .07       0
  4233.5    .035       0  4997.8    .035       0  5001.8    .035       0
  5027.7     .07       0  5332.3    .035       0  5464.2     .07       0
  5626.3    .035       0
Bank Sta=4997.8,5001.8
XS Rating Curve= 0 ,0
Exp/Cntr=0.3,0.1

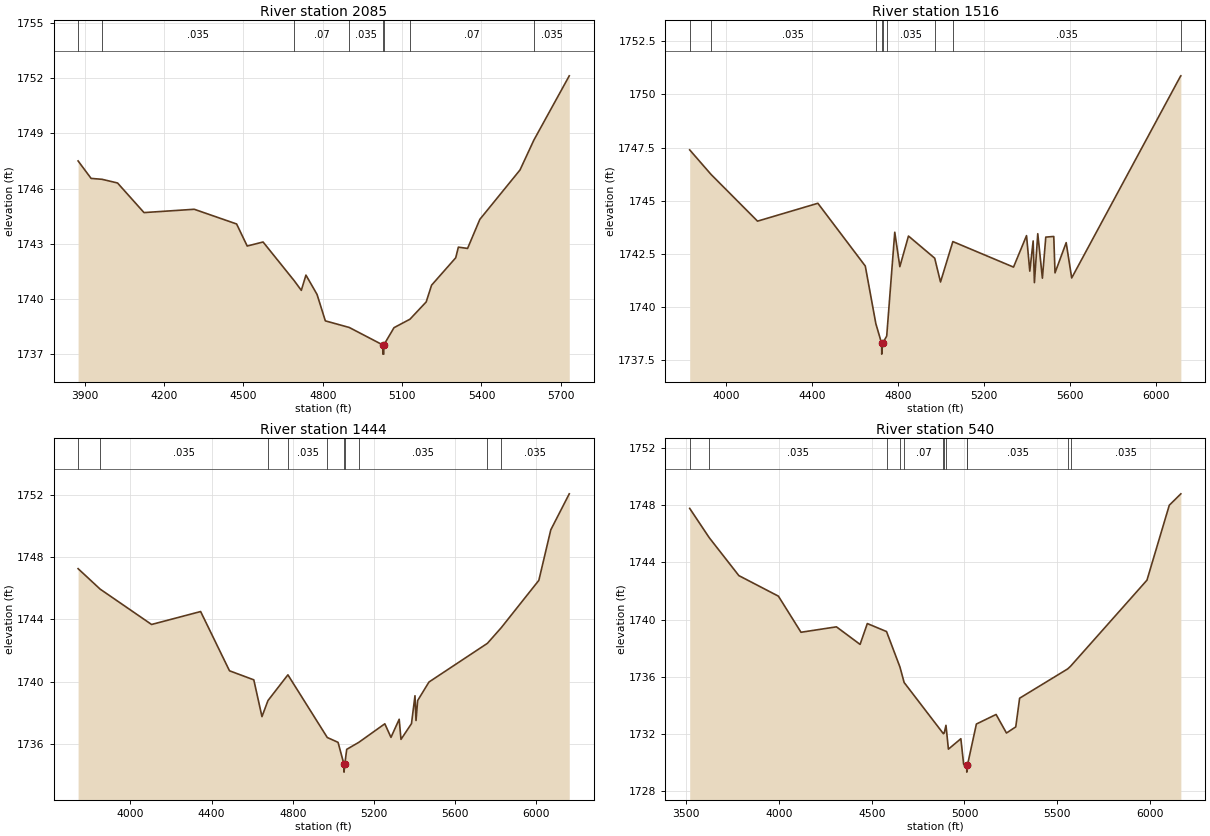
Type RM Length L Ch R = 1 ,2085    ,569,569,569
BEGIN DESCRIPTION:
Mapping XS 74939ee4
END DESCRIPTION:
XS GIS Cut Line= 4
      1541708.67      6859438.94      1541706.07      6860269.69
      1541989.92      6860358.23      1542708.64      6860241.05
#Sta/Elev= 30
  3875.6  1747.5  3924.7 1746.55  3966.4  1746.5  4024.7  1746.3  4124.7 1744.69
  4314.7 1744.87  4474.7 1744.07  4514.7 1742.87  4574.7 1743.09  4692.6 1740.98
  4719.2 1740.46  4736.7 1741.29  4778.6 1740.24    4810  1738.8  4900.4 1738.44
  5027.1 1737.49  5027.4 1736.99  5030.9 1736.99  5031.1 1737.49  5069.6 1738.43
  5129.9 1738.89  5191.2 1739.83  5211.5 1740.74  5302.7 1742.23  5312.8 1742.81
  5347.6 1742.74  5393.9 1744.32  5545.8 1747.01    5598 1748.63  5731.9 1752.13
#Mann= 8 ,-1 , 0
  3875.6     .07       0  3966.4    .035       0  4692.6     .07       0
  4900.4    .035       0  5027.1    .035       0  5031.1    .035       0
  5129.9     .07       0    5598    .035       0
Bank Sta=5027.1,5031.1
XS Rating Curve= 0 ,0
Exp/Cntr=0.3,0.1

Type RM Length L Ch R = 1 ,1516    ,72,72,72
BEGIN DESCRIPTION:
Mapping XS e1994443
END DESCRIPTION:
XS GIS Cut Line= 6
      1541696.67      6859413.22      1541616.81      6860572.93
      1541786.94      6860600.71      1541970.97      6860569.46
      1542137.64      6860472.23      1542671.14      6860285.16
#Sta/Elev= 30
  3829.2 1747.39  3928.3 1746.24  4145.2 1744.04  4426.3 1744.88  4647.2 1741.93
  4696.4 1739.22  4723.5 1738.29  4723.8 1737.79  4727.5 1738.29    4747 1738.64
  4784.5 1743.52  4808.1  1741.9  4848.4 1743.34  4970.5  1742.3  4997.6 1741.18
  5055.1 1743.08  5337.7 1741.88  5398.3 1743.36  5413.5 1741.69  5429.2 1743.11
    5435 1741.15  5450.7 1743.45  5472.2 1741.36    5488 1743.29  5525.2 1743.32
    5531 1741.61    5583 1743.03  5608.7 1741.37    6116 1750.86  6117.2 1750.87
#Mann= 9 ,-1 , 0
  3829.2     .07       0  3928.3    .035       0  4696.4     .07       0
  4723.5     .07       0  4727.5     .07       0    4747    .035       0
  4970.5     .07       0  5055.1    .035       0    6116     .07       0
Bank Sta=4723.5,4727.5
XS Rating Curve= 0 ,0
Exp/Cntr=0.3,0.1

Type RM Length L Ch R = 1 ,1444    ,904,904,904
BEGIN DESCRIPTION:
Mapping XS 0db0a6e9
END DESCRIPTION:
XS GIS Cut Line= 5
      1541683.51      6859388.57      1541532.46      6860578.71
      1541579.33      6860638.61      1541735.58       6860695.9
       1542704.3      6860550.07
#Sta/Elev= 30
  3741.7 1747.26  3850.2 1745.95    4104 1743.68  4345.9 1744.51  4488.2 1740.71
    4608 1740.13  4648.3 1737.77  4677.9  1738.8  4776.2 1740.45  4970.4 1736.43
  5023.5 1736.12  5052.7 1734.71  5052.9 1734.21  5056.7 1734.71  5066.1 1735.67
  5125.7 1736.12  5254.1 1737.31  5284.4 1736.44  5324.9  1737.6  5333.8 1736.31
  5385.5 1737.32  5402.8 1739.11  5407.9 1737.52  5415.9  1738.8  5471.8 1739.99
  5759.8 1742.47  5827.3 1743.46  6013.5 1746.51  6072.4 1749.75  6163.5 1752.06
#Mann= 10 ,-1 , 0
  3741.7     .07       0  3850.2    .035       0  4677.9     .07       0
  4776.2    .035       0  4970.4     .07       0  5052.7     .07       0
  5056.7     .07       0  5125.7    .035       0  5759.8     .07       0
  5827.3    .035       0
Bank Sta=5052.7,5056.7
XS Rating Curve= 0 ,0
Exp/Cntr=0.3,0.1

Type RM Length L Ch R = 1 ,540     ,0,0,0
BEGIN DESCRIPTION:
BULL WAGON CREEK TRIBUTARY 2_1 1.0
END DESCRIPTION:
XS GIS Cut Line= 3
      1541610.87      6859270.16      1540947.25       6860595.5
        1541814.      6861376.94
#Sta/Elev= 30
  3517.8 1747.79  3623.1 1745.74    3783 1743.08  3996.3 1741.64  4118.2 1739.11
  4309.4 1739.49  4436.8 1738.26  4475.9 1739.72  4579.5 1739.16    4652 1736.67
  4674.5 1735.59  4886.3    1732  4890.7 1732.05  4900.1 1732.59  4913.3 1730.92
  4980.4 1731.65  4995.5 1729.86  5012.2 1729.81  5012.4 1729.31  5016.2 1729.81
  5064.2 1732.68  5170.4 1733.35  5226.4 1732.05  5276.5 1732.48  5297.4 1734.49
  5556.3 1736.54  5572.2 1736.73  5984.2 1742.76  6104.6 1748.01    6167 1748.81
#Mann= 12 ,-1 , 0
  3517.8     .07       0  3623.1    .035       0  4579.5     .07       0
    4652    .035       0  4674.5     .07       0  4886.3    .035       0
  4890.7     .07       0  4900.1    .035       0  5012.2    .035       0
  5016.2    .035       0  5556.3     .07       0  5572.2    .035       0
Bank Sta=5012.2,5016.2
XS Rating Curve= 0 ,0
Exp/Cntr=0.3,0.1

Chan Stop Cuts=-1
Use User Specified Reach Order=0
Composite Channel Slope=5