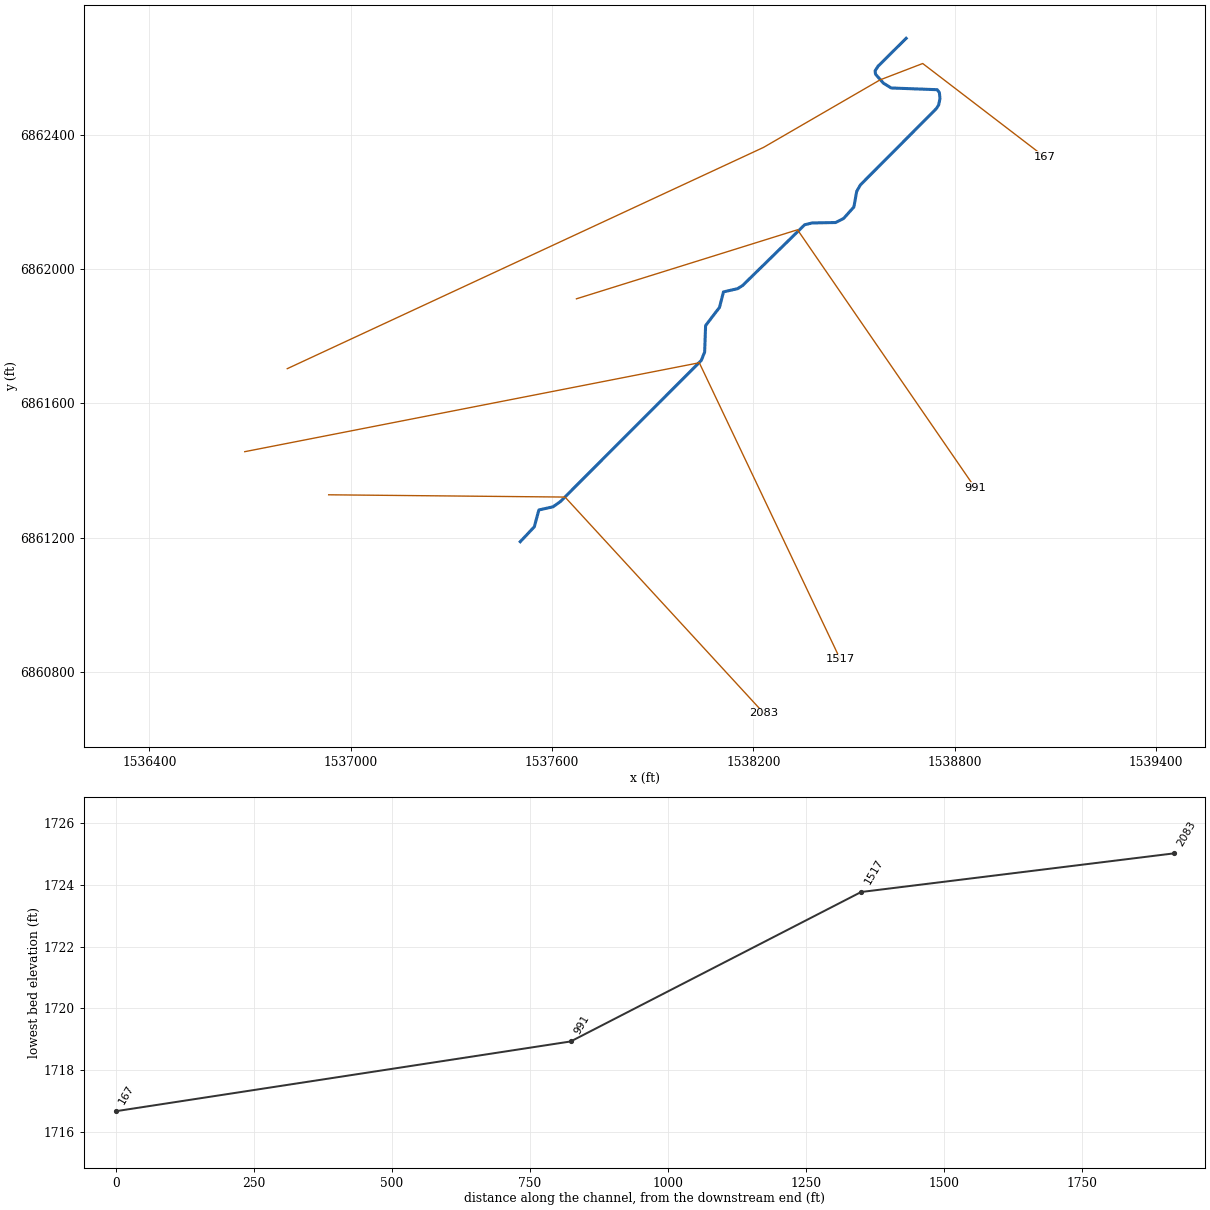
--- BULL WAGON CREEK TRIBUTARY 3.prj (project) ---

Proj Title=BULL WAGON CREEK TRIBUTARY 3 Base Level Engineering
Current Plan=p01
Default Exp/Contr=0.3,0.1
English Units
Geom File=g01
Flow File=f01
Plan File=p01
BEGIN DESCRIPTION:
BULL WAGON CREEK TRIBUTARY 3
END DESCRIPTION:

--- BULL WAGON CREEK TRIBUTARY 3.p01 (plan) ---

Plan Title=Multiple Run
Short Identifier=Multiple
Geom File=g01
Flow File=f01
Subcritical Flow
K Sum by GR= 0
Std Step Tol= 0.01
Critical Tol= 0.01
Num of Std Step Trials= 20
Max Error Tol= 0.3
Flow Tol Ratio= 0.001
Split Flow NTrial= 30
Split Flow Tol= 0.02
Split Flow Ratio= 0.02
Log Output Level= 0
Friction Slope Method= 1
Unsteady Friction Slope Method= 2
Unsteady Bridges Friction Slope Method= 1
Parabolic Critical Depth
Global Vel Dist=  1 , 1 , 1
Global Log Level= 0
CheckData=True
Encroach Param= -1, 0, 0, 0
BEGIN DESCRIPTION:
Multiple Run
END DESCRIPTION:

--- BULL WAGON CREEK TRIBUTARY 3.f01 (steady flow) ---

Flow Title=Multiple
Number of Profiles=7
Profile Names=10-year,25-year,50-year,1pct_min,100-year,1pct_plu,500-year
River Rch & RM= BULL WAGON CREEK,Reach-1,2083
     176     238     289     174     348     694     512
Boundary for River Rch & Prof#=BULL WAGON CREEK,Reach-1,1
Up Type=0
Dn Type=3
Dn Slope=0.005
Boundary for River Rch & Prof#=BULL WAGON CREEK,Reach-1,2
Up Type=0
Dn Type=3
Dn Slope=0.005
Boundary for River Rch & Prof#=BULL WAGON CREEK,Reach-1,3
Up Type=0
Dn Type=3
Dn Slope=0.005
Boundary for River Rch & Prof#=BULL WAGON CREEK,Reach-1,4
Up Type=0
Dn Type=3
Dn Slope=0.005
Boundary for River Rch & Prof#=BULL WAGON CREEK,Reach-1,5
Up Type=0
Dn Type=3
Dn Slope=0.005
Boundary for River Rch & Prof#=BULL WAGON CREEK,Reach-1,6
Up Type=0
Dn Type=3
Dn Slope=0.005
Boundary for River Rch & Prof#=BULL WAGON CREEK,Reach-1,7
Up Type=0
Dn Type=3
Dn Slope=0.005

--- BULL WAGON CREEK TRIBUTARY 3.g01 (geometry) ---

Geom Title=Existing Conditions

River Reach=BULL WAGON CREEK,Reach-1
Reach XY= 30
      1537505.00      6861188.00      1537546.88      6861232.30
      1537560.44      6861282.49      1537603.00      6861292.10
      1537624.92      6861307.85      1538044.48      6861728.21
      1538054.48      6861753.22      1538057.32      6861832.06
      1538098.72      6861886.16      1538110.59      6861932.39
      1538152.99      6861942.13      1538167.98      6861951.73
      1538352.58      6862132.47      1538375.06      6862137.86
      1538444.67      6862139.10      1538468.65      6862151.26
      1538499.26      6862185.43      1538507.55      6862231.91
      1538518.64      6862251.20      1538744.95      6862478.63
      1538752.09      6862490.09      1538755.65      6862508.59
      1538754.02      6862526.31      1538747.48      6862534.92
      1538610.46      6862540.07      1538587.31      6862554.42
      1538563.76      6862580.99      1538562.37      6862591.11
      1538570.94      6862604.56      1538655.00      6862688.00

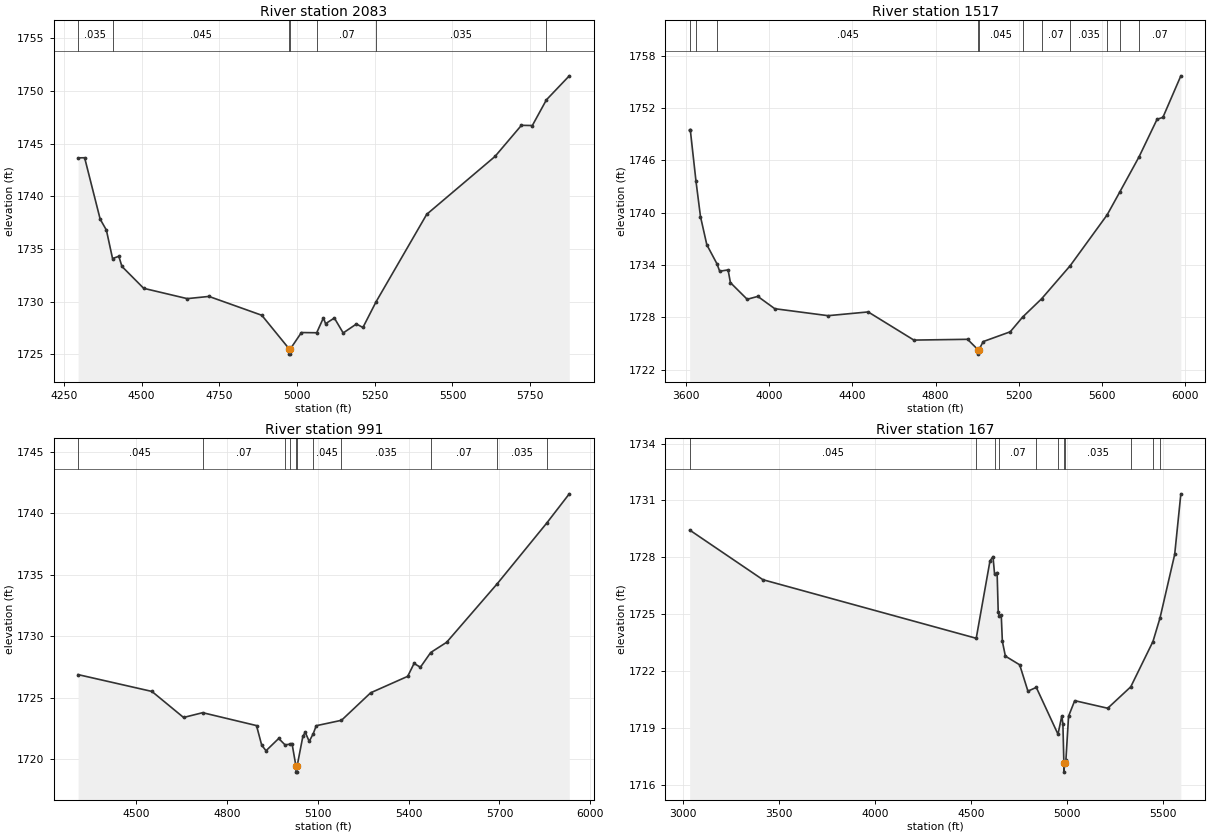
Type RM Length L Ch R = 1,2083,566,566,566
BEGIN DESCRIPTION:
BULL WAGON CREEK TRIBUTARY 3 1.0
END DESCRIPTION:
XS GIS Cut Line= 3
      1536934.04      6861327.75      1537638.41      6861320.99
      1538231.30      6860676.39
#Sta/Elev= 30
  4295.6 1743.66  4316.6 1743.67  4366.6 1737.84  4386.6 1736.80  4406.4 1734.10
  4426.6 1734.31  4436.6 1733.35  4506.6 1731.27  4646.6 1730.29  4716.6 1730.50
  4886.6 1728.71  4974.6 1725.52  4974.8 1725.02  4978.3 1725.02  4978.6 1725.52
  5014.0 1727.07  5063.2 1727.05  5084.9 1728.47  5091.7 1727.91  5120.0 1728.45
  5148.4 1727.03  5190.9 1727.88  5211.9 1727.55  5254.2 1729.99  5417.2 1738.30
  5636.7 1743.79  5721.8 1746.75  5756.9 1746.73  5802.2 1749.17  5875.8 1751.45
#Mann=7,-1,0
  4295.6   0.035       0  4406.4   0.045       0  4974.6   0.045       0
  4978.6   0.045       0  5063.2    0.07       0  5254.2   0.035       0
  5802.2    0.07       0
Bank Sta=4974.6,4978.6
Exp/Cntr=0.3,0.1

Type RM Length L Ch R = 1,1517,526,526,526
BEGIN DESCRIPTION:
BULL WAGON CREEK TRIBUTARY 3 0.0
END DESCRIPTION:
XS GIS Cut Line= 3
      1536684.03      6861456.23      1538038.54      6861721.25
      1538458.32      6860838.14
#Sta/Elev= 30
  3619.8 1749.50  3622.8 1749.50  3650.2 1743.59  3671.7 1739.55  3702.2 1736.31
  3750.6 1734.14  3763.9 1733.28  3804.2 1733.43  3815.4 1731.97  3895.9 1730.06
  3946.9 1730.39  4028.4 1728.98  4284.1 1728.18  4476.7 1728.61  4696.2 1725.38
  4953.8 1725.47  5004.3 1724.27  5004.5 1723.77  5008.3 1724.27  5029.0 1725.21
  5158.6 1726.33  5219.0 1728.04  5309.4 1730.12  5446.8 1733.92  5624.1 1739.75
  5683.8 1742.33  5776.9 1746.39  5863.5 1750.70  5891.7 1750.93  5977.8 1755.69
#Mann=11,-1,0
  3619.8    0.07       0  3650.2   0.035       0  3750.6   0.045       0
  5004.3   0.045       0  5008.3   0.045       0  5219.0   0.035       0
  5309.4    0.07       0  5446.8   0.035       0  5624.1    0.07       0
  5683.8   0.035       0  5776.9    0.07       0
Bank Sta=5004.3,5008.3
Exp/Cntr=0.3,0.1

Type RM Length L Ch R = 1,991,824,824,824
BEGIN DESCRIPTION:
Mapping XS e0bfd604
END DESCRIPTION:
XS GIS Cut Line= 3
      1537672.43      6861911.79      1538331.24      6862117.51
      1538859.87      6861349.30
#Sta/Elev= 30
  4307.9 1726.87  4551.8 1725.50  4656.3 1723.38  4719.5 1723.77  4897.3 1722.72
  4914.4 1721.13  4928.7 1720.67  4970.6 1721.67  4991.6 1721.15  5006.5 1721.20
  5014.6 1721.26  5027.5 1719.43  5027.8 1718.93  5031.3 1718.93  5031.5 1719.43
  5050.5 1721.85  5058.2 1722.18  5071.4 1721.43  5084.9 1722.07  5094.6 1722.71
  5178.0 1723.15  5274.4 1725.39  5396.8 1726.73  5417.8 1727.78  5438.7 1727.47
  5472.8 1728.67  5525.3 1729.50  5692.6 1734.27  5855.8 1739.20  5930.6 1741.59
#Mann=11,-1,0
  4307.9   0.045       0  4719.5    0.07       0  4991.6   0.045       0
  5006.5    0.07       0  5027.5   0.045       0  5031.5    0.07       0
  5084.9   0.045       0  5178.0   0.035       0  5472.8    0.07       0
  5692.6   0.035       0  5855.8    0.07       0
Bank Sta=5027.5,5031.5
Exp/Cntr=0.3,0.1

Type RM Length L Ch R = 1,167,0,0,0
BEGIN DESCRIPTION:
BULL WAGON CREEK TRIBUTARY 3 2.0
END DESCRIPTION:
XS GIS Cut Line= 5
      1536810.74      6861703.62      1538230.00      6862363.00
      1538577.18      6862564.16      1538704.28      6862613.00
      1539067.45      6862334.87
#Sta/Elev= 30
  3033.8 1729.44  3415.5 1726.82  4527.2 1723.73  4598.8 1727.81  4614.5 1728.04
  4623.0 1727.10  4636.0 1727.20  4641.8 1725.13  4647.1 1724.89  4657.6 1724.95
  4663.4 1723.57  4679.1 1722.79  4753.7 1722.33  4796.7 1720.94  4840.2 1721.14
  4953.3 1718.67  4973.2 1719.64  4978.9 1719.21  4983.9 1717.17  4984.2 1716.67
  4987.9 1717.17  4994.7 1717.33  5008.4 1719.62  5040.5 1720.44  5212.4 1720.04
  5332.5 1721.17  5448.2 1723.56  5484.9 1724.80  5561.4 1728.15  5593.6 1731.35
#Mann=11,-1,0
  3033.8   0.045       0  4527.2    0.07       0  4623.0   0.045       0
  4647.1    0.07       0  4840.2   0.045       0  4953.3   0.035       0
  4983.9   0.035       0  4987.9   0.035       0  5332.5   0.045       0
  5448.2   0.035       0  5484.9   0.045       0
Bank Sta=4983.9,4987.9
Exp/Cntr=0.3,0.1

Chan Stop Cuts=-1