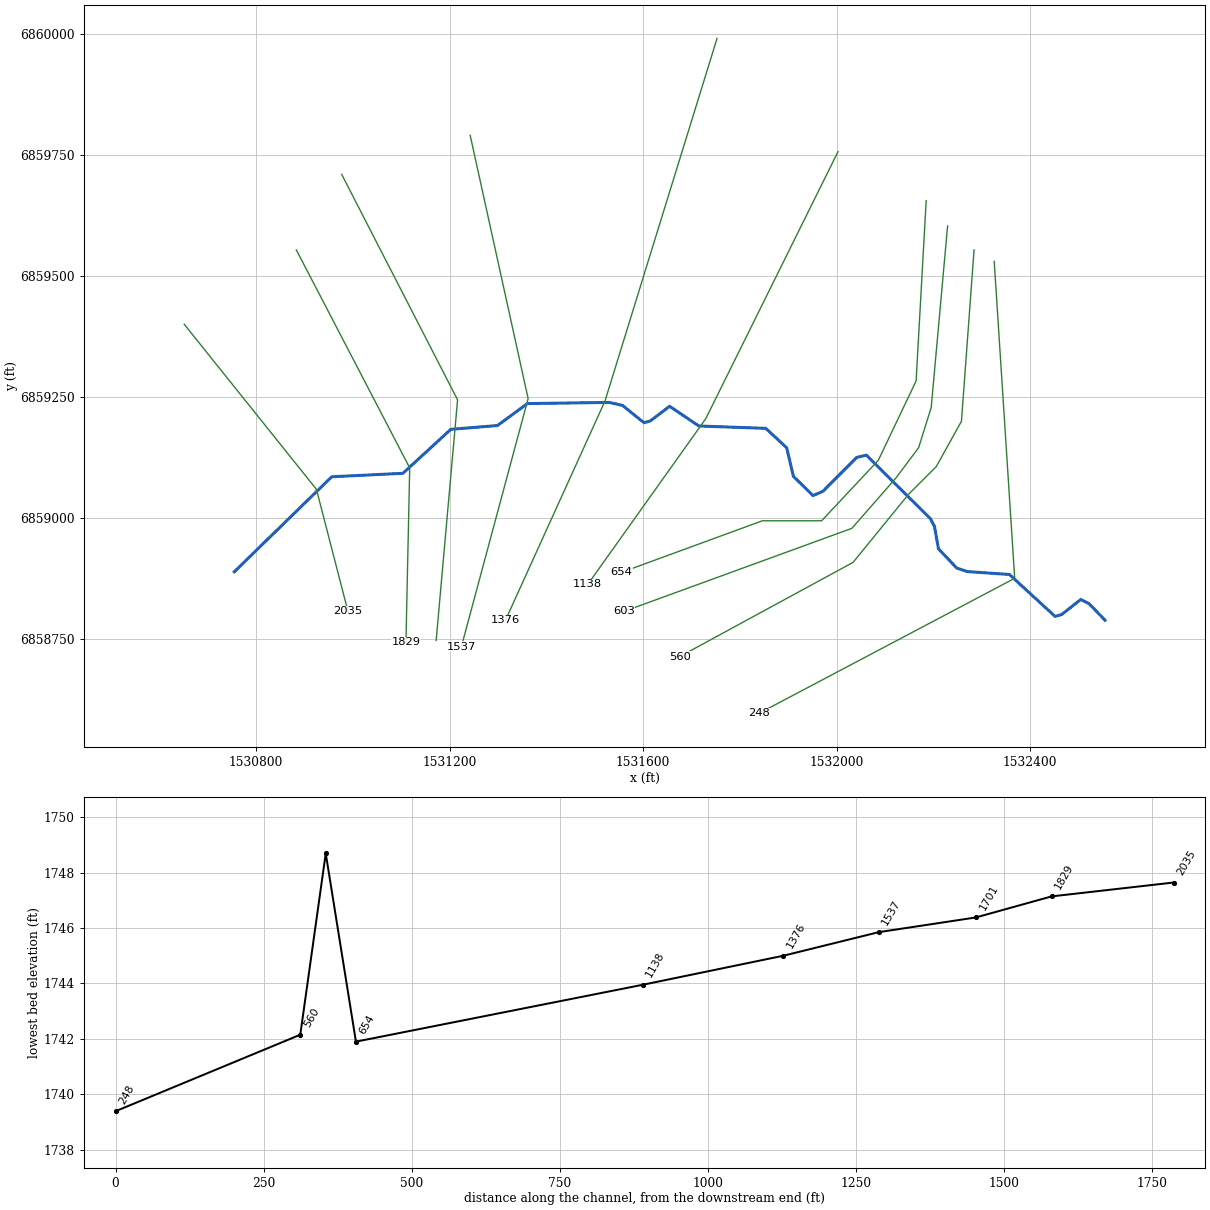
--- BULL WAGON CREEK TRIBUTARY 4.prj (project) ---

Proj Title=BULL WAGON CREEK TRIBUTARY 4 Base Level Engineering
Current Plan=p01
Default Exp/Contr=0.3,0.1
English Units
Geom File=g01
Flow File=f01
Plan File=p01
BEGIN DESCRIPTION:
BULL WAGON CREEK TRIBUTARY 4
END DESCRIPTION:

--- BULL WAGON CREEK TRIBUTARY 4.p01 (plan) ---

Plan Title=Multiple Run
Short Identifier=Multiple
Geom File=g01
Flow File=f01
Subcritical Flow
K Sum by GR= 0
Std Step Tol= 0.01
Critical Tol= 0.01
Num of Std Step Trials= 20
Max Error Tol= 0.3
Flow Tol Ratio= 0.001
Split Flow NTrial= 30
Split Flow Tol= 0.02
Split Flow Ratio= 0.02
Log Output Level= 0
Friction Slope Method= 1
Unsteady Friction Slope Method= 2
Unsteady Bridges Friction Slope Method= 1
Parabolic Critical Depth
Global Vel Dist=  1 , 1 , 1
Global Log Level= 0
CheckData=True
Encroach Param= -1, 0, 0, 0
BEGIN DESCRIPTION:
Multiple Run
END DESCRIPTION:

--- BULL WAGON CREEK TRIBUTARY 4.f01 (steady flow) ---

Flow Title=Multiple
Number of Profiles=7
Profile Names=10-year,25-year,50-year,1pct_min,100-year,1pct_plu,500-year
River Rch & RM= BULL WAGON CREEK,Reach-1,2035
      75      96     111      65     129     258     176
River Rch & RM= BULL WAGON CREEK,Reach-1,654
      82     106     124      73     145     289     199
Boundary for River Rch & Prof#=BULL WAGON CREEK,Reach-1,1
Up Type=0
Dn Type=3
Dn Slope=0.005
Boundary for River Rch & Prof#=BULL WAGON CREEK,Reach-1,2
Up Type=0
Dn Type=3
Dn Slope=0.005
Boundary for River Rch & Prof#=BULL WAGON CREEK,Reach-1,3
Up Type=0
Dn Type=3
Dn Slope=0.005
Boundary for River Rch & Prof#=BULL WAGON CREEK,Reach-1,4
Up Type=0
Dn Type=3
Dn Slope=0.005
Boundary for River Rch & Prof#=BULL WAGON CREEK,Reach-1,5
Up Type=0
Dn Type=3
Dn Slope=0.005
Boundary for River Rch & Prof#=BULL WAGON CREEK,Reach-1,6
Up Type=0
Dn Type=3
Dn Slope=0.005
Boundary for River Rch & Prof#=BULL WAGON CREEK,Reach-1,7
Up Type=0
Dn Type=3
Dn Slope=0.005

--- BULL WAGON CREEK TRIBUTARY 4.g01 (geometry) ---

Geom Title=Existing Conditions

River Reach=BULL WAGON CREEK,Reach-1
Reach XY= 30
      1530755.00      6858888.00      1530956.47      6859084.46
      1531103.53      6859091.56      1531202.58      6859182.46
      1531299.02      6859190.36      1531360.94      6859235.74
      1531530.12      6859238.12      1531557.45      6859232.00
      1531601.78      6859196.28      1531615.05      6859199.83
      1531654.90      6859230.21      1531715.44      6859189.39
      1531853.75      6859184.54      1531896.98      6859144.34
      1531910.87      6859085.16      1531951.42      6859045.50
      1531971.58      6859054.23      1532041.67      6859124.53
      1532061.67      6859129.03      1532194.21      6858997.66
      1532202.45      6858981.91      1532210.74      6858935.43
      1532248.55      6858895.75      1532270.09      6858888.47
      1532357.42      6858882.45      1532451.67      6858795.87
      1532465.00      6858799.42      1532505.00      6858830.76
      1532521.78      6858822.31      1532555.00      6858788.00

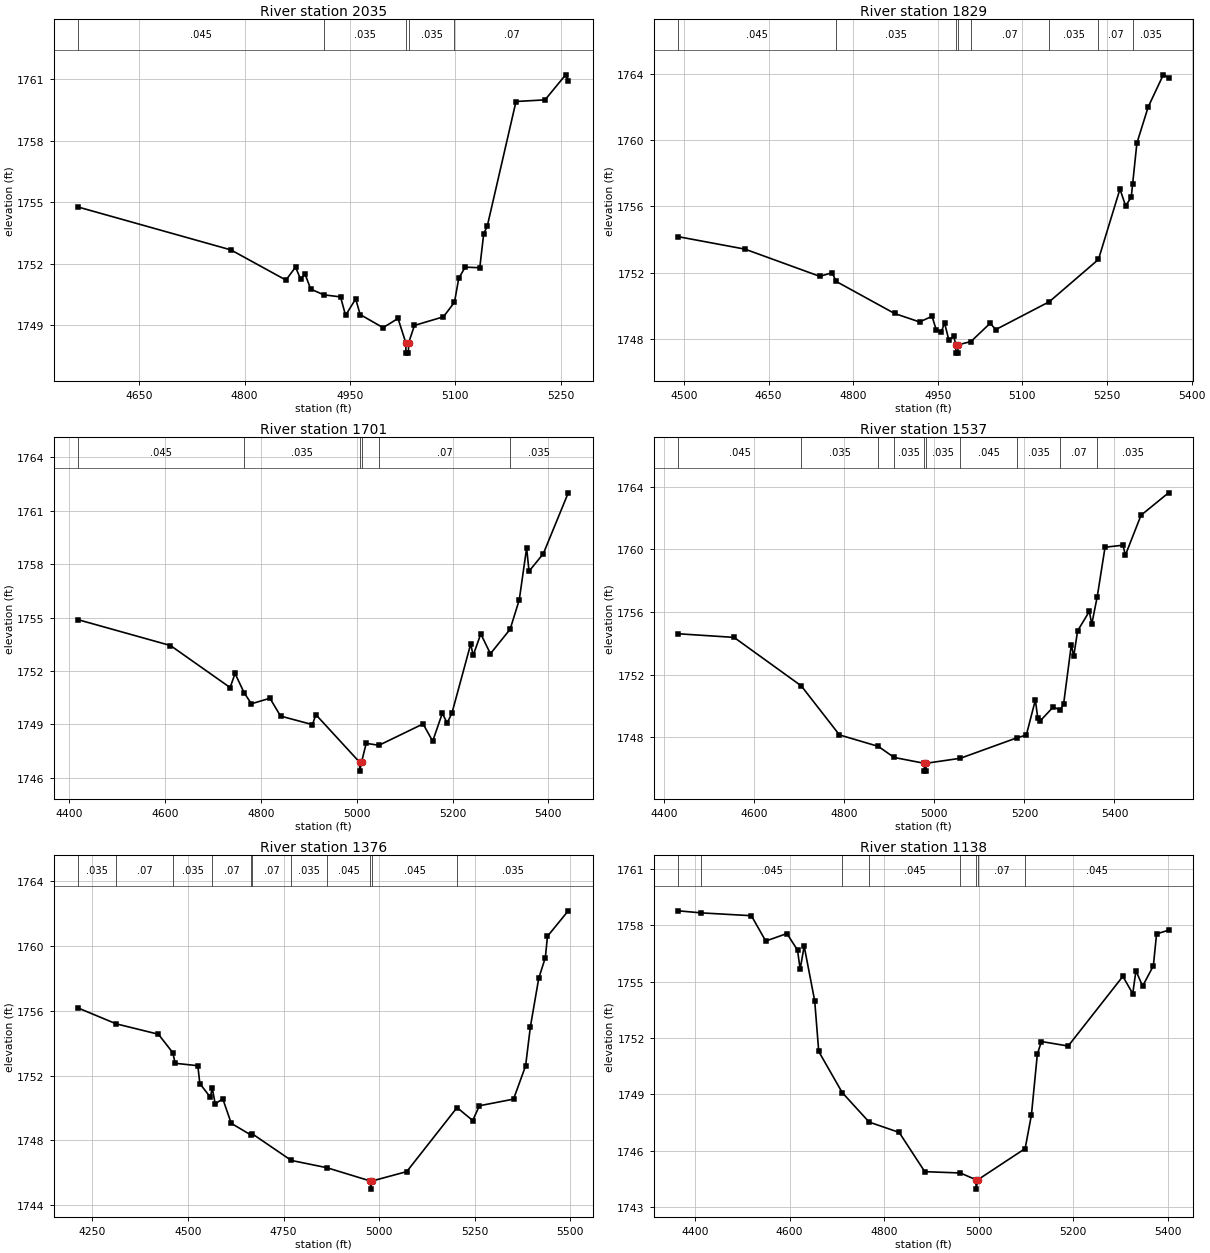
Type RM Length L Ch R = 1,2035,206,206,206
BEGIN DESCRIPTION:
BULL WAGON CREEK TRIBUTARY 4 2.0
END DESCRIPTION:
XS GIS Cut Line= 3
      1530651.47      6859399.72      1530924.80      6859058.49
      1530990.02      6858805.98
#Sta/Elev= 30
  4562.8 1754.76  4780.4 1752.67  4858.8 1751.20  4872.5 1751.83  4879.6 1751.25
  4886.0 1751.50  4894.0 1750.76  4912.8 1750.48  4936.6 1750.38  4943.7 1749.48
  4958.1 1750.28  4964.5 1749.52  4997.1 1748.88  5018.4 1749.33  5029.5 1748.14
  5029.7 1747.64  5033.2 1747.64  5033.5 1748.14  5041.8 1748.99  5083.1 1749.41
  5098.8 1750.12  5104.9 1751.29  5114.1 1751.83  5134.8 1751.80  5140.4 1753.45
  5145.5 1753.83  5186.4 1759.90  5227.7 1759.98  5257.1 1761.20  5260.8 1760.92
#Mann=5,-1,0
  4562.8   0.045       0  4912.8   0.035       0  5029.5   0.035       0
  5033.5   0.035       0  5098.8    0.07       0
Bank Sta=5029.5,5033.5
Exp/Cntr=0.3,0.1

Type RM Length L Ch R = 1,1829,128,128,128
BEGIN DESCRIPTION:
Mapping XS f836a658
END DESCRIPTION:
XS GIS Cut Line= 3
      1530883.24      6859553.39      1531117.63      6859102.83
      1531109.84      6858741.89
#Sta/Elev= 30
  4490.1 1754.16  4608.2 1753.41  4740.8 1751.77  4762.9 1751.99  4769.5 1751.47
  4873.4 1749.53  4917.7 1749.02  4939.8 1749.36  4947.1 1748.56  4956.2 1748.40
  4961.9 1748.97  4969.6 1747.93  4978.3 1748.15  4982.0 1747.64  4982.2 1747.14
  4985.7 1747.14  4986.0 1747.64  5008.8 1747.84  5042.8 1748.94  5052.8 1748.56
  5147.7 1750.24  5234.8 1752.79  5272.9 1757.03  5282.9 1756.02  5292.9 1756.54
  5295.3 1757.32  5302.9 1759.80  5322.9 1761.98  5349.7 1763.92  5359.0 1763.75
#Mann=8,-1,0
  4490.1   0.045       0  4769.5   0.035       0  4982.0   0.035       0
  4986.0   0.035       0  5008.8    0.07       0  5147.7   0.035       0
  5234.8    0.07       0  5295.3   0.035       0
Bank Sta=4982,4986
Exp/Cntr=0.3,0.1

Type RM Length L Ch R = 1,1701,164,164,164
BEGIN DESCRIPTION:
Mapping XS a7589c67
END DESCRIPTION:
XS GIS Cut Line= 3
      1530977.02      6859709.58      1531216.59      6859243.46
      1531172.32      6858746.10
#Sta/Elev= 30
  4418.2 1754.88  4611.1 1753.43  4735.7 1751.07  4746.0 1751.86  4764.9 1750.78
  4780.1 1750.16  4818.8 1750.47  4841.0 1749.47  4907.5 1748.99  4914.7 1749.55
  5006.0 1746.88  5006.2 1746.38  5010.0 1746.88  5019.8 1747.94  5046.4 1747.83
  5138.5 1749.03  5158.6 1748.06  5178.7 1749.63  5188.7 1749.08  5198.7 1749.63
  5238.0 1753.52  5243.0 1752.87  5259.0 1754.08  5279.1 1752.97  5320.2 1754.34
  5339.3 1755.99  5354.7 1758.90  5359.7 1757.60  5389.5 1758.58  5441.6 1762.00
#Mann=6,-1,0
  4418.2   0.045       0  4764.9   0.035       0  5006.0   0.035       0
  5010.0   0.035       0  5046.4    0.07       0  5320.2   0.035       0
Bank Sta=5006,5010
Exp/Cntr=0.3,0.1

Type RM Length L Ch R = 1,1537,161,161,161
BEGIN DESCRIPTION:
Mapping XS c035c8c5
END DESCRIPTION:
XS GIS Cut Line= 3
      1531242.63      6859790.33      1531362.42      6859246.06
      1531224.39      6858733.00
#Sta/Elev= 30
  4431.5 1754.61  4555.2 1754.38  4704.4 1751.29  4789.3 1748.16  4875.4 1747.43
  4910.9 1746.72  4977.6 1746.35  4977.9 1745.85  4981.4 1745.85  4981.6 1746.35
  5057.9 1746.67  5183.0 1747.97  5204.3 1748.15  5224.4 1750.39  5229.6 1749.25
  5235.3 1749.06  5264.4 1749.95  5279.7 1749.73  5287.1 1750.14  5304.3 1753.92
  5309.5 1753.17  5318.2 1754.80  5344.3 1756.04  5349.5 1755.21  5361.8 1756.98
  5379.1 1760.13  5419.0 1760.26  5424.2 1759.62  5459.0 1762.17  5520.1 1763.60
#Mann=10,-1,0
  4431.5   0.045       0  4704.4   0.035       0  4875.4   0.045       0
  4910.9   0.035       0  4977.6   0.035       0  4981.6   0.035       0
  5057.9   0.045       0  5183.0   0.035       0  5279.7    0.07       0
  5361.8   0.035       0
Bank Sta=4977.6,4981.6
Exp/Cntr=0.3,0.1

Type RM Length L Ch R = 1,1376,238,238,238
BEGIN DESCRIPTION:
Mapping XS a019a6e0
END DESCRIPTION:
XS GIS Cut Line= 3
      1531753.03      6859990.81      1531521.27      6859240.86
      1531315.54      6858787.72
#Sta/Elev= 30
  4212.3 1756.17  4312.3 1755.19  4422.6 1754.55  4460.2 1753.41  4466.4 1752.76
  4525.7 1752.61  4530.9 1751.51  4558.3 1750.67  4563.5 1751.22  4571.1 1750.26
  4591.0 1750.57  4613.0 1749.06  4664.5 1748.34  4666.9 1748.43  4770.2 1746.77
  4863.5 1746.32  4977.3 1745.50  4977.6 1745.00  4981.3 1745.50  5072.3 1746.08
  5204.0 1750.03  5244.9 1749.23  5262.4 1750.14  5351.8 1750.55  5383.3 1752.60
  5395.8 1755.01  5417.7 1758.00  5435.0 1759.28  5440.5 1760.59  5494.9 1762.16
#Mann=11,-1,0
  4212.3   0.035       0  4312.3    0.07       0  4460.2   0.035       0
  4563.5    0.07       0  4664.5   0.035       0  4666.9    0.07       0
  4770.2   0.035       0  4863.5   0.045       0  4977.3   0.045       0
  4981.3   0.045       0  5204.0   0.035       0
Bank Sta=4977.3,4981.3
Exp/Cntr=0.3,0.1

Type RM Length L Ch R = 1,1138,484,484,484
BEGIN DESCRIPTION:
Mapping XS 00d001f3
END DESCRIPTION:
XS GIS Cut Line= 3
      1532003.05      6859756.48      1531729.61      6859204.40
      1531485.68      6858861.86
#Sta/Elev= 30
  4364.9 1758.77  4413.7 1758.66  4519.4 1758.51  4549.7 1757.16  4594.5 1757.56
  4616.9 1756.68  4622.5 1755.66  4631.0 1756.89  4653.3 1753.97  4661.8 1751.28
  4711.5 1749.09  4768.4 1747.52  4831.9 1746.97  4886.0 1744.88  4961.3 1744.81
  4994.3 1744.45  4994.5 1743.95  4998.3 1744.45  5098.3 1746.11  5111.6 1747.91
  5124.1 1751.14  5132.7 1751.81  5189.3 1751.57  5304.9 1755.28  5325.8 1754.36
  5332.6 1755.58  5346.7 1754.76  5369.4 1755.84  5376.2 1757.54  5401.5 1757.74
#Mann=8,-1,0
  4364.9    0.07       0  4413.7   0.045       0  4711.5   0.035       0
  4768.4   0.045       0  4961.3    0.07       0  4994.3    0.07       0
  4998.3    0.07       0  5098.3   0.045       0
Bank Sta=4994.3,4998.3
Exp/Cntr=0.3,0.1

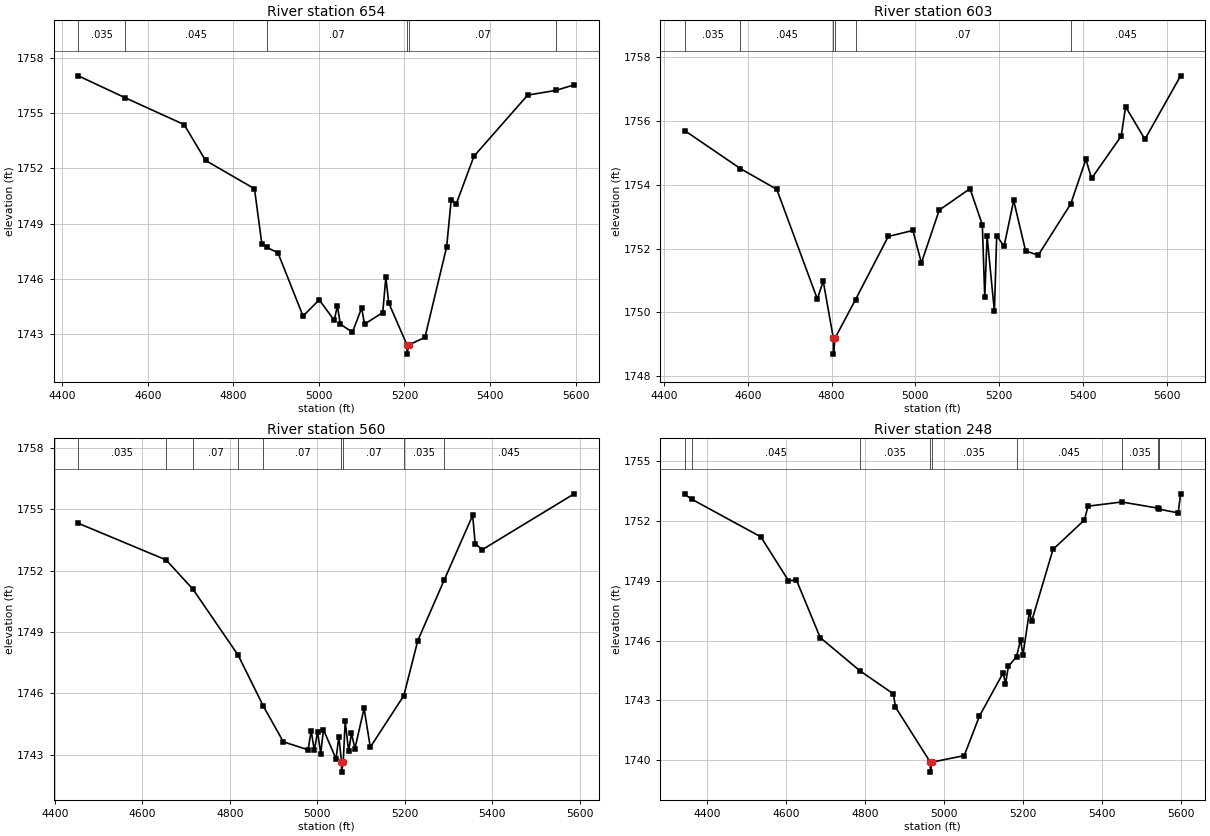
Type RM Length L Ch R = 1,654,51,51,51
BEGIN DESCRIPTION:
Mapping XS e51184a1
END DESCRIPTION:
XS GIS Cut Line= 6
      1532185.34      6859654.95      1532164.50      6859282.52
      1532086.38      6859118.46      1531969.19      6858993.46
      1531846.80      6858993.46      1531555.08      6858886.67
#Sta/Elev= 30
  4437.6 1757.03  4545.9 1755.85  4684.9 1754.38  4735.0 1752.43  4849.4 1750.89
  4866.5 1747.91  4877.7 1747.71  4904.2 1747.41  4962.9 1743.97  5000.7 1744.85
  5035.9 1743.74  5043.2 1744.53  5050.1 1743.53  5078.4 1743.09  5099.9 1744.41
  5106.7 1743.53  5149.2 1744.16  5156.5 1746.08  5163.1 1744.69  5205.9 1742.40
  5206.1 1741.90  5209.9 1742.40  5247.9 1742.81  5298.6 1747.73  5309.3 1750.30
  5320.9 1750.06  5362.5 1752.66  5488.0 1755.98  5554.2 1756.24  5596.7 1756.54
#Mann=6,-1,0
  4437.6   0.035       0  4545.9   0.045       0  4877.7    0.07       0
  5205.9    0.07       0  5209.9    0.07       0  5554.2   0.045       0
Bank Sta=5205.9,5209.9
Exp/Cntr=0.3,0.1

Type RM Length L Ch R = 1,603,43,43,43
BEGIN DESCRIPTION:
Mapping XS 0d73195f
END DESCRIPTION:
XS GIS Cut Line= 6
      1532229.61      6859602.81      1532195.75      6859227.83
      1532169.71      6859144.50      1532122.84      6859082.00
      1532031.69      6858977.83      1531560.36      6858805.97
#Sta/Elev= 30
  4449.9 1755.70  4582.5 1754.51  4669.3 1753.86  4766.0 1750.42  4780.1 1750.98
  4804.2 1749.19  4804.4 1748.69  4808.2 1749.19  4857.1 1750.40  4935.2 1752.38
  4994.0 1752.57  5014.2 1751.55  5056.9 1753.21  5130.2 1753.88  5159.6 1752.75
  5165.4 1750.47  5170.9 1752.39  5188.4 1750.03  5193.9 1752.41  5211.4 1752.07
  5234.4 1753.51  5262.8 1751.93  5292.8 1751.79  5370.4 1753.40  5406.7 1754.80
  5420.1 1754.20  5490.9 1755.53  5501.4 1756.45  5547.4 1755.43  5632.6 1757.42
#Mann=6,-1,0
  4449.9   0.035       0  4582.5   0.045       0  4804.2    0.07       0
  4808.2   0.045       0  4857.1    0.07       0  5370.4   0.045       0
Bank Sta=4804.2,4808.2
Exp/Cntr=0.3,0.1

Type RM Length L Ch R = 1,560,312,312,312
BEGIN DESCRIPTION:
Mapping XS f6e2efa4
END DESCRIPTION:
XS GIS Cut Line= 6
      1532284.30      6859553.38      1532258.25      6859199.19
      1532206.17      6859105.44      1532148.88      6859048.15
      1532034.30      6858907.52      1531675.65      6858712.61
#Sta/Elev= 30
  4453.9 1754.31  4654.4 1752.52  4716.1 1751.08  4819.2 1747.86  4876.8 1745.37
  4922.4 1743.63  4978.9 1743.24  4986.0 1744.17  4993.1 1743.21  5000.6 1744.13
  5007.7 1743.06  5014.1 1744.22  5042.8 1742.80  5049.3 1743.89  5055.2 1742.65
  5055.5 1742.15  5059.2 1742.65  5063.7 1744.63  5071.6 1743.16  5078.0 1744.05
  5085.9 1743.30  5106.8 1745.26  5121.1 1743.37  5197.7 1745.89  5229.6 1748.58
  5290.2 1751.55  5355.0 1754.70  5360.7 1753.32  5376.9 1753.02  5586.9 1755.75
#Mann=9,-1,0
  4453.9   0.035       0  4654.4   0.045       0  4716.1    0.07       0
  4819.2   0.045       0  4876.8    0.07       0  5055.2    0.07       0
  5059.2    0.07       0  5197.7   0.035       0  5290.2   0.045       0
Bank Sta=5055.2,5059.2
Exp/Cntr=0.3,0.1

Type RM Length L Ch R = 1,248,0,0,0
BEGIN DESCRIPTION:
BULL WAGON CREEK TRIBUTARY 4 1.0
END DESCRIPTION:
XS GIS Cut Line= 3
      1532325.97      6859529.87      1532368.30      6858874.54
      1531839.50      6858595.30
#Sta/Elev= 30
  4343.3 1753.34  4361.7 1753.09  4535.6 1751.21  4605.7 1749.01  4625.8 1749.04
  4685.9 1746.15  4787.1 1744.47  4871.2 1743.32  4876.3 1742.66  4964.5 1739.89
  4964.7 1739.39  4968.5 1739.89  5050.4 1740.22  5088.8 1742.20  5149.1 1744.38
  5154.8 1743.82  5162.1 1744.70  5182.7 1745.19  5193.2 1746.05  5198.8 1745.25
  5215.2 1747.44  5220.9 1746.96  5275.1 1750.58  5354.3 1752.05  5363.7 1752.75
  5449.1 1752.96  5540.8 1752.65  5543.8 1752.60  5591.8 1752.41  5598.0 1753.37
#Mann=9,-1,0
  4343.3   0.035       0  4361.7   0.045       0  4787.1   0.035       0
  4964.5   0.035       0  4968.5   0.035       0  5182.7   0.045       0
  5449.1   0.035       0  5540.8   0.045       0  5543.8   0.035       0
Bank Sta=4964.5,4968.5
Exp/Cntr=0.3,0.1

Chan Stop Cuts=-1