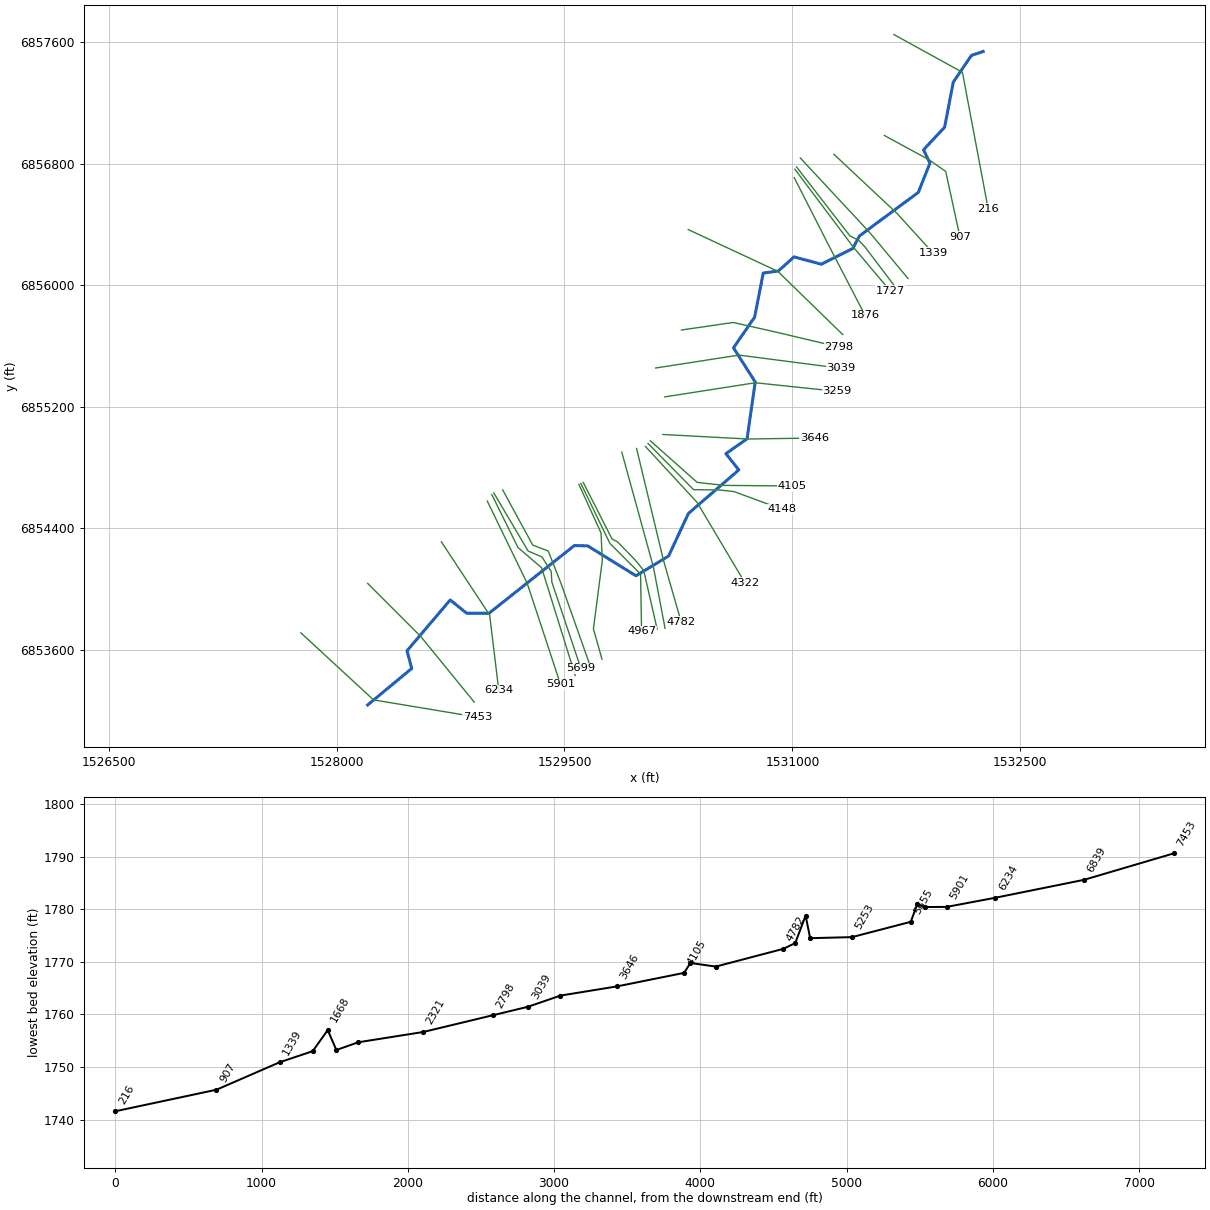
--- BULL WAGON CREEK TRIBUTARY 5.prj (project) ---

Proj Title=BULL WAGON CREEK TRIBUTARY 5 Base Level Engineering
Current Plan=p01
Default Exp/Contr=0.3,0.1
English Units
Geom File=g01
Flow File=f01
Plan File=p01
BEGIN DESCRIPTION:
BULL WAGON CREEK TRIBUTARY 5
END DESCRIPTION:

--- BULL WAGON CREEK TRIBUTARY 5.p01 (plan) ---

Plan Title=Multiple Run
Short Identifier=Multiple
Geom File=g01
Flow File=f01
Subcritical Flow
K Sum by GR= 0
Std Step Tol= 0.01
Critical Tol= 0.01
Num of Std Step Trials= 20
Max Error Tol= 0.3
Flow Tol Ratio= 0.001
Split Flow NTrial= 30
Split Flow Tol= 0.02
Split Flow Ratio= 0.02
Log Output Level= 0
Friction Slope Method= 1
Unsteady Friction Slope Method= 2
Unsteady Bridges Friction Slope Method= 1
Parabolic Critical Depth
Global Vel Dist=  1 , 1 , 1
Global Log Level= 0
CheckData=True
Encroach Param= -1, 0, 0, 0
BEGIN DESCRIPTION:
Multiple Run
END DESCRIPTION:

--- BULL WAGON CREEK TRIBUTARY 5.f01 (steady flow) ---

Flow Title=Multiple
Number of Profiles=7
Profile Names=10-year,25-year,50-year,1pct_min,100-year,1pct_plu,500-year
River Rch & RM= BULL WAGON CREEK,Reach-1,7453
      79     101     118      69     138     274     188
River Rch & RM= BULL WAGON CREEK,Reach-1,4148
     134     178     213     127     253     505     363
Boundary for River Rch & Prof#=BULL WAGON CREEK,Reach-1,1
Up Type=0
Dn Type=3
Dn Slope=0.005
Boundary for River Rch & Prof#=BULL WAGON CREEK,Reach-1,2
Up Type=0
Dn Type=3
Dn Slope=0.005
Boundary for River Rch & Prof#=BULL WAGON CREEK,Reach-1,3
Up Type=0
Dn Type=3
Dn Slope=0.005
Boundary for River Rch & Prof#=BULL WAGON CREEK,Reach-1,4
Up Type=0
Dn Type=3
Dn Slope=0.005
Boundary for River Rch & Prof#=BULL WAGON CREEK,Reach-1,5
Up Type=0
Dn Type=3
Dn Slope=0.005
Boundary for River Rch & Prof#=BULL WAGON CREEK,Reach-1,6
Up Type=0
Dn Type=3
Dn Slope=0.005
Boundary for River Rch & Prof#=BULL WAGON CREEK,Reach-1,7
Up Type=0
Dn Type=3
Dn Slope=0.005

--- BULL WAGON CREEK TRIBUTARY 5.g01 (geometry) ---

Geom Title=Existing Conditions

River Reach=BULL WAGON CREEK,Reach-1
Reach XY= 30
      1528205.00      6853238.00      1528494.93      6853478.01
      1528464.17      6853594.72      1528748.33      6853929.04
      1528856.47      6853841.55      1529003.53      6853841.53
      1529565.49      6854287.06      1529653.50      6854284.53
      1529970.39      6854088.07      1530185.23      6854217.87
      1530315.51      6854497.81      1530647.39      6854784.67
      1530562.50      6854891.58      1530701.54      6854989.25
      1530755.29      6855363.12      1530612.30      6855588.08
      1530751.24      6855789.56      1530808.03      6856079.99
      1530907.36      6856093.57      1531011.04      6856186.37
      1531189.78      6856138.25      1531396.65      6856241.19
      1531441.47      6856324.44      1531828.82      6856611.13
      1531904.85      6856803.42      1531862.82      6856891.41
      1532001.46      6857039.47      1532058.62      6857336.50
      1532177.73      6857511.85      1532255.00      6857538.00

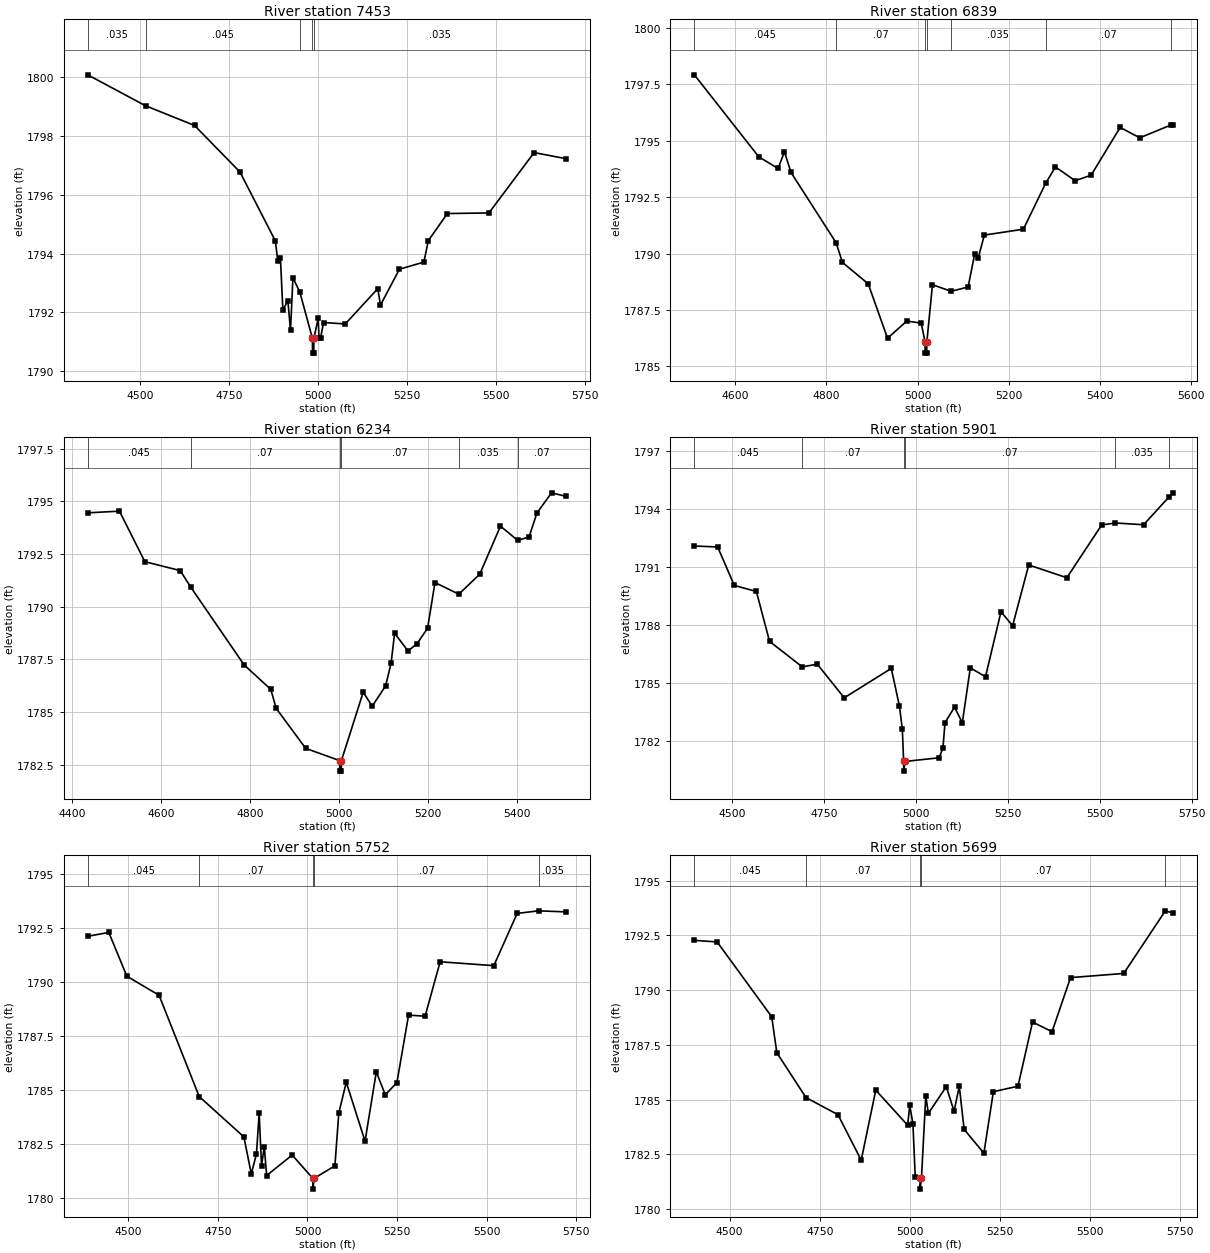
Type RM Length L Ch R = 1,7453,614,614,614
BEGIN DESCRIPTION:
BULL WAGON CREEK TRIBUTARY 5 13.0
END DESCRIPTION:
XS GIS Cut Line= 3
      1527765.59      6853712.48      1528243.43      6853271.53
      1528927.03      6853157.81
#Sta/Elev= 30
  4353.4 1800.07  4515.6 1799.02  4653.2 1798.35  4780.7 1796.77  4880.0 1794.43
  4886.8 1793.75  4894.2 1793.86  4901.0 1792.09  4915.1 1792.40  4922.5 1791.39
  4929.3 1793.18  4948.7 1792.69  4984.0 1791.12  4984.3 1790.62  4987.8 1790.62
  4988.0 1791.12  5000.2 1791.80  5002.5 1791.14  5006.9 1791.14  5015.3 1791.66
  5076.2 1791.61  5167.4 1792.81  5175.0 1792.25  5228.2 1793.47  5296.7 1793.71
  5309.3 1794.44  5362.7 1795.36  5479.4 1795.38  5606.2 1797.43  5696.6 1797.22
#Mann=5,-1,0
  4353.4   0.035       0  4515.6   0.045       0  4948.7   0.035       0
  4984.0   0.035       0  4988.0   0.035       0
Bank Sta=4984,4988
Exp/Cntr=0.3,0.1

Type RM Length L Ch R = 1,6839,605,605,605
BEGIN DESCRIPTION:
BULL WAGON CREEK TRIBUTARY 5 12.0
END DESCRIPTION:
XS GIS Cut Line= 3
      1528205.03      6854037.97      1528555.00      6853688.00
      1528906.21      6853256.75
#Sta/Elev= 30
  4509.9 1797.92  4651.3 1794.29  4693.7 1793.77  4707.8 1794.51  4722.0 1793.60
  4821.2 1790.48  4835.1 1789.61  4891.7 1788.66  4934.1 1786.25  4976.5 1787.01
  5008.1 1786.92  5016.5 1786.09  5016.7 1785.59  5020.2 1785.59  5020.5 1786.09
  5032.8 1788.62  5073.9 1788.33  5111.1 1788.52  5125.5 1789.98  5133.4 1789.81
  5146.7 1790.82  5232.5 1791.08  5281.3 1793.11  5302.9 1793.84  5346.0 1793.23
  5381.1 1793.47  5445.0 1795.59  5488.1 1795.13  5556.9 1795.70  5561.0 1795.70
#Mann=7,-1,0
  4509.9   0.045       0  4821.2    0.07       0  5016.5    0.07       0
  5020.5    0.07       0  5073.9   0.035       0  5281.3    0.07       0
  5556.9   0.035       0
Bank Sta=5016.5,5020.5
Exp/Cntr=0.3,0.1

Type RM Length L Ch R = 1,6234,333,333,333
BEGIN DESCRIPTION:
BULL WAGON CREEK TRIBUTARY 5 11.0
END DESCRIPTION:
XS GIS Cut Line= 3
      1528690.05      6854311.46      1529007.75      6853829.69
      1529067.65      6853334.90
#Sta/Elev= 30
  4435.9 1794.45  4507.2 1794.53  4564.4 1792.13  4643.7 1791.71  4667.2 1790.93
  4787.4 1787.23  4847.3 1786.07  4859.4 1785.17  4925.7 1783.27  5002.0 1782.69
  5002.2 1782.19  5005.7 1782.19  5006.0 1782.69  5055.0 1785.94  5075.1 1785.27
  5105.4 1786.24  5117.7 1787.33  5125.5 1788.74  5155.7 1787.89  5175.9 1788.24
  5199.6 1788.97  5216.2 1791.14  5269.8 1790.59  5316.9 1791.54  5363.4 1793.82
  5402.2 1793.14  5427.7 1793.31  5445.3 1794.44  5478.1 1795.40  5511.4 1795.23
#Mann=6,-1,0
  4435.9   0.045       0  4667.2    0.07       0  5002.0    0.07       0
  5006.0    0.07       0  5269.8   0.035       0  5402.2    0.07       0
Bank Sta=5002,5006
Exp/Cntr=0.3,0.1

Type RM Length L Ch R = 1,5901,149,149,149
BEGIN DESCRIPTION:
BULL WAGON CREEK TRIBUTARY 5 10.0
END DESCRIPTION:
XS GIS Cut Line= 3
      1528992.13      6854579.69      1529255.00      6854038.00
      1529473.90      6853373.95
#Sta/Elev= 30
  4397.9 1792.09  4461.3 1792.04  4506.5 1790.05  4566.5 1789.74  4602.3 1787.16
  4691.3 1785.84  4732.1 1785.98  4805.4 1784.24  4933.3 1785.76  4955.5 1783.81
  4963.4 1782.61  4966.9 1780.95  4967.2 1780.45  4970.9 1780.95  5063.2 1781.14
  5073.7 1781.63  5079.4 1782.96  5105.3 1783.76  5126.4 1782.95  5148.2 1785.79
  5189.5 1785.33  5231.6 1788.69  5263.2 1787.97  5307.0 1791.11  5410.6 1790.45
  5505.4 1793.18  5542.9 1793.28  5619.4 1793.19  5687.5 1794.61  5699.2 1794.84
#Mann=6,-1,0
  4397.9   0.045       0  4691.3    0.07       0  4966.9    0.07       0
  4970.9    0.07       0  5542.9   0.035       0  5687.5    0.07       0
Bank Sta=4966.9,4970.9
Exp/Cntr=0.3,0.1

Type RM Length L Ch R = 1,5752,53,53,53
BEGIN DESCRIPTION:
Mapping XS c1dc06f2
END DESCRIPTION:
XS GIS Cut Line= 4
      1529022.16      6854622.06      1529193.60      6854274.83
      1529349.85      6854140.28      1529570.85      6853431.79
#Sta/Elev= 30
  4386.8 1792.13  4445.6 1792.31  4496.1 1790.28  4585.9 1789.40  4697.8 1784.71
  4822.5 1782.84  4843.3 1781.13  4857.6 1782.04  4865.2 1783.94  4871.8 1781.50
  4879.5 1782.39  4886.1 1781.05  4957.4 1782.00  5014.8 1780.92  5015.1 1780.42
  5018.8 1780.92  5076.6 1781.50  5087.4 1783.94  5108.3 1785.37  5160.7 1782.64
  5192.1 1785.85  5217.1 1784.79  5249.6 1785.35  5282.1 1788.48  5328.3 1788.43
  5370.2 1790.95  5520.1 1790.77  5585.1 1793.19  5645.0 1793.31  5722.4 1793.26
#Mann=5,-1,0
  4386.8   0.045       0  4697.8    0.07       0  5014.8    0.07       0
  5018.8    0.07       0  5645.0   0.035       0
Bank Sta=5014.8,5018.8
Exp/Cntr=0.3,0.1

Type RM Length L Ch R = 1,5699,44,44,44
BEGIN DESCRIPTION:
Mapping XS b0a07305
END DESCRIPTION:
XS GIS Cut Line= 6
      1529035.19      6854632.89      1529260.88      6854250.96
      1529352.02      6854211.89      1529412.79      6854116.41
      1529417.13      6854046.96      1529608.10      6853478.38
#Sta/Elev= 30
  4402.0 1792.27  4465.2 1792.20  4616.8 1788.78  4630.9 1787.14  4711.9 1785.09
  4800.7 1784.31  4865.2 1782.23  4905.6 1785.43  4994.1 1783.83  5000.0 1784.73
  5008.8 1783.89  5015.2 1781.46  5028.5 1781.41  5028.7 1780.91  5032.5 1781.41
  5044.4 1785.17  5051.6 1784.37  5101.4 1785.59  5122.9 1784.47  5137.5 1785.60
  5150.9 1783.64  5205.8 1782.55  5232.1 1785.36  5300.4 1785.61  5340.8 1788.54
  5395.0 1788.10  5446.3 1790.57  5594.0 1790.76  5709.5 1793.62  5730.7 1793.52
#Mann=5,-1,0
  4402.0   0.045       0  4711.9    0.07       0  5028.5    0.07       0
  5032.5    0.07       0  5709.5   0.035       0
Bank Sta=5028.5,5032.5
Exp/Cntr=0.3,0.1

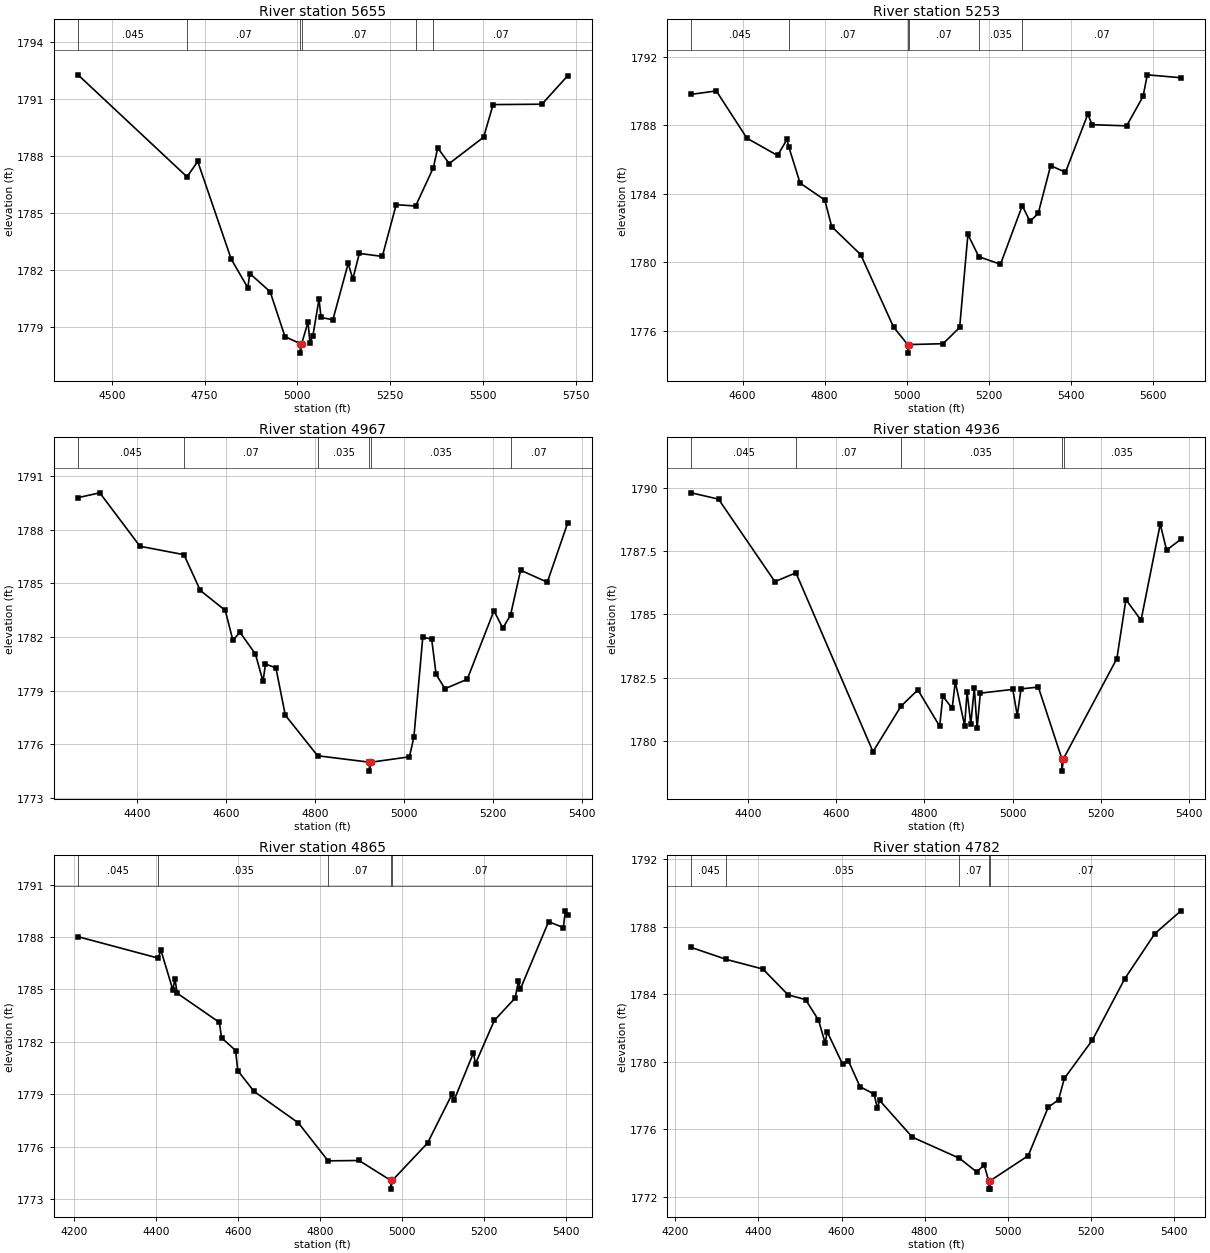
Type RM Length L Ch R = 1,5655,402,402,402
BEGIN DESCRIPTION:
Mapping XS 946ebc21
END DESCRIPTION:
XS GIS Cut Line= 5
      1529093.76      6854652.47      1529291.26      6854290.02
      1529393.26      6854250.96      1529477.89      6854036.11
      1529666.57      6853502.60
#Sta/Elev= 30
  4409.2 1792.29  4702.7 1786.91  4731.6 1787.72  4822.0 1782.56  4866.5 1781.06
  4871.9 1781.81  4926.6 1780.85  4966.6 1778.48  5007.6 1778.11  5007.9 1777.61
  5011.6 1778.11  5028.6 1779.24  5034.0 1778.16  5041.8 1778.53  5058.3 1780.46
  5063.7 1779.49  5095.6 1779.37  5136.9 1782.34  5149.3 1781.52  5166.9 1782.87
  5228.7 1782.71  5266.2 1785.44  5318.5 1785.37  5366.2 1787.39  5378.0 1788.43
  5408.9 1787.61  5501.6 1789.00  5527.2 1790.72  5658.6 1790.74  5728.0 1792.24
#Mann=6,-1,0
  4409.2   0.045       0  4702.7    0.07       0  5007.6    0.07       0
  5011.6    0.07       0  5318.5   0.035       0  5366.2    0.07       0
Bank Sta=5007.6,5011.6
Exp/Cntr=0.3,0.1

Type RM Length L Ch R = 1,5253,286,286,286
BEGIN DESCRIPTION:
Mapping XS e4e4e033
END DESCRIPTION:
XS GIS Cut Line= 5
      1529595.07      6854689.34      1529740.48      6854370.31
      1529749.16      6854190.19      1529690.56      6853738.80
      1529746.99      6853539.14
#Sta/Elev= 30
  4475.1 1789.81  4536.1 1790.01  4610.7 1787.25  4685.4 1786.24  4708.4 1787.18
  4712.6 1786.76  4740.3 1784.63  4800.6 1783.64  4817.3 1782.09  4888.1 1780.45
  4968.2 1776.22  5002.6 1775.20  5002.9 1774.70  5006.6 1775.20  5088.9 1775.25
  5129.3 1776.20  5149.4 1781.63  5176.0 1780.33  5228.8 1779.89  5282.0 1783.31
  5300.7 1782.39  5320.8 1782.86  5351.1 1785.65  5387.2 1785.26  5441.9 1788.66
  5451.9 1788.04  5536.3 1787.97  5576.4 1789.69  5586.7 1790.95  5668.7 1790.78
#Mann=6,-1,0
  4475.1   0.045       0  4712.6    0.07       0  5002.6    0.07       0
  5006.6    0.07       0  5176.0   0.035       0  5282.0    0.07       0
Bank Sta=5002.6,5006.6
Exp/Cntr=0.3,0.1

Type RM Length L Ch R = 1,4967,31,31,31
BEGIN DESCRIPTION:
Mapping XS 63d8ea8e
END DESCRIPTION:
XS GIS Cut Line= 4
      1529608.11      6854695.81      1529799.07      6854300.87
      1530000.89      6854099.05      1530007.39      6853722.21
#Sta/Elev= 30
  4267.4 1789.80  4316.3 1790.07  4406.7 1787.08  4505.6 1786.61  4542.3 1784.61
  4598.5 1783.49  4615.6 1781.82  4631.5 1782.27  4666.3 1781.05  4683.4 1779.52
  4688.9 1780.49  4712.3 1780.28  4733.5 1777.63  4806.1 1775.36  4922.4 1775.00
  4922.7 1774.50  4926.4 1775.00  5012.6 1775.30  5022.6 1776.40  5042.6 1781.99
  5062.6 1781.89  5072.6 1779.91  5092.6 1779.11  5142.6 1779.64  5202.6 1783.47
  5222.6 1782.50  5239.9 1783.23  5262.6 1785.74  5322.6 1785.07  5368.4 1788.38
#Mann=6,-1,0
  4267.4   0.045       0  4505.6    0.07       0  4806.1   0.035       0
  4922.4   0.035       0  4926.4   0.035       0  5239.9    0.07       0
Bank Sta=4922.4,4926.4
Exp/Cntr=0.3,0.1

Type RM Length L Ch R = 1,4936,71,71,71
BEGIN DESCRIPTION:
Mapping XS 0c375037
END DESCRIPTION:
XS GIS Cut Line= 6
      1529623.87      6854701.62      1529813.11      6854330.09
      1529849.56      6854311.00      1529967.62      6854189.47
      1530021.44      6854123.50      1530109.99      6853736.32
#Sta/Elev= 30
  4271.8 1789.82  4333.5 1789.57  4461.3 1786.30  4509.0 1786.65  4683.7 1779.56
  4747.0 1781.36  4785.4 1782.01  4834.8 1780.57  4842.0 1781.76  4863.1 1781.28
  4870.3 1782.33  4891.4 1780.59  4896.9 1781.93  4905.4 1780.67  4913.3 1782.08
  4919.7 1780.50  4927.0 1781.88  5000.6 1782.03  5010.7 1780.99  5019.3 1782.05
  5058.5 1782.12  5111.6 1779.29  5111.9 1778.79  5115.6 1779.29  5236.5 1783.25
  5257.0 1785.59  5291.3 1784.77  5334.8 1788.58  5349.2 1787.55  5381.7 1787.98
#Mann=5,-1,0
  4271.8   0.045       0  4509.0    0.07       0  4747.0   0.035       0
  5111.6   0.035       0  5115.6   0.035       0
Bank Sta=5111.6,5115.6
Exp/Cntr=0.3,0.1

Type RM Length L Ch R = 1,4865,83,83,83
BEGIN DESCRIPTION:
Mapping XS 4e2e7e3f
END DESCRIPTION:
XS GIS Cut Line= 3
      1529877.35      6854901.25      1530085.67      6854144.33
      1530161.93      6853742.27
#Sta/Elev= 30
  4209.0 1788.02  4404.7 1786.79  4411.0 1787.26  4440.2 1784.98  4445.4 1785.60
  4450.9 1784.78  4553.8 1783.11  4559.0 1782.23  4593.4 1781.50  4598.6 1780.35
  4638.2 1779.16  4746.6 1777.35  4818.9 1775.18  4894.5 1775.20  4971.7 1774.06
  4971.9 1773.56  4975.7 1774.06  5061.6 1776.20  5121.1 1778.99  5126.2 1778.65
  5173.4 1781.36  5178.5 1780.75  5224.4 1783.22  5275.3 1784.51  5283.0 1785.46
  5288.1 1785.03  5356.8 1788.88  5392.7 1788.54  5397.8 1789.50  5403.3 1789.26
#Mann=5,-1,0
  4209.0   0.045       0  4404.7   0.035       0  4818.9    0.07       0
  4971.7    0.07       0  4975.7    0.07       0
Bank Sta=4971.7,4975.7
Exp/Cntr=0.3,0.1

Type RM Length L Ch R = 1,4782,460,460,460
BEGIN DESCRIPTION:
Mapping XS 7022643c
END DESCRIPTION:
XS GIS Cut Line= 3
      1529974.57      6854925.54      1530151.65      6854189.47
      1530267.97      6853784.93
#Sta/Elev= 30
  4238.5 1786.78  4322.9 1786.07  4410.8 1785.50  4471.4 1783.97  4513.4 1783.69
  4544.5 1782.48  4560.5 1781.12  4565.6 1781.78  4602.4 1779.87  4616.5 1780.06
  4644.4 1778.53  4678.2 1778.09  4686.3 1777.25  4691.5 1777.72  4770.2 1775.54
  4883.5 1774.29  4925.1 1773.48  4943.1 1773.89  4953.9 1772.96  4954.2 1772.46
  4957.7 1772.46  4957.9 1772.96  5049.1 1774.44  5097.1 1777.31  5122.0 1777.75
  5136.0 1779.02  5203.4 1781.29  5281.2 1784.92  5353.8 1787.60  5416.5 1788.95
#Mann=5,-1,0
  4238.5   0.045       0  4322.9   0.035       0  4883.5    0.07       0
  4953.9    0.07       0  4957.9    0.07       0
Bank Sta=4953.9,4957.9
Exp/Cntr=0.3,0.1

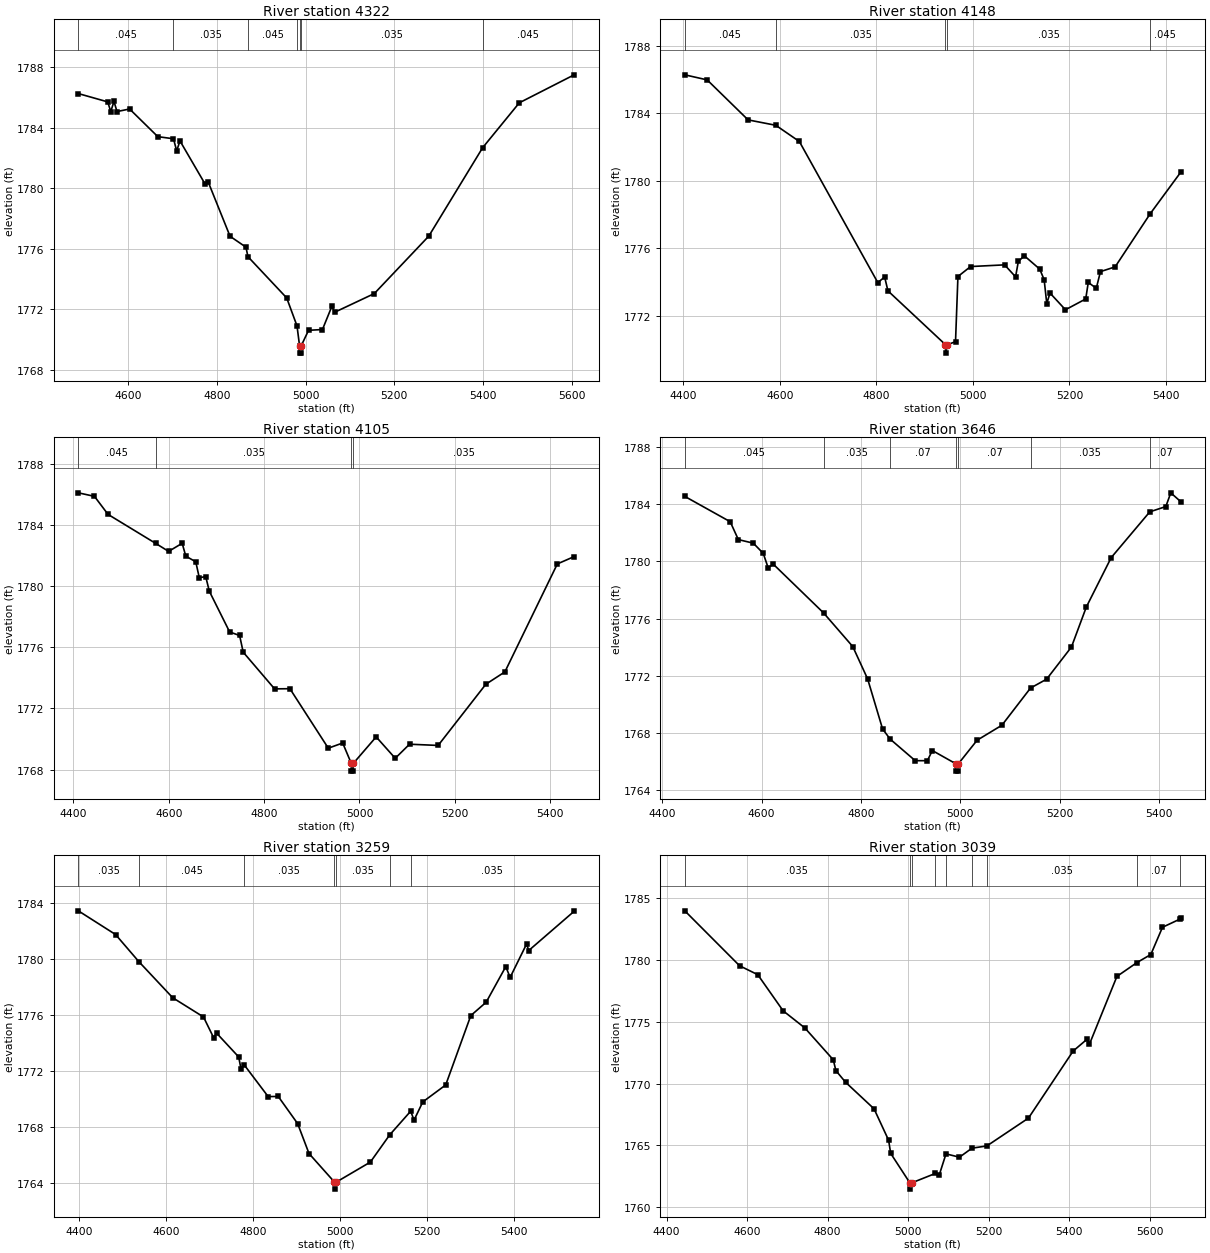
Type RM Length L Ch R = 1,4322,174,174,174
BEGIN DESCRIPTION:
Mapping XS 1fd46bd8
END DESCRIPTION:
XS GIS Cut Line= 3
      1530032.73      6854939.02      1530373.44      6854570.11
      1530687.38      6854041.82
#Sta/Elev= 30
  4488.3 1786.27  4554.5 1785.72  4561.3 1785.08  4568.6 1785.75  4575.4 1785.08
  4603.8 1785.25  4667.3 1783.42  4702.6 1783.28  4709.8 1782.48  4717.2 1783.14
  4773.9 1780.28  4780.7 1780.43  4830.0 1776.83  4865.8 1776.11  4870.3 1775.48
  4957.6 1772.75  4980.8 1770.90  4986.5 1769.60  4986.8 1769.10  4990.3 1769.10
  4990.5 1769.60  5006.8 1770.61  5038.1 1770.66  5059.5 1772.21  5065.3 1771.80
  5154.9 1773.04  5277.6 1776.84  5398.9 1782.69  5481.5 1785.66  5605.0 1787.51
#Mann=7,-1,0
  4488.3   0.045       0  4702.6   0.035       0  4870.3   0.045       0
  4980.8   0.035       0  4986.5   0.035       0  4990.5   0.035       0
  5398.9   0.045       0
Bank Sta=4986.5,4990.5
Exp/Cntr=0.3,0.1

Type RM Length L Ch R = 1,4148,43,43,43
BEGIN DESCRIPTION:
Mapping XS b9fb78f6
END DESCRIPTION:
XS GIS Cut Line= 5
      1530050.09      6854958.56      1530349.56      6854654.75
      1530521.00      6854652.58      1530616.49      6854641.73
      1530928.94      6854526.73
#Sta/Elev= 30
  4403.2 1786.27  4449.5 1785.97  4534.3 1783.60  4591.7 1783.28  4640.5 1782.32
  4803.0 1773.96  4817.2 1774.29  4824.0 1773.47  4943.2 1770.28  4943.5 1769.78
  4947.2 1770.28  4964.0 1770.46  4969.0 1774.32  4995.2 1774.91  5065.7 1775.01
  5088.4 1774.30  5094.1 1775.21  5106.4 1775.55  5138.4 1774.76  5147.6 1774.13
  5153.0 1772.72  5159.7 1773.34  5191.7 1772.35  5233.7 1772.99  5239.0 1773.97
  5255.6 1773.62  5264.2 1774.61  5294.6 1774.89  5367.3 1778.04  5430.3 1780.49
#Mann=5,-1,0
  4403.2   0.045       0  4591.7   0.035       0  4943.2   0.035       0
  4947.2   0.035       0  5367.3   0.045       0
Bank Sta=4943.2,4947.2
Exp/Cntr=0.3,0.1

Type RM Length L Ch R = 1,4105,459,459,459
BEGIN DESCRIPTION:
Mapping XS da407d26
END DESCRIPTION:
XS GIS Cut Line= 4
      1530065.24      6854975.96      1530373.44      6854702.49
      1530549.22      6854682.96      1531000.30      6854678.62
#Sta/Elev= 30
  4410.3 1786.10  4444.1 1785.87  4472.6 1784.69  4572.7 1782.79  4599.7 1782.27
  4628.1 1782.80  4635.7 1781.96  4656.6 1781.59  4664.0 1780.55  4677.5 1780.62
  4685.0 1779.67  4727.7 1777.00  4748.6 1776.77  4756.1 1775.68  4821.9 1773.28
  4854.1 1773.29  4934.6 1769.40  4964.8 1769.74  4982.9 1768.40  4983.1 1767.90
  4986.6 1767.90  4986.9 1768.40  5035.0 1770.14  5075.0 1768.74  5105.0 1769.66
  5165.0 1769.58  5265.0 1773.58  5305.0 1774.39  5415.0 1781.45  5450.3 1781.93
#Mann=4,-1,0
  4410.3   0.045       0  4572.7   0.035       0  4982.9   0.035       0
  4986.9   0.035       0
Bank Sta=4982.9,4986.9
Exp/Cntr=0.3,0.1

Type RM Length L Ch R = 1,3646,387,387,387
BEGIN DESCRIPTION:
BULL WAGON CREEK TRIBUTARY 5 5.0
END DESCRIPTION:
XS GIS Cut Line= 3
      1530147.33      6855017.80      1530705.00      6854988.00
      1531144.79      6854994.36
#Sta/Elev= 30
  4445.5 1784.54  4536.9 1782.77  4553.3 1781.52  4583.4 1781.27  4603.4 1780.56
  4613.4 1779.54  4623.4 1779.81  4725.0 1776.39  4783.7 1774.04  4813.7 1771.77
  4843.7 1768.28  4858.9 1767.57  4909.5 1766.06  4933.9 1766.06  4943.9 1766.77
  4992.0 1765.83  4992.2 1765.33  4995.7 1765.33  4996.0 1765.83  5034.0 1767.49
  5084.0 1768.54  5141.6 1771.14  5174.0 1771.76  5224.0 1774.01  5254.0 1776.81
  5304.0 1780.26  5381.7 1783.46  5414.0 1783.83  5424.0 1784.79  5443.8 1784.18
#Mann=7,-1,0
  4445.5   0.045       0  4725.0   0.035       0  4858.9    0.07       0
  4992.0    0.07       0  4996.0    0.07       0  5141.6   0.035       0
  5381.7    0.07       0
Bank Sta=4992,4996
Exp/Cntr=0.3,0.1

Type RM Length L Ch R = 1,3259,220,220,220
BEGIN DESCRIPTION:
BULL WAGON CREEK TRIBUTARY 5 4.0
END DESCRIPTION:
XS GIS Cut Line= 3
      1530160.35      6855265.19      1530755.43      6855358.18
      1531291.58      6855301.82
#Sta/Elev= 30
  4397.7 1783.43  4483.4 1781.74  4536.9 1779.81  4615.0 1777.23  4685.8 1775.86
  4709.2 1774.38  4716.2 1774.70  4766.8 1773.01  4772.0 1772.18  4779.6 1772.44
  4834.7 1770.18  4857.9 1770.19  4902.6 1768.25  4928.7 1766.12  4987.4 1764.08
  4987.7 1763.58  4991.4 1764.08  5070.0 1765.51  5114.5 1767.45  5162.8 1769.14
  5170.5 1768.50  5190.6 1769.80  5243.4 1771.01  5301.2 1775.96  5336.5 1776.91
  5381.7 1779.45  5391.7 1778.68  5429.5 1781.06  5434.6 1780.60  5539.1 1783.40
#Mann=7,-1,0
  4397.7   0.035       0  4536.9   0.045       0  4779.6   0.035       0
  4987.4   0.035       0  4991.4   0.035       0  5114.5    0.07       0
  5162.8   0.035       0
Bank Sta=4987.4,4991.4
Exp/Cntr=0.3,0.1

Type RM Length L Ch R = 1,3039,241,241,241
BEGIN DESCRIPTION:
BULL WAGON CREEK TRIBUTARY 5 3.0
END DESCRIPTION:
XS GIS Cut Line= 3
      1530100.52      6855455.30      1530648.57      6855540.29
      1531319.72      6855452.97
#Sta/Elev= 30
  4445.4 1783.96  4581.5 1779.52  4626.6 1778.80  4689.6 1775.88  4743.4 1774.50
  4814.2 1771.92  4820.6 1771.05  4844.6 1770.11  4915.4 1767.96  4951.6 1765.42
  4956.7 1764.36  5004.5 1761.97  5004.7 1761.47  5008.5 1761.97  5067.9 1762.74
  5077.1 1762.59  5094.1 1764.32  5127.5 1764.05  5158.6 1764.78  5195.6 1764.96
  5298.9 1767.21  5409.9 1772.63  5444.6 1773.59  5450.2 1773.17  5518.6 1778.66
  5568.4 1779.78  5602.8 1780.43  5631.7 1782.63  5676.3 1783.31  5676.8 1783.35
#Mann=9,-1,0
  4445.4   0.035       0  5004.5   0.035       0  5008.5   0.035       0
  5067.9    0.07       0  5094.1   0.035       0  5158.6    0.07       0
  5195.6   0.035       0  5568.4    0.07       0  5676.3   0.035       0
Bank Sta=5004.5,5008.5
Exp/Cntr=0.3,0.1

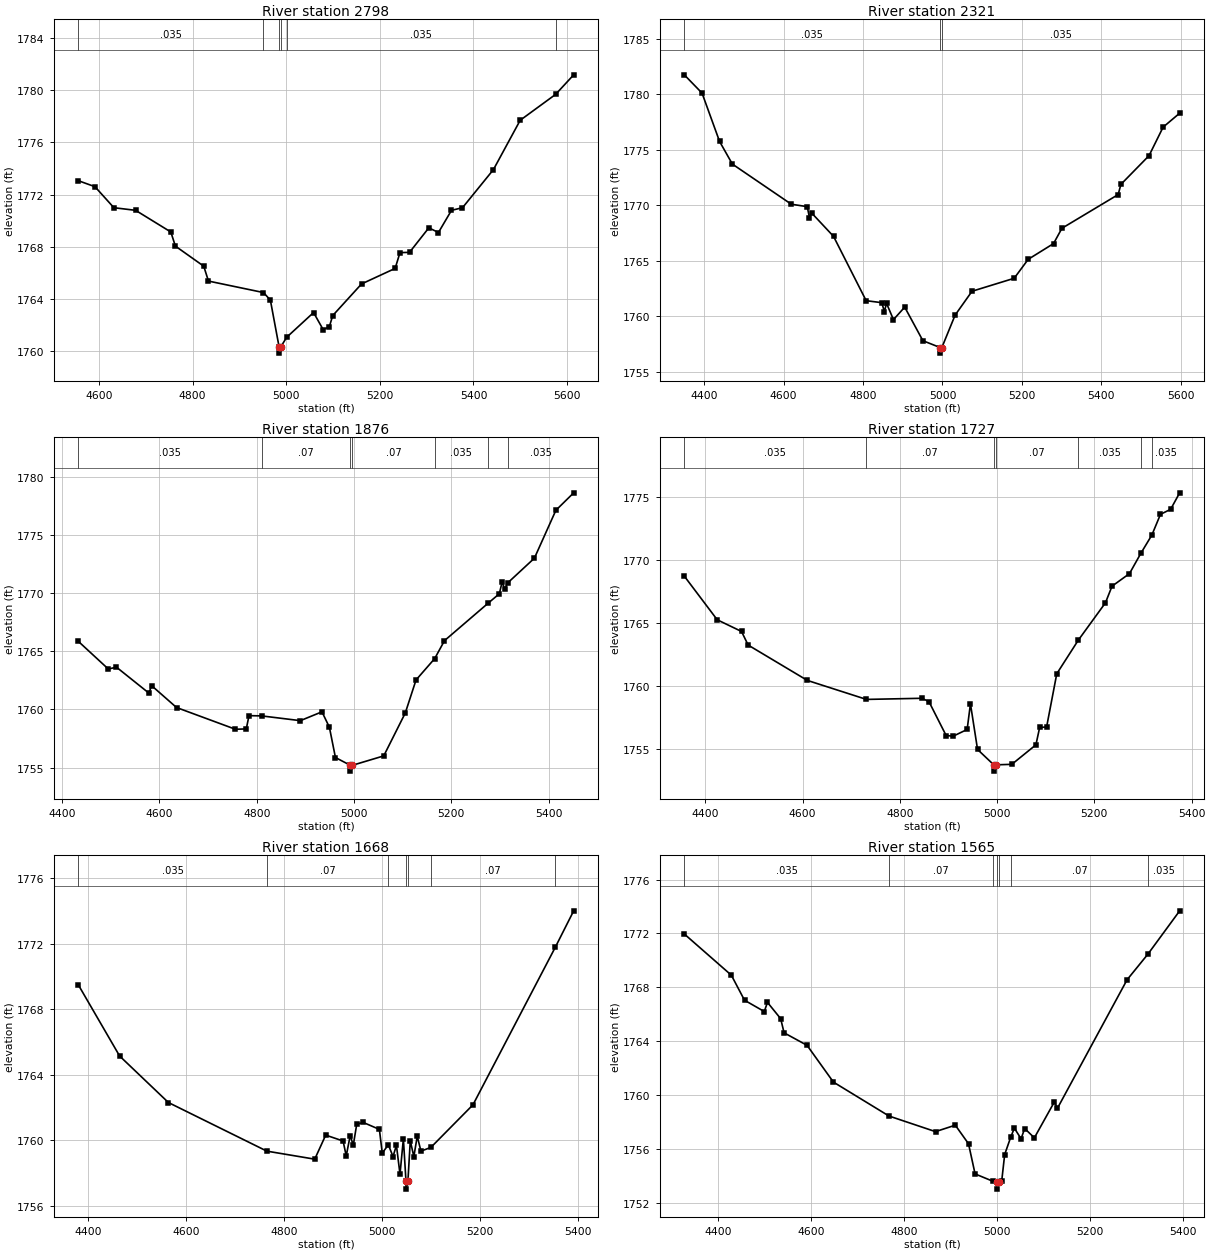
Type RM Length L Ch R = 1,2798,477,477,477
BEGIN DESCRIPTION:
Mapping XS 6c252147
END DESCRIPTION:
XS GIS Cut Line= 4
      1530269.78      6855705.30      1530610.91      6855754.78
      1530910.39      6855687.07      1531306.20      6855593.32
#Sta/Elev= 30
  4555.7 1773.06  4591.3 1772.60  4631.7 1770.99  4678.1 1770.79  4753.4 1769.13
  4763.1 1768.05  4823.7 1766.51  4833.8 1765.37  4951.4 1764.49  4966.1 1763.91
  4984.6 1760.35  4984.9 1759.85  4988.6 1760.35  5001.1 1761.07  5058.4 1762.96
  5078.9 1761.65  5092.0 1761.87  5099.4 1762.73  5160.9 1765.15  5232.7 1766.34
  5243.0 1767.55  5263.4 1767.57  5304.7 1769.45  5325.2 1769.09  5353.1 1770.79
  5376.6 1770.99  5442.7 1773.91  5499.9 1777.69  5575.5 1779.67  5614.2 1781.17
#Mann=6,-1,0
  4555.7   0.035       0  4951.4    0.07       0  4984.6    0.07       0
  4988.6    0.07       0  5001.1   0.035       0  5575.5    0.07       0
Bank Sta=4984.6,4988.6
Exp/Cntr=0.3,0.1

Type RM Length L Ch R = 1,2321,445,445,445
BEGIN DESCRIPTION:
Mapping XS 90c30da7
END DESCRIPTION:
XS GIS Cut Line= 3
      1530314.51      6856366.06      1530903.42      6856091.66
      1531331.12      6855675.15
#Sta/Elev= 30
  4350.3 1781.76  4395.0 1780.11  4439.1 1775.75  4471.3 1773.71  4619.6 1770.09
  4659.7 1769.87  4665.3 1768.89  4670.8 1769.30  4725.9 1767.19  4808.0 1761.39
  4847.3 1761.21  4853.8 1760.41  4859.3 1761.15  4876.7 1759.68  4905.0 1760.81
  4950.8 1757.78  4994.5 1757.16  4994.8 1756.66  4998.5 1757.16  5031.9 1760.09
  5074.4 1762.24  5180.5 1763.41  5215.8 1765.12  5279.6 1766.54  5300.7 1767.92
  5442.2 1770.96  5449.1 1771.88  5519.9 1774.47  5555.3 1777.04  5597.0 1778.30
#Mann=3,-1,0
  4350.3   0.035       0  4994.5   0.035       0  4998.5   0.035       0
Bank Sta=4994.5,4998.5
Exp/Cntr=0.3,0.1

Type RM Length L Ch R = 1,1876,149,149,149
BEGIN DESCRIPTION:
Mapping XS 9aa4e738
END DESCRIPTION:
XS GIS Cut Line= 3
      1531011.94      6856707.92      1531230.70      6856278.21
      1531477.75      6855802.30
#Sta/Elev= 30
  4433.2 1765.86  4494.9 1763.48  4511.6 1763.64  4578.3 1761.41  4583.9 1762.05
  4635.1 1760.17  4756.2 1758.30  4778.5 1758.33  4784.1 1759.47  4809.8 1759.45
  4889.7 1759.04  4934.1 1759.80  4949.4 1758.47  4961.8 1755.87  4992.5 1755.20
  4992.7 1754.70  4996.5 1755.20  5061.1 1756.01  5105.4 1759.70  5127.5 1762.54
  5165.9 1764.38  5186.0 1765.92  5275.7 1769.14  5298.7 1769.95  5304.4 1770.95
  5310.1 1770.34  5315.6 1770.87  5370.8 1773.01  5415.0 1777.13  5451.6 1778.63
#Mann=7,-1,0
  4433.2   0.035       0  4809.8    0.07       0  4992.5    0.07       0
  4996.5    0.07       0  5165.9   0.035       0  5275.7    0.07       0
  5315.6   0.035       0
Bank Sta=4992.5,4996.5
Exp/Cntr=0.3,0.1

Type RM Length L Ch R = 1,1727,59,59,59
BEGIN DESCRIPTION:
Mapping XS cb13aed1
END DESCRIPTION:
XS GIS Cut Line= 3
      1531016.29      6856763.02      1531402.57      6856248.70
      1531644.37      6855961.57
#Sta/Elev= 30
  4356.8 1768.73  4424.5 1765.26  4474.5 1764.33  4488.1 1763.25  4609.8 1760.44
  4731.4 1758.93  4845.2 1759.02  4859.8 1758.76  4895.2 1756.06  4909.8 1756.01
  4938.4 1756.54  4945.2 1758.58  4959.8 1754.95  4993.2 1753.73  4993.4 1753.23
  4997.2 1753.73  5030.3 1753.77  5079.8 1755.32  5087.5 1756.70  5101.8 1756.74
  5122.7 1760.97  5166.8 1763.63  5222.8 1766.61  5236.3 1767.93  5272.2 1768.93
  5295.4 1770.53  5318.3 1772.00  5335.9 1773.64  5356.8 1774.04  5375.4 1775.35
#Mann=7,-1,0
  4356.8   0.035       0  4731.4    0.07       0  4993.2    0.07       0
  4997.2    0.07       0  5166.8   0.035       0  5295.4    0.07       0
  5318.3   0.035       0
Bank Sta=4993.2,4997.2
Exp/Cntr=0.3,0.1

Type RM Length L Ch R = 1,1668,103,103,103
BEGIN DESCRIPTION:
Mapping XS d4e6ab04
END DESCRIPTION:
XS GIS Cut Line= 6
      1531027.12      6856778.24      1531339.64      6856374.57
      1531378.70      6856324.65      1531437.30      6856294.27
      1531476.36      6856253.04      1531666.68      6856002.16
#Sta/Elev= 30
  4379.4 1769.50  4463.8 1765.15  4563.4 1762.31  4764.5 1759.34  4862.2 1758.85
  4884.6 1760.32  4920.1 1759.96  4926.5 1759.05  4934.6 1760.29  4940.9 1759.70
  4948.0 1760.99  4961.5 1761.09  4994.2 1760.67  5000.1 1759.22  5012.5 1759.73
  5022.1 1759.01  5029.0 1759.70  5036.3 1757.93  5043.2 1760.09  5048.5 1757.52
  5048.7 1757.02  5052.5 1757.52  5057.3 1759.97  5064.6 1759.01  5071.5 1760.25
  5079.1 1759.34  5099.4 1759.57  5185.3 1762.17  5353.2 1771.78  5391.0 1774.02
#Mann=7,-1,0
  4379.4   0.035       0  4764.5    0.07       0  5012.5   0.035       0
  5048.5    0.07       0  5052.5   0.035       0  5099.4    0.07       0
  5353.2   0.035       0
Bank Sta=5048.5,5052.5
Exp/Cntr=0.3,0.1

Type RM Length L Ch R = 1,1565,226,226,226
BEGIN DESCRIPTION:
Mapping XS 5d8f3c35
END DESCRIPTION:
XS GIS Cut Line= 3
      1531051.77      6856837.64      1531511.80      6856342.88
      1531760.72      6856044.19
#Sta/Elev= 30
  4327.7 1771.96  4428.8 1768.90  4457.1 1767.04  4499.6 1766.20  4506.4 1766.88
  4534.8 1765.67  4542.1 1764.62  4591.5 1763.69  4648.1 1760.96  4767.5 1758.44
  4867.5 1757.28  4910.0 1757.76  4938.4 1756.38  4952.5 1754.14  4991.8 1753.58
  4999.9 1753.51  5000.1 1753.01  5003.9 1753.51  5009.7 1753.60  5016.1 1755.58
  5029.3 1756.89  5036.9 1757.54  5051.3 1756.75  5059.1 1757.51  5079.9 1756.82
  5122.9 1759.49  5129.4 1759.01  5279.1 1768.56  5324.0 1770.47  5392.1 1773.68
#Mann=7,-1,0
  4327.7   0.035       0  4767.5    0.07       0  4991.8   0.035       0
  4999.9   0.035       0  5003.9   0.035       0  5029.3    0.07       0
  5324.0   0.035       0
Bank Sta=4999.9,5003.9
Exp/Cntr=0.3,0.1

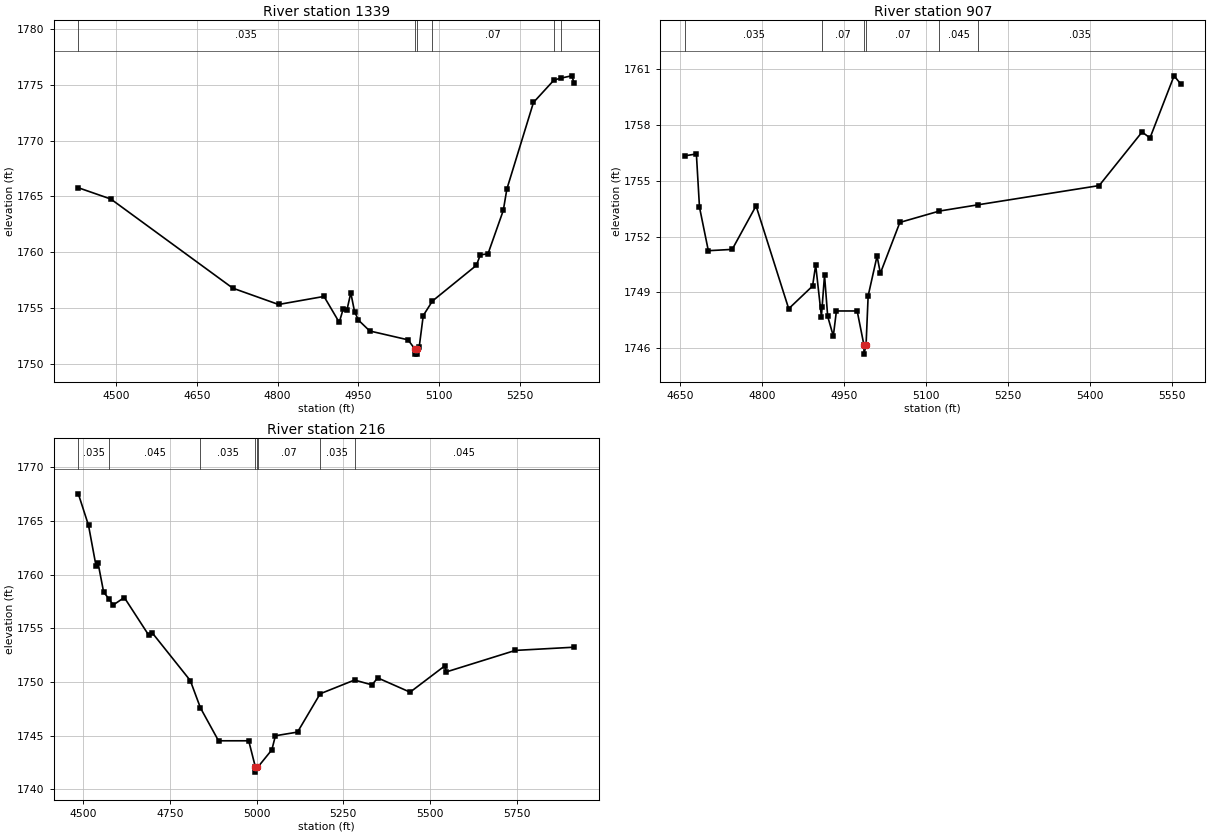
Type RM Length L Ch R = 1,1339,432,432,432
BEGIN DESCRIPTION:
Mapping XS 36ee3d6c
END DESCRIPTION:
XS GIS Cut Line= 3
      1531273.06      6856861.57      1531689.75      6856470.92
      1531925.17      6856211.75
#Sta/Elev= 30
  4429.8 1765.78  4490.2 1764.77  4716.8 1756.80  4801.8 1755.34  4886.3 1756.06
  4914.6 1753.74  4921.9 1754.93  4928.8 1754.83  4936.1 1756.38  4943.0 1754.71
  4950.3 1753.94  4971.3 1752.97  5042.3 1752.18  5054.5 1751.40  5054.8 1750.90
  5058.3 1750.90  5058.5 1751.40  5063.3 1751.58  5070.7 1754.35  5087.8 1755.65
  5169.4 1758.84  5176.8 1759.78  5191.0 1759.87  5219.4 1763.75  5226.1 1765.67
  5275.5 1773.41  5313.6 1775.41  5326.0 1775.58  5346.4 1775.79  5351.1 1775.17
#Mann=6,-1,0
  4429.8   0.035       0  5054.5   0.035       0  5058.5   0.035       0
  5087.8    0.07       0  5313.6   0.035       0  5326.0    0.07       0
Bank Sta=5054.5,5058.5
Exp/Cntr=0.3,0.1

Type RM Length L Ch R = 1,907,691,691,691
BEGIN DESCRIPTION:
Mapping XS 28939cde
END DESCRIPTION:
XS GIS Cut Line= 4
      1531605.15      6856985.23      1531900.26      6856824.65
      1532008.76      6856748.70      1532102.08      6856319.03
#Sta/Elev= 30
  4658.4 1756.34  4679.6 1756.44  4685.3 1753.58  4701.5 1751.24  4745.2 1751.31
  4788.9 1753.65  4848.7 1748.12  4892.4 1749.34  4898.1 1750.47  4908.6 1747.70
  4909.9 1748.21  4914.3 1749.93  4920.1 1747.71  4930.4 1746.65  4936.1 1748.00
  4974.1 1748.00  4986.4 1746.18  4986.6 1745.68  4990.4 1746.18  4994.2 1748.81
  5010.5 1750.95  5016.6 1750.03  5052.3 1752.76  5124.6 1753.37  5196.0 1753.71
  5417.3 1754.74  5495.9 1757.62  5510.4 1757.30  5554.5 1760.64  5566.5 1760.21
#Mann=6,-1,0
  4658.4   0.035       0  4909.9    0.07       0  4986.4    0.07       0
  4990.4    0.07       0  5124.6   0.045       0  5196.0   0.035       0
Bank Sta=4986.4,4990.4
Exp/Cntr=0.3,0.1

Type RM Length L Ch R = 1,216,0,0,0
BEGIN DESCRIPTION:
BULL WAGON CREEK TRIBUTARY 5 1.0
END DESCRIPTION:
XS GIS Cut Line= 3
      1531668.05      6857649.31      1532118.56      6857401.24
      1532288.34      6856501.11
#Sta/Elev= 30
  4485.7 1767.52  4515.1 1764.58  4536.9 1760.77  4542.6 1761.07  4558.7 1758.36
  4573.4 1757.76  4586.2 1757.16  4618.3 1757.86  4689.4 1754.32  4699.1 1754.56
  4808.7 1750.12  4837.9 1747.58  4890.1 1744.51  4977.2 1744.51  4996.2 1742.09
  4996.4 1741.59  5000.2 1742.09  5004.6 1742.10  5044.0 1743.67  5054.2 1744.98
  5118.0 1745.32  5183.3 1748.89  5282.4 1750.17  5332.7 1749.72  5349.3 1750.37
  5442.7 1749.04  5542.4 1751.48  5547.5 1750.93  5746.2 1752.93  5916.0 1753.23
#Mann=8,-1,0
  4485.7   0.035       0  4573.4   0.045       0  4837.9   0.035       0
  4996.2   0.035       0  5000.2   0.035       0  5004.6    0.07       0
  5183.3   0.035       0  5282.4   0.045       0
Bank Sta=4996.2,5000.2
Exp/Cntr=0.3,0.1

Chan Stop Cuts=-1