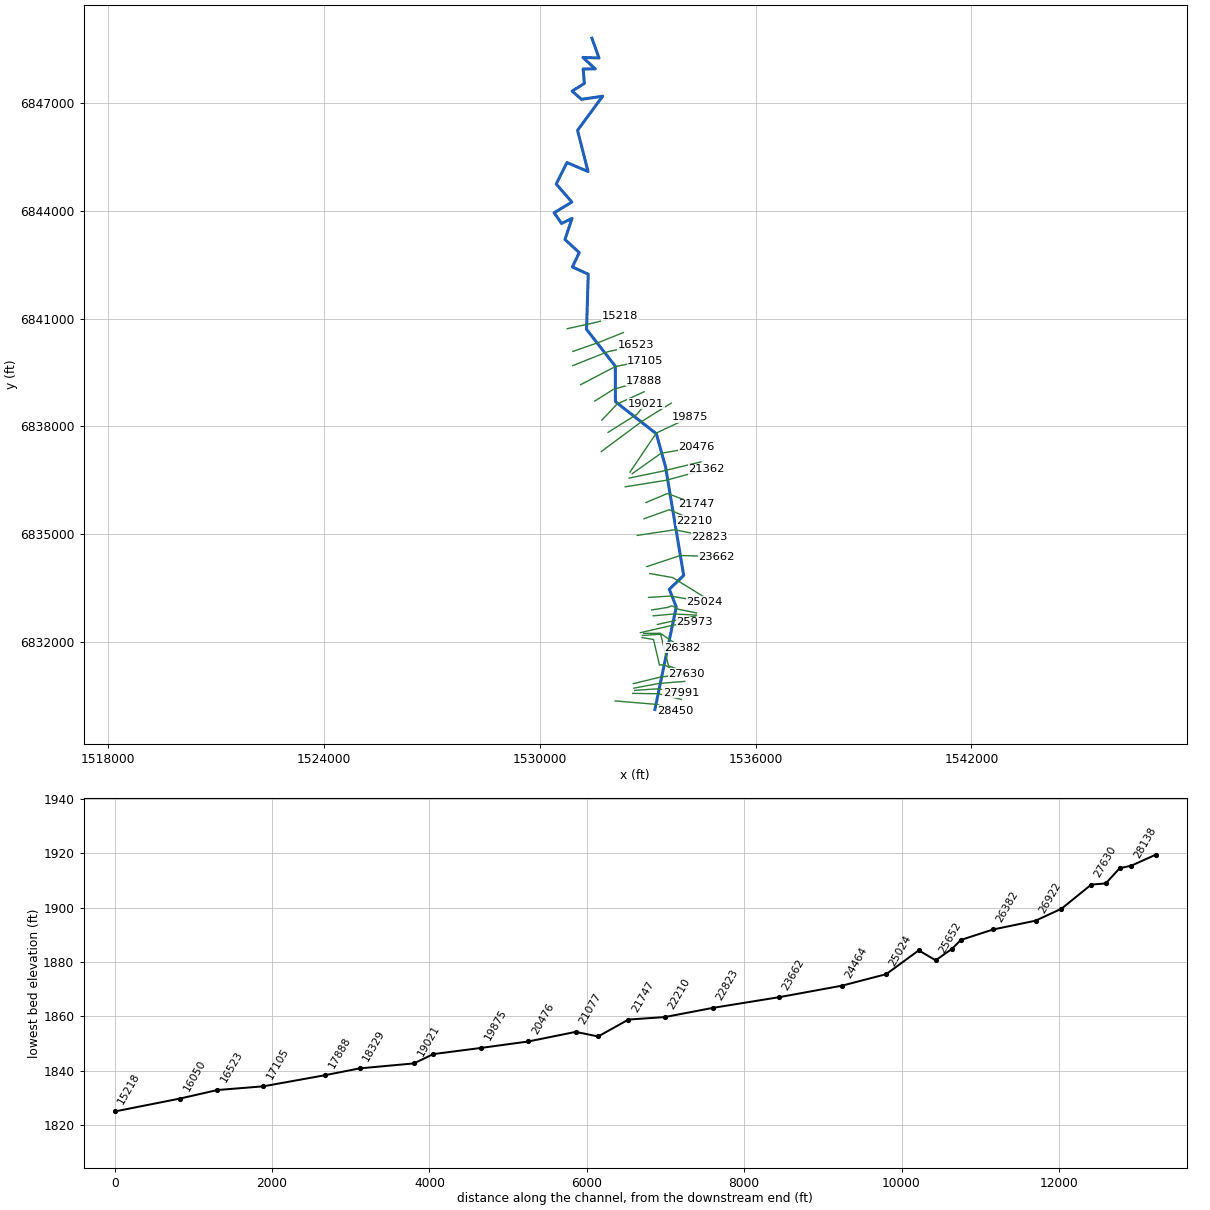
--- BULL WAGON CREEK TRIBUTARY 6.prj (project) ---

Proj Title=BULL WAGON CREEK TRIBUTARY 6 Base Level Engineering
Current Plan=p01
Default Exp/Contr=0.3,0.1
English Units
Geom File=g01
Flow File=f01
Plan File=p01
Y Axis Title=Elevation
X Axis Title(PF)=Main Channel Distance
X Axis Title(XS)=Station
BEGIN DESCRIPTION:
BULL WAGON CREEK TRIBUTARY 6
END DESCRIPTION:
DSS Export Rating Curves= 0
DSS Export Rating Curve Sorted= 0
DSS Export Volume Flow Curves= 0
DXF OffsetX= 0
DXF OffsetY= 0
DXF ScaleX= 1
DXF ScaleY= 10

--- BULL WAGON CREEK TRIBUTARY 6.p01 (plan) ---

Plan Title=Multiple Run
Short Identifier=Multiple
Geom File=g01
Flow File=f01
Subcritical Flow
K Sum by GR= 0
Std Step Tol= 0.01
Critical Tol= 0.01
Num of Std Step Trials= 20
Max Error Tol= 0.3
Flow Tol Ratio= 0.001
Split Flow NTrial= 30
Split Flow Tol= 0.02
Split Flow Ratio= 0.02
Log Output Level= 0
Friction Slope Method= 1
Unsteady Friction Slope Method= 2
Unsteady Bridges Friction Slope Method= 1
Parabolic Critical Depth
Global Vel Dist=  1 , 1 , 1
Global Log Level= 0
CheckData=True
Encroach Param= -1, 0, 0, 0
BEGIN DESCRIPTION:
Multiple Run
END DESCRIPTION:

--- BULL WAGON CREEK TRIBUTARY 6.f01 (steady flow) ---

Flow Title=Multiple
Program Version=4.10
Number of Profiles= 7
Profile Names=10-year,25-year,50-year,1pct_min,100-year,1pct_plu,500-year
River Rch & RM=BULL WAGON CREEK,Reach-1         ,28450
     127     170     203     122     243     485     352
River Rch & RM=BULL WAGON CREEK,Reach-1         ,22210
     378     540     678     424     845    1686    1332
River Rch & RM=BULL WAGON CREEK,Reach-1         ,21077
     444     637     802     501    1001    1996    1581
River Rch & RM=BULL WAGON CREEK,Reach-1         ,16523
     467     669     841     526    1049    2093    1653
River Rch & RM=BULL WAGON CREEK,Reach-1         ,11525
     558     804    1015     636    1270    2534    2015
River Rch & RM=BULL WAGON CREEK,Reach-1         ,5856
     572     823    1038     650    1297    2588    2052
Boundary for River Rch & Prof#=BULL WAGON CREEK,Reach-1         , 1
Up Type= 0
Dn Type= 3
Dn Slope=0.005
Boundary for River Rch & Prof#=BULL WAGON CREEK,Reach-1         , 2
Up Type= 0
Dn Type= 3
Dn Slope=0.005
Boundary for River Rch & Prof#=BULL WAGON CREEK,Reach-1         , 3
Up Type= 0
Dn Type= 3
Dn Slope=0.005
Boundary for River Rch & Prof#=BULL WAGON CREEK,Reach-1         , 4
Up Type= 0
Dn Type= 3
Dn Slope=0.005
Boundary for River Rch & Prof#=BULL WAGON CREEK,Reach-1         , 5
Up Type= 0
Dn Type= 3
Dn Slope=0.005
Boundary for River Rch & Prof#=BULL WAGON CREEK,Reach-1         , 6
Up Type= 0
Dn Type= 3
Dn Slope=0.005
Boundary for River Rch & Prof#=BULL WAGON CREEK,Reach-1         , 7
Up Type= 0
Dn Type= 3
Dn Slope=0.005
DSS Import GetInterval= 0
DSS Import GetPeak= 0
DSS Import FillOption= 0

--- BULL WAGON CREEK TRIBUTARY 6.g01 (geometry) ---

Geom Title=Existing Conditions
Program Version=4.10

River Reach=BULL WAGON CREEK,Reach-1
Reach XY= 30
        1533205.        6830138.      1533797.71      6832988.09
      1533605.87      6833477.67       1534005.3      6833862.88
      1533497.37      6836891.34      1533244.68      6837798.18
      1532108.53      6838689.45      1532103.61      6839676.42
      1531305.67      6840699.05      1531353.02      6842232.33
      1530912.32      6842431.62      1531103.43      6842831.96
      1530706.56      6843194.09      1530902.93      6843782.56
      1530611.04      6843639.57        1530405.        6843938.
      1530897.59       6844234.6      1530462.01      6844738.18
      1530760.41      6845332.84      1531347.58      6845084.55
      1531055.53      6846227.31      1531754.45      6847177.36
      1531165.29      6847088.97      1530904.45      6847317.87
      1531245.87      6847531.26      1531210.69      6847932.93
      1531547.47      6847934.82      1531204.99      6848253.47
      1531651.46      6848238.97        1531455.        6848788.

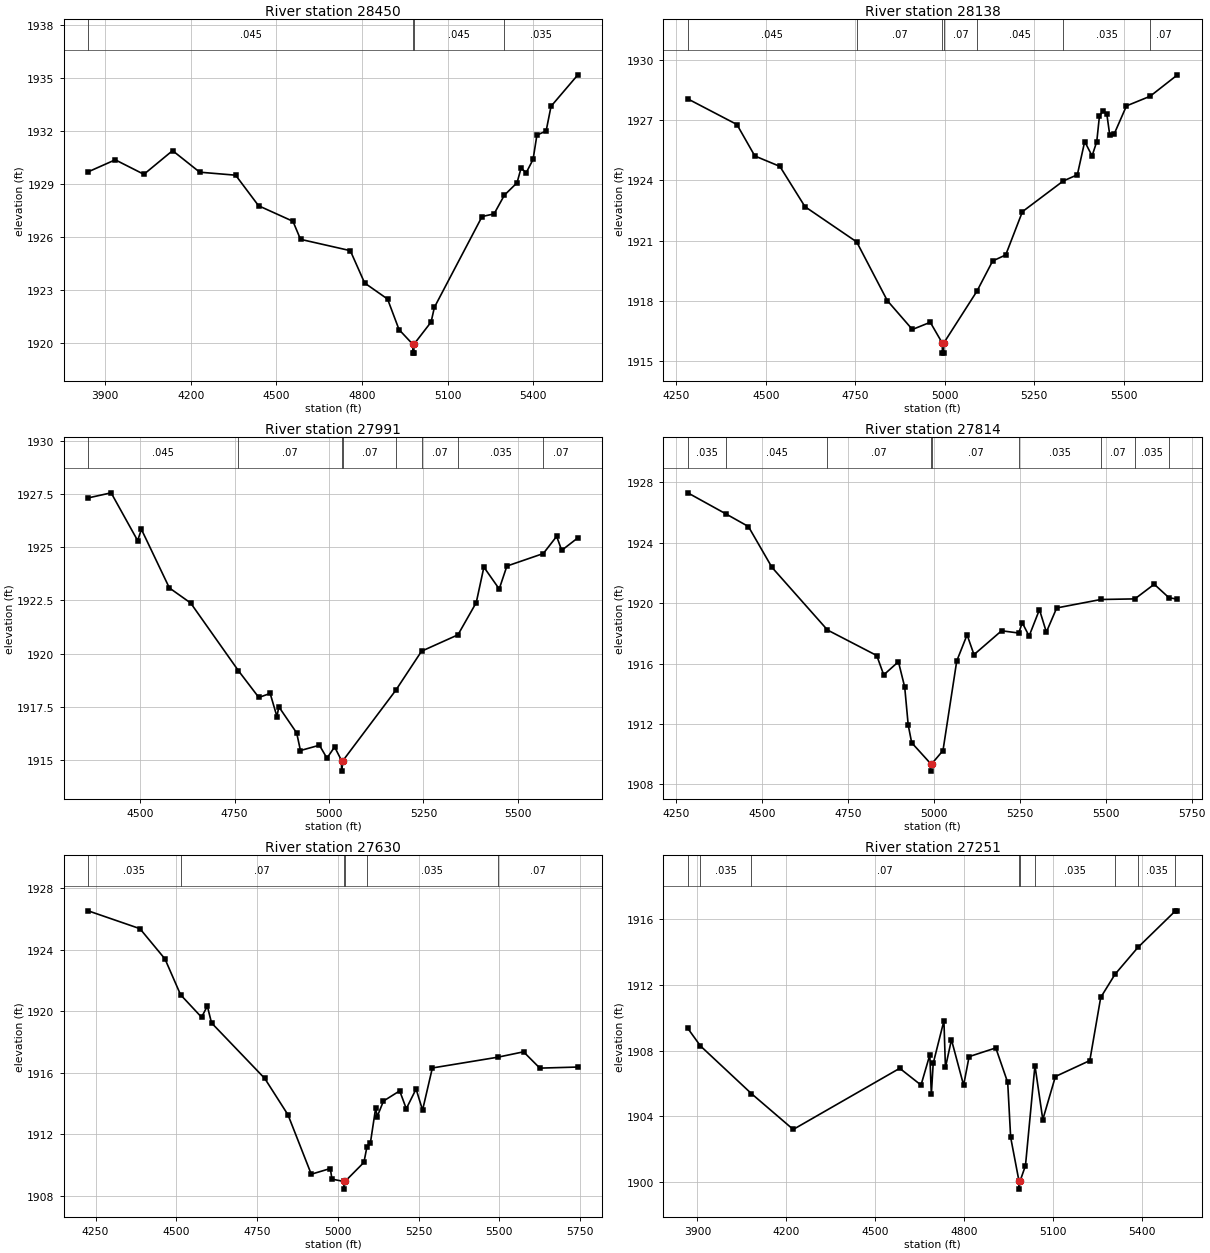
Type RM Length L Ch R = 1 ,28450   ,312,312,312
BEGIN DESCRIPTION:
BULL WAGON CREEK TRIBUTARY 6 45.0
END DESCRIPTION:
XS GIS Cut Line= 3
      1532100.45      6830376.02       1533255.1      6830277.96
      1533784.48      6830108.66
#Sta/Elev= 30
  3841.2  1929.7  3936.1 1930.38  4036.4 1929.56  4136.8  1930.9  4231.8 1929.68
  4357.6 1929.51  4437.9 1927.78  4558.3  1926.9  4584.7 1925.88    4759 1925.24
  4809.2 1923.41  4889.5  1922.5  4929.7 1920.77  4977.8 1919.94  4978.1 1919.44
  4981.6 1919.44  4981.8 1919.94  5041.9  1921.2  5053.4 1922.03  5220.4 1927.17
  5262.4 1927.32  5298.5 1928.38  5342.8 1929.08  5356.9 1929.91    5375 1929.65
  5398.9  1930.4  5412.4 1931.78  5444.6 1932.01  5461.9 1933.41  5555.8 1935.19
#Mann= 4 ,-1 , 0
  3841.2    .045       0  4977.8    .045       0  4981.8    .045       0
  5298.5    .035       0
Bank Sta=4977.8,4981.8
XS Rating Curve= 0 ,0
Exp/Cntr=0.3,0.1

Type RM Length L Ch R = 1 ,28138   ,147,147,147
BEGIN DESCRIPTION:
Mapping XS 91989085
END DESCRIPTION:
XS GIS Cut Line= 3
      1532587.68      6830585.24      1533301.21      6830574.83
      1533936.67      6830418.57
#Sta/Elev= 30
  4282.3 1928.07  4419.6 1926.79  4469.6 1925.22  4539.6  1924.7  4609.7 1922.69
  4754.2 1920.93  4839.7    1918  4909.7 1916.56  4959.7 1916.92  4993.3 1915.88
  4993.6 1915.38  4997.1 1915.38  4997.3 1915.88    5090 1918.47    5134 1919.98
  5170.4 1920.28  5217.1 1922.44    5331 1923.97  5370.5 1924.28  5391.1 1925.94
  5411.7 1925.22  5424.8 1925.94  5432.3 1927.22  5442.6 1927.47  5452.9 1927.31
  5461.1 1926.26  5473.5 1926.32  5507.8 1927.72  5573.8  1928.2  5650.3 1929.27
#Mann= 7 ,-1 , 0
  4282.3    .045       0  4754.2     .07       0  4993.3     .07       0
  4997.3     .07       0    5090    .045       0    5331    .035       0
  5573.8     .07       0
Bank Sta=4993.3,4997.3
XS Rating Curve= 0 ,0
Exp/Cntr=0.3,0.1

Type RM Length L Ch R = 1 ,27991   ,177,177,177
BEGIN DESCRIPTION:
Mapping XS 43374b08
END DESCRIPTION:
XS GIS Cut Line= 3
      1532644.31      6830668.21      1533282.37      6830712.48
      1533930.45      6830605.77
#Sta/Elev= 30
  4362.4 1927.33  4423.2 1927.57  4493.4 1925.32  4503.4 1925.85  4577.4 1923.09
  4633.7 1922.38  4760.2 1919.19  4814.2 1917.93  4844.2 1918.12  4862.2 1917.03
  4867.2 1917.49  4914.4 1916.26  4924.4 1915.43  4974.6 1915.68  4994.6 1915.07
  5014.8  1915.6  5033.1 1914.96  5033.3 1914.46  5037.1 1914.96  5176.8 1918.27
    5245 1920.11  5341.3 1920.88  5389.8  1922.4    5410 1924.07  5450.6 1923.04
  5470.9 1924.12  5567.3 1924.71  5602.6 1925.52    5616 1924.86  5658.8 1925.45
#Mann= 8 ,-1 , 0
  4362.4    .045       0  4760.2     .07       0  5033.1     .07       0
  5037.1     .07       0  5176.8    .045       0    5245     .07       0
  5341.3    .035       0  5567.3     .07       0
Bank Sta=5033.1,5037.1
XS Rating Curve= 0 ,0
Exp/Cntr=0.3,0.1

Type RM Length L Ch R = 1 ,27814   ,184,184,184
BEGIN DESCRIPTION:
Mapping XS 462cb4f2
END DESCRIPTION:
XS GIS Cut Line= 3
      1532624.13      6830731.08      1533322.04      6830861.29
      1534035.59      6830918.58
#Sta/Elev= 30
    4283  1927.3  4393.7 1925.91  4459.5 1925.07    4528 1922.37  4689.8 1918.22
  4833.2 1916.53  4853.5 1915.25  4896.3 1916.12  4914.6 1914.44  4924.8 1911.93
  4934.9 1910.76  4989.9 1909.38  4990.2 1908.88  4993.9 1909.38    5026 1910.24
  5066.1 1916.17  5096.2  1917.9  5116.3 1916.59  5196.6 1918.17  5246.6 1918.02
  5256.8  1918.7  5276.8 1917.82  5306.9 1919.57    5327 1918.08  5357.1 1919.68
  5485.6 1920.24  5584.7 1920.28  5641.1 1921.25  5683.8 1920.36  5708.8 1920.26
#Mann= 9 ,-1 , 0
    4283    .035       0  4393.7    .045       0  4689.8     .07       0
  4989.9     .07       0  4993.9     .07       0  5246.6    .035       0
  5485.6     .07       0  5584.7    .035       0  5683.8     .07       0
Bank Sta=4989.9,4993.9
XS Rating Curve= 0 ,0
Exp/Cntr=0.3,0.1

Type RM Length L Ch R = 1 ,27630   ,379,379,379
BEGIN DESCRIPTION:
BULL WAGON CREEK TRIBUTARY 6 43.0
END DESCRIPTION:
XS GIS Cut Line= 3
      1532603.95      6830855.19        1533355.        6831038.
      1534091.76      6831132.74
#Sta/Elev= 30
  4227.1 1926.54  4387.3 1925.38  4464.9 1923.41  4513.2 1921.08  4578.1 1919.62
    4596 1920.34    4609 1919.25  4773.7 1915.64  4845.7 1913.27  4917.7 1909.41
  4976.6 1909.78  4981.8 1909.09  5018.2 1908.94  5018.5 1908.44  5022.2 1908.94
  5080.7 1910.18  5089.6 1911.15  5100.9 1911.47  5116.9  1913.7  5121.9 1913.16
  5141.2 1914.17  5191.4 1914.83  5211.8 1913.67  5242.1 1914.95  5262.2 1913.58
  5292.5 1916.32    5495 1917.02  5574.8 1917.37  5625.2 1916.31  5742.9 1916.38
#Mann= 6 ,-1 , 0
  4227.1    .035       0  4513.2     .07       0  5018.2     .07       0
  5022.2     .07       0  5089.6    .035       0    5495     .07       0
Bank Sta=5018.2,5022.2
XS Rating Curve= 0 ,0
Exp/Cntr=0.3,0.1

Type RM Length L Ch R = 1 ,27251   ,329,329,329
BEGIN DESCRIPTION:
Mapping XS 0885f0ca
END DESCRIPTION:
XS GIS Cut Line= 5
      1532848.82      6832135.98      1533166.36      6832080.86
       1533331.3      6831375.92      1533480.14      6831376.51
      1533871.34      6831138.15
#Sta/Elev= 30
  3867.2 1909.36    3910 1908.29  4082.1 1905.39  4223.2 1903.21  4582.7 1906.93
  4654.6 1905.91  4684.3 1907.75  4689.4 1905.34  4695.7 1907.23  4731.9 1909.82
    4737 1906.98  4757.3 1908.67  4798.4  1905.9  4816.9 1907.64    4907 1908.17
  4947.2 1906.07  4957.2 1902.73  4985.2 1900.08  4985.4 1899.58  4989.2 1900.08
  5007.2 1901.01  5039.2  1907.1  5065.7 1903.81  5108.2 1906.43  5224.4  1907.4
  5261.2 1911.24  5309.5 1912.65  5386.6 1914.28    5513  1916.5  5520.4 1916.51
#Mann= 9 ,-1 , 0
  3867.2     .07       0    3910    .035       0  4082.1     .07       0
  4985.2     .07       0  4989.2     .07       0  5039.2    .035       0
  5309.5     .07       0  5386.6    .035       0    5513     .07       0
Bank Sta=4985.2,4989.2
XS Rating Curve= 0 ,0
Exp/Cntr=0.3,0.1

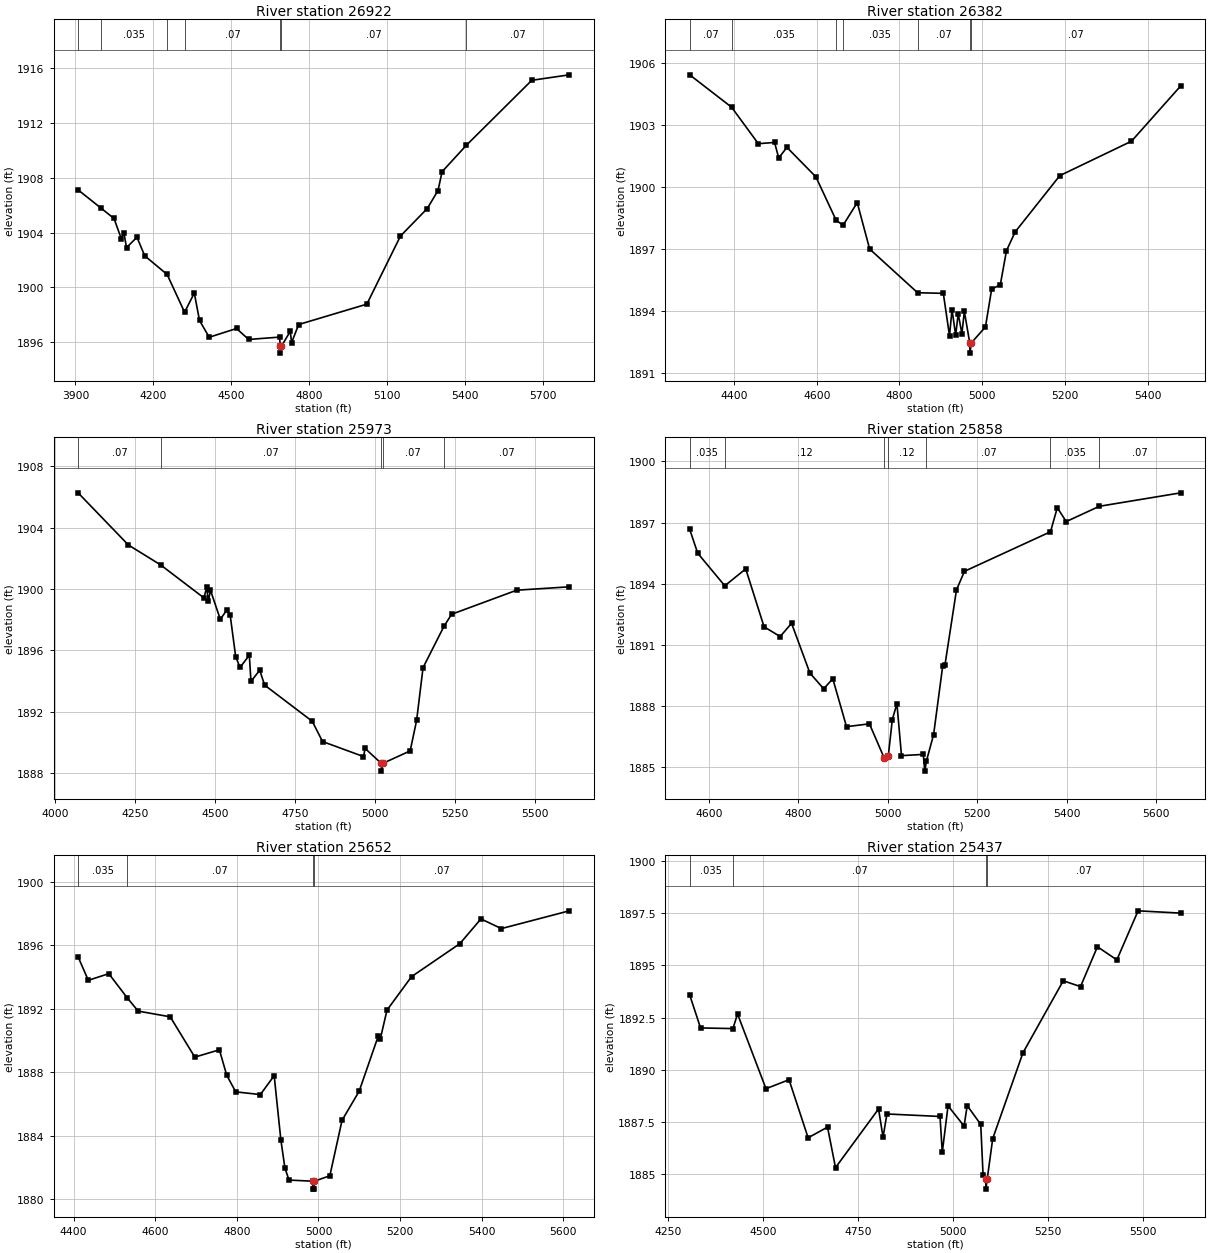
Type RM Length L Ch R = 1 ,26922   ,540,540,540
BEGIN DESCRIPTION:
Mapping XS 9e406278
END DESCRIPTION:
XS GIS Cut Line= 4
      1532859.29      6832193.28      1533364.45      6832229.73
       1533583.2      6831349.52      1534030.56      6831188.27
#Sta/Elev= 30
  3910.5 1907.12  3999.8 1905.77  4048.6 1905.03  4076.6 1903.56  4086.7 1903.97
  4096.7  1902.9  4136.8 1903.66  4166.9  1902.3  4252.9 1900.94    4320 1898.18
  4357.4 1899.58  4377.4 1897.58  4414.7 1896.35  4519.8 1896.99  4566.3 1896.19
  4685.1 1896.36  4688.3 1895.69  4688.5 1895.19  4692.3 1895.69  4726.5 1896.78
  4731.6 1895.96  4758.8 1897.28    5021 1898.77  5150.4 1903.75  5253.4 1905.76
  5294.6 1907.07  5310.4 1908.45  5403.1 1910.37  5655.4 1915.13  5799.5 1915.53
#Mann= 7 ,-1 , 0
  3910.5     .07       0  3999.8    .035       0  4252.9     .07       0
    4320     .07       0  4688.3     .07       0  4692.3     .07       0
  5403.1     .07       0
Bank Sta=4688.3,4692.3
XS Rating Curve= 0 ,0
Exp/Cntr=0.3,0.1

Type RM Length L Ch R = 1 ,26382   ,409,409,409
BEGIN DESCRIPTION:
Mapping XS 7ccff009
END DESCRIPTION:
XS GIS Cut Line= 3
      1532889.75      6832251.91      1533353.73      6832255.04
      1533954.02      6831850.07
#Sta/Elev= 30
  4292.5 1905.45  4393.8 1903.88  4458.5 1902.11  4497.8 1902.17  4507.8 1901.42
  4527.8 1901.93  4597.8  1900.5  4646.6  1898.4  4663.4 1898.15  4697.8 1899.25
  4727.8    1897  4843.8 1894.88    4906 1894.85    4921 1892.79    4927 1894.06
  4935.9 1892.82    4942 1893.87  4950.9 1892.89  4956.9 1893.97  4969.9 1892.45
  4970.2 1891.95  4973.9 1892.45  5007.9 1893.22  5022.9 1895.05  5043.9 1895.27
  5058.8 1896.92  5079.8 1897.83  5187.8 1900.56  5361.2 1902.23  5480.6 1904.92
#Mann= 7 ,-1 , 0
  4292.5     .07       0  4393.8    .035       0  4646.6     .07       0
  4663.4    .035       0  4843.8     .07       0  4969.9     .07       0
  4973.9     .07       0
Bank Sta=4969.9,4973.9
XS Rating Curve= 0 ,0
Exp/Cntr=0.3,0.1

Type RM Length L Ch R = 1 ,25973   ,115,115,115
BEGIN DESCRIPTION:
Mapping XS 411da65f
END DESCRIPTION:
XS GIS Cut Line= 3
      1532801.98      6832271.41      1533700.13      6832479.53
      1534307.81      6832562.01
#Sta/Elev= 30
  4072.7 1906.27  4229.8 1902.87  4330.6 1901.57  4465.9 1899.42  4474.7  1900.1
  4479.8  1899.2  4486.4 1899.92  4517.2 1898.02  4537.7 1898.63    4548  1898.3
  4565.2 1895.59  4578.8 1894.88  4607.9 1895.68    4613 1893.97  4640.4  1894.7
  4655.7 1893.73  4804.6 1891.37  4836.7 1890.05  4964.7 1889.07  4969.8  1889.6
  5020.6 1888.62  5020.9 1888.12  5024.6 1888.62  5110.6 1889.44  5130.8 1891.43
  5150.9 1894.87  5216.2 1897.56  5240.1 1898.35  5443.6 1899.92  5607.9 1900.14
#Mann= 5 ,-1 , 0
  4072.7     .07       0  4330.6     .07       0  5020.6     .07       0
  5024.6     .07       0  5216.2     .07       0
Bank Sta=5020.6,5024.6
XS Rating Curve= 0 ,0
Exp/Cntr=0.3,0.1

Type RM Length L Ch R = 1 ,25858   ,206,206,206
BEGIN DESCRIPTION:
Mapping XS 7344d408
END DESCRIPTION:
XS GIS Cut Line= 3
      1533272.65      6832499.07       1533702.3      6832594.55
      1534344.69      6832737.79
#Sta/Elev= 30
  4557.1 1896.67    4575  1895.5  4635.6  1893.9  4682.4 1894.73  4723.4 1891.89
  4759.4 1891.41  4784.9 1892.06  4825.9 1889.62  4856.7 1888.85  4877.1 1889.34
  4907.8 1886.99    4959 1887.13  4992.5 1885.43  5001.2 1885.55  5010.2 1887.34
  5020.5 1888.12  5030.7 1885.57  5079.4 1885.63  5082.8 1884.81  5086.5 1885.31
  5102.5  1886.6  5122.9 1889.97    5128 1890.03  5153.7  1893.7  5171.5 1894.61
  5363.9 1896.55  5379.1 1897.73  5399.1 1897.05  5473.2  1897.8  5655.4 1898.46
#Mann= 7 ,-1 , 0
  4557.1    .035       0  4635.6     .12       0  4992.5     .07       0
  5001.2     .12       0  5086.5     .07       0  5363.9    .035       0
  5473.2     .07       0
#XS Ineff= 2 , 0
       0                  5020.5       0 1888.12
Permanent Ineff=
       F       F
Bank Sta=4992.5,5001.2
XS Rating Curve= 0 ,0
Exp/Cntr=0.3,0.1

Type RM Length L Ch R = 1 ,25652   ,215,215,215
BEGIN DESCRIPTION:
Mapping XS b0e91bc6
END DESCRIPTION:
XS GIS Cut Line= 4
       1533160.1      6832740.13      1533691.81      6832787.87
      1533843.72       6832785.7      1534361.19      6832759.72
#Sta/Elev= 30
  4410.9 1895.27  4435.9 1893.79  4486.1 1894.21  4530.9  1892.7  4558.1 1891.85
  4636.7 1891.49  4696.9 1888.95  4757.2 1889.41  4775.3  1887.8  4797.3 1886.76
  4857.6 1886.59  4891.5 1887.78  4907.8 1883.75  4917.8 1881.96  4927.9  1881.2
  4985.9 1881.13  4986.2 1880.63  4989.7 1880.63  4989.9 1881.13  5027.9 1881.47
  5057.9 1884.97  5099.8  1886.8  5146.8 1890.29  5151.8 1890.11    5168 1891.91
  5228.1 1894.02  5346.6  1896.1  5398.3 1897.66  5448.4 1897.05  5614.8 1898.17
#Mann= 4 ,-1 , 0
  4410.9    .035       0  4530.9     .07       0  4985.9     .07       0
  4989.9     .07       0
Bank Sta=4985.9,4989.9
XS Rating Curve= 0 ,0
Exp/Cntr=0.3,0.1

Type RM Length L Ch R = 1 ,25437   ,413,413,413
BEGIN DESCRIPTION:
Mapping XS 41f33aa0
END DESCRIPTION:
XS GIS Cut Line= 6
      1533116.77       6832902.9      1533576.79      6832976.68
      1533650.58       6833011.4      1533693.98      6833015.74
      1533850.23      6832924.59      1534360.14      6832820.44
#Sta/Elev= 30
    4306 1893.58  4334.6    1892  4419.9 1891.97  4431.9 1892.67  4506.8 1889.09
  4567.5 1889.52  4617.7 1886.74  4668.8 1887.25  4689.8 1885.31  4803.1 1888.12
  4814.9 1886.77  4825.2 1887.88  4964.9 1887.76  4970.8 1886.04    4986 1888.27
  5028.2  1887.3  5036.4 1888.28  5072.1 1887.38  5078.2 1884.95  5085.3 1884.78
  5085.6 1884.28  5089.3 1884.78  5103.6  1886.7  5183.2 1890.81  5289.3 1894.26
  5334.7 1893.98  5379.2 1895.89  5430.3 1895.26  5486.2 1897.61  5598.8  1897.5
#Mann= 4 ,-1 , 0
    4306    .035       0  4419.9     .07       0  5085.3     .07       0
  5089.3     .07       0
Bank Sta=5085.3,5089.3
XS Rating Curve= 0 ,0
Exp/Cntr=0.3,0.1

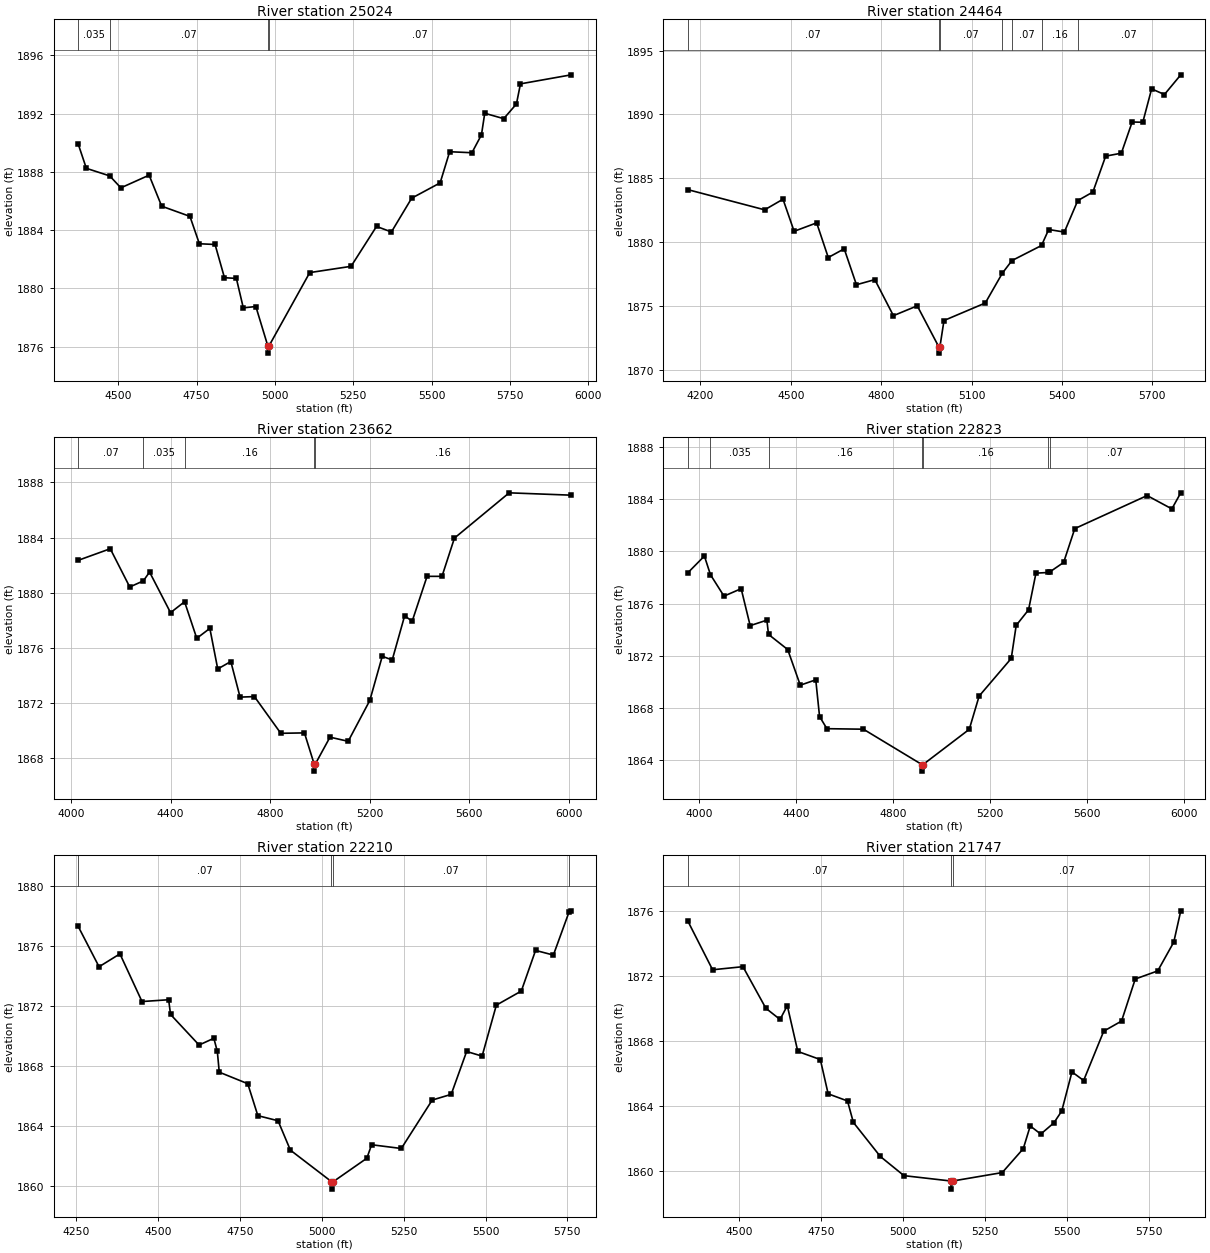
Type RM Length L Ch R = 1 ,25024   ,560,560,560
BEGIN DESCRIPTION:
Mapping XS 23c2e86d
END DESCRIPTION:
XS GIS Cut Line= 3
      1533029.03      6833250.66      1533640.99      6833289.72
      1534587.22      6833124.78
#Sta/Elev= 30
  4371.8 1889.91  4397.8 1888.24  4472.4 1887.72    4508  1886.9  4598.2 1887.77
  4638.3 1885.64  4728.5 1884.94  4758.6 1883.06  4808.7 1883.01  4838.7 1880.73
  4876.7 1880.68  4898.8 1878.66  4938.9 1878.75    4977 1876.05  4977.3 1875.55
    4981 1876.05  5110.9 1881.08  5242.8 1881.51  5324.1 1884.25  5371.6 1883.87
  5436.3 1886.19  5527.1 1887.24  5557.5 1889.38  5628.6 1889.31    5659 1890.54
  5669.5 1892.02  5730.1 1891.65  5770.7 1892.66  5783.5 1894.04  5945.5 1894.66
#Mann= 4 ,-1 , 0
  4371.8    .035       0  4472.4     .07       0    4977     .07       0
    4981     .07       0
Bank Sta=4977,4981
XS Rating Curve= 0 ,0
Exp/Cntr=0.3,0.1

Type RM Length L Ch R = 1 ,24464   ,802,802,802
BEGIN DESCRIPTION:
Mapping XS 45ae5015
END DESCRIPTION:
XS GIS Cut Line= 3
      1533063.74      6833914.72      1533701.75      6833801.87
      1534542.15      6833282.04
#Sta/Elev= 30
    4158 1884.12  4413.2 1882.54  4474.1 1883.37    4511 1880.86  4585.8 1881.52
  4624.3 1878.81  4677.2 1879.49  4717.8 1876.68  4778.8 1877.08  4840.5 1874.26
  4919.6 1875.03  4990.9 1871.83  4991.2 1871.33  4994.9 1871.83  5008.3 1873.88
  5145.4 1875.25  5202.2 1877.59  5233.9 1878.57    5332 1879.75  5355.8    1881
  5407.8  1880.8  5452.2 1883.26  5502.4 1883.93  5544.9 1886.74  5596.9 1886.97
  5632.8 1889.41  5668.1 1889.39  5697.4    1892  5739.9 1891.56  5794.1  1893.1
#Mann= 7 ,-1 , 0
    4158     .07       0  4990.9     .07       0  4994.9     .07       0
  5202.2     .16       0  5233.9     .07       0    5332     .16       0
  5452.2     .07       0
Bank Sta=4990.9,4994.9
XS Rating Curve= 0 ,0
Exp/Cntr=0.3,0.1

Type RM Length L Ch R = 1 ,23662   ,839,839,839
BEGIN DESCRIPTION:
Mapping XS 25afc0f1
END DESCRIPTION:
XS GIS Cut Line= 3
      1532982.69        6834108.      1533911.53      6834416.17
      1534914.14      6834385.78
#Sta/Elev= 30
  4028.3 1882.35  4157.2 1883.19  4235.5 1880.42  4290.1 1880.86  4315.2  1881.5
  4399.5 1878.56  4455.9 1879.35  4504.9  1876.7  4557.5 1877.42  4589.2 1874.48
  4641.8 1875.02    4679 1872.44  4736.6 1872.48  4842.7 1869.82  4937.7 1869.85
    4977 1867.58  4977.2 1867.08    4981 1867.58  5040.4 1869.54  5113.5 1869.24
  5200.5  1872.2  5250.5  1875.4  5290.5 1875.13  5340.6 1878.34  5370.6 1877.93
  5430.6 1881.19  5490.6 1881.19  5540.6 1883.96  5760.7 1887.24    6010 1887.07
#Mann= 5 ,-1 , 0
  4028.3     .07       0  4290.1    .035       0  4455.9     .16       0
    4977     .07       0    4981     .16       0
#XS Ineff= 2 , 0
       0  4937.7 1869.85               0
Permanent Ineff=
       F       F
Bank Sta=4977,4981
XS Rating Curve= 0 ,0
Exp/Cntr=0.3,0.1

Type RM Length L Ch R = 1 ,22823   ,613,613,613
BEGIN DESCRIPTION:
Mapping XS d40b6638
END DESCRIPTION:
XS GIS Cut Line= 3
       1532717.1      6834974.33      1533753.55      6835130.58
      1534721.13       6834938.1
#Sta/Elev= 30
  3951.7 1878.35  4020.4 1879.64  4045.4 1878.21  4101.3 1876.57  4172.1 1877.14
  4209.3 1874.31  4278.2 1874.73    4285 1873.64  4364.2 1872.48  4416.1 1869.75
    4480 1870.16  4495.7 1867.35    4526 1866.42  4676.7 1866.38  4918.4 1863.67
  4918.7 1863.17  4922.4 1863.67  5113.5 1866.37  5154.3 1868.92  5286.8  1871.8
  5307.2 1874.33  5358.2 1875.52  5388.8 1878.33    5440 1878.38  5444.9 1878.41
    5503 1879.15    5549 1881.74  5847.6 1884.27  5949.6 1883.25  5986.4 1884.48
#Mann= 7 ,-1 , 0
  3951.7     .07       0  4045.4    .035       0    4285     .16       0
  4918.4     .07       0  4922.4     .16       0    5440    .035       0
  5444.9     .07       0
Bank Sta=4918.4,4922.4
XS Rating Curve= 0 ,0
Exp/Cntr=0.3,0.1

Type RM Length L Ch R = 1 ,22210   ,463,463,463
BEGIN DESCRIPTION:
BULL WAGON CREEK TRIBUTARY 6 31.0
END DESCRIPTION:
XS GIS Cut Line= 3
      1532905.01        6835438.        1533605.        6835688.
      1534305.03      6835387.99
#Sta/Elev= 30
  4256.7  1877.3  4320.4 1874.61  4384.1 1875.47  4451.5 1872.29  4532.8 1872.41
  4538.6 1871.43  4625.7 1869.39  4670.8 1869.84  4681.4 1868.96  4687.3 1867.58
  4774.3 1866.81  4805.1 1864.68  4866.7 1864.34  4904.4 1862.38  5029.9 1860.28
  5030.3 1859.78  5035.4 1860.28  5137.8 1861.84  5152.3 1862.74    5243 1862.49
  5337.3 1865.72  5395.3  1866.1  5442.4 1868.96  5489.6 1868.65  5533.1 1872.05
  5609.3 1872.99  5652.8  1875.7  5707.2 1875.39  5755.3 1878.28  5761.6 1878.34
#Mann= 4 ,-1 , 0
  4256.7     .07       0  5029.9     .07       0  5035.4     .07       0
  5755.3    .035       0
Bank Sta=5029.9,5035.4
XS Rating Curve= 0 ,0
Exp/Cntr=0.3,0.1

Type RM Length L Ch R = 1 ,21747   ,385,385,385
BEGIN DESCRIPTION:
BULL WAGON CREEK TRIBUTARY 6 30.0
END DESCRIPTION:
XS GIS Cut Line= 3
      1532955.03      6835888.01        1533555.        6836138.
      1534355.03      6835837.99
#Sta/Elev= 30
  4343.4 1875.38  4419.2 1872.37  4511.8 1872.56  4581.7    1870    4625 1869.31
  4647.2 1870.16  4679.2 1867.34    4748 1866.84  4771.8 1864.73  4830.9 1864.29
  4848.7 1862.97  4931.1 1860.87  5003.2 1859.69  5146.4 1859.36  5146.8 1858.86
  5151.9 1859.36  5303.1 1859.88  5367.2 1861.35  5388.5 1862.75  5420.6 1862.25
  5460.6 1862.94  5484.6 1863.67  5515.8 1866.08  5551.4 1865.55  5612.8 1868.59
  5667.1 1869.21  5708.9  1871.8  5777.5  1872.3  5826.4 1874.07  5847.8    1876
#Mann= 3 ,-1 , 0
  4343.4     .07       0  5146.4     .07       0  5151.9     .07       0
Bank Sta=5146.4,5151.9
XS Rating Curve= 0 ,0
Exp/Cntr=0.3,0.1

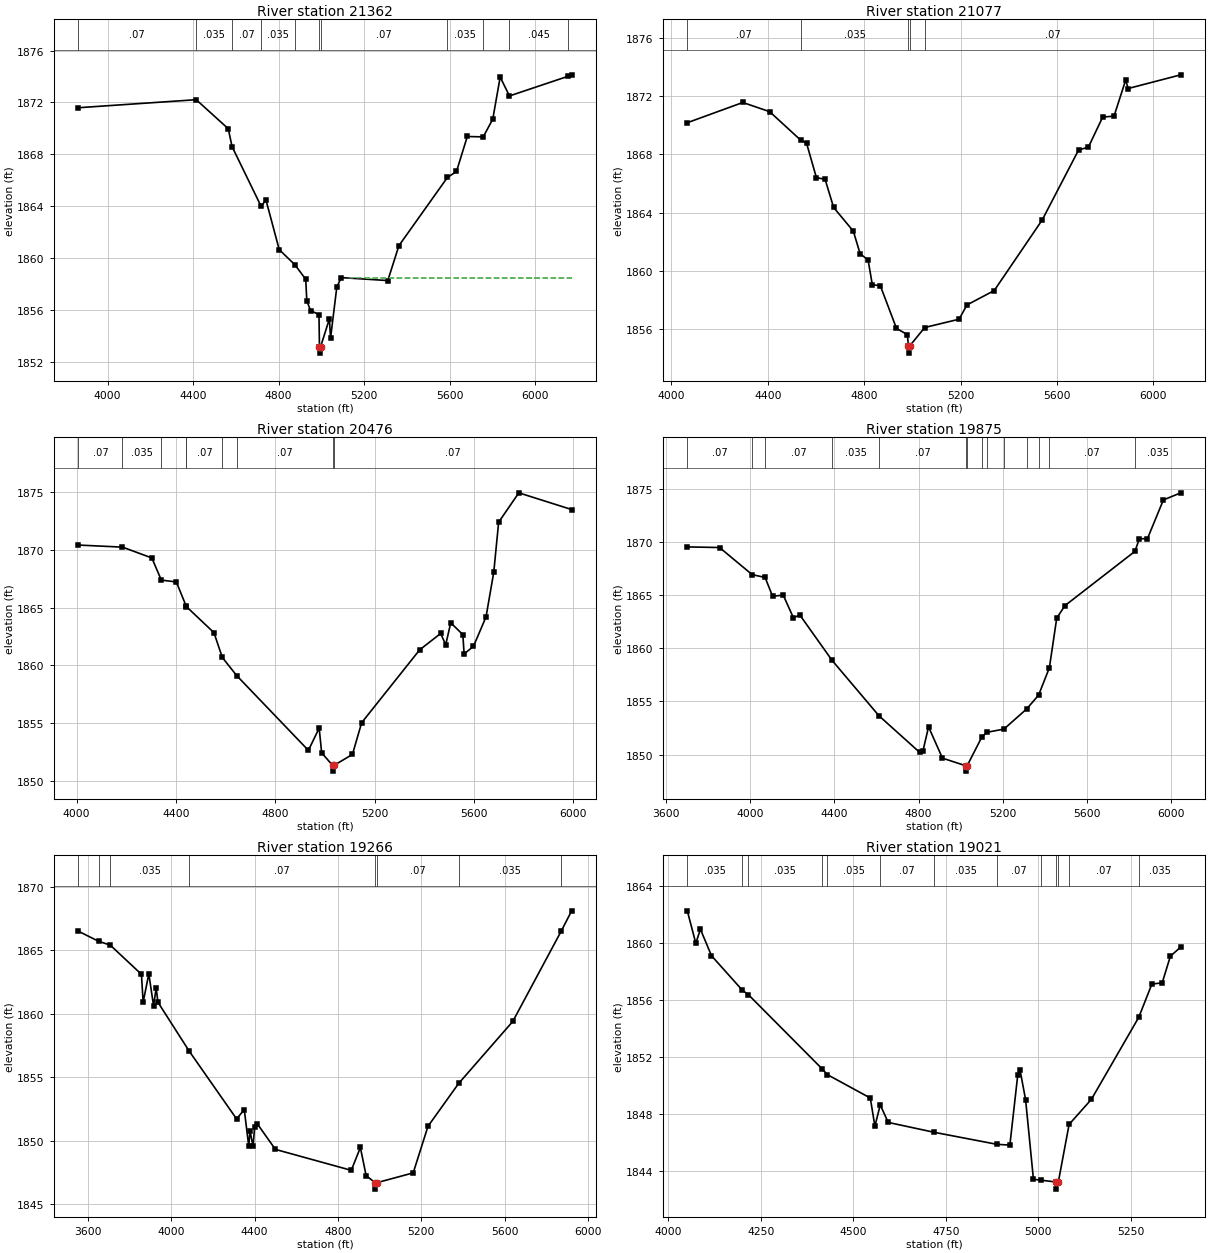
Type RM Length L Ch R = 1 ,21362   ,285,285,285
BEGIN DESCRIPTION:
Mapping XS 9a09b9f9
END DESCRIPTION:
XS GIS Cut Line= 3
      1532382.02      6836324.15      1533519.17      6836506.44
      1534634.66      6836810.27
#Sta/Elev= 30
  3862.5 1871.59  4414.3 1872.21  4564.3 1869.97    4582 1868.59  4717.9 1863.98
  4740.6 1864.47  4802.6 1860.64  4876.5 1859.46  4926.6 1858.35  4931.6 1856.69
  4949.2 1855.93  4988.5 1855.63  4990.8 1853.15  4991.2 1852.65  4996.3 1853.15
  5037.4  1855.3  5042.6 1853.79    5072 1857.76  5092.8 1858.48  5310.5 1858.25
  5362.2 1860.94  5589.3 1866.21  5631.7 1866.67  5682.2 1869.37  5756.7 1869.34
  5801.4 1870.71    5836 1873.96  5879.4  1872.5    6152 1874.01  6170.3 1874.13
#Mann= 11 ,-1 , 0
  3862.5     .07       0  4414.3    .035       0    4582     .07       0
  4717.9    .035       0  4876.5     .07       0  4990.8     .07       0
  4996.3     .07       0  5589.3    .035       0  5756.7     .07       0
  5879.4    .045       0    6152     .07       0
#XS Ineff= 2 , 0
       0                  5123.9       0 1858.46
Permanent Ineff=
       F       F
Bank Sta=4990.8,4996.3
XS Rating Curve= 0 ,0
Exp/Cntr=0.3,0.1

Type RM Length L Ch R = 1 ,21077   ,601,601,601
BEGIN DESCRIPTION:
Mapping XS 09adb22e
END DESCRIPTION:
XS GIS Cut Line= 3
      1532490.48       6836567.2      1533393.31      6836753.84
       1534487.1      6837018.61
#Sta/Elev= 30
  4066.3 1870.17  4296.6 1871.56  4407.9 1870.93  4536.9 1868.97  4561.1 1868.76
  4601.9  1866.4    4638 1866.28  4673.4 1864.35  4755.1 1862.72  4783.5 1861.16
  4816.3 1860.75  4833.8 1859.05  4867.4 1858.96  4934.2 1856.04  4979.3 1855.61
  4983.7 1854.84  4984.1 1854.34  4989.4 1854.84  5051.3  1856.1  5193.9 1856.67
  5226.6 1857.65  5339.8 1858.64  5538.8 1863.49  5689.6 1868.29  5730.7  1868.5
  5789.8 1870.56  5836.8 1870.62  5885.1  1873.1  5895.4 1872.52  6113.6 1873.46
#Mann= 5 ,-1 , 0
  4066.3     .07       0  4536.9    .035       0  4983.7    .035       0
  4989.4    .035       0  5051.3     .07       0
Bank Sta=4983.7,4989.4
XS Rating Curve= 0 ,0
Exp/Cntr=0.3,0.1

Type RM Length L Ch R = 1 ,20476   ,601,601,601
BEGIN DESCRIPTION:
Mapping XS 9a931418
END DESCRIPTION:
XS GIS Cut Line= 3
      1532572.99      6836687.87      1533375.08      6837255.58
       1534364.7      6837427.46
#Sta/Elev= 30
  4006.3 1870.43  4184.6 1870.25  4302.8 1869.31    4341 1867.39  4401.5 1867.23
  4441.7  1865.1    4442 1865.09  4552.9 1862.83  4586.6 1860.68  4644.8  1859.1
  4933.2 1852.62  4976.6 1854.55  4986.7 1852.41  5030.6 1851.32  5031.1 1850.82
  5036.4 1851.32  5110.7 1852.27  5147.7 1855.02  5381.3 1861.34  5465.9 1862.76
  5486.2 1861.78  5506.5 1863.69  5555.2 1862.66  5560.3 1860.99  5597.9 1861.64
  5648.6  1864.2  5679.7 1868.07  5699.4 1872.41  5780.6 1874.96  5993.4 1873.51
#Mann= 9 ,-1 , 0
  4006.3     .07       0  4184.6    .035       0    4341     .07       0
  4441.7    .035       0    4442     .07       0  4586.6    .035       0
  4644.8     .07       0  5030.6     .07       0  5036.4     .07       0
Bank Sta=5030.6,5036.4
XS Rating Curve= 0 ,0
Exp/Cntr=0.3,0.1

Type RM Length L Ch R = 1 ,19875   ,609,609,609
BEGIN DESCRIPTION:
Mapping XS 37312e26
END DESCRIPTION:
XS GIS Cut Line= 3
      1532511.35      6836730.38      1533245.74      6837818.94
      1534178.06      6838256.46
#Sta/Elev= 30
  3701.7 1869.52  3854.9 1869.46  4009.9 1866.91    4071 1866.65  4106.7 1864.88
  4157.2 1864.99  4205.7 1862.85  4235.7 1863.13  4388.6 1858.87  4611.8 1853.65
  4805.2 1850.21  4820.2 1850.31  4847.2 1852.61  4913.2 1849.67  5024.5 1848.95
    5025 1848.45  5030.4 1848.95  5101.2 1851.69  5124.9  1852.1  5205.1  1852.4
    5313 1854.29  5369.7 1855.59  5420.9 1858.16  5455.9 1862.83  5494.8    1864
  5827.1  1869.1  5848.1 1870.28  5886.7  1870.3  5962.2 1873.93  6044.7  1874.6
#Mann= 14 ,-1 , 0
  3701.7     .07       0  4009.9    .035       0    4071     .07       0
  4388.6    .035       0  4611.8     .07       0  5024.5     .07       0
  5030.4     .07       0  5101.2    .035       0  5124.9     .07       0
  5205.1    .035       0    5313     .07       0  5369.7    .035       0
  5420.9     .07       0  5827.1    .035       0
Bank Sta=5024.5,5030.4
XS Rating Curve= 0 ,0
Exp/Cntr=0.3,0.1

Type RM Length L Ch R = 1 ,19266   ,245,245,245
BEGIN DESCRIPTION:
Mapping XS 39305861
END DESCRIPTION:
XS GIS Cut Line= 3
       1531714.5      6837303.33      1532865.53      6838157.49
      1533661.19      6838651.52
#Sta/Elev= 30
  3552.5 1866.49  3650.6 1865.69  3706.3 1865.39  3856.1 1863.09  3864.4 1860.89
  3891.6 1863.13  3914.3 1860.62    3927 1862.01  3935.4 1860.89  4085.1 1857.05
    4313  1851.7  4350.1 1852.43  4371.5 1849.56  4377.7 1850.76  4392.3 1849.53
  4399.9 1851.09  4413.2  1851.3  4499.5  1849.3  4863.9 1847.65  4907.7 1849.45
  4935.4 1847.23  4979.4 1846.67  4979.9 1846.17  4985.3 1846.67  5161.4 1847.45
  5232.4 1851.12  5379.5 1854.49  5639.7 1859.38  5873.2 1866.52  5922.4 1868.09
#Mann= 8 ,-1 , 0
  3552.5    .035       0  3650.6     .07       0  3706.3    .035       0
  4085.1     .07       0  4979.4     .07       0  4985.3     .07       0
  5379.5    .035       0  5873.2     .07       0
Bank Sta=4979.4,4985.3
XS Rating Curve= 0 ,0
Exp/Cntr=0.3,0.1

Type RM Length L Ch R = 1 ,19021   ,692,692,692
BEGIN DESCRIPTION:
BULL WAGON CREEK TRIBUTARY 6 24.0
END DESCRIPTION:
XS GIS Cut Line= 3
      1531905.02      6837838.01        1532705.        6838338.
      1532955.01      6838638.01
#Sta/Elev= 30
  4051.2 1862.28  4074.2    1860  4086.6 1860.99  4116.6 1859.13  4200.4  1856.7
  4215.9 1856.41  4414.7 1851.22  4429.9 1850.79  4545.9 1849.15  4558.3 1847.17
  4572.8 1848.67  4594.2 1847.44  4717.8 1846.75  4888.7  1845.9  4923.2 1845.85
  4944.5 1850.77  4950.4 1851.15  4965.7 1849.03  4986.9 1843.45  5006.1 1843.39
  5048.2 1843.26  5048.7 1842.76  5054.2 1843.26  5083.3  1847.3  5143.6 1849.06
  5271.6 1854.81    5307 1857.14    5335 1857.23  5357.1  1859.1  5385.1 1859.74
#Mann= 13 ,-1 , 0
  4051.2    .035       0  4200.4     .07       0  4215.9    .035       0
  4414.7     .07       0  4429.9    .035       0  4572.8     .07       0
  4717.8    .035       0  4888.7     .07       0  5006.1     .16       0
  5048.2     .07       0  5054.2     .16       0  5083.3     .07       0
  5271.6    .035       0
Bank Sta=5048.2,5054.2
XS Rating Curve= 0 ,0
Exp/Cntr=0.3,0.1

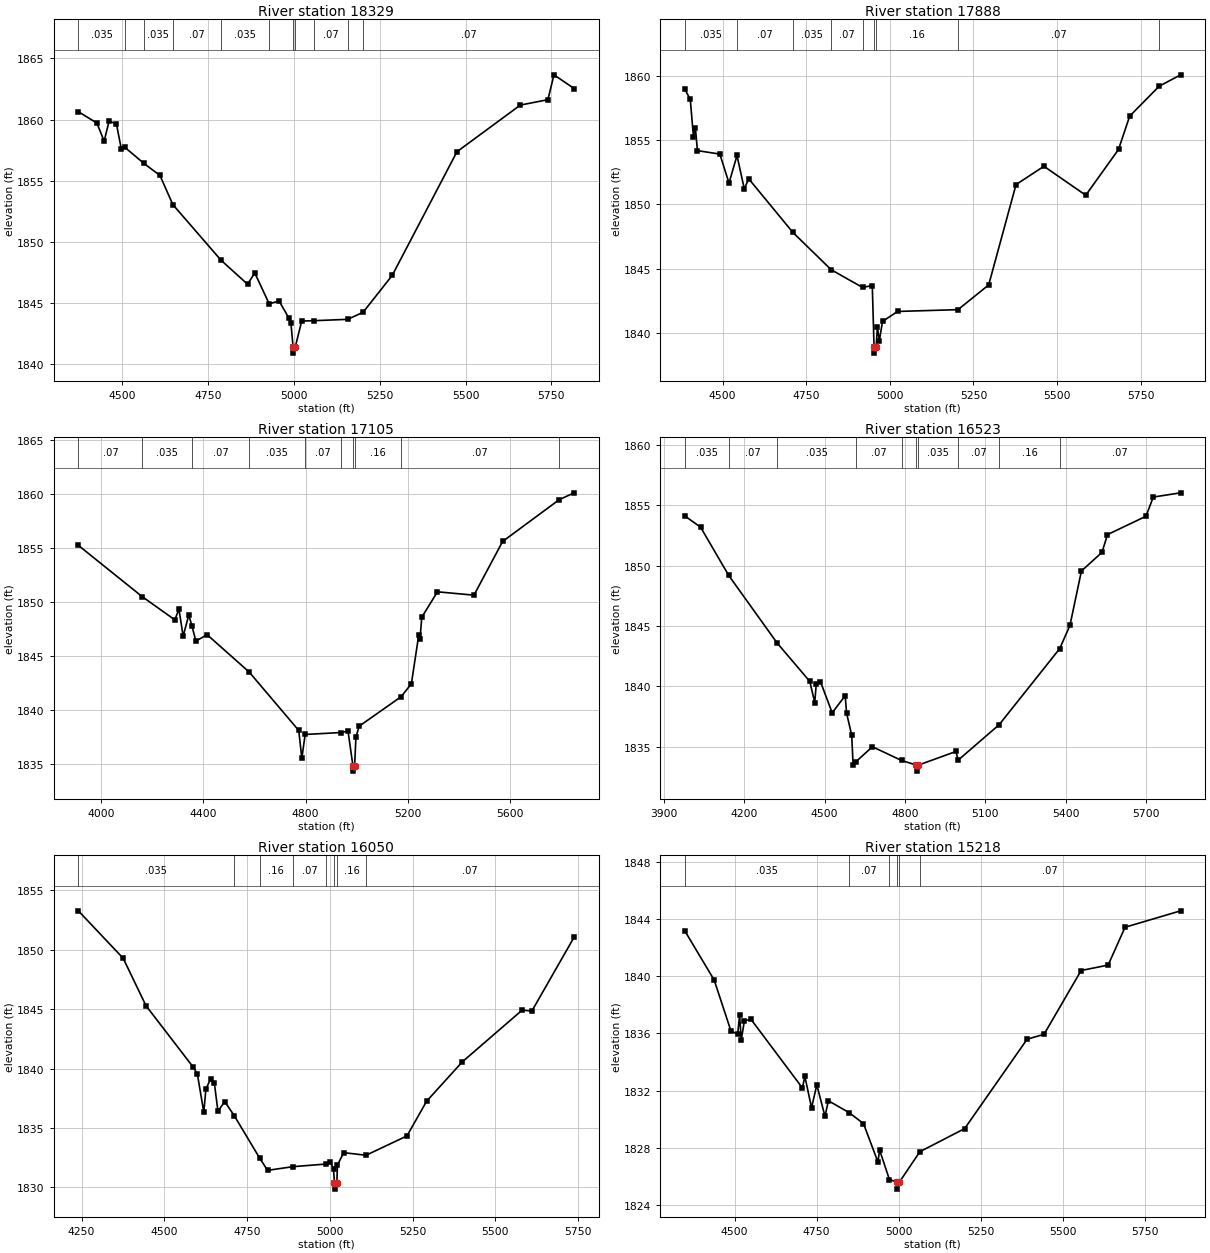
Type RM Length L Ch R = 1 ,18329   ,441,441,441
BEGIN DESCRIPTION:
Mapping XS 0e2aed04
END DESCRIPTION:
XS GIS Cut Line= 3
      1531730.98      6838175.72      1532151.99      6838622.76
      1532907.21      6838965.65
#Sta/Elev= 30
  4372.7 1860.64  4426.8 1859.71  4447.8 1858.23    4462 1859.84  4483.4 1859.67
  4497.6 1857.63  4507.7 1857.74  4563.8 1856.41  4610.4 1855.43  4647.9 1853.05
  4788.1 1848.51  4865.3 1846.55  4886.4 1847.47  4928.3 1844.95  4957.2 1845.18
  4985.3  1843.8  4991.5  1843.4  4997.9 1841.42  4998.4 1840.92  5004.3 1841.42
    5023 1843.54  5059.7 1843.57  5156.7 1843.68  5201.5 1844.25  5286.6 1847.27
    5475 1857.37  5659.6 1861.18  5739.8 1861.62  5757.4 1863.65  5816.2 1862.53
#Mann= 11 ,-1 , 0
  4372.7    .035       0  4507.7     .07       0  4563.8    .035       0
  4647.9     .07       0  4788.1    .035       0  4928.3     .16       0
  4997.9     .07       0  5004.3     .16       0  5059.7     .07       0
  5156.7     .16       0  5201.5     .07       0
Bank Sta=4997.9,5004.3
XS Rating Curve= 0 ,0
Exp/Cntr=0.3,0.1

Type RM Length L Ch R = 1 ,17888   ,783,783,783
BEGIN DESCRIPTION:
Mapping XS 51d3bfe3
END DESCRIPTION:
XS GIS Cut Line= 3
       1531533.1      6838706.12      1532046.95      6839029.01
      1532887.26      6839275.55
#Sta/Elev= 30
  4386.9 1858.99  4403.3 1858.19  4412.7 1855.29  4418.6 1855.99  4424.6  1854.2
  4491.7 1853.93  4519.1 1851.67    4543 1853.82  4564.7 1851.22  4578.1    1852
  4709.8 1847.83  4824.7 1844.91  4918.6 1843.53  4947.5 1843.68  4952.8 1838.91
  4953.3 1838.41  4959.2 1838.91  4962.8 1840.45  4968.7 1839.39  4978.1 1840.88
    5023 1841.66  5203.9  1841.8  5295.6 1843.73  5377.3 1851.55  5460.7 1852.98
  5585.8 1850.72  5683.8 1854.29  5717.2 1856.89  5805.3 1859.22  5869.5 1860.11
#Mann= 9 ,-1 , 0
  4386.9    .035       0    4543     .07       0  4709.8    .035       0
  4824.7     .07       0  4918.6     .16       0  4952.8     .07       0
  4959.2     .16       0  5203.9     .07       0  5805.3    .035       0
Bank Sta=4952.8,4959.2
XS Rating Curve= 0 ,0
Exp/Cntr=0.3,0.1

Type RM Length L Ch R = 1 ,17105   ,582,582,582
BEGIN DESCRIPTION:
Mapping XS 9becd8d7
END DESCRIPTION:
XS GIS Cut Line= 3
      1531140.73      6839160.97      1532102.51      6839664.43
      1532939.29      6839831.09
#Sta/Elev= 30
  3911.4 1855.27  4161.8  1850.5  4288.7 1848.36  4304.8 1849.35  4321.2 1846.84
  4343.3 1848.81  4355.3 1847.82    4371 1846.39  4415.1 1846.98  4579.5 1843.52
  4773.3  1838.1  4785.3 1835.52  4798.3 1837.73    4939 1837.91  4965.9 1838.05
  4985.1 1834.83  4985.6 1834.33  4991.7 1834.83    4997 1837.51  5009.7  1838.5
  5173.5 1841.23  5213.7 1842.43  5242.4 1846.93  5247.5 1846.62  5254.4  1848.6
  5315.6 1850.96  5458.4 1850.65  5570.5 1855.63  5792.1 1859.51  5850.2 1860.14
#Mann= 10 ,-1 , 0
  3911.4     .07       0  4161.8    .035       0  4355.3     .07       0
  4579.5    .035       0  4798.3     .07       0    4939     .16       0
  4985.1     .07       0  4991.7     .16       0  5173.5     .07       0
  5792.1    .035       0
Bank Sta=4985.1,4991.7
XS Rating Curve= 0 ,0
Exp/Cntr=0.3,0.1

Type RM Length L Ch R = 1 ,16523   ,473,473,473
BEGIN DESCRIPTION:
Mapping XS c897a2d2
END DESCRIPTION:
XS GIS Cut Line= 3
      1530924.54      6839691.33      1531883.76      6840073.28
      1532681.18       6840255.3
#Sta/Elev= 30
  3978.4 1854.11  4037.5 1853.17  4142.3 1849.18  4322.5  1843.6  4444.8 1840.41
  4463.3 1838.66  4469.1 1840.21  4484.8 1840.38  4528.4 1837.81  4576.9 1839.22
  4582.3 1837.77  4601.2 1835.96  4606.6 1833.49  4617.2 1833.76  4678.5    1835
  4787.4 1833.86    4843 1833.48  4843.5 1832.98  4850.2 1833.48  4990.7 1834.61
  4998.1 1833.88  5151.4 1836.82  5377.5 1843.12  5415.7 1845.04  5458.6 1849.55
  5535.3 1851.09  5555.8 1852.56  5699.4 1854.08  5726.8 1855.67  5828.8 1856.02
#Mann= 10 ,-1 , 0
  3978.4    .035       0  4142.3     .07       0  4322.5    .035       0
  4617.2     .07       0  4787.4    .035       0    4843     .07       0
  4850.2    .035       0  4998.1     .07       0  5151.4     .16       0
  5377.5     .07       0
Bank Sta=4843,4850.2
XS Rating Curve= 0 ,0
Exp/Cntr=0.3,0.1

Type RM Length L Ch R = 1 ,16050   ,832,832,832
BEGIN DESCRIPTION:
Mapping XS 85df8421
END DESCRIPTION:
XS GIS Cut Line= 3
       1530927.2      6840085.45      1531642.44      6840335.44
      1532329.97      6840609.75
#Sta/Elev= 30
  4240.3 1853.28  4375.7 1849.29  4444.8 1845.29  4587.5 1840.12    4600 1839.53
  4619.3 1836.34  4625.8 1838.29  4640.5 1839.16  4651.1 1838.81  4662.1 1836.41
  4682.5 1837.23  4711.6 1836.03  4788.1 1832.47    4812 1831.44  4888.7 1831.75
  4988.1 1831.97    5002 1832.14  5011.5 1831.53  5013.9 1830.36  5014.4 1829.86
  5021.3 1830.36    5023 1831.88  5041.9 1832.93  5109.5 1832.71  5233.2 1834.34
  5292.5 1837.26  5400.3 1840.57  5580.9 1844.92  5610.5 1844.85  5738.2 1851.07
#Mann= 8 ,-1 , 0
  4240.3    .035       0  4711.6     .07       0  4788.1     .16       0
  4888.7     .07       0  4988.1     .16       0  5013.9     .07       0
  5021.3     .16       0  5109.5     .07       0
Bank Sta=5013.9,5021.3
XS Rating Curve= 0 ,0
Exp/Cntr=0.3,0.1

Type RM Length L Ch R = 1 ,15218   ,213,213,213
BEGIN DESCRIPTION:
Mapping XS 416dcb97
END DESCRIPTION:
XS GIS Cut Line= 3
      1530767.48      6840717.39      1531406.33      6840856.27
      1532239.67      6841057.66
#Sta/Elev= 30
  4348.3 1843.19  4437.9 1839.74    4489 1836.17  4509.5 1835.96  4515.3 1837.28
  4520.4 1835.55    4530  1836.9  4550.4 1836.98  4706.6 1832.19  4714.2 1832.99
  4734.6  1830.8  4750.6  1832.4  4775.6 1830.19  4785.8 1831.29  4848.9 1830.46
  4892.9 1829.69  4936.9    1827    4942 1827.84  4972.1 1825.76  4995.1  1825.6
  4995.6  1825.1  5002.6  1825.6  5064.7 1827.72  5201.2 1829.34  5391.6  1835.6
  5443.1 1835.94  5556.2 1840.41  5638.5 1840.79    5690 1843.44  5859.4 1844.59
#Mann= 6 ,-1 , 0
  4348.3    .035       0  4848.9     .07       0  4972.1    .035       0
  4995.1    .035       0  5002.6    .035       0  5064.7     .07       0
Bank Sta=4995.1,5002.6
XS Rating Curve= 0 ,0
Exp/Cntr=0.3,0.1