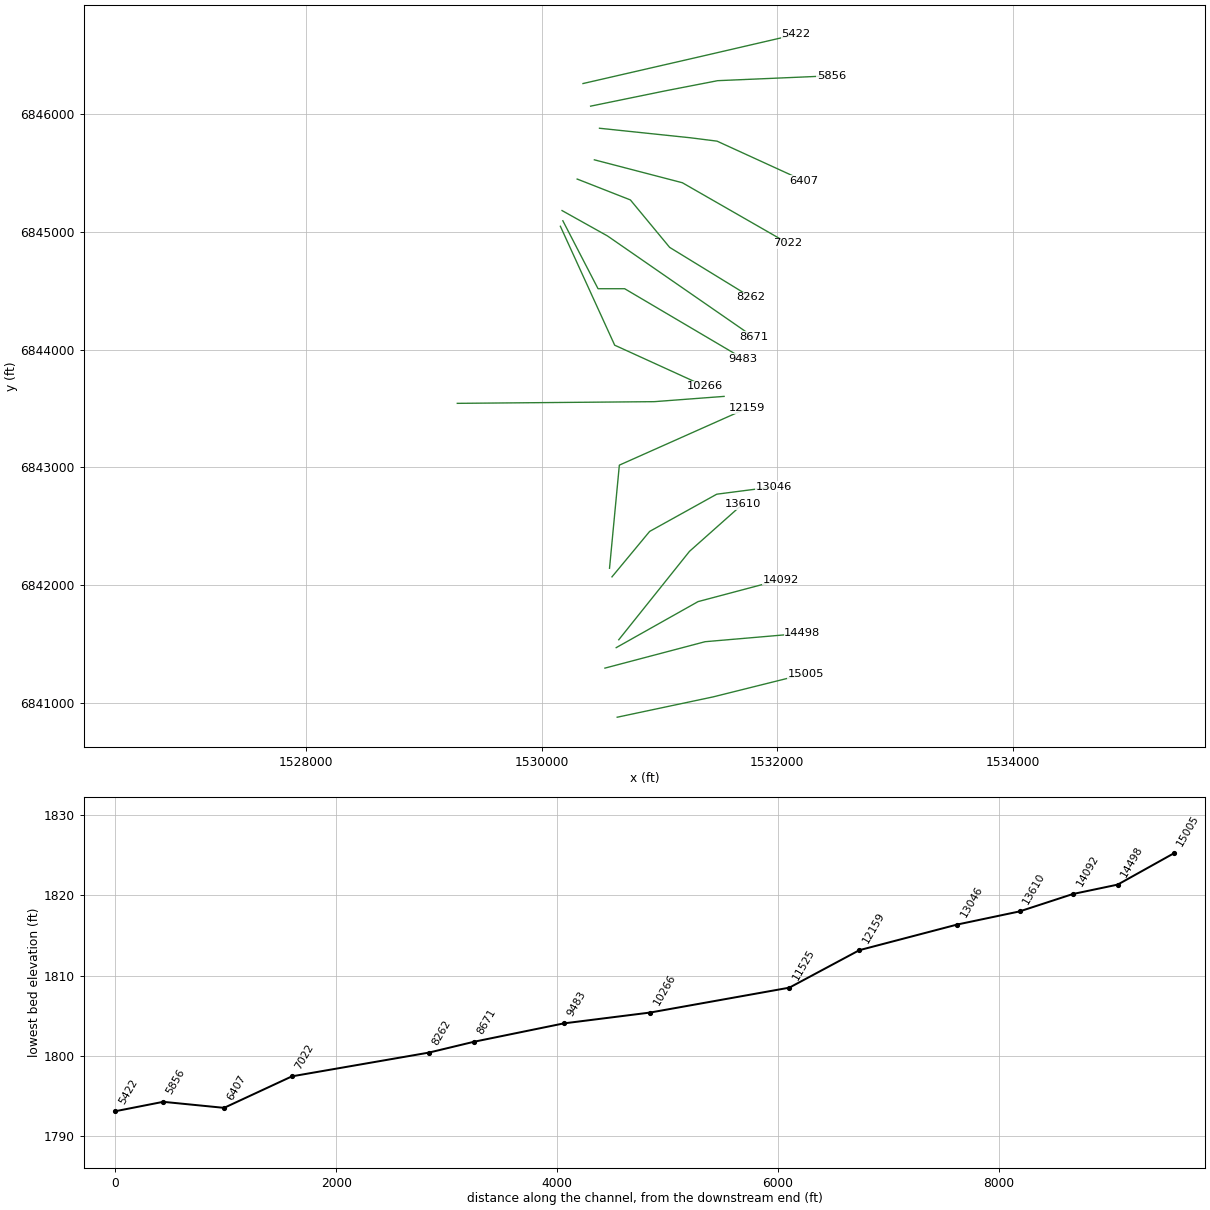
HEC-RAS study BULL WAGON CREEK TRIBUTARY 6.prj: BULL WAGON CREEK TRIBUTARY 6 Base Level Engineering

--- BULL WAGON CREEK TRIBUTARY 6.g01 (geometry) --- (continued)

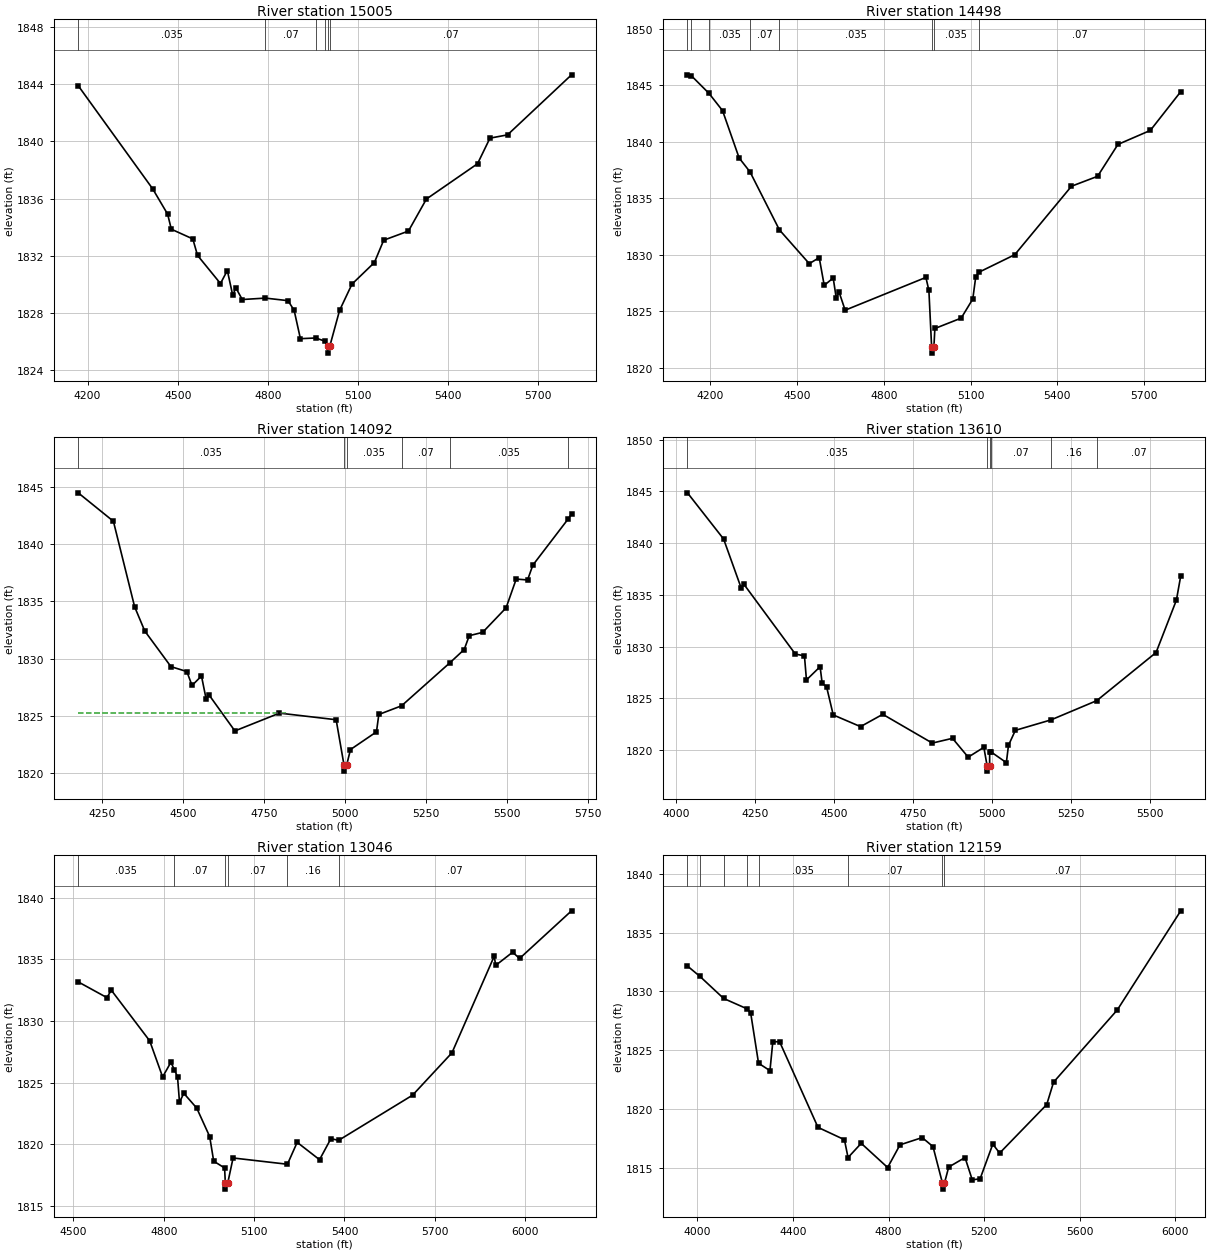
Type RM Length L Ch R = 1 ,15005   ,507,507,507
BEGIN DESCRIPTION:
BULL WAGON CREEK TRIBUTARY 6 15.0
END DESCRIPTION:
XS GIS Cut Line= 3
       1530641.8      6840880.63      1531455.04      6841052.98
      1532241.65      6841249.13
#Sta/Elev= 30
  4168.7  1843.9  4416.7 1836.68  4466.4 1834.91  4478.6 1833.86  4550.2 1833.18
  4565.8 1832.03  4642.2 1830.06  4665.1 1830.97  4683.1 1829.23  4693.3 1829.76
  4714.8 1828.94  4791.9 1829.04  4867.1 1828.86  4887.5 1828.18  4908.3  1826.2
    4959 1826.25  4990.6 1826.02  4998.8 1825.69  4999.3 1825.19  5006.3 1825.69
  5038.7 1828.18    5080 1830.02  5154.6 1831.53  5185.5 1833.09  5267.9 1833.73
  5327.7 1835.97  5497.9 1838.44  5539.2 1840.23  5597.7 1840.46  5810.7 1844.66
#Mann= 6 ,-1 , 0
  4168.7    .035       0  4791.9     .07       0    4959    .035       0
  4990.6     .07       0  4998.8     .07       0  5006.3     .07       0
Bank Sta=4998.8,5006.3
XS Rating Curve= 0 ,0
Exp/Cntr=0.3,0.1

Type RM Length L Ch R = 1 ,14498   ,406,406,406
BEGIN DESCRIPTION:
BULL WAGON CREEK TRIBUTARY 6 14.0
END DESCRIPTION:
XS GIS Cut Line= 3
       1530537.6      6841297.29      1531387.46      6841521.34
      1532211.51      6841592.31
#Sta/Elev= 30
  4121.1 1845.94  4134.2 1845.87  4195.6  1844.3  4242.5 1842.77  4299.9 1838.58
  4337.5 1837.35  4439.1 1832.22  4542.4 1829.23  4576.8 1829.76  4594.1 1827.31
  4625.2 1827.96  4635.5 1826.21  4645.8 1826.69  4666.5 1825.11  4945.7 1828.01
  4956.1 1826.86  4965.6 1821.81  4966.1 1821.31  4973.3 1821.81  4976.8 1823.49
  5067.8 1824.41  5107.9  1826.1    5118 1828.04  5129.1 1828.47    5253 1830.02
  5449.2 1836.08  5539.5 1836.96  5609.8 1839.78  5721.9 1841.02  5827.1 1844.45
#Mann= 8 ,-1 , 0
  4121.1    .035       0  4134.2     .07       0  4195.6    .035       0
  4337.5     .07       0  4439.1    .035       0  4965.6    .035       0
  4973.3    .035       0  5129.1     .07       0
#XS Ineff= 2 , 0
       0  4945.7 1828.01               0
Permanent Ineff=
       F       F
Bank Sta=4965.6,4973.3
XS Rating Curve= 0 ,0
Exp/Cntr=0.3,0.1

Type RM Length L Ch R = 1 ,14092   ,482,482,482
BEGIN DESCRIPTION:
Mapping XS e6de8668
END DESCRIPTION:
XS GIS Cut Line= 3
      1530633.12      6841470.91      1531327.56      6841861.53
      1532030.36      6842048.08
#Sta/Elev= 30
  4175.3 1844.51    4284 1842.02  4349.6 1834.53  4380.9 1832.41  4461.8 1829.29
  4510.9 1828.86  4526.9 1827.64  4556.1 1828.47  4570.2 1826.49    4579 1826.83
  4659.3 1823.66  4797.1 1825.22  4972.1 1824.64  4996.6 1820.64  4997.1 1820.14
  5004.3 1820.64  5016.4 1822.03  5096.7 1823.58  5103.9  1825.1  5174.2 1825.86
  5322.8 1829.61  5367.7 1830.79  5383.3    1832  5424.6 1832.29  5497.1 1834.44
  5528.4 1836.96  5563.4 1836.88  5579.8 1838.18  5688.8 1842.22  5699.2 1842.66
#Mann= 6 ,-1 , 0
  4175.3    .035       0  4996.6    .035       0  5004.3    .035       0
  5174.2     .07       0  5322.8    .035       0  5688.8     .07       0
#XS Ineff= 2 , 0
       0    4820 1825.27               0
Permanent Ineff=
       F       F
Bank Sta=4996.6,5004.3
XS Rating Curve= 0 ,0
Exp/Cntr=0.3,0.1

Type RM Length L Ch R = 1 ,13610   ,564,564,564
BEGIN DESCRIPTION:
BULL WAGON CREEK TRIBUTARY 6 13.0
END DESCRIPTION:
XS GIS Cut Line= 3
      1530654.99      6841537.99        1531255.        6842288.
      1531705.03      6842688.02
#Sta/Elev= 30
  4034.7 1844.87  4149.2 1840.41  4205.2 1835.65  4213.2 1836.05  4376.5 1829.29
  4405.3 1829.12  4411.7 1826.79  4454.9 1828.07  4461.3 1826.51  4475.7 1826.09
  4496.5 1823.41    4583 1822.28  4653.4 1823.47  4810.3 1820.69  4874.3 1821.15
    4924 1819.33  4973.6 1820.28    4984 1818.48  4984.5 1817.98  4991.9 1818.48
    4992 1819.84  4996.2 1819.84  5044.9  1818.8  5051.6 1820.47  5073.4 1821.92
  5186.2 1822.93  5331.2 1824.79  5519.1 1829.44  5583.5  1834.5  5597.3 1836.85
#Mann= 6 ,-1 , 0
  4034.7    .035       0    4984     .07       0  4991.9    .035       0
  4996.2     .07       0  5186.2     .16       0  5331.2     .07       0
Bank Sta=4984,4991.9
XS Rating Curve= 0 ,0
Exp/Cntr=0.3,0.1

Type RM Length L Ch R = 1 ,13046   ,887,887,887
BEGIN DESCRIPTION:
Mapping XS 12200295
END DESCRIPTION:
XS GIS Cut Line= 4
      1530597.31      6842071.57      1530916.74      6842456.96
      1531486.19      6842772.94      1531968.86      6842835.44
#Sta/Elev= 30
  4515.7 1833.18  4611.2  1831.9  4625.5 1832.51  4753.2 1828.39  4796.1 1825.46
  4823.5 1826.65    4835 1826.05  4845.6 1825.47  4852.1 1823.41  4866.5 1824.13
  4909.4 1822.93  4952.4 1820.62  4965.7 1818.62  5001.9 1818.07  5004.4 1816.85
  5004.9 1816.35  5012.4 1816.85  5030.1 1818.88  5210.6 1818.37    5243 1820.15
  5317.3 1818.74  5355.1 1820.45  5380.5 1820.31  5626.3 1823.98  5757.1 1827.42
  5897.4 1835.26  5902.4 1834.52  5958.7 1835.59  5981.7 1835.08  6154.2 1838.95
#Mann= 6 ,-1 , 0
  4515.7    .035       0    4835     .07       0  5004.4     .07       0
  5012.4     .07       0  5210.6     .16       0  5380.5     .07       0
Bank Sta=5004.4,5012.4
XS Rating Curve= 0 ,0
Exp/Cntr=0.3,0.1

Type RM Length L Ch R = 1 ,12159   ,634,634,634
BEGIN DESCRIPTION:
Mapping XS 4a9a4c10
END DESCRIPTION:
XS GIS Cut Line= 3
      1530576.46      6842144.44       1530659.8      6843019.46
      1531741.52      6843501.39
#Sta/Elev= 30
  3958.9 1832.16  4011.5 1831.27  4110.1  1829.4  4208.7 1828.51  4223.7 1828.12
  4256.3 1823.88    4304 1823.25  4315.9  1825.7  4344.2 1825.72  4504.9 1818.42
  4615.4 1817.37  4630.6 1815.85  4685.7 1817.06  4796.2    1815  4847.8 1816.93
  4940.7 1817.55  4985.9 1816.78  5025.6 1813.66  5026.1 1813.16  5033.7 1813.66
  5051.6 1815.04  5119.8 1815.85  5150.1 1813.95  5182.9 1814.04    5236 1816.99
  5264.7 1816.23  5461.5 1820.36  5490.2 1822.27  5756.7 1828.42  6022.1 1836.86
#Mann= 8 ,-1 , 0
  3958.9    .035       0  4011.5     .07       0  4110.1    .035       0
  4208.7     .07       0  4256.3    .035       0  4630.6     .07       0
  5025.6     .07       0  5033.7     .07       0
Bank Sta=5025.6,5033.7
XS Rating Curve= 0 ,0
Exp/Cntr=0.3,0.1

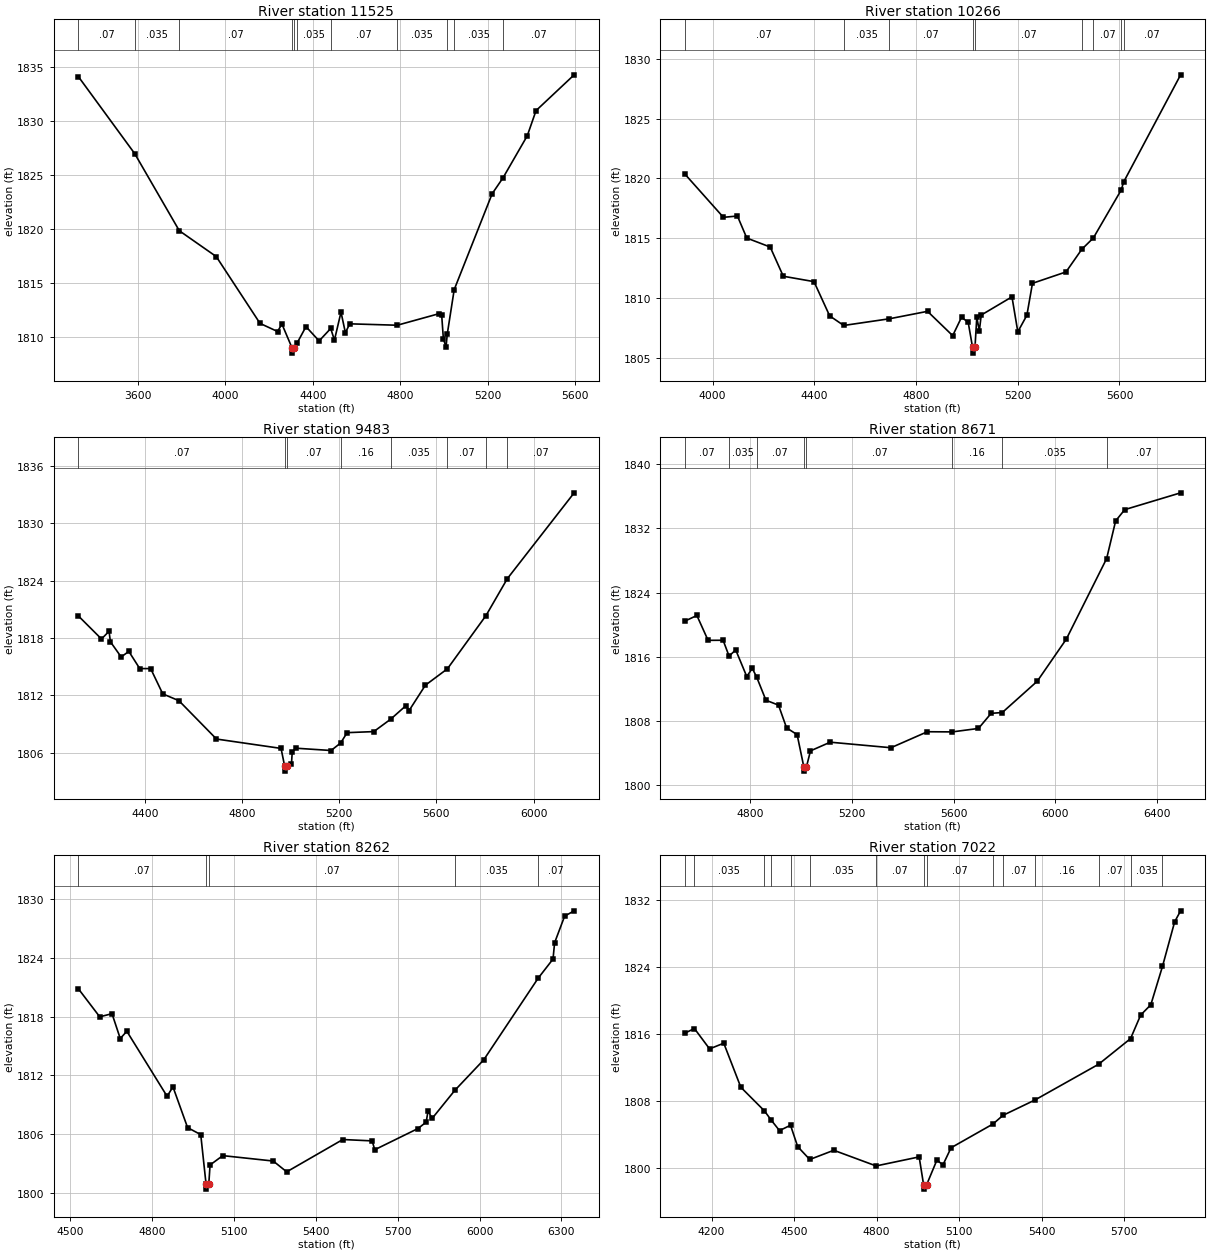
Type RM Length L Ch R = 1 ,11525   ,1259,1259,1259
BEGIN DESCRIPTION:
BULL WAGON CREEK TRIBUTARY 6 10.0
END DESCRIPTION:
XS GIS Cut Line= 3
      1529284.77      6843543.77      1530955.61      6843558.04
      1531548.72       6843602.8
#Sta/Elev= 30
  3329.1 1834.08  3587.1 1826.94  3790.5 1819.82  3959.4 1817.43  4159.4 1811.25
  4239.4  1810.5  4259.4 1811.19  4305.3    1809  4305.8  1808.5  4313.5    1809
  4329.5 1809.46  4369.4 1810.95  4429.4 1809.63  4482.3 1810.78  4499.4  1809.7
  4529.4 1812.29  4549.4 1810.39  4569.4 1811.21  4786.2 1811.08  4979.4 1812.16
  4989.4 1812.03  4997.2 1809.82  5009.4 1809.07  5014.8 1810.24  5046.6 1814.37
    5220 1823.24  5269.9 1824.72  5380.5  1828.6  5420.6 1830.93  5594.8 1834.24
#Mann= 11 ,-1 , 0
  3329.1     .07       0  3587.1    .035       0  3790.5     .07       0
  4305.3    .035       0  4313.5     .07       0  4329.5    .035       0
  4482.3     .07       0  4786.2    .035       0  5014.8     .07       0
  5046.6    .035       0  5269.9     .07       0
Bank Sta=4305.3,4313.5
XS Rating Curve= 0 ,0
Exp/Cntr=0.3,0.1

Type RM Length L Ch R = 1 ,10266   ,783,783,783
BEGIN DESCRIPTION:
BULL WAGON CREEK TRIBUTARY 6 9.0
END DESCRIPTION:
XS GIS Cut Line= 3
      1530159.47      6845046.17      1530620.28      6844037.33
      1531385.12      6843688.57
#Sta/Elev= 30
  3890.9 1820.37  4042.8 1816.75  4097.8 1816.86  4134.6 1815.02  4226.7 1814.27
  4278.2 1811.83  4398.9 1811.38  4460.6 1808.52  4515.9 1807.72  4695.8 1808.28
  4845.4  1808.9  4944.3 1806.87    4979  1808.4  5005.2 1807.99  5022.3 1805.91
  5022.8 1805.41    5032 1805.91  5039.1 1808.39  5049.1 1807.28  5056.6 1808.59
  5177.4 1810.11  5200.4 1807.19    5236 1808.57    5258 1811.24  5389.9 1812.19
    5452 1814.08  5497.5 1815.03  5607.7 1819.06    5616 1819.68  5840.6 1828.65
#Mann= 9 ,-1 , 0
  3890.9     .07       0  4515.9    .035       0  4695.8     .07       0
  5022.3     .07       0    5032     .07       0    5452    .035       0
  5497.5     .07       0  5607.7    .035       0    5616     .07       0
Bank Sta=5022.3,5032
XS Rating Curve= 0 ,0
Exp/Cntr=0.3,0.1

Type RM Length L Ch R = 1 ,9483    ,812,812,812
BEGIN DESCRIPTION:
BULL WAGON CREEK TRIBUTARY 6 8.0
END DESCRIPTION:
XS GIS Cut Line= 4
      1530180.48      6845092.68      1530479.07      6844516.34
      1530704.97      6844516.34      1531710.52      6843923.29
#Sta/Elev= 30
    4125 1820.32  4220.4  1817.9  4251.5 1818.71  4257.1 1817.61  4301.4 1816.02
    4333  1816.6    4378  1814.8  4422.9  1814.8  4472.8 1812.15  4539.2 1811.44
  4694.1 1807.42    4960 1806.44  4975.1 1804.56  4975.6 1804.06  4984.9 1804.56
  5002.9 1804.82  5006.2 1806.09  5021.9 1806.46  5166.2 1806.22  5205.6 1807.01
  5232.2 1808.09  5341.9  1808.2  5411.6  1809.5  5474.6 1810.92  5487.6 1810.41
  5554.6 1813.06  5645.4 1814.78  5804.4 1820.36  5892.1 1824.22  6167.4 1833.21
#Mann= 8 ,-1 , 0
    4125     .07       0  4975.1     .07       0  4984.9     .07       0
  5205.6     .16       0  5411.6    .035       0  5645.4     .07       0
  5804.4    .035       0  5892.1     .07       0
Bank Sta=4975.1,4984.9
XS Rating Curve= 0 ,0
Exp/Cntr=0.3,0.1

Type RM Length L Ch R = 1 ,8671    ,409,409,409
BEGIN DESCRIPTION:
Mapping XS d50bbf94
END DESCRIPTION:
XS GIS Cut Line= 3
       1530173.5      6845179.54      1530558.93      6844964.26
      1531798.48      6844106.64
#Sta/Elev= 30
  4543.1 1820.44  4590.6 1821.14  4634.6 1818.05  4693.7 1818.06  4717.1 1816.09
  4743.2 1816.86  4786.6 1813.55  4808.3 1814.56  4825.3  1813.5    4862  1810.6
  4911.4 1809.99  4943.1 1807.16  4984.6 1806.32  5011.1 1802.28  5011.6 1801.78
    5021 1802.28    5037  1804.3  5114.7 1805.38  5353.3 1804.69  5496.5 1806.68
  5594.4 1806.66  5697.3 1807.09  5747.3 1808.97    5791 1809.07  5928.3 1812.96
  6042.6  1818.2  6201.1 1828.22  6236.5 1832.91  6272.3 1834.31  6491.9  1836.4
#Mann= 8 ,-1 , 0
  4543.1     .07       0  4717.1    .035       0  4825.3     .07       0
  5011.1     .07       0    5021     .07       0  5594.4     .16       0
    5791    .035       0  6201.1     .07       0
Bank Sta=5011.1,5021
XS Rating Curve= 0 ,0
Exp/Cntr=0.3,0.1

Type RM Length L Ch R = 1 ,8262    ,1240,1240,1240
BEGIN DESCRIPTION:
Mapping XS c04036a5
END DESCRIPTION:
XS GIS Cut Line= 4
      1530301.96      6845446.91      1530753.38      6845269.81
      1531086.71      6844867.03      1531777.66      6844443.43
#Sta/Elev= 30
  4528.9 1820.83  4607.4 1817.97  4652.4 1818.29  4682.6 1815.76  4706.7  1816.5
  4854.4 1809.88  4875.9 1810.84  4929.6 1806.69  4977.8 1805.98  4997.3 1800.93
  4997.8 1800.43  5007.2 1800.93    5012 1802.89  5058.6 1803.84  5243.6 1803.29
    5293 1802.19  5498.8 1805.48  5606.3 1805.34  5615.9 1804.44  5774.5  1806.6
  5804.4 1807.25  5811.2 1808.37  5826.7 1807.64  5909.4 1810.48  6015.5 1813.59
    6215  1821.9  6269.6 1823.85  6275.4 1825.51  6312.2 1828.22  6347.1 1828.76
#Mann= 5 ,-1 , 0
  4528.9     .07       0  4997.3     .07       0  5007.2     .07       0
  5909.4    .035       0    6215     .07       0
Bank Sta=4997.3,5007.2
XS Rating Curve= 0 ,0
Exp/Cntr=0.3,0.1

Type RM Length L Ch R = 1 ,7022    ,615,615,615
BEGIN DESCRIPTION:
Mapping XS 8e4ae042
END DESCRIPTION:
XS GIS Cut Line= 3
      1530447.85      6845610.08      1531194.35      6845415.64
      1532088.99      6844902.44
#Sta/Elev= 30
  4102.5 1816.11  4137.5 1816.66  4192.6 1814.23  4244.2 1814.91  4306.2 1809.65
  4391.9 1806.83  4417.2  1805.7  4446.9 1804.47  4486.9 1805.11  4512.9 1802.56
  4556.9 1801.02  4644.2 1802.12  4798.1 1800.25  4954.6 1801.33  4970.9 1797.98
  4971.4 1797.48  4981.5 1797.98  5019.3 1800.96  5040.9 1800.36  5070.6 1802.42
  5223.1 1805.26  5259.3 1806.29  5375.3 1808.12  5607.3  1812.4  5723.3 1815.46
    5760 1818.27  5796.9  1819.5  5839.3 1824.08  5883.7 1829.42  5905.3 1830.72
#Mann= 15 ,-1 , 0
  4102.5     .07       0  4137.5    .035       0  4391.9     .07       0
  4417.2    .035       0  4486.9     .07       0  4556.9    .035       0
  4798.1     .07       0  4970.9     .07       0  4981.5     .07       0
  5223.1    .035       0  5259.3     .07       0  5375.3     .16       0
  5607.3     .07       0  5723.3    .035       0  5839.3     .07       0
Bank Sta=4970.9,4981.5
XS Rating Curve= 0 ,0
Exp/Cntr=0.3,0.1

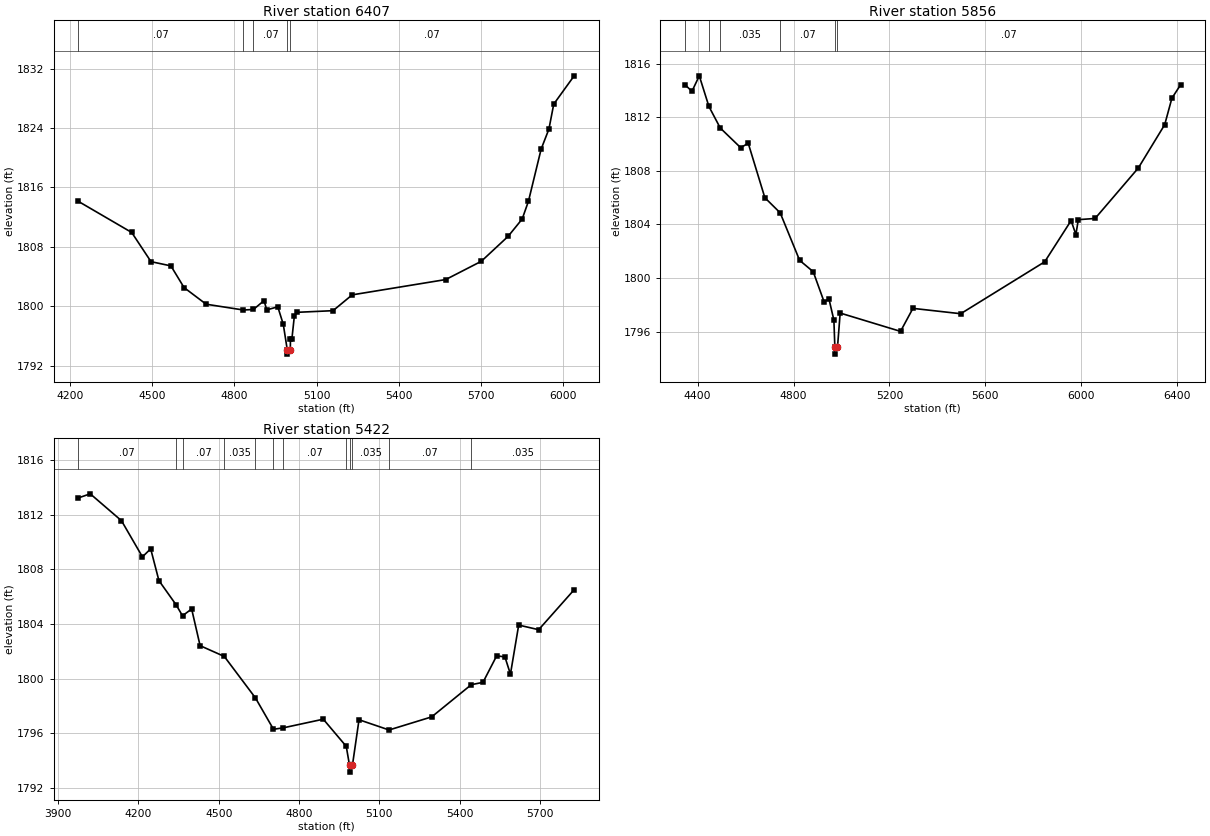
Type RM Length L Ch R = 1 ,6407    ,551,551,551
BEGIN DESCRIPTION:
Mapping XS 46a00d80
END DESCRIPTION:
XS GIS Cut Line= 4
      1530491.36      6845877.88       1531262.2      6845797.16
      1531488.76      6845768.51      1532221.06      6845433.52
#Sta/Elev= 30
  4231.2 1814.13  4425.9 1809.94  4496.3 1806.01  4568.9 1805.44  4616.9 1802.52
  4697.4 1800.28  4833.3  1799.5  4869.8 1799.57  4908.5 1800.76  4918.6 1799.52
  4958.8 1799.93  4978.9 1797.56  4993.7 1794.06  4994.2 1793.56  5004.3 1794.06
  5005.1 1795.59  5010.2 1795.59  5019.2 1798.69  5029.2 1799.19  5160.3 1799.41
  5230.2 1801.54  5571.4  1803.6  5701.2 1806.06  5798.8 1809.41  5850.3 1811.75
  5873.3 1814.16  5919.4 1821.16  5947.9 1823.87  5965.4 1827.22  6039.9 1831.03
#Mann= 5 ,-1 , 0
  4231.2     .07       0  4833.3    .035       0  4869.8     .07       0
  4993.7     .07       0  5004.3     .07       0
Bank Sta=4993.7,5004.3
XS Rating Curve= 0 ,0
Exp/Cntr=0.3,0.1

Type RM Length L Ch R = 1 ,5856    ,434,434,434
BEGIN DESCRIPTION:
Mapping XS 391e830d
END DESCRIPTION:
XS GIS Cut Line= 4
      1530415.82      6846065.38      1531051.26      6846195.59
      1531493.97      6846281.53      1532461.35      6846323.14
#Sta/Elev= 30
  4346.6 1814.46  4376.4 1813.95    4407 1815.11  4447.2 1812.82  4494.5 1811.21
  4579.6 1809.74  4611.2 1810.07  4680.5    1806  4744.4 1804.87  4825.5 1801.32
  4882.2 1800.47  4927.5 1798.22    4948 1798.42  4968.4 1796.85  4972.5 1794.81
    4973 1794.31  4983.4 1794.81  4994.6 1797.38  5246.3 1796.01    5298 1797.73
  5497.3 1797.33  5847.6 1801.21  5957.7 1804.29  5977.7 1803.25  5987.8 1804.36
  6057.8 1804.45    6238 1808.22  6348.1 1811.46  6378.1 1813.44  6414.5 1814.44
#Mann= 6 ,-1 , 0
  4346.6    .035       0  4447.2     .07       0  4494.5    .035       0
  4744.4     .07       0  4972.5     .07       0  4983.4     .07       0
Bank Sta=4972.5,4983.4
XS Rating Curve= 0 ,0
Exp/Cntr=0.3,0.1

Type RM Length L Ch R = 1 ,5422    ,112,112,112
BEGIN DESCRIPTION:
Mapping XS ff827025
END DESCRIPTION:
XS GIS Cut Line= 3
      1530351.59      6846257.22      1531349.01      6846486.39
      1532156.93      6846673.44
#Sta/Elev= 30
  3975.5 1813.24    4020 1813.54  4136.7 1811.57    4215 1808.92  4245.8 1809.51
  4276.6 1807.18    4341  1805.4  4364.8  1804.6  4398.9  1805.1  4430.5 1802.41
  4520.9 1801.62  4637.3 1798.58  4704.7 1796.28  4742.1 1796.39  4890.8 1797.02
  4976.6 1795.03  4988.8 1793.64  4989.3 1793.14  4999.7 1793.64  5024.3 1796.98
  5136.6 1796.23  5295.9 1797.19  5443.8 1799.55  5487.5 1799.72  5538.8 1801.67
  5569.6 1801.58  5590.1 1800.32  5620.9 1803.92  5695.6 1803.58  5828.2 1806.51
#Mann= 12 ,-1 , 0
  3975.5     .07       0    4341    .035       0  4364.8     .07       0
  4520.9    .035       0  4637.3     .07       0  4704.7    .035       0
  4742.1     .07       0  4976.6    .035       0  4988.8    .035       0
  4999.7    .035       0  5136.6     .07       0  5443.8    .035       0
Bank Sta=4988.8,4999.7
XS Rating Curve= 0 ,0
Exp/Cntr=0.3,0.1