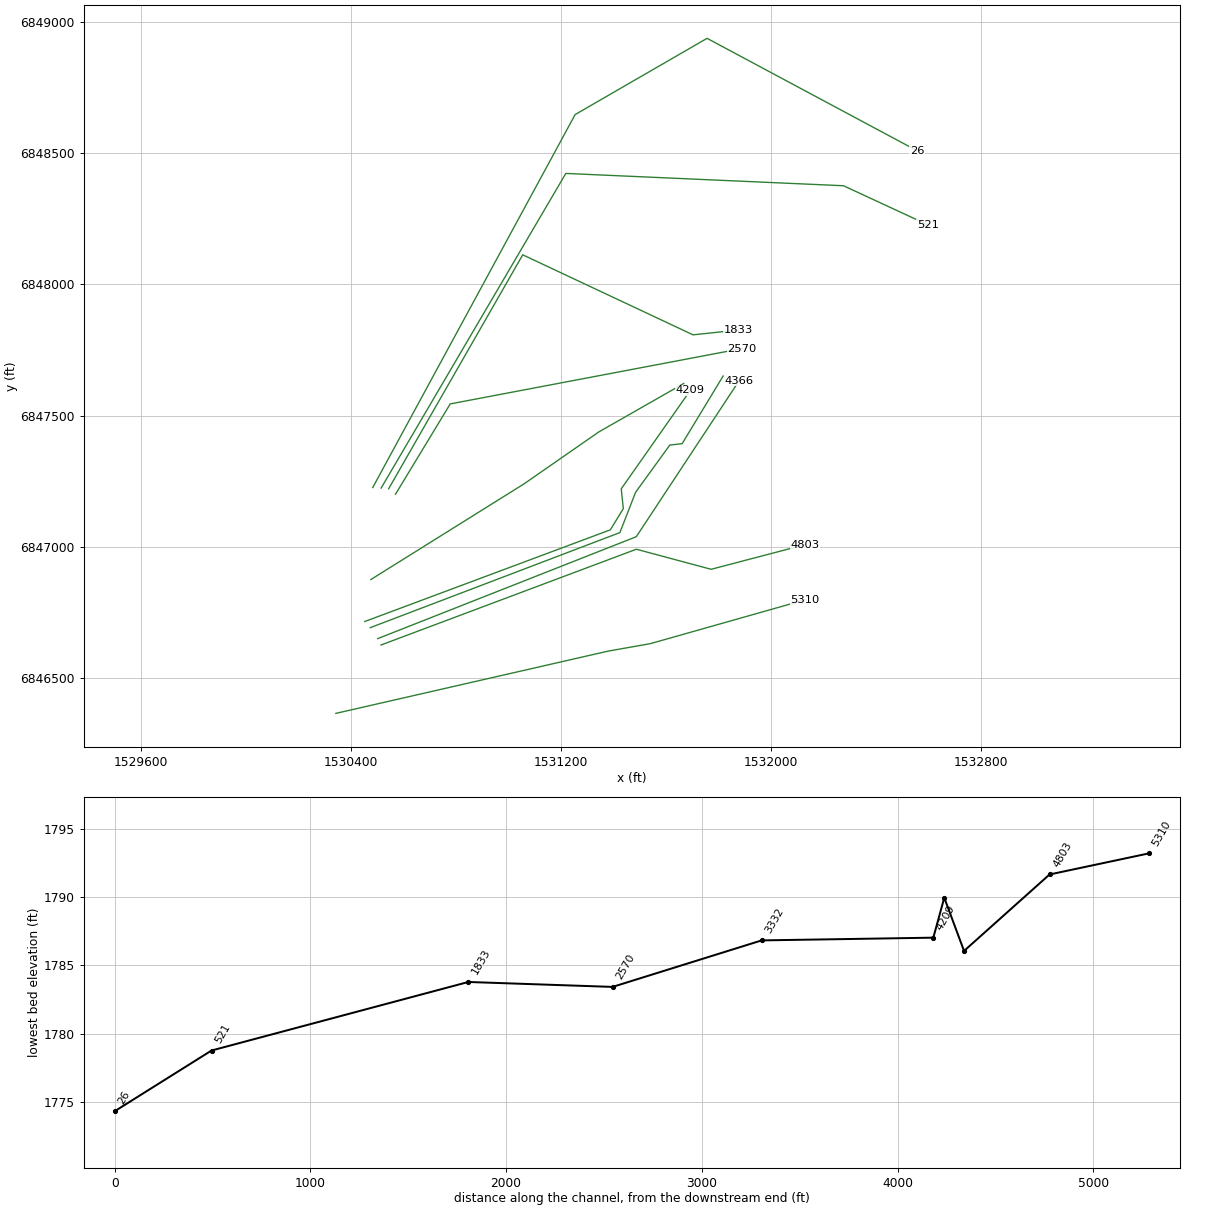
HEC-RAS study BULL WAGON CREEK TRIBUTARY 6.prj: BULL WAGON CREEK TRIBUTARY 6 Base Level Engineering

--- BULL WAGON CREEK TRIBUTARY 6.g01 (geometry) --- (continued)

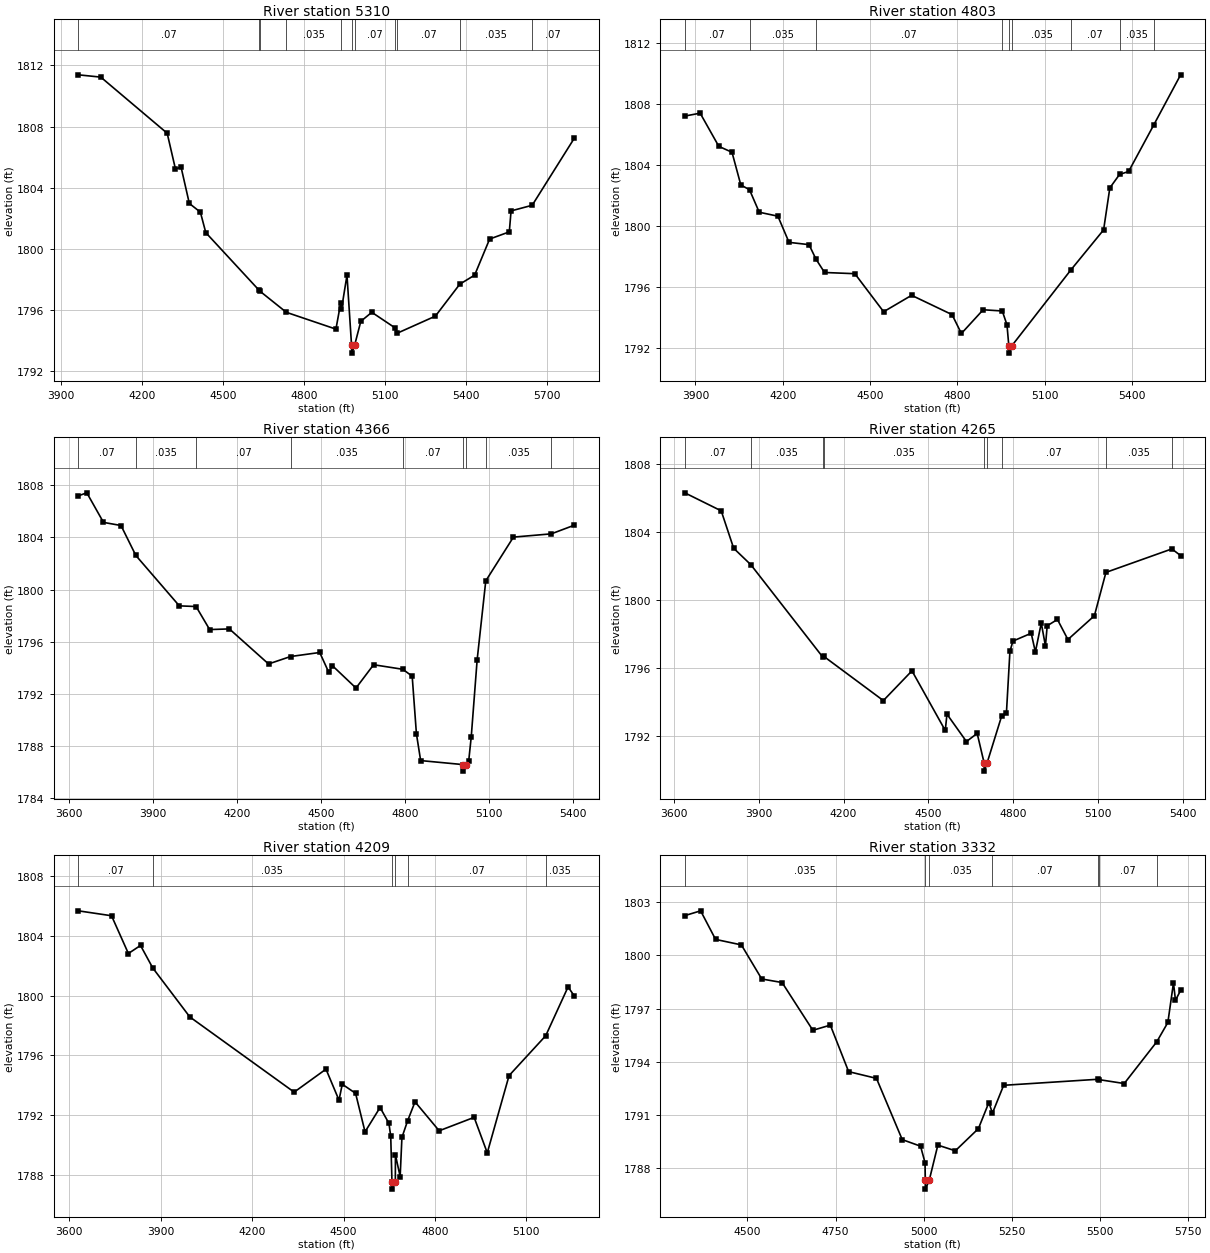
Type RM Length L Ch R = 1 ,5310    ,507,507,507
BEGIN DESCRIPTION:
Mapping XS c2b1db52
END DESCRIPTION:
XS GIS Cut Line= 4
      1530343.76      6846366.59      1531380.26      6846603.58
      1531541.71      6846632.22      1532130.15      6846798.86
#Sta/Elev= 30
  3963.3 1811.39  4046.6 1811.24  4292.8 1807.57  4323.6 1805.22  4344.1 1805.37
  4374.9 1802.98  4415.9 1802.41    4436 1801.07  4633.7  1797.3  4636.9 1797.24
  4734.6 1795.86  4918.6 1794.76  4936.4 1796.48  4939.2 1796.05  4959.6 1798.29
  4976.6 1793.69  4977.1 1793.19  4987.7 1793.69  5010.9 1795.27  5051.7 1795.86
  5137.2 1794.85  5146.8  1794.5  5287.5 1795.61    5378  1797.7    5433 1798.29
  5488.6 1800.65  5561.6 1801.12  5568.1 1802.49  5646.5 1802.86  5802.1 1807.23
#Mann= 11 ,-1 , 0
  3963.3     .07       0  4633.7    .035       0  4636.9     .07       0
  4734.6    .035       0  4936.4     .07       0  4976.6     .07       0
  4987.7     .07       0  5137.2    .035       0  5146.8     .07       0
    5378    .035       0  5646.5     .07       0
Bank Sta=4976.6,4987.7
XS Rating Curve= 0 ,0
Exp/Cntr=0.3,0.1

Type RM Length L Ch R = 1 ,4803    ,437,437,437
BEGIN DESCRIPTION:
Mapping XS 2498708f
END DESCRIPTION:
XS GIS Cut Line= 4
      1530515.68      6846627.02      1531487.89       6846991.6
      1531772.62      6846915.21      1532130.12      6847008.93
#Sta/Elev= 30
  3863.7 1807.23  3916.4 1807.42  3980.5 1805.24  4025.8 1804.85  4056.1  1802.7
  4085.9 1802.39  4119.3 1800.91  4183.4 1800.65  4221.6 1798.93  4290.2 1798.78
  4314.4 1797.82  4343.6 1796.95  4447.7 1796.87  4546.5 1794.37  4642.6 1795.45
  4781.5 1794.18  4813.5 1792.94  4888.3  1794.5  4953.9 1794.42  4970.1 1793.51
  4976.3 1792.15  4976.8 1791.65  4987.4 1792.15    5190 1797.13  5301.9 1799.75
  5323.3 1802.51  5356.6 1803.39  5387.9 1803.59  5474.5 1806.66  5566.4 1809.94
#Mann= 9 ,-1 , 0
  3863.7     .07       0  4085.9    .035       0  4314.4     .07       0
  4953.9    .035       0  4976.3    .035       0  4987.4    .035       0
    5190     .07       0  5356.6    .035       0  5474.5     .07       0
Bank Sta=4976.3,4987.4
XS Rating Curve= 0 ,0
Exp/Cntr=0.3,0.1

Type RM Length L Ch R = 1 ,4366    ,101,101,101
BEGIN DESCRIPTION:
Mapping XS d57294bc
END DESCRIPTION:
XS GIS Cut Line= 3
      1530503.33      6846651.32      1531487.72      6847039.34
      1531879.61      6847633.66
#Sta/Elev= 30
  3633.9  1807.2  3664.2 1807.43  3723.7 1805.16  3786.2 1804.92  3839.2 1802.62
  3994.4 1798.75  4054.2  1798.7  4102.7 1796.93  4173.1 1796.98  4312.9 1794.29
  4391.5 1794.86  4495.6 1795.17  4527.8 1793.65  4541.2 1794.15  4625.1 1792.44
  4687.9 1794.23  4792.1 1793.88  4825.7 1793.35  4840.8 1788.93  4855.9 1786.87
  5008.3 1786.56  5008.8 1786.06  5019.4 1786.56  5027.5 1786.85  5036.5 1788.69
  5057.6 1794.61  5088.4 1800.67  5187.1 1804.03  5322.3 1804.28  5403.9 1804.94
#Mann= 9 ,-1 , 0
  3633.9     .07       0  3839.2    .035       0  4054.2     .07       0
  4391.5    .035       0  4792.1     .07       0  5008.3     .07       0
  5019.4     .07       0  5088.4    .035       0  5322.3     .07       0
Bank Sta=5008.3,5019.4
XS Rating Curve= 0 ,0
Exp/Cntr=0.3,0.1

Type RM Length L Ch R = 1 ,4265    ,56,56,56
BEGIN DESCRIPTION:
Mapping XS ebcbc96f
END DESCRIPTION:
XS GIS Cut Line= 6
      1530474.71      6846692.99      1531425.22      6847054.97
      1531485.12      6847208.61      1531615.33       6847388.3
       1531662.2      6847393.51      1531818.43      6847651.28
#Sta/Elev= 30
  3638.7 1806.32  3767.4 1805.26  3811.4 1803.06  3872.2 1802.09  4126.3 1796.66
  4129.1 1796.71  4340.5  1794.1  4441.6 1795.85  4559.3 1792.34  4565.3  1793.3
  4634.2 1791.69  4672.1 1792.17  4696.4 1790.45  4696.9 1789.95  4707.5 1790.45
  4758.6 1793.19  4775.4 1793.34  4787.9    1797  4798.6  1797.6  4863.1 1798.06
  4877.8 1796.96  4898.7 1798.66  4913.4 1797.31  4919.6  1798.5  4955.8 1798.87
  4992.8 1797.69  5086.4 1799.09  5127.2 1801.64  5360.1 1803.02  5391.2 1802.63
#Mann= 9 ,-1 , 0
  3638.7     .07       0  3872.2    .035       0  4126.3     .07       0
  4129.1    .035       0  4696.4     .07       0  4707.5    .035       0
  4758.6     .07       0  5127.2    .035       0  5360.1     .07       0
Bank Sta=4696.4,4707.5
XS Rating Curve= 0 ,0
Exp/Cntr=0.3,0.1

Type RM Length L Ch R = 1 ,4209    ,877,877,877
BEGIN DESCRIPTION:
Mapping XS 5dcbf20d
END DESCRIPTION:
XS GIS Cut Line= 5
      1530453.91      6846716.44      1531388.76      6847065.38
      1531438.24      6847146.11      1531430.43      6847221.63
      1531693.44      6847596.63
#Sta/Elev= 30
  3630.1 1805.68    3739 1805.35  3794.3 1802.82  3834.1 1803.36  3874.3 1801.85
  3995.8 1798.57  4338.1 1793.53  4442.5 1795.07  4485.2 1792.99  4495.9 1794.06
  4539.6 1793.45  4570.6 1790.87  4619.9  1792.5    4649 1791.44  4654.9 1790.57
  4658.9 1787.53  4659.4 1787.03    4670 1787.53  4670.3 1789.33  4685.8 1787.87
  4691.6 1790.49  4710.1  1791.6  4734.6 1792.88  4813.8 1790.94  4928.5 1791.84
  4971.6 1789.46  5043.1 1794.64  5163.3 1797.31  5236.6 1800.58  5256.6 1799.99
#Mann= 6 ,-1 , 0
  3630.1     .07       0  3874.3    .035       0  4658.9     .07       0
    4670    .035       0  4710.1     .07       0  5163.3    .035       0
Bank Sta=4658.9,4670
XS Rating Curve= 0 ,0
Exp/Cntr=0.3,0.1

Type RM Length L Ch R = 1 ,3332    ,762,762,762
BEGIN DESCRIPTION:
Mapping XS 008ea7fe
END DESCRIPTION:
XS GIS Cut Line= 4
      1530476.87      6846876.15      1531060.64      6847240.73
      1531344.93      6847438.21       1531668.3      6847622.69
#Sta/Elev= 30
  4322.3 1802.24  4367.2 1802.51  4409.6  1800.9  4482.8 1800.59  4540.6 1798.67
  4598.3 1798.47  4685.6 1795.78  4735.2 1796.07  4787.1 1793.45  4866.1 1793.07
  4939.2 1789.62  4991.1 1789.25  5003.9 1788.32  5004.6 1787.33  5005.1 1786.83
  5015.8 1787.33  5040.2 1789.31  5089.8 1788.99  5155.3 1790.24    5185 1791.71
  5195.1 1791.11  5226.9 1792.68  5494.8 1793.02  5497.3    1793    5569 1792.78
  5661.3 1795.13  5692.8 1796.22  5708.7 1798.45  5714.4 1797.47    5729 1798.03
#Mann= 7 ,-1 , 0
  4322.3    .035       0  5004.6    .035       0  5015.8    .035       0
  5195.1     .07       0  5494.8    .035       0  5497.3     .07       0
  5661.3    .035       0
Bank Sta=5004.6,5015.8
XS Rating Curve= 0 ,0
Exp/Cntr=0.3,0.1

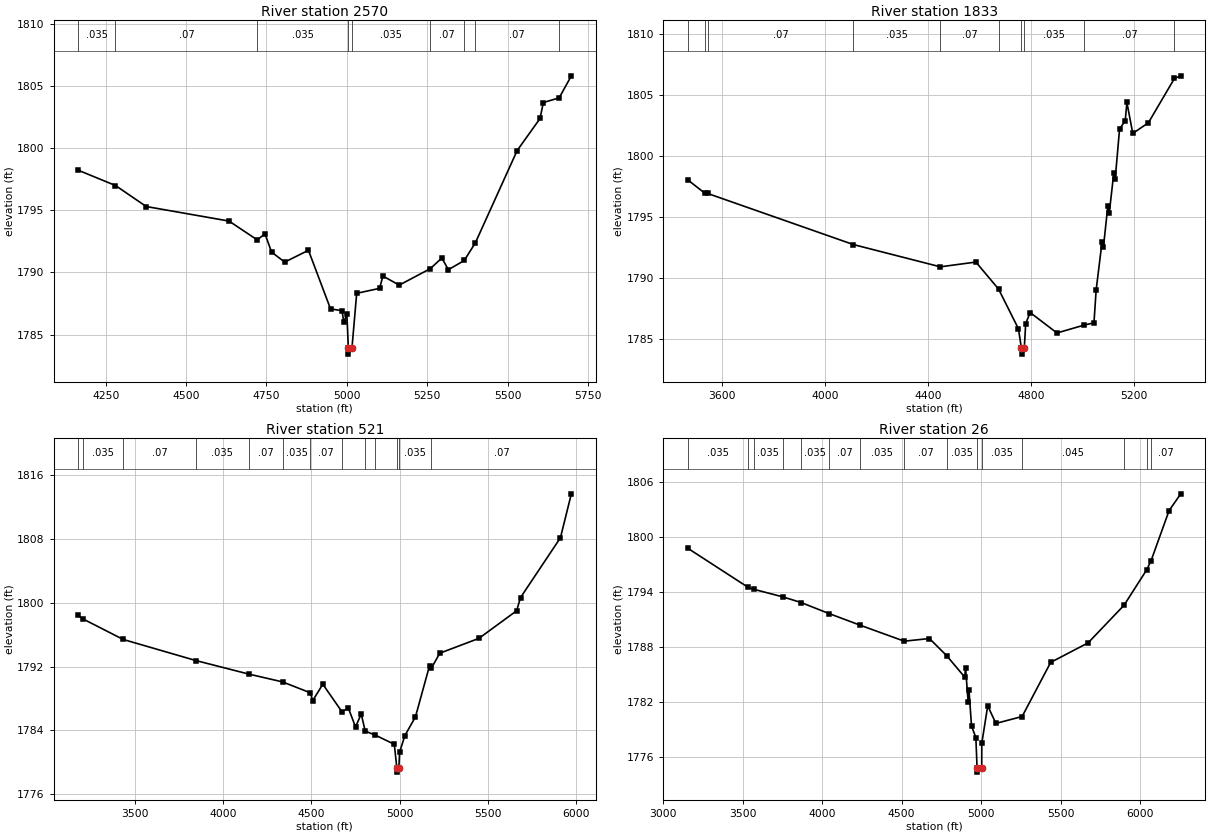
Type RM Length L Ch R = 1 ,2570    ,737,737,737
BEGIN DESCRIPTION:
Mapping XS 7b2f487e
END DESCRIPTION:
XS GIS Cut Line= 3
      1530570.92      6847201.21      1530779.24      6847544.95
      1531890.59      6847755.77
#Sta/Elev= 30
  4164.7 1798.22  4280.6 1796.99  4376.2  1795.3  4633.6 1794.13  4721.1 1792.62
  4745.5  1793.1  4765.8 1791.64  4806.6 1790.83  4880.5 1791.78  4949.1 1787.07
  4985.1 1786.92  4990.2    1786    5000 1786.63  5004.5 1783.93    5005 1783.43
  5015.8 1783.93  5030.5 1788.32  5101.8 1788.72  5111.9 1789.71  5162.8 1788.98
  5259.1  1790.3  5295.2 1791.16  5315.5 1790.22  5364.9 1790.96  5399.4 1792.38
  5529.3  1799.8  5600.5 1802.38  5610.7 1803.66    5660 1804.04  5697.8 1805.81
#Mann= 9 ,-1 , 0
  4164.7    .035       0  4280.6     .07       0  4721.1    .035       0
  5004.5    .035       0  5015.8    .035       0  5259.1     .07       0
  5364.9    .035       0  5399.4     .07       0    5660    .035       0
Bank Sta=5004.5,5015.8
XS Rating Curve= 0 ,0
Exp/Cntr=0.3,0.1

Type RM Length L Ch R = 1 ,1833    ,1312,1312,1312
BEGIN DESCRIPTION:
Mapping XS 74a0147a
END DESCRIPTION:
XS GIS Cut Line= 4
      1530544.89      6847222.07      1531055.28      6848112.66
      1531703.72      6847807.97      1531875.63       6847826.2
#Sta/Elev= 30
  3465.9 1798.05    3534 1796.93  3543.7 1796.93    4110 1792.75  4447.7 1790.93
  4585.8 1791.32  4673.9 1789.11    4751 1785.87  4762.6 1784.29  4763.1 1783.79
  4773.9 1784.29  4779.3 1786.29  4796.6 1787.19  4900.9 1785.52  5007.2 1786.17
  5044.5 1786.35    5053 1789.03  5075.8 1792.95  5081.3 1792.54  5098.6 1795.94
  5104.1 1795.35  5121.4 1798.58  5126.9 1798.09  5143.9 1802.18    5166 1802.89
  5172.5 1804.37  5195.3 1801.84  5255.9 1802.71  5357.3 1806.34  5381.7 1806.55
#Mann= 10 ,-1 , 0
  3465.9     .07       0    3534    .035       0  3543.7     .07       0
    4110    .035       0  4447.7     .07       0  4673.9    .035       0
  4762.6    .035       0  4773.9    .035       0  5007.2     .07       0
  5357.3    .035       0
Bank Sta=4762.6,4773.9
XS Rating Curve= 0 ,0
Exp/Cntr=0.3,0.1

Type RM Length L Ch R = 1 ,521     ,495,495,495
BEGIN DESCRIPTION:
Mapping XS 11c1d3fd
END DESCRIPTION:
XS GIS Cut Line= 4
      1530516.21      6847224.61      1531219.35      6848422.55
      1532276.64      6848375.68      1532596.93      6848227.25
#Sta/Elev= 30
  3175.2 1798.42  3203.6 1797.97    3431 1795.41  3843.2 1792.77  4144.1 1791.07
  4335.8 1790.09    4494 1788.72  4506.5 1787.73  4564.3  1789.8  4672.3 1786.37
  4710.1 1786.77  4750.1 1784.44  4782.5 1786.07  4804.9 1783.92  4860.4 1783.44
  4970.3 1782.27  4984.7 1779.28  4985.2 1778.78    4996 1779.28  5000.3 1781.27
  5030.4 1783.37  5090.4 1785.71  5170.5 1792.14  5180.7 1791.81  5228.5 1793.69
  5450.8 1795.55  5664.9 1799.01  5686.9 1800.66  5913.6 1808.16  5975.6 1813.67
#Mann= 13 ,-1 , 0
  3175.2     .07       0  3203.6    .035       0    3431     .07       0
  3843.2    .035       0  4144.1     .07       0  4335.8    .035       0
    4494     .07       0  4672.3    .035       0  4804.9     .07       0
  4860.4    .035       0  4984.7    .035       0    4996    .035       0
  5180.7     .07       0
Bank Sta=4984.7,4996
XS Rating Curve= 0 ,0
Exp/Cntr=0.3,0.1

Type RM Length L Ch R = 1 ,26      ,0,0,0
BEGIN DESCRIPTION:
BULL WAGON CREEK TRIBUTARY 6 1.0
END DESCRIPTION:
XS GIS Cut Line= 4
      1530484.12      6847226.41      1531254.83      6848646.65
      1531757.19      6848936.96      1532556.17      6848509.35
#Sta/Elev= 30
  3153.3 1798.75  3534.8 1794.47  3568.4 1794.27  3752.1 1793.44  3867.9 1792.82
  4044.6 1791.61  4240.7 1790.34  4516.2 1788.61  4674.6  1788.9  4783.1 1787.03
  4896.2  1784.7    4902 1785.69  4917.8 1782.02  4923.5 1783.26  4939.3 1779.36
  4966.6 1778.11  4974.1 1774.84  4974.6 1774.34  5003.5 1774.84  5003.9 1777.48
  5041.2 1781.56  5092.8 1779.65  5257.6  1780.4  5437.3  1786.3  5672.9 1788.43
  5898.8 1792.53  6041.8  1796.4  6069.2  1797.4  6182.4 1802.85  6255.6 1804.67
#Mann= 15 ,-1 , 0
  3153.3    .035       0  3534.8     .07       0  3568.4    .035       0
  3752.1     .07       0  3867.9    .035       0  4044.6     .07       0
  4240.7    .035       0  4516.2     .07       0  4783.1    .035       0
  4974.1     .07       0  5003.5    .035       0  5257.6    .045       0
  5898.8     .07       0  6041.8    .035       0  6069.2     .07       0
Bank Sta=4974.1,5003.5
XS Rating Curve= 0 ,0
Exp/Cntr=0.3,0.1

Chan Stop Cuts=-1
Use User Specified Reach Order=0
Composite Channel Slope=5