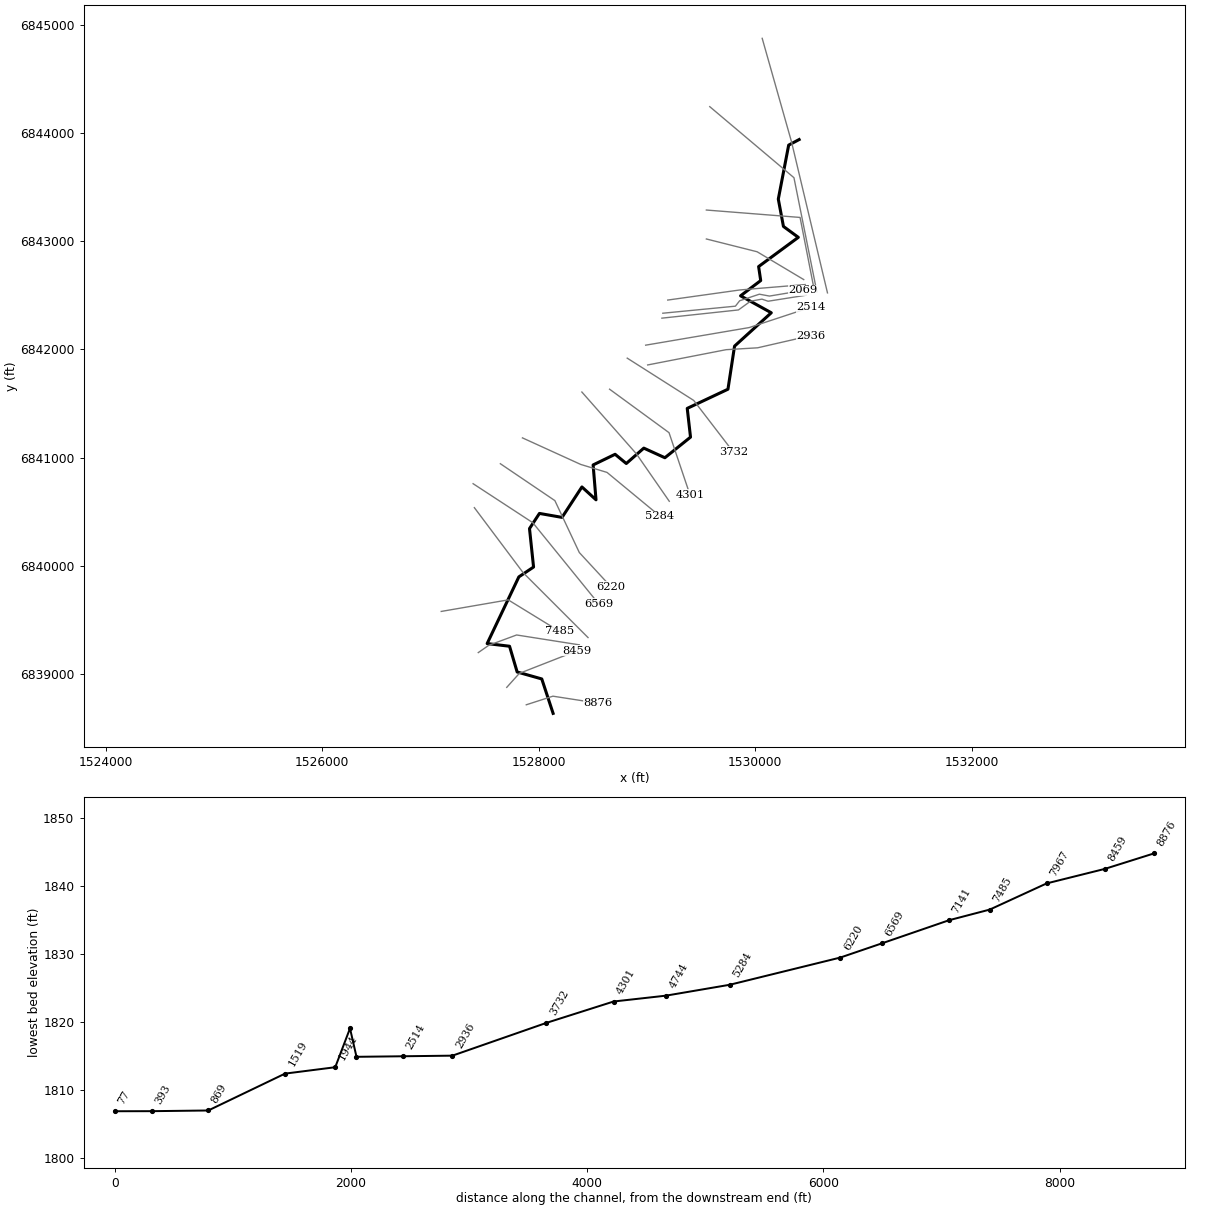
--- BULL WAGON CREEK TRIBUTARY 6_1.prj (project) ---

Proj Title=BULL WAGON CREEK TRIBUTARY 6_1 Base Level Engineering
Current Plan=p01
Default Exp/Contr=0.3,0.1
English Units
Geom File=g01
Flow File=f01
Plan File=p01
Y Axis Title=Elevation
X Axis Title(PF)=Main Channel Distance
X Axis Title(XS)=Station
BEGIN DESCRIPTION:
BULL WAGON CREEK TRIBUTARY 6_1
END DESCRIPTION:
DSS Export Rating Curves= 0
DSS Export Rating Curve Sorted= 0
DSS Export Volume Flow Curves= 0
DXF OffsetX= 0
DXF OffsetY= 0
DXF ScaleX= 1
DXF ScaleY= 10

--- BULL WAGON CREEK TRIBUTARY 6_1.p01 (plan) ---

Plan Title=Multiple Run
Short Identifier=Multiple
Geom File=g01
Flow File=f01
Subcritical Flow
K Sum by GR= 0
Std Step Tol= 0.01
Critical Tol= 0.01
Num of Std Step Trials= 20
Max Error Tol= 0.3
Flow Tol Ratio= 0.001
Split Flow NTrial= 30
Split Flow Tol= 0.02
Split Flow Ratio= 0.02
Log Output Level= 0
Friction Slope Method= 1
Unsteady Friction Slope Method= 2
Unsteady Bridges Friction Slope Method= 1
Parabolic Critical Depth
Global Vel Dist=  1 , 1 , 1
Global Log Level= 0
CheckData=True
Encroach Param= -1, 0, 0, 0
BEGIN DESCRIPTION:
Multiple Run
END DESCRIPTION:

--- BULL WAGON CREEK TRIBUTARY 6_1.f01 (steady flow) ---

Flow Title=Multiple
Number of Profiles=7
Profile Names=10-year,25-year,50-year,1pct_min,100-year,1pct_plu,500-year
River Rch & RM= BULL WAGON CREEK,Reach-1,8876
     123     162     193     114     228     455     324
Boundary for River Rch & Prof#=BULL WAGON CREEK,Reach-1,1
Up Type=0
Dn Type=3
Dn Slope=0.005
Boundary for River Rch & Prof#=BULL WAGON CREEK,Reach-1,2
Up Type=0
Dn Type=3
Dn Slope=0.005
Boundary for River Rch & Prof#=BULL WAGON CREEK,Reach-1,3
Up Type=0
Dn Type=3
Dn Slope=0.005
Boundary for River Rch & Prof#=BULL WAGON CREEK,Reach-1,4
Up Type=0
Dn Type=3
Dn Slope=0.005
Boundary for River Rch & Prof#=BULL WAGON CREEK,Reach-1,5
Up Type=0
Dn Type=3
Dn Slope=0.005
Boundary for River Rch & Prof#=BULL WAGON CREEK,Reach-1,6
Up Type=0
Dn Type=3
Dn Slope=0.005
Boundary for River Rch & Prof#=BULL WAGON CREEK,Reach-1,7
Up Type=0
Dn Type=3
Dn Slope=0.005

--- BULL WAGON CREEK TRIBUTARY 6_1.g01 (geometry) ---

Geom Title=Existing Conditions
Program Version=4.10

River Reach=BULL WAGON CREEK,Reach-1
Reach XY= 30
      1528132.46      6838637.73      1528027.77      6838955.79
      1527800.34      6839020.02      1527730.03      6839257.87
      1527523.21      6839282.39      1527815.98      6839898.37
      1527951.93      6839989.43      1527914.41      6840344.62
      1528006.28      6840484.63        1528215.      6840448.06
      1528398.49      6840729.12      1528528.81      6840610.43
        1528502.      6840932.48      1528705.01      6841030.89
      1528808.33      6840945.61      1528970.22      6841087.76
        1529165.      6840998.96      1529401.63      6841189.28
      1529371.39      6841454.79       1529747.5      6841631.91
      1529808.37      6842029.85      1530147.72       6842338.1
      1529863.95      6842494.67      1530049.99      6842635.46
      1530030.72      6842764.69      1530397.49      6843034.83
      1530260.01      6843135.46      1530212.53      6843387.99
       1530308.3       6843886.7        1530405.        6843938.

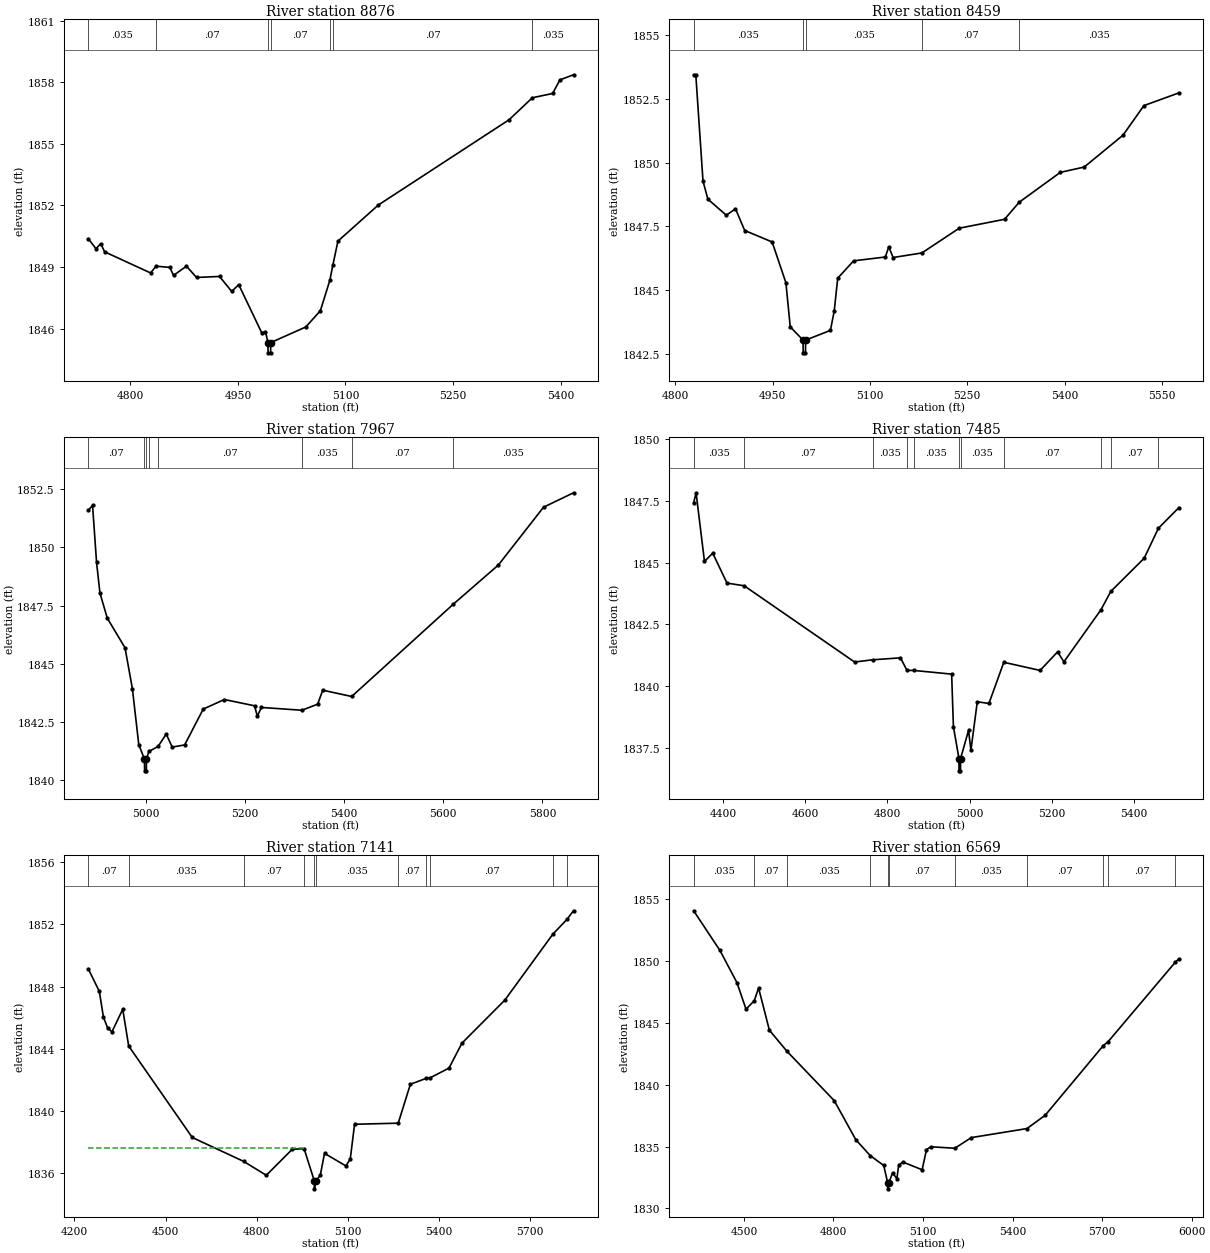
Type RM Length L Ch R = 1 ,8876    ,417,417,417
BEGIN DESCRIPTION:
BULL WAGON CREEK TRIBUTARY 6_1 10.0
END DESCRIPTION:
XS GIS Cut Line= 3
       1527884.7      6838717.18      1528130.81      6838796.59
      1528543.78      6838732.55
#Sta/Elev= 30
  4741.4 1850.38  4752.2 1849.89  4758.9 1850.14  4764.2 1849.74  4828.3 1848.71
  4835.9 1849.04  4855.1 1848.98  4860.3 1848.59  4878.3 1849.04  4892.4 1848.49
  4924.4 1848.54  4941.4 1847.81  4951.2 1848.14  4983.2  1845.8  4988.5 1845.85
  4991.9 1845.32  4992.1 1844.82  4995.6 1844.82  4995.9 1845.32  5044.7 1846.08
    5065 1846.87  5078.2 1848.35  5082.4 1849.09  5089.5 1850.26  5145.9 1852.02
  5328.1 1856.17  5360.5 1857.24  5388.8 1857.45  5398.9 1858.11  5417.9 1858.36
#Mann= 7 ,-1 , 0
  4741.4    .035       0  4835.9     .07       0  4991.9     .07       0
  4995.9     .07       0  5078.2    .035       0  5082.4     .07       0
  5360.5    .035       0
Bank Sta=4991.9,4995.9
XS Rating Curve= 0 ,0
Exp/Cntr=0.3,0.1

Type RM Length L Ch R = 1 ,8459    ,492,492,492
BEGIN DESCRIPTION:
Mapping XS b2c464a7
END DESCRIPTION:
XS GIS Cut Line= 3
      1527704.25        6838878.      1527820.33      6839007.09
      1528355.29      6839216.52
#Sta/Elev= 30
  4828.2 1853.45  4831.5 1853.45  4842.6 1849.28  4850.1 1848.57  4878.5 1847.94
  4892.7 1848.19  4906.9 1847.34  4949.2 1846.89  4970.4 1845.29  4977.1 1843.56
  4996.8 1843.04  4997.1 1842.54  5000.6 1842.54  5000.8 1843.04    5039 1843.42
  5044.9 1844.18  5050.3 1845.47  5074.8 1846.15  5123.7  1846.3    5129  1846.7
  5135.7 1846.28  5180.1 1846.46  5237.6 1847.43  5307.5 1847.78  5330.1 1848.45
  5393.4 1849.62  5430.3 1849.83  5490.1 1851.08  5522.3 1852.24  5576.3 1852.74
#Mann= 5 ,-1 , 0
  4828.2    .035       0  4996.8    .035       0  5000.8    .035       0
  5180.1     .07       0  5330.1    .035       0
Bank Sta=4996.8,5000.8
XS Rating Curve= 0 ,0
Exp/Cntr=0.3,0.1

Type RM Length L Ch R = 1 ,7967    ,482,482,482
BEGIN DESCRIPTION:
Mapping XS 686b4739
END DESCRIPTION:
XS GIS Cut Line= 4
      1527441.23      6839199.17      1527538.86      6839266.85
      1527795.37      6839361.91      1528374.79      6839270.76
#Sta/Elev= 30
  4883.8 1851.58  4892.5  1851.8  4900.6 1849.35  4907.4 1848.04  4922.2 1846.96
    4958 1845.69  4972.9 1843.93  4985.7 1841.54  4997.2 1840.91  4997.5 1840.41
    5001 1840.41  5001.2 1840.91  5006.1 1841.24  5024.8 1841.46  5041.1 1841.99
  5053.1 1841.43  5078.2 1841.52  5115.8 1843.06  5158.4 1843.47  5219.4  1843.2
  5224.8 1842.75  5233.1 1843.13  5314.6 1843.01  5346.6 1843.27  5356.8 1843.87
  5415.2  1843.6  5619.7 1847.55  5711.1 1849.24  5802.2 1851.72  5862.7 1852.34
#Mann= 8 ,-1 , 0
  4883.8     .07       0  4997.2     .07       0  5001.2     .07       0
  5006.1    .035       0  5024.8     .07       0  5314.6    .035       0
  5415.2     .07       0  5619.7    .035       0
Bank Sta=4997.2,5001.2
XS Rating Curve= 0 ,0
Exp/Cntr=0.3,0.1

Type RM Length L Ch R = 1 ,7485    ,344,344,344
BEGIN DESCRIPTION:
Mapping XS 6ce35878
END DESCRIPTION:
XS GIS Cut Line= 3
      1527099.23      6839579.36      1527717.68      6839686.13
      1528189.01      6839397.08
#Sta/Elev= 30
  4328.7 1847.42  4334.6 1847.83    4355 1845.05  4375.1 1845.38  4409.8 1844.17
  4451.6 1844.06  4720.2 1840.97  4763.8 1841.06  4831.8 1841.14  4847.8 1840.63
  4863.7 1840.63  4956.3 1840.48  4960.6 1838.35  4974.1 1837.06  4974.3 1836.56
  4977.8 1836.56  4978.1 1837.06  4997.4  1838.2  5003.2  1837.4  5018.7 1839.36
    5047 1839.29  5083.2 1840.96  5171.4 1840.63    5214 1841.38  5229.4 1840.98
  5319.6 1843.09  5343.4 1843.83  5424.8 1845.18  5459.2 1846.39  5509.2 1847.23
#Mann= 11 ,-1 , 0
  4328.7    .035       0  4451.6     .07       0  4763.8    .035       0
  4847.8     .07       0  4863.7    .035       0  4974.1    .035       0
  4978.1    .035       0  5083.2     .07       0  5319.6    .035       0
  5343.4     .07       0  5459.2    .035       0
Bank Sta=4974.1,4978.1
XS Rating Curve= 0 ,0
Exp/Cntr=0.3,0.1

Type RM Length L Ch R = 1 ,7141    ,572,572,572
BEGIN DESCRIPTION:
BULL WAGON CREEK TRIBUTARY 6_1 9.0
END DESCRIPTION:
XS GIS Cut Line= 3
      1527404.99      6840538.02        1527855.        6839938.
      1528454.97      6839338.03
#Sta/Elev= 30
  4245.3 1849.14  4281.8 1847.69  4295.3 1846.04  4308.9 1845.35  4323.4 1845.09
  4358.9 1846.54  4378.5 1844.18    4588  1838.3  4757.7 1836.76  4831.8 1835.87
  4917.2 1837.54  4956.3 1837.58  4990.2  1835.5  4990.4    1835  4994.2  1835.5
  5009.5 1835.86  5023.6 1837.28  5094.3 1836.47  5108.5 1836.93  5122.6 1839.15
  5266.4 1839.22  5306.4 1841.72  5358.3  1842.1  5372.1 1842.14  5433.7 1842.76
  5476.2 1844.36  5617.6 1847.13  5775.9 1851.37  5821.9 1852.31  5843.8 1852.87
#Mann= 11 ,-1 , 0
  4245.3     .07       0  4378.5    .035       0  4757.7     .07       0
  4956.3    .035       0  4990.2    .035       0  4994.2    .035       0
  5266.4     .07       0  5358.3    .035       0  5372.1     .07       0
  5775.9    .035       0  5821.9     .07       0
#XS Ineff= 2 , 0
       0  4952.6 1837.62               0
Permanent Ineff=
       F       F
Bank Sta=4990.2,4994.2
XS Rating Curve= 0 ,0
Exp/Cntr=0.3,0.1

Type RM Length L Ch R = 1 ,6569    ,349,349,349
BEGIN DESCRIPTION:
Mapping XS 712bfcf0
END DESCRIPTION:
XS GIS Cut Line= 3
      1527393.62      6840759.21      1527944.82      6840398.98
      1528554.65      6839648.09
#Sta/Elev= 30
  4331.6 1854.05  4419.5 1850.85  4476.7 1848.24    4507  1846.1  4534.7 1846.78
  4549.1 1847.81  4585.3  1844.4  4644.1  1842.7  4802.5 1838.71  4874.9 1835.55
  4923.3 1834.26  4968.4 1833.47  4981.5 1832.08  4981.8 1831.58  4985.5 1832.08
    4998 1832.86  5012.4 1832.41  5018.8 1833.52  5033.2 1833.74  5097.1 1833.12
  5111.5 1834.74  5125.9 1834.98  5206.8 1834.86  5261.7 1835.72  5448.3 1836.45
  5509.5 1837.53  5704.2 1843.16  5720.1 1843.47  5945.1 1849.89  5957.4 1850.16
#Mann= 11 ,-1 , 0
  4331.6    .035       0  4534.7     .07       0  4644.1    .035       0
  4923.3     .07       0  4981.5     .07       0  4985.5     .07       0
  5206.8    .035       0  5448.3     .07       0  5704.2    .035       0
  5720.1     .07       0  5945.1    .035       0
Bank Sta=4981.5,4985.5
XS Rating Curve= 0 ,0
Exp/Cntr=0.3,0.1

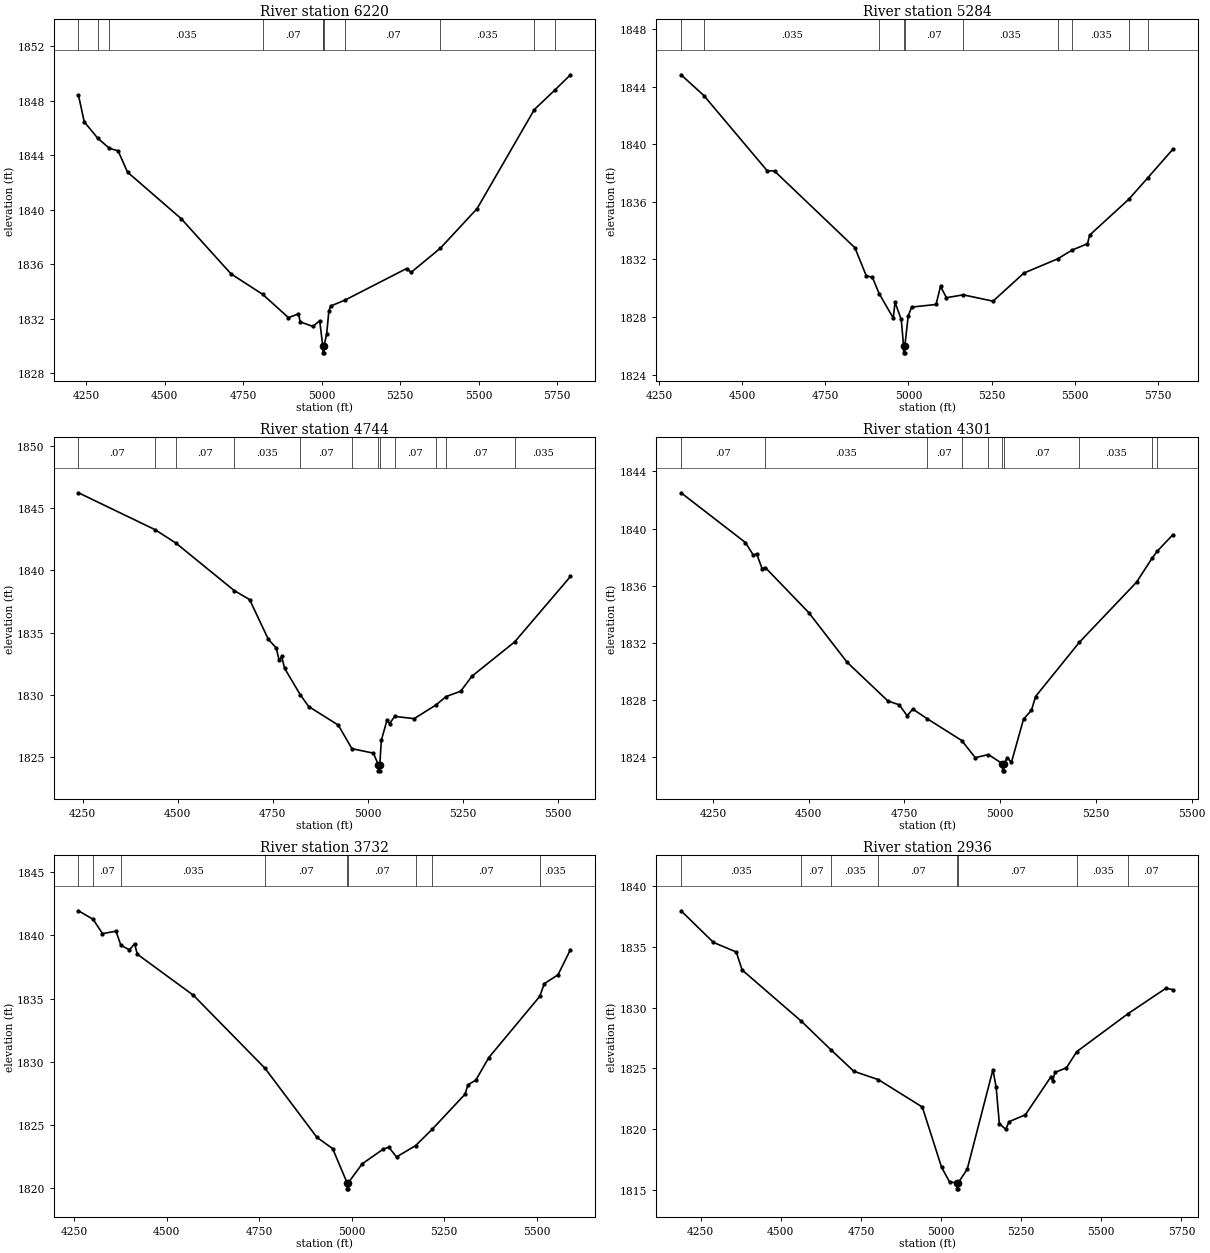
Type RM Length L Ch R = 1 ,6220    ,936,936,936
BEGIN DESCRIPTION:
Mapping XS 40e81762
END DESCRIPTION:
XS GIS Cut Line= 4
      1527645.33      6840943.69      1528148.81      6840602.97
      1528374.51      6840123.37      1528665.34      6839808.67
#Sta/Elev= 30
  4225.3 1848.41  4243.7 1846.45  4286.6 1845.25  4323.8 1844.51  4351.6 1844.32
  4381.5 1842.76  4552.3 1839.35  4711.1  1835.3  4811.7  1833.8    4894 1832.09
  4925.8 1832.37  4931.3 1831.78  4971.4 1831.45  4993.5 1831.86  5002.9 1830.04
  5003.2 1830.01  5003.5 1829.51    5007 1829.51  5007.2 1830.01  5015.6 1830.91
  5022.5 1832.56    5028 1832.94  5074.3 1833.38  5269.8 1835.69  5284.3 1835.41
  5377.5 1837.18  5494.6 1840.09  5676.8 1847.35  5743.9 1848.82  5791.8  1849.9
#Mann= 11 ,-1 , 0
  4225.3    .035       0  4286.6     .07       0  4323.8    .035       0
  4811.7     .07       0  5002.9    .035       0  5003.2     .07       0
  5007.2    .035       0  5074.3     .07       0  5377.5    .035       0
  5676.8     .07       0  5743.9    .035       0
Bank Sta=5003.2,5007.2
XS Rating Curve= 0 ,0
Exp/Cntr=0.3,0.1

Type RM Length L Ch R = 1 ,5284    ,540,540,540
BEGIN DESCRIPTION:
Mapping XS 56218523
END DESCRIPTION:
XS GIS Cut Line= 4
      1527849.32       6841182.4      1528387.53      6840937.17
      1528630.58      6840863.39      1529118.89      6840459.72
#Sta/Elev= 30
  4316.3 1844.83  4384.8 1843.39    4575 1838.17  4597.3 1838.14    4839 1832.81
  4873.5 1830.84  4891.1 1830.78  4912.1 1829.61  4954.3 1827.93  4959.6 1829.02
  4978.3 1827.83  4985.2 1826.01  4985.5 1825.51    4989 1825.51  4989.2 1826.01
  4999.2 1828.08  5009.6 1828.69  5082.8 1828.87  5096.3 1830.13  5114.1 1829.34
  5164.5 1829.54  5254.2  1829.1  5346.7 1831.05  5448.4 1832.04  5492.7 1832.66
  5538.1 1833.09  5544.6 1833.69  5661.8 1836.17  5719.7 1837.68  5795.3 1839.67
#Mann= 10 ,-1 , 0
  4316.3     .07       0  4384.8    .035       0  4912.1     .07       0
  4985.2     .07       0  4989.2     .07       0  5164.5    .035       0
  5448.4     .07       0  5492.7    .035       0  5661.8     .07       0
  5719.7    .035       0
Bank Sta=4985.2,4989.2
XS Rating Curve= 0 ,0
Exp/Cntr=0.3,0.1

Type RM Length L Ch R = 1 ,4744    ,443,443,443
BEGIN DESCRIPTION:
Mapping XS 60ad1cc0
END DESCRIPTION:
XS GIS Cut Line= 3
      1528398.11      6841605.98      1528901.56      6841035.26
      1529205.38      6840596.89
#Sta/Elev= 30
  4238.7 1846.23  4439.5 1843.28  4494.3 1842.21  4648.9 1838.37  4688.9 1837.66
  4738.2 1834.47  4759.1 1833.77  4766.7 1832.77  4773.3 1833.09  4780.9 1832.15
    4822 1830.03  4844.5 1829.07  4922.3 1827.58  4958.1 1825.69  5014.6 1825.33
  5027.5 1824.41  5027.7 1823.91  5031.2 1823.91  5031.5 1824.41  5035.5 1826.35
  5050.4 1827.98  5057.2  1827.7  5070.6 1828.28    5122  1828.1  5179.4  1829.2
  5205.7 1829.87  5244.3  1830.3    5274 1831.51    5386 1834.25  5533.1 1839.51
#Mann= 12 ,-1 , 0
  4238.7     .07       0  4439.5    .035       0  4494.3     .07       0
  4648.9    .035       0    4822     .07       0  4958.1    .035       0
  5027.5    .035       0  5031.5    .035       0  5070.6     .07       0
  5179.4    .035       0  5205.7     .07       0    5386    .035       0
Bank Sta=5027.5,5031.5
XS Rating Curve= 0 ,0
Exp/Cntr=0.3,0.1

Type RM Length L Ch R = 1 ,4301    ,569,569,569
BEGIN DESCRIPTION:
Mapping XS 1e61be39
END DESCRIPTION:
XS GIS Cut Line= 3
      1528654.15      6841632.06      1529203.21      6841230.57
      1529396.36      6840657.64
#Sta/Elev= 30
  4166.6 1842.51  4334.7 1839.03  4355.5 1838.14    4364 1838.24  4378.3  1837.2
  4386.6 1837.28  4499.9 1834.13  4600.3 1830.65  4706.8 1827.94  4736.2 1827.67
    4757 1826.91  4771.7 1827.37  4808.8 1826.71  4899.7 1825.17  4934.9 1823.97
  4969.3 1824.19  5005.8 1823.55  5006.1 1823.05  5009.6 1823.05  5009.8 1823.55
  5018.4 1823.96  5029.4 1823.65  5060.9 1826.66  5081.7 1827.29  5092.3 1828.25
  5206.9 1832.05    5356 1836.25  5397.3 1837.96  5410.1 1838.42  5451.4 1839.59
#Mann= 10 ,-1 , 0
  4166.6     .07       0  4386.6    .035       0  4808.8     .07       0
  4899.7    .035       0  4969.3     .07       0  5005.8     .07       0
  5009.8     .07       0  5206.9    .035       0  5397.3     .07       0
  5410.1    .035       0
Bank Sta=5005.8,5009.8
XS Rating Curve= 0 ,0
Exp/Cntr=0.3,0.1

Type RM Length L Ch R = 1 ,3732    ,796,796,796
BEGIN DESCRIPTION:
Mapping XS 7112eda4
END DESCRIPTION:
XS GIS Cut Line= 3
      1528817.07      6841918.95      1529431.22      6841528.32
      1529797.19      6841051.91
#Sta/Elev= 30
  4262.2 1841.96  4301.9 1841.28  4327.1 1840.15  4363.5 1840.34  4376.7 1839.23
  4399.9 1838.86  4413.8 1839.35    4421 1838.52  4572.6 1835.26    4766 1829.47
  4906.2 1823.99  4948.6  1823.1  4987.3 1820.41  4987.6 1819.91  4991.1 1819.91
  4991.3 1820.41  5028.3 1821.89  5085.8 1823.07  5100.3 1823.21  5121.1 1822.44
  5172.7 1823.34  5217.3 1824.63    5306 1827.41  5314.2 1828.17    5335 1828.52
  5370.3 1830.32  5507.8 1835.17  5520.1 1836.18  5557.1 1836.88  5590.8 1838.88
#Mann= 9 ,-1 , 0
  4262.2    .045       0  4301.9     .07       0  4376.7    .035       0
    4766     .07       0  4987.3     .07       0  4991.3     .07       0
  5172.7    .035       0  5217.3     .07       0  5507.8    .035       0
Bank Sta=4987.3,4991.3
XS Rating Curve= 0 ,0
Exp/Cntr=0.3,0.1

Type RM Length L Ch R = 1 ,2936    ,422,422,422
BEGIN DESCRIPTION:
Mapping XS 1c16087f
END DESCRIPTION:
XS GIS Cut Line= 4
      1529005.84        6841856.       1529730.7      6841997.07
       1530021.5      6842014.43      1530514.16      6842127.29
#Sta/Elev= 30
  4188.7 1837.96  4289.7 1835.36    4361 1834.57  4379.3 1833.09    4564 1828.88
  4656.6 1826.52  4727.8 1824.76  4804.5 1824.07  4941.5 1821.82  5001.6 1816.87
  5026.7 1815.65  5049.7 1815.59  5049.9 1815.09  5053.4 1815.09  5053.7 1815.59
  5081.7 1816.71  5161.9 1824.89  5171.9 1823.45  5181.9 1820.46  5201.9 1819.98
    5212 1820.61  5263.1 1821.18  5343.2 1824.32  5348.4 1823.95  5355.4 1824.66
  5391.3 1825.05  5423.7 1826.38  5584.2 1829.51  5701.9 1831.59  5723.9 1831.47
#Mann= 8 ,-1 , 0
  4188.7    .035       0    4564     .07       0  4656.6    .035       0
  4804.5     .07       0  5049.7     .07       0  5053.7     .07       0
  5423.7    .035       0  5584.2     .07       0
Bank Sta=5049.7,5053.7
XS Rating Curve= 0 ,0
Exp/Cntr=0.3,0.1

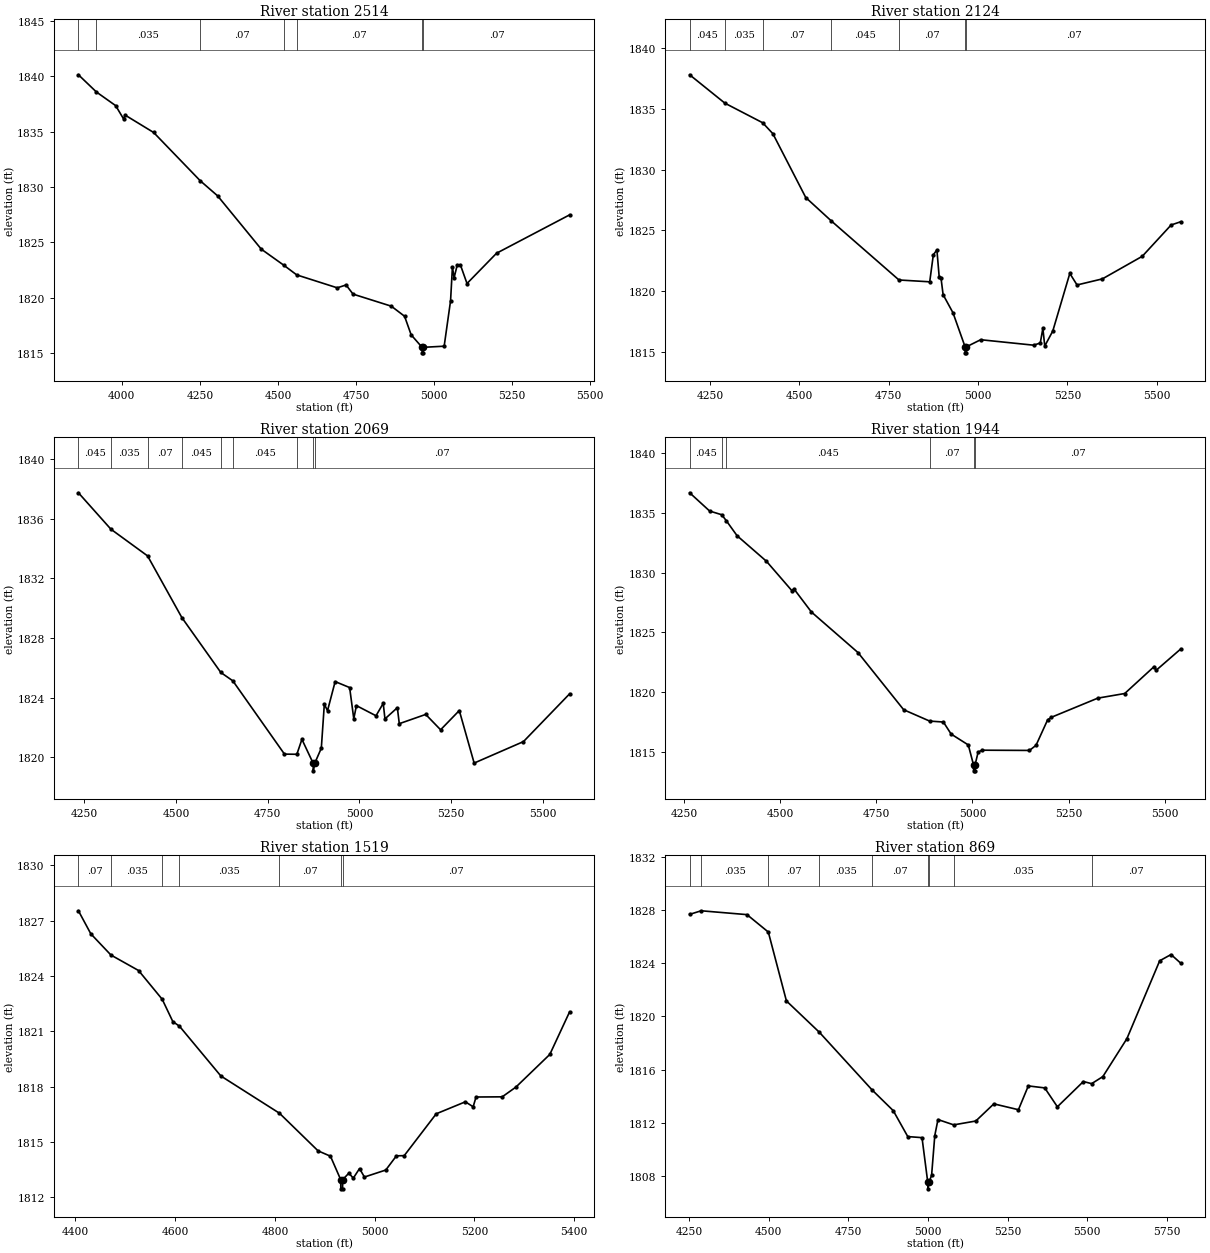
Type RM Length L Ch R = 1 ,2514    ,390,390,390
BEGIN DESCRIPTION:
Mapping XS 5efea5cf
END DESCRIPTION:
XS GIS Cut Line= 3
      1528987.34      6842038.73      1529944.39      6842201.49
       1530517.3      6842390.29
#Sta/Elev= 30
  3860.8 1840.15  3918.6 1838.59  3980.1 1837.36  4005.5 1836.16  4010.6  1836.5
  4101.9 1834.93  4251.3 1830.56  4306.8  1829.2  4446.7 1824.38  4518.2 1822.94
  4560.3 1822.05  4690.2 1820.88  4718.4 1821.14  4740.9 1820.31  4863.4 1819.22
  4905.9 1818.31    4927 1816.63    4962  1815.5  4962.3    1815  4965.8    1815
    4966  1815.5  5032.8  1815.6  5053.3 1819.71  5059.3 1822.77  5064.6 1821.79
  5074.4 1822.91  5084.9 1822.95    5106 1821.27  5200.7 1824.01  5434.8 1827.48
#Mann= 7 ,-1 , 0
  3860.8     .07       0  3918.6    .035       0  4251.3     .07       0
  4518.2    .045       0  4560.3     .07       0    4962     .07       0
    4966     .07       0
Bank Sta=4962,4966
XS Rating Curve= 0 ,0
Exp/Cntr=0.3,0.1

Type RM Length L Ch R = 1 ,2124    ,55,55,55
BEGIN DESCRIPTION:
Mapping XS 73512858
END DESCRIPTION:
XS GIS Cut Line= 6
      1529137.12       6842288.3      1529844.56      6842364.25
      1529955.24      6842444.55      1530061.57      6842464.08
        1530118.      6842444.55      1530471.91      6842500.66
#Sta/Elev= 30
  4193.2 1837.82  4291.9 1835.48  4397.4 1833.87    4426 1832.97  4518.1 1827.71
  4589.7 1825.78  4778.9 1820.92  4864.9 1820.77    4875 1822.99    4885  1823.4
  4891.5 1821.14  4896.5 1821.08  4902.4 1819.71    4930 1818.22  4963.8 1815.42
    4964 1814.92  4967.5 1814.92  4967.8 1815.42  5007.5    1816  5155.7 1815.55
  5174.3 1815.73  5181.5 1816.94  5186.8 1815.48  5209.3 1816.72  5256.9 1821.46
  5277.1 1820.51    5348 1821.01  5459.6 1822.87  5540.4 1825.45  5567.6 1825.72
#Mann= 7 ,-1 , 0
  4193.2    .045       0  4291.9    .035       0  4397.4     .07       0
  4589.7    .045       0  4778.9     .07       0  4963.8     .07       0
  4967.8     .07       0
Bank Sta=4963.8,4967.8
XS Rating Curve= 0 ,0
Exp/Cntr=0.3,0.1

Type RM Length L Ch R = 1 ,2069    ,125,125,125
BEGIN DESCRIPTION:
Mapping XS 86f68c64
END DESCRIPTION:
XS GIS Cut Line= 6
      1529145.81      6842333.88      1529816.35      6842398.98
      1529855.41      6842448.89       1530037.7      6842509.65
      1530131.02      6842492.29      1530441.74      6842544.08
#Sta/Elev= 30
  4233.7 1837.73  4322.3 1835.29  4422.3  1833.5  4515.7 1829.37    4622 1825.69
  4654.7 1825.13  4795.5 1820.22  4829.3 1820.21  4843.1 1821.21  4873.9  1819.6
  4874.1  1819.1  4877.9  1819.6    4896 1820.62  4904.2 1823.56  4912.9 1823.13
  4933.7 1825.08  4973.2 1824.68  4984.5 1822.59  4991.7 1823.47  5045.1 1822.79
  5064.8 1823.62  5069.5 1822.58  5103.3 1823.33  5108.6 1822.26  5180.6 1822.88
  5221.2 1821.85  5272.2 1823.14  5312.7 1819.62  5447.2 1821.06    5573 1824.26
#Mann= 9 ,-1 , 0
  4233.7    .045       0  4322.3    .035       0  4422.3     .07       0
  4515.7    .045       0    4622     .07       0  4654.7    .045       0
  4829.3     .07       0  4873.9     .07       0  4877.9     .07       0
Bank Sta=4873.9,4877.9
XS Rating Curve= 0 ,0
Exp/Cntr=0.3,0.1

Type RM Length L Ch R = 1 ,1944    ,425,425,425
BEGIN DESCRIPTION:
Mapping XS 202c97df
END DESCRIPTION:
XS GIS Cut Line= 4
      1529191.33       6842455.4      1529857.58      6842548.72
      1530065.91      6842566.08      1530460.47       6842598.6
#Sta/Elev= 30
  4264.4 1836.69  4316.4 1835.16  4347.8 1834.85  4359.5 1834.36  4387.8 1833.09
  4464.2 1830.95  4530.5 1828.48  4535.6 1828.64  4581.1  1826.7  4702.3  1823.3
  4821.1 1818.51  4888.6 1817.56  4924.4 1817.48  4944.6 1816.47  4989.2 1815.56
  5002.8 1813.89  5003.1 1813.39  5006.6 1813.39  5006.8 1813.89  5014.8 1814.96
  5024.9 1815.12  5148.3  1815.1  5165.4 1815.53  5195.5 1817.66  5205.5 1817.88
  5325.9 1819.48  5396.1 1819.87  5472.7 1822.13  5477.7 1821.81  5542.1 1823.61
#Mann= 6 ,-1 , 0
  4264.4    .045       0  4347.8     .07       0  4359.5    .045       0
  4888.6     .07       0  5002.8     .07       0  5006.8     .07       0
Bank Sta=5002.8,5006.8
XS Rating Curve= 0 ,0
Exp/Cntr=0.3,0.1

Type RM Length L Ch R = 1 ,1519    ,650,650,650
BEGIN DESCRIPTION:
Mapping XS fc6553e8
END DESCRIPTION:
XS GIS Cut Line= 3
      1529548.09      6843019.64      1530016.87      6842901.58
      1530447.41      6842644.64
#Sta/Elev= 30
    4406 1827.53  4430.9 1826.28  4471.2 1825.13  4526.6 1824.29    4574 1822.73
  4595.3 1821.52  4608.6 1821.27  4691.6 1818.57  4809.1 1816.55  4886.5 1814.51
  4911.3 1814.22  4931.8 1812.95  4932.1 1812.45  4935.6 1812.45  4935.8 1812.95
  4948.2  1813.3  4957.1 1813.03  4969.6 1813.55  4979.4 1813.09  5022.2 1813.47
  5043.6 1814.24  5059.2 1814.25  5123.4 1816.52  5181.8 1817.17  5197.4  1816.9
  5203.2 1817.43  5255.7 1817.44  5283.2 1817.97  5351.1 1819.74  5390.8 1822.05
#Mann= 7 ,-1 , 0
    4406     .07       0  4471.2    .035       0    4574     .07       0
  4608.6    .035       0  4809.1     .07       0  4931.8     .07       0
  4935.8     .07       0
Bank Sta=4931.8,4935.8
XS Rating Curve= 0 ,0
Exp/Cntr=0.3,0.1

Type RM Length L Ch R = 1 ,869     ,476,476,476
BEGIN DESCRIPTION:
Mapping XS b3663709
END DESCRIPTION:
XS GIS Cut Line= 3
       1529548.1        6843287.      1530413.57      6843218.57
       1530542.7      6842557.74
#Sta/Elev= 30
  4252.3 1827.67  4288.5 1827.94  4432.3 1827.65  4499.2 1826.34    4556 1821.16
  4659.5  1818.8  4825.1 1814.46  4891.2 1812.91  4936.8 1810.96  4981.5 1810.88
  4999.5 1807.53  4999.8 1807.03  5003.5 1807.53  5011.6 1808.05  5021.6 1811.04
  5031.6 1812.24    5081 1811.84  5150.3 1812.13  5206.9 1813.42  5284.1 1812.98
  5315.1 1814.77  5366.6 1814.62  5406.3  1813.2  5487.9  1815.1  5513.8 1814.94
    5549 1815.47  5624.4 1818.32  5727.4 1824.18    5763 1824.65  5793.8 1823.99
#Mann= 9 ,-1 , 0
  4252.3     .07       0  4288.5    .035       0  4499.2     .07       0
  4659.5    .035       0  4825.1     .07       0  4999.5     .07       0
  5003.5     .07       0    5081    .035       0  5513.8     .07       0
Bank Sta=4999.5,5003.5
XS Rating Curve= 0 ,0
Exp/Cntr=0.3,0.1

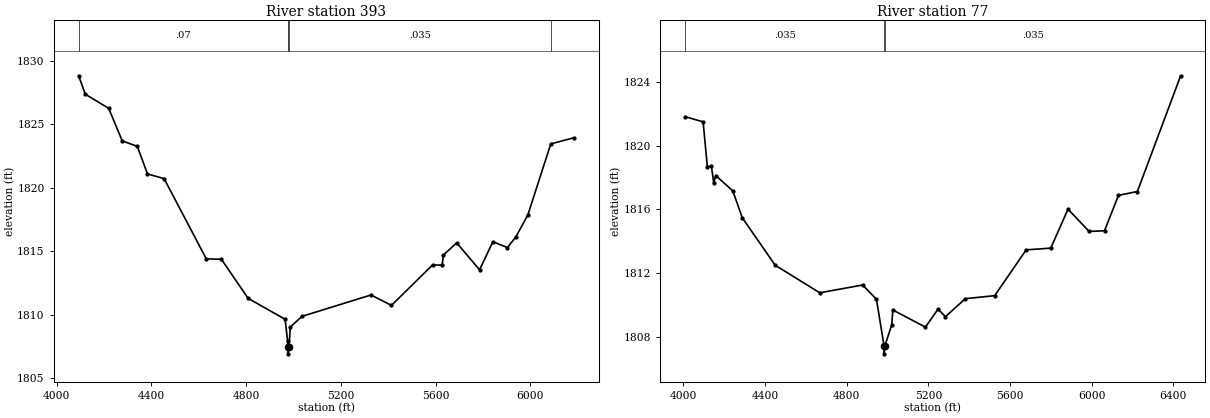
Type RM Length L Ch R = 1 ,393     ,316,316,316
BEGIN DESCRIPTION:
Mapping XS 15026cab
END DESCRIPTION:
XS GIS Cut Line= 3
       1529579.4      6844241.83      1530357.15      6843585.61
      1530568.66      6842531.53
#Sta/Elev= 30
  4092.3  1828.8  4120.4 1827.35  4219.2 1826.24  4276.4 1823.68  4340.1 1823.25
    4383 1821.08  4453.3 1820.71  4631.4  1814.4  4695.1 1814.37  4808.3 1811.29
  4964.3 1809.65  4974.9 1807.92  4976.6 1807.43  4976.8 1806.93  4980.6 1807.43
  4986.3 1809.04  5035.8 1809.88  5327.2 1811.56  5413.4 1810.74  5586.9 1813.92
  5627.6 1813.91  5632.7  1814.7  5688.8 1815.66  5785.5 1813.54  5841.8 1815.75
    5903 1815.29  5938.2 1816.11  5989.1 1817.84  6086.1 1823.44    6185 1823.93
#Mann= 5 ,-1 , 0
  4092.3     .07       0  4974.9    .035       0  4976.6    .035       0
  4980.6    .035       0  6086.1     .07       0
Bank Sta=4976.6,4980.6
XS Rating Curve= 0 ,0
Exp/Cntr=0.3,0.1

Type RM Length L Ch R = 1 ,77      ,0,0,0
BEGIN DESCRIPTION:
BULL WAGON CREEK TRIBUTARY 6_1 1.0
END DESCRIPTION:
XS GIS Cut Line= 3
      1530063.75      6844872.92      1530334.21       6843918.5
      1530666.75      6842521.74
#Sta/Elev= 30
    4008 1821.84  4096.3 1821.51    4117 1818.69  4136.8 1818.73  4148.2 1817.68
  4158.6 1818.13  4241.8 1817.17  4288.1 1815.48  4449.6 1812.49  4667.9 1810.76
  4877.8 1811.25  4945.6 1810.35  4982.7 1807.42    4983 1806.92  4986.7 1807.42
  5020.5 1808.75  5025.6 1809.68  5185.5  1808.6  5247.2 1809.73  5283.6 1809.26
  5380.9 1810.39  5524.8 1810.58    5679 1813.46  5799.7 1813.57    5884 1816.02
  5987.3 1814.62  6062.8 1814.66  6131.3 1816.89  6223.8 1817.13  6435.8 1824.41
#Mann= 3 ,-1 , 0
    4008    .035       0  4982.7    .035       0  4986.7    .035       0
Bank Sta=4982.7,4986.7
XS Rating Curve= 0 ,0
Exp/Cntr=0.3,0.1

Chan Stop Cuts=-1
Use User Specified Reach Order=0
Composite Channel Slope=5