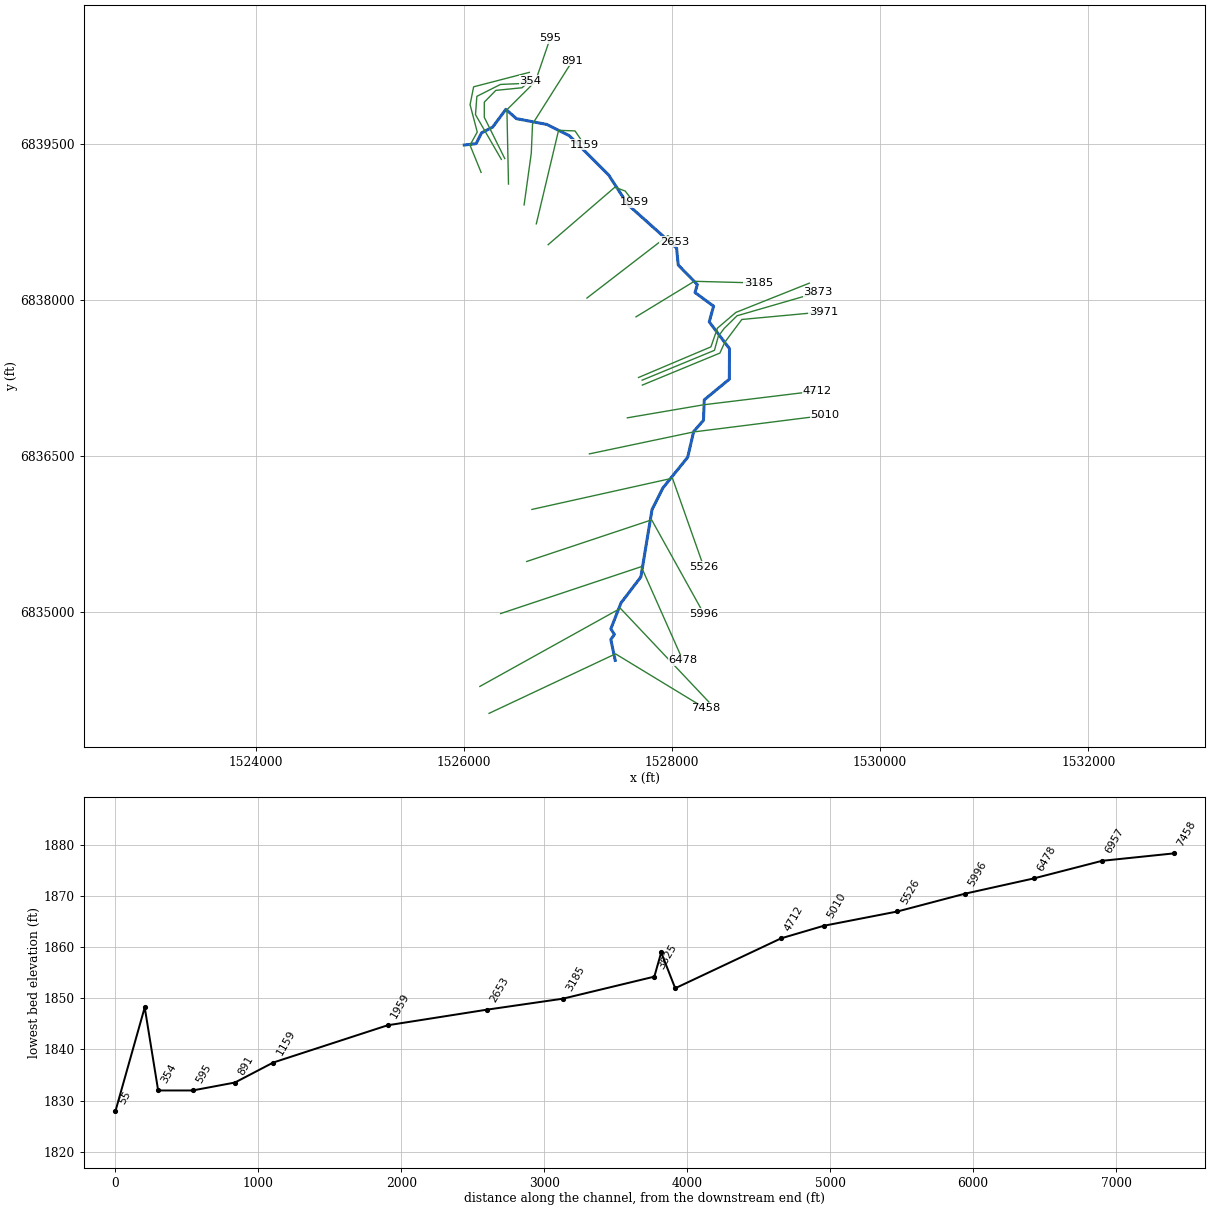
--- BULL WAGON CREEK TRIBUTARY 7.prj (project) ---

Proj Title=BULL WAGON CREEK TRIBUTARY 7 Base Level Engineering
Current Plan=p01
Default Exp/Contr=0.3,0.1
English Units
Geom File=g01
Flow File=f01
Plan File=p01
Y Axis Title=Elevation
X Axis Title(PF)=Main Channel Distance
X Axis Title(XS)=Station
BEGIN DESCRIPTION:
BULL WAGON CREEK TRIBUTARY 7
END DESCRIPTION:
DSS Export Rating Curves= 0
DSS Export Rating Curve Sorted= 0
DSS Export Volume Flow Curves= 0
DXF OffsetX= 0
DXF OffsetY= 0
DXF ScaleX= 1
DXF ScaleY= 10

--- BULL WAGON CREEK TRIBUTARY 7.p01 (plan) ---

Plan Title=Multiple Run
Short Identifier=Multiple
Geom File=g01
Flow File=f01
Subcritical Flow
K Sum by GR= 0
Std Step Tol= 0.01
Critical Tol= 0.01
Num of Std Step Trials= 20
Max Error Tol= 0.3
Flow Tol Ratio= 0.001
Split Flow NTrial= 30
Split Flow Tol= 0.02
Split Flow Ratio= 0.02
Log Output Level= 0
Friction Slope Method= 1
Unsteady Friction Slope Method= 2
Unsteady Bridges Friction Slope Method= 1
Parabolic Critical Depth
Global Vel Dist=  1 , 1 , 1
Global Log Level= 0
CheckData=True
Encroach Param= -1, 0, 0, 0
BEGIN DESCRIPTION:
Multiple Run
END DESCRIPTION:

--- BULL WAGON CREEK TRIBUTARY 7.f01 (steady flow) ---

Flow Title=Multiple
Program Version=4.10
Number of Profiles= 7
Profile Names=10-year,25-year,50-year,1pct_min,100-year,1pct_plu,500-year
River Rch & RM=BULL WAGON CREEK,Reach-1         ,7458
     149     198     237     141     282     563     404
River Rch & RM=BULL WAGON CREEK,Reach-1         ,3971
     213     290     353     213     426     850     629
Boundary for River Rch & Prof#=BULL WAGON CREEK,Reach-1         , 1
Up Type= 0
Dn Type= 3
Dn Slope=0.09
Boundary for River Rch & Prof#=BULL WAGON CREEK,Reach-1         , 2
Up Type= 0
Dn Type= 3
Dn Slope=0.09
Boundary for River Rch & Prof#=BULL WAGON CREEK,Reach-1         , 3
Up Type= 0
Dn Type= 3
Dn Slope=0.09
Boundary for River Rch & Prof#=BULL WAGON CREEK,Reach-1         , 4
Up Type= 0
Dn Type= 3
Dn Slope=0.09
Boundary for River Rch & Prof#=BULL WAGON CREEK,Reach-1         , 5
Up Type= 0
Dn Type= 3
Dn Slope=0.09
Boundary for River Rch & Prof#=BULL WAGON CREEK,Reach-1         , 6
Up Type= 0
Dn Type= 3
Dn Slope=0.09
Boundary for River Rch & Prof#=BULL WAGON CREEK,Reach-1         , 7
Up Type= 0
Dn Type= 3
Dn Slope=0.09
DSS Import GetInterval= 0
DSS Import GetPeak= 0
DSS Import FillOption= 0

--- BULL WAGON CREEK TRIBUTARY 7.g01 (geometry) ---

Geom Title=Existing Conditions
Program Version=4.10

River Reach=BULL WAGON CREEK,Reach-1
Reach XY= 30
        1527455.        6834538.      1527412.78       6834738.1
      1527446.97        6834788.      1527413.27      6834841.22
      1527510.84      6835090.29      1527701.45      6835339.47
      1527808.75      6835986.45      1527913.14      6836194.06
      1528151.38       6836489.5      1528208.62       6836736.5
      1528302.93      6836843.86      1528310.46      6837040.45
      1528551.55      6837239.25      1528552.76      6837532.07
      1528358.13      6837789.64      1528400.01      6837940.55
      1528221.38       6838071.3      1528243.76        6838148.
      1528060.47      6838335.55      1528044.52       6838497.8
      1527578.01      6838914.53      1527391.37      6839201.21
      1527014.68      6839577.24      1526799.07      6839685.75
       1526506.5      6839741.64      1526404.78      6839831.01
      1526278.51        6839661.       1526171.5      6839605.04
      1526118.71      6839501.19        1526005.        6839488.

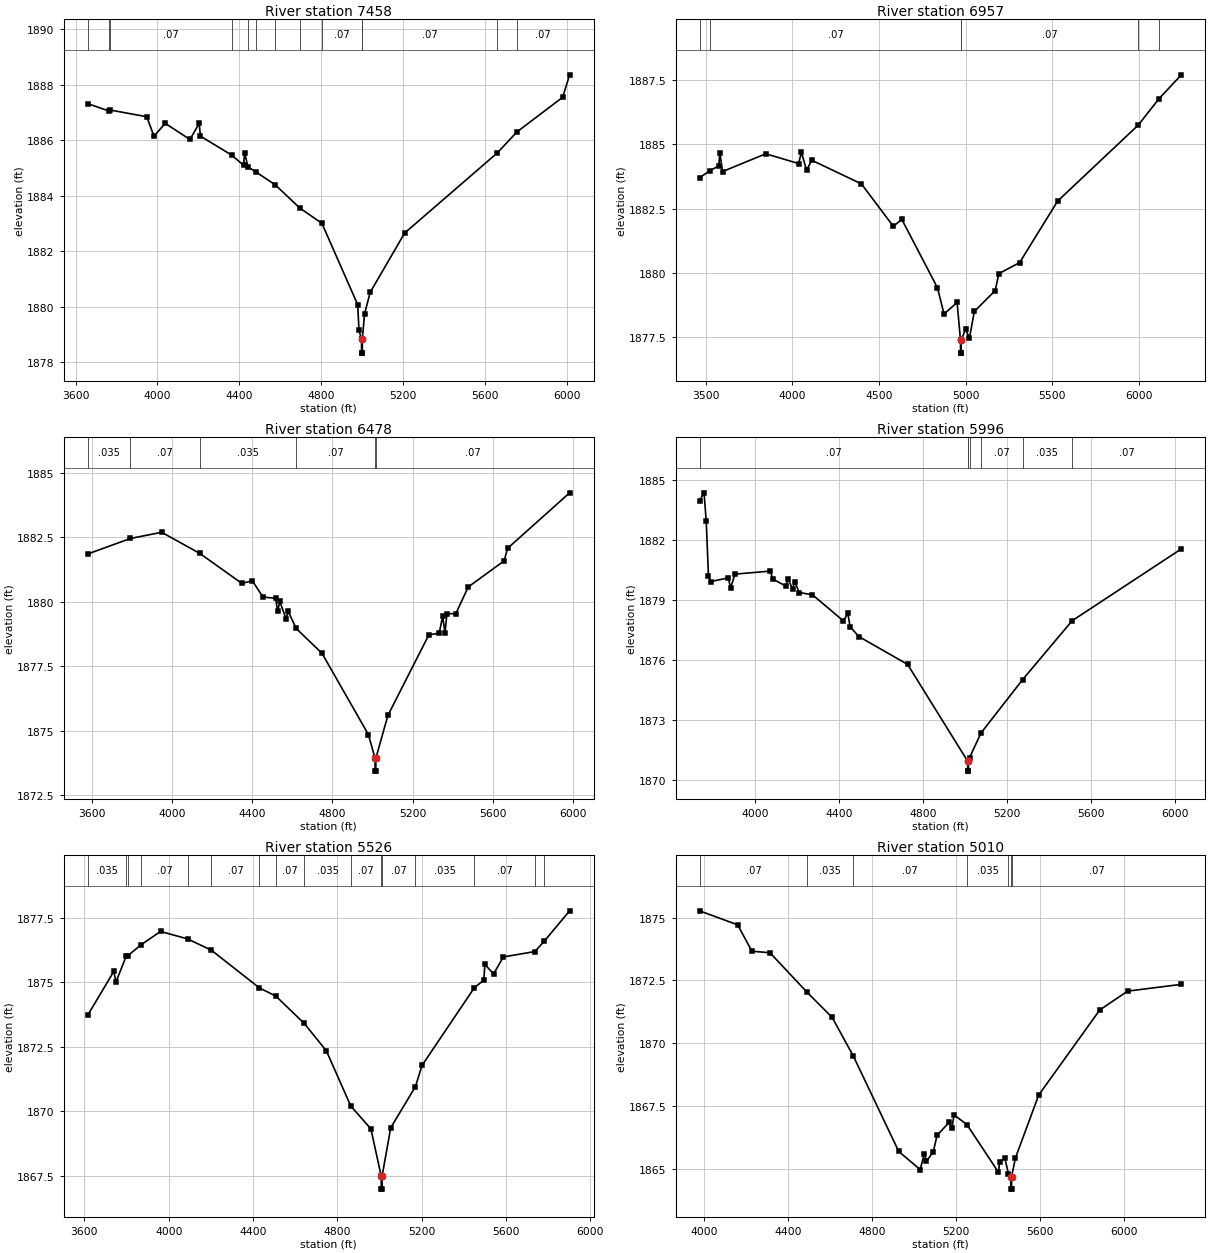
Type RM Length L Ch R = 1 ,7458    ,501,501,501
BEGIN DESCRIPTION:
BULL WAGON CREEK TRIBUTARY 7 14.0
END DESCRIPTION:
XS GIS Cut Line= 3
      1526243.06        6834029.      1527457.92      6834600.62
      1528320.63      6834076.23
#Sta/Elev= 30
  3660.4 1887.32  3765.7 1887.05  3769.8 1887.09    3948 1886.85    3983 1886.15
  4038.3 1886.61  4158.7 1886.03  4204.1 1886.61  4209.8 1886.15    4362 1885.47
  4420.5  1885.1    4426 1885.55    4442 1885.04    4479 1884.87  4576.2 1884.39
    4695 1883.56  4802.9 1883.01  4977.7 1880.08  4984.2 1879.15  4996.6 1878.83
  4996.9 1878.33  5000.4 1878.33  5000.6 1878.83  5011.3 1879.75  5038.8 1880.52
  5207.3 1882.66  5660.2 1885.55    5755  1886.3  5978.5 1887.55  6012.6 1888.36
#Mann= 13 ,-1 , 0
  3660.4     .07       0  3765.7    .035       0  3769.8     .07       0
    4362    .035       0    4442     .07       0    4479    .035       0
  4576.2     .07       0    4695    .035       0  4802.9     .07       0
  4996.6     .07       0  5000.6     .07       0  5660.2    .035       0
    5755     .07       0
Bank Sta=4996.6,5000.6
XS Rating Curve= 0 ,0
Exp/Cntr=0.3,0.1

Type RM Length L Ch R = 1 ,6957    ,479,479,479
BEGIN DESCRIPTION:
BULL WAGON CREEK TRIBUTARY 7 13.0
END DESCRIPTION:
XS GIS Cut Line= 3
      1526154.96      6834287.98        1527505.        6835038.
      1528354.98      6834138.02
#Sta/Elev= 30
    3464  1883.7  3525.1 1883.98    3575 1884.16  3580.7 1884.68  3596.7 1883.94
  3846.1 1884.63    4036 1884.25    4052 1884.69  4081.8 1883.99  4111.5 1884.38
  4398.7 1883.46  4582.8 1881.81    4632 1882.08  4837.9 1879.42  4875.7  1878.4
  4951.2 1878.85  4970.9 1877.38  4971.2 1876.88  4974.7 1876.88  4974.9 1877.38
  5000.4 1877.82  5022.3 1877.46  5050.7  1878.5  5171.2 1879.31  5192.3 1879.97
  5312.4  1880.4  5531.7 1882.79  5998.1 1885.75  6117.2 1886.77  6246.3  1887.7
#Mann= 6 ,-1 , 0
    3464    .035       0  3525.1     .07       0  4970.9     .07       0
  4974.9     .07       0  5998.1    .035       0  6117.2     .07       0
Bank Sta=4970.9,4974.9
XS Rating Curve= 0 ,0
Exp/Cntr=0.3,0.1

Type RM Length L Ch R = 1 ,6478    ,482,482,482
BEGIN DESCRIPTION:
BULL WAGON CREEK TRIBUTARY 7 12.0
END DESCRIPTION:
XS GIS Cut Line= 3
      1526354.98      6834987.99        1527705.        6835438.
      1528104.99      6834538.03
#Sta/Elev= 30
  3577.3 1881.85  3789.5 1882.45  3946.3 1882.69  4136.9 1881.87  4346.8 1880.71
  4399.5 1880.81  4452.2 1880.18  4515.5 1880.13    4526 1879.62  4536.5 1880.01
  4568.2 1879.33  4578.7 1879.62  4618.5 1878.96  4747.4    1878  4979.3 1874.85
  5012.7 1873.93    5013 1873.43  5016.5 1873.43  5016.7 1873.93  5076.9 1875.59
  5281.4 1878.71  5333.4 1878.78  5350.5 1879.43  5362.2  1878.8  5372.4 1879.54
  5416.2 1879.53  5478.4 1880.57  5657.6 1881.58  5675.4 1882.07  5985.2 1884.22
#Mann= 6 ,-1 , 0
  3577.3    .035       0  3789.5     .07       0  4136.9    .035       0
  4618.5     .07       0  5012.7     .07       0  5016.7     .07       0
Bank Sta=5012.7,5016.7
XS Rating Curve= 0 ,0
Exp/Cntr=0.3,0.1

Type RM Length L Ch R = 1 ,5996    ,470,470,470
BEGIN DESCRIPTION:
BULL WAGON CREEK TRIBUTARY 7 11.0
END DESCRIPTION:
XS GIS Cut Line= 3
      1526605.01        6835488.        1527805.        6835888.
      1528305.02      6834987.96
#Sta/Elev= 30
  3735.1 1883.95  3756.2 1884.34  3766.7 1882.93  3777.2 1880.21  3787.8 1879.91
  3872.1 1880.09  3882.7 1879.59  3903.7 1880.28  4072.4 1880.43  4082.9 1880.04
  4146.2 1879.68  4156.7 1880.04  4177.8 1879.53  4188.3 1879.91  4209.4 1879.36
  4272.7 1879.25  4420.2 1877.94  4441.3 1878.32  4451.9 1877.65    4494 1877.16
  4725.9 1875.77  5011.7 1870.94    5012 1870.44  5015.5 1870.44  5015.7 1870.94
    5021 1871.12  5075.9 1872.35  5273.6 1875.01  5509.5 1877.95  6029.6 1881.54
#Mann= 7 ,-1 , 0
  3735.1     .07       0  5011.7     .07       0  5015.7     .07       0
    5021    .035       0  5075.9     .07       0  5273.6    .035       0
  5509.5     .07       0
Bank Sta=5011.7,5015.7
XS Rating Curve= 0 ,0
Exp/Cntr=0.3,0.1

Type RM Length L Ch R = 1 ,5526    ,516,516,516
BEGIN DESCRIPTION:
BULL WAGON CREEK TRIBUTARY 7 10.0
END DESCRIPTION:
XS GIS Cut Line= 3
      1526654.96      6835987.99        1528005.        6836288.
      1528305.01      6835437.96
#Sta/Elev= 30
  3616.8 1873.74  3739.8 1875.43    3750 1875.02  3798.6 1876.02  3806.2 1876.04
  3868.9 1876.46  3961.3 1876.98  4089.7 1876.69  4202.8 1876.25  4429.9 1874.79
  4508.3 1874.47  4642.8 1873.41  4747.5 1872.35  4863.9  1870.2  4958.8 1869.32
  5007.9 1867.48  5008.2 1866.98  5011.7 1866.98  5011.9 1867.48  5052.8 1869.36
  5170.2 1870.96  5201.3 1871.78  5449.8  1874.8  5494.2 1875.09  5499.5  1875.7
  5540.6 1875.33    5587 1875.99  5736.6  1876.2  5781.9 1876.61  5901.2 1877.78
#Mann= 16 ,-1 , 0
  3616.8    .035       0  3798.6     .07       0  3806.2    .035       0
  3868.9     .07       0  4089.7    .035       0  4202.8     .07       0
  4429.9    .035       0  4508.3     .07       0  4642.8    .035       0
  4863.9     .07       0  5007.9     .07       0  5011.9     .07       0
  5170.2    .035       0  5449.8     .07       0  5736.6    .035       0
  5781.9     .07       0
Bank Sta=5007.9,5011.9
XS Rating Curve= 0 ,0
Exp/Cntr=0.3,0.1

Type RM Length L Ch R = 1 ,5010    ,298,298,298
BEGIN DESCRIPTION:
BULL WAGON CREEK TRIBUTARY 7 9.0
END DESCRIPTION:
XS GIS Cut Line= 3
      1527207.27      6836521.62      1528207.16      6836732.11
      1529468.57      6836891.13
#Sta/Elev= 30
  3978.2 1875.27  4159.8 1874.71  4226.9 1873.66  4313.1  1873.6  4490.4 1872.02
  4609.5 1871.02  4710.8 1869.47  4926.3 1865.68  5028.1 1864.96  5048.2 1865.59
  5058.3 1865.29  5090.3 1865.66  5108.7 1866.32  5165.6 1866.84  5179.2  1866.6
  5189.3 1867.14    5251 1866.75    5401 1864.85  5406.5 1865.28  5431.2 1865.41
  5448.5 1864.79  5459.5 1864.68  5459.7 1864.18  5463.2 1864.18  5463.5 1864.68
  5481.6 1865.42  5592.5 1867.93  5883.2 1871.32  6015.8 1872.07  6271.4 1872.34
#Mann= 7 ,-1 , 0
  3978.2     .07       0  4490.4    .035       0  4710.8     .07       0
    5251    .035       0  5448.5     .07       0  5459.5     .07       0
  5463.5     .07       0
Bank Sta=5459.5,5463.5
XS Rating Curve= 0 ,0
Exp/Cntr=0.3,0.1

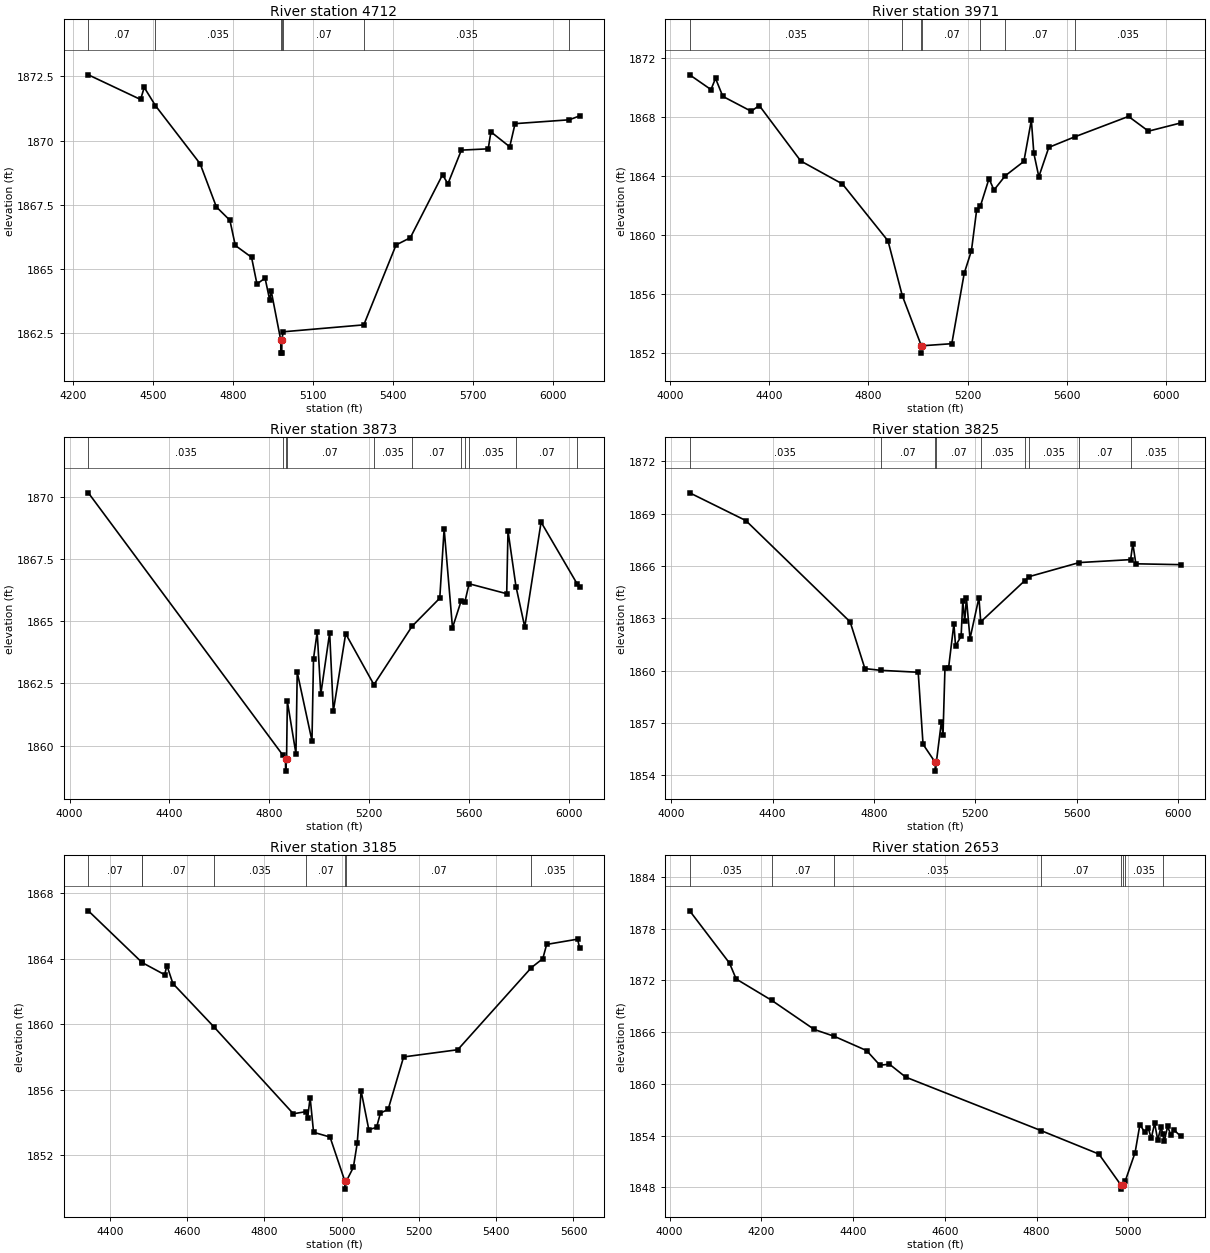
Type RM Length L Ch R = 1 ,4712    ,741,741,741
BEGIN DESCRIPTION:
BULL WAGON CREEK TRIBUTARY 7 8.0
END DESCRIPTION:
XS GIS Cut Line= 3
      1527571.85      6836867.97      1528304.53       6836993.2
      1529394.79      6837125.79
#Sta/Elev= 30
  4256.7 1872.56  4452.6  1871.6  4466.2 1872.07  4508.3 1871.36  4675.8  1869.1
  4736.7 1867.42  4787.4  1866.9  4807.7 1865.92  4868.6 1865.46  4888.9 1864.42
  4919.3 1864.65    4937 1863.78  4942.1 1864.16  4978.2 1862.23  4978.4 1861.73
  4981.9 1861.73  4982.2 1862.23  4987.1 1862.56  5289.5 1862.83  5410.5 1865.94
  5463.9 1866.22  5584.7 1868.67  5604.9 1868.32  5655.3 1869.63    5756 1869.68
  5766.1 1870.34  5836.6 1869.76  5856.7 1870.66  6059.8 1870.81  6098.3 1870.96
#Mann= 7 ,-1 , 0
  4256.7     .07       0  4508.3    .035       0  4978.2     .07       0
  4982.2    .035       0  4987.1     .07       0  5289.5    .035       0
  6059.8     .07       0
Bank Sta=4978.2,4982.2
XS Rating Curve= 0 ,0
Exp/Cntr=0.3,0.1

Type RM Length L Ch R = 1 ,3971    ,98,98,98
BEGIN DESCRIPTION:
BULL WAGON CREEK TRIBUTARY 7 7.0
END DESCRIPTION:
XS GIS Cut Line= 5
      1527715.71      6837182.42       1528460.5      6837489.71
      1528507.74      6837594.14      1528671.43      6837812.63
      1529455.24      6837885.54
#Sta/Elev= 30
  4079.7 1870.84  4165.5 1869.84  4183.9  1870.6  4213.2 1869.38  4327.7 1868.37
  4360.2 1868.76  4527.4    1865  4695.5 1863.44  4879.4 1859.58  4936.9 1855.87
  5013.7 1852.47    5014 1851.97  5017.9 1852.47  5136.6 1852.61  5186.6 1857.38
  5215.8 1858.92  5236.6 1861.65  5251.9 1861.94  5286.6  1863.8  5306.7 1863.03
  5352.4    1864  5427.2 1864.97  5457.4 1867.77  5467.4 1865.52  5487.5 1863.93
  5527.7 1865.92  5631.5 1866.63  5849.1 1868.02  5929.6 1867.02  6060.2 1867.58
#Mann= 7 ,-1 , 0
  4079.7    .035       0  4936.9     .07       0  5013.7     .07       0
  5017.9     .07       0  5251.9    .035       0  5352.4     .07       0
  5631.5    .035       0
Bank Sta=5013.7,5017.9
XS Rating Curve= 0 ,0
Exp/Cntr=0.3,0.1

Type RM Length L Ch R = 1 ,3873    ,48,48,48
BEGIN DESCRIPTION:
Mapping XS 94d1cc7a
END DESCRIPTION:
XS GIS Cut Line= 6
      1527713.96      6837229.73      1528408.41      6837516.19
       1528445.3      6837650.74      1528501.73      6837726.69
      1528625.43      6837848.22       1529402.9      6838073.45
#Sta/Elev= 30
  4075.4 1870.17  4855.8  1859.6  4865.5 1859.47  4865.8 1858.97  4869.7 1859.47
  4872.8 1861.78  4907.3 1859.67  4912.4 1862.95  4971.5 1860.19  4977.7  1863.5
  4992.3 1864.56  5006.9 1862.07  5042.4 1864.54    5057 1861.38  5106.5  1864.5
  5219.7 1862.45  5372.6  1864.8  5483.6 1865.93  5501.1 1868.72  5534.6 1864.74
  5569.6 1865.83  5583.9 1865.77  5601.2 1866.51  5751.8 1866.11    5757 1868.64
    5789  1866.4  5824.2 1864.77  5889.6 1868.99  6033.9 1866.51  6043.6 1866.36
#Mann= 11 ,-1 , 0
  4075.4    .035       0  4855.8     .07       0  4865.5     .07       0
  4869.7     .07       0  5219.7    .035       0  5372.6     .07       0
  5569.6    .035       0  5583.9     .07       0  5601.2    .035       0
    5789     .07       0  6033.9    .035       0
Bank Sta=4865.5,4869.7
XS Rating Curve= 0 ,0
Exp/Cntr=0.3,0.1

Type RM Length L Ch R = 1 ,3825    ,640,640,640
BEGIN DESCRIPTION:
Mapping XS 4b0c9644
END DESCRIPTION:
XS GIS Cut Line= 5
      1527679.27      6837255.35      1528374.56      6837549.61
      1528437.06      6837729.29      1528614.14      6837880.34
      1529319.88      6838161.59
#Sta/Elev= 30
  4073.1  1870.2  4294.5 1868.61  4706.1  1862.8  4764.3 1860.12  4827.2 1860.02
  4974.6 1859.91  4993.7 1855.78  5041.9 1854.74  5042.2 1854.24  5046.1 1854.74
    5066 1857.06  5072.5 1856.33  5080.2 1860.15  5094.5 1860.17  5115.4 1862.69
  5121.9 1861.42  5143.9 1861.98  5150.5    1864  5158.2 1862.84  5164.8 1864.16
    5179 1861.84  5214.2 1864.19  5221.3  1862.8  5395.5 1865.17  5411.3 1865.39
  5609.6  1866.2  5812.6 1866.37  5821.3 1867.29  5833.3 1866.13  6010.8 1866.08
#Mann= 9 ,-1 , 0
  4073.1    .035       0  4827.2     .07       0  5041.9     .07       0
  5046.1     .07       0  5221.3    .035       0  5395.5     .07       0
  5411.3    .035       0  5609.6     .07       0  5812.6    .035       0
Bank Sta=5041.9,5046.1
XS Rating Curve= 0 ,0
Exp/Cntr=0.3,0.1

Type RM Length L Ch R = 1 ,3185    ,532,532,532
BEGIN DESCRIPTION:
BULL WAGON CREEK TRIBUTARY 7 6.0
END DESCRIPTION:
XS GIS Cut Line= 3
      1527655.03      6837838.02      1528214.51      6838179.19
      1528829.99        6838163.
#Sta/Elev= 30
  4344.7 1866.92    4483 1863.78  4484.8 1863.75  4542.1 1863.02    4548 1863.58
  4563.5 1862.48  4669.5 1859.84  4875.2 1854.53  4907.7 1854.66    4912 1854.27
  4918.6 1855.52  4927.5  1853.4  4970.1 1853.11  5008.3 1850.43  5008.6 1849.93
  5012.6 1850.43  5030.5 1851.26  5040.5 1852.74  5050.5 1855.93  5070.5 1853.56
  5090.5  1853.7  5100.5 1854.57  5120.5  1854.8  5160.5    1858  5300.6 1858.44
    5491 1863.45  5520.7    1864  5530.7 1864.87  5610.7 1865.19  5615.7 1864.68
#Mann= 8 ,-1 , 0
  4344.7     .07       0    4483    .035       0  4484.8     .07       0
  4669.5    .035       0  4907.7     .07       0  5008.3     .07       0
  5012.6     .07       0    5491    .035       0
Bank Sta=5008.3,5012.6
XS Rating Curve= 0 ,0
Exp/Cntr=0.3,0.1

Type RM Length L Ch R = 1 ,2653    ,694,694,694
BEGIN DESCRIPTION:
Mapping XS c1434697
END DESCRIPTION:
XS GIS Cut Line= 3
      1527183.56      6838018.26      1527961.92      6838618.21
      1528026.09      6838557.91
#Sta/Elev= 30
  4043.7 1880.08  4130.5 1874.01    4145 1872.17  4222.2  1869.7  4315.3 1866.31
  4358.7 1865.52  4429.4 1863.86  4458.4 1862.16  4479.2 1862.28  4514.6 1860.78
  4809.8 1854.57  4935.8 1851.85  4983.5 1848.28  4983.8 1847.78  4987.8 1848.28
    4993 1848.68  5014.7 1852.02  5025.2 1855.27  5035.8 1854.38  5043.1  1854.9
    5050 1853.68  5057.3 1855.43  5064.1 1853.48  5071.4 1855.04  5074.8  1854.2
  5078.3 1853.34  5085.6 1855.05  5092.4 1854.11  5099.3 1854.66  5114.5  1853.9
#Mann= 8 ,-1 , 0
  4043.7    .035       0  4222.2     .07       0  4358.7    .035       0
  4809.8     .07       0  4983.5    .035       0  4987.8     .07       0
    4993    .035       0  5074.8     .07       0
Bank Sta=4983.5,4987.8
XS Rating Curve= 0 ,0
Exp/Cntr=0.3,0.1

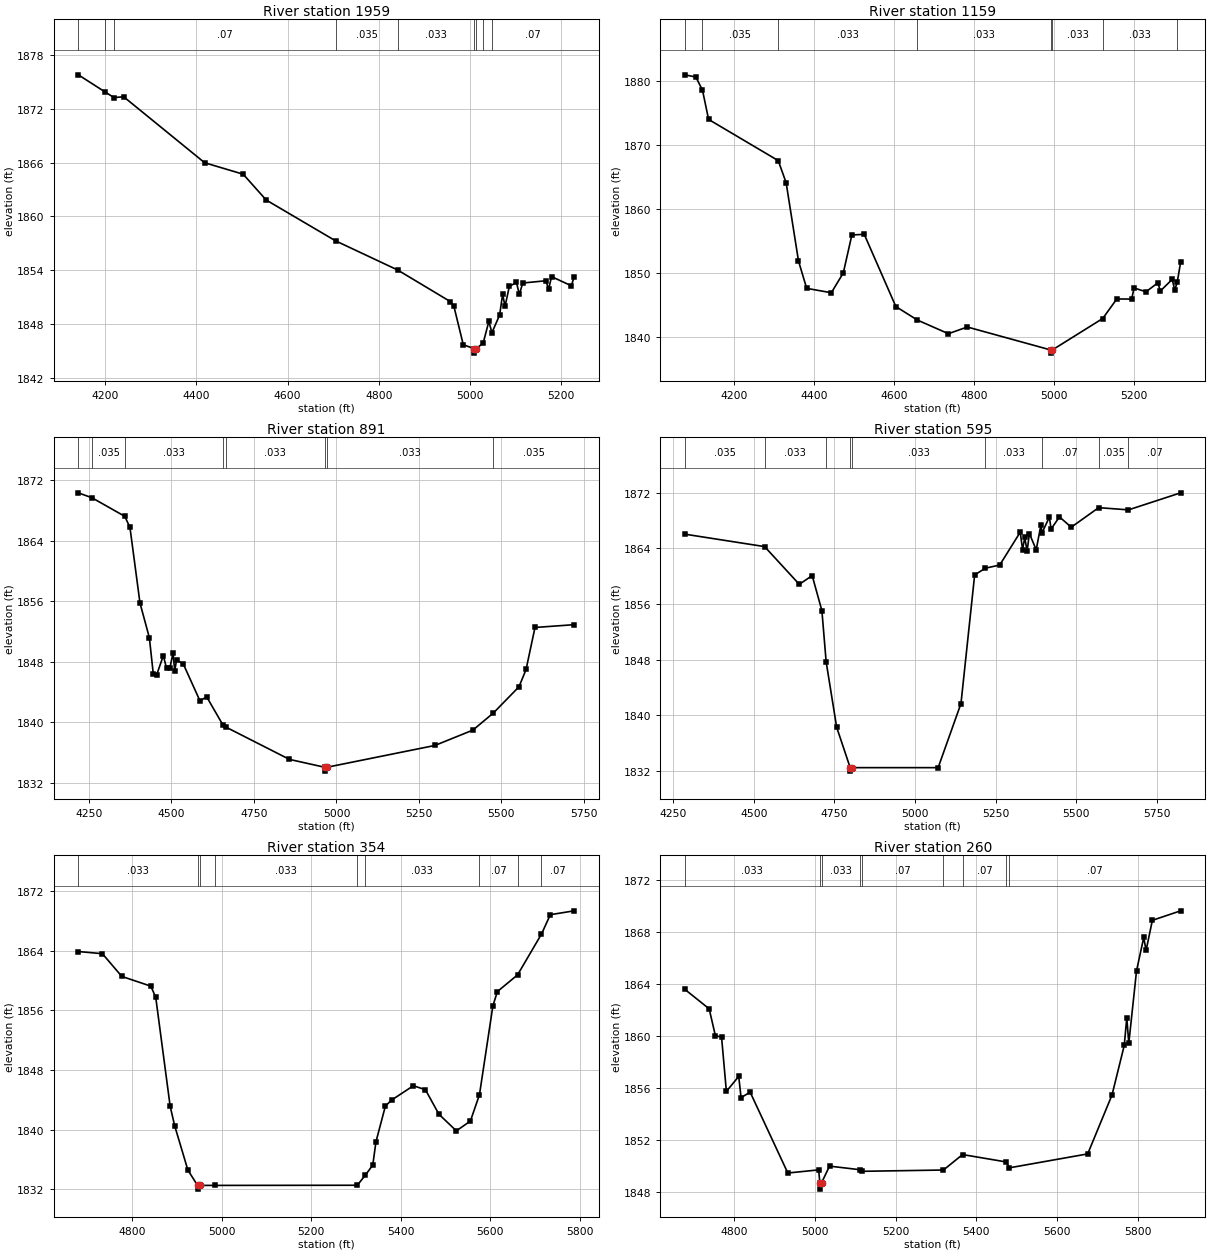
Type RM Length L Ch R = 1 ,1959    ,800,800,800
BEGIN DESCRIPTION:
Mapping XS 067deabd
END DESCRIPTION:
XS GIS Cut Line= 4
      1526811.11      6838531.24      1527451.77      6839083.35
       1527551.3      6839045.85      1527634.08      6838938.69
#Sta/Elev= 30
  4141.1 1875.81  4200.3 1873.88  4219.2 1873.27  4240.5 1873.36  4418.2 1865.99
  4502.7 1864.71  4553.1 1861.83  4705.3 1857.27  4841.6 1854.01  4956.9 1850.49
  4964.5 1850.03  4985.4 1845.67  5009.1 1845.23  5009.4 1844.73  5013.5 1845.23
    5029 1845.84  5041.5 1848.28  5048.2 1847.01  5065.1 1848.98  5071.7  1851.3
    5077 1849.96  5086.5 1852.19  5102.1 1852.62  5108.4 1851.28  5115.8 1852.56
  5166.3 1852.81  5172.7 1851.91  5179.1 1853.27  5222.5 1852.25  5228.6 1853.25
#Mann= 9 ,-1 , 0
  4141.1     .16       0  4200.3    .035       0  4219.2     .07       0
  4705.3    .035       0  4841.6    .033       0  5009.1    .033       0
  5013.5    .033       0    5029    .035       0  5048.2     .07       0
Bank Sta=5009.1,5013.5
XS Rating Curve= 0 ,0
Exp/Cntr=0.3,0.1

Type RM Length L Ch R = 1 ,1159    ,268,268,268
BEGIN DESCRIPTION:
Mapping XS 5f8cba83
END DESCRIPTION:
XS GIS Cut Line= 4
      1526697.12      6838731.07      1526910.94      6839629.58
      1527069.02      6839623.72      1527159.09      6839491.71
#Sta/Elev= 30
  4076.4 1881.01  4104.1 1880.67  4120.7  1878.6    4136 1874.03  4310.4 1867.58
  4330.2 1864.11  4361.1 1851.87  4381.6 1847.59  4443.3  1846.9  4473.3    1850
  4494.7 1855.94  4525.7 1856.05  4604.9 1844.74  4658.7 1842.63  4736.5 1840.49
  4783.8 1841.54  4992.4 1837.95  4992.7 1837.45  4996.8 1837.95  5122.9 1842.87
  5158.2 1845.93  5195.4 1845.91  5201.4 1847.65  5231.3 1847.05  5261.1 1848.46
  5267.2 1847.17    5297    1849  5303.1 1847.34  5309.4 1848.51    5318 1851.68
#Mann= 8 ,-1 , 0
  4076.4     .07       0  4120.7    .035       0  4310.4    .033       0
  4658.7    .033       0  4992.4    .033       0  4996.8    .033       0
  5122.9    .033       0  5309.4     .07       0
Bank Sta=4992.4,4996.8
XS Rating Curve= 0 ,0
Exp/Cntr=0.3,0.1

Type RM Length L Ch R = 1 ,891     ,296,296,296
BEGIN DESCRIPTION:
Mapping XS 3aa9cad6
END DESCRIPTION:
XS GIS Cut Line= 4
        1526580.      6838912.98      1526648.85      6839409.82
      1526660.94      6839690.27      1527045.99      6840299.25
#Sta/Elev= 30
  4217.7 1870.31  4259.3 1869.65  4358.6  1867.2  4374.2 1865.73  4404.5 1855.76
    4433 1851.17  4444.9 1846.37    4455 1846.25  4475.2 1848.78  4485.3 1847.13
  4495.4 1847.23  4504.8 1849.16  4509.8 1846.81  4515.5 1848.23  4535.7 1847.71
  4586.6  1842.8  4606.4 1843.38  4656.3 1839.61  4664.4 1839.37  4857.6 1835.09
  4965.5 1834.04  4965.8 1833.54  4969.9 1834.04  5298.3 1836.93  5413.6 1838.96
  5475.9 1841.23  5553.4 1844.69  5574.7 1846.97  5601.8 1852.52  5720.5 1852.89
#Mann= 8 ,-1 , 0
  4217.7     .07       0  4259.3    .035       0  4358.6    .033       0
  4656.3    .035       0  4664.4    .033       0  4965.5    .033       0
  4969.9    .033       0  5475.9    .035       0
Bank Sta=4965.5,4969.9
XS Rating Curve= 0 ,0
Exp/Cntr=0.3,0.1

Type RM Length L Ch R = 1 ,595     ,241,241,241
BEGIN DESCRIPTION:
Mapping XS 4d836dc5
END DESCRIPTION:
XS GIS Cut Line= 4
        1526430.      6839113.04      1526414.86      6839827.08
       1526688.4      6840098.84        1526830.      6840513.01
#Sta/Elev= 30
  4285.8 1866.05  4533.3 1864.26  4640.8 1858.84  4680.8 1860.09  4710.9 1855.06
  4724.1 1847.71  4756.7  1838.3  4798.6 1832.49  4798.9 1831.99  4803.1 1832.49
  5071.4 1832.49  5142.2 1841.71  5184.6 1860.19  5217.9 1861.16  5262.4 1861.61
    5326 1866.34  5333.1 1863.83  5340.1 1865.58  5347.2 1863.57  5354.3 1866.14
  5375.5  1863.8  5390.3 1867.43  5393.1  1866.2  5416.3  1868.5  5421.6 1866.79
  5447.6 1868.53  5484.2 1867.05  5569.2 1869.86  5661.6 1869.54  5823.3 1871.99
#Mann= 9 ,-1 , 0
  4285.8    .035       0  4533.3    .033       0  4724.1    .033       0
  4798.6    .033       0  4803.1    .033       0  5217.9    .033       0
  5393.1     .07       0  5569.2    .035       0  5661.6     .07       0
Bank Sta=4798.6,4803.1
XS Rating Curve= 0 ,0
Exp/Cntr=0.3,0.1

Type RM Length L Ch R = 1 ,354     ,94,94,94
BEGIN DESCRIPTION:
Mapping XS 4598bc73
END DESCRIPTION:
XS GIS Cut Line= 6
        1526394.      6839358.29      1526197.49      6839754.58
      1526197.49      6839899.98      1526308.17        6840013.
      1526560.03      6840038.38      1526640.24      6840107.99
#Sta/Elev= 30
  4679.4 1863.91  4733.2 1863.62  4776.5 1860.57  4841.4 1859.26  4852.4 1857.75
  4884.6 1843.12  4894.8 1840.48  4924.2 1834.55  4945.8 1832.49  4946.1 1831.99
  4950.3 1832.49  4984.1 1832.49  5302.8 1832.51  5320.7 1833.86  5337.4 1835.23
  5344.5 1838.35  5365.6 1843.16  5379.8 1843.97  5428.1 1845.88    5455 1845.35
  5485.2 1842.05  5524.1 1839.82  5555.5 1841.13  5575.8 1844.68  5605.8 1856.61
  5615.8 1858.53    5661 1860.78  5714.4 1866.26  5734.1 1868.86  5787.4 1869.38
#Mann= 9 ,-1 , 0
  4679.4    .033       0  4945.8    .033       0  4950.3    .033       0
  4984.1    .033       0  5302.8    .033       0  5320.7    .033       0
  5575.8     .07       0    5661    .035       0  5714.4     .07       0
Bank Sta=4945.8,4950.3
XS Rating Curve= 0 ,0
Exp/Cntr=0.3,0.1

Type RM Length L Ch R = 1 ,260     ,205,205,205
BEGIN DESCRIPTION:
Mapping XS 3c7edf71
END DESCRIPTION:
XS GIS Cut Line= 6
      1526361.14      6839350.52      1526113.11      6839779.69
      1526126.16      6839955.94        1526353.      6840070.18
      1526545.57      6840078.34       1526630.2      6840128.79
#Sta/Elev= 30
  4677.7  1863.6  4738.1  1862.1  4753.4 1860.04  4768.8 1859.92  4780.7 1855.75
  4811.3  1856.9  4817.1 1855.27  4839.6 1855.69  4932.9 1849.47  5009.3 1849.71
  5012.2 1848.73  5012.5 1848.23  5016.7 1848.73  5036.2    1850  5112.5 1849.72
  5116.6  1849.6  5318.5  1849.7  5365.8 1850.89  5474.1 1850.32    5482 1849.87
  5675.8 1850.94    5736 1855.47  5766.4 1859.29  5772.6 1861.42  5777.6 1859.45
  5796.8 1865.03  5814.6 1867.59  5820.4 1866.59    5836 1868.91    5906 1869.64
#Mann= 9 ,-1 , 0
  4677.7    .033       0  5012.2    .033       0  5016.7    .033       0
  5112.5    .033       0  5116.6     .07       0  5318.5     .16       0
  5365.8     .07       0  5474.1     .16       0    5482     .07       0
Bank Sta=5012.2,5016.7
XS Rating Curve= 0 ,0
Exp/Cntr=0.3,0.1

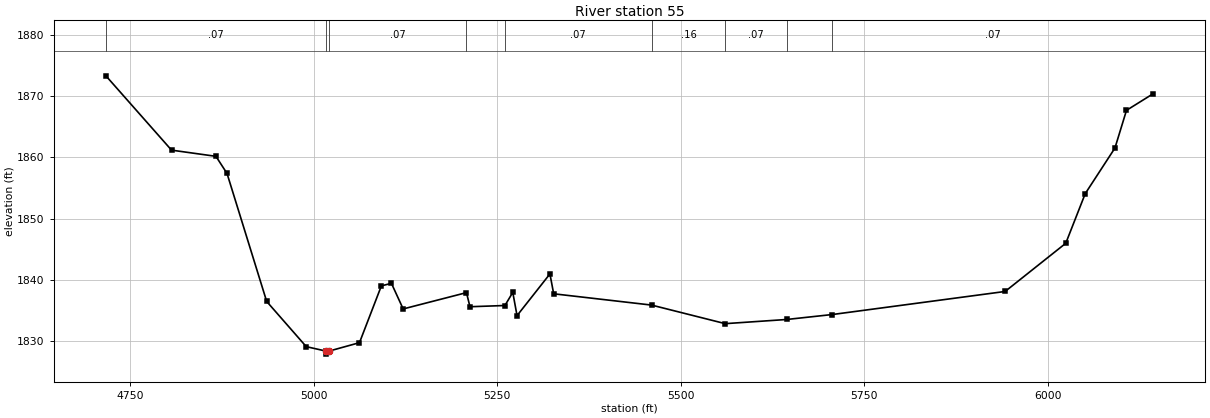
Type RM Length L Ch R = 1 ,55      ,0,0,0
BEGIN DESCRIPTION:
BULL WAGON CREEK TRIBUTARY 7 1.0
END DESCRIPTION:
XS GIS Cut Line= 6
      1526166.88      6839225.14      1526060.37      6839487.22
        1526130.        6839613.      1526060.89      6839875.98
      1526095.16      6840047.33      1526630.05      6840186.06
#Sta/Elev= 30
  4717.1 1873.32  4806.5  1861.2    4867 1860.19  4882.1 1857.39  4936.1 1836.52
    4990 1829.15  5016.7 1828.43    5017 1827.93  5021.2 1828.43  5062.5  1829.8
  5092.3 1839.06    5106 1839.48    5122  1835.3  5208.2 1837.96    5213 1835.66
  5260.6 1835.86  5271.3    1838  5277.1 1834.21  5321.9 1841.01    5327 1837.77
  5460.3 1835.93  5560.7  1832.9  5644.3 1833.58  5706.6 1834.39  5941.9 1838.15
  6024.5 1846.01    6051  1854.1  6091.5 1861.55  6107.2 1867.69  6143.4 1870.39
#Mann= 9 ,-1 , 0
  4717.1     .07       0  5016.7     .07       0  5021.2     .07       0
  5208.2     .16       0  5260.6     .07       0  5460.3     .16       0
  5560.7     .07       0  5644.3     .16       0  5706.6     .07       0
Bank Sta=5016.7,5021.2
XS Rating Curve= 0 ,0
Exp/Cntr=0.3,0.1

Chan Stop Cuts=-1
Use User Specified Reach Order=0
Composite Channel Slope=5