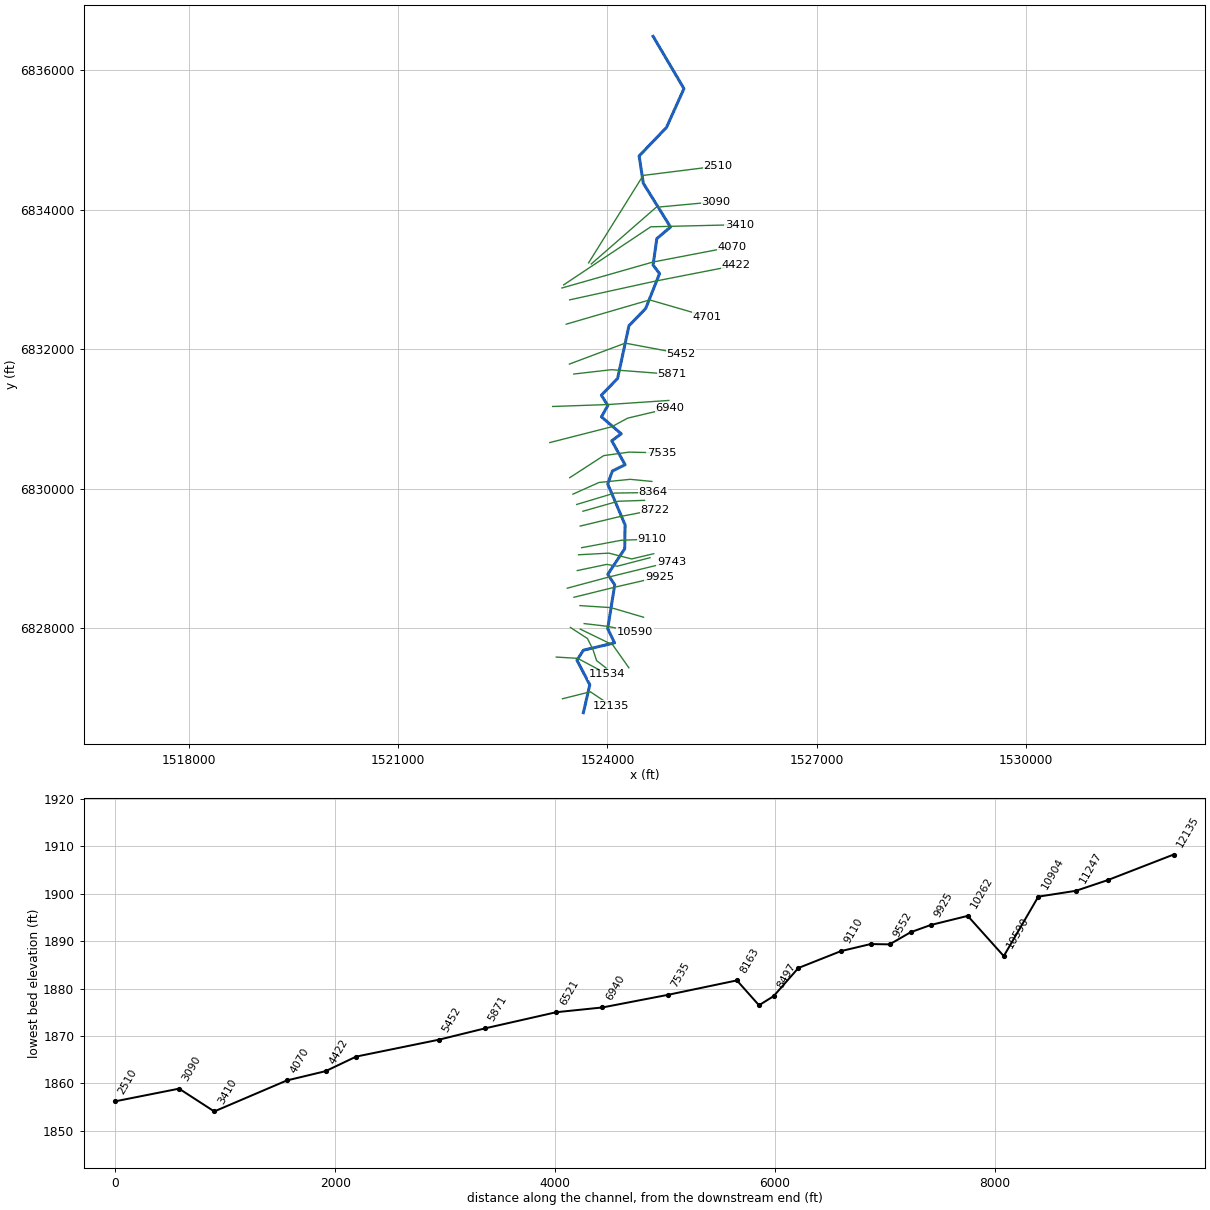
--- BULL WAGON CREEK TRIBUTARY 8.prj (project) ---

Proj Title=BULL WAGON CREEK TRIBUTARY 8 Base Level Engineering
Current Plan=p01
Default Exp/Contr=0.3,0.1
English Units
Geom File=g01
Flow File=f01
Plan File=p01
Y Axis Title=Elevation
X Axis Title(PF)=Main Channel Distance
X Axis Title(XS)=Station
BEGIN DESCRIPTION:
BULL WAGON CREEK TRIBUTARY 8
END DESCRIPTION:
DSS Export Rating Curves= 0
DSS Export Rating Curve Sorted= 0
DSS Export Volume Flow Curves= 0
DXF OffsetX= 0
DXF OffsetY= 0
DXF ScaleX= 1
DXF ScaleY= 10

--- BULL WAGON CREEK TRIBUTARY 8.p01 (plan) ---

Plan Title=Multiple Run
Short Identifier=Multiple
Geom File=g01
Flow File=f01
Subcritical Flow
K Sum by GR= 0
Std Step Tol= 0.01
Critical Tol= 0.01
Num of Std Step Trials= 20
Max Error Tol= 0.3
Flow Tol Ratio= 0.001
Split Flow NTrial= 30
Split Flow Tol= 0.02
Split Flow Ratio= 0.02
Log Output Level= 0
Friction Slope Method= 1
Unsteady Friction Slope Method= 2
Unsteady Bridges Friction Slope Method= 1
Parabolic Critical Depth
Global Vel Dist=  1 , 1 , 1
Global Log Level= 0
CheckData=True
Encroach Param= -1, 0, 0, 0
BEGIN DESCRIPTION:
Multiple Run
END DESCRIPTION:

--- BULL WAGON CREEK TRIBUTARY 8.f01 (steady flow) ---

Flow Title=Multiple
Program Version=4.10
Number of Profiles= 7
Profile Names=10-year,25-year,50-year,1pct_min,100-year,1pct_plu,500-year
River Rch & RM=BULL WAGON CREEK,Reach-1         ,12135
     192     263     320     195     388     775     579
River Rch & RM=BULL WAGON CREEK,Reach-1         ,9925
     275     383     473     291     580    1158     885
River Rch & RM=BULL WAGON CREEK,Reach-1         ,5871
     359     508     633     392     782    1561    1213
Boundary for River Rch & Prof#=BULL WAGON CREEK,Reach-1         , 1
Up Type= 0
Dn Type= 3
Dn Slope=0.008
Boundary for River Rch & Prof#=BULL WAGON CREEK,Reach-1         , 2
Up Type= 0
Dn Type= 3
Dn Slope=0.008
Boundary for River Rch & Prof#=BULL WAGON CREEK,Reach-1         , 3
Up Type= 0
Dn Type= 3
Dn Slope=0.008
Boundary for River Rch & Prof#=BULL WAGON CREEK,Reach-1         , 4
Up Type= 0
Dn Type= 3
Dn Slope=0.008
Boundary for River Rch & Prof#=BULL WAGON CREEK,Reach-1         , 5
Up Type= 0
Dn Type= 3
Dn Slope=0.008
Boundary for River Rch & Prof#=BULL WAGON CREEK,Reach-1         , 6
Up Type= 0
Dn Type= 3
Dn Slope=0.008
Boundary for River Rch & Prof#=BULL WAGON CREEK,Reach-1         , 7
Up Type= 0
Dn Type= 3
Dn Slope=0.008
DSS Import GetInterval= 0
DSS Import GetPeak= 0
DSS Import FillOption= 0

--- BULL WAGON CREEK TRIBUTARY 8.g01 (geometry) ---

Geom Title=Existing Conditions
Program Version=4.10

River Reach=BULL WAGON CREEK,Reach-1
Reach XY= 30
        1523655.        6826788.      1523747.25      6827187.91
      1523562.83      6827541.23      1523656.25      6827684.55
      1524101.91      6827789.63      1524004.07      6827993.38
      1524105.04      6828622.66      1524005.02      6828772.59
      1524247.67       6829137.9      1524253.03      6829482.11
      1524004.33      6830067.92      1524071.45      6830255.13
      1524253.52      6830343.88      1524062.01      6830688.21
      1524198.02       6830787.8      1523913.96      6831031.33
      1524005.87      6831193.04       1523912.6      6831341.34
       1524145.7      6831581.33      1524308.54      6832336.53
      1524549.17       6832585.7      1524747.39      6833084.67
       1524654.8      6833208.05      1524708.15      6833586.36
      1524904.82      6833753.09      1524514.31      6834381.34
      1524454.95      6834772.66      1524847.18      6835181.81
      1525097.45        6835738.        1524655.        6836488.

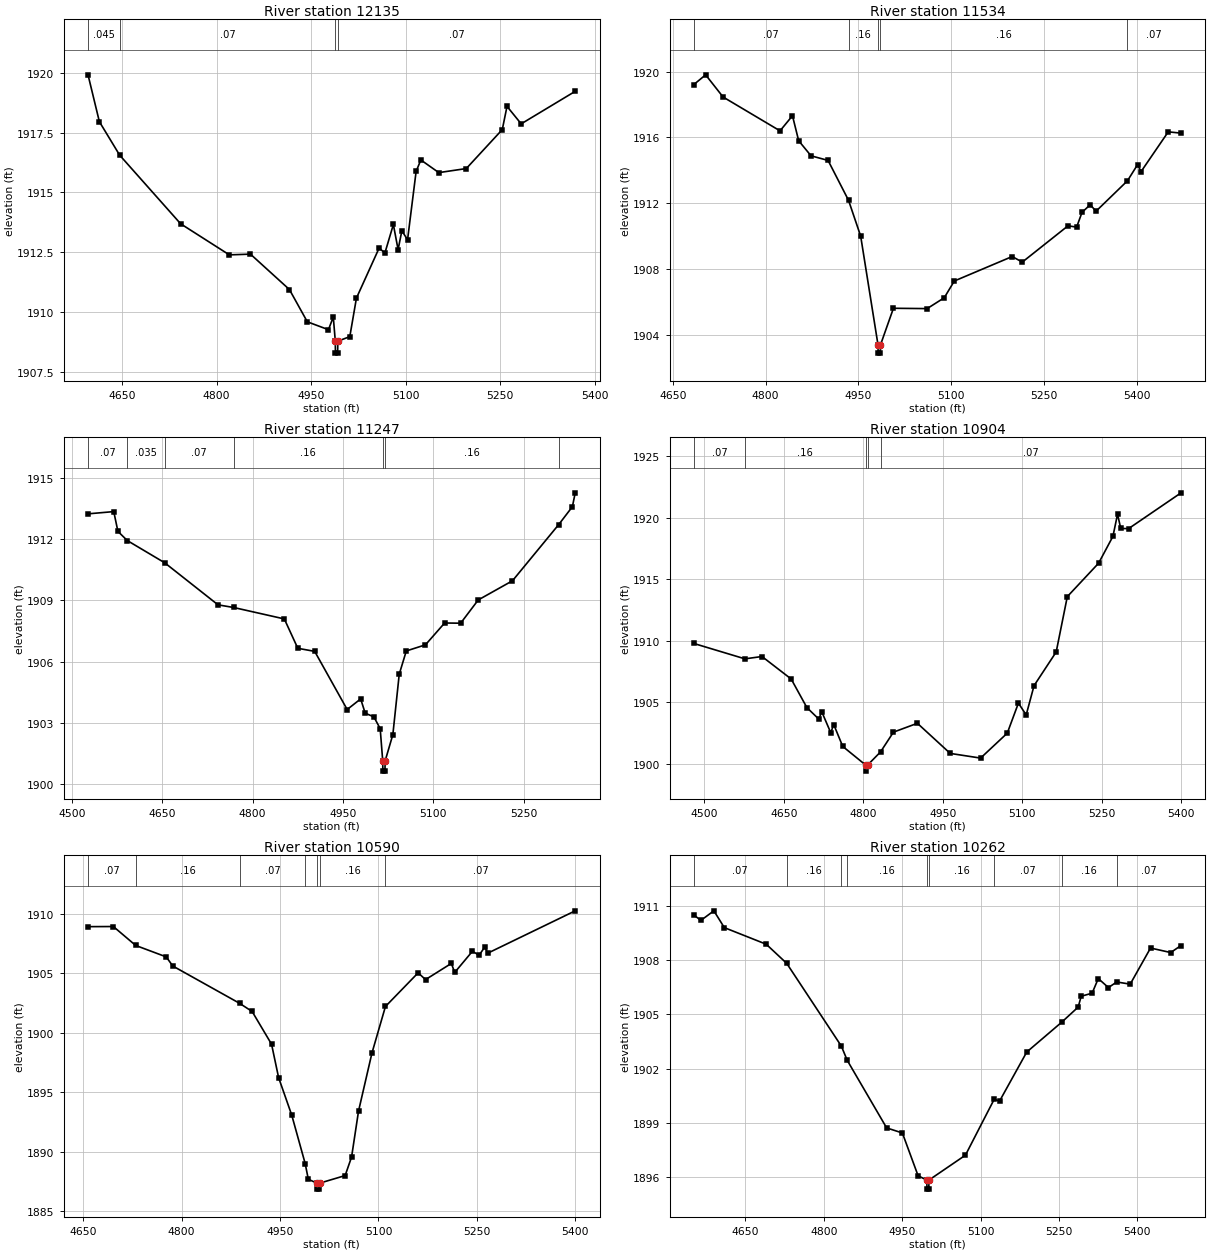
Type RM Length L Ch R = 1 ,12135   ,601,601,601
BEGIN DESCRIPTION:
BULL WAGON CREEK TRIBUTARY 8 20.0
END DESCRIPTION:
XS GIS Cut Line= 3
      1523355.01        6826988.        1523755.        6827088.
      1524055.03      6826887.98
#Sta/Elev= 30
    4596 1919.92    4614 1917.96  4646.2 1916.56  4742.9 1913.69  4820.2 1912.39
  4853.7 1912.42  4915.5 1910.94  4943.9 1909.59  4977.4 1909.26  4985.1 1909.79
  4988.3 1908.78  4988.5 1908.28    4992 1908.28  4992.3 1908.78  5011.3 1908.97
  5021.8 1910.58  5057.9 1912.68  5066.9 1912.46  5080.4 1913.66  5087.9 1912.61
  5093.9  1913.4  5102.9 1913.02  5116.5 1915.88    5124 1916.36  5152.5 1915.83
  5196.1    1916  5253.2 1917.63  5260.7  1918.6  5283.2 1917.87  5368.9 1919.23
#Mann= 4 ,-1 , 0
    4596    .045       0  4646.2     .07       0  4988.3     .07       0
  4992.3     .07       0
Bank Sta=4988.3,4992.3
XS Rating Curve= 0 ,0
Exp/Cntr=0.3,0.1

Type RM Length L Ch R = 1 ,11534   ,287,287,287
BEGIN DESCRIPTION:
Mapping XS f62ef874
END DESCRIPTION:
XS GIS Cut Line= 3
        1523266.      6827585.99      1523573.34      6827567.75
      1523996.11       6827342.1
#Sta/Elev= 30
  4684.1 1919.22  4703.1 1919.81  4731.3 1918.46  4823.3  1916.4  4843.4 1917.32
  4853.4  1915.8  4873.4 1914.88  4900.9  1914.6    4934 1912.17  4953.6 1909.99
  4981.6 1903.37  4981.9 1902.87  4985.4 1902.87  4985.6 1903.37  5006.5  1905.6
    5061 1905.58  5088.6 1906.24  5104.9 1907.26  5198.4 1908.75  5214.7 1908.41
  5288.6 1910.62  5302.5 1910.54  5311.2 1911.44  5324.4  1911.9  5333.9 1911.51
  5384.6 1913.36  5400.9 1914.34  5406.6 1913.92  5450.5 1916.34  5471.2 1916.26
#Mann= 5 ,-1 , 0
  4684.1     .07       0    4934     .16       0  4981.6     .07       0
  4985.6     .16       0  5384.6     .07       0
Bank Sta=4981.6,4985.6
XS Rating Curve= 0 ,0
Exp/Cntr=0.3,0.1

Type RM Length L Ch R = 1 ,11247   ,343,343,343
BEGIN DESCRIPTION:
Mapping XS 7c5d1598
END DESCRIPTION:
XS GIS Cut Line= 5
      1523469.17      6828010.46      1523713.96      6827851.61
      1523792.09      6827695.36      1523844.17       6827536.5
       1523981.1      6827427.99
#Sta/Elev= 30
    4527 1913.24  4569.7 1913.35  4576.6 1912.38  4592.2 1911.93  4654.3 1910.84
  4742.7 1908.78  4768.6 1908.65  4852.7 1908.09  4875.1 1906.65  4903.1  1906.5
    4957 1903.65  4979.4 1904.17  4986.9 1903.47  5001.3 1903.29  5011.8 1902.71
    5016 1901.13  5016.2 1900.63  5019.7 1900.63    5020 1901.13  5032.8 1902.42
  5043.4 1905.38  5055.1 1906.52  5086.9 1906.82  5118.7 1907.89  5145.3 1907.88
  5174.5 1909.02  5231.3 1909.96  5307.9 1912.71  5330.7 1913.59  5335.4 1914.27
#Mann= 7 ,-1 , 0
    4527     .07       0  4592.2    .035       0  4654.3     .07       0
  4768.6     .16       0    5016     .07       0    5020     .16       0
  5307.9     .07       0
Bank Sta=5016,5020
XS Rating Curve= 0 ,0
Exp/Cntr=0.3,0.1

Type RM Length L Ch R = 1 ,10904   ,314,314,314
BEGIN DESCRIPTION:
Mapping XS c332e9e5
END DESCRIPTION:
XS GIS Cut Line= 3
       1523609.8      6827987.02      1524075.94      6827760.46
      1524307.48      6827432.67
#Sta/Elev= 30
    4480 1909.77  4576.4 1908.52  4608.6 1908.71  4663.7 1906.88  4693.3 1904.56
  4715.8 1903.62  4721.4 1904.22  4738.4 1902.51    4744 1903.18    4761  1901.4
  4804.1 1899.89  4804.3 1899.39  4808.1 1899.89  4832.3 1900.95  4856.7 1902.56
  4901.9 1903.28  4963.9 1900.83  5021.2 1900.45  5071.6 1902.48  5092.6 1904.92
  5107.3 1903.96  5122.1 1906.34  5163.9 1909.08  5184.9 1913.58    5244  1916.3
    5271 1918.48  5279.7 1920.28  5285.8 1919.12  5300.6 1919.11  5399.6 1922.02
#Mann= 5 ,-1 , 0
    4480     .07       0  4576.4     .16       0  4804.1     .07       0
  4808.1     .16       0  4832.3     .07       0
Bank Sta=4804.1,4808.1
XS Rating Curve= 0 ,0
Exp/Cntr=0.3,0.1

Type RM Length L Ch R = 1 ,10590   ,328,328,328
BEGIN DESCRIPTION:
Mapping XS c572d1e9
END DESCRIPTION:
XS GIS Cut Line= 3
      1523666.67      6828066.06      1524000.03        6828027.
      1524398.49      6827946.26
#Sta/Elev= 30
  4657.5  1908.9  4696.1 1908.91  4730.1 1907.32  4776.6 1906.36  4786.7 1905.59
  4888.3 1902.46  4907.5 1901.77  4937.1 1899.02  4947.8 1896.22  4967.9 1893.05
  4988.3 1888.99  4993.1 1887.67  5006.3 1887.34  5006.5 1886.84    5010 1886.84
  5010.3 1887.34  5049.2 1887.98    5059 1889.54  5069.6  1893.4    5090 1898.27
  5110.6 1902.19  5160.4 1905.02  5171.7 1904.45    5211 1905.81  5216.1 1905.05
  5243.1 1906.83  5253.3  1906.5  5261.7 1907.17  5266.8 1906.68  5399.7 1910.23
#Mann= 7 ,-1 , 0
  4657.5     .07       0  4730.1     .16       0  4888.3     .07       0
  4988.3     .16       0  5006.3     .07       0  5010.3     .16       0
  5110.6     .07       0
Bank Sta=5006.3,5010.3
XS Rating Curve= 0 ,0
Exp/Cntr=0.3,0.1

Type RM Length L Ch R = 1 ,10262   ,337,337,337
BEGIN DESCRIPTION:
Mapping XS 1edd463d
END DESCRIPTION:
XS GIS Cut Line= 3
      1523606.82      6828323.87      1524049.51      6828295.23
       1524518.3       6828157.2
#Sta/Elev= 30
  4551.4 1910.51  4564.8 1910.21  4589.7 1910.74  4609.7 1909.81  4689.9 1908.89
  4729.1 1907.83  4833.6 1903.25  4844.9 1902.46  4920.3 1898.72  4950.4 1898.44
  4980.5 1896.07  4997.2 1895.83  4997.5 1895.33    5001 1895.33  5001.2 1895.83
  5071.1 1897.21  5126.2 1900.31  5136.3  1900.2  5188.4 1902.92  5255.2 1904.57
  5286.8 1905.41  5292.6 1906.01  5313.5 1906.18  5325.3 1906.99  5344.7 1906.49
  5360.6  1906.8  5386.4 1906.68  5425.3 1908.68  5463.9 1908.43  5483.7 1908.82
#Mann= 9 ,-1 , 0
  4551.4     .07       0  4729.1     .16       0  4833.6     .07       0
  4844.9     .16       0  4997.2     .07       0  5001.2     .16       0
  5126.2     .07       0  5255.2     .16       0  5360.6     .07       0
Bank Sta=4997.2,5001.2
XS Rating Curve= 0 ,0
Exp/Cntr=0.3,0.1

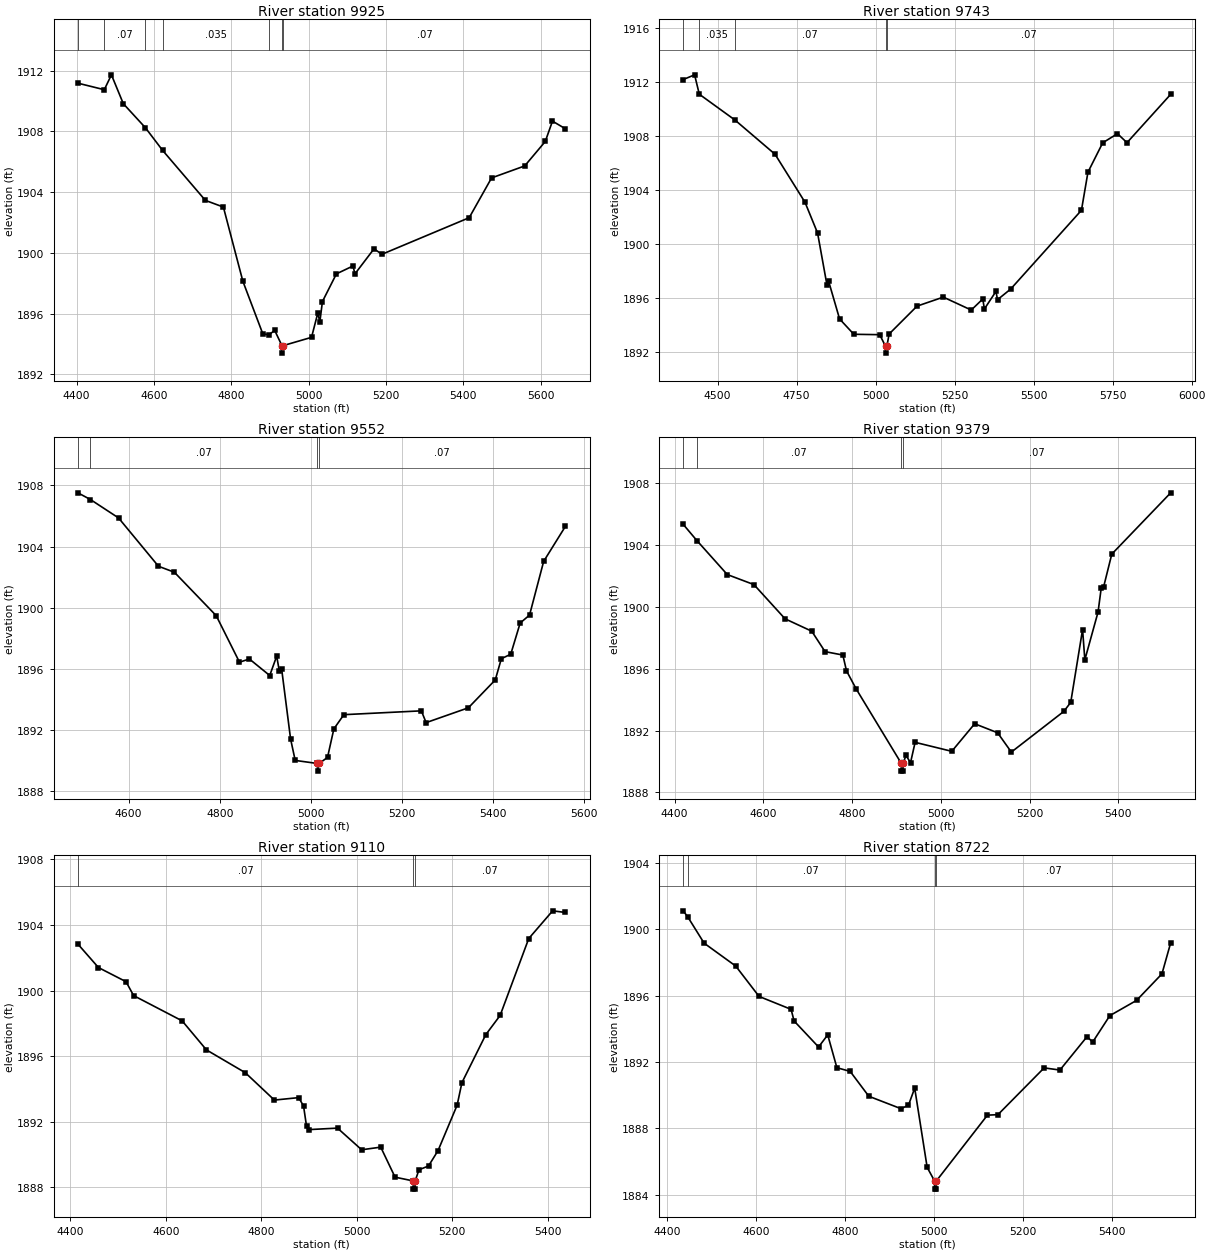
Type RM Length L Ch R = 1 ,9925    ,182,182,182
BEGIN DESCRIPTION:
BULL WAGON CREEK TRIBUTARY 8 15.0
END DESCRIPTION:
XS GIS Cut Line= 3
      1523520.86      6828443.67        1524105.        6828588.
      1524747.42      6828735.33
#Sta/Elev= 30
  4403.3 1911.18  4471.5 1910.75    4490 1911.73  4520.7 1909.83  4577.7 1908.25
  4622.5 1906.75    4733 1903.46  4779.6 1903.02  4829.9 1898.14  4881.4 1894.68
  4897.2  1894.6  4912.3  1894.9  4930.9  1893.9  4931.1  1893.4  4934.9  1893.9
  5007.6 1894.44  5023.9 1896.05    5029 1895.44  5035.8  1896.8  5071.9 1898.62
  5114.8 1899.14  5119.9 1898.62  5169.2 1900.27  5189.7 1899.91  5415.4 1902.32
  5473.3 1904.94    5559 1905.73  5612.2 1907.34  5630.8 1908.68  5664.1 1908.18
#Mann= 7 ,-1 , 0
  4403.3    .035       0  4471.5     .07       0  4577.7     .16       0
  4622.5    .035       0  4897.2     .07       0  4930.9     .07       0
  4934.9     .07       0
Bank Sta=4930.9,4934.9
XS Rating Curve= 0 ,0
Exp/Cntr=0.3,0.1

Type RM Length L Ch R = 1 ,9743    ,191,191,191
BEGIN DESCRIPTION:
Mapping XS c1871623
END DESCRIPTION:
XS GIS Cut Line= 3
       1523424.5      6828573.87      1524005.24      6828730.12
      1524919.31      6828954.08
#Sta/Elev= 30
  4391.1  1912.2    4427 1912.55  4441.9 1911.11  4554.9 1909.19  4681.6 1906.65
  4776.3 1903.09  4816.2  1900.8  4845.8 1896.95    4851 1897.23  4885.8 1894.42
  4930.9 1893.28  5012.8 1893.25  5031.4 1892.38  5031.7 1891.88  5035.4 1892.38
  5042.6  1893.3  5130.9 1895.37  5214.1 1896.04  5302.5 1895.08    5339  1895.9
  5344.1 1895.16  5380.6 1896.46  5385.7 1895.85  5427.3 1896.64  5651.2 1902.49
  5671.8 1905.32  5718.5  1907.5  5765.3 1908.18  5795.3 1907.51  5933.6  1911.1
#Mann= 5 ,-1 , 0
  4391.1     .07       0  4441.9    .035       0  4554.9     .07       0
  5031.4     .07       0  5035.4     .07       0
Bank Sta=5031.4,5035.4
XS Rating Curve= 0 ,0
Exp/Cntr=0.3,0.1

Type RM Length L Ch R = 1 ,9552    ,173,173,173
BEGIN DESCRIPTION:
Mapping XS 8930658e
END DESCRIPTION:
XS GIS Cut Line= 4
      1523567.75      6828826.48      1523989.61      6828915.02
      1524140.66      6828888.98      1524611.03      6829011.12
#Sta/Elev= 30
  4488.6 1907.51  4516.2 1907.07  4577.8 1905.87  4665.5 1902.71  4700.4 1902.32
  4792.3 1899.48  4843.4 1896.44  4865.1 1896.65  4909.8 1895.57  4925.1 1896.84
  4930.9 1895.85  4935.9 1896.01  4955.6 1891.42  4965.7 1890.02  5014.5 1889.82
  5014.7 1889.32  5018.5 1889.82  5036.7 1890.22  5050.6 1892.08  5072.6 1893.01
  5242.7 1893.26  5253.2 1892.49    5346 1893.46    5405 1895.28  5418.4 1896.67
    5439 1896.96  5459.7    1899  5480.3 1899.52  5511.3 1903.03  5558.9 1905.31
#Mann= 4 ,-1 , 0
  4488.6    .045       0  4516.2     .07       0  5014.5     .07       0
  5018.5     .07       0
Bank Sta=5014.5,5018.5
XS Rating Curve= 0 ,0
Exp/Cntr=0.3,0.1

Type RM Length L Ch R = 1 ,9379    ,269,269,269
BEGIN DESCRIPTION:
Mapping XS 794b1ef5
END DESCRIPTION:
XS GIS Cut Line= 4
      1523585.92      6829053.04      1524020.86      6829076.48
      1524346.38      6828993.14      1524664.14      6829068.68
#Sta/Elev= 30
  4419.7 1905.32  4450.3 1904.28  4518.9 1902.08    4579 1901.43  4649.1 1899.22
  4709.2 1898.42  4739.2  1897.1  4779.3 1896.88  4787.5 1895.86  4809.3 1894.69
    4911 1889.88  4911.2 1889.38  4914.7 1889.38    4915 1889.88  4921.5 1890.39
  4931.8 1889.93  4942.1 1891.24  5024.7 1890.66  5076.3 1892.44  5127.9 1891.86
  5158.9 1890.61  5277.2 1893.24  5292.7 1893.82  5319.4 1898.53  5324.5 1896.57
  5354.3 1899.66  5361.5 1901.23  5366.7 1901.27  5385.2  1903.4  5517.9 1907.36
#Mann= 4 ,-1 , 0
  4419.7    .045       0  4450.3     .07       0    4911     .07       0
    4915     .07       0
Bank Sta=4911,4915
XS Rating Curve= 0 ,0
Exp/Cntr=0.3,0.1

Type RM Length L Ch R = 1 ,9110    ,388,388,388
BEGIN DESCRIPTION:
Mapping XS c61d861f
END DESCRIPTION:
XS GIS Cut Line= 3
      1523630.22       6829154.6      1524200.55      6829261.37
      1524641.63      6829276.94
#Sta/Elev= 30
  4415.7 1902.84  4458.8 1901.41  4516.5 1900.55  4532.5  1899.7  4634.2 1898.16
  4685.1 1896.39  4766.5    1895  4827.5 1893.33  4878.4 1893.48  4888.6 1892.97
  4894.9 1891.73    4900 1891.53  4959.8 1891.62  5010.4  1890.3  5050.4 1890.46
  5080.4 1888.63  5118.4  1888.4  5118.6  1887.9  5122.3  1887.9  5122.6  1888.4
  5130.5 1889.08  5150.5 1889.31  5170.5 1890.25  5210.5 1893.02  5220.5 1894.39
  5270.6 1897.32  5300.6 1898.49  5360.6 1903.18  5410.7 1904.87  5437.3 1904.77
#Mann= 3 ,-1 , 0
  4415.7     .07       0  5118.4     .07       0  5122.6     .07       0
Bank Sta=5118.4,5122.6
XS Rating Curve= 0 ,0
Exp/Cntr=0.3,0.1

Type RM Length L Ch R = 1 ,8722    ,225,225,225
BEGIN DESCRIPTION:
Mapping XS 42450cc8
END DESCRIPTION:
XS GIS Cut Line= 3
      1523609.37      6829464.49      1524160.62      6829596.88
      1524679.28       6829696.7
#Sta/Elev= 30
  4437.2 1901.11  4447.9 1900.72  4484.1 1899.16  4555.1 1897.78  4607.5 1895.95
  4679.5 1895.17  4686.2 1894.47  4741.2  1892.9  4761.8 1893.63  4782.4 1891.65
  4812.2 1891.43  4854.1 1889.93  4926.4 1889.18  4943.2 1889.39  4957.2 1890.42
  4985.2 1885.64  5001.7 1884.83    5002 1884.33  5005.7 1884.33    5006 1884.83
  5120.6 1888.79  5144.2 1888.82    5248 1891.64  5283.5 1891.51  5344.6 1893.53
  5356.9 1893.19  5395.6 1894.79  5455.7 1895.71  5512.7 1897.31  5532.3 1899.18
#Mann= 4 ,-1 , 0
  4437.2    .045       0  4447.9     .07       0  5001.7     .07       0
    5006     .07       0
Bank Sta=5001.7,5006
XS Rating Curve= 0 ,0
Exp/Cntr=0.3,0.1

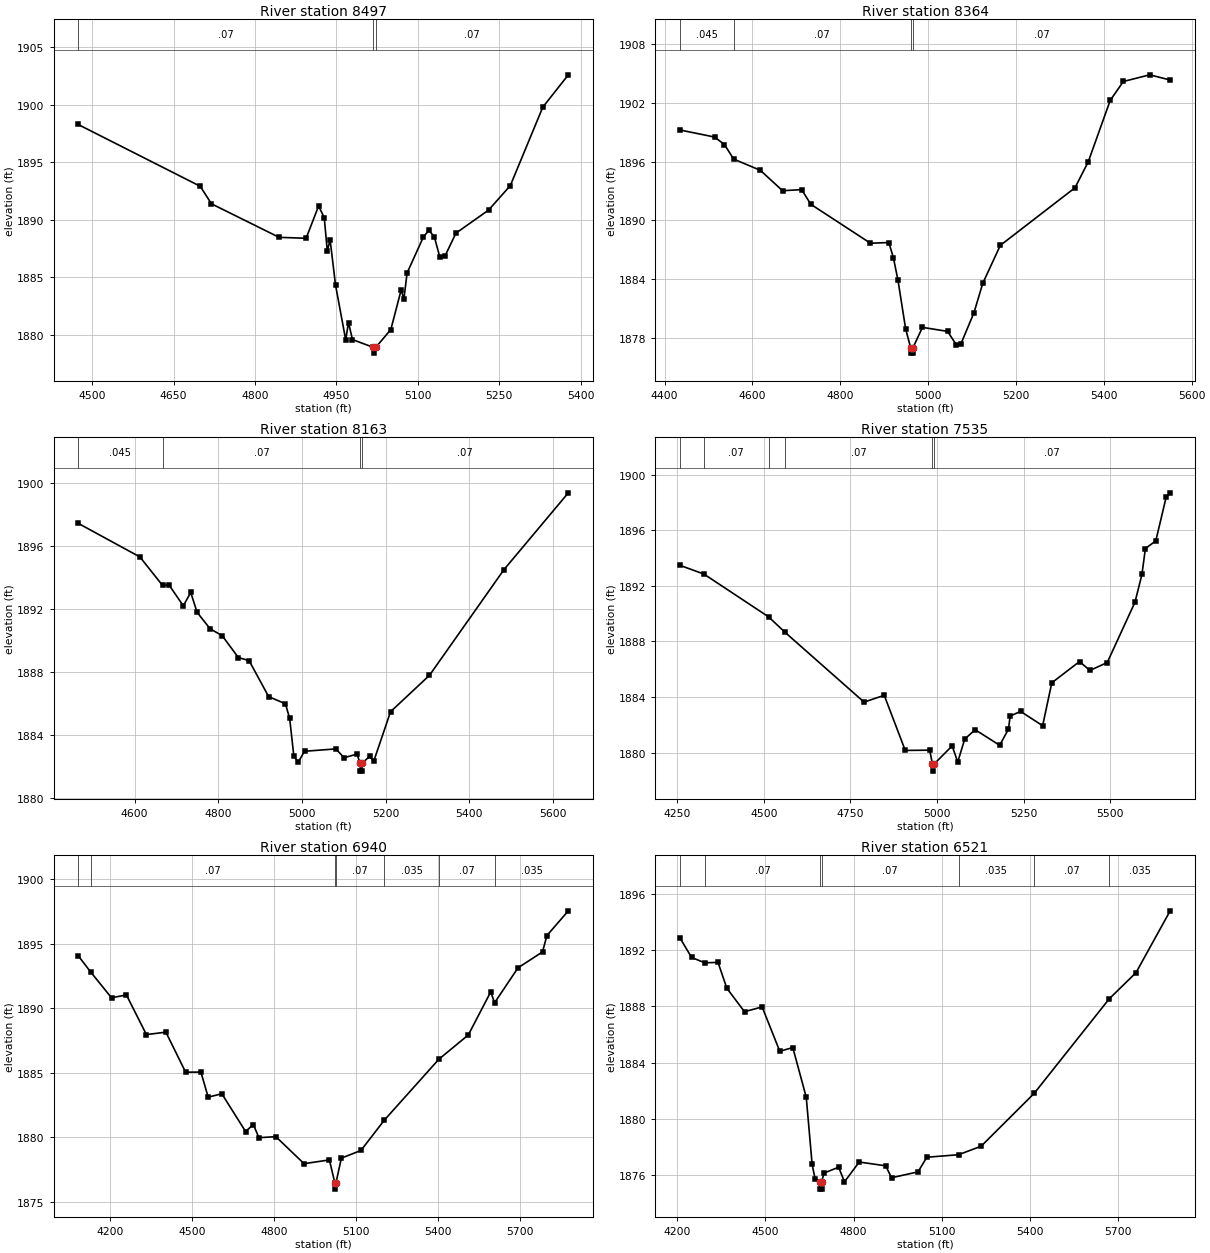
Type RM Length L Ch R = 1 ,8497    ,133,133,133
BEGIN DESCRIPTION:
Mapping XS b0fbeb05
END DESCRIPTION:
XS GIS Cut Line= 3
      1523648.48      6829677.18      1524151.94       6829820.4
      1524531.99      6829833.36
#Sta/Elev= 30
  4473.8  1898.3  4698.9 1892.92  4719.7 1891.39  4844.5 1888.47  4894.2 1888.39
  4917.2  1891.2  4927.6 1890.18  4933.2 1887.29  4938.4 1888.25  4948.4 1884.32
  4967.1 1879.55  4972.3 1881.05  4979.6 1879.57  5018.1 1878.89  5018.4 1878.39
  5022.5 1878.89  5050.3 1880.44  5069.4  1883.9  5074.4  1883.1  5080.3 1885.37
  5110.4 1888.51  5120.4 1889.07  5130.4 1888.54  5140.4 1886.79  5150.4 1886.87
  5170.4 1888.84  5230.4 1890.84  5270.5 1892.97  5330.5 1899.81  5377.5 1902.62
#Mann= 3 ,-1 , 0
  4473.8     .07       0  5018.1     .07       0  5022.5     .07       0
Bank Sta=5018.1,5022.5
XS Rating Curve= 0 ,0
Exp/Cntr=0.3,0.1

Type RM Length L Ch R = 1 ,8364    ,201,201,201
BEGIN DESCRIPTION:
Mapping XS 8ce159bb
END DESCRIPTION:
XS GIS Cut Line= 3
      1523559.48      6829774.83      1524102.03      6829937.59
      1524651.62      6829946.24
#Sta/Elev= 30
    4435 1899.24  4513.8 1898.52  4536.5 1897.75  4557.3 1896.27  4618.2 1895.12
  4668.7 1893.04  4712.2 1893.15  4733.1 1891.65  4868.8 1887.68  4910.6 1887.75
    4921 1886.21  4931.5 1883.89  4948.9 1878.93  4960.6 1876.96  4960.9 1876.46
  4964.7 1876.46    4965 1876.96  4987.2 1879.09  5044.4 1878.68  5064.4  1877.3
  5074.4 1877.37  5104.4 1880.58  5124.4 1883.58  5164.4 1887.46  5334.4 1893.34
  5364.5 1895.98  5414.5 1902.25  5444.5 1904.19  5504.5 1904.87  5551.1 1904.34
#Mann= 4 ,-1 , 0
    4435    .045       0  4557.3     .07       0  4960.6     .07       0
    4965     .07       0
Bank Sta=4960.6,4965
XS Rating Curve= 0 ,0
Exp/Cntr=0.3,0.1

Type RM Length L Ch R = 1 ,8163    ,628,628,628
BEGIN DESCRIPTION:
Mapping XS b7368b28
END DESCRIPTION:
XS GIS Cut Line= 4
      1523505.23      6829922.39       1523878.5       6830089.5
      1524325.55      6830135.07      1524638.04      6830104.69
#Sta/Elev= 30
  4464.6 1897.44  4612.6  1895.3  4666.7 1893.49  4682.2 1893.52  4716.3  1892.2
    4734 1893.05  4749.2 1891.79  4780.4 1890.74  4809.1 1890.31  4847.8 1888.92
  4873.6 1888.72  4920.3 1886.44  4960.5 1885.98  4970.6 1885.05  4980.6 1882.66
  4990.7 1882.27  5006.2 1882.97  5081.1 1883.12  5100.8 1882.56  5131.4 1882.79
  5139.2 1882.21  5139.5 1881.71  5143.3 1881.71  5143.6 1882.21  5161.6 1882.64
  5171.6 1882.34  5211.8 1885.48  5304.9 1887.79  5483.1  1894.5  5636.9 1899.37
#Mann= 4 ,-1 , 0
  4464.6    .045       0  4666.7     .07       0  5139.2     .07       0
  5143.6     .07       0
Bank Sta=5139.2,5143.6
XS Rating Curve= 0 ,0
Exp/Cntr=0.3,0.1

Type RM Length L Ch R = 1 ,7535    ,595,595,595
BEGIN DESCRIPTION:
Mapping XS 876ebc29
END DESCRIPTION:
XS GIS Cut Line= 4
      1523459.25      6830158.52      1523947.51      6830475.35
      1524309.93      6830525.26      1524776.52      6830514.41
#Sta/Elev= 30
  4258.1 1893.48  4327.4 1892.85    4514 1889.77  4560.3 1888.68  4789.5 1883.63
  4847.7 1884.12  4908.3 1880.15  4978.9 1880.17  4986.8 1879.16  4987.1 1878.66
  4991.2 1879.16  5043.7 1880.48  5059.7 1879.31  5079.9 1880.97  5110.2 1881.64
  5180.8 1880.52    5206 1881.68  5211.1 1882.63  5241.1 1882.96  5304.7 1881.93
  5331.1 1885.02  5411.1 1886.55  5441.1 1885.91  5491.1 1886.48  5571.2 1890.83
  5591.2 1892.82  5601.2 1894.69  5631.2 1895.24  5661.2  1898.4  5672.7  1898.7
#Mann= 6 ,-1 , 0
  4258.1    .045       0  4327.4     .07       0    4514    .045       0
  4560.3     .07       0  4986.8     .07       0  4991.2     .07       0
Bank Sta=4986.8,4991.2
XS Rating Curve= 0 ,0
Exp/Cntr=0.3,0.1

Type RM Length L Ch R = 1 ,6940    ,419,419,419
BEGIN DESCRIPTION:
Mapping XS ff31fa29
END DESCRIPTION:
XS GIS Cut Line= 4
      1523173.61      6830662.19      1524059.06      6830887.89
       1524291.7      6831012.89      1524891.23      6831154.98
#Sta/Elev= 30
  4081.6 1894.08  4128.4 1892.79    4204 1890.81  4258.5 1891.03  4331.8 1887.96
    4403 1888.15  4475.2 1885.05  4531.1 1885.06  4557.7 1883.12  4607.7 1883.38
  4694.6 1880.46  4722.9    1881  4743.5 1879.98  4805.4 1880.06  4908.6 1877.97
  5001.3 1878.26    5021  1876.5  5021.3    1876  5025.5  1876.5  5045.1  1878.4
  5116.6 1878.99  5202.3 1881.34  5402.2 1886.06  5509.5 1887.93  5591.7 1891.27
  5605.6 1890.42  5691.5 1893.13  5781.1 1894.36  5797.3 1895.63  5875.6 1897.54
#Mann= 7 ,-1 , 0
  4081.6    .045       0  4128.4     .07       0    5021     .07       0
  5025.5     .07       0  5202.3    .035       0  5402.2     .07       0
  5605.6    .035       0
Bank Sta=5021,5025.5
XS Rating Curve= 0 ,0
Exp/Cntr=0.3,0.1

Type RM Length L Ch R = 1 ,6521    ,650,650,650
BEGIN DESCRIPTION:
Mapping XS b4f4477d
END DESCRIPTION:
XS GIS Cut Line= 3
      1523215.35      6831179.56      1524006.97      6831207.34
      1524880.98       6831266.3
#Sta/Elev= 30
  4209.2 1892.89  4248.9 1891.49  4293.9 1891.11  4338.9 1891.14  4368.9  1889.3
    4429 1887.63    4489 1887.97  4549.1 1884.81  4593.3 1885.08  4639.1 1881.54
  4659.1 1876.76  4669.1 1875.74  4686.9  1875.5  4687.2    1875  4691.1    1875
  4691.4  1875.5  4699.2 1876.14  4749.2 1876.56  4769.2 1875.52  4819.2 1876.93
  4909.3 1876.66  4929.3 1875.81  5019.4 1876.23  5049.4 1877.27  5157.5 1877.45
  5234.4 1878.06  5414.3 1881.81  5669.7 1888.54  5761.1 1890.41  5877.3 1894.81
#Mann= 7 ,-1 , 0
  4209.2    .045       0  4293.9     .07       0  4686.9     .07       0
  4691.4     .07       0  5157.5    .035       0  5414.3     .07       0
  5669.7    .035       0
Bank Sta=4686.9,4691.4
XS Rating Curve= 0 ,0
Exp/Cntr=0.3,0.1

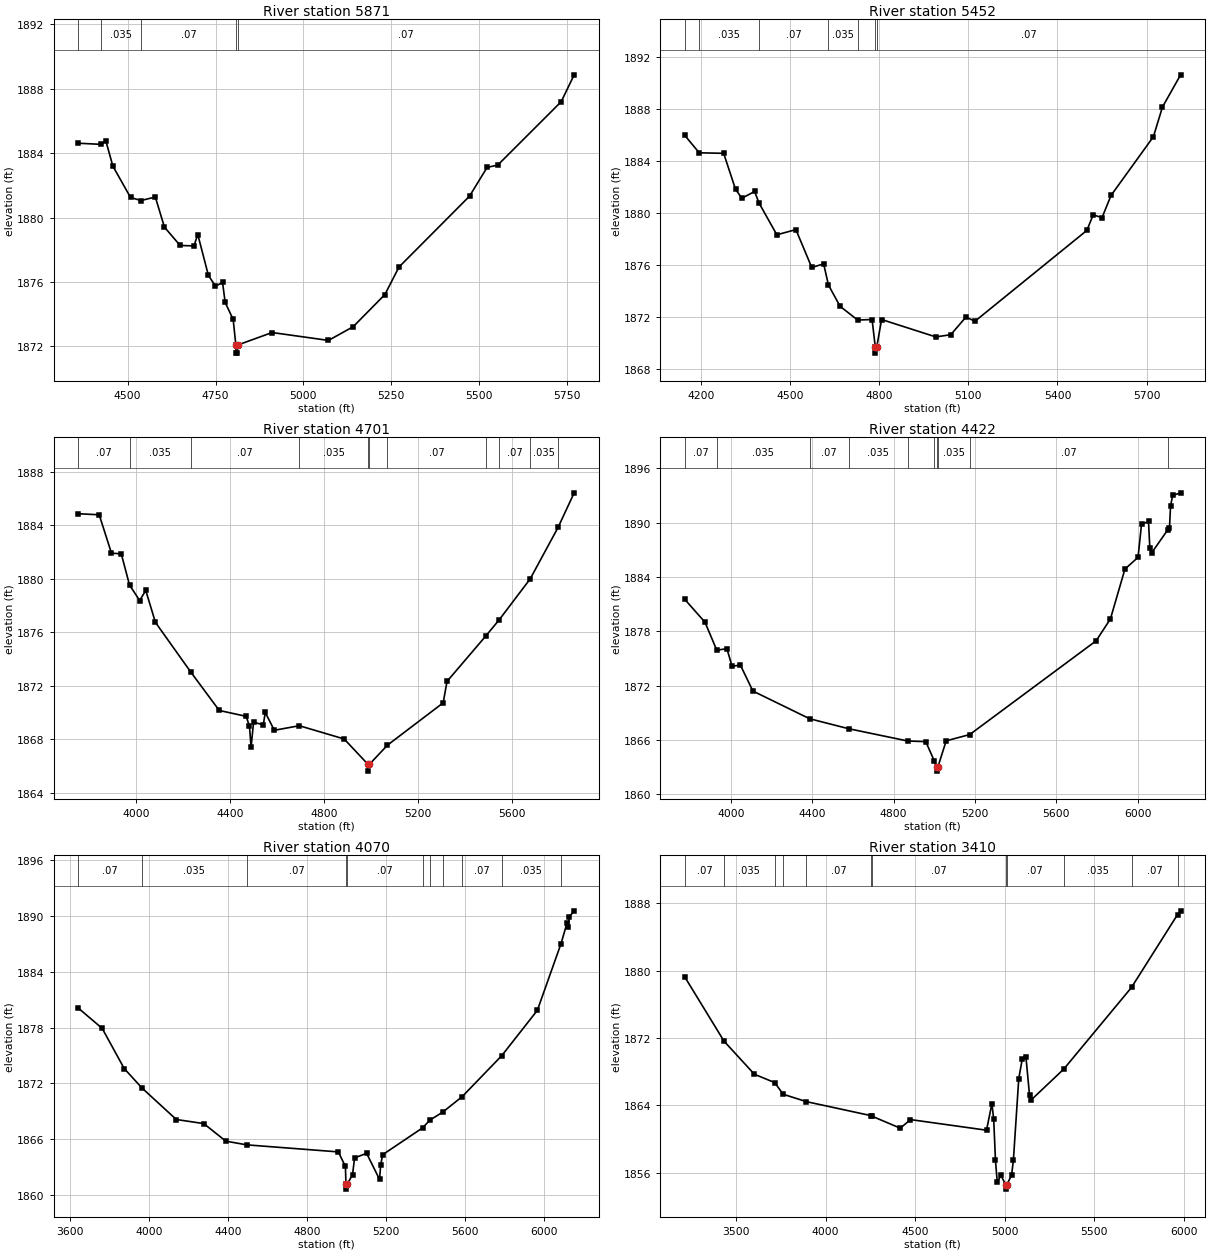
Type RM Length L Ch R = 1 ,5871    ,419,419,419
BEGIN DESCRIPTION:
Mapping XS 7595cc43
END DESCRIPTION:
XS GIS Cut Line= 3
      1523517.44      6831644.84      1524059.06      6831707.34
      1524921.83       6831641.5
#Sta/Elev= 30
  4359.7 1884.62  4425.3 1884.55  4437.8 1884.78  4457.9  1883.2  4508.2 1881.25
  4538.1 1881.06  4578.7 1881.28  4604.6 1879.41  4649.2 1878.27  4688.5 1878.24
  4699.5 1878.95  4729.7 1876.41  4749.8 1875.74    4770 1875.97  4777.4 1874.73
  4800.2 1873.67  4807.8 1872.08  4808.2 1871.58  4812.3 1871.58  4812.6 1872.08
  4910.9 1872.86  5071.3 1872.37  5141.5 1873.22  5231.8 1875.22  5271.9 1876.93
  5472.5 1881.33  5522.6 1883.12  5552.7 1883.26  5733.3  1887.2  5770.2 1888.87
#Mann= 5 ,-1 , 0
  4359.7     .07       0  4425.3    .035       0  4538.1     .07       0
  4807.8     .07       0  4812.6     .07       0
Bank Sta=4807.8,4812.6
XS Rating Curve= 0 ,0
Exp/Cntr=0.3,0.1

Type RM Length L Ch R = 1 ,5452    ,751,751,751
BEGIN DESCRIPTION:
BULL WAGON CREEK TRIBUTARY 8 6.0
END DESCRIPTION:
XS GIS Cut Line= 3
      1523455.05      6831788.02        1524255.        6832088.
      1525055.01        6831938.
#Sta/Elev= 30
    4146 1885.97  4194.5 1884.63  4276.8 1884.59  4316.8 1881.81  4338.2 1881.13
  4380.9 1881.65  4395.5 1880.77  4455.7 1878.31  4519.8 1878.71  4573.2 1875.79
  4613.2 1876.07  4629.3 1874.44  4668.4  1872.8  4727.6 1871.74  4776.1 1871.78
  4786.8 1869.69  4787.2 1869.19  4792.1 1869.69  4808.1 1871.78  4990.6 1870.44
    5041 1870.61  5091.9 1871.97  5122.4 1871.65  5498.9 1878.65  5520.1 1879.85
  5549.8 1879.63  5580.3 1881.35  5722.7 1885.87  5753.2 1888.16  5814.3 1890.64
#Mann= 7 ,-1 , 0
    4146     .07       0  4194.5    .035       0  4395.5     .07       0
  4629.3    .035       0  4727.6     .07       0  4786.8     .07       0
  4792.1     .07       0
Bank Sta=4786.8,4792.1
XS Rating Curve= 0 ,0
Exp/Cntr=0.3,0.1

Type RM Length L Ch R = 1 ,4701    ,279,279,279
BEGIN DESCRIPTION:
BULL WAGON CREEK TRIBUTARY 8 5.0
END DESCRIPTION:
XS GIS Cut Line= 3
      1523409.73      6832360.11      1524604.92      6832708.03
       1525434.1      6832467.74
#Sta/Elev= 30
  3755.2 1884.85    3844 1884.77  3896.1  1881.9  3937.7 1881.86  3972.8 1879.53
  4015.9 1878.37  4041.9 1879.12  4082.9 1876.74  4232.8 1873.04  4354.3 1870.16
  4468.9 1869.72  4482.8 1868.98  4489.7 1867.42  4500.2 1869.28  4541.8 1869.09
  4549.8 1870.01  4588.6 1868.68  4694.7 1869.02  4885.5 1868.03    4987 1866.13
  4987.4 1865.63  4992.4 1866.13  5069.6 1867.57  5306.4 1870.73  5322.8 1872.33
  5488.1 1875.73  5545.1 1876.94  5676.2 1879.98  5795.3 1883.84  5863.3 1886.41
#Mann= 11 ,-1 , 0
  3755.2     .07       0  3972.8    .035       0  4232.8     .07       0
  4694.7    .035       0    4987    .035       0  4992.4    .035       0
  5069.6     .07       0  5488.1    .035       0  5545.1     .07       0
  5676.2    .035       0  5795.3     .07       0
Bank Sta=4987,4992.4
XS Rating Curve= 0 ,0
Exp/Cntr=0.3,0.1

Type RM Length L Ch R = 1 ,4422    ,352,352,352
BEGIN DESCRIPTION:
Mapping XS 2d880ba7
END DESCRIPTION:
XS GIS Cut Line= 3
      1523458.11      6832708.72      1524671.67      6832974.35
      1525843.58      6833203.52
#Sta/Elev= 30
  3774.4 1881.53  3873.6 1879.01  3931.5 1875.92  3981.3 1876.08  4006.7 1874.14
  4047.6 1874.27    4109  1871.4  4387.9 1868.34    4579 1867.24  4869.9 1865.88
  4958.6 1865.81  5000.5 1863.67  5013.1 1863.05  5013.5 1862.55  5018.6 1863.05
  5058.8  1865.9  5174.4 1866.59  5795.4 1876.95  5865.8 1879.37  5937.1 1884.88
  6001.5 1886.18  6018.6 1889.81    6053 1890.15  6059.4 1887.22  6069.6 1886.71
  6147.3 1889.21  6156.1 1889.44  6161.3 1891.86  6171.5 1893.02  6210.8 1893.31
#Mann= 10 ,-1 , 0
  3774.4     .07       0  3931.5    .035       0  4387.9     .07       0
    4579    .035       0  4869.9     .07       0  5000.5    .035       0
  5013.1     .07       0  5018.6    .035       0  5174.4     .07       0
  6147.3    .035       0
Bank Sta=5013.1,5018.6
XS Rating Curve= 0 ,0
Exp/Cntr=0.3,0.1

Type RM Length L Ch R = 1 ,4070    ,660,660,660
BEGIN DESCRIPTION:
Mapping XS 32ff0497
END DESCRIPTION:
XS GIS Cut Line= 3
      1523347.35      6832878.86      1524649.45      6833250.39
      1525788.36      6833469.15
#Sta/Elev= 30
    3641 1880.09  3761.8 1877.91  3873.6 1873.58  3963.9 1871.48  4137.7 1868.09
  4276.9 1867.65  4388.7 1865.76  4494.6 1865.36  4959.2  1864.6  4995.1 1863.03
  4997.9 1861.09  4998.4 1860.59  5003.5 1861.09  5031.3 1862.16  5041.5 1863.95
  5102.5 1864.45  5168.3 1861.63  5173.8 1863.21    5184  1864.3  5386.3 1867.19
  5423.2 1868.02  5489.4  1868.9  5586.9 1870.55  5787.4 1874.96  5968.2 1879.85
  6088.1 1887.03    6119 1889.28  6124.1 1888.79    6131 1889.94  6154.8 1890.57
#Mann= 11 ,-1 , 0
    3641     .07       0  3963.9    .035       0  4494.6     .07       0
  4997.9     .07       0  5003.5     .07       0  5386.3    .035       0
  5423.2     .07       0  5489.4    .035       0  5586.9     .07       0
  5787.4    .035       0  6088.1     .07       0
Bank Sta=4997.9,5003.5
XS Rating Curve= 0 ,0
Exp/Cntr=0.3,0.1

Type RM Length L Ch R = 1 ,3410    ,320,320,320
BEGIN DESCRIPTION:
Mapping XS 37da9bac
END DESCRIPTION:
XS GIS Cut Line= 3
      1523371.65      6832923.12      1524621.67      6833756.47
      1525889.07      6833786.85
#Sta/Elev= 30
  3213.7 1879.25  3433.1 1871.62  3602.3  1867.7  3716.4  1866.7  3763.2 1865.32
  3893.5 1864.44  4254.2 1862.78  4260.1 1862.71  4417.5 1861.29  4474.5 1862.31
  4899.4 1861.05  4929.4 1864.21  4939.4 1862.37  4949.4 1857.46  4959.4 1854.84
  4979.4 1855.71  5006.6 1854.55  5007.1 1854.05  5012.2 1854.55  5039.5 1855.71
  5049.5  1857.5  5079.5 1867.18  5099.5 1869.56  5119.5 1869.79  5139.5 1865.24
  5149.5 1864.66    5331 1868.31  5709.4 1878.01  5966.5 1886.66  5983.8 1887.11
#Mann= 12 ,-1 , 0
  3213.7     .07       0  3433.1    .035       0  3716.4     .07       0
  3763.2    .035       0  3893.5     .07       0  4254.2     .16       0
  4260.1     .07       0  5006.6     .07       0  5012.2     .07       0
    5331    .035       0  5709.4     .07       0  5966.5    .035       0
Bank Sta=5006.6,5012.2
XS Rating Curve= 0 ,0
Exp/Cntr=0.3,0.1

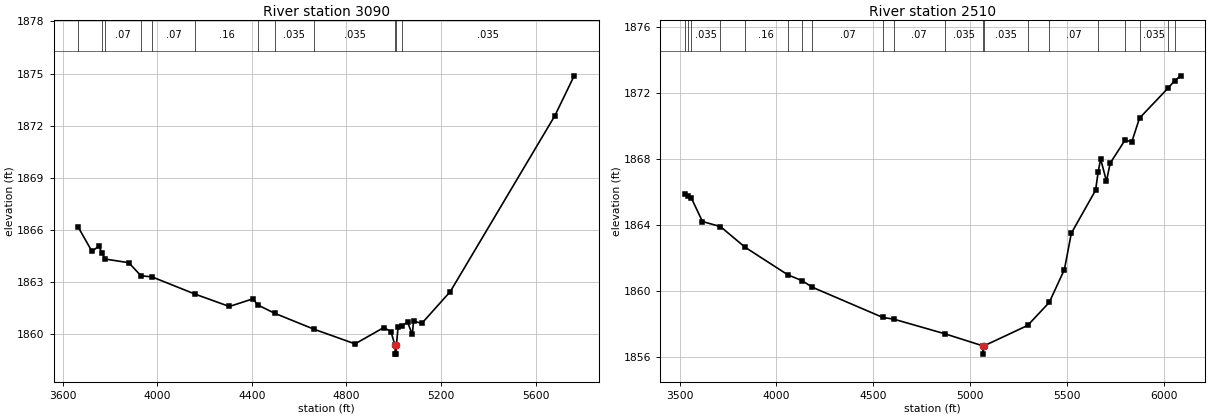
Type RM Length L Ch R = 1 ,3090    ,580,580,580
BEGIN DESCRIPTION:
Mapping XS 6fe303d1
END DESCRIPTION:
XS GIS Cut Line= 3
       1523768.2      6833223.61      1524698.75       6834036.1
       1525556.4      6834115.96
#Sta/Elev= 30
  3666.6 1866.15  3724.3 1864.77  3752.8 1865.07  3768.1 1864.65  3779.6 1864.33
    3880 1864.12  3931.2 1863.37  3978.9  1863.3  4160.7 1862.31  4305.2  1861.6
  4404.9 1862.04  4425.5 1861.69  4496.7 1861.21  4663.8 1860.29  4836.8 1859.45
  4958.4 1860.39  4988.6 1860.15  5005.9 1859.36  5006.3 1858.86    5011 1858.86
  5011.5 1859.36  5018.7  1860.4  5033.9  1860.5  5058.9 1860.69    5079 1859.99
  5084.1 1860.76  5119.1 1860.63  5239.6 1862.46  5681.5 1872.57  5763.3 1874.87
#Mann= 12 ,-1 , 0
  3666.6     .07       0  3768.1    .035       0  3779.6     .07       0
  3931.2     .16       0  3978.9     .07       0  4160.7     .16       0
  4425.5     .07       0  4496.7    .035       0  4663.8    .035       0
  5005.9    .035       0  5011.5    .035       0  5033.9    .035       0
Bank Sta=5005.9,5011.5
XS Rating Curve= 0 ,0
Exp/Cntr=0.3,0.1

Type RM Length L Ch R = 1 ,2510    ,0,0,0
BEGIN DESCRIPTION:
BULL WAGON CREEK TRIBUTARY 8 1.0
END DESCRIPTION:
XS GIS Cut Line= 3
      1523729.74      6833238.88      1524512.72      6834493.22
      1525584.76      6834627.77
#Sta/Elev= 30
  3527.2  1865.9  3541.6 1865.77  3560.7 1865.65  3618.3 1864.22  3711.4 1863.91
  3838.5 1862.66  4057.7    1861  4133.6 1860.63  4185.4 1860.24  4549.4 1858.41
    4605 1858.31    4870 1857.42  5065.8 1856.69  5066.3 1856.19  5071.4 1856.69
  5297.1 1857.93  5408.1 1859.32  5486.4 1861.31  5522.2 1863.51  5647.3 1866.11
  5660.9 1867.23  5673.3 1868.01  5703.6 1866.66  5722.7 1867.75  5798.9 1869.14
  5834.6 1869.05  5874.1 1870.48  6020.1 1872.28  6055.5 1872.74  6086.3 1873.04
#Mann= 20 ,-1 , 0
  3527.2    .035       0  3541.6     .07       0  3560.7    .035       0
  3711.4     .07       0  3838.5     .16       0  4057.7     .07       0
  4133.6     .16       0  4185.4     .07       0  4549.4     .16       0
    4605     .07       0    4870    .035       0  5065.8    .035       0
  5071.4    .035       0  5297.1    .035       0  5408.1     .07       0
  5660.9    .035       0  5798.9     .07       0  5874.1    .035       0
  6020.1     .07       0  6055.5    .035       0
Bank Sta=5065.8,5071.4
XS Rating Curve= 0 ,0
Exp/Cntr=0.3,0.1

Chan Stop Cuts=-1
Use User Specified Reach Order=0
Composite Channel Slope=5