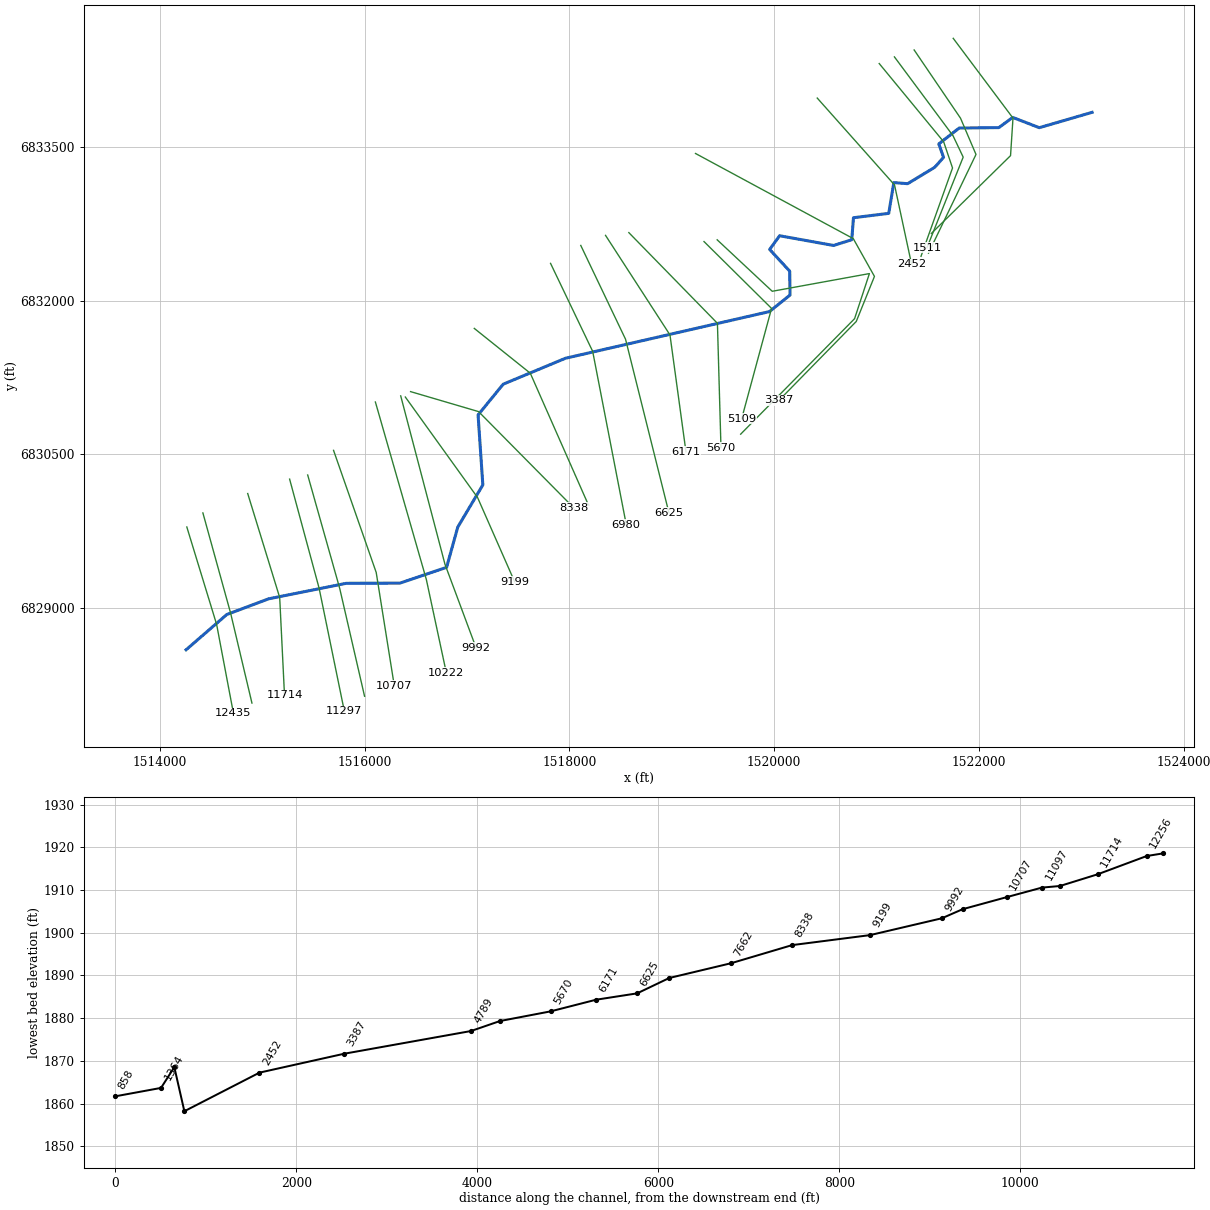
--- BULL WAGON CREEK TRIBUTARY 9.prj (project) ---

Proj Title=BULL WAGON CREEK TRIBUTARY 9 Base Level Engineering
Current Plan=p01
Default Exp/Contr=0.3,0.1
English Units
Geom File=g01
Flow File=f01
Plan File=p01
Y Axis Title=Elevation
X Axis Title(PF)=Main Channel Distance
X Axis Title(XS)=Station
BEGIN DESCRIPTION:
BULL WAGON CREEK TRIBUTARY 9
END DESCRIPTION:
DSS Export Rating Curves= 0
DSS Export Rating Curve Sorted= 0
DSS Export Volume Flow Curves= 0
DXF OffsetX= 0
DXF OffsetY= 0
DXF ScaleX= 1
DXF ScaleY= 10

--- BULL WAGON CREEK TRIBUTARY 9.p01 (plan) ---

Plan Title=Multiple Run
Short Identifier=Multiple
Geom File=g01
Flow File=f01
Subcritical Flow
K Sum by GR= 0
Std Step Tol= 0.01
Critical Tol= 0.01
Num of Std Step Trials= 20
Max Error Tol= 0.3
Flow Tol Ratio= 0.001
Split Flow NTrial= 30
Split Flow Tol= 0.02
Split Flow Ratio= 0.02
Log Output Level= 0
Friction Slope Method= 1
Unsteady Friction Slope Method= 2
Unsteady Bridges Friction Slope Method= 1
Parabolic Critical Depth
Global Vel Dist=  1 , 1 , 1
Global Log Level= 0
CheckData=True
Encroach Param= -1, 0, 0, 0
BEGIN DESCRIPTION:
Multiple Run
END DESCRIPTION:

--- BULL WAGON CREEK TRIBUTARY 9.f01 (steady flow) ---

Flow Title=Multiple
Number of Profiles=7
Profile Names=10-year,25-year,50-year,1pct_min,100-year,1pct_plu,500-year
River Rch & RM= BULL WAGON CREEK,Reach-1,12435
     346     502     638     405     808    1612    1310
River Rch & RM= BULL WAGON CREEK,Reach-1,12256
     492     723     927     591    1180    2353    1938
River Rch & RM= BULL WAGON CREEK,Reach-1,3387
     523     768     984     627    1251    2496    2052
Boundary for River Rch & Prof#=BULL WAGON CREEK,Reach-1,1
Up Type=0
Dn Type=3
Dn Slope=0.005
Boundary for River Rch & Prof#=BULL WAGON CREEK,Reach-1,2
Up Type=0
Dn Type=3
Dn Slope=0.005
Boundary for River Rch & Prof#=BULL WAGON CREEK,Reach-1,3
Up Type=0
Dn Type=3
Dn Slope=0.005
Boundary for River Rch & Prof#=BULL WAGON CREEK,Reach-1,4
Up Type=0
Dn Type=3
Dn Slope=0.005
Boundary for River Rch & Prof#=BULL WAGON CREEK,Reach-1,5
Up Type=0
Dn Type=3
Dn Slope=0.005
Boundary for River Rch & Prof#=BULL WAGON CREEK,Reach-1,6
Up Type=0
Dn Type=3
Dn Slope=0.005
Boundary for River Rch & Prof#=BULL WAGON CREEK,Reach-1,7
Up Type=0
Dn Type=3
Dn Slope=0.005

--- BULL WAGON CREEK TRIBUTARY 9.g01 (geometry) ---

Geom Title=Existing Conditions
Program Version=4.10

River Reach=BULL WAGON CREEK,Reach-1
Reach XY= 30
        1514255.        6828588.      1514652.57      6828932.48
      1515060.93      6829085.74      1515820.22      6829237.48
       1516344.5      6829239.22      1516799.75      6829393.44
      1516908.83      6829786.42       1517153.8       6830198.5
      1517107.23      6830882.07      1517352.63      6831182.46
      1517960.94      6831435.74      1519953.44      6831891.76
      1520154.62      6832053.15      1520151.46      6832286.54
      1519955.55      6832498.64      1520052.53      6832632.55
        1520580.       6832537.6      1520757.62      6832593.73
      1520774.22      6832808.58      1521118.81      6832851.22
      1521168.61      6833152.03      1521303.35      6833141.16
      1521568.34      6833301.39       1521654.4      6833398.62
      1521607.64      6833529.52      1521806.46      6833684.46
      1522194.56      6833689.06      1522329.96      6833788.49
      1522589.61      6833688.08        1523105.        6833838.

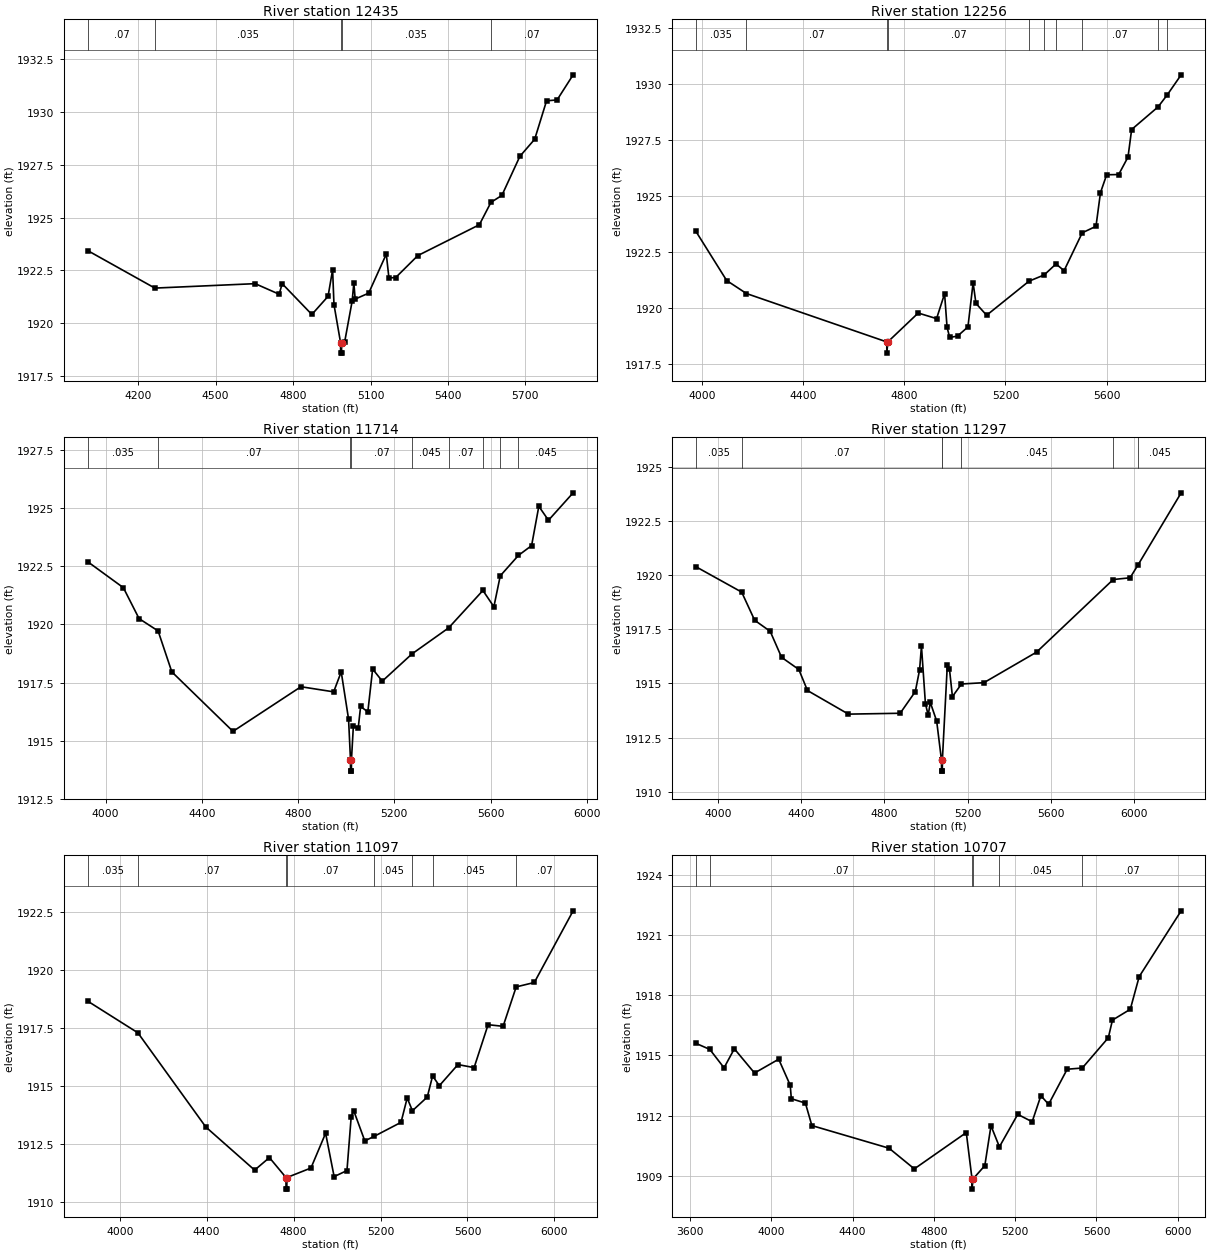
Type RM Length L Ch R = 1 ,12435   ,179,179,179
BEGIN DESCRIPTION:
BULL WAGON CREEK TRIBUTARY 9 12.0
END DESCRIPTION:
XS GIS Cut Line= 3
      1514262.16      6829787.61      1514553.17      6828836.22
       1514717.7      6827966.85
#Sta/Elev= 30
  4005.1 1923.43  4264.4 1921.66    4653 1921.87  4745.9 1921.37  4757.6 1921.87
  4872.6 1920.41  4935.4 1921.27    4953 1922.53  4958.3 1920.88  4983.8 1919.08
  4984.1 1918.58  4987.6 1918.58  4987.8 1919.08    5000 1919.13  5028.7 1921.04
  5035.3 1921.91  5040.4 1921.14  5092.7 1921.42    5161 1923.27  5171.2 1922.14
  5197.4 1922.16  5283.2  1923.2  5521.5 1924.66  5566.4 1925.72  5608.8 1926.05
  5678.5  1927.9  5735.9 1928.71  5781.9 1930.53  5822.6 1930.57  5884.8 1931.76
#Mann= 5 ,-1 , 0
  4005.1     .07       0  4264.4    .035       0  4983.8    .035       0
  4987.8    .035       0  5566.4     .07       0
Bank Sta=4983.8,4987.8
XS Rating Curve= 0 ,0
Exp/Cntr=0.3,0.1

Type RM Length L Ch R = 1 ,12256   ,542,542,542
BEGIN DESCRIPTION:
Mapping XS 50ca003a
END DESCRIPTION:
XS GIS Cut Line= 3
      1514419.11       6829925.1      1514689.93      6828945.97
      1514898.26      6828067.53
#Sta/Elev= 30
  3976.1  1923.4  4097.6 1921.21  4175.7 1920.63  4730.7 1918.47  4730.9 1917.97
  4734.7 1918.47    4855 1919.76  4927.6 1919.51  4959.3 1920.62  4969.1 1919.12
  4979.5 1918.67  5010.5 1918.73  5051.6 1919.14  5072.1 1921.11  5083.3 1920.19
  5125.5 1919.66    5293 1921.18  5353.2 1921.46  5399.9 1921.95  5431.8 1921.65
  5503.6 1923.34    5558 1923.63  5575.7 1925.13  5600.2 1925.93  5647.7 1925.94
  5684.6 1926.72    5699 1927.95  5803.6 1928.96  5840.1  1929.5  5894.8 1930.39
#Mann= 10 ,-1 , 0
  3976.1    .035       0  4175.7     .07       0  4730.7     .07       0
  4734.7     .07       0    5293    .035       0  5353.2     .07       0
  5399.9    .045       0  5503.6     .07       0  5803.6    .035       0
  5840.1    .045       0
Bank Sta=4730.7,4734.7
XS Rating Curve= 0 ,0
Exp/Cntr=0.3,0.1

Type RM Length L Ch R = 1 ,11714   ,417,417,417
BEGIN DESCRIPTION:
Mapping XS 77c2cd8a
END DESCRIPTION:
XS GIS Cut Line= 3
      1514856.89      6830114.38      1515169.39      6829098.75
      1515216.26      6828145.62
#Sta/Elev= 30
  3926.5 1922.69  4073.8 1921.58  4139.1 1920.25  4218.2 1919.72  4275.2 1917.96
  4529.5  1915.4    4812 1917.32    4948  1917.1  4979.4 1917.96  5009.9 1915.93
  5017.9 1914.19  5018.1 1913.69  5021.7 1913.69    5022 1914.19  5029.9 1915.63
  5049.9 1915.53    5060 1916.47    5090 1916.24    5110 1918.08  5150.1 1917.56
  5273.4 1918.73  5425.8 1919.85  5568.4 1921.46    5614 1920.76  5640.5 1922.09
  5716.2 1922.97  5770.8 1923.39  5800.8 1925.08  5840.9 1924.48  5943.4 1925.66
#Mann= 9 ,-1 , 0
  3926.5    .035       0  4218.2     .07       0  5017.9     .07       0
    5022     .07       0  5273.4    .045       0  5425.8     .07       0
  5568.4    .045       0  5640.5     .07       0  5716.2    .045       0
Bank Sta=5017.9,5022
XS Rating Curve= 0 ,0
Exp/Cntr=0.3,0.1

Type RM Length L Ch R = 1 ,11297   ,200,200,200
BEGIN DESCRIPTION:
Mapping XS 650da8ea
END DESCRIPTION:
XS GIS Cut Line= 3
      1515266.32        6830255.      1515554.52      6829189.03
      1515801.05       6827987.6
#Sta/Elev= 30
  3895.1 1920.38  4114.7 1919.21  4177.1 1917.91  4251.7  1917.4  4306.4  1916.2
  4389.2 1915.64  4430.7 1914.67  4627.5 1913.58  4876.1 1913.62  4948.8 1914.62
  4969.3 1915.62  4978.3 1916.72  4997.3 1914.07  5010.6 1913.53  5020.8 1914.12
  5051.4 1913.26  5074.6 1911.45  5074.9 1910.95  5078.5 1910.95  5078.7 1911.45
  5102.5 1915.84  5112.7 1915.67  5127.1 1914.39  5170.5 1914.97  5278.2 1915.03
  5531.2 1916.44  5899.4 1919.79  5980.4 1919.87  6018.4 1920.46  6225.8 1923.79
#Mann= 7 ,-1 , 0
  3895.1    .035       0  4114.7     .07       0  5074.6     .07       0
  5078.7     .07       0  5170.5    .045       0  5899.4     .07       0
  6018.4    .045       0
Bank Sta=5074.6,5078.7
XS Rating Curve= 0 ,0
Exp/Cntr=0.3,0.1

Type RM Length L Ch R = 1 ,11097   ,390,390,390
BEGIN DESCRIPTION:
Mapping XS 99538471
END DESCRIPTION:
XS GIS Cut Line= 3
      1515442.83       6830295.5      1515755.33      6829188.74
      1515998.39      6828134.02
#Sta/Elev= 30
  3853.6 1918.67  4083.5 1917.31  4395.9 1913.25  4620.6 1911.39  4688.6 1911.93
  4764.9 1911.07  4765.1 1910.57  4768.7 1910.57    4769 1911.07  4879.7 1911.48
  4947.2 1912.98  4986.4 1911.11  5045.4 1911.37  5064.9 1913.69  5076.2 1913.96
  5127.5 1912.65  5169.4 1912.84  5294.2 1913.45  5322.5  1914.5  5346.6 1913.95
  5414.9 1914.54  5439.4 1915.45  5470.5 1915.03  5556.1 1915.94  5630.4 1915.81
  5694.7 1917.66  5763.8 1917.59    5824 1919.29  5907.5 1919.48    6086 1922.57
#Mann= 8 ,-1 , 0
  3853.6    .035       0  4083.5     .07       0  4764.9     .07       0
    4769     .07       0  5169.4    .045       0  5346.6     .07       0
  5439.4    .045       0    5824     .07       0
Bank Sta=4764.9,4769
XS Rating Curve= 0 ,0
Exp/Cntr=0.3,0.1

Type RM Length L Ch R = 1 ,10707   ,485,485,485
BEGIN DESCRIPTION:
Mapping XS 3d863035
END DESCRIPTION:
XS GIS Cut Line= 3
      1515695.43      6830536.26       1516112.1      6829343.54
      1516289.18      6828234.19
#Sta/Elev= 30
  3629.7  1915.6  3697.7  1915.3  3767.9 1914.38  3818.5 1915.33  3917.8 1914.12
  4036.7 1914.81  4093.5 1913.51  4098.8 1912.84  4168.1 1912.62  4199.9  1911.5
  4579.7 1910.37  4703.9 1909.34  4959.5 1911.15  4987.8 1908.83  4988.1 1908.33
  4991.9 1908.83  5050.6  1909.5    5081 1911.49  5122.4 1910.44  5212.6 1912.06
  5283.5 1911.69  5326.5 1912.99  5364.5 1912.56  5455.8 1914.31  5530.1 1914.37
  5658.2 1915.88  5678.5 1916.76  5766.3  1917.3  5810.1 1918.93  6016.5 1922.21
#Mann= 6 ,-1 , 0
  3629.7    .035       0  3697.7     .07       0  4987.8     .07       0
  4991.9     .07       0  5122.4    .045       0  5530.1     .07       0
Bank Sta=4987.8,4991.9
XS Rating Curve= 0 ,0
Exp/Cntr=0.3,0.1

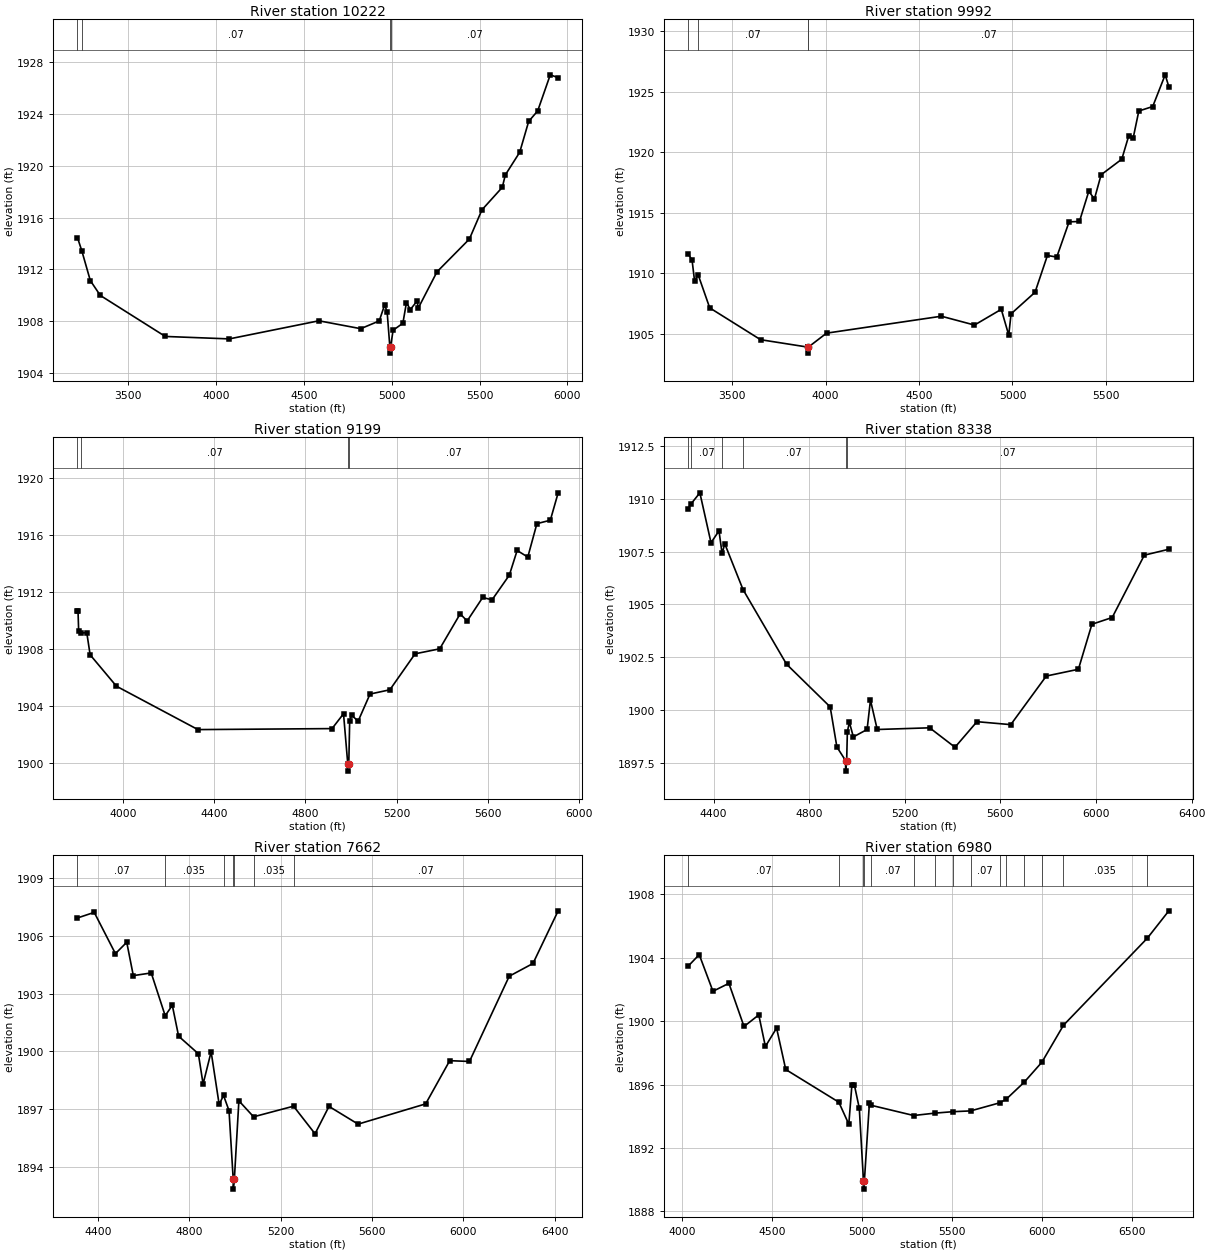
Type RM Length L Ch R = 1 ,10222   ,230,230,230
BEGIN DESCRIPTION:
Mapping XS 4f494dfc
END DESCRIPTION:
XS GIS Cut Line= 3
      1516104.17      6831008.37      1516601.68      6829275.55
        1516797.      6828364.07
#Sta/Elev= 30
  3212.1 1914.46  3237.6  1913.4  3285.3 1911.13  3342.2 1909.98  3711.9 1906.81
    4076 1906.62  4585.8 1908.02  4823.8 1907.41  4929.1 1908.01  4960.4 1909.27
  4974.3 1908.67  4989.4 1906.02  4989.7 1905.52  4993.8 1906.02    5008 1907.29
  5063.6 1907.83    5084 1909.43    5106 1908.89  5145.2 1909.56  5150.3 1908.98
  5257.9 1911.81    5442 1914.34  5513.5  1916.6  5629.3 1918.34  5646.5  1919.3
  5728.3 1921.05  5779.4 1923.44  5830.6 1924.25  5902.2 1927.04  5947.1 1926.82
#Mann= 4 ,-1 , 0
  3212.1    .035       0  3237.6     .07       0  4989.4     .07       0
  4993.8     .07       0
Bank Sta=4989.4,4993.8
XS Rating Curve= 0 ,0
Exp/Cntr=0.3,0.1

Type RM Length L Ch R = 1 ,9992    ,793,793,793
BEGIN DESCRIPTION:
Mapping XS 033d1278
END DESCRIPTION:
XS GIS Cut Line= 3
      1516351.56      6831068.28      1516783.97      6829423.12
      1517087.78      6828607.18
#Sta/Elev= 30
  3264.7  1911.6  3285.7 1911.08  3299.5 1909.31  3318.2 1909.87  3380.2 1907.13
  3652.3  1904.5  3903.8 1903.89  3904.1 1903.39  3908.2 1903.89  4005.1 1905.04
  4619.5 1906.44  4796.6 1905.71    4940 1907.01  4979.8 1904.88  4992.5 1906.64
  5120.6 1908.42  5186.8 1911.46  5236.8 1911.33  5302.8 1914.24  5358.1 1914.27
  5408.1 1916.76  5438.5 1916.14  5474.1 1918.13  5584.8 1919.42  5622.1 1921.36
  5645.5 1921.16  5675.8  1923.4  5750.2 1923.77  5816.8 1926.39  5836.4 1925.41
#Mann= 4 ,-1 , 0
  3264.7    .035       0  3318.2     .07       0  3903.8     .07       0
  3908.2     .07       0
Bank Sta=3903.8,3908.2
XS Rating Curve= 0 ,0
Exp/Cntr=0.3,0.1

Type RM Length L Ch R = 1 ,9199    ,861,861,861
BEGIN DESCRIPTION:
Mapping XS 0c4fd11f
END DESCRIPTION:
XS GIS Cut Line= 3
      1516396.71      6831056.97      1517102.44       6830075.2
      1517464.25      6829252.66
#Sta/Elev= 30
  3800.2  1910.7  3802.6  1910.7  3805.5 1909.28    3816 1909.13  3841.1 1909.15
  3855.8  1907.6  3971.2  1905.4  4328.5 1902.36  4916.5 1902.43  4966.8 1903.47
  4985.5 1899.95  4985.8 1899.45  4989.9 1899.95  4993.8 1902.95  5002.4 1903.37
  5030.8 1902.95    5083 1904.85  5170.1 1905.15  5280.6 1907.67  5388.6 1908.02
  5478.3 1910.47  5508.8 1909.97  5577.1 1911.62    5618 1911.45  5693.8 1913.18
  5728.1 1914.91  5774.8 1914.45  5814.7 1916.79  5873.6 1917.03  5907.9 1918.95
#Mann= 4 ,-1 , 0
  3800.2    .035       0    3816     .07       0  4985.5     .07       0
  4989.9     .07       0
Bank Sta=4985.5,4989.9
XS Rating Curve= 0 ,0
Exp/Cntr=0.3,0.1

Type RM Length L Ch R = 1 ,8338    ,676,676,676
BEGIN DESCRIPTION:
Mapping XS d6af404a
END DESCRIPTION:
XS GIS Cut Line= 3
       1516447.9      6831109.93       1517112.1      6830914.72
       1518039.2       6829977.2
#Sta/Elev= 30
  4293.7 1909.53    4304 1909.73  4342.8 1910.28  4389.4 1907.92  4422.8 1908.48
  4435.7 1907.41    4447 1907.87  4523.4  1905.7  4705.4 1902.17  4887.9 1900.15
    4916 1898.25  4952.3 1897.61  4952.6 1897.11  4956.9 1897.61  4959.8 1898.98
  4968.2 1899.42  4984.9 1898.73  5042.3 1899.08  5056.4 1900.47  5084.7 1899.08
    5304 1899.16    5410 1898.24  5501.9 1899.45  5643.3 1899.31  5791.9 1901.61
  5926.2 1901.93  5982.7 1904.06  6067.6 1904.38    6202 1907.33  6304.5 1907.61
#Mann= 6 ,-1 , 0
  4293.7    .035       0    4304     .07       0  4435.7    .035       0
  4523.4     .07       0  4952.3     .07       0  4956.9     .07       0
Bank Sta=4952.3,4956.9
XS Rating Curve= 0 ,0
Exp/Cntr=0.3,0.1

Type RM Length L Ch R = 1 ,7662    ,682,682,682
BEGIN DESCRIPTION:
Mapping XS da2f61a1
END DESCRIPTION:
XS GIS Cut Line= 3
      1517070.43      6831727.23       1517617.3      6831289.72
      1518185.01      6830003.26
#Sta/Elev= 30
  4309.3 1906.92  4382.8 1907.21  4475.7 1905.07  4525.3 1905.66  4554.1 1903.93
  4632.6 1904.07  4693.8 1901.85    4725 1902.39  4752.6 1900.79  4839.1 1899.88
  4859.9 1898.31  4895.1 1899.98  4930.3 1897.25  4949.4 1897.72  4973.5 1896.93
  4991.9 1893.36  4992.2 1892.86  4996.8 1893.36  5016.7 1897.44  5081.1 1896.61
  5256.2 1897.16  5350.4 1895.73  5411.6 1897.15  5539.1 1896.23  5835.2 1897.28
  5940.6 1899.52  6027.2 1899.48  6201.4  1903.9  6305.5 1904.56  6415.8 1907.29
#Mann= 7 ,-1 , 0
  4309.3     .07       0  4693.8    .035       0  4949.4     .07       0
  4991.9     .07       0  4996.8     .07       0  5081.1    .035       0
  5256.2     .07       0
Bank Sta=4991.9,4996.8
XS Rating Curve= 0 ,0
Exp/Cntr=0.3,0.1

Type RM Length L Ch R = 1 ,6980    ,355,355,355
BEGIN DESCRIPTION:
Mapping XS ff49ee38
END DESCRIPTION:
XS GIS Cut Line= 3
      1517815.21      6832362.67      1518226.68      6831503.27
      1518554.57      6829811.79
#Sta/Elev= 30
  4031.8 1903.46  4093.6 1904.19    4170 1901.88  4258.7 1902.38  4342.9 1899.66
    4425 1900.39  4461.8  1898.4  4524.2 1899.56  4575.1 1896.95  4870.6 1894.89
  4926.2  1893.5  4943.3 1895.95  4957.2 1895.97  4984.6 1894.51  5007.9 1889.91
  5008.3 1889.41  5012.8 1889.91  5040.9 1894.84    5052 1894.69  5287.3 1894.05
  5405.7  1894.2  5504.9 1894.29  5604.1 1894.34  5766.2 1894.85  5802.6 1895.08
  5901.8 1896.14    6001 1897.41  6121.2 1899.74  6588.2 1905.23  6707.6 1906.95
#Mann= 15 ,-1 , 0
  4031.8     .07       0  4870.6    .035       0  5007.9    .035       0
  5012.8    .035       0    5052     .07       0  5287.3    .035       0
  5405.7     .07       0  5504.9    .035       0  5604.1     .07       0
  5766.2    .035       0  5802.6     .07       0  5901.8    .035       0
    6001     .07       0  6121.2    .035       0  6588.2     .07       0
Bank Sta=5007.9,5012.8
XS Rating Curve= 0 ,0
Exp/Cntr=0.3,0.1

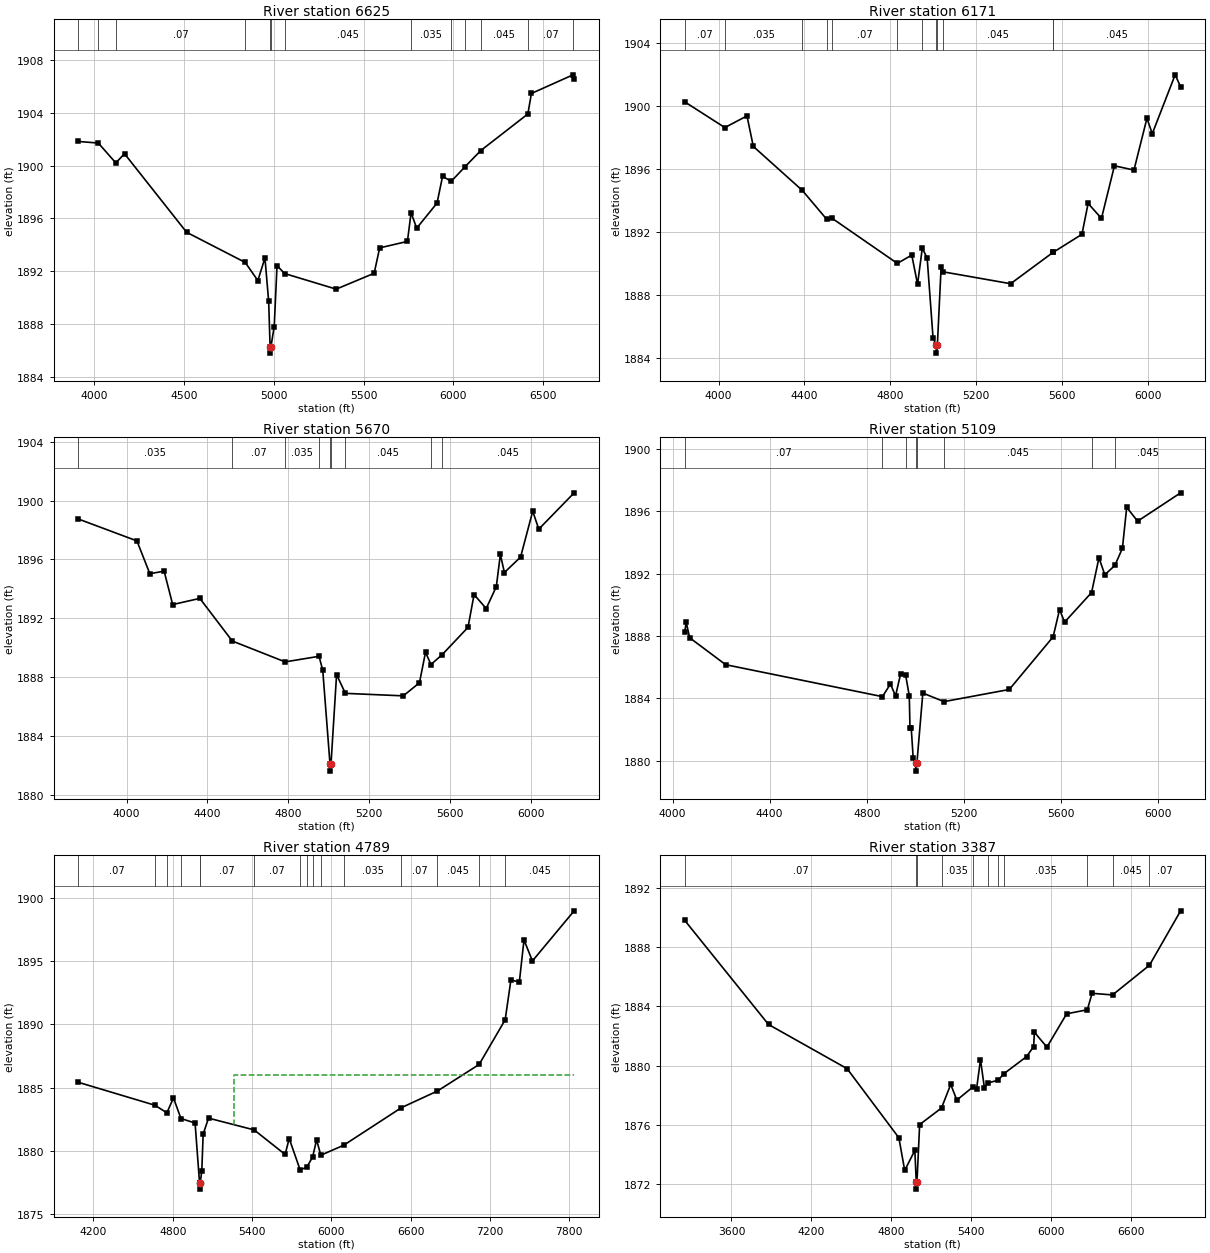
Type RM Length L Ch R = 1 ,6625    ,454,454,454
BEGIN DESCRIPTION:
Mapping XS 12a79543
END DESCRIPTION:
XS GIS Cut Line= 3
      1518110.37      6832537.97      1518547.86      6831621.32
      1518971.47      6829926.87
#Sta/Elev= 30
  3910.6 1901.82    4022  1901.7  4119.1  1900.2    4168 1900.89  4513.9 1894.95
  4840.3 1892.67  4910.7  1891.3  4950.3 1893.01    4971 1889.72  4978.9 1886.31
  4979.3 1885.81  4983.8 1886.31  5001.9 1887.82  5017.5 1892.43  5059.6 1891.83
  5347.3 1890.65  5558.6 1891.85  5589.4 1893.77    5744 1894.26  5764.3 1896.43
  5795.6 1895.26    5909 1897.16  5939.9 1899.19  5987.7  1898.8  6065.1 1899.91
  6152.5 1901.13    6415  1903.9  6434.7 1905.45  6666.7 1906.86  6672.9 1906.58
#Mann= 13 ,-1 , 0
  3910.6     .07       0    4022    .035       0  4119.1     .07       0
  4840.3    .035       0  4978.9    .035       0  4983.8    .035       0
  5059.6    .045       0  5764.3    .035       0  5987.7    .045       0
  6065.1    .035       0  6152.5    .045       0    6415     .07       0
  6666.7    .045       0
Bank Sta=4978.9,4983.8
XS Rating Curve= 0 ,0
Exp/Cntr=0.3,0.1

Type RM Length L Ch R = 1 ,6171    ,501,501,501
BEGIN DESCRIPTION:
Mapping XS 6af8ce0d
END DESCRIPTION:
XS GIS Cut Line= 3
      1518352.45      6832635.94      1518981.78      6831663.74
      1519137.98       6830522.6
#Sta/Elev= 30
  3842.6 1900.28  4029.2 1898.65  4132.3 1899.39  4161.8 1897.45  4389.9 1894.66
  4504.5 1892.81  4529.4 1892.88  4832.8 1890.02  4899.9 1890.55    4927  1888.7
  4949.1    1891  4971.8 1890.34  4999.1 1885.29  5014.1 1884.82  5014.5 1884.32
  5019.2 1884.82  5036.8  1889.8  5043.9 1889.49  5360.5 1888.73  5559.1 1890.73
  5559.6 1890.73  5692.8 1891.87  5721.5 1893.83  5783.7 1892.88  5844.2 1896.22
  5935.1 1895.95  5995.6 1899.24  6020.4 1898.26  6126.9    1902  6152.5 1901.24
#Mann= 12 ,-1 , 0
  3842.6     .07       0  4029.2    .035       0  4389.9     .07       0
  4504.5    .035       0  4529.4     .07       0  4832.8    .035       0
  4949.1     .07       0  5014.1     .07       0  5019.2     .07       0
  5043.9    .045       0  5559.1     .07       0  5559.6    .045       0
Bank Sta=5014.1,5019.2
XS Rating Curve= 0 ,0
Exp/Cntr=0.3,0.1

Type RM Length L Ch R = 1 ,5670    ,561,561,561
BEGIN DESCRIPTION:
Mapping XS cf3245ae
END DESCRIPTION:
XS GIS Cut Line= 3
      1518579.98      6832663.02      1519445.35      6831777.15
        1519480.      6830563.04
#Sta/Elev= 30
  3761.6 1898.75  4051.5 1897.26  4115.3 1895.03    4186  1895.2  4228.4 1892.93
  4362.7 1893.35  4523.2 1890.45  4784.6 1889.03  4952.5 1889.41  4970.9 1888.45
  5006.6  1882.1    5007  1881.6  5011.7  1882.1  5039.2 1888.16  5082.9 1886.89
  5369.3 1886.72  5449.3 1887.61  5479.3 1889.69    5506 1888.85  5562.2 1889.53
  5689.4 1891.38  5719.4 1893.61  5779.5 1892.66  5829.5 1894.15  5849.5 1896.34
  5869.5 1895.11  5949.5 1896.16  6009.6 1899.28  6039.6 1898.06  6214.6 1900.53
#Mann= 9 ,-1 , 0
  3761.6    .035       0  4523.2     .07       0  4784.6    .035       0
  4952.5     .07       0  5006.6     .07       0  5011.7     .07       0
  5082.9    .045       0    5506     .07       0  5562.2    .045       0
Bank Sta=5006.6,5011.7
XS Rating Curve= 0 ,0
Exp/Cntr=0.3,0.1

Type RM Length L Ch R = 1 ,5109    ,320,320,320
BEGIN DESCRIPTION:
Mapping XS 6184b42d
END DESCRIPTION:
XS GIS Cut Line= 3
      1519314.36      6832575.62      1519974.11      6831922.81
      1519682.46      6830846.46
#Sta/Elev= 30
  4050.3 1888.29  4056.1 1888.88  4070.3 1887.89  4218.8 1886.16  4864.8 1884.11
  4897.6 1884.92  4918.8 1884.16    4940 1885.59  4960.1 1885.52  4975.4 1884.16
  4978.3 1882.08  4983.5 1882.08  4991.4 1880.19  5001.6 1879.83    5002 1879.33
  5006.7 1879.83  5031.2 1884.34  5118.4 1883.79  5387.5 1884.57  5568.2 1887.95
  5594.7  1889.7  5615.4 1888.89  5726.6 1890.79  5757.1 1893.02  5781.2 1891.93
  5822.6 1892.53  5853.7 1893.63  5871.4 1896.26  5916.4 1895.37  6093.6 1897.19
#Mann= 8 ,-1 , 0
  4050.3     .07       0  4864.8    .035       0  4960.1     .07       0
  5001.6     .07       0  5006.7     .07       0  5118.4    .045       0
  5726.6     .07       0  5822.6    .045       0
Bank Sta=5001.6,5006.7
XS Rating Curve= 0 ,0
Exp/Cntr=0.3,0.1

Type RM Length L Ch R = 1 ,4789    ,1402,1402,1402
BEGIN DESCRIPTION:
Mapping XS e89e1555
END DESCRIPTION:
XS GIS Cut Line= 5
      1519442.89      6832592.93      1519980.77      6832090.06
        1520930.        6832263.       1520785.1      6831822.42
      1519672.33      6830694.27
#Sta/Elev= 30
  4086.4 1885.43  4665.3 1883.62    4756 1883.02  4805.9  1884.2  4862.4 1882.57
  4969.3 1882.21    5003 1877.49  5003.4 1876.99  5008.5 1877.49  5020.2 1878.45
  5030.3 1881.33    5071  1882.6  5415.8 1881.67  5650.4 1879.73    5681 1880.99
  5763.4 1878.52  5813.3 1878.71  5858.2 1879.53  5888.2 1880.88  5920.1 1879.67
  6093.6 1880.46  6530.1 1883.43  6801.7 1884.74  7117.4 1886.84  7314.3 1890.37
  7357.7 1893.52  7421.4 1893.35  7456.7 1896.68  7520.4 1895.02    7836 1898.98
#Mann= 16 ,-1 , 0
  4086.4     .07       0  4665.3     .16       0    4756     .07       0
  4862.4     .07       0    5003     .07       0  5008.5     .07       0
  5415.8     .07       0  5763.4    .035       0  5813.3     .07       0
  5858.2    .035       0  5920.1     .07       0  6093.6    .035       0
  6530.1     .07       0  6801.7    .045       0  7117.4     .07       0
  7314.3    .045       0
#XS Ineff= 2 , 0
       0                  5264.1       0    1886
Permanent Ineff=
       F       F
Bank Sta=5003,5008.5
XS Rating Curve= 0 ,0
Exp/Cntr=0.3,0.1

Type RM Length L Ch R = 1 ,3387    ,935,935,935
BEGIN DESCRIPTION:
Mapping XS 385ab9fa
END DESCRIPTION:
XS GIS Cut Line= 5
      1519231.26      6833436.21      1520772.23      6832604.48
       1520979.3      6832235.33      1520801.51      6831795.14
      1520046.69      6831024.68
#Sta/Elev= 30
  3248.9 1889.78  3878.2 1882.77  4469.1 1879.79  4858.4 1875.13  4902.2 1872.93
  4978.4 1874.28    4989 1872.17  4989.4 1871.67  4994.6 1872.17  5014.5 1876.02
  5178.9 1877.14  5248.2 1878.73  5294.1 1877.67  5417.8 1878.58    5442 1878.39
  5471.9  1880.4  5501.4  1878.5  5524.8 1878.82  5604.2 1879.01  5647.9 1879.45
    5818  1880.6  5871.7 1881.28    5877 1882.25  5971.3 1881.24  6119.8 1883.49
  6275.3 1883.76  6310.8 1884.87  6464.7 1884.76  6742.1 1886.76  6976.6 1890.43
#Mann= 11 ,-1 , 0
  3248.9     .07       0    4989     .07       0  4994.6     .07       0
  5178.9    .035       0  5417.8     .07       0  5524.8    .035       0
  5604.2     .07       0  5647.9    .035       0  6275.3     .07       0
  6464.7    .045       0  6742.1     .07       0
Bank Sta=4989,4994.6
XS Rating Curve= 0 ,0
Exp/Cntr=0.3,0.1

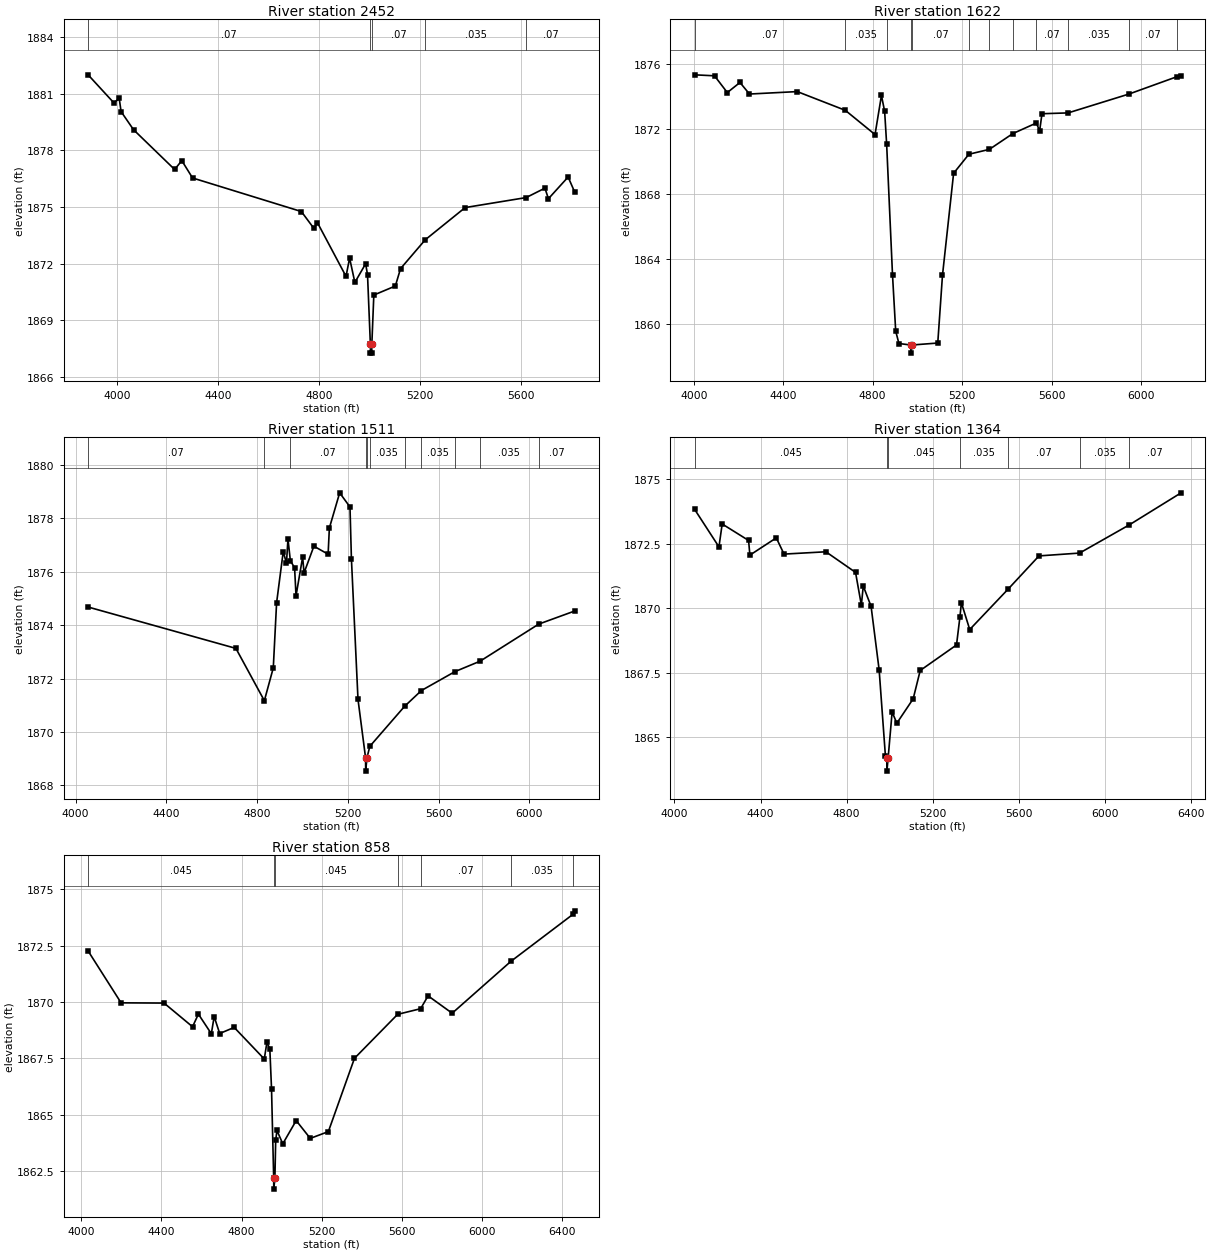
Type RM Length L Ch R = 1 ,2452    ,830,830,830
BEGIN DESCRIPTION:
Mapping XS 7936ab12
END DESCRIPTION:
XS GIS Cut Line= 3
      1520420.29      6833977.63      1521175.46       6833128.7
       1521342.1       6832352.8
#Sta/Elev= 30
  3883.5 1882.01  3985.9 1880.52  4006.8 1880.76  4014.3 1880.06  4063.6  1879.1
  4226.7 1876.99  4255.1 1877.46  4297.8 1876.54  4729.3 1874.76  4779.4 1873.86
  4793.1 1874.17  4906.5 1871.32  4920.7 1872.29  4941.6    1871  4984.3 1871.99
  4991.8 1871.41    5003 1867.75  5003.5 1867.25  5008.5 1867.25    5009 1867.75
  5016.8 1870.33  5102.2 1870.81  5122.7 1871.73  5220.7 1873.26  5379.1 1874.97
    5621  1875.5  5695.5    1876  5709.4 1875.44  5787.5 1876.59  5813.3  1875.8
#Mann= 5 ,-1 , 0
  3883.5     .07       0    5003     .07       0    5009     .07       0
  5220.7    .035       0    5621     .07       0
Bank Sta=5003,5009
XS Rating Curve= 0 ,0
Exp/Cntr=0.3,0.1

Type RM Length L Ch R = 1 ,1622    ,111,111,111
BEGIN DESCRIPTION:
Mapping XS 3e1ba22e
END DESCRIPTION:
XS GIS Cut Line= 4
      1521025.75      6834314.65      1521655.09      6833550.76
      1521741.89      6833294.68       1521434.1      6832431.98
#Sta/Elev= 30
  4003.4 1875.31  4092.5 1875.25  4149.8 1874.22  4206.4 1874.84  4248.9 1874.13
  4462.6 1874.28  4677.5 1873.13  4810.5 1871.64  4839.2 1874.04  4853.5 1873.07
  4862.5 1871.04  4888.7 1863.02    4903 1859.56  4917.4  1858.8  4970.3 1858.71
  4970.8 1858.21  4976.4 1858.71  5091.1 1858.83  5112.2 1862.99    5162 1869.26
  5230.3 1870.43  5321.9 1870.73  5426.9  1871.7  5532.3 1872.35  5546.7 1871.86
  5557.3 1872.92  5673.9 1872.97  5946.4 1874.13  6161.9  1875.2  6179.5 1875.23
#Mann= 12 ,-1 , 0
  4003.4     .07       0  4677.5    .035       0  4862.5     .07       0
  4970.3     .07       0  4976.4     .07       0  5230.3    .035       0
  5321.9     .07       0  5426.9    .035       0  5532.3     .07       0
  5673.9    .035       0  5946.4     .07       0  6161.9    .035       0
Bank Sta=4970.3,4976.4
XS Rating Curve= 0 ,0
Exp/Cntr=0.3,0.1

Type RM Length L Ch R = 1 ,1511    ,147,147,147
BEGIN DESCRIPTION:
Mapping XS 9d1edb7e
END DESCRIPTION:
XS GIS Cut Line= 4
      1521174.19      6834379.74       1521747.1      6833608.92
      1521846.06      6833400.59      1521491.89      6832515.15
#Sta/Elev= 30
  4054.8 1874.68  4706.3 1873.13  4831.7 1871.17  4871.1  1872.4  4885.7 1874.84
    4915 1876.76  4929.1 1876.32  4935.8 1877.23  4946.3 1876.42    4965 1876.15
  4971.3  1875.1  5000.5 1876.55  5006.7 1875.96  5050.1 1876.96  5112.8 1876.66
  5118.3 1877.64  5163.7 1878.96  5209.2 1878.43  5215.5 1876.49  5244.5 1871.22
  5277.9 1869.03  5278.4 1868.53    5284 1869.03  5296.7 1869.46  5450.1 1870.96
    5524 1871.55  5672.1 1872.26  5782.7 1872.65  6041.2 1874.04  6199.5 1874.53
#Mann= 11 ,-1 , 0
  4054.8     .07       0  4831.7    .035       0  4946.3     .07       0
  5277.9     .07       0    5284     .07       0  5296.7    .035       0
  5450.1     .07       0    5524    .035       0  5672.1     .07       0
  5782.7    .035       0  6041.2     .07       0
Bank Sta=5277.9,5284
XS Rating Curve= 0 ,0
Exp/Cntr=0.3,0.1

Type RM Length L Ch R = 1 ,1364    ,506,506,506
BEGIN DESCRIPTION:
Mapping XS a3d2d591
END DESCRIPTION:
XS GIS Cut Line= 4
      1521366.91      6834447.44      1521820.02       6833780.8
      1521971.06      6833426.63      1521507.53      6832463.11
#Sta/Elev= 30
  4093.5 1873.84  4206.7 1872.38  4221.7 1873.27  4344.4 1872.63  4350.4 1872.06
  4473.1 1872.73  4509.1  1872.1  4703.6 1872.19  4841.3 1871.39  4868.3 1870.12
  4877.2 1870.86  4913.5 1870.07    4951  1867.6  4980.1 1864.26  4986.5 1864.17
    4987 1863.67  4992.6 1864.17  5011.3 1865.97    5033 1865.53  5109.1 1866.48
  5141.8 1867.58  5310.4 1868.57  5326.3 1869.66  5333.1 1870.21  5371.8 1869.17
  5550.2 1870.74  5693.6 1872.03  5882.2 1872.14  6114.1 1873.24  6353.8 1874.48
#Mann= 7 ,-1 , 0
  4093.5    .045       0  4986.5    .035       0  4992.6    .045       0
  5326.3    .035       0  5550.2     .07       0  5882.2    .035       0
  6114.1     .07       0
Bank Sta=4986.5,4992.6
XS Rating Curve= 0 ,0
Exp/Cntr=0.3,0.1

Type RM Length L Ch R = 1 ,858     ,0,0,0
BEGIN DESCRIPTION:
Mapping XS 6e565f90
END DESCRIPTION:
XS GIS Cut Line= 4
      1521748.72      6834560.94      1522332.49      6833781.86
      1522308.62      6833415.11      1521534.84      6832654.75
#Sta/Elev= 30
  4034.7 1872.26  4199.1 1869.96  4413.3 1869.95  4555.4  1868.9  4584.6 1869.46
  4649.1 1868.59  4663.2 1869.35  4690.8  1868.6  4763.1 1868.87  4913.1 1867.47
  4926.3 1868.21  4940.8 1867.91  4949.2 1866.16    4960  1862.2  4960.5  1861.7
  4966.1  1862.2    4970 1863.86  4976.3  1864.3  5005.4 1863.71  5072.2 1864.74
  5142.4 1863.95  5232.6 1864.25  5362.8  1867.5    5578 1869.45  5692.7  1869.7
  5729.9 1870.27    5850  1869.5  6142.8  1871.8  6454.6  1873.9  6460.6 1874.04
#Mann= 7 ,-1 , 0
  4034.7    .045       0    4960    .035       0  4966.1    .045       0
    5578    .035       0  5692.7     .07       0  6142.8    .035       0
  6454.6     .07       0
Bank Sta=4960,4966.1
XS Rating Curve= 0 ,0
Exp/Cntr=0.3,0.1

Chan Stop Cuts=-1
Use User Specified Reach Order=0
Composite Channel Slope=5