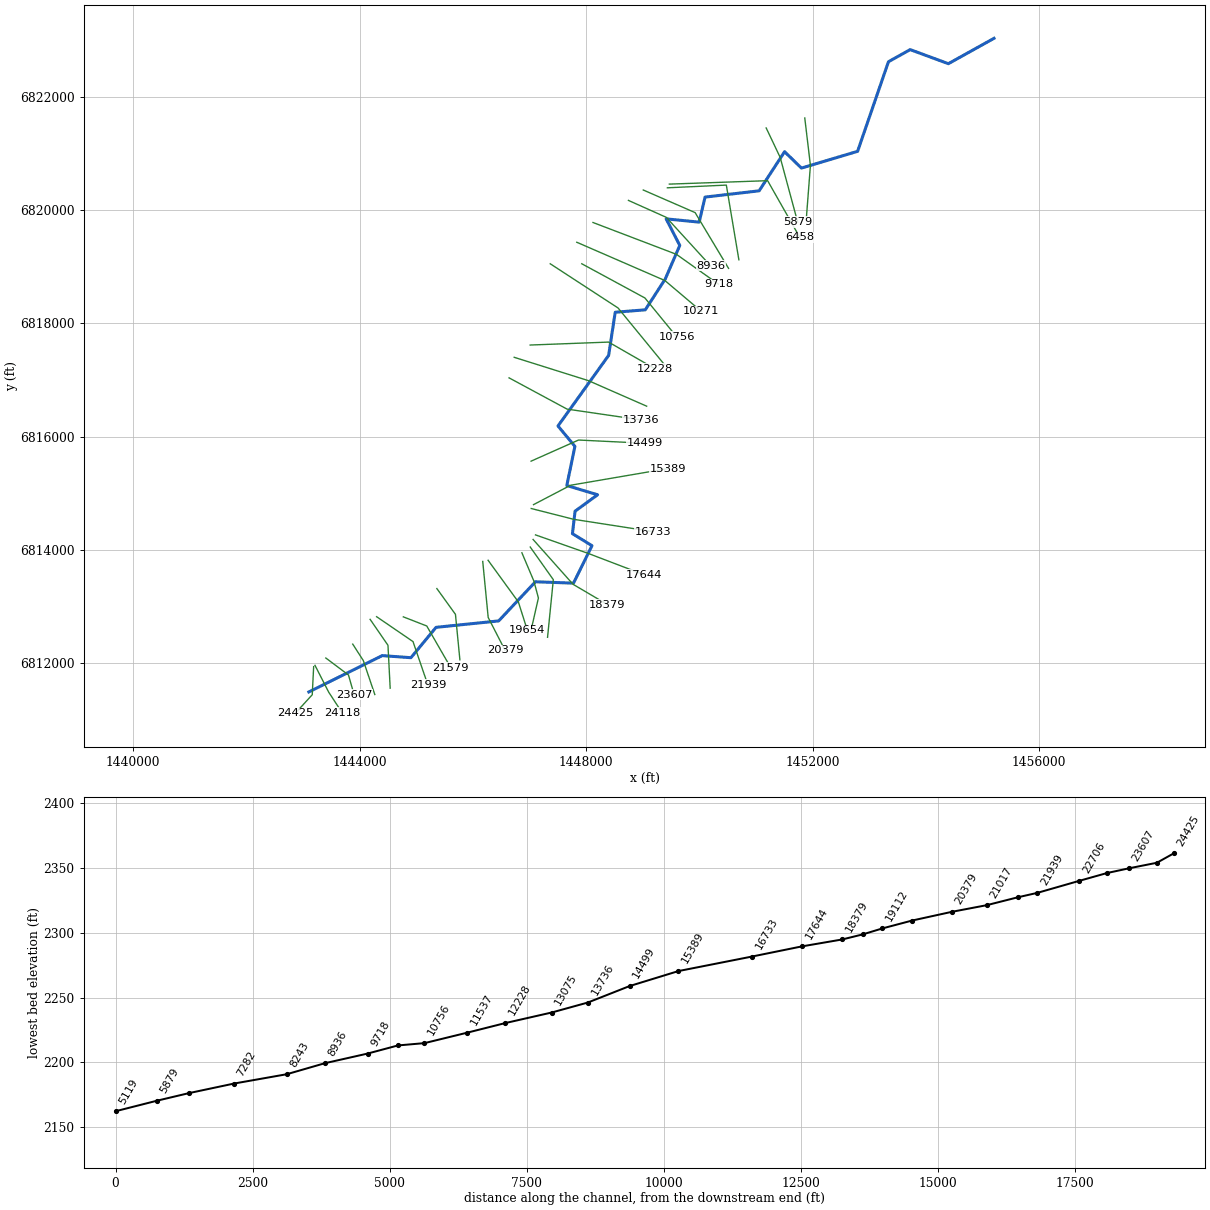
--- COFFEE HOLLOW.prj (project) ---

Proj Title=COFFEE HOLLOW Base Level Engineering
Current Plan=p01
Default Exp/Contr=0.3,0.1
English Units
Geom File=g01
Flow File=f01
Plan File=p01
Y Axis Title=Elevation
X Axis Title(PF)=Main Channel Distance
X Axis Title(XS)=Station
BEGIN DESCRIPTION:
COFFEE HOLLOW
END DESCRIPTION:
DSS Export Rating Curves= 0
DSS Export Rating Curve Sorted= 0
DSS Export Volume Flow Curves= 0
DXF OffsetX= 0
DXF OffsetY= 0
DXF ScaleX= 1
DXF ScaleY= 10

--- COFFEE HOLLOW.p01 (plan) ---

Plan Title=Multiple Run
Short Identifier=Multiple
Geom File=g01
Flow File=f01
Subcritical Flow
K Sum by GR= 0
Std Step Tol= 0.01
Critical Tol= 0.01
Num of Std Step Trials= 20
Max Error Tol= 0.3
Flow Tol Ratio= 0.001
Split Flow NTrial= 30
Split Flow Tol= 0.02
Split Flow Ratio= 0.02
Log Output Level= 0
Friction Slope Method= 1
Unsteady Friction Slope Method= 2
Unsteady Bridges Friction Slope Method= 1
Parabolic Critical Depth
Global Vel Dist=  1 , 1 , 1
Global Log Level= 0
CheckData=True
Encroach Param= -1, 0, 0, 0
BEGIN DESCRIPTION:
Multiple Run
END DESCRIPTION:

--- COFFEE HOLLOW.f01 (steady flow) ---

Flow Title=Multiple
Number of Profiles=7
Profile Names=10-year,25-year,50-year,1pct_min,100-year,1pct_plu,500-year
River Rch & RM= COFFEE HOLLOW,Reach-1,24425
     211     293     362     222     444     885     675
River Rch & RM= COFFEE HOLLOW,Reach-1,23607
     460     671     854     541    1079    2152    1742
River Rch & RM= COFFEE HOLLOW,Reach-1,22706
     536     787    1005     639    1274    2542    2072
River Rch & RM= COFFEE HOLLOW,Reach-1,18379
     727    1084    1399     897    1791    3573    2969
River Rch & RM= COFFEE HOLLOW,Reach-1,16733
     757    1129    1459     936    1867    3725    3098
River Rch & RM= COFFEE HOLLOW,Reach-1,13736
     881    1324    1720    1108    2211    4412    3702
River Rch & RM= COFFEE HOLLOW,Reach-1,11537
    1016    1535    2000    1292    2579    5145    4342
River Rch & RM= COFFEE HOLLOW,Reach-1,5879
    1063    1608    2096    1355    2703    5394    4555
Boundary for River Rch & Prof#=COFFEE HOLLOW,Reach-1,1
Up Type=0
Dn Type=3
Dn Slope=0.005
Boundary for River Rch & Prof#=COFFEE HOLLOW,Reach-1,2
Up Type=0
Dn Type=3
Dn Slope=0.005
Boundary for River Rch & Prof#=COFFEE HOLLOW,Reach-1,3
Up Type=0
Dn Type=3
Dn Slope=0.005
Boundary for River Rch & Prof#=COFFEE HOLLOW,Reach-1,4
Up Type=0
Dn Type=3
Dn Slope=0.005
Boundary for River Rch & Prof#=COFFEE HOLLOW,Reach-1,5
Up Type=0
Dn Type=3
Dn Slope=0.005
Boundary for River Rch & Prof#=COFFEE HOLLOW,Reach-1,6
Up Type=0
Dn Type=3
Dn Slope=0.005
Boundary for River Rch & Prof#=COFFEE HOLLOW,Reach-1,7
Up Type=0
Dn Type=3
Dn Slope=0.005

--- COFFEE HOLLOW.g01 (geometry) ---

Geom Title=Existing Conditions
Program Version=4.10

River Reach=COFFEE HOLLOW   ,Reach-1
Reach XY= 30
        1443105.        6811488.      1444401.58      6812130.21
      1444908.03      6812093.46      1445351.68      6812629.96
      1446457.71       6812743.4      1447106.39      6813434.97
      1447779.09      6813410.85      1448105.49      6814072.88
      1447759.97      6814285.42      1447806.97      6814682.35
      1448204.77      6814972.78      1447660.82      6815135.69
      1447803.95      6815827.57        1447505.        6816188.
      1448399.54      6817435.55      1448515.75      6818197.71
      1449047.15      6818240.93      1449399.53      6818785.55
      1449655.92      6819378.25      1449415.35      6819848.09
      1449999.15      6819790.04      1450102.32       6820232.7
      1451057.43      6820343.52      1451506.64      6821034.87
      1451804.66      6820745.21      1452796.54       6821041.5
      1453341.27      6822624.77      1453725.08      6822838.67
      1454399.32      6822589.97        1455205.        6823038.

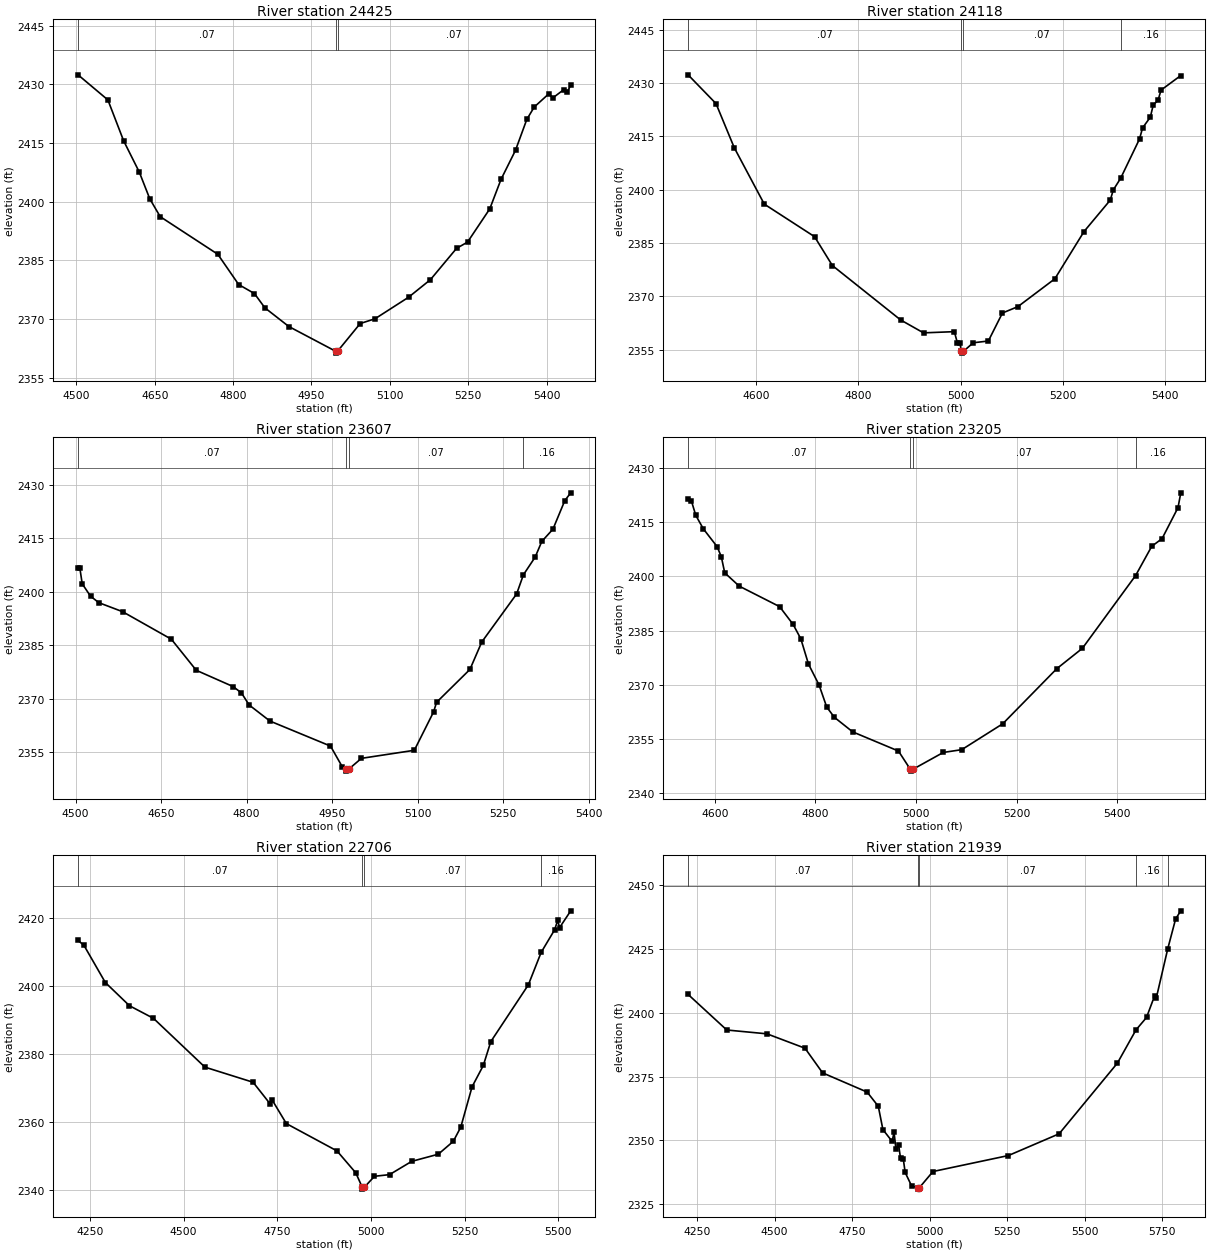
Type RM Length L Ch R = 1 ,24425   ,307,307,307
BEGIN DESCRIPTION:
COFFEE HOLLOW 46.0
END DESCRIPTION:
XS GIS Cut Line= 3
      1443190.06      6811935.05       1443165.4      6811438.96
      1442864.55      6811109.57
#Sta/Elev= 30
  4503.3 2432.46  4560.4 2426.04  4590.5 2415.59  4620.5 2407.58  4640.5 2400.76
  4660.5 2396.18  4770.7 2386.56  4810.7 2378.81  4840.8 2376.51  4860.8 2372.86
  4906.6 2368.08    4996 2361.77  4996.2 2361.27    5000 2361.77  5043.2 2368.84
  5071.6 2370.06  5135.7 2375.56  5177.6 2380.06  5227.6 2388.07  5248.6 2389.67
  5291.1 2398.16  5312.7 2405.72  5340.4 2413.16    5362 2421.05  5376.2 2424.22
  5404.6 2427.66  5411.4 2426.51    5433  2428.7  5439.7  2428.1  5446.1 2429.86
#Mann= 3 ,-1 , 0
  4503.3     .07       0    4996     .07       0    5000     .07       0
Bank Sta=4996,5000
XS Rating Curve= 0 ,0
Exp/Cntr=0.3,0.1

Type RM Length L Ch R = 1 ,24118   ,511,511,511
BEGIN DESCRIPTION:
Mapping XS d316596f
END DESCRIPTION:
XS GIS Cut Line= 3
       1443213.5      6811958.52      1443455.69      6811484.56
      1443692.55      6811122.76
#Sta/Elev= 30
  4466.6 2432.33  4521.3 2424.23    4557 2411.83  4615.8 2395.96  4714.2 2386.81
  4749.1 2378.69  4882.7 2363.39  4927.6 2359.75  4987.9 2360.09  4994.1 2356.83
  4998.9 2356.83  5001.7 2354.55    5002 2354.05  5005.7 2354.55  5024.8 2356.96
  5054.5 2357.46  5082.1 2365.34  5112.3 2367.12  5184.7 2374.95  5241.9 2388.26
  5293.2 2397.09  5299.2 2399.96  5313.5 2403.22  5350.5 2414.28  5356.5 2417.41
  5371.6  2420.4  5377.5 2423.91  5386.7 2425.12  5392.6 2428.03  5431.3 2432.13
#Mann= 4 ,-1 , 0
  4466.6     .07       0  5001.7     .07       0  5005.7     .07       0
  5313.5     .16       0
Bank Sta=5001.7,5005.7
XS Rating Curve= 0 ,0
Exp/Cntr=0.3,0.1

Type RM Length L Ch R = 1 ,23607   ,402,402,402
BEGIN DESCRIPTION:
COFFEE HOLLOW 45.0
END DESCRIPTION:
XS GIS Cut Line= 3
      1443404.99      6812088.01        1443805.        6811788.
        1443905.      6811438.02
#Sta/Elev= 30
  4504.4 2406.69  4507.5 2406.69  4511.7 2402.23  4526.3 2398.76  4540.9 2396.94
  4582.5 2394.42    4668 2386.71  4711.7    2378  4776.3 2373.44  4790.9 2371.67
  4804.4 2368.29  4840.9 2363.78  4947.1 2356.77    4968  2350.9  4973.8 2350.25
  4974.2 2349.75  4978.7 2350.25  5001.3 2353.33  5094.1 2355.59  5127.9 2366.35
  5133.1 2369.03  5191.6 2378.24  5212.4 2385.93  5273.5 2399.39  5285.4 2404.76
    5306 2409.71  5317.7 2414.12  5337.2 2417.54    5358 2425.55  5368.4 2427.72
#Mann= 4 ,-1 , 0
  4504.4     .07       0  4973.8     .07       0  4978.7     .07       0
  5285.4     .16       0
Bank Sta=4973.8,4978.7
XS Rating Curve= 0 ,0
Exp/Cntr=0.3,0.1

Type RM Length L Ch R = 1 ,23205   ,499,499,499
BEGIN DESCRIPTION:
Mapping XS aab76651
END DESCRIPTION:
XS GIS Cut Line= 3
      1443880.18       6812333.5      1444067.67      6812041.85
      1444269.95       6811442.8
#Sta/Elev= 30
  4547.1 2421.28  4553.6  2420.9  4562.4 2416.87  4577.4 2413.14  4604.7 2408.23
  4613.1 2405.44  4619.9 2400.97  4648.7 2397.29  4728.9 2391.62  4755.9 2386.67
  4771.1 2382.71  4786.3 2375.72  4807.4 2369.91  4822.6 2363.81  4837.8 2360.98
  4874.2 2356.95  4965.1 2351.65  4988.7 2346.59  4989.1 2346.09  4993.7 2346.59
  5054.2 2351.26  5090.9 2352.03  5172.3 2359.19  5279.7 2374.44  5330.6 2380.08
  5436.4 2400.23  5468.4 2408.31  5488.9 2410.43  5520.6 2419.02  5526.1 2423.11
#Mann= 4 ,-1 , 0
  4547.1     .07       0  4988.7     .07       0  4993.7     .07       0
  5436.4     .16       0
Bank Sta=4988.7,4993.7
XS Rating Curve= 0 ,0
Exp/Cntr=0.3,0.1

Type RM Length L Ch R = 1 ,22706   ,767,767,767
BEGIN DESCRIPTION:
Mapping XS 91bc8eb4
END DESCRIPTION:
XS GIS Cut Line= 3
      1444187.44      6812771.04      1444502.56      6812312.69
      1444541.62      6811554.92
#Sta/Elev= 30
  4218.5 2413.29  4234.3 2411.84  4291.3 2400.92  4355.7 2394.09  4419.8 2390.38
  4557.1 2376.03  4685.7 2371.58  4730.4 2365.33  4736.4  2366.4  4774.5 2359.42
  4909.6 2351.39  4959.7 2344.95  4977.2 2340.65  4977.5 2340.15  4982.2 2340.65
  5009.7 2343.93  5049.8 2344.41  5109.1 2348.32    5180 2350.42    5220  2354.2
    5240 2358.38  5270.1 2370.24  5300.1 2376.51  5320.1 2383.53  5420.3 2400.22
  5454.5 2409.77  5490.4 2416.41  5498.7 2419.19  5503.7 2417.06  5533.5    2422
#Mann= 4 ,-1 , 0
  4218.5     .07       0  4977.2     .07       0  4982.2     .07       0
  5454.5     .16       0
Bank Sta=4977.2,4982.2
XS Rating Curve= 0 ,0
Exp/Cntr=0.3,0.1

Type RM Length L Ch R = 1 ,21939   ,360,360,360
BEGIN DESCRIPTION:
Mapping XS cfae9a61
END DESCRIPTION:
XS GIS Cut Line= 3
      1444302.04       6812817.9      1444944.92      6812378.14
      1445207.12      6811612.28
#Sta/Elev= 30
  4221.1 2407.24  4345.8 2393.28  4475.4 2391.78    4598 2386.14  4654.8 2376.46
  4798.4 2368.92  4834.3 2363.35  4849.2  2354.2  4878.9 2349.58  4885.1 2353.16
  4891.1 2346.65    4900 2348.01    4906 2342.94  4914.9 2342.67  4920.9 2337.39
  4941.9 2332.06  4961.2 2331.35  4961.5 2330.85  4966.3 2331.35  5010.6 2337.76
  5253.8 2344.03  5417.3 2352.56  5605.1 2380.28  5665.1 2393.32    5699 2398.19
    5725 2406.66  5730.3 2405.71  5767.6  2425.2  5792.9 2436.87  5809.5 2440.04
#Mann= 5 ,-1 , 0
  4221.1     .07       0  4961.2     .07       0  4966.3     .07       0
  5665.1     .16       0  5767.6     .07       0
Bank Sta=4961.2,4966.3
XS Rating Curve= 0 ,0
Exp/Cntr=0.3,0.1

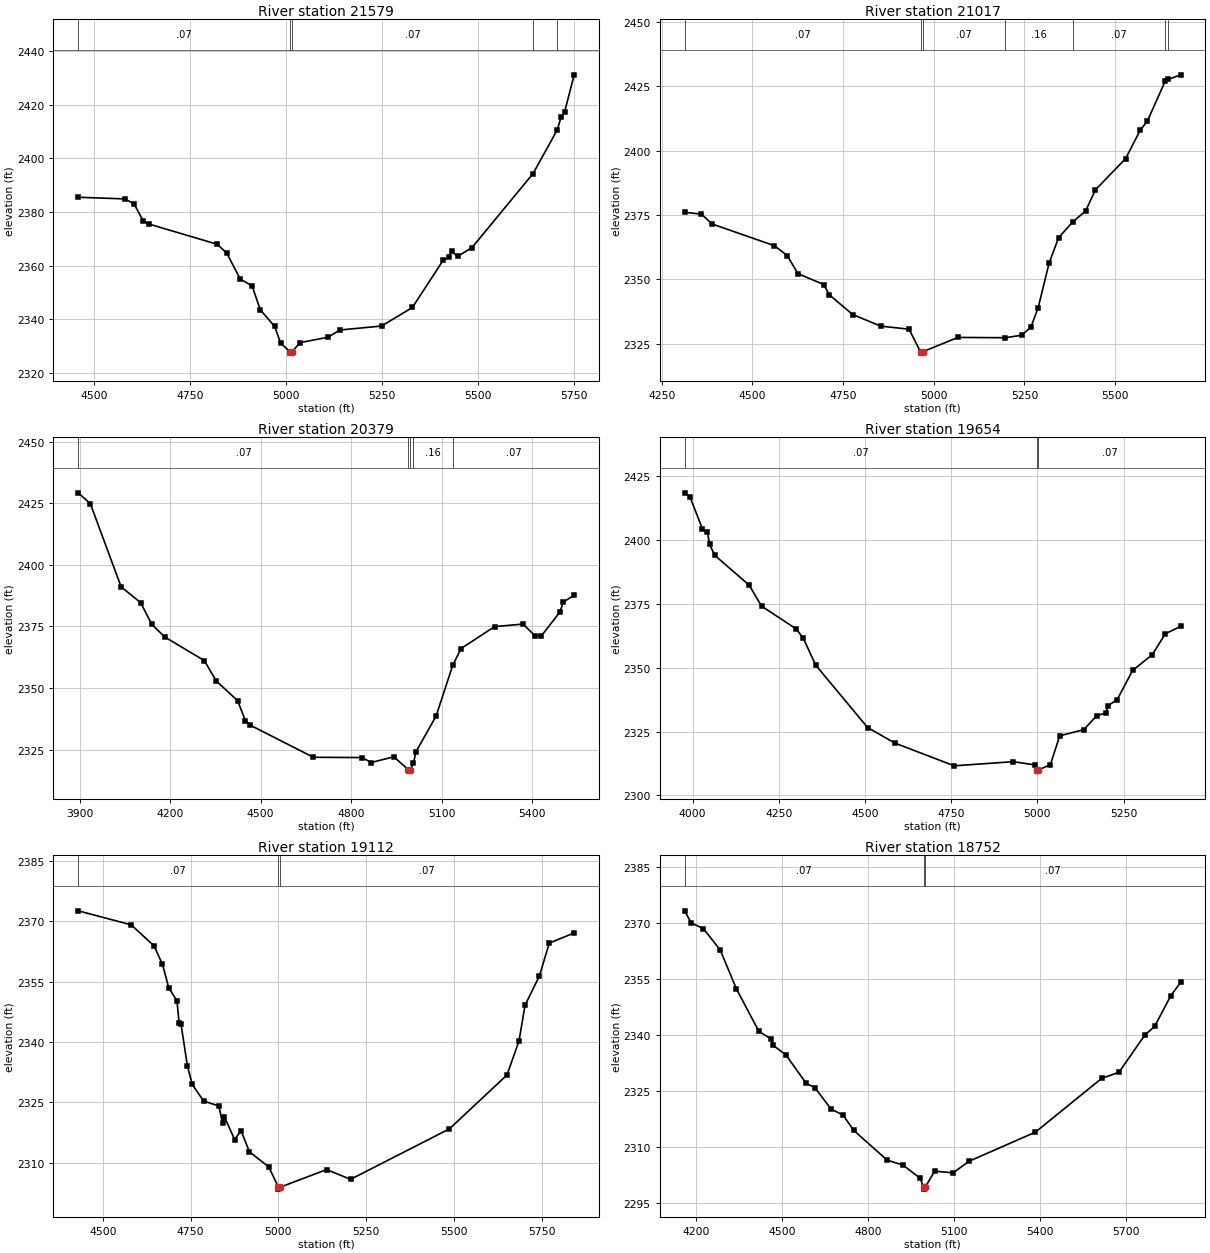
Type RM Length L Ch R = 1 ,21579   ,562,562,562
BEGIN DESCRIPTION:
Mapping XS 9785e5c7
END DESCRIPTION:
XS GIS Cut Line= 3
       1444773.4      6812815.29      1445187.46      6812653.83
      1445610.99      6811918.51
#Sta/Elev= 30
    4458 2385.52  4578.8 2384.91  4603.3 2383.15  4627.8 2376.59  4642.2 2375.54
  4820.7 2367.97  4845.2 2364.69  4880.4 2355.03  4911.2 2352.48  4932.8 2343.52
  4970.1 2337.36  4985.9 2331.08  5010.6 2327.89    5011 2327.39  5015.8 2327.89
  5036.1  2331.3  5109.5 2333.33    5140 2336.01  5248.9  2337.5  5329.3 2344.42
  5409.8  2362.1  5425.6 2363.15  5431.3 2365.41  5447.1 2363.47  5484.5 2366.72
    5644 2394.38    5707 2410.67    5717 2415.47  5725.9  2417.2    5751 2431.18
#Mann= 5 ,-1 , 0
    4458     .07       0  5010.6     .07       0  5015.8     .07       0
    5644     .16       0    5707     .07       0
Bank Sta=5010.6,5015.8
XS Rating Curve= 0 ,0
Exp/Cntr=0.3,0.1

Type RM Length L Ch R = 1 ,21017   ,638,638,638
BEGIN DESCRIPTION:
Mapping XS 4a3f10e7
END DESCRIPTION:
XS GIS Cut Line= 3
      1445366.27      6813314.86       1445694.4      6812859.13
      1445772.53        6812057.
#Sta/Elev= 30
  4313.2 2376.08  4359.3 2375.38  4388.7 2371.56  4560.6 2363.11  4596.2 2359.23
  4625.6 2352.23  4696.8 2348.02  4711.5 2344.09  4776.5 2336.35  4853.9 2331.85
  4931.8 2330.66  4963.6 2321.86    4964 2321.36  4969.1 2321.86  5066.8 2327.46
  5197.2 2327.35  5242.3  2328.3  5267.8 2331.45  5287.8 2338.96    5318 2356.31
  5344.1 2366.19  5383.2 2372.39  5418.5 2376.55  5445.9 2384.84    5529 2396.96
  5569.2 2407.96  5589.3 2411.61  5638.2 2427.09  5646.1 2427.71  5680.7 2429.52
#Mann= 7 ,-1 , 0
  4313.2     .07       0  4963.6     .07       0  4969.1     .07       0
  5197.2     .16       0  5383.2     .07       0  5638.2     .16       0
  5646.1     .07       0
Bank Sta=4963.6,4969.1
XS Rating Curve= 0 ,0
Exp/Cntr=0.3,0.1

Type RM Length L Ch R = 1 ,20379   ,725,725,725
BEGIN DESCRIPTION:
Mapping XS 98578e61
END DESCRIPTION:
XS GIS Cut Line= 3
      1446176.17      6813794.03      1446272.53      6812804.44
      1446569.42      6812226.28
#Sta/Elev= 30
  3895.3 2429.23  3935.6  2424.8  4037.5 2391.07  4102.3 2384.63  4139.3 2375.78
  4182.7 2370.66  4313.3 2361.11  4353.5 2352.77  4423.8 2344.83  4449.8 2336.64
    4464 2334.98    4675 2321.84  4835.8 2321.73  4867.2 2319.72  4941.8 2322.05
  4990.1 2316.72  4990.6 2316.22  4995.7 2316.72  5006.7 2319.38  5015.1 2324.09
  5081.7 2338.56    5137 2359.23  5164.8 2366.01  5275.7  2374.9  5370.1 2375.94
  5408.9 2371.29    5431 2371.18    5492 2380.77  5503.8 2384.91  5539.5 2387.65
#Mann= 5 ,-1 , 0
  3895.3     .07       0  4990.1     .07       0  4995.7     .07       0
  5006.7     .16       0    5137     .07       0
Bank Sta=4990.1,4995.7
XS Rating Curve= 0 ,0
Exp/Cntr=0.3,0.1

Type RM Length L Ch R = 1 ,19654   ,542,542,542
BEGIN DESCRIPTION:
Mapping XS b5f72459
END DESCRIPTION:
XS GIS Cut Line= 3
      1446270.49      6813815.17      1446805.23      6813079.03
      1446964.96      6812575.52
#Sta/Elev= 30
  3977.2 2418.47  3992.8 2416.83  4028.4 2404.41  4043.1  2403.1  4049.2 2398.42
  4063.9 2394.06  4164.4 2382.29    4200 2374.11  4300.4 2365.19  4321.3 2361.51
  4356.9 2351.04  4507.6 2326.57  4587.2 2320.44  4758.8 2311.57  4930.1 2313.19
  4993.1 2311.92  4997.4 2309.99  4997.8 2309.49    5003 2309.99  5037.7 2312.01
  5064.7 2323.32  5134.5 2325.73    5172 2331.22    5199  2332.3  5204.3 2335.06
  5231.3 2337.49  5276.3 2348.96  5333.4 2355.11  5370.9 2363.31  5415.3 2366.15
#Mann= 3 ,-1 , 0
  3977.2     .07       0  4997.4     .07       0    5003     .07       0
Bank Sta=4997.4,5003
XS Rating Curve= 0 ,0
Exp/Cntr=0.3,0.1

Type RM Length L Ch R = 1 ,19112   ,360,360,360
BEGIN DESCRIPTION:
Mapping XS e04a92ce
END DESCRIPTION:
XS GIS Cut Line= 4
      1446867.71      6813947.14      1447079.53      6813447.09
      1447159.39      6813148.48      1447034.76      6812601.46
#Sta/Elev= 30
  4429.7 2372.56  4580.8 2369.08    4646 2363.83  4669.7 2359.28    4688 2353.37
  4711.1 2350.22  4717.1  2344.8  4722.5 2344.51  4740.8 2334.06  4754.6 2329.44
  4787.1  2325.3  4830.6 2324.09  4840.9 2319.74  4846.3 2321.39  4875.4 2315.74
  4893.7 2317.99  4917.4 2312.72  4972.8 2308.93    5000 2303.93  5000.4 2303.43
  5005.8 2303.93  5137.4 2308.28  5205.8 2305.86  5487.5  2318.4  5651.6 2331.79
  5685.9  2340.3  5702.9 2349.09  5743.9 2356.37  5771.9 2364.54  5842.9 2367.07
#Mann= 3 ,-1 , 0
  4429.7     .07       0    5000     .07       0  5005.8     .07       0
Bank Sta=5000,5005.8
XS Rating Curve= 0 ,0
Exp/Cntr=0.3,0.1

Type RM Length L Ch R = 1 ,18752   ,373,373,373
BEGIN DESCRIPTION:
Mapping XS c5d92ce1
END DESCRIPTION:
XS GIS Cut Line= 3
      1447014.84      6814049.18      1447422.82      6813471.93
      1447320.82       6812454.1
#Sta/Elev= 30
  4161.2 2373.36  4184.2 2370.09  4226.1 2368.62  4285.1 2362.87  4341.8 2352.43
  4419.8 2341.09  4463.7 2338.98  4469.8 2337.33  4514.2 2334.76  4585.5  2327.1
  4615.1 2326.02  4671.7 2320.25  4713.7 2318.63  4750.4 2314.57  4867.4 2306.57
  4922.3 2305.24  4982.6 2301.73  4994.3  2299.3  4994.7  2298.8  5000.1  2299.3
  5032.8  2303.6  5097.6 2303.18  5153.4 2306.28  5384.6 2314.07  5615.7 2328.48
    5676 2330.11  5766.5 2340.11  5800.3 2342.38  5856.9 2350.65    5891 2354.17
#Mann= 3 ,-1 , 0
  4161.2     .07       0  4994.3     .07       0  5000.1     .07       0
Bank Sta=4994.3,5000.1
XS Rating Curve= 0 ,0
Exp/Cntr=0.3,0.1

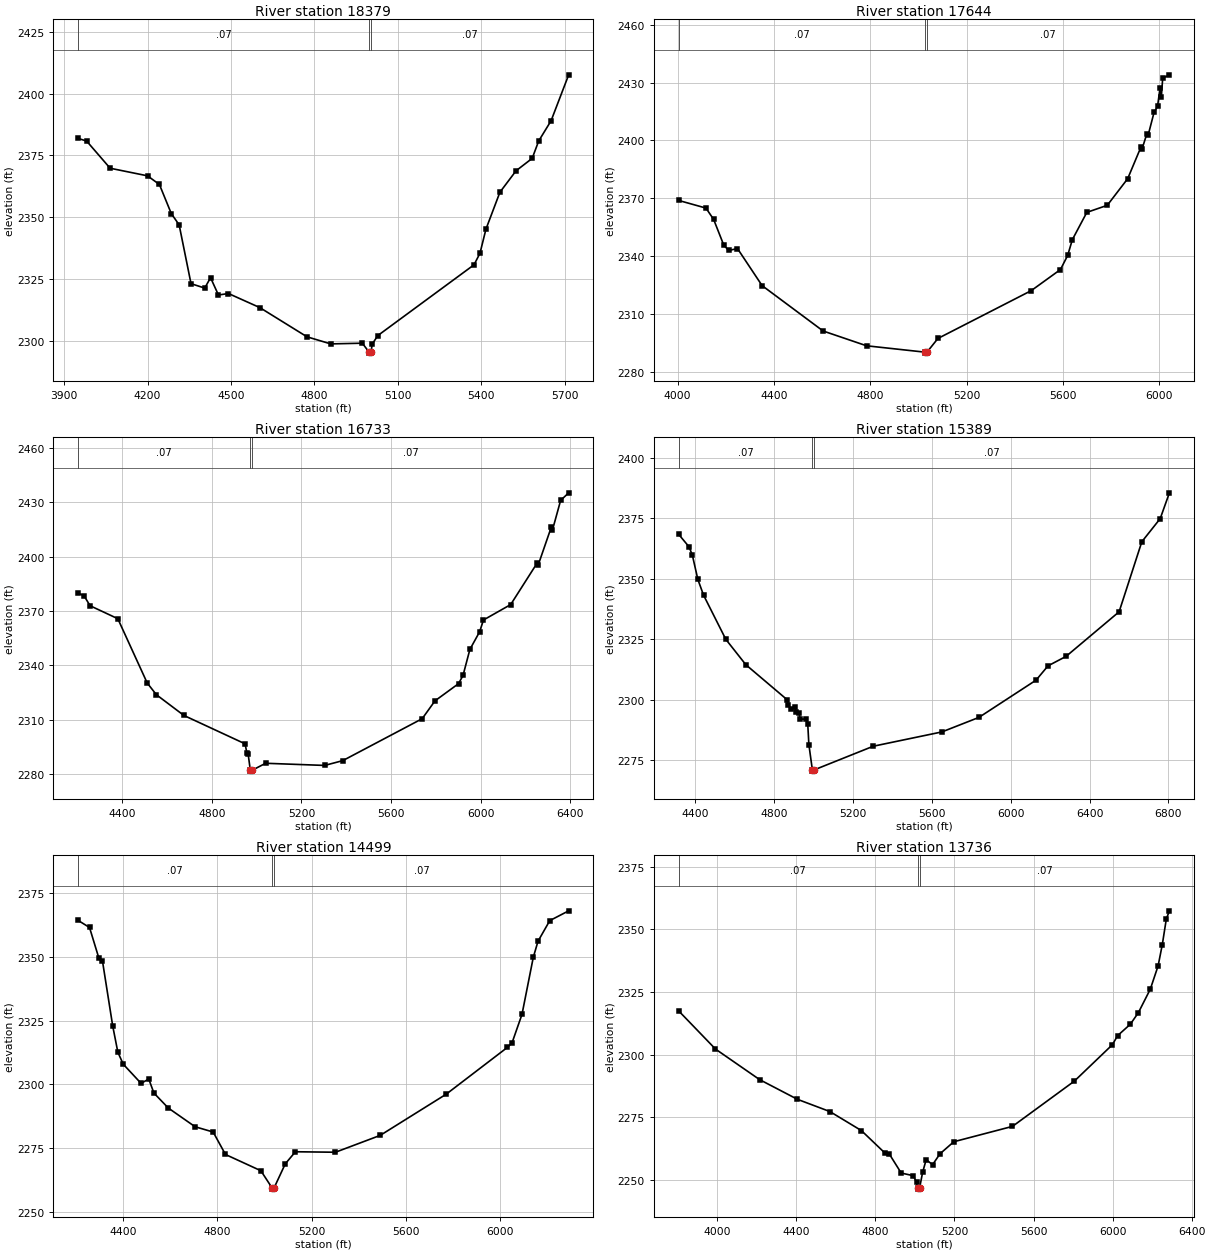
Type RM Length L Ch R = 1 ,18379   ,735,735,735
BEGIN DESCRIPTION:
Mapping XS 1e61fa4b
END DESCRIPTION:
XS GIS Cut Line= 3
      1447065.65      6814182.32       1447770.5      6813390.67
       1448378.1      6813033.05
#Sta/Elev= 30
  3949.7 2381.84  3980.9 2380.75  4065.4 2369.75    4200 2366.67  4242.7 2363.17
  4285.3 2351.42  4313.7 2346.81  4356.4 2323.01  4405.7 2321.24  4426.6 2325.44
    4455 2318.43    4491 2319.03  4603.9 2313.33  4773.6  2301.5  4858.9 2298.64
  4972.6 2298.92  4996.1  2295.4  4996.6  2294.9  5004.3  2295.4  5007.7  2298.5
  5028.5 2302.03  5374.2 2330.65  5395.7 2335.34  5417.1 2345.07  5467.4 2360.04
  5525.4 2368.71  5583.5 2373.75  5606.7 2380.75  5651.5 2388.99  5714.7 2407.56
#Mann= 3 ,-1 , 0
  3949.7     .07       0  4996.1     .07       0  5004.3     .07       0
Bank Sta=4996.1,5004.3
XS Rating Curve= 0 ,0
Exp/Cntr=0.3,0.1

Type RM Length L Ch R = 1 ,17644   ,911,911,911
BEGIN DESCRIPTION:
Mapping XS f57f35df
END DESCRIPTION:
XS GIS Cut Line= 3
      1447108.15      6814263.51      1448045.68      6813933.64
      1449021.08      6813560.81
#Sta/Elev= 30
  4004.5 2368.86  4117.8 2364.89  4149.6 2359.03    4192 2345.57  4212.4 2342.88
  4248.7 2343.87    4351 2324.62  4604.4 2301.05  4784.9 2293.37  5027.5 2290.06
    5028 2289.56  5035.7 2290.06  5081.1 2297.17  5468.7 2322.01  5590.1 2332.97
  5620.1  2340.3  5639.5  2348.5  5699.6 2362.66  5784.5 2366.33  5869.3 2380.15
  5924.1 2396.51  5929.4 2395.69  5948.8 2403.49  5954.1 2402.66  5978.8 2414.57
  5993.3 2417.68  6003.5 2427.05  6008.9 2422.34  6014.7 2432.29  6042.6  2434.1
#Mann= 3 ,-1 , 0
  4004.5     .07       0  5027.5     .07       0  5035.7     .07       0
Bank Sta=5027.5,5035.7
XS Rating Curve= 0 ,0
Exp/Cntr=0.3,0.1

Type RM Length L Ch R = 1 ,16733   ,1344,1344,1344
BEGIN DESCRIPTION:
Mapping XS 59717c3a
END DESCRIPTION:
XS GIS Cut Line= 3
      1447032.67      6814729.64      1447783.52      6814538.67
      1449180.52      6814321.75
#Sta/Elev= 30
  4203.5 2379.94  4231.1 2378.28  4257.5 2372.88  4381.3 2365.73  4512.4 2330.28
  4553.3 2323.84    4676 2312.41  4948.8 2296.77  4957.3 2291.49  4962.5 2291.16
  4972.2 2282.22  4972.7 2281.72  4980.6 2282.22  5040.5 2286.05  5303.6 2284.86
  5384.5  2287.5  5738.7 2310.62  5795.8 2320.46  5900.7 2329.92  5920.9 2334.48
  5951.3 2348.77  5994.8 2358.51    6012 2365.02  6133.4 2373.52  6251.6 2396.45
  6256.7 2395.54  6314.6 2416.26  6319.6 2414.57  6356.1 2430.93    6392 2435.11
#Mann= 3 ,-1 , 0
  4203.5     .07       0  4972.2     .07       0  4980.6     .07       0
Bank Sta=4972.2,4980.6
XS Rating Curve= 0 ,0
Exp/Cntr=0.3,0.1

Type RM Length L Ch R = 1 ,15389   ,890,890,890
BEGIN DESCRIPTION:
Mapping XS 9349168e
END DESCRIPTION:
XS GIS Cut Line= 3
      1447073.41       6814798.2      1447728.84       6815141.1
      1449450.95      6815436.07
#Sta/Elev= 30
  4317.7 2368.35  4370.7 2363.14  4387.2 2359.66  4414.9 2349.71  4443.6 2343.25
  4556.5 2324.97  4658.1 2314.47  4867.1 2300.02  4872.7  2297.7  4889.2    2296
  4905.6 2297.08  4911.2 2294.87  4927.7 2294.44  4933.3 2292.04  4962.8 2291.97
  4971.8 2289.93  4977.5 2281.48  4995.2    2271  4995.7  2270.5  5003.9    2271
  5303.8 2280.79  5652.1 2286.71  5839.2  2292.7  6128.9  2308.1  6189.4    2314
  6281.1 2317.93  6549.7 2336.35  6664.8 2365.29    6758 2374.86  6804.6 2385.51
#Mann= 3 ,-1 , 0
  4317.7     .07       0  4995.2     .07       0  5003.9     .07       0
Bank Sta=4995.2,5003.9
XS Rating Curve= 0 ,0
Exp/Cntr=0.3,0.1

Type RM Length L Ch R = 1 ,14499   ,763,763,763
BEGIN DESCRIPTION:
Mapping XS b83b08bf
END DESCRIPTION:
XS GIS Cut Line= 3
      1447030.05      6815566.45      1447867.73      6815939.71
      1449035.29      6815883.29
#Sta/Elev= 30
  4207.2 2364.25  4256.4 2361.43  4295.9 2349.49  4311.1 2348.48  4354.9 2322.89
  4376.8 2312.58  4399.7 2307.89  4475.4 2300.39  4508.2 2302.07  4530.1 2296.59
  4591.1 2290.73  4705.3 2283.38  4781.9 2281.32  4834.3 2272.52  4984.7 2266.16
  5032.2 2259.45  5032.7 2258.95    5041 2259.45  5088.6 2268.87  5131.6 2273.59
  5301.8  2273.4    5492    2280  5772.3 2296.12  6032.6 2314.46  6052.6 2316.29
  6094.8 2327.42  6142.7 2349.72  6162.8 2356.04  6212.8 2364.12  6293.2 2367.96
#Mann= 3 ,-1 , 0
  4207.2     .07       0  5032.2     .07       0    5041     .07       0
Bank Sta=5032.2,5041
XS Rating Curve= 0 ,0
Exp/Cntr=0.3,0.1

Type RM Length L Ch R = 1 ,13736   ,661,661,661
BEGIN DESCRIPTION:
Mapping XS 149d7241
END DESCRIPTION:
XS GIS Cut Line= 3
      1446641.18       6817038.3       1447665.5      6816486.21
      1448970.48      6816295.32
#Sta/Elev= 30
  3804.9 2317.43    3991 2302.19  4214.5 2289.97  4405.9  2282.1  4569.8 2277.22
  4729.4 2269.61  4848.8  2260.6  4870.7 2260.22  4930.7 2252.65    4992  2251.6
  5008.4  2248.9  5013.4 2246.73  5013.9 2246.23  5023.7 2246.73  5038.8 2252.88
  5056.9 2258.01  5089.3 2255.99  5126.8 2260.34  5196.7 2265.16  5493.6  2271.3
  5806.9  2289.4  5998.9 2303.92  6025.6 2307.56  6089.8 2312.11  6130.3 2316.71
  6190.9 2326.14  6230.3 2335.44  6251.5 2343.95  6271.8 2354.14  6287.4 2357.41
#Mann= 3 ,-1 , 0
  3804.9     .07       0  5013.4     .07       0  5023.7     .07       0
Bank Sta=5013.4,5023.7
XS Rating Curve= 0 ,0
Exp/Cntr=0.3,0.1

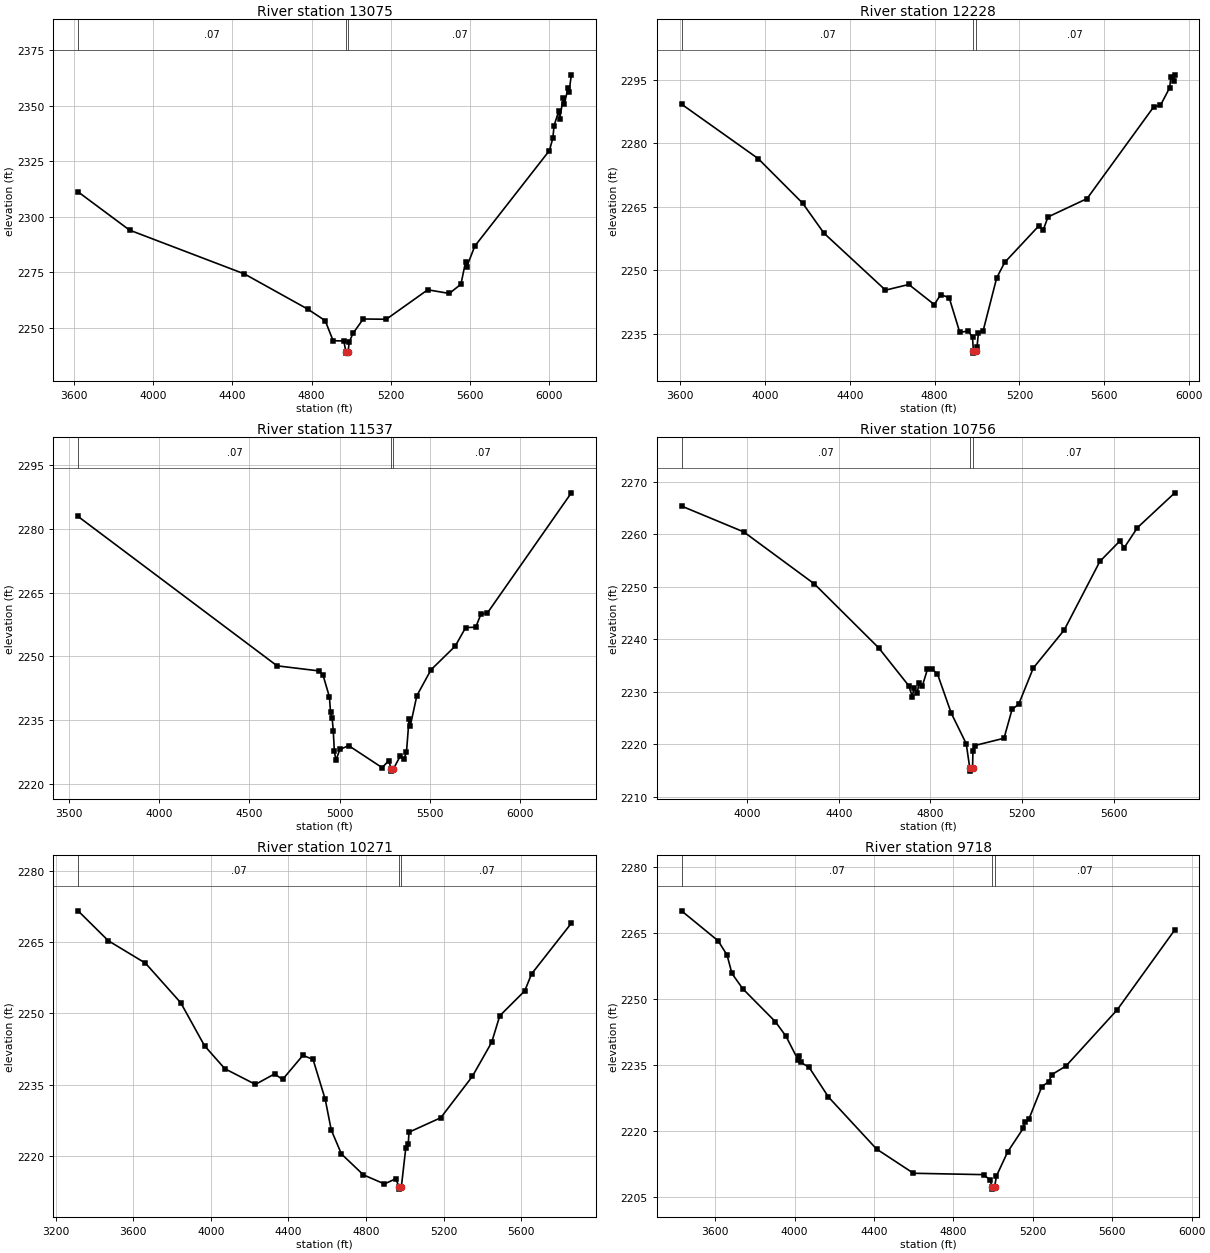
Type RM Length L Ch R = 1 ,13075   ,847,847,847
BEGIN DESCRIPTION:
Mapping XS b4def909
END DESCRIPTION:
XS GIS Cut Line= 3
      1446732.08      6817401.42      1448042.81       6816989.1
      1449070.74      6816538.03
#Sta/Elev= 30
  3618.6 2311.16  3879.2 2293.93  4460.3  2274.2  4779.9  2258.4  4869.2 2253.16
  4909.4 2244.11  4963.5 2243.99  4974.2 2239.02  4974.7 2238.52  4984.7 2239.02
  4991.2 2243.54  5009.6 2247.38  5061.8  2253.9  5178.6 2253.78  5388.2 2267.05
  5497.4  2265.4  5556.4 2269.57  5579.8 2279.74  5585.2  2277.3  5626.5 2286.74
  6004.2 2329.78  6021.6 2335.43  6027.6 2340.99    6051 2347.47  6056.4 2344.18
  6074.3 2353.61  6079.8 2350.71  6097.7  2357.8  6103.2 2356.25  6115.2 2363.88
#Mann= 3 ,-1 , 0
  3618.6     .07       0  4974.2     .07       0  4984.7     .07       0
Bank Sta=4974.2,4984.7
XS Rating Curve= 0 ,0
Exp/Cntr=0.3,0.1

Type RM Length L Ch R = 1 ,12228   ,691,691,691
BEGIN DESCRIPTION:
Mapping XS 6042062e
END DESCRIPTION:
XS GIS Cut Line= 3
      1447014.13      6817618.44      1448398.72      6817670.53
      1449213.65      6817202.37
#Sta/Elev= 30
  3606.9 2289.31    3968 2276.43  4178.2 2265.85  4278.2 2258.78  4568.5 2245.28
  4678.5 2246.62  4798.6 2241.86  4828.6 2244.22  4868.7 2243.49  4918.7 2235.28
  4958.7  2235.6  4978.7 2234.12  4982.8 2230.87  4983.3 2230.37  4993.4 2230.87
  4999.7 2231.72  5006.5 2235.09  5028.1 2235.52  5092.8  2248.2  5130.2 2251.83
  5291.2 2260.49  5312.8 2259.62  5334.4  2262.6  5518.7 2266.95  5833.2 2288.69
  5864.7 2289.03    5908 2293.18  5913.8  2295.7  5929.6 2294.71  5932.3 2296.25
#Mann= 3 ,-1 , 0
  3606.9     .07       0  4982.8     .07       0  4993.4     .07       0
Bank Sta=4982.8,4993.4
XS Rating Curve= 0 ,0
Exp/Cntr=0.3,0.1

Type RM Length L Ch R = 1 ,11537   ,781,781,781
BEGIN DESCRIPTION:
Mapping XS 212cc0fa
END DESCRIPTION:
XS GIS Cut Line= 3
      1447367.93      6819054.55      1448565.82      6818273.32
      1449388.73      6817268.12
#Sta/Elev= 30
    3553 2282.91    4654 2247.77  4886.4 2246.57  4907.5 2245.69  4943.7 2240.44
  4949.7 2236.83  4958.3 2235.59  4964.8 2232.55  4970.8 2227.69  4979.6 2225.53
    5001  2228.1  5050.5 2228.99  5235.5 2223.81  5270.9 2225.45  5285.8  2223.5
  5286.3    2223  5297.5  2223.5  5334.7 2226.49  5355.6 2225.82  5369.9  2227.5
  5384.3 2235.31  5390.7 2233.59  5427.3 2240.75  5505.6 2246.84  5639.8 2252.42
  5697.2 2256.77  5753.2 2256.86  5781.9 2259.95  5817.1 2260.17  6282.2 2288.47
#Mann= 3 ,-1 , 0
    3553     .07       0  5285.8     .07       0  5297.5     .07       0
Bank Sta=5285.8,5297.5
XS Rating Curve= 0 ,0
Exp/Cntr=0.3,0.1

Type RM Length L Ch R = 1 ,10756   ,485,485,485
BEGIN DESCRIPTION:
Mapping XS baad9bc8
END DESCRIPTION:
XS GIS Cut Line= 3
      1447925.15      6819054.59      1449039.77       6818450.4
      1449601.11      6817764.33
#Sta/Elev= 30
  3713.1 2265.35  3984.7 2260.44    4293 2250.55  4574.3 2238.37  4705.5 2231.17
  4721.6 2229.03  4727.3  2230.7  4743.5  2229.8  4749.2 2231.71  4765.4 2231.21
  4787.2 2234.31  4809.1 2234.29    4831  2233.4  4890.9 2225.97  4956.5 2220.14
  4972.3 2215.42  4972.8 2214.92  4984.1 2215.42  4985.9 2218.82  4993.8 2219.79
  5121.6 2221.18  5156.7 2226.67  5185.5 2227.63  5249.3 2234.53  5384.6 2241.78
  5540.1 2254.82  5626.2 2258.65    5647 2257.46  5704.4 2261.25  5867.4 2267.87
#Mann= 3 ,-1 , 0
  3713.1     .07       0  4972.3     .07       0  4984.1     .07       0
Bank Sta=4972.3,4984.1
XS Rating Curve= 0 ,0
Exp/Cntr=0.3,0.1

Type RM Length L Ch R = 1 ,10271   ,553,553,553
BEGIN DESCRIPTION:
Mapping XS 33a02ecb
END DESCRIPTION:
XS GIS Cut Line= 3
      1447836.65      6819434.78      1449393.94       6818757.7
      1450038.49      6818211.91
#Sta/Elev= 30
    3316 2271.54  3471.6 2265.27  3663.1 2260.56  3845.1 2252.25  3967.8 2243.22
  4072.5  2238.4  4230.2 2235.11  4328.7 2237.31  4370.1 2236.14  4474.8 2241.21
  4527.2 2240.35    4590 2231.96  4620.9 2225.55  4673.3 2220.52  4786.3 2216.13
  4895.2 2214.22    4953  2215.3  4970.4 2213.63  4970.9 2213.13  4982.4 2213.63
  5005.3 2221.83  5017.7 2222.52  5021.7 2225.08  5185.4 2228.11    5348 2236.77
  5447.9 2243.94  5489.7 2249.52  5618.3 2254.73  5653.4 2258.29  5858.7 2268.94
#Mann= 3 ,-1 , 0
    3316     .07       0  4970.4     .07       0  4982.4     .07       0
Bank Sta=4970.4,4982.4
XS Rating Curve= 0 ,0
Exp/Cntr=0.3,0.1

Type RM Length L Ch R = 1 ,9718    ,782,782,782
BEGIN DESCRIPTION:
Mapping XS ab7974c2
END DESCRIPTION:
XS GIS Cut Line= 3
      1448123.14      6819783.72      1449597.07      6819221.24
      1450336.66      6818695.19
#Sta/Elev= 30
  3429.9 2270.04  3613.9 2263.25  3659.2 2260.03  3683.9 2255.82  3738.7 2252.34
  3902.8 2244.87  3956.4 2241.56  4018.1 2236.11  4023.4 2237.06  4031.3 2235.63
  4072.9  2234.5  4170.4 2227.76  4412.4 2215.97  4598.6 2210.46  4951.8 2210.15
  4983.9 2208.96  4995.3 2207.36  4995.8 2206.86  5007.3 2207.36  5016.4 2209.82
    5073  2215.3  5152.2 2220.71  5159.1 2222.17    5180 2222.75  5245.1 2230.12
  5280.8 2231.29  5295.6 2232.86  5366.9 2234.81  5625.1 2247.58  5915.1 2265.72
#Mann= 3 ,-1 , 0
  3429.9     .07       0  4995.3     .07       0  5007.3     .07       0
Bank Sta=4995.3,5007.3
XS Rating Curve= 0 ,0
Exp/Cntr=0.3,0.1

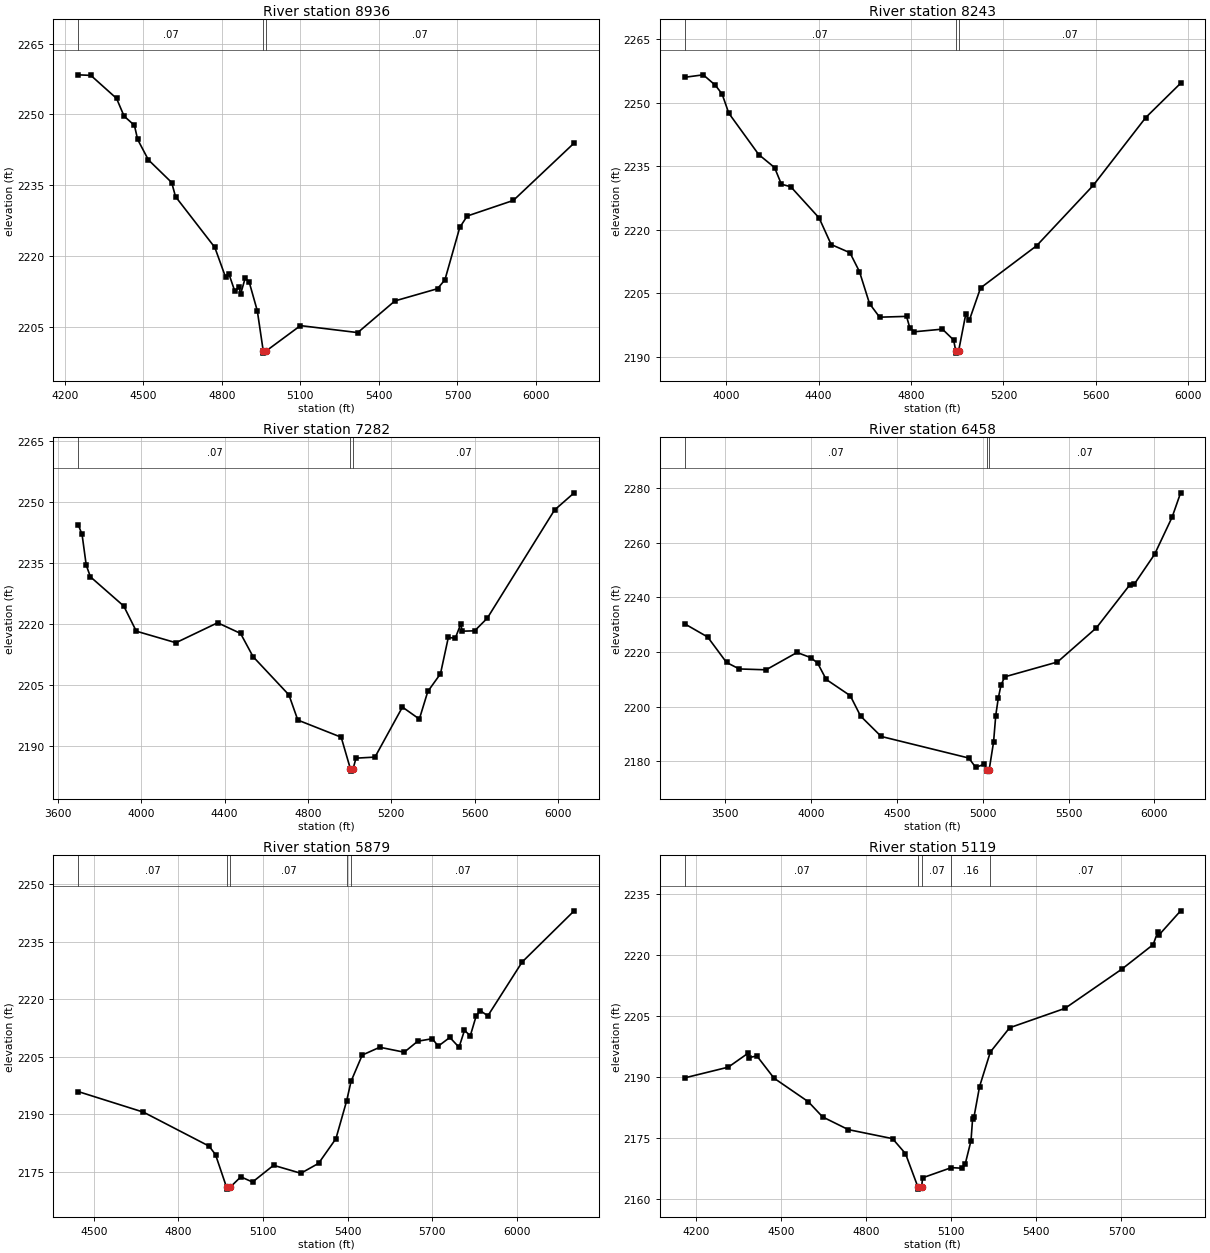
Type RM Length L Ch R = 1 ,8936    ,693,693,693
BEGIN DESCRIPTION:
Mapping XS e20c5f0e
END DESCRIPTION:
XS GIS Cut Line= 3
      1448749.04      6820174.11      1449418.29      6819874.64
      1450201.09      6819016.41
#Sta/Elev= 30
    4251 2258.37  4299.3 2258.25  4397.5 2253.37  4426.2 2249.62  4465.7 2247.67
  4478.1 2244.67    4519 2240.36  4608.1 2235.55  4622.7 2232.57  4772.9  2221.8
  4813.8 2215.52  4827.2 2216.11  4849.1 2212.55  4865.7 2213.39  4871.1 2211.85
  4888.9 2215.28  4903.9 2214.53  4935.3 2208.36  4957.8  2199.9  4958.3  2199.4
    4970  2199.9  5100.1 2205.23    5319 2203.75  5460.9 2210.46  5623.7 2213.05
  5652.1 2214.94  5708.8 2226.04  5737.2 2228.45  5913.6 2231.76  6145.8 2243.92
#Mann= 3 ,-1 , 0
    4251     .07       0  4957.8     .07       0    4970     .07       0
Bank Sta=4957.8,4970
XS Rating Curve= 0 ,0
Exp/Cntr=0.3,0.1

Type RM Length L Ch R = 1 ,8243    ,961,961,961
BEGIN DESCRIPTION:
Mapping XS b0d30c74
END DESCRIPTION:
XS GIS Cut Line= 3
      1449011.23      6820357.75      1449926.99      6819958.45
      1450517.29      6818973.18
#Sta/Elev= 30
  3819.7 2256.01  3900.2 2256.59    3953 2254.11  3981.8 2252.05  4010.7 2247.54
  4140.2 2237.79    4209 2234.71  4238.4 2230.79  4279.2 2230.18  4401.8 2222.83
  4454.1 2216.55  4535.3 2214.62  4576.6 2210.16  4620.2 2202.61  4663.8 2199.41
  4780.4  2199.6  4794.7 2196.89  4814.9 2195.97  4935.7 2196.59  4984.3 2194.03
  4993.7 2191.43  4994.2 2190.93  5005.9 2191.43  5036.8 2200.09  5052.3 2198.68
  5100.9 2206.31  5343.8 2216.27  5588.9 2230.51  5816.4 2246.52  5967.3  2254.6
#Mann= 3 ,-1 , 0
  3819.7     .07       0  4993.7     .07       0  5005.9     .07       0
Bank Sta=4993.7,5005.9
XS Rating Curve= 0 ,0
Exp/Cntr=0.3,0.1

Type RM Length L Ch R = 1 ,7282    ,824,824,824
BEGIN DESCRIPTION:
Mapping XS d13b6d58
END DESCRIPTION:
XS GIS Cut Line= 3
       1449436.5      6820396.82      1450478.21      6820444.57
      1450699.56       6819125.1
#Sta/Elev= 30
    3697 2244.35  3715.5 2241.95  3735.5 2234.39  3755.6 2231.53  3915.7 2224.34
  3975.8 2218.16    4166 2215.32  4366.2 2220.23  4476.3 2217.61  4536.4 2211.89
  4708.6 2202.48  4751.1  2196.3  4959.4 2192.08  5003.9 2184.24  5004.4 2183.74
  5016.2 2184.24  5030.4 2186.93  5121.6 2187.19  5253.4 2199.49  5334.6 2196.54
  5375.1 2203.33    5436 2207.68  5473.7 2216.63  5506.9 2216.42  5534.3 2220.03
  5539.4 2218.16    5600 2218.25  5660.7 2221.36  5983.5 2247.96  6077.7 2252.19
#Mann= 3 ,-1 , 0
    3697     .07       0  5003.9     .07       0  5016.2     .07       0
Bank Sta=5003.9,5016.2
XS Rating Curve= 0 ,0
Exp/Cntr=0.3,0.1

Type RM Length L Ch R = 1 ,6458    ,579,579,579
BEGIN DESCRIPTION:
Mapping XS 05195d09
END DESCRIPTION:
XS GIS Cut Line= 3
      1449471.31      6820461.93      1451207.37      6820522.69
      1451775.14      6819521.51
#Sta/Elev= 30
  3264.5 2230.27  3398.3 2225.44  3508.3 2216.12  3582.2 2213.75  3738.5 2213.43
  3918.6 2219.78  3998.6  2217.9  4038.7 2215.88  4088.7 2209.91  4228.8 2203.96
  4288.8 2196.51  4408.9 2189.04  4919.2 2181.14  4959.2 2177.72  5009.9 2178.89
  5025.2 2176.85  5025.7 2176.35  5037.7 2176.85  5063.3 2186.99    5076 2196.71
  5090.6    2203  5106.5  2207.8  5128.2 2210.86  5435.4 2216.29  5662.3 2228.81
  5855.2 2244.41  5882.6 2244.76  6000.9 2255.69  6103.3 2269.34  6152.6 2278.21
#Mann= 3 ,-1 , 0
  3264.5     .07       0  5025.2     .07       0  5037.7     .07       0
Bank Sta=5025.2,5037.7
XS Rating Curve= 0 ,0
Exp/Cntr=0.3,0.1

Type RM Length L Ch R = 1 ,5879    ,760,760,760
BEGIN DESCRIPTION:
Mapping XS 709d1747
END DESCRIPTION:
XS GIS Cut Line= 3
      1451181.91       6821454.4      1451429.31      6820933.57
      1451737.35      6819792.52
#Sta/Elev= 30
  4445.1 2195.96  4676.4  2190.6  4909.2 2181.74  4931.9 2179.53    4971 2171.04
  4971.5 2170.54  4983.8 2171.04  5021.7 2173.74  5063.2 2172.39  5137.8 2176.75
  5234.6 2174.67  5297.4 2177.26  5358.9 2183.69  5396.9 2193.54  5412.6 2198.65
  5452.1 2205.47  5514.3 2207.51  5601.1 2206.22  5648.9 2209.08  5700.7 2209.74
  5721.5 2207.79  5762.9 2210.07  5795.4  2207.5  5814.7  2211.9  5835.4 2210.51
  5856.1 2215.65  5870.1 2217.08  5897.5 2215.69  6019.3 2229.73  6203.6 2243.06
#Mann= 5 ,-1 , 0
  4445.1     .07       0    4971     .07       0  4983.8     .07       0
  5396.9     .16       0  5412.6     .07       0
Bank Sta=4971,4983.8
XS Rating Curve= 0 ,0
Exp/Cntr=0.3,0.1

Type RM Length L Ch R = 1 ,5119    ,606,606,606
BEGIN DESCRIPTION:
Mapping XS 48a91cb1
END DESCRIPTION:
XS GIS Cut Line= 3
      1451863.34      6821630.59      1451963.16      6820792.95
      1451893.83      6819891.58
#Sta/Elev= 30
  4160.9 2189.75  4314.6 2192.39  4383.1 2195.76  4388.2 2194.74  4415.3 2195.15
  4475.7 2189.68  4596.6 2183.88  4646.9 2180.15  4737.5 2177.02  4893.4  2174.8
    4939 2171.11  4982.9 2162.88  4983.4 2162.38  4995.7 2162.88  4999.4 2165.17
  5100.7 2167.67  5139.8 2167.52  5149.8 2168.65  5169.9 2174.32  5175.5 2179.72
  5180.5 2180.18    5200 2187.61    5238 2196.11  5305.9 2202.08  5500.9 2206.85
    5702 2216.54  5811.8 2222.54  5827.4 2225.58  5832.4 2224.92  5908.5 2230.85
#Mann= 5 ,-1 , 0
  4160.9     .07       0  4982.9     .07       0  4995.7     .07       0
  5100.7     .16       0    5238     .07       0
Bank Sta=4982.9,4995.7
XS Rating Curve= 0 ,0
Exp/Cntr=0.3,0.1