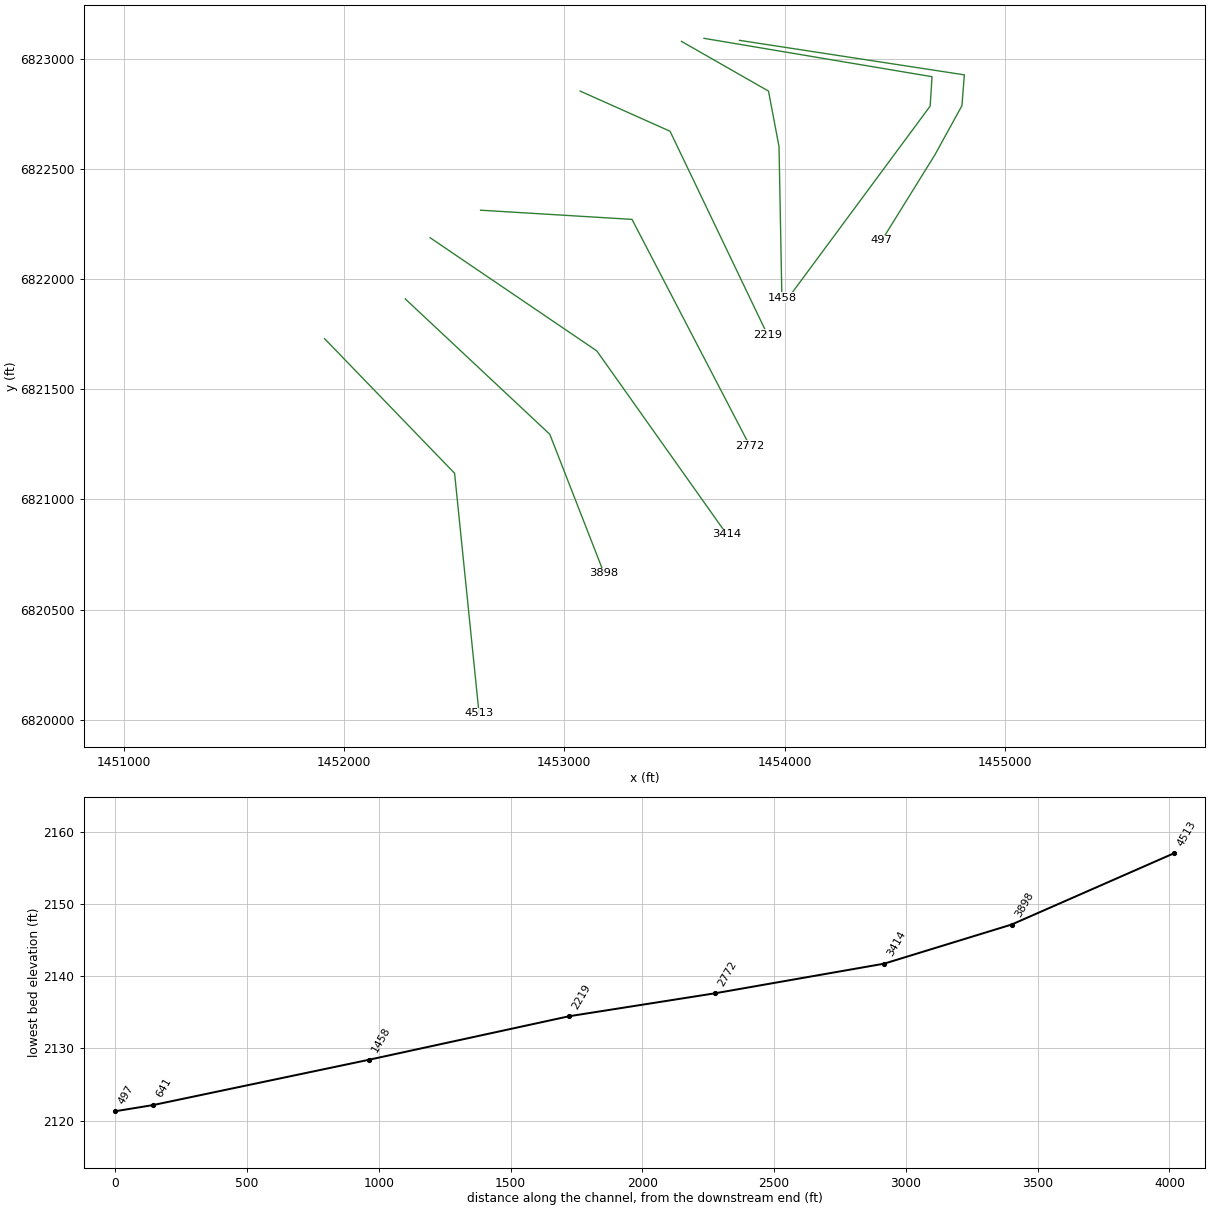
HEC-RAS study COFFEE HOLLOW.prj: COFFEE HOLLOW Base Level Engineering

--- COFFEE HOLLOW.g01 (geometry) --- (continued)

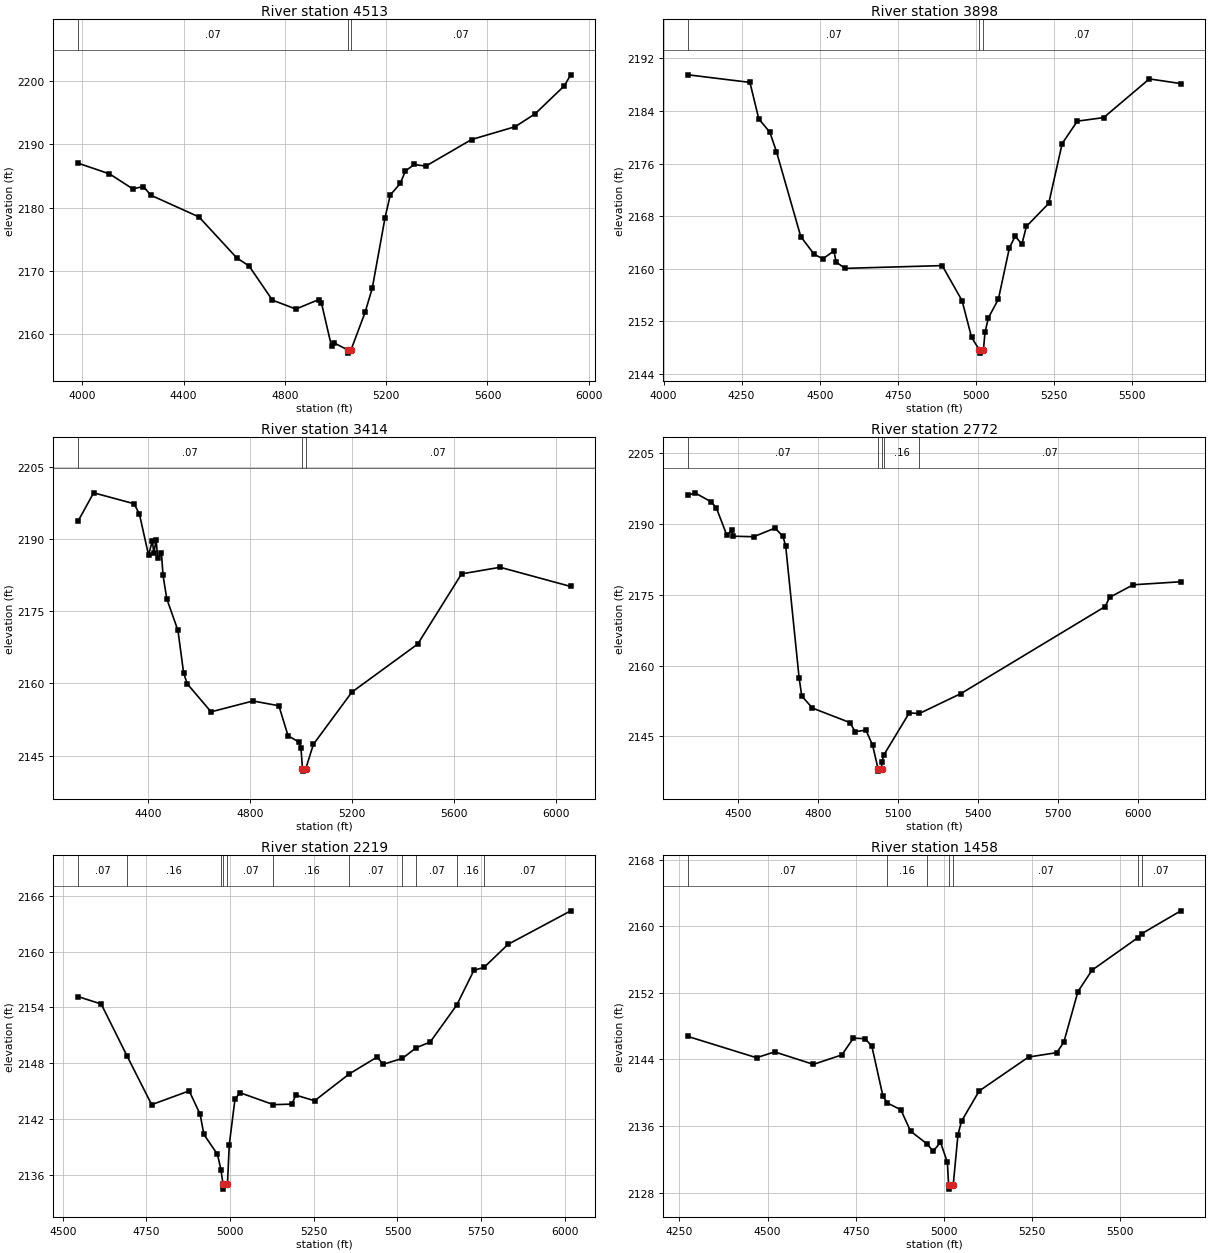
Type RM Length L Ch R = 1 ,4513    ,615,615,615
BEGIN DESCRIPTION:
Mapping XS 10c33755
END DESCRIPTION:
XS GIS Cut Line= 3
      1451911.31       6821729.7      1452501.57      6821118.61
      1452612.68      6820028.37
#Sta/Elev= 30
  3983.3    2187  4107.4 2185.31  4199.2 2182.95  4241.7 2183.32    4270 2181.96
  4460.9 2178.52  4609.5 2172.09  4658.9 2170.78  4750.8 2165.41  4843.6 2164.01
    4934  2165.5  4944.1 2165.01  4984.3 2158.11  4994.4 2158.67  5048.2 2157.56
  5048.7 2157.06  5061.1 2157.56  5116.6 2163.47  5145.1  2167.3  5195.4 2178.37
  5216.2 2181.99  5255.7  2183.8  5275.8 2185.76  5310.8 2186.79  5356.2 2186.53
  5537.1 2190.72  5709.1 2192.74  5788.4 2194.78  5903.2 2199.18  5928.8 2200.92
#Mann= 3 ,-1 , 0
  3983.3     .07       0  5048.2     .07       0  5061.1     .07       0
Bank Sta=5048.2,5061.1
XS Rating Curve= 0 ,0
Exp/Cntr=0.3,0.1

Type RM Length L Ch R = 1 ,3898    ,484,484,484
BEGIN DESCRIPTION:
Mapping XS bd8e99e0
END DESCRIPTION:
XS GIS Cut Line= 3
      1452277.63      6821910.26      1452933.91      6821295.64
      1453180.23      6820664.23
#Sta/Elev= 30
  4078.7 2189.48  4276.6 2188.33    4305 2182.78  4340.1 2180.78  4361.6  2177.8
  4439.3  2164.9  4481.8 2162.23  4510.1 2161.51  4545.3 2162.73  4552.6 2161.03
  4580.9 2160.07  4892.1 2160.49  4955.6 2155.16    4986 2149.58    5011 2147.69
  5011.5 2147.19  5023.9 2147.69    5029 2150.35  5039.7 2152.55  5071.8 2155.38
  5107.1 2163.19  5125.6 2164.96  5147.1 2163.74  5161.4 2166.44  5232.9 2169.94
  5275.9 2179.03  5324.5 2182.44  5408.7 2182.98    5555 2188.86  5655.6 2188.15
#Mann= 3 ,-1 , 0
  4078.7     .07       0    5011     .07       0  5023.9     .07       0
Bank Sta=5011,5023.9
XS Rating Curve= 0 ,0
Exp/Cntr=0.3,0.1

Type RM Length L Ch R = 1 ,3414    ,642,642,642
BEGIN DESCRIPTION:
Mapping XS 0f61b56b
END DESCRIPTION:
XS GIS Cut Line= 3
      1452390.45      6822188.06      1453147.41      6821674.17
      1453736.92      6820841.92
#Sta/Elev= 30
  4124.5 2193.66  4185.7 2199.55  4344.3 2197.29  4365.3 2195.18  4401.3 2186.62
  4416.2 2189.58  4422.2 2187.09  4431.2 2189.81  4437.2 2185.98  4452.1 2186.97
  4458.2 2182.41  4473.1 2177.51  4516.8 2170.97    4539 2162.18    4553 2159.91
  4646.8 2154.07  4811.5 2156.33  4913.2 2155.33  4949.2 2149.11  4991.1 2147.82
    5000  2146.5  5005.8 2142.26  5006.3 2141.76  5018.8 2142.26  5048.5 2147.31
  5199.9 2158.17  5458.3 2168.14  5630.6 2182.72    5782 2184.09  6059.3  2180.1
#Mann= 3 ,-1 , 0
  4124.5     .07       0  5005.8     .07       0  5018.8     .07       0
Bank Sta=5005.8,5018.8
XS Rating Curve= 0 ,0
Exp/Cntr=0.3,0.1

Type RM Length L Ch R = 1 ,2772    ,553,553,553
BEGIN DESCRIPTION:
Mapping XS d2e143d1
END DESCRIPTION:
XS GIS Cut Line= 3
      1452619.63      6822313.06      1453307.13      6822271.39
      1453841.84      6821243.63
#Sta/Elev= 30
  4312.8 2196.07  4338.2 2196.61  4398.3 2194.74  4418.4 2193.47  4458.4 2187.58
  4476.2  2188.7  4481.3 2187.42  4558.6 2187.31  4638.8 2189.14  4668.8 2187.37
  4678.8 2185.29  4728.9 2157.47    4739 2153.56    4779 2151.01  4919.3 2147.94
  4939.3 2146.01  4979.7 2146.33  5004.7 2143.12    5025 2138.15  5025.5 2137.65
  5038.1 2138.15  5039.2 2139.66  5047.5 2141.15    5142 2149.98    5180 2149.86
  5335.4 2154.07  5876.7 2172.52  5893.2 2174.46  5981.6 2177.13  6160.1 2177.77
#Mann= 5 ,-1 , 0
  4312.8     .07       0    5025     .07       0  5038.1     .07       0
  5047.5     .16       0    5180     .07       0
Bank Sta=5025,5038.1
XS Rating Curve= 0 ,0
Exp/Cntr=0.3,0.1

Type RM Length L Ch R = 1 ,2219    ,761,761,761
BEGIN DESCRIPTION:
Mapping XS c0fea176
END DESCRIPTION:
XS GIS Cut Line= 3
      1453071.84      6822853.87      1453479.87      6822671.56
      1453922.57       6821747.1
#Sta/Elev= 30
  4545.8 2155.17    4615 2154.37  4692.3 2148.78  4765.7 2143.55  4877.8 2145.03
  4910.4 2142.52  4921.7 2140.36  4962.3  2138.2  4972.6 2136.58    4979 2134.97
  4979.5 2134.47  4992.1 2134.97  4997.6 2139.26  5014.7 2144.16  5029.9 2144.83
  5129.6 2143.55  5185.1 2143.61    5196 2144.58  5252.5 2143.97  5356.6 2146.87
  5440.2 2148.69  5456.4 2147.88  5514.9 2148.53  5556.1 2149.67    5598 2150.29
  5677.2 2154.26  5728.4 2157.99  5759.1 2158.32  5830.1 2160.78  6017.7 2164.39
#Mann= 11 ,-1 , 0
  4545.8     .07       0  4692.3     .16       0  4972.6     .07       0
    4979     .07       0  4992.1     .07       0  5129.6     .16       0
  5356.6     .07       0  5514.9     .16       0  5556.1     .07       0
  5677.2     .16       0  5759.1     .07       0
Bank Sta=4979,4992.1
XS Rating Curve= 0 ,0
Exp/Cntr=0.3,0.1

Type RM Length L Ch R = 1 ,1458    ,817,817,817
BEGIN DESCRIPTION:
Mapping XS ae1cf04c
END DESCRIPTION:
XS GIS Cut Line= 4
      1453531.92      6823079.57      1453926.92      6822853.85
      1453974.66      6822602.12      1453987.68      6821916.31
#Sta/Elev= 30
  4274.5 2146.76  4468.6 2144.21  4519.9 2144.91  4629.9 2143.41  4710.5 2144.55
  4743.2 2146.56  4776.1  2146.5  4795.5  2145.6    4827  2139.6  4839.4 2138.77
  4877.9 2137.95  4905.2 2135.39  4952.8 2133.83  4969.5 2132.96  4990.2 2134.06
  5009.8 2131.63  5013.2 2128.92  5013.7 2128.42  5026.3 2128.92  5039.8 2134.97
  5049.8 2136.58  5099.8 2140.21  5239.8 2144.29  5319.8 2144.82  5339.8 2146.06
  5379.9 2152.15  5419.9 2154.73  5549.2 2158.61  5560.8 2159.11  5671.6 2161.86
#Mann= 7 ,-1 , 0
  4274.5     .07       0  4839.4     .16       0  4952.8     .07       0
  5013.2     .07       0  5026.3     .07       0  5549.2     .16       0
  5560.8     .07       0
Bank Sta=5013.2,5026.3
XS Rating Curve= 0 ,0
Exp/Cntr=0.3,0.1

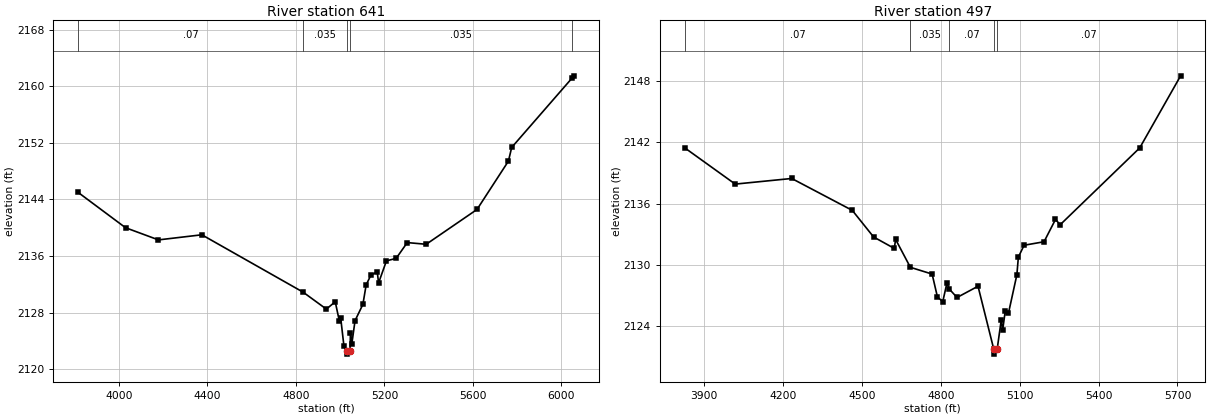
Type RM Length L Ch R = 1 ,641     ,144,144,144
BEGIN DESCRIPTION:
Mapping XS ab623f82
END DESCRIPTION:
XS GIS Cut Line= 4
      1453634.15      6823093.43      1454669.42      6822919.25
      1454660.94      6822785.74      1454032.28      6821935.76
#Sta/Elev= 30
  3816.4 2144.99  4030.2 2140.01  4178.9 2138.29    4375 2139.01  4832.8  2130.9
  4937.6 2128.51  4977.7 2129.55  4996.4 2126.81  5002.5 2127.23  5017.1 2123.26
  5031.4 2122.65  5031.9 2122.15  5044.6 2122.65  5046.4  2125.1  5052.6 2123.59
  5067.2 2126.88  5102.7 2129.18  5117.3 2131.92  5138.2 2133.28  5167.4 2133.79
  5173.6 2132.22  5209.1 2135.33    5253 2135.68  5303.1 2137.91  5388.7 2137.67
  5618.3 2142.59  5760.2 2149.42  5774.9 2151.35  6046.3  2161.1  6057.2 2161.47
#Mann= 5 ,-1 , 0
  3816.4     .07       0  4832.8    .035       0  5031.4    .035       0
  5044.6    .035       0  6046.3     .07       0
Bank Sta=5031.4,5044.6
XS Rating Curve= 0 ,0
Exp/Cntr=0.3,0.1

Type RM Length L Ch R = 1 ,497     ,0,0,0
BEGIN DESCRIPTION:
COFFEE HOLLOW 1.0
END DESCRIPTION:
XS GIS Cut Line= 5
      1453795.08      6823084.34      1454816.29      6822927.59
      1454805.17       6822787.6      1454682.61      6822564.74
       1454441.3      6822175.86
#Sta/Elev= 30
  3826.4 2141.47  4018.5 2137.92  4233.4 2138.47  4463.7 2135.35  4544.6 2132.75
  4623.3 2131.63  4628.4 2132.51  4684.5 2129.78  4767.2 2129.12  4787.4 2126.88
  4807.7 2126.43  4823.4 2128.23    4833 2127.64  4861.9 2126.83  4941.7 2127.93
  5001.4 2121.79  5001.9 2121.29  5014.6 2121.79  5029.8 2124.59  5035.5 2123.67
  5045.2  2125.5  5057.3 2125.27  5089.4 2129.05  5095.1 2130.78  5116.9 2131.94
  5192.7 2132.28  5236.2 2134.46  5254.3 2133.95  5556.5 2141.46    5712 2148.51
#Mann= 5 ,-1 , 0
  3826.4     .07       0  4684.5    .035       0    4833     .07       0
  5001.4    .035       0  5014.6     .07       0
Bank Sta=5001.4,5014.6
XS Rating Curve= 0 ,0
Exp/Cntr=0.3,0.1

Chan Stop Cuts=-1
Use User Specified Reach Order=0
Composite Channel Slope=5