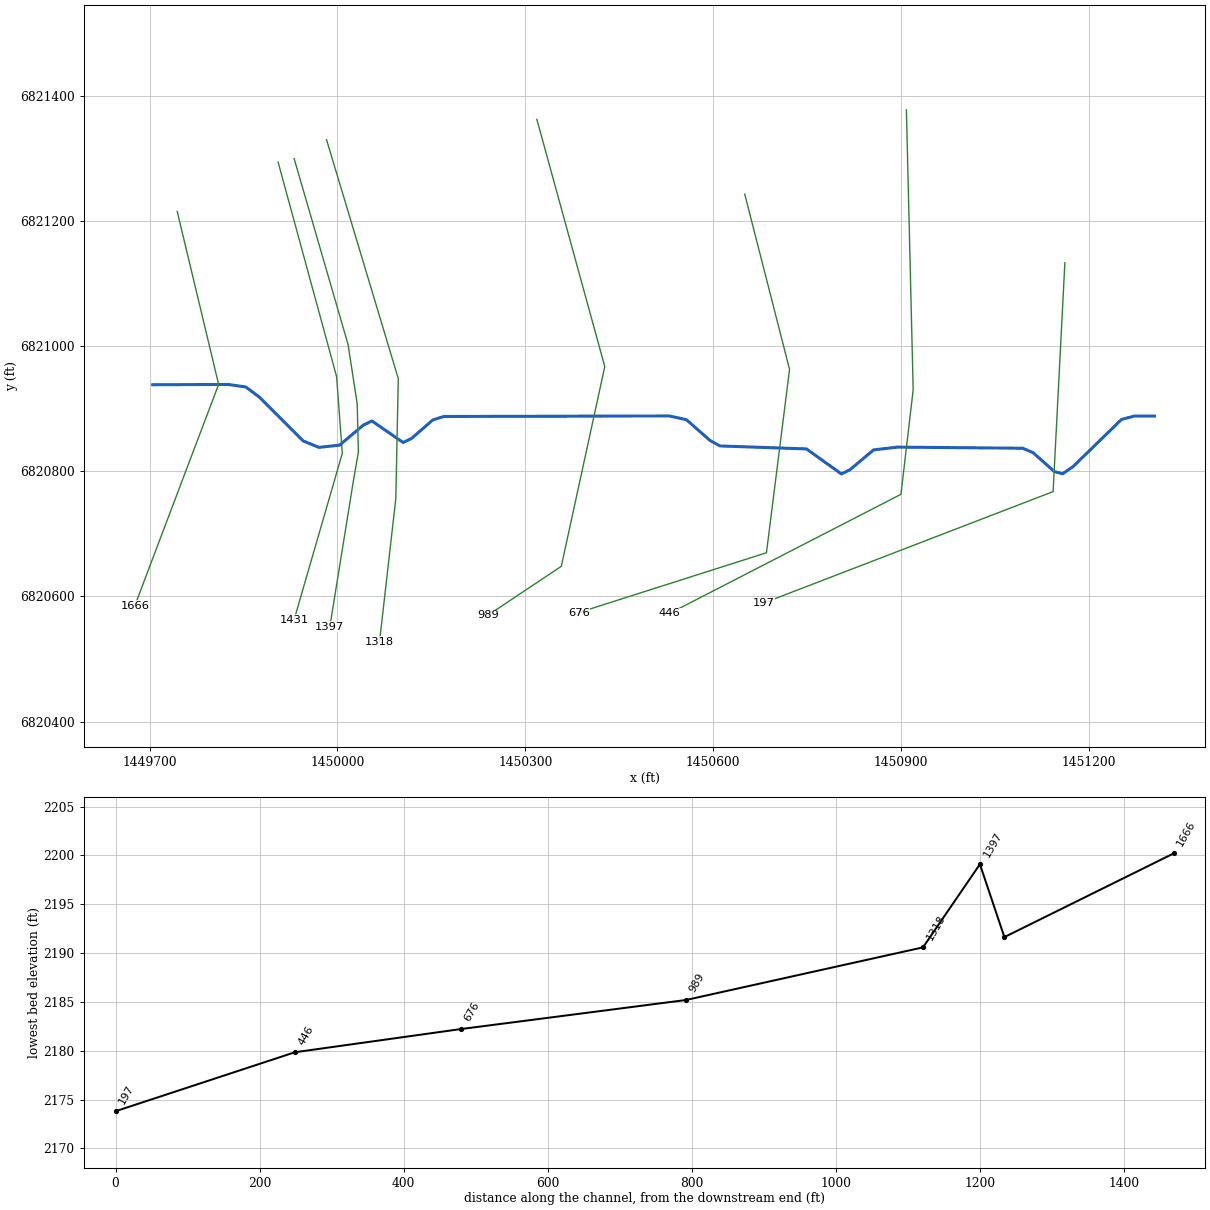
--- COFFEE HOLLOW TRIBUTARY 1.prj (project) ---

Proj Title=COFFEE HOLLOW TRIBUTARY 1 Base Level Engineering
Current Plan=p01
Default Exp/Contr=0.3,0.1
English Units
Geom File=g01
Flow File=f01
Plan File=p01
BEGIN DESCRIPTION:
COFFEE HOLLOW TRIBUTARY 1
END DESCRIPTION:

--- COFFEE HOLLOW TRIBUTARY 1.p01 (plan) ---

Plan Title=Multiple Run
Short Identifier=Multiple
Geom File=g01
Flow File=f01
Subcritical Flow
K Sum by GR= 0
Std Step Tol= 0.01
Critical Tol= 0.01
Num of Std Step Trials= 20
Max Error Tol= 0.3
Flow Tol Ratio= 0.001
Split Flow NTrial= 30
Split Flow Tol= 0.02
Split Flow Ratio= 0.02
Log Output Level= 0
Friction Slope Method= 1
Unsteady Friction Slope Method= 2
Unsteady Bridges Friction Slope Method= 1
Parabolic Critical Depth
Global Vel Dist=  1 , 1 , 1
Global Log Level= 0
CheckData=True
Encroach Param= -1, 0, 0, 0
BEGIN DESCRIPTION:
Multiple Run
END DESCRIPTION:

--- COFFEE HOLLOW TRIBUTARY 1.f01 (steady flow) ---

Flow Title=Multiple
Number of Profiles=7
Profile Names=10-year,25-year,50-year,1pct_min,100-year,1pct_plu,500-year
River Rch & RM= COFFEE HOLLOW TR,Reach-1,1666
      97     128     153      92     183     366     264
Boundary for River Rch & Prof#=COFFEE HOLLOW TR,Reach-1,1
Up Type=0
Dn Type=3
Dn Slope=0.005
Boundary for River Rch & Prof#=COFFEE HOLLOW TR,Reach-1,2
Up Type=0
Dn Type=3
Dn Slope=0.005
Boundary for River Rch & Prof#=COFFEE HOLLOW TR,Reach-1,3
Up Type=0
Dn Type=3
Dn Slope=0.005
Boundary for River Rch & Prof#=COFFEE HOLLOW TR,Reach-1,4
Up Type=0
Dn Type=3
Dn Slope=0.005
Boundary for River Rch & Prof#=COFFEE HOLLOW TR,Reach-1,5
Up Type=0
Dn Type=3
Dn Slope=0.005
Boundary for River Rch & Prof#=COFFEE HOLLOW TR,Reach-1,6
Up Type=0
Dn Type=3
Dn Slope=0.005
Boundary for River Rch & Prof#=COFFEE HOLLOW TR,Reach-1,7
Up Type=0
Dn Type=3
Dn Slope=0.005

--- COFFEE HOLLOW TRIBUTARY 1.g01 (geometry) ---

Geom Title=Existing Conditions

River Reach=COFFEE HOLLOW TR,Reach-1
Reach XY= 30
      1449705.00      6820938.00      1449825.21      6820938.51
      1449853.55      6820934.49      1449875.15      6820918.35
      1449945.33      6820848.23      1449970.36      6820838.01
      1450003.35      6820841.56      1450041.81      6820873.86
      1450055.08      6820880.17      1450104.90      6820845.79
      1450118.16      6820852.07      1450152.55      6820882.00
      1450170.16      6820887.35      1450530.08      6820888.20
      1450557.33      6820882.25      1450595.36      6820848.86
      1450610.94      6820840.27      1450749.14      6820835.53
      1450805.00      6820795.56      1450818.21      6820801.95
      1450856.47      6820833.99      1450894.79      6820838.40
      1451094.57      6820836.61      1451111.19      6820829.53
      1451145.16      6820799.33      1451158.42      6820795.78
      1451175.02      6820807.28      1451252.48      6820882.65
      1451273.12      6820888.06      1451305.00      6820888.00

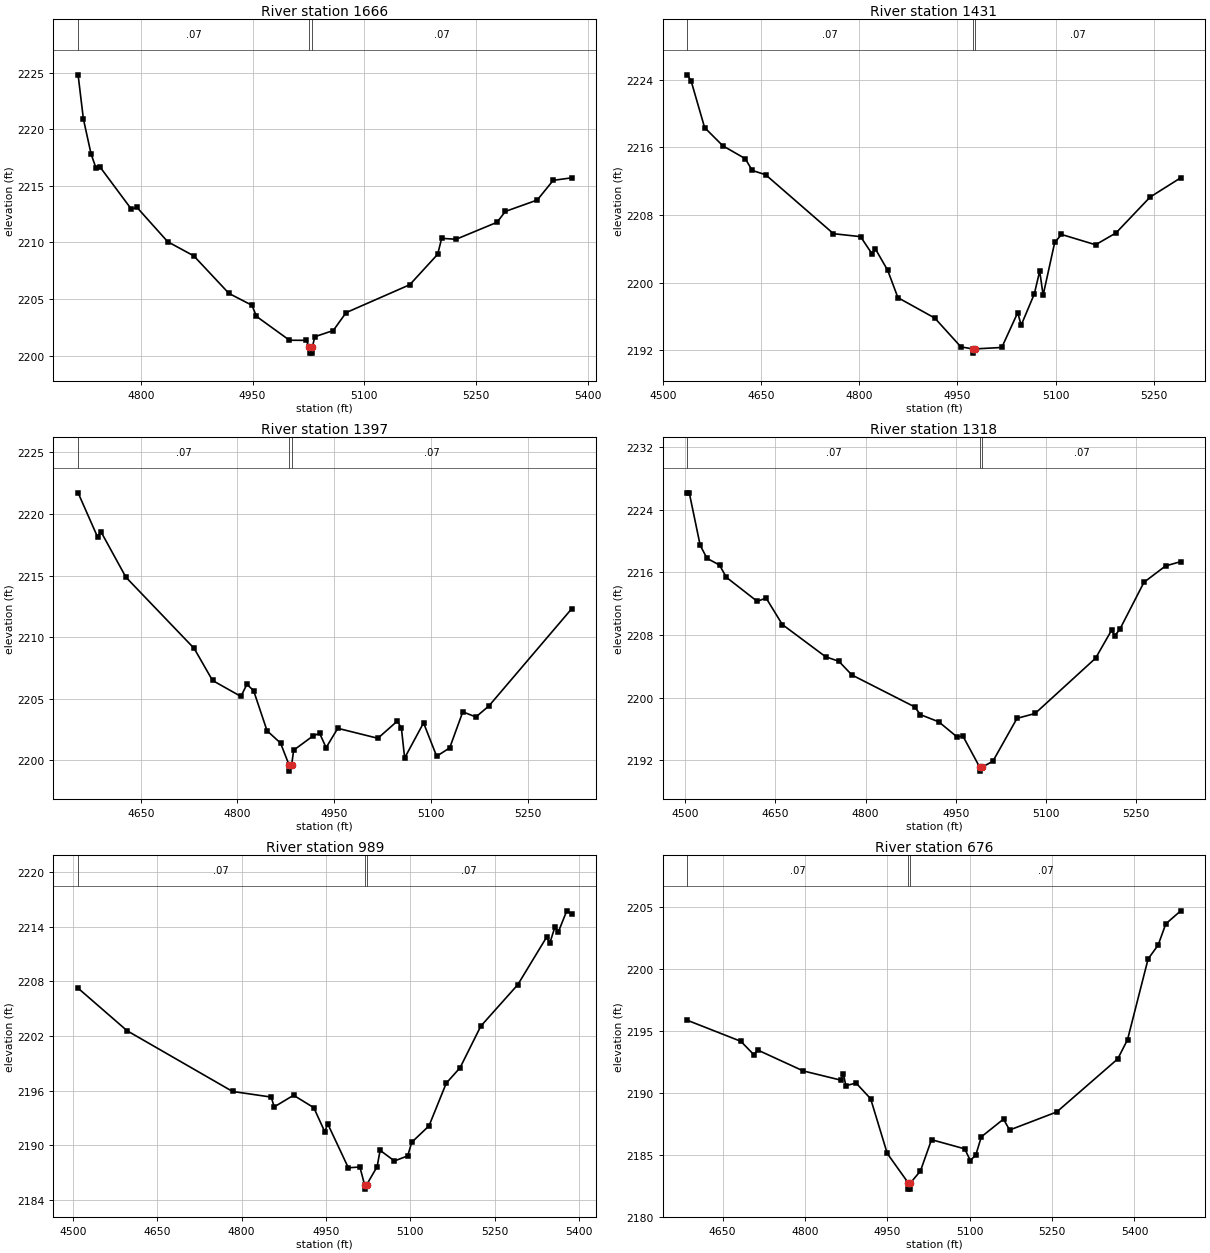
Type RM Length L Ch R = 1,1666,235,235,235
BEGIN DESCRIPTION:
COFFEE HOLLOW TRIBUTARY 1 2.0
END DESCRIPTION:
XS GIS Cut Line= 3
      1449744.03      6821214.95      1449810.23      6820938.57
      1449676.27      6820584.88
#Sta/Elev= 30
  4715.8 2224.82  4722.9 2220.92  4733.2 2217.83  4739.9 2216.56  4745.0 2216.69
  4787.1 2212.96  4794.9 2213.09  4836.1 2210.06  4871.1 2208.81  4918.3 2205.49
  4949.2 2204.44  4955.2 2203.46  4999.5 2201.35  5022.0 2201.34  5026.1 2200.71
  5026.4 2200.21  5029.9 2200.21  5030.1 2200.71  5033.5 2201.66  5058.3 2202.21
  5075.5 2203.79  5161.0 2206.26  5198.4 2208.95  5203.8 2210.36  5223.2 2210.28
  5278.1 2211.78  5289.3 2212.74  5332.1 2213.75  5353.5 2215.49  5378.2 2215.71
#Mann=3,-1,0
  4715.8    0.07       0  5026.1    0.07       0  5030.1    0.07       0
Bank Sta=5026.1,5030.1
Exp/Cntr=0.3,0.1

Type RM Length L Ch R = 1,1431,34,34,34
BEGIN DESCRIPTION:
Mapping XS 0efc9228
END DESCRIPTION:
XS GIS Cut Line= 4
      1449905.20      6821293.67      1449998.61      6820951.18
      1450007.77      6820828.48      1449930.85      6820562.94
#Sta/Elev= 30
  4536.8 2224.59  4542.7 2223.88  4563.4 2218.34  4591.2 2216.19  4625.6 2214.66
  4636.1 2213.27  4656.7 2212.76  4760.4 2205.78  4801.8 2205.43  4819.2 2203.41
  4824.4 2203.99  4843.3 2201.44  4858.9 2198.21  4915.3 2195.79  4955.2 2192.38
  4973.2 2192.14  4973.5 2191.64  4977.2 2192.14  5017.7 2192.31  5042.1 2196.44
  5047.3 2194.94  5067.4 2198.64  5075.7 2201.36  5080.9 2198.49  5098.6 2204.74
  5109.0 2205.69  5161.1 2204.47  5192.3 2205.87  5244.4 2210.11  5291.3 2212.40
#Mann=3,-1,0
  4536.8    0.07       0  4973.2    0.07       0  4977.2    0.07       0
Bank Sta=4973.2,4977.2
Exp/Cntr=0.3,0.1

Type RM Length L Ch R = 1,1397,79,79,79
BEGIN DESCRIPTION:
Mapping XS ad40155a
END DESCRIPTION:
XS GIS Cut Line= 6
      1449930.84      6821299.17      1450016.93      6821002.46
      1450031.58      6820907.23      1450033.41      6820830.31
      1450026.08      6820788.19      1449987.86      6820551.55
#Sta/Elev= 30
  4553.0 2221.72  4583.1 2218.14  4588.3 2218.57  4627.1 2214.86  4732.9 2209.07
  4761.3 2206.47  4805.3 2205.17  4814.5 2206.15  4824.9 2205.65  4845.8 2202.38
  4866.7 2201.38  4879.9 2199.60  4880.2 2199.10  4883.9 2199.60  4887.0 2200.80
  4917.0 2201.96  4927.2 2202.18  4937.3 2201.01  4955.4 2202.58  5017.5 2201.77
  5047.7 2203.17  5054.0 2202.58  5059.0 2200.17  5088.3 2203.02  5108.6 2200.31
  5128.8 2200.99  5149.1 2203.92  5169.4 2203.50  5189.6 2204.40  5317.7 2212.29
#Mann=3,-1,0
  4553.0    0.07       0  4879.9    0.07       0  4883.9    0.07       0
Bank Sta=4879.9,4883.9
Exp/Cntr=0.3,0.1

Type RM Length L Ch R = 1,1318,329,329,329
BEGIN DESCRIPTION:
Mapping XS ca1aa63b
END DESCRIPTION:
XS GIS Cut Line= 4
      1449982.57      6821329.44      1450097.16      6820947.91
      1450093.26      6820756.50      1450067.21      6820527.29
#Sta/Elev= 30
  4503.4 2226.18  4506.8 2226.18  4524.9 2219.48  4536.2 2217.81  4557.1 2216.94
  4568.4 2215.38  4619.8 2212.30  4634.5 2212.73  4661.5 2209.34  4733.6 2205.21
  4755.5 2204.64  4777.1 2202.89  4881.4 2198.81  4891.2 2197.81  4921.7 2196.89
  4951.7 2194.98  4961.7 2195.08  4989.7 2191.09  4989.9 2190.59  4993.7 2191.09
  5011.7 2191.87  5051.7 2197.34  5081.7 2197.96  5182.3 2205.03  5209.0 2208.62
  5214.1 2207.90  5222.5 2208.71  5262.8 2214.74  5298.6 2216.83  5323.9 2217.38
#Mann=3,-1,0
  4503.4    0.07       0  4989.7    0.07       0  4993.7    0.07       0
Bank Sta=4989.7,4993.7
Exp/Cntr=0.3,0.1

Type RM Length L Ch R = 1,989,313,313,313
BEGIN DESCRIPTION:
Mapping XS f960cc98
END DESCRIPTION:
XS GIS Cut Line= 4
      1450318.52      6821361.96      1450427.02      6820967.00
      1450357.58      6820647.99      1450240.40      6820569.87
#Sta/Elev= 30
  4509.6 2207.25  4596.7 2202.58  4784.0 2195.92  4852.8 2195.30  4858.0 2194.22
  4892.5 2195.50  4928.4 2194.14  4948.0 2191.48  4953.1 2192.37  4989.8 2187.54
  5010.3 2187.63  5018.5 2185.70  5018.8 2185.20  5022.5 2185.70  5041.0 2187.67
  5046.2 2189.46  5071.7 2188.29  5095.3 2188.85  5102.4 2190.34  5133.1 2192.14
  5163.8 2196.83  5188.3 2198.52  5225.2 2203.09  5290.8 2207.63  5341.9 2212.83
  5347.9 2212.22  5356.9 2213.98  5362.9 2213.42  5377.9 2215.74  5386.5 2215.40
#Mann=3,-1,0
  4509.6    0.07       0  5018.5    0.07       0  5022.5    0.07       0
Bank Sta=5018.5,5022.5
Exp/Cntr=0.3,0.1

Type RM Length L Ch R = 1,676,230,230,230
BEGIN DESCRIPTION:
Mapping XS 46c48cd9
END DESCRIPTION:
XS GIS Cut Line= 4
      1450650.55      6821242.60      1450722.16      6820962.66
      1450685.27      6820669.69      1450385.76      6820574.20
#Sta/Elev= 30
  4585.7 2195.85  4683.3 2194.15  4706.8 2193.08  4714.3 2193.44  4796.9 2191.76
  4865.0 2191.02  4870.1 2191.51  4874.5 2190.57  4893.2 2190.78  4919.7 2189.51
  4949.9 2185.10  4988.2 2182.72  4988.5 2182.22  4992.0 2182.22  4992.2 2182.72
  5010.4 2183.69  5030.5 2186.21  5091.0 2185.47  5101.1 2184.53  5111.2 2184.98
  5121.2 2186.44  5161.6 2187.87  5172.7 2186.99  5258.6 2188.45  5369.6 2192.73
  5387.4 2194.28  5424.9 2200.80  5443.1 2201.91  5457.1 2203.63  5484.3 2204.68
#Mann=3,-1,0
  4585.7    0.07       0  4988.2    0.07       0  4992.2    0.07       0
Bank Sta=4988.2,4992.2
Exp/Cntr=0.3,0.1

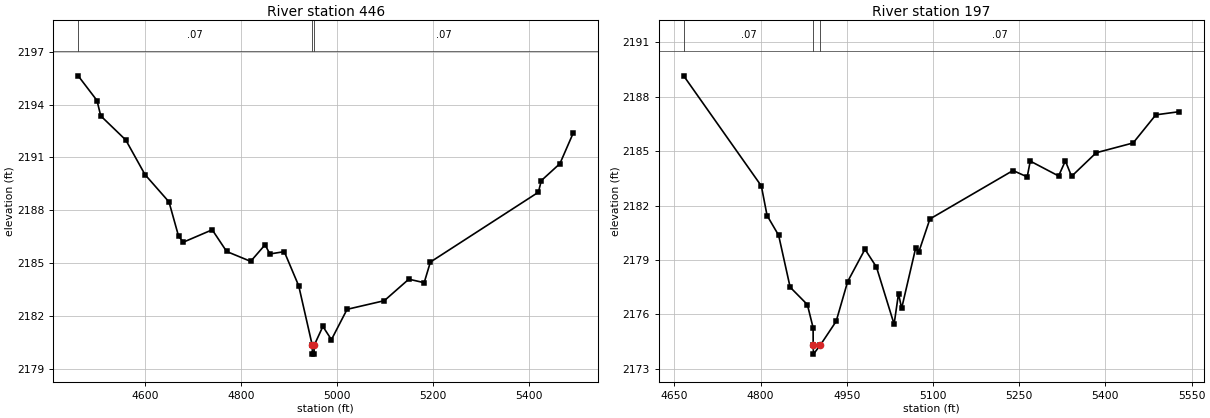
Type RM Length L Ch R = 1,446,249,249,249
BEGIN DESCRIPTION:
Mapping XS 89a7398c
END DESCRIPTION:
XS GIS Cut Line= 4
      1450908.79      6821377.17      1450919.64      6820930.11
      1450900.11      6820763.01      1450530.42      6820572.76
#Sta/Elev= 30
  4460.4 2195.63  4499.6 2194.23  4507.4 2193.36  4559.6 2191.99  4599.6 2190.03
  4649.6 2188.48  4669.6 2186.53  4679.6 2186.20  4739.6 2186.90  4769.7 2185.67
  4819.7 2185.11  4849.7 2186.05  4859.7 2185.53  4889.7 2185.66  4919.8 2183.72
  4948.0 2180.35  4948.2 2179.85  4951.7 2179.85  4952.0 2180.35  4970.1 2181.42
  4987.9 2180.67  5020.5 2182.39  5098.1 2182.88  5149.1 2184.10  5181.1 2183.90
  5194.0 2185.07  5419.0 2189.03  5425.1 2189.69  5463.8 2190.65  5491.6 2192.39
#Mann=3,-1,0
  4460.4    0.07       0  4948.0    0.07       0  4952.0    0.07       0
Bank Sta=4948,4952
Exp/Cntr=0.3,0.1

Type RM Length L Ch R = 1,197,0,0,0
BEGIN DESCRIPTION:
COFFEE HOLLOW TRIBUTARY 1 1.0
END DESCRIPTION:
XS GIS Cut Line= 3
      1451161.94      6821132.94      1451143.17      6820767.35
      1450680.91      6820589.39
#Sta/Elev= 30
  4666.2 2189.15  4801.3 2183.08  4811.3 2181.45  4831.4 2180.36  4851.4 2177.50
  4881.4 2176.54  4891.4 2175.26  4891.5 2174.31  4892.0 2173.81  4904.0 2174.31
  4931.5 2175.62  4951.5 2177.81  4981.6 2179.59  5001.6 2178.61  5032.3 2175.46
  5040.0 2177.15  5045.4 2176.33  5070.0 2179.68  5075.4 2179.45  5094.6 2181.26
  5239.2 2183.93  5263.9 2183.58  5269.2 2184.45  5318.5 2183.63  5330.3 2184.46
  5341.1 2183.61  5383.9 2184.91  5448.2 2185.45  5487.7 2187.00  5527.6 2187.17
#Mann=3,-1,0
  4666.2    0.07       0  4891.5    0.07       0  4904.0    0.07       0
Bank Sta=4891.5,4904
Exp/Cntr=0.3,0.1

Chan Stop Cuts=-1