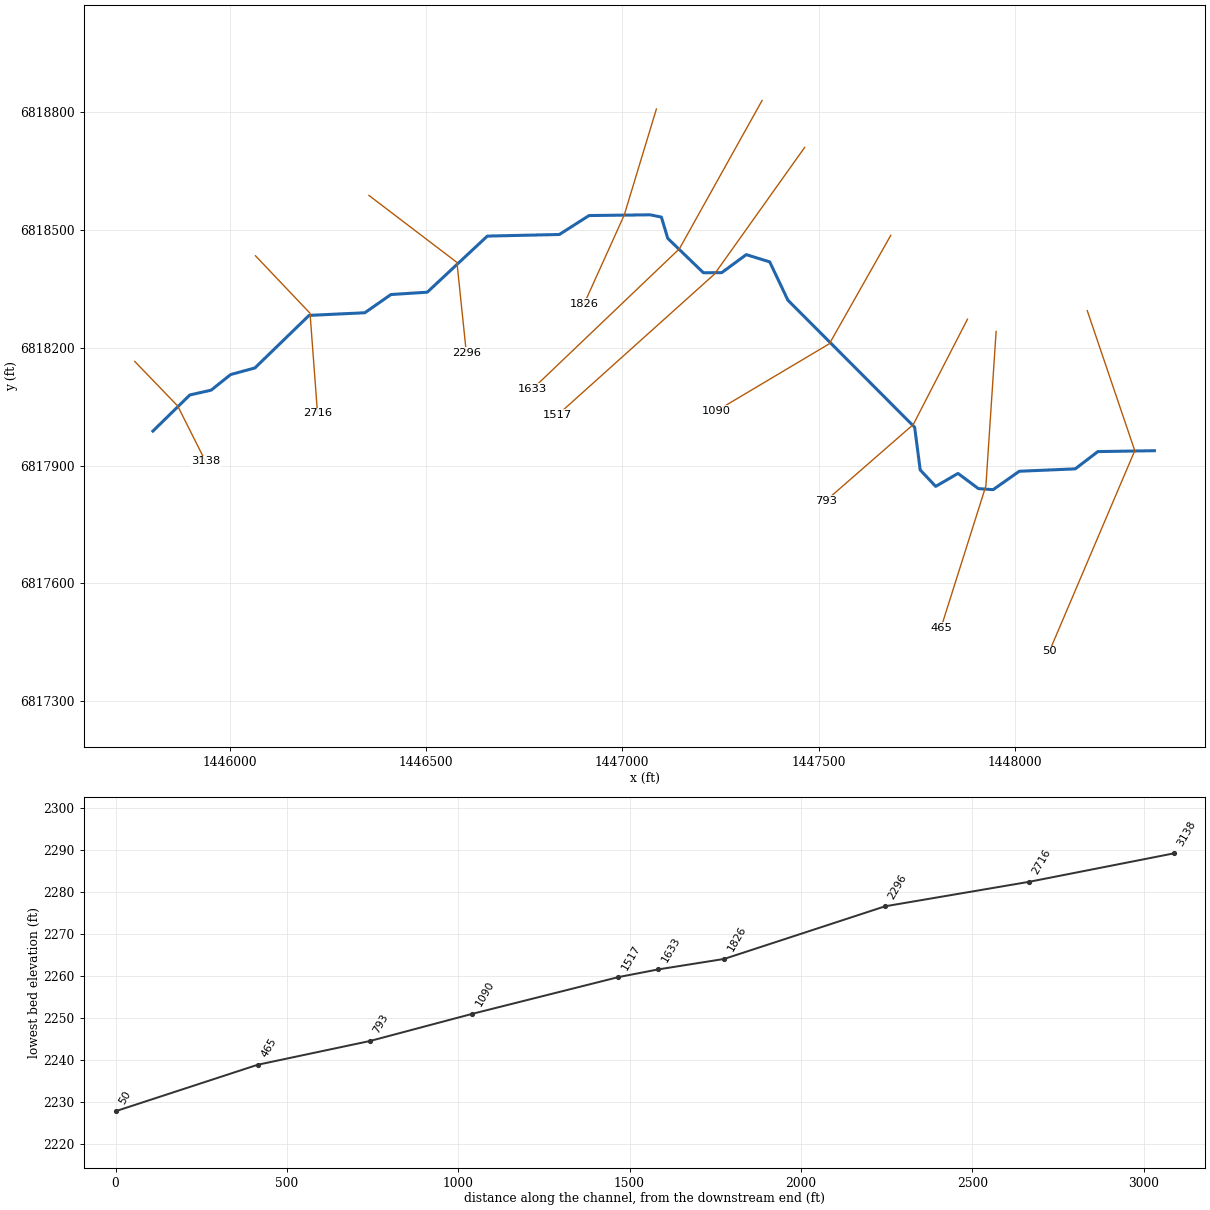
--- COFFEE HOLLOW TRIBUTARY 2.prj (project) ---

Proj Title=COFFEE HOLLOW TRIBUTARY 2 Base Level Engineering
Current Plan=p01
Default Exp/Contr=0.3,0.1
English Units
Geom File=g01
Flow File=f01
Plan File=p01
BEGIN DESCRIPTION:
COFFEE HOLLOW TRIBUTARY 2
END DESCRIPTION:

--- COFFEE HOLLOW TRIBUTARY 2.p01 (plan) ---

Plan Title=Multiple Run
Short Identifier=Multiple
Geom File=g01
Flow File=f01
Subcritical Flow
K Sum by GR= 0
Std Step Tol= 0.01
Critical Tol= 0.01
Num of Std Step Trials= 20
Max Error Tol= 0.3
Flow Tol Ratio= 0.001
Split Flow NTrial= 30
Split Flow Tol= 0.02
Split Flow Ratio= 0.02
Log Output Level= 0
Friction Slope Method= 1
Unsteady Friction Slope Method= 2
Unsteady Bridges Friction Slope Method= 1
Parabolic Critical Depth
Global Vel Dist=  1 , 1 , 1
Global Log Level= 0
CheckData=True
Encroach Param= -1, 0, 0, 0
BEGIN DESCRIPTION:
Multiple Run
END DESCRIPTION:

--- COFFEE HOLLOW TRIBUTARY 2.f01 (steady flow) ---

Flow Title=Multiple
Number of Profiles=7
Profile Names=10-year,25-year,50-year,1pct_min,100-year,1pct_plu,500-year
River Rch & RM= COFFEE HOLLOW TR,Reach-1,3138
     252     357     447     279     557    1111     873
Boundary for River Rch & Prof#=COFFEE HOLLOW TR,Reach-1,1
Up Type=0
Dn Type=3
Dn Slope=0.005
Boundary for River Rch & Prof#=COFFEE HOLLOW TR,Reach-1,2
Up Type=0
Dn Type=3
Dn Slope=0.005
Boundary for River Rch & Prof#=COFFEE HOLLOW TR,Reach-1,3
Up Type=0
Dn Type=3
Dn Slope=0.005
Boundary for River Rch & Prof#=COFFEE HOLLOW TR,Reach-1,4
Up Type=0
Dn Type=3
Dn Slope=0.005
Boundary for River Rch & Prof#=COFFEE HOLLOW TR,Reach-1,5
Up Type=0
Dn Type=3
Dn Slope=0.005
Boundary for River Rch & Prof#=COFFEE HOLLOW TR,Reach-1,6
Up Type=0
Dn Type=3
Dn Slope=0.005
Boundary for River Rch & Prof#=COFFEE HOLLOW TR,Reach-1,7
Up Type=0
Dn Type=3
Dn Slope=0.005

--- COFFEE HOLLOW TRIBUTARY 2.g01 (geometry) ---

Geom Title=Existing Conditions

River Reach=COFFEE HOLLOW TR,Reach-1
Reach XY= 30
      1445805.00      6817988.00      1445898.92      6818079.91
      1445953.27      6818092.18      1446002.81      6818131.90
      1446064.68      6818148.77      1446202.55      6818282.53
      1446344.49      6818289.23      1446410.98      6818335.64
      1446503.50      6818341.61      1446656.46      6818484.46
      1446839.78      6818488.52      1446915.51      6818536.78
      1447070.55      6818538.64      1447099.56      6818532.82
      1447115.90      6818478.60      1447206.62      6818391.13
      1447253.26      6818391.37      1447315.75      6818437.28
      1447375.47      6818418.73      1447421.66      6818321.34
      1447744.48      6817997.78      1447758.61      6817889.03
      1447798.00      6817847.16      1447854.90      6817880.16
      1447906.63      6817841.59      1447944.29      6817838.81
      1448010.93      6817885.70      1448153.43      6817891.78
      1448210.92      6817935.78      1448355.00      6817938.00

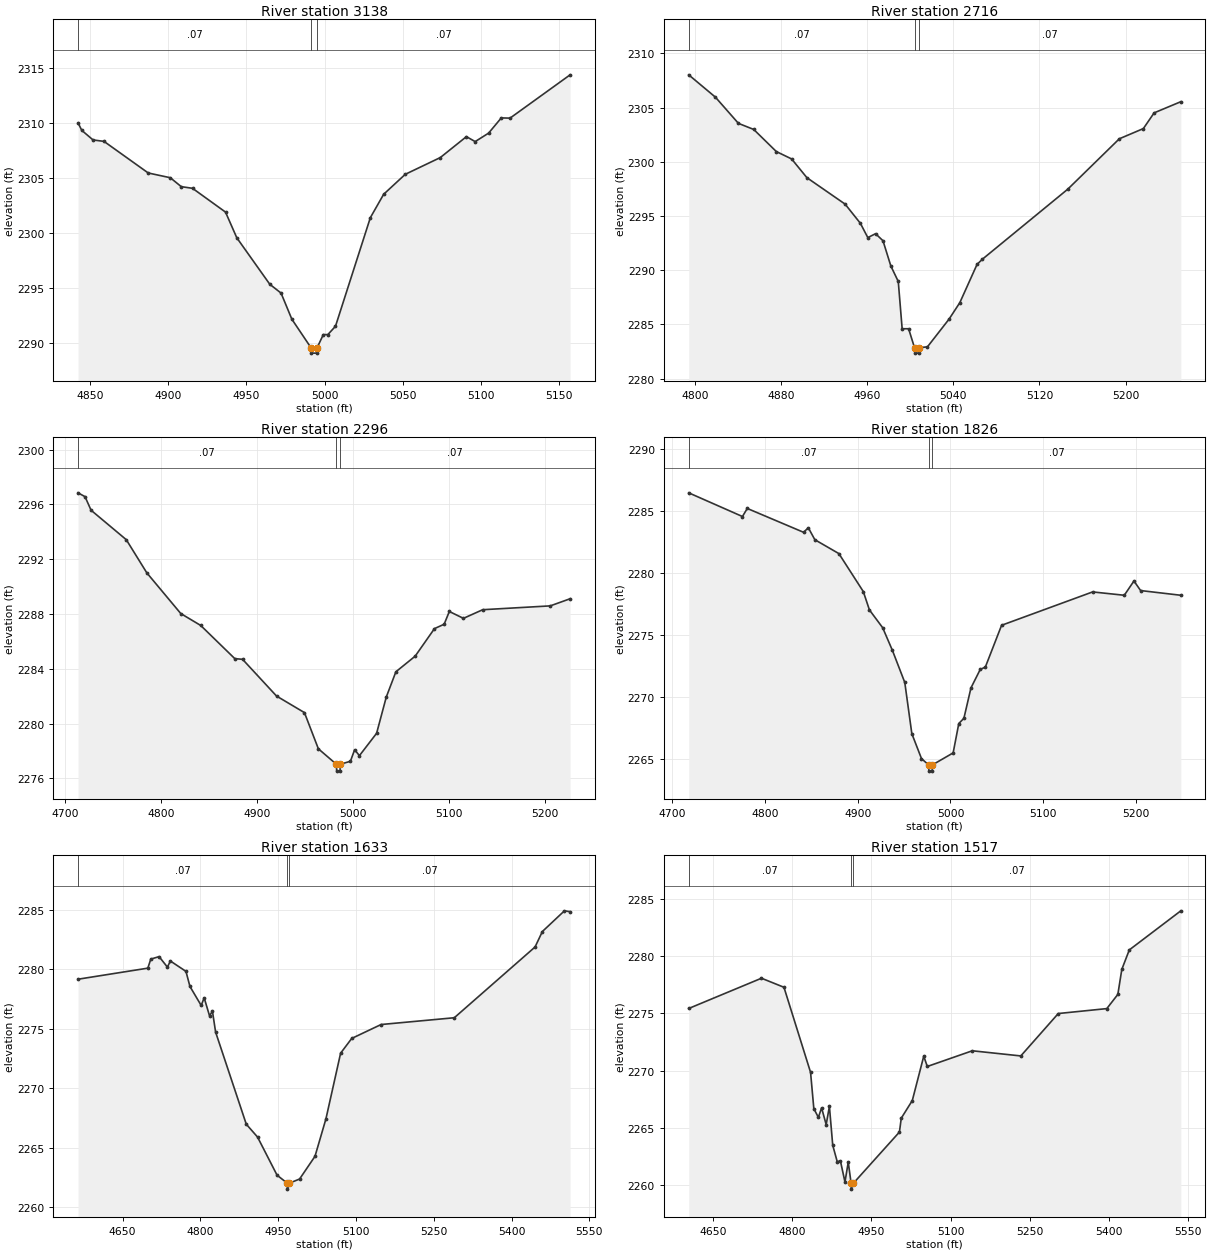
Type RM Length L Ch R = 1,3138,422,422,422
BEGIN DESCRIPTION:
COFFEE HOLLOW TRIBUTARY 2 7.0
END DESCRIPTION:
XS GIS Cut Line= 3
      1445758.77      6818165.24      1445868.15      6818051.78
      1445938.60      6817911.48
#Sta/Elev= 30
  4842.4 2310.01  4844.8 2309.33  4852.0 2308.46  4859.0 2308.33  4887.3 2305.46
  4901.4 2305.03  4908.4 2304.22  4915.6 2304.07  4936.7 2301.91  4943.9 2299.58
  4965.0 2295.36  4972.2 2294.56  4979.1 2292.19  4991.3 2289.61  4991.5 2289.11
  4995.0 2289.11  4995.3 2289.61  4999.2 2290.79  5002.1 2290.79  5007.0 2291.55
  5029.3 2301.41  5037.8 2303.53  5051.6 2305.34  5074.0 2306.86  5090.7 2308.76
  5096.3 2308.31  5104.9 2309.08  5113.0 2310.46  5118.6 2310.44  5157.0 2314.37
#Mann=3,-1,0
  4842.4    0.07       0  4991.3    0.07       0  4995.3    0.07       0
Bank Sta=4991.3,4995.3
Exp/Cntr=0.3,0.1

Type RM Length L Ch R = 1,2716,420,420,420
BEGIN DESCRIPTION:
COFFEE HOLLOW TRIBUTARY 2 6.0
END DESCRIPTION:
XS GIS Cut Line= 3
      1446066.07      6818434.33      1446205.00      6818288.00
      1446224.05      6818033.29
#Sta/Elev= 30
  4794.1 2308.03  4818.9 2305.97  4840.3 2303.55  4854.5 2302.99  4875.5 2300.95
  4889.7 2300.27  4903.9 2298.54  4939.4 2296.10  4953.6 2294.33  4960.5 2293.01
  4967.7 2293.37  4974.6 2292.72  4981.9 2290.39  4988.8 2288.96  4992.4 2284.60
  4998.4 2284.60  5003.9 2282.85  5004.2 2282.35  5007.7 2282.35  5007.9 2282.85
  5015.9 2282.93  5036.0 2285.49  5046.0 2287.01  5062.0 2290.54  5067.0 2291.02
  5146.3 2297.48  5194.2 2302.13  5216.5 2303.07  5226.5 2304.52  5251.3 2305.55
#Mann=3,-1,0
  4794.1    0.07       0  5003.9    0.07       0  5007.9    0.07       0
Bank Sta=5003.9,5007.9
Exp/Cntr=0.3,0.1

Type RM Length L Ch R = 1,2296,470,470,470
BEGIN DESCRIPTION:
COFFEE HOLLOW TRIBUTARY 2 5.0
END DESCRIPTION:
XS GIS Cut Line= 3
      1446354.98      6818588.01      1446579.08      6818417.41
      1446602.95      6818187.40
#Sta/Elev= 30
  4713.5 2296.84  4720.8 2296.56  4727.1 2295.57  4763.8 2293.42  4785.2 2291.00
  4820.6 2288.03  4841.4 2287.16  4876.9 2284.74  4885.0 2284.69  4920.4 2282.01
  4949.5 2280.80  4964.0 2278.16  4982.8 2277.03  4983.1 2276.53  4986.6 2276.53
  4986.8 2277.03  4997.4 2277.25  5001.8 2278.09  5006.8 2277.66  5024.7 2279.29
  5034.8 2281.94  5044.8 2283.78  5064.9 2284.92  5085.0 2286.93  5095.1 2287.25
  5100.5 2288.18  5115.2 2287.68  5135.3 2288.31  5205.7 2288.59  5226.4 2289.11
#Mann=3,-1,0
  4713.5    0.07       0  4982.8    0.07       0  4986.8    0.07       0
Bank Sta=4982.8,4986.8
Exp/Cntr=0.3,0.1

Type RM Length L Ch R = 1,1826,193,193,193
BEGIN DESCRIPTION:
COFFEE HOLLOW TRIBUTARY 2 4.0
END DESCRIPTION:
XS GIS Cut Line= 3
      1447086.90      6818808.05      1447005.00      6818538.00
      1446902.85      6818312.00
#Sta/Elev= 30
  4718.0 2286.44  4775.9 2284.53  4781.1 2285.18  4841.7 2283.26  4846.9 2283.62
  4853.9 2282.66  4879.8 2281.54  4906.1 2278.48  4912.7 2277.00  4927.0 2275.56
  4937.5 2273.73  4950.8 2271.15  4958.4 2267.02  4968.8 2265.01  4976.5 2264.50
  4976.8 2264.00  4980.3 2264.00  4980.5 2264.50  5002.9 2265.47  5009.0 2267.84
  5014.5 2268.26  5022.1 2270.71  5032.1 2272.20  5037.6 2272.39  5055.1 2275.76
  5153.2 2278.45  5187.3 2278.18  5197.7 2279.33  5204.9 2278.56  5248.2 2278.18
#Mann=3,-1,0
  4718.0    0.07       0  4976.5    0.07       0  4980.5    0.07       0
Bank Sta=4976.5,4980.5
Exp/Cntr=0.3,0.1

Type RM Length L Ch R = 1,1633,116,116,116
BEGIN DESCRIPTION:
Mapping XS c0b22cc3
END DESCRIPTION:
XS GIS Cut Line= 3
      1447356.01      6818829.76      1447145.49      6818452.14
      1446771.88      6818095.56
#Sta/Elev= 30
  4564.0 2279.15  4698.6 2280.08  4704.3 2280.84  4720.3 2281.05  4736.3 2280.17
  4742.1 2280.68  4772.1 2279.81  4779.8 2278.54  4801.5 2276.94  4807.2 2277.59
  4817.5 2276.08  4823.2 2276.45  4829.3 2274.70  4888.4 2266.96  4910.1 2265.88
  4947.8 2262.67  4967.5 2262.00  4967.7 2261.50  4971.5 2262.00  4991.2 2262.35
  5020.9 2264.26  5042.0 2267.41  5070.3 2272.93  5091.7 2274.17  5148.3 2275.34
  5289.5 2275.91  5445.2 2281.86  5459.3 2283.16  5501.8 2284.90  5512.8 2284.83
#Mann=3,-1,0
  4564.0    0.07       0  4967.5    0.07       0  4971.5    0.07       0
Bank Sta=4967.5,4971.5
Exp/Cntr=0.3,0.1

Type RM Length L Ch R = 1,1517,427,427,427
BEGIN DESCRIPTION:
COFFEE HOLLOW TRIBUTARY 2 3.0
END DESCRIPTION:
XS GIS Cut Line= 3
      1447464.48      6818710.36      1447234.79      6818387.65
      1446835.74      6818029.21
#Sta/Elev= 30
  4603.9 2275.43  4741.8 2278.07  4784.4 2277.28  4834.8 2269.86  4841.0 2266.69
  4849.6 2265.93  4855.7 2266.76  4864.4 2265.30  4870.5 2266.89  4876.8 2263.50
  4885.3 2262.07  4891.4 2262.13  4900.0 2260.29  4906.2 2262.02  4911.7 2260.17
  4911.9 2259.67  4915.7 2260.17  5003.2 2264.65  5006.7 2265.86  5027.6 2267.40
  5049.3 2271.27  5056.0 2270.37  5141.3 2271.74  5233.2 2271.29  5304.2 2274.99
  5396.2 2275.42  5417.1 2276.66  5424.6 2278.84  5438.8 2280.54  5536.4 2283.95
#Mann=3,-1,0
  4603.9    0.07       0  4911.7    0.07       0  4915.7    0.07       0
Bank Sta=4911.7,4915.7
Exp/Cntr=0.3,0.1

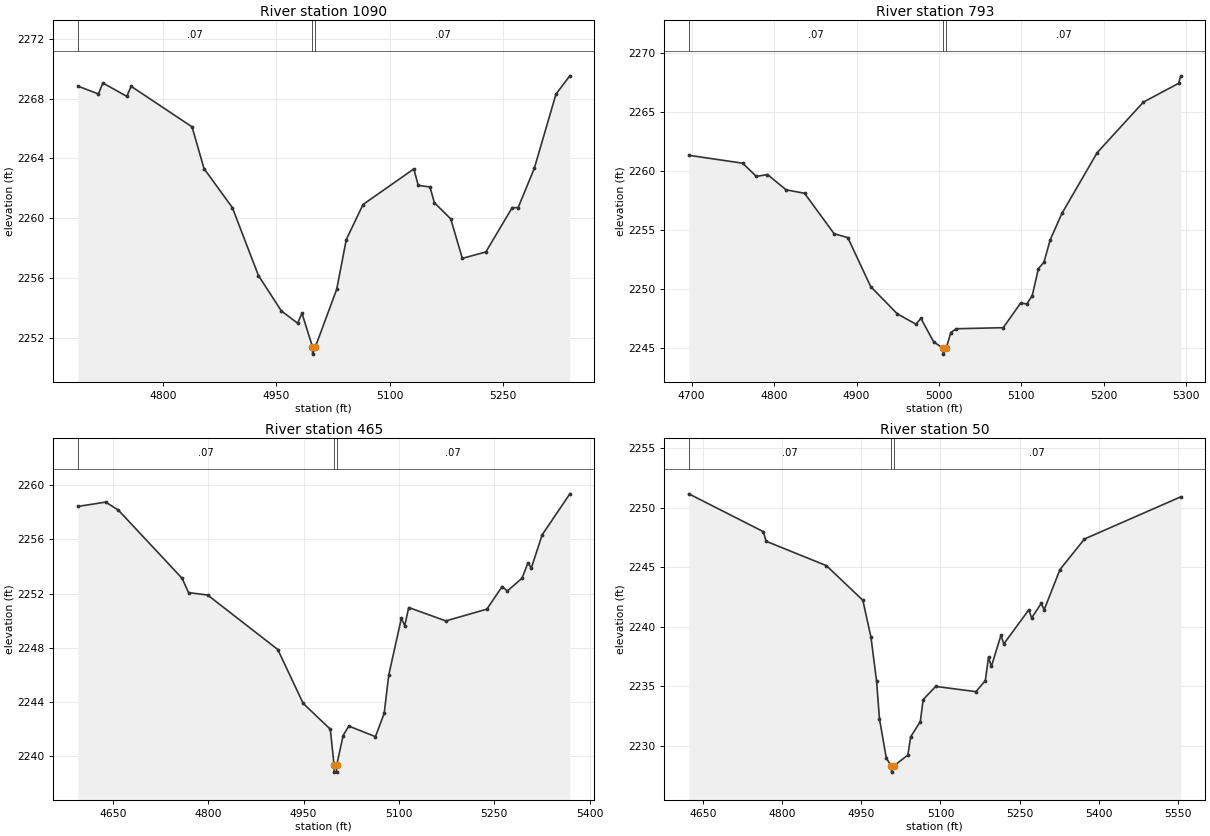
Type RM Length L Ch R = 1,1090,297,297,297
BEGIN DESCRIPTION:
Mapping XS 2455ec50
END DESCRIPTION:
XS GIS Cut Line= 3
      1447683.68      6818486.42      1447527.43      6818210.38
      1447239.22      6818039.01
#Sta/Elev= 30
  4686.6 2268.83  4713.9 2268.31  4719.7 2269.04  4751.5 2268.15  4757.2 2268.82
  4838.0 2266.11  4853.9 2263.32  4891.5 2260.71  4926.1 2256.17  4956.4 2253.81
  4978.0 2252.99  4983.8 2253.65  4997.7 2251.42  4997.9 2250.92  5001.7 2251.42
  5029.9 2255.26  5042.6 2258.58  5064.8 2260.92  5132.2 2263.30  5138.0 2262.20
  5153.6 2262.09  5159.4 2261.04  5181.1 2259.96  5196.5 2257.32  5227.7 2257.75
  5262.6 2260.71  5270.5 2260.71  5291.9 2263.33  5320.7 2268.30  5339.1 2269.52
#Mann=3,-1,0
  4686.6    0.07       0  4997.7    0.07       0  5001.7    0.07       0
Bank Sta=4997.7,5001.7
Exp/Cntr=0.3,0.1

Type RM Length L Ch R = 1,793,328,328,328
BEGIN DESCRIPTION:
Mapping XS a0b9b7c4
END DESCRIPTION:
XS GIS Cut Line= 3
      1447878.99      6818272.87      1447740.98      6818004.65
      1447518.53      6817810.66
#Sta/Elev= 30
  4696.6 2261.33  4761.9 2260.66  4778.5 2259.54  4792.0 2259.70  4814.5 2258.41
  4837.0 2258.11  4872.8 2254.69  4889.4 2254.36  4917.2 2250.21  4949.5 2247.90
  4972.0 2247.03  4978.1 2247.52  4993.5 2245.54  5004.8 2244.99  5005.0 2244.49
  5008.8 2244.99  5014.4 2246.32  5021.0 2246.64  5078.0 2246.73  5099.1 2248.82
  5106.5 2248.74  5113.1 2249.43  5120.7 2251.74  5127.3 2252.26  5135.0 2254.18
  5149.2 2256.41  5191.9 2261.55  5247.9 2265.83  5290.6 2267.42  5293.4 2268.06
#Mann=3,-1,0
  4696.6    0.07       0  5004.8    0.07       0  5008.8    0.07       0
Bank Sta=5004.8,5008.8
Exp/Cntr=0.3,0.1

Type RM Length L Ch R = 1,465,415,415,415
BEGIN DESCRIPTION:
Mapping XS 02f86d43
END DESCRIPTION:
XS GIS Cut Line= 3
      1447951.92      6818241.67      1447925.87      6817848.40
      1447811.29      6817486.43
#Sta/Elev= 30
  4595.0 2258.44  4638.8 2258.76  4658.8 2258.16  4759.0 2253.13  4769.0 2252.08
  4799.1 2251.90  4909.4 2247.88  4949.4 2243.90  4992.0 2242.00  4998.0 2239.33
  4998.3 2238.83  5001.8 2238.83  5002.0 2239.33  5012.2 2241.53  5021.0 2242.23
  5063.0 2241.45  5076.8 2243.18  5083.9 2245.99  5103.8 2250.19  5109.1 2249.64
  5115.4 2250.98  5173.7 2249.99  5238.3 2250.86  5262.3 2252.53  5270.6 2252.20
  5293.7 2253.15  5302.9 2254.29  5308.1 2253.88  5325.2 2256.34  5368.8 2259.37
#Mann=3,-1,0
  4595.0    0.07       0  4998.0    0.07       0  5002.0    0.07       0
Bank Sta=4998,5002
Exp/Cntr=0.3,0.1

Type RM Length L Ch R = 1,50,0,0,0
BEGIN DESCRIPTION:
COFFEE HOLLOW TRIBUTARY 2 1.0
END DESCRIPTION:
XS GIS Cut Line= 3
      1448183.99      6818294.55      1448304.95      6817938.11
      1448087.63      6817427.43
#Sta/Elev= 30
  4623.6 2251.18  4764.6 2248.00  4769.9 2247.19  4884.0 2245.14  4953.0 2242.23
  4968.4 2239.12  4979.0 2235.43  4984.4 2232.28  4997.4 2228.95  5007.1 2228.27
  5007.4 2227.77  5011.1 2228.27  5038.2 2229.21  5043.6 2230.75  5061.8 2232.02
  5067.2 2233.87  5090.9 2234.98  5167.2 2234.54  5184.9 2235.47  5190.9 2237.43
  5196.3 2236.66  5214.5 2239.28  5219.9 2238.56  5267.2 2241.42  5272.6 2240.74
  5290.8 2241.97  5296.3 2241.43  5326.2 2244.81  5372.6 2247.38  5555.0 2250.93
#Mann=3,-1,0
  4623.6    0.07       0  5007.1    0.07       0  5011.1    0.07       0
Bank Sta=5007.1,5011.1
Exp/Cntr=0.3,0.1

Chan Stop Cuts=-1