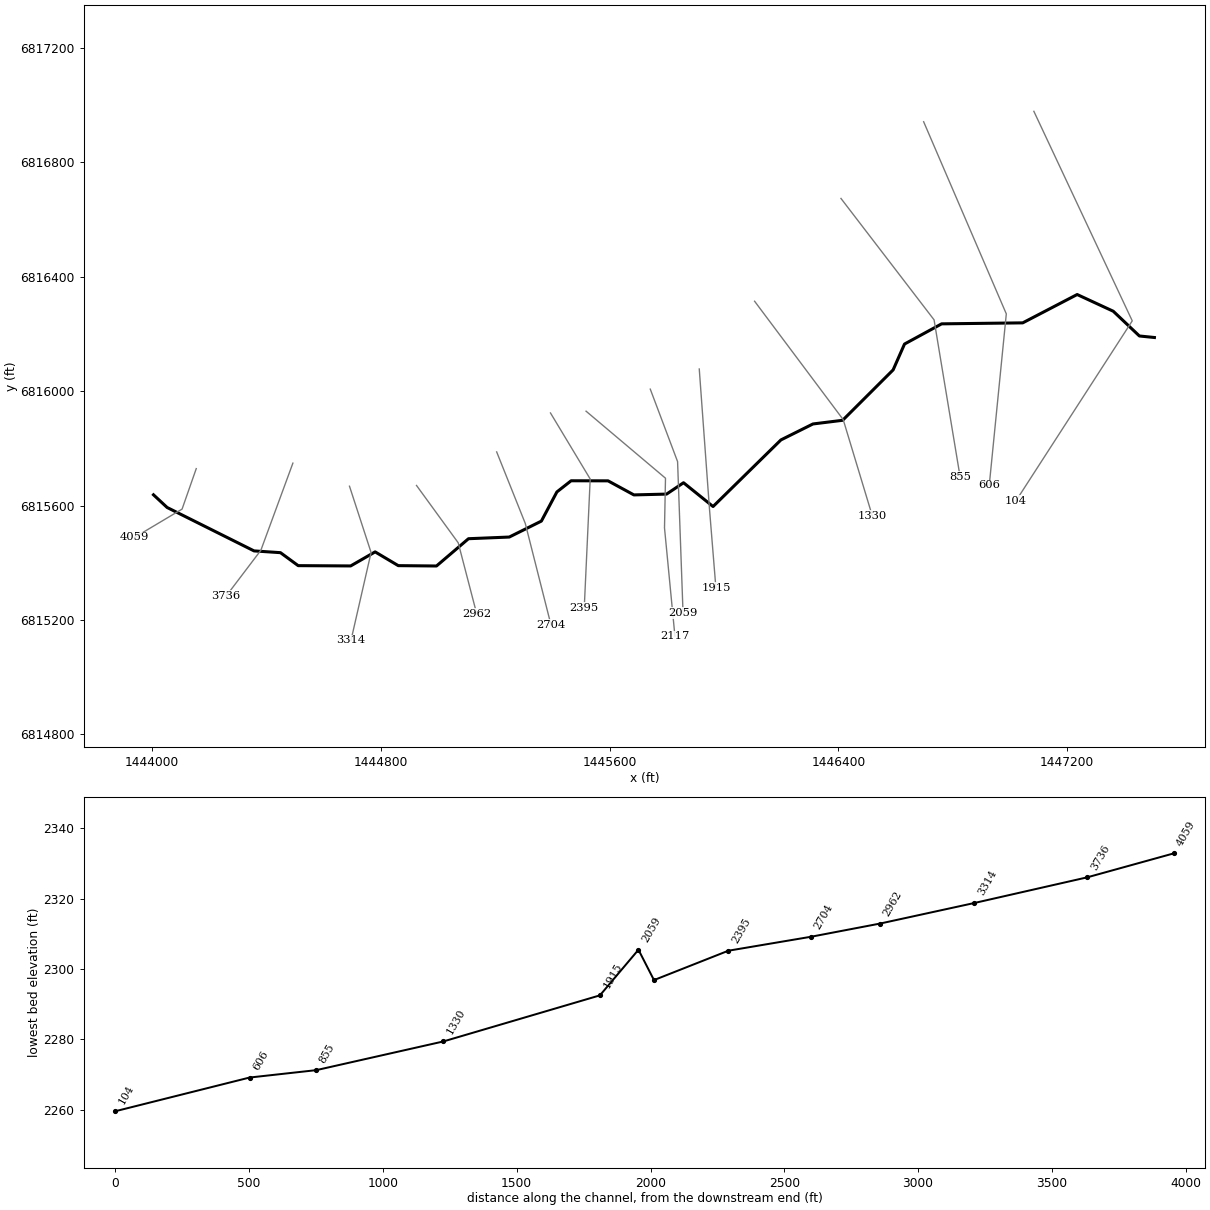
--- COFFEE HOLLOW TRIBUTARY 3.prj (project) ---

Proj Title=COFFEE HOLLOW TRIBUTARY 3 Base Level Engineering
Current Plan=p01
Default Exp/Contr=0.3,0.1
English Units
Geom File=g01
Flow File=f01
Plan File=p01
BEGIN DESCRIPTION:
COFFEE HOLLOW TRIBUTARY 3
END DESCRIPTION:

--- COFFEE HOLLOW TRIBUTARY 3.p01 (plan) ---

Plan Title=Multiple Run
Short Identifier=Multiple
Geom File=g01
Flow File=f01
Subcritical Flow
K Sum by GR= 0
Std Step Tol= 0.01
Critical Tol= 0.01
Num of Std Step Trials= 20
Max Error Tol= 0.3
Flow Tol Ratio= 0.001
Split Flow NTrial= 30
Split Flow Tol= 0.02
Split Flow Ratio= 0.02
Log Output Level= 0
Friction Slope Method= 1
Unsteady Friction Slope Method= 2
Unsteady Bridges Friction Slope Method= 1
Parabolic Critical Depth
Global Vel Dist=  1 , 1 , 1
Global Log Level= 0
CheckData=True
Encroach Param= -1, 0, 0, 0
BEGIN DESCRIPTION:
Multiple Run
END DESCRIPTION:

--- COFFEE HOLLOW TRIBUTARY 3.f01 (steady flow) ---

Flow Title=Multiple
Number of Profiles=7
Profile Names=10-year,25-year,50-year,1pct_min,100-year,1pct_plu,500-year
River Rch & RM= COFFEE HOLLOW TR,Reach-1,4059
     257     364     455     284     566    1130     886
Boundary for River Rch & Prof#=COFFEE HOLLOW TR,Reach-1,1
Up Type=0
Dn Type=3
Dn Slope=0.005
Boundary for River Rch & Prof#=COFFEE HOLLOW TR,Reach-1,2
Up Type=0
Dn Type=3
Dn Slope=0.005
Boundary for River Rch & Prof#=COFFEE HOLLOW TR,Reach-1,3
Up Type=0
Dn Type=3
Dn Slope=0.005
Boundary for River Rch & Prof#=COFFEE HOLLOW TR,Reach-1,4
Up Type=0
Dn Type=3
Dn Slope=0.005
Boundary for River Rch & Prof#=COFFEE HOLLOW TR,Reach-1,5
Up Type=0
Dn Type=3
Dn Slope=0.005
Boundary for River Rch & Prof#=COFFEE HOLLOW TR,Reach-1,6
Up Type=0
Dn Type=3
Dn Slope=0.005
Boundary for River Rch & Prof#=COFFEE HOLLOW TR,Reach-1,7
Up Type=0
Dn Type=3
Dn Slope=0.005

--- COFFEE HOLLOW TRIBUTARY 3.g01 (geometry) ---

Geom Title=Existing Conditions

River Reach=COFFEE HOLLOW TR,Reach-1
Reach XY= 30
      1444005.00      6815638.00      1444052.64      6815593.67
      1444356.58      6815441.83      1444449.02      6815435.64
      1444510.94      6815390.26      1444694.50      6815389.24
      1444780.00      6815438.40      1444860.93      6815390.28
      1444994.56      6815389.04      1445106.47      6815484.44
      1445249.07      6815490.25      1445361.34      6815546.02
      1445415.63      6815648.04      1445465.29      6815687.03
      1445594.49      6815686.79      1445684.87      6815637.61
      1445799.14      6815640.46      1445858.42      6815680.18
      1445961.67      6815596.97      1446198.94      6815829.86
      1446310.97      6815885.67      1446414.79      6815898.52
      1446591.36      6816074.80      1446631.16      6816165.15
      1446760.93      6816235.76      1447044.50      6816239.20
      1447234.82      6816338.30      1447361.05      6816279.86
      1447452.49      6816193.33      1447505.00      6816188.00

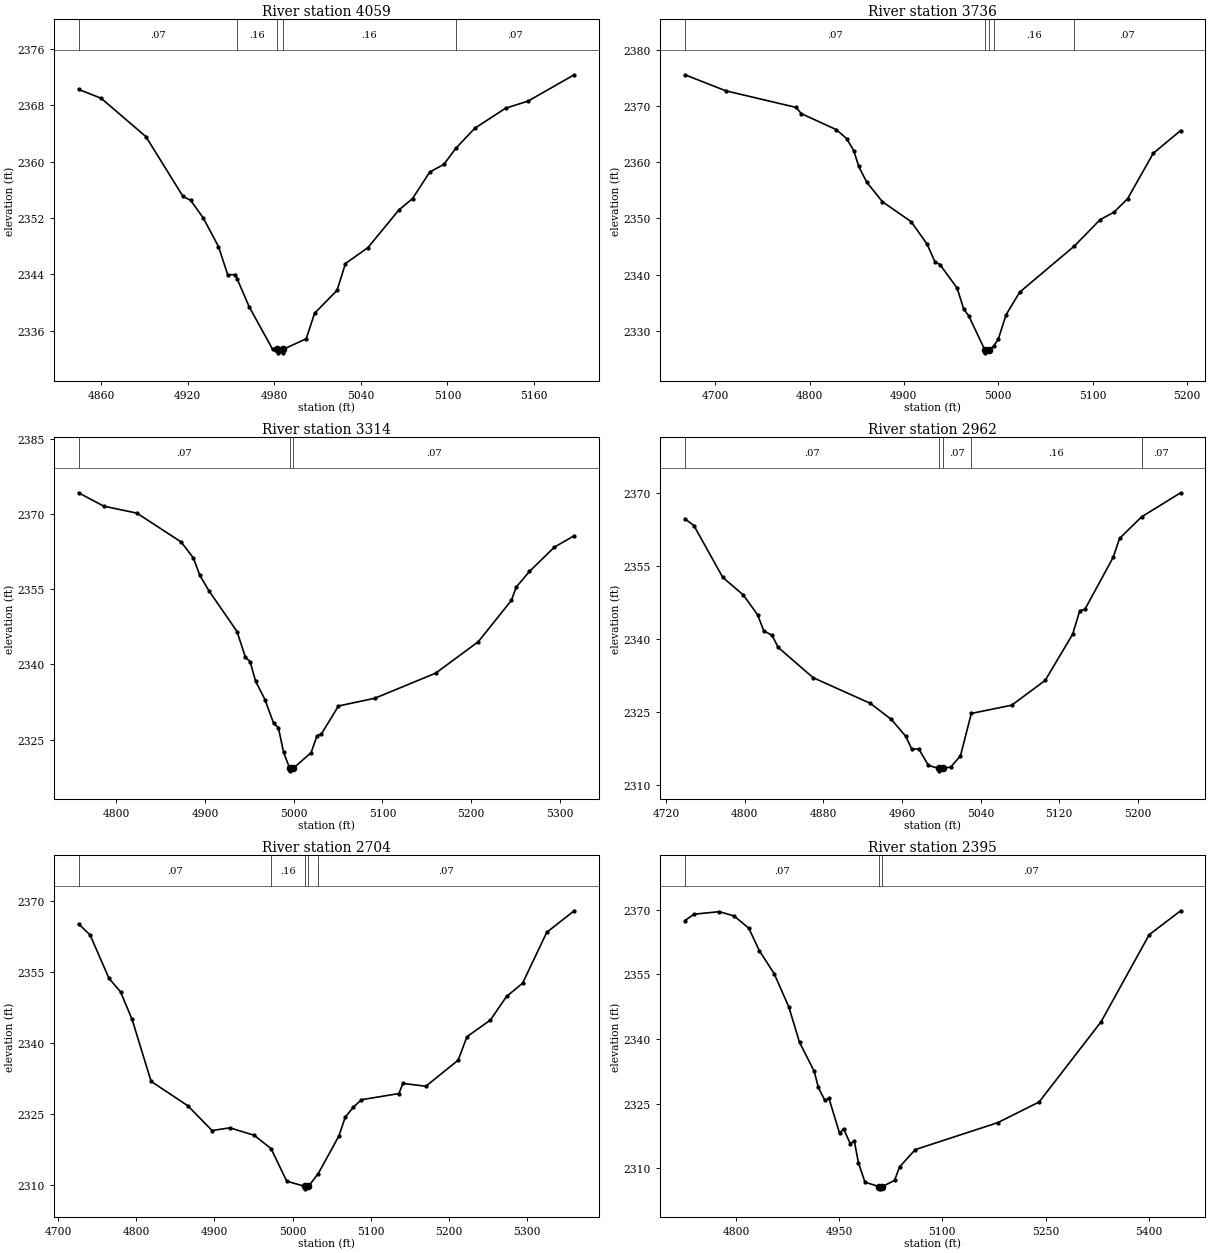
Type RM Length L Ch R = 1,4059,323,323,323
BEGIN DESCRIPTION:
COFFEE HOLLOW TRIBUTARY 3 9.0
END DESCRIPTION:
XS GIS Cut Line= 3
      1444154.55      6815729.56      1444105.00      6815588.00
      1443938.74      6815488.97
#Sta/Elev= 30
  4844.3 2370.24  4860.0 2368.98  4891.0 2363.54  4916.7 2355.06  4922.0 2354.51
  4930.7 2352.01  4941.3 2347.95  4947.7 2343.95  4953.0 2343.96  4954.3 2343.34
  4962.5 2339.43  4978.8 2333.38  4982.1 2333.37  4982.3 2332.87  4985.8 2332.87
  4986.1 2333.37  5002.1 2334.86  5007.9 2338.48  5023.5 2341.74  5029.3 2345.54
  5044.9 2347.80  5066.3 2353.13  5075.8 2354.75  5087.7 2358.51  5097.5 2359.60
  5105.7 2361.86  5118.9 2364.72  5140.3 2367.57  5155.9 2368.58  5187.8 2372.31
#Mann=5,-1,0
  4844.3    0.07       0  4954.3    0.16       0  4982.1    0.07       0
  4986.1    0.16       0  5105.7    0.07       0
Bank Sta=4982.1,4986.1
Exp/Cntr=0.3,0.1

Type RM Length L Ch R = 1,3736,422,422,422
BEGIN DESCRIPTION:
Mapping XS e889ee94
END DESCRIPTION:
XS GIS Cut Line= 3
      1444492.48      6815748.76      1444380.49      6815444.04
      1444259.21      6815284.06
#Sta/Elev= 30
  4668.0 2375.55  4711.4 2372.69  4785.9 2369.74  4791.2 2368.65  4828.6 2365.77
  4839.3 2364.20  4846.9 2362.05  4852.2 2359.25  4860.6 2356.45  4877.3 2352.96
  4907.8 2349.40  4924.5 2345.45  4933.0 2342.27  4938.3 2341.78  4956.5 2337.58
  4963.4 2333.89  4968.8 2332.65  4985.9 2326.57  4986.1 2326.07  4989.9 2326.57
  4995.1 2327.22  5000.2 2328.56  5008.3 2332.82  5022.8 2336.87  5080.6 2345.05
  5108.1 2349.77  5122.7 2351.09  5137.2 2353.50  5164.3 2361.56  5193.4 2365.63
#Mann=5,-1,0
  4668.0    0.07       0  4985.9    0.07       0  4989.9    0.07       0
  4995.1    0.16       0  5080.6    0.07       0
Bank Sta=4985.9,4989.9
Exp/Cntr=0.3,0.1

Type RM Length L Ch R = 1,3314,352,352,352
BEGIN DESCRIPTION:
Mapping XS 078458be
END DESCRIPTION:
XS GIS Cut Line= 3
      1444690.39      6815667.97      1444765.90      6815436.23
      1444695.58      6815128.90
#Sta/Elev= 30
  4757.3 2374.28  4785.9 2371.60  4823.1 2370.22  4873.0 2364.47  4886.9 2361.25
  4894.0 2357.84  4904.5 2354.69  4936.1 2346.58  4945.5 2341.45  4950.8 2340.58
  4957.1 2336.62  4967.6 2332.99  4977.4 2328.23  4982.7 2327.40  4988.6 2322.46
  4995.5 2319.27  4995.7 2318.77  4999.5 2319.27  5019.7 2322.42  5026.2 2325.75
  5031.3 2326.16  5050.5 2331.72  5091.5 2333.26  5160.1 2338.27  5208.2 2344.55
  5245.4 2352.78  5251.1 2355.47  5265.9 2358.58  5294.0 2363.43  5316.3 2365.70
#Mann=3,-1,0
  4757.3    0.07       0  4995.5    0.07       0  4999.5    0.07       0
Bank Sta=4995.5,4999.5
Exp/Cntr=0.3,0.1

Type RM Length L Ch R = 1,2962,258,258,258
BEGIN DESCRIPTION:
Mapping XS 6d9660d2
END DESCRIPTION:
XS GIS Cut Line= 3
      1444924.77      6815670.59      1445070.59      6815470.08
      1445135.33      6815221.50
#Sta/Elev= 30
  4739.0 2364.70  4748.1 2363.32  4777.5 2352.67  4798.4 2349.07  4813.1 2344.96
  4819.2 2341.69  4827.7 2340.78  4833.9 2338.29  4869.5 2332.07  4927.7 2326.80
  4949.1 2323.51  4963.8 2320.04  4969.9 2317.41  4977.1 2317.43  4986.9 2314.05
  4997.4 2313.43  4997.7 2312.93  5001.4 2313.43  5009.7 2313.71  5019.6 2316.02
  5030.6 2324.72  5071.8 2326.42  5105.8 2331.50  5133.8 2340.98  5141.1 2345.84
  5146.3 2346.11  5175.1 2356.80  5181.6 2360.68  5204.0 2365.11  5243.8 2370.06
#Mann=5,-1,0
  4739.0    0.07       0  4997.4    0.07       0  5001.4    0.07       0
  5030.6    0.16       0  5204.0    0.07       0
Bank Sta=4997.4,5001.4
Exp/Cntr=0.3,0.1

Type RM Length L Ch R = 1,2704,309,309,309
BEGIN DESCRIPTION:
COFFEE HOLLOW TRIBUTARY 3 6.0
END DESCRIPTION:
XS GIS Cut Line= 3
      1445205.02      6815787.96      1445305.00      6815538.00
      1445394.71      6815184.01
#Sta/Elev= 30
  4726.1 2365.16  4740.9 2362.83  4765.1 2353.65  4779.9 2350.81  4794.7 2344.97
  4819.0 2331.89  4866.1 2326.72  4897.0 2321.50  4919.9 2322.07  4950.9 2320.50
  4972.6 2317.67  4992.6 2310.79  5016.4 2309.68  5016.6 2309.18  5020.4 2309.68
  5033.0 2312.42  5059.4 2320.36  5067.5 2324.32  5077.8 2326.42  5088.2 2328.01
  5136.2 2329.31  5141.3 2331.45  5170.7 2330.86  5212.0 2336.36  5223.3 2341.33
  5253.2 2344.83  5273.9 2349.82  5294.5 2352.63  5325.4 2363.37  5360.5 2367.93
#Mann=5,-1,0
  4726.1    0.07       0  4972.6    0.16       0  5016.4    0.07       0
  5020.4    0.16       0  5033.0    0.07       0
Bank Sta=5016.4,5020.4
Exp/Cntr=0.3,0.1

Type RM Length L Ch R = 1,2395,278,278,278
BEGIN DESCRIPTION:
Mapping XS 00325ba9
END DESCRIPTION:
XS GIS Cut Line= 3
      1445393.18      6815924.16      1445532.07      6815693.26
      1445511.26      6815242.40
#Sta/Elev= 30
  4725.7 2367.48  4738.8 2368.94  4775.7 2369.54  4797.1 2368.53  4818.5 2365.69
  4834.0 2360.43  4855.4 2355.15  4876.8 2347.38  4892.3 2339.19  4913.7 2332.47
  4919.6 2328.74  4929.2 2325.72  4935.0 2326.25  4950.6 2318.06  4956.4 2319.16
  4966.1 2315.65  4971.9 2316.37  4978.0 2311.21  4987.5 2306.75  5008.4 2305.71
  5008.7 2305.21  5012.4 2305.71  5030.5 2307.17  5037.7 2310.27  5060.5 2314.31
  5180.6 2320.57  5240.7 2325.37  5330.8 2343.98  5400.8 2364.19  5446.5 2369.74
#Mann=3,-1,0
  4725.7    0.07       0  5008.4    0.07       0  5012.4    0.07       0
Bank Sta=5008.4,5012.4
Exp/Cntr=0.3,0.1

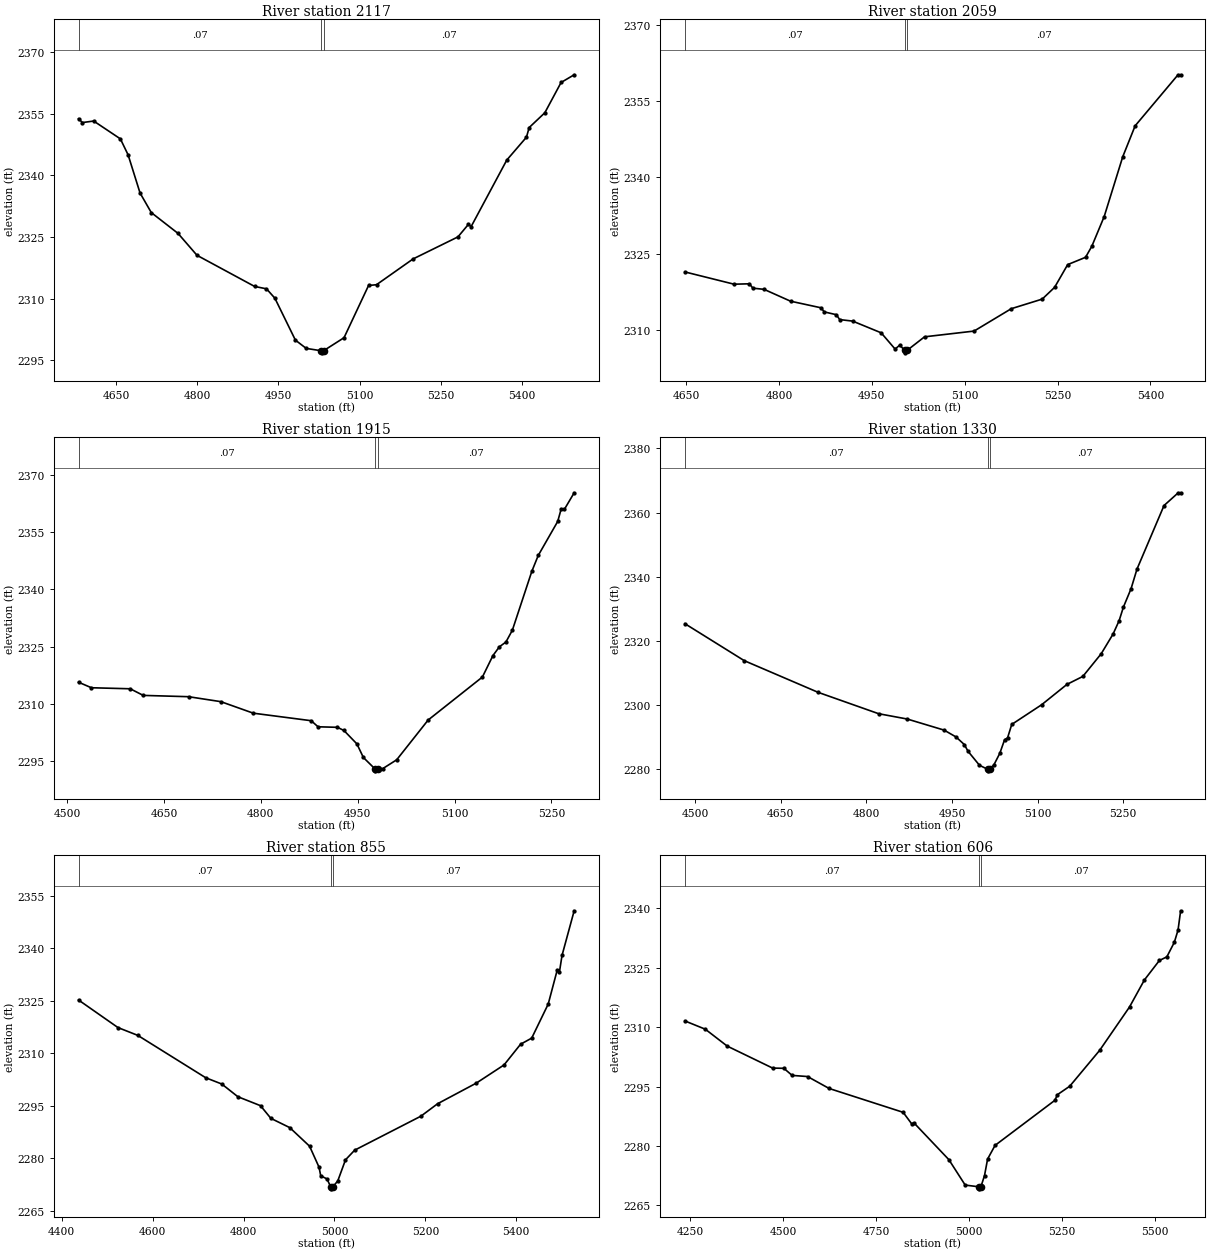
Type RM Length L Ch R = 1,2117,58,58,58
BEGIN DESCRIPTION:
COFFEE HOLLOW TRIBUTARY 3 5.0
END DESCRIPTION:
XS GIS Cut Line= 4
      1445517.60      6815930.35      1445795.36      6815695.99
      1445791.89      6815522.38      1445828.35      6815143.90
#Sta/Elev= 30
  4579.9 2353.78  4587.2 2352.87  4608.0 2353.24  4657.4 2348.90  4671.7 2345.01
  4693.8 2335.73  4714.6 2330.97  4764.0 2325.92  4799.2 2320.58  4905.8 2313.01
  4927.8 2312.43  4943.3 2310.15  4981.3 2299.95  5001.3 2297.94  5029.3 2297.36
  5029.6 2296.86  5033.3 2297.36  5071.3 2300.54  5116.7 2313.24  5131.4 2313.43
  5199.1 2319.70  5282.1 2325.06  5301.5 2328.11  5306.5 2327.56  5372.5 2343.75
  5408.9 2349.31  5413.9 2351.65  5442.9 2355.25  5473.0 2362.62  5497.2 2364.49
#Mann=3,-1,0
  4579.9    0.07       0  5029.3    0.07       0  5033.3    0.07       0
Bank Sta=5029.3,5033.3
Exp/Cntr=0.3,0.1

Type RM Length L Ch R = 1,2059,144,144,144
BEGIN DESCRIPTION:
Mapping XS 54f374b4
END DESCRIPTION:
XS GIS Cut Line= 3
      1445742.13      6816007.51      1445837.62      6815754.03
      1445856.72      6815224.54
#Sta/Elev= 30
  4648.1 2321.40  4727.4 2318.99  4752.3 2319.07  4757.7 2318.21  4775.8 2317.98
  4818.6 2315.65  4867.8 2314.35  4873.2 2313.54  4892.7 2312.99  4898.0 2312.03
  4919.0 2311.73  4965.0 2309.43  4987.5 2306.24  4995.0 2306.99  5003.1 2305.99
  5003.3 2305.49  5007.1 2305.99  5035.1 2308.64  5115.1 2309.77  5175.2 2314.17
  5225.2 2316.06  5245.2 2318.37  5266.3 2322.84  5295.2 2324.28  5305.3 2326.44
  5325.3 2332.29  5355.3 2344.06  5375.3 2350.14  5444.6 2360.18  5448.8 2360.18
#Mann=3,-1,0
  4648.1    0.07       0  5003.1    0.07       0  5007.1    0.07       0
Bank Sta=5003.1,5007.1
Exp/Cntr=0.3,0.1

Type RM Length L Ch R = 1,1915,585,585,585
BEGIN DESCRIPTION:
Mapping XS 9445efb5
END DESCRIPTION:
XS GIS Cut Line= 3
      1445913.42      6816077.91      1445949.06      6815590.05
      1445971.60      6815312.63
#Sta/Elev= 30
  4517.7 2315.70  4537.7 2314.25  4597.8 2313.98  4617.9 2312.25  4688.1 2311.91
  4738.2 2310.61  4788.3 2307.60  4878.0 2305.63  4888.6 2304.04  4918.7 2303.90
  4928.7 2303.07  4948.8 2299.56  4958.8 2296.01  4976.8 2293.02  4977.1 2292.52
  4980.8 2293.02  4988.9 2293.11  5010.4 2295.41  5059.1 2305.81  5143.1 2317.05
  5159.4 2322.66  5169.4 2324.96  5179.5 2326.20  5189.5 2329.30  5219.6 2344.68
  5229.6 2348.86  5259.7 2357.74  5265.1 2361.01  5270.1 2360.92  5285.2 2365.24
#Mann=3,-1,0
  4517.7    0.07       0  4976.8    0.07       0  4980.8    0.07       0
Bank Sta=4976.8,4980.8
Exp/Cntr=0.3,0.1

Type RM Length L Ch R = 1,1330,475,475,475
BEGIN DESCRIPTION:
Mapping XS 7b5d1695
END DESCRIPTION:
XS GIS Cut Line= 3
      1446106.90      6816314.84      1446416.77      6815900.81
      1446518.34      6815564.87
#Sta/Elev= 30
  4482.3 2325.31  4586.1 2313.79  4715.3 2303.92  4821.5 2297.24  4871.6 2295.58
  4936.2 2292.12  4957.0 2289.99  4971.6 2287.61  4978.0 2285.53  4998.1 2281.15
  5012.3 2279.92  5012.6 2279.42  5016.3 2279.92  5023.3 2281.27  5033.7 2284.88
  5042.0 2289.10  5047.3 2289.71  5054.6 2293.90  5106.9 2300.03  5151.3 2306.39
  5179.1 2308.87  5211.3 2315.95  5232.2 2322.13  5242.7 2326.28  5250.2 2330.51
  5263.6 2336.25  5274.0 2342.37  5321.3 2362.18  5346.2 2366.16  5350.4 2366.16
#Mann=3,-1,0
  4482.3    0.07       0  5012.3    0.07       0  5016.3    0.07       0
Bank Sta=5012.3,5016.3
Exp/Cntr=0.3,0.1

Type RM Length L Ch R = 1,855,249,249,249
BEGIN DESCRIPTION:
Mapping XS a1de0b95
END DESCRIPTION:
XS GIS Cut Line= 3
      1446408.98      6816674.23      1446734.48      6816249.77
      1446825.40      6815701.66
#Sta/Elev= 30
  4436.8 2325.22  4523.6 2317.34  4567.2 2315.11  4716.7 2303.00  4752.0 2301.21
  4787.4 2297.58  4837.2 2295.02  4860.0 2291.40  4901.6 2288.75  4945.2 2283.44
  4966.0 2277.44  4969.7 2274.99  4983.6 2274.08  4991.8 2271.76  4992.0 2271.26
  4995.8 2271.76  5007.2 2273.52  5024.2 2279.55  5044.4 2282.31  5190.1 2292.02
  5226.9 2295.58  5312.0 2301.47  5373.0 2306.66  5409.4 2312.58  5433.9 2314.33
  5470.2 2324.05  5489.8 2333.67  5494.9 2333.22  5500.6 2337.96  5527.3 2350.71
#Mann=3,-1,0
  4436.8    0.07       0  4991.8    0.07       0  4995.8    0.07       0
Bank Sta=4991.8,4995.8
Exp/Cntr=0.3,0.1

Type RM Length L Ch R = 1,606,502,502,502
BEGIN DESCRIPTION:
Mapping XS 1e581f18
END DESCRIPTION:
XS GIS Cut Line= 3
      1446698.04      6816942.45      1446987.08      6816270.61
      1446927.39      6815671.05
#Sta/Elev= 30
  4235.6 2311.57  4290.3 2309.49  4349.3 2305.22  4471.4 2299.67  4501.7 2299.61
  4523.9 2297.82  4565.5 2297.53  4623.5 2294.52  4822.7 2288.49  4846.2 2285.52
  4851.7 2285.84  4945.8 2276.53  4989.7 2270.11  5027.9 2269.66  5028.1 2269.16
  5031.9 2269.66  5041.7 2272.51  5050.0 2276.69  5070.1 2280.14  5230.9 2291.51
  5238.1 2292.96  5271.1 2295.09  5351.5 2304.14  5431.9 2315.10  5472.1 2321.95
  5512.3 2326.85  5532.4 2327.77  5552.5 2331.44  5562.5 2334.53  5569.5 2339.41
#Mann=3,-1,0
  4235.6    0.07       0  5027.9    0.07       0  5031.9    0.07       0
Bank Sta=5027.9,5031.9
Exp/Cntr=0.3,0.1

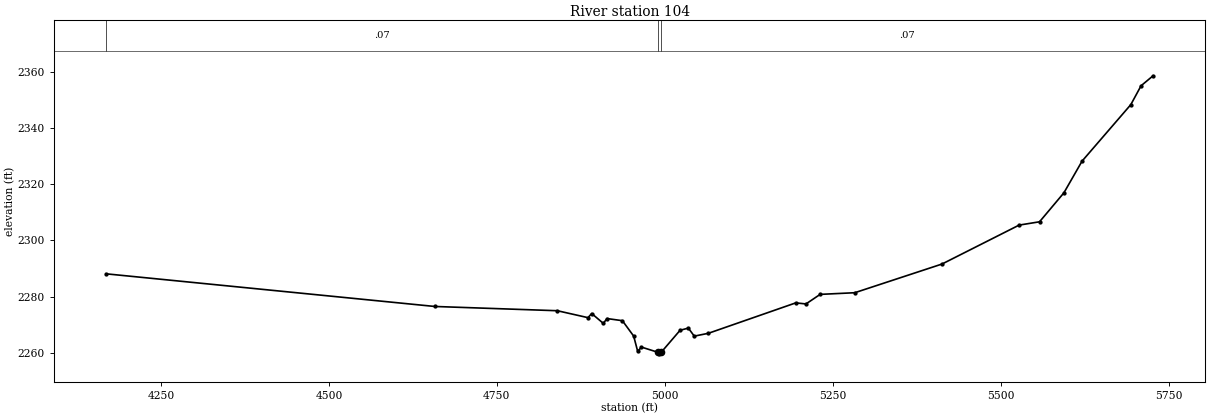
Type RM Length L Ch R = 1,104,0,0,0
BEGIN DESCRIPTION:
COFFEE HOLLOW TRIBUTARY 3 1.0
END DESCRIPTION:
XS GIS Cut Line= 3
      1447083.46      6816978.90      1447427.47      6816246.21
      1447020.93      6815616.94
#Sta/Elev= 30
  4168.3 2288.11  4657.6 2276.47  4840.1 2274.95  4885.7 2272.48  4891.2 2273.96
  4908.5 2270.44  4914.0 2272.16  4936.9 2271.40  4953.7 2265.91  4959.7 2260.45
  4965.2 2261.99  4990.5 2260.08  4990.7 2259.58  4994.5 2260.08  5022.8 2267.98
  5035.1 2268.76  5043.9 2265.89  5065.0 2266.91  5195.0 2277.75  5210.2 2277.37
  5231.3 2280.78  5282.8 2281.37  5412.7 2291.60  5527.5 2305.48  5557.9 2306.66
  5594.2 2317.00  5621.2 2328.29  5693.8 2348.44  5709.0 2355.15  5726.9 2358.72
#Mann=3,-1,0
  4168.3    0.07       0  4990.5    0.07       0  4994.5    0.07       0
Bank Sta=4990.5,4994.5
Exp/Cntr=0.3,0.1

Chan Stop Cuts=-1