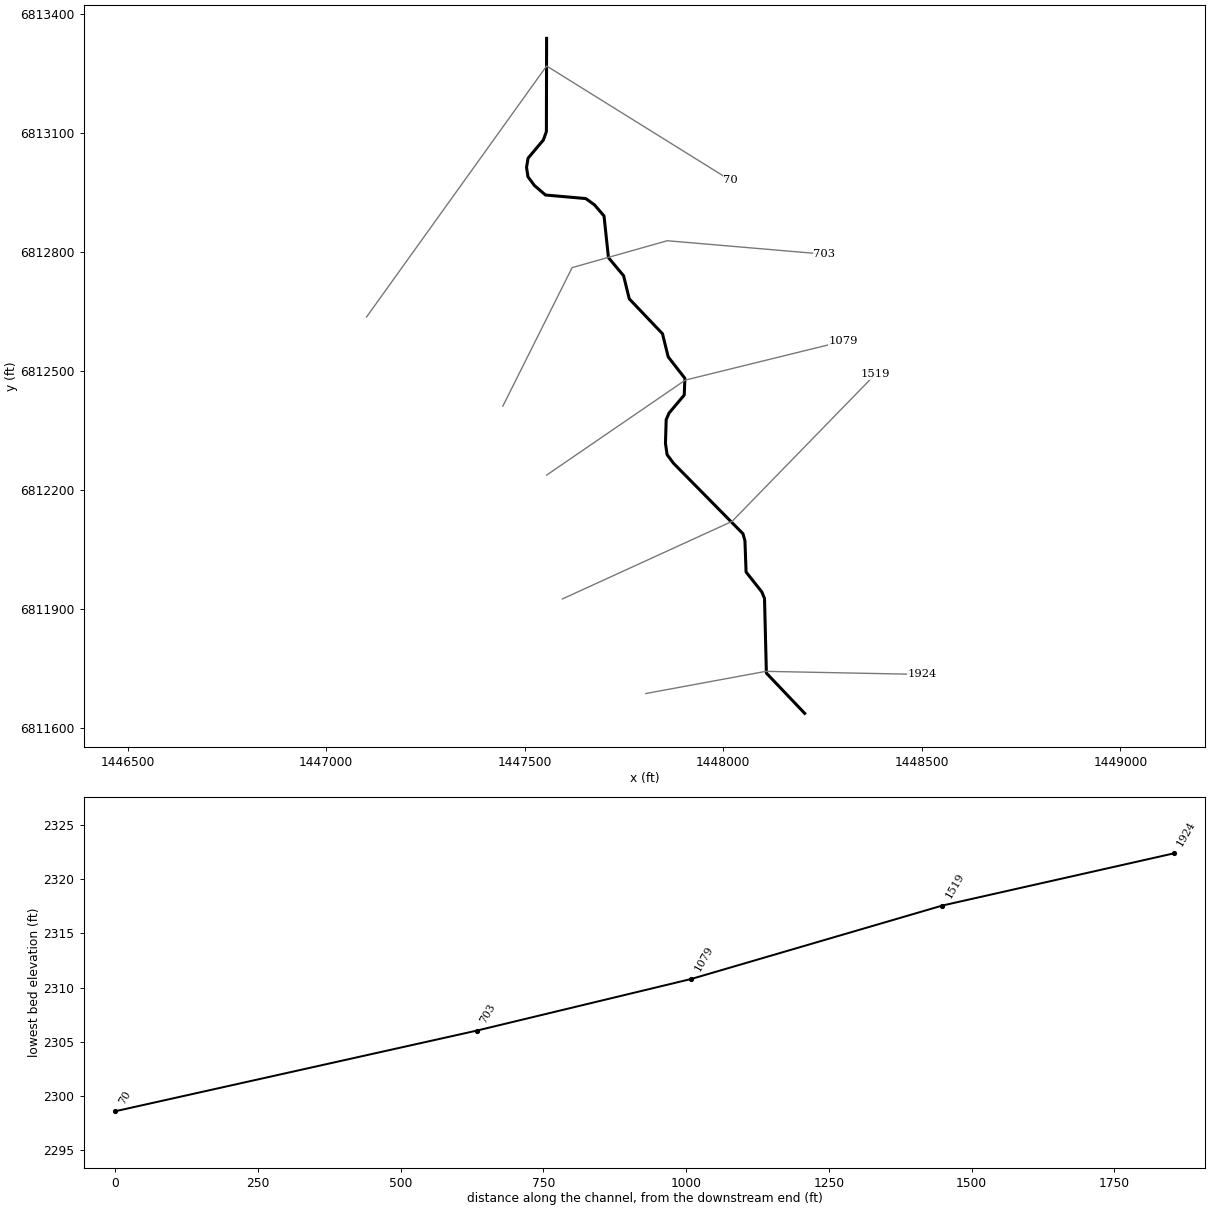
--- COFFEE HOLLOW TRIBUTARY 4.prj (project) ---

Proj Title=COFFEE HOLLOW TRIBUTARY 4 Base Level Engineering
Current Plan=p01
Default Exp/Contr=0.3,0.1
English Units
Geom File=g01
Flow File=f01
Plan File=p01
Y Axis Title=Elevation
X Axis Title(PF)=Main Channel Distance
X Axis Title(XS)=Station
BEGIN DESCRIPTION:
COFFEE HOLLOW TRIBUTARY 4
END DESCRIPTION:
DSS Export Rating Curves= 0
DSS Export Rating Curve Sorted= 0
DSS Export Volume Flow Curves= 0
DXF OffsetX= 0
DXF OffsetY= 0
DXF ScaleX= 1
DXF ScaleY= 10

--- COFFEE HOLLOW TRIBUTARY 4.p01 (plan) ---

Plan Title=Multiple Run
Short Identifier=Multiple
Geom File=g01
Flow File=f01
Subcritical Flow
K Sum by GR= 0
Std Step Tol= 0.01
Critical Tol= 0.01
Num of Std Step Trials= 20
Max Error Tol= 0.3
Flow Tol Ratio= 0.001
Split Flow NTrial= 30
Split Flow Tol= 0.02
Split Flow Ratio= 0.02
Log Output Level= 0
Friction Slope Method= 1
Unsteady Friction Slope Method= 2
Unsteady Bridges Friction Slope Method= 1
Parabolic Critical Depth
Global Vel Dist=  1 , 1 , 1
Global Log Level= 0
CheckData=True
Encroach Param= -1, 0, 0, 0
BEGIN DESCRIPTION:
Multiple Run
END DESCRIPTION:

--- COFFEE HOLLOW TRIBUTARY 4.f01 (steady flow) ---

Flow Title=Multiple
Program Version=4.10
Number of Profiles= 7
Profile Names=10-year,25-year,50-year,1pct_min,100-year,1pct_plu,500-year
River Rch & RM=COFFEE HOLLOW TR,Reach-1         ,1924
     336     483     608     381     760    1517    1204
Boundary for River Rch & Prof#=COFFEE HOLLOW TR,Reach-1         , 1
Up Type= 0
Dn Type= 3
Dn Slope=0.012
Boundary for River Rch & Prof#=COFFEE HOLLOW TR,Reach-1         , 2
Up Type= 0
Dn Type= 3
Dn Slope=0.012
Boundary for River Rch & Prof#=COFFEE HOLLOW TR,Reach-1         , 3
Up Type= 0
Dn Type= 3
Dn Slope=0.012
Boundary for River Rch & Prof#=COFFEE HOLLOW TR,Reach-1         , 4
Up Type= 0
Dn Type= 3
Dn Slope=0.012
Boundary for River Rch & Prof#=COFFEE HOLLOW TR,Reach-1         , 5
Up Type= 0
Dn Type= 3
Dn Slope=0.012
Boundary for River Rch & Prof#=COFFEE HOLLOW TR,Reach-1         , 6
Up Type= 0
Dn Type= 3
Dn Slope=0.012
Boundary for River Rch & Prof#=COFFEE HOLLOW TR,Reach-1         , 7
Up Type= 0
Dn Type= 3
Dn Slope=0.012
DSS Import GetInterval= 0
DSS Import GetPeak= 0
DSS Import FillOption= 0

--- COFFEE HOLLOW TRIBUTARY 4.g01 (geometry) ---

Geom Title=Existing Conditions
Program Version=4.10

River Reach=COFFEE HOLLOW TR,Reach-1
Reach XY= 30
        1448205.        6811638.      1448108.48      6811739.44
      1448103.78       6811927.5      1448096.86      6811944.06
      1448057.36      6811993.98      1448054.48      6812072.78
      1448049.48      6812090.43      1447874.58      6812267.85
      1447858.46       6812289.5      1447854.33      6812317.92
      1447856.12      6812377.45      1447863.14      6812394.05
      1447901.63      6812439.74       1447903.2      6812481.89
      1447861.18      6812535.81      1447846.85      6812594.05
      1447763.16      6812681.95      1447748.86      6812740.17
      1447710.77      6812785.68      1447699.59      6812890.71
      1447675.64      6812918.57      1447653.74      6812934.48
      1447552.25      6812943.42      1447524.23      6812967.43
      1447508.03      6812989.39      1447504.46      6813012.87
      1447508.33      6813036.22      1447546.81      6813081.92
      1447554.46      6813103.21        1447555.        6813338.

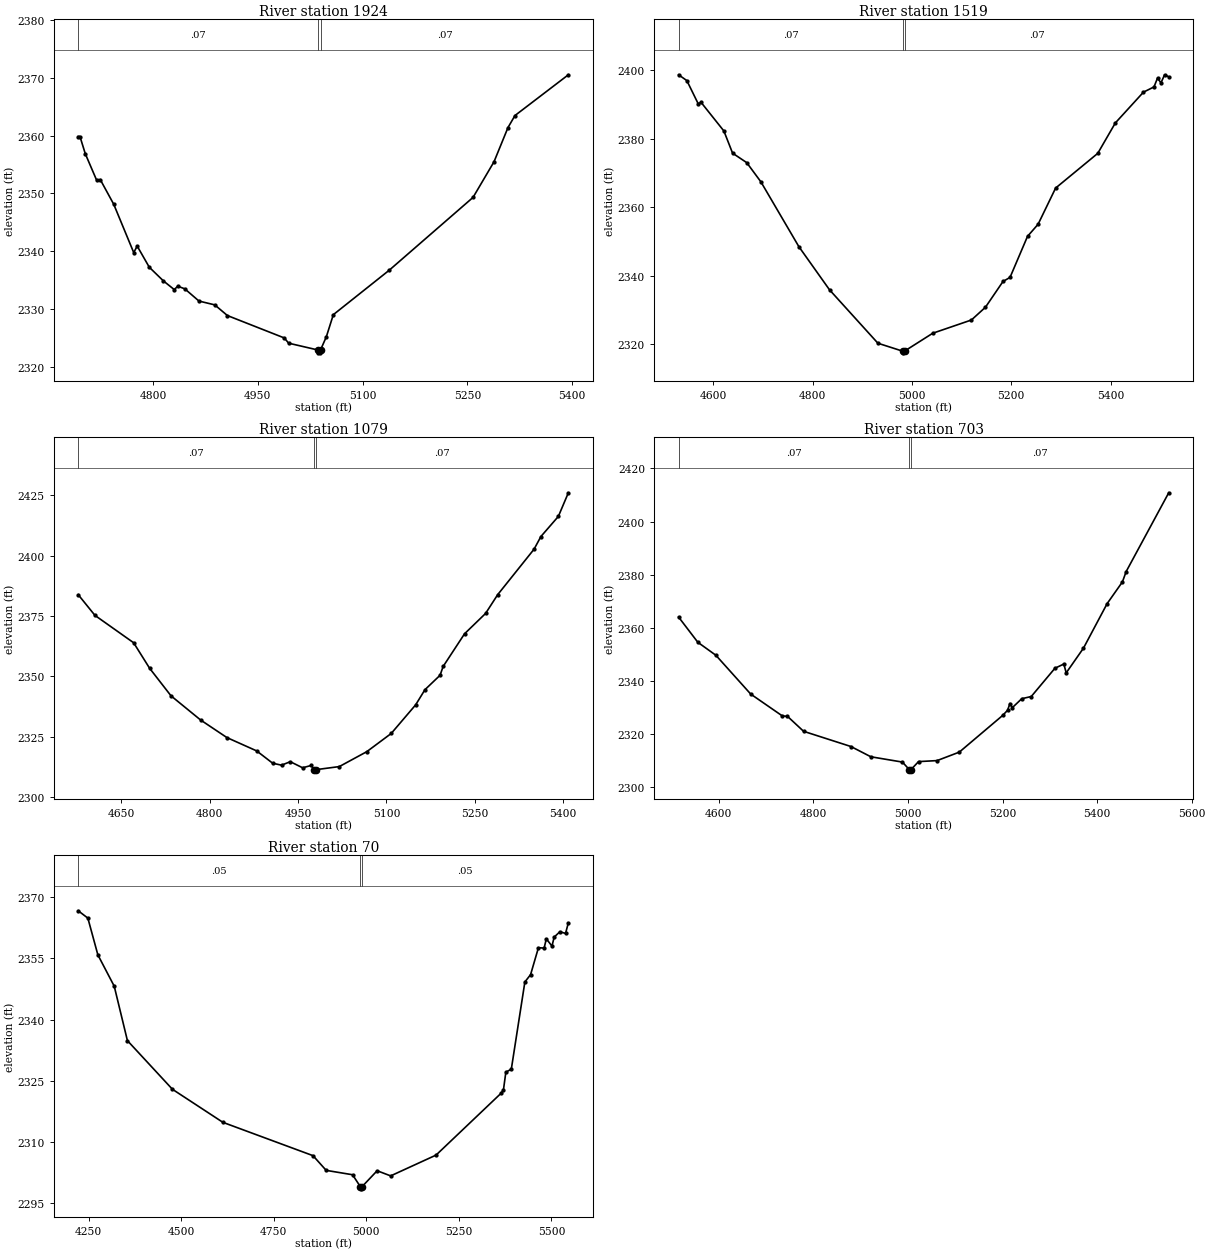
Type RM Length L Ch R = 1 ,1924    ,405,405,405
BEGIN DESCRIPTION:
COFFEE HOLLOW TRIBUTARY 4 4.0
END DESCRIPTION:
XS GIS Cut Line= 3
      1447805.04      6811688.01      1448107.02      6811743.84
      1448501.34      6811736.07
#Sta/Elev= 30
  4692.9 2359.84  4695.4 2359.84    4703 2356.87  4719.3 2352.27  4724.4  2352.4
  4743.7 2348.12  4772.3 2339.75  4777.3 2340.87  4794.6 2337.21  4814.9 2334.83
  4830.3 2333.34  4835.4 2333.92  4845.4 2333.47  4865.7 2331.35  4888.3 2330.69
  4906.4 2328.84  4987.8 2324.96  4994.1 2324.05  5035.7 2322.88    5036 2322.38
  5039.5 2322.38  5039.7 2322.88    5048 2325.16    5058 2328.99    5138 2336.69
    5258 2349.31    5288 2355.48    5308 2361.41    5318 2363.49  5394.4 2370.55
#Mann= 3 ,-1 , 0
  4692.9     .07       0  5035.7     .07       0  5039.7     .07       0
Bank Sta=5035.7,5039.7
XS Rating Curve= 0 ,0
Exp/Cntr=0.3,0.1

Type RM Length L Ch R = 1 ,1519    ,440,440,440
BEGIN DESCRIPTION:
COFFEE HOLLOW TRIBUTARY 4 3.0
END DESCRIPTION:
XS GIS Cut Line= 3
      1447594.75      6811926.17      1448022.12      6812121.52
      1448382.89      6812492.11
#Sta/Elev= 30
  4530.1 2398.59  4546.7 2396.89  4569.7  2390.1  4575.2 2390.58  4621.3 2382.21
  4638.8 2375.75  4667.3 2372.99  4695.8  2367.4  4772.3 2348.51    4834 2335.94
  4931.5 2320.37  4981.1 2318.07  4981.3 2317.57  4985.1 2318.07  5041.9 2323.28
  5119.8 2327.14  5148.1 2330.86  5183.4 2338.36  5197.6 2339.56  5232.8 2351.51
  5254.1 2355.04  5289.4 2365.58  5374.3  2375.7  5409.7 2384.56  5466.3 2393.53
  5487.5 2395.05  5494.6 2397.61  5501.6 2396.24  5508.8 2398.58  5517.2    2398
#Mann= 3 ,-1 , 0
  4530.1     .07       0  4981.1     .07       0  4985.1     .07       0
Bank Sta=4981.1,4985.1
XS Rating Curve= 0 ,0
Exp/Cntr=0.3,0.1

Type RM Length L Ch R = 1 ,1079    ,376,376,376
BEGIN DESCRIPTION:
COFFEE HOLLOW TRIBUTARY 4 2.0
END DESCRIPTION:
XS GIS Cut Line= 3
      1447554.98      6812237.99      1447904.25      6812477.32
       1448301.5      6812575.08
#Sta/Elev= 30
  4576.6 2383.78    4605 2375.21  4670.7 2363.87  4697.8 2353.31  4734.2 2341.87
  4784.4 2331.87  4829.1 2324.58  4879.7 2319.05  4906.9 2313.94  4921.9 2313.14
  4936.8 2314.58  4957.7 2312.06  4972.6 2313.04  4976.7 2311.29  4976.9 2310.79
  4980.7 2311.29    5020 2312.55  5066.7 2318.73  5108.2 2326.27  5149.7 2338.13
  5165.5 2344.41  5191.2  2350.4  5196.4 2354.04  5232.8 2367.59  5268.5 2376.02
  5289.1 2383.81  5350.9 2402.66  5362.5  2407.9  5392.1 2416.22  5409.1 2426.02
#Mann= 3 ,-1 , 0
  4576.6     .07       0  4976.7     .07       0  4980.7     .07       0
Bank Sta=4976.7,4980.7
XS Rating Curve= 0 ,0
Exp/Cntr=0.3,0.1

Type RM Length L Ch R = 1 ,703     ,633,633,633
BEGIN DESCRIPTION:
Mapping XS 7d00da8a
END DESCRIPTION:
XS GIS Cut Line= 4
      1447444.77      6812411.64      1447619.23      6812760.57
      1447858.81      6812828.28      1448254.69      6812794.42
#Sta/Elev= 30
  4515.1 2363.98  4555.8 2354.47  4593.9 2349.59  4667.6 2334.95  4734.6  2326.7
  4745.3 2326.57  4779.4 2320.92  4879.5 2315.19  4921.6 2311.32  4988.4 2309.32
  5002.7 2306.52    5003 2306.02  5006.7 2306.52  5022.4  2309.5  5061.6 2309.88
  5108.7 2313.08  5200.5 2326.93  5210.6 2328.84  5215.8  2331.4  5220.9 2329.86
  5240.7 2333.21  5260.8 2334.04  5310.9  2344.7  5329.7 2346.28  5334.7 2342.95
  5371.2 2352.27  5421.3 2369.07  5453.6 2377.25  5461.5 2381.15  5551.5 2410.84
#Mann= 3 ,-1 , 0
  4515.1     .07       0  5002.7     .07       0  5006.7     .07       0
Bank Sta=5002.7,5006.7
XS Rating Curve= 0 ,0
Exp/Cntr=0.3,0.1

Type RM Length L Ch R = 1 ,70      ,0,0,0
BEGIN DESCRIPTION:
COFFEE HOLLOW TRIBUTARY 4 1.0
END DESCRIPTION:
XS GIS Cut Line= 3
      1447101.62      6812636.39      1447555.03      6813268.36
       1448018.3      6812980.18
#Sta/Elev= 30
  4222.2 2366.63  4248.2 2364.83  4275.2 2355.84  4319.4 2348.17    4355 2334.85
  4476.6 2322.94  4612.9 2314.85  4856.1  2306.7  4891.7  2303.1  4962.9 2302.03
  4984.2 2299.08  4984.5 2298.58  4988.2 2299.08  5029.3 2303.01  5065.8 2301.75
  5188.4 2306.84  5364.5 2322.02  5370.4 2322.83  5376.8 2327.13  5391.6 2327.87
  5428.2 2349.21  5443.6    2351  5464.8 2357.59  5480.2  2357.5  5486.1 2359.76
  5501.4 2357.99  5507.3 2360.19  5522.7  2361.5    5538 2361.09  5545.6 2363.68
#Mann= 3 ,-1 , 0
  4222.2     .05       0  4984.2    .045       0  4988.2     .05       0
Bank Sta=4984.2,4988.2
XS Rating Curve= 0 ,0
Exp/Cntr=0.3,0.1

Chan Stop Cuts=-1
Use User Specified Reach Order=0
Composite Channel Slope=5