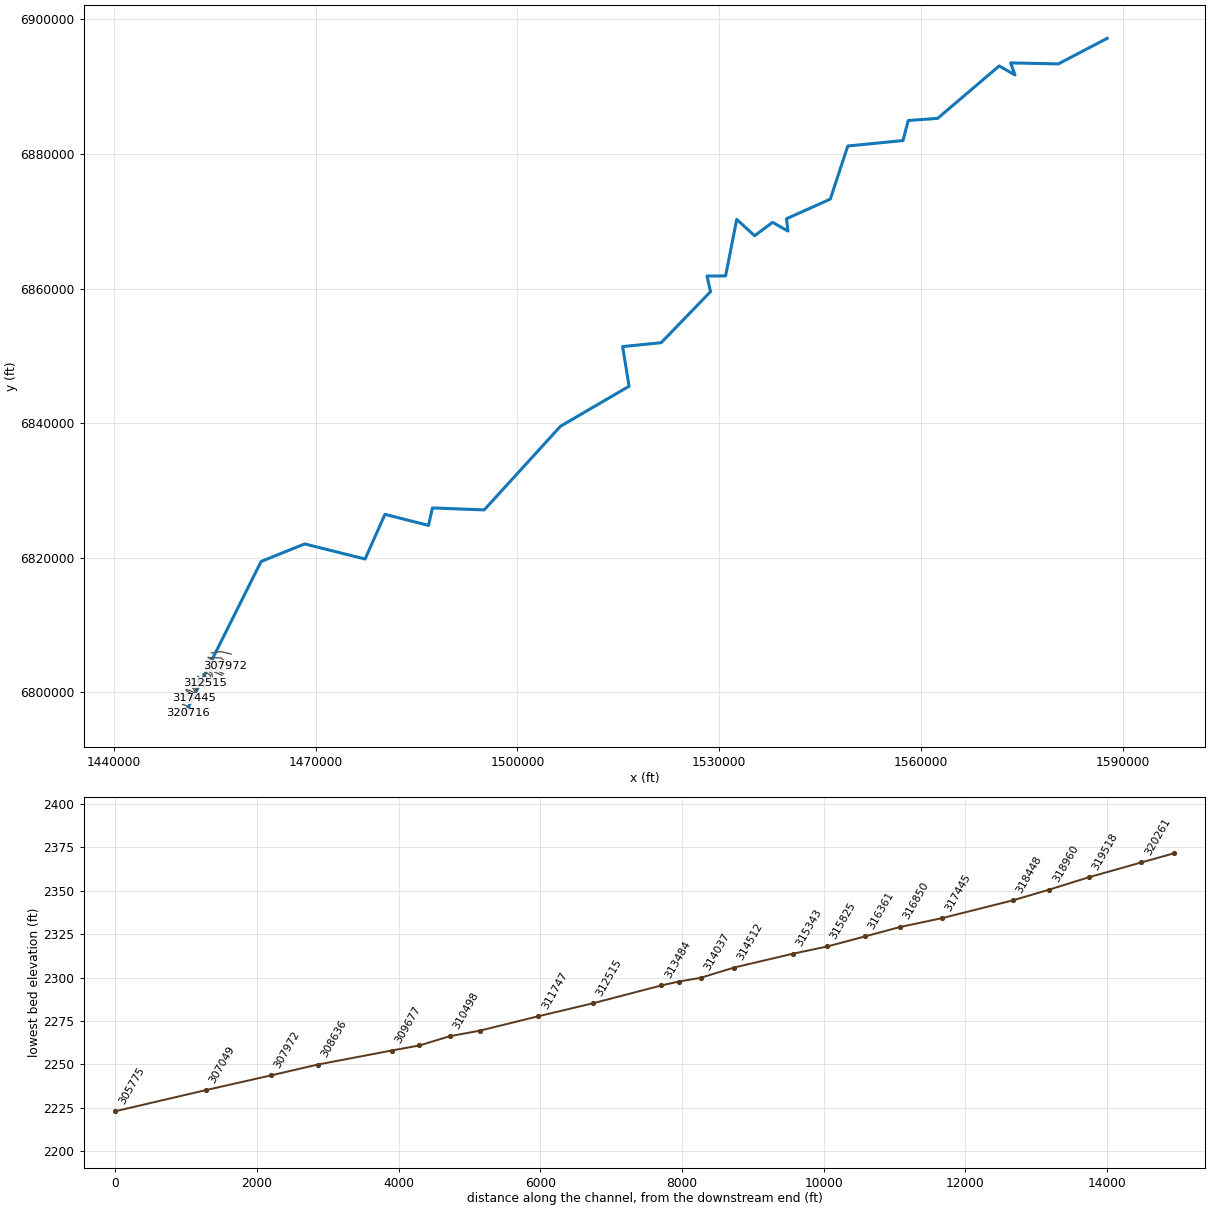
--- MULBERRY CREEK.prj (project) ---

Proj Title=MULBERRY CREEK Base Level Engineering
Current Plan=p01
Default Exp/Contr=0.3,0.1
English Units
Geom File=g01
Geom File=g02
Flow File=f01
Plan File=p01
Y Axis Title=Elevation
X Axis Title(PF)=Main Channel Distance
X Axis Title(XS)=Station
BEGIN DESCRIPTION:
MULBERRY CREEK
END DESCRIPTION:
DSS Export Rating Curves= 0
DSS Export Rating Curve Sorted= 0
DSS Export Volume Flow Curves= 0
DXF OffsetX= 0
DXF OffsetY= 0
DXF ScaleX= 1
DXF ScaleY= 10

--- MULBERRY CREEK.p01 (plan) ---

Plan Title=Multiple Run
Short Identifier=Multiple
Geom File=g01
Flow File=f01
Subcritical Flow
K Sum by GR= 0
Std Step Tol= 0.01
Critical Tol= 0.01
Num of Std Step Trials= 20
Max Error Tol= 0.3
Flow Tol Ratio= 0.001
Split Flow NTrial= 30
Split Flow Tol= 0.02
Split Flow Ratio= 0.02
Log Output Level= 0
Friction Slope Method= 1
Unsteady Friction Slope Method= 2
Unsteady Bridges Friction Slope Method= 1
Parabolic Critical Depth
Global Vel Dist=  1 , 1 , 1
Global Log Level= 0
CheckData=True
Encroach Param= -1, 0, 0, 0
BEGIN DESCRIPTION:
Multiple Run
END DESCRIPTION:

--- MULBERRY CREEK.f01 (steady flow) ---

Flow Title=Multiple
Program Version=4.10
Number of Profiles= 7
Profile Names=10-year,25-year,50-year,1pct_min,100-year,1pct_plu,500-year
River Rch & RM=MULBERRY CREEK,Reach-1         ,320716
     295     417     521     324     646    1288    1004
River Rch & RM=MULBERRY CREEK,Reach-1         ,319518
     483     705     896     567    1131    2257    1823
River Rch & RM=MULBERRY CREEK,Reach-1         ,318448
     587     864    1105     702    1401    2796    2282
River Rch & RM=MULBERRY CREEK,Reach-1         ,313727
     697    1033    1329     849    1694    3380    2786
River Rch & RM=MULBERRY CREEK,Reach-1         ,310069
     962    1447    1880    1211    2416    4821    4044
River Rch & RM=MULBERRY CREEK,Reach-1         ,304336
    1313    1999    2616    1697    3386    6756    5745
River Rch & RM=MULBERRY CREEK,Reach-1         ,294424
    1400    2134    2797    1816    3623    7230    6160
River Rch & RM=MULBERRY CREEK,Reach-1         ,290471
    1455    2219    2910    1890    3770    7523    6413
River Rch & RM=MULBERRY CREEK,Reach-1         ,286377
    1763    2705    3560    2319    4627    9232    7917
River Rch & RM=MULBERRY CREEK,Reach-1         ,278189
    1847    2838    3738    2437    4862    9701    8333
River Rch & RM=MULBERRY CREEK,Reach-1         ,277157
    3664    5761    7713    5104   10183   20318   17971
River Rch & RM=MULBERRY CREEK,Reach-1         ,274654
    3995    6289    8425    5577   11128   22203   19655
River Rch & RM=MULBERRY CREEK,Reach-1         ,269107
    4124    6491    8697    5757   11487   22920   20286
River Rch & RM=MULBERRY CREEK,Reach-1         ,266364
    4639    7313    9810    6499   12968   25874   22939
River Rch & RM=MULBERRY CREEK,Reach-1         ,260984
    4553    7158    9584    6338   12646   25231   22282
River Rch & RM=MULBERRY CREEK,Reach-1         ,252671
    4613    7241    9683    6394   12759   25457   22421
River Rch & RM=MULBERRY CREEK,Reach-1         ,244944
    4626    7255    9698    6401   12772   25484   22422
River Rch & RM=MULBERRY CREEK,Reach-1         ,241369
    4575    7164    9565    6306   12581   25103   22033
River Rch & RM=MULBERRY CREEK,Reach-1         ,234968
    4610    7218    9636    6352   12674   25287   22189
River Rch & RM=MULBERRY CREEK,Reach-1         ,234174
    4555    7120    9494    6251   12472   24886   21785
River Rch & RM=MULBERRY CREEK,Reach-1         ,232270
    5967    9368   12533    8275   16511   32943   28989
River Rch & RM=MULBERRY CREEK,Reach-1         ,228476
    5960    9363   12530    8277   16514   32950   29019
River Rch & RM=MULBERRY CREEK,Reach-1         ,218019
    5891    9234   12340    8139   16239   32401   28447
River Rch & RM=MULBERRY CREEK,Reach-1         ,212709
    6424   10056   13427    8846   17651   35218   30857
River Rch & RM=MULBERRY CREEK,Reach-1         ,191568
    6683   10408   13852    9098   18152   36219   31514
River Rch & RM=MULBERRY CREEK,Reach-1         ,183894
    6683   10408   13852    9098   18152   36219   31514
River Rch & RM=MULBERRY CREEK,Reach-1         ,175623
    6614   10286   13678    8975   17907   35728   31029
River Rch & RM=MULBERRY CREEK,Reach-1         ,168796
    6624   10282   13655    8948   17853   35622   30855
River Rch & RM=MULBERRY CREEK,Reach-1         ,156459
    6724   10425   13834    9059   18075   36064   31193
River Rch & RM=MULBERRY CREEK,Reach-1         ,139454
    6680   10346   13720    8977   17912   35739   30865
River Rch & RM=MULBERRY CREEK,Reach-1         ,133796
    6605   10215   13533    8846   17650   35216   30353
River Rch & RM=MULBERRY CREEK,Reach-1         ,125674
    6565   10144   13430    8772   17503   34924   30060
River Rch & RM=MULBERRY CREEK,Reach-1         ,119765
    6831   10554   13973    9129   18215   36343   31291
River Rch & RM=MULBERRY CREEK,Reach-1         ,112785
    6838   10563   13984    9135   18226   36365   31301
River Rch & RM=MULBERRY CREEK,Reach-1         ,109829
    6745   10399   13750    8969   17896   35708   30654
River Rch & RM=MULBERRY CREEK,Reach-1         ,105234
    7492   11568   15312   10002   19956   39818   34272
River Rch & RM=MULBERRY CREEK,Reach-1         ,91104
    7536   11632   15394   10053   20059   40022   34433
River Rch & RM=MULBERRY CREEK,Reach-1         ,89728
    7530   11619   15375   10039   20030   39965   34372
River Rch & RM=MULBERRY CREEK,Reach-1         ,86078
    7583   11693   15465   10093   20138   40182   34524
River Rch & RM=MULBERRY CREEK,Reach-1         ,76971
    7626   11751   15534   10132   20217   40338   34623
River Rch & RM=MULBERRY CREEK,Reach-1         ,72900
    7854   12094   15982   10421   20793   41487   35585
River Rch & RM=MULBERRY CREEK,Reach-1         ,57003
    7799   11998   15846   10326   20602   41107   35212
River Rch & RM=MULBERRY CREEK,Reach-1         ,47991
    7761   11932   15750   10259   20469   40841   34953
River Rch & RM=MULBERRY CREEK,Reach-1         ,45089
    8063   12401   16375   10669   21288   42474   36374
River Rch & RM=MULBERRY CREEK,Reach-1         ,39015
    8075   12418   16397   10683   21315   42528   36415
River Rch & RM=MULBERRY CREEK,Reach-1         ,38042
    8085   12432   16414   10693   21335   42570   36445
River Rch & RM=MULBERRY CREEK,Reach-1         ,37580
    8206   12603   16628   10825   21598   43094   36840
River Rch & RM=MULBERRY CREEK,Reach-1         ,23397
    8356   12836   16937   11027   22002   43900   37538
River Rch & RM=MULBERRY CREEK,Reach-1         ,19538
    8273   12692   16731   10883   21714   43325   36976
River Rch & RM=MULBERRY CREEK,Reach-1         ,13625
    8434   12935   17050   11089   22126   44147   37670
Boundary for River Rch & Prof#=MULBERRY CREEK,Reach-1         , 1
Up Type= 0
Dn Type= 3
Dn Slope=0.00104
Boundary for River Rch & Prof#=MULBERRY CREEK,Reach-1         , 2
Up Type= 0
Dn Type= 3
Dn Slope=0.00104
Boundary for River Rch & Prof#=MULBERRY CREEK,Reach-1         , 3
Up Type= 0
Dn Type= 3
Dn Slope=0.00104
Boundary for River Rch & Prof#=MULBERRY CREEK,Reach-1         , 4
Up Type= 0
Dn Type= 3
Dn Slope=0.00104
Boundary for River Rch & Prof#=MULBERRY CREEK,Reach-1         , 5
Up Type= 0
Dn Type= 3
Dn Slope=0.00104
Boundary for River Rch & Prof#=MULBERRY CREEK,Reach-1         , 6
Up Type= 0
Dn Type= 3
Dn Slope=0.00104
Boundary for River Rch & Prof#=MULBERRY CREEK,Reach-1         , 7
Up Type= 0
Dn Type= 3
Dn Slope=0.00104
DSS Import GetInterval= 0
DSS Import GetPeak= 0
DSS Import FillOption= 0

--- MULBERRY CREEK.g01 (geometry) ---

Geom Title=Existing Conditions
Program Version=4.10

River Reach=MULBERRY CREEK  ,Reach-1
Reach XY= 30
        1450655.        6796938.        1461895.      6819427.37
      1468375.46      6822038.48      1477348.92      6819789.78
      1480306.65      6826434.84      1486780.11      6824787.68
      1487360.89      6827386.04      1495061.05      6827096.16
      1506391.68      6839524.63      1516591.37      6845474.79
      1515631.28      6851365.12      1521365.05      6851948.96
      1528697.66      6859531.67      1528174.57       6861858.2
      1530938.86      6861871.39      1532591.62      6870274.47
      1535251.65      6867845.59      1537920.27      6869837.62
       1540203.5      6868541.46      1539995.21      6870377.57
      1546497.68      6873281.62      1549102.65      6881183.43
       1557303.6      6881990.99      1558091.31      6884974.74
      1562457.31      6885293.08      1571606.55      6893084.25
      1573949.48      6891739.76      1573306.62      6893534.88
      1580399.06      6893390.26        1587655.        6897188.

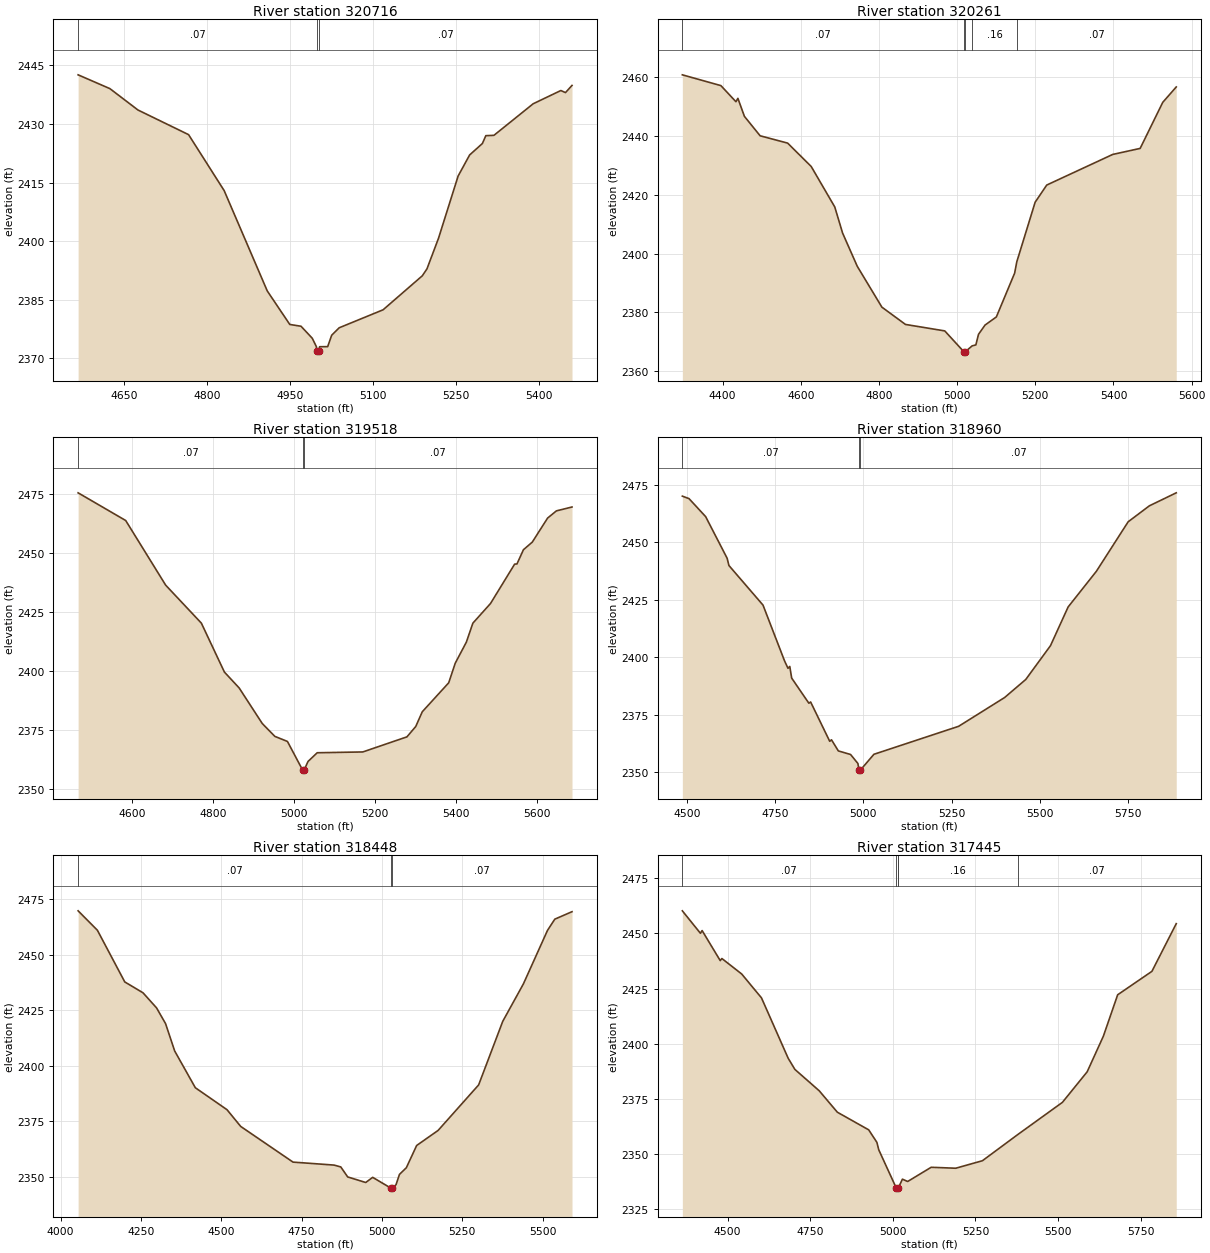
Type RM Length L Ch R = 1 ,320716  ,455,455,455
BEGIN DESCRIPTION:
MULBERRY CREEK 161.0
END DESCRIPTION:
XS GIS Cut Line= 3
      1450228.48      6797047.03      1450654.96      6797123.02
      1451023.64       6796849.1
#Sta/Elev= 30
  4566.8 2442.59  4624.2 2439.06    4675 2433.58  4766.4 2427.28  4830.7 2412.96
  4908.6 2387.27  4949.3 2378.69  4969.6 2378.23  4989.9 2375.16  4997.4 2372.99
    4998 2371.85  4998.2 2371.35    5002 2371.85  5003.2 2372.99  5017.8 2373.01
    5025 2375.93  5038.6 2377.84  5117.9 2382.44  5188.8 2391.15  5197.2 2392.92
    5218 2400.73  5253.5 2416.68  5274.3 2422.08  5297.3    2425  5303.6 2427.02
  5318.2  2427.1  5389.1 2435.18  5439.1 2438.57  5447.5 2438.04  5459.3 2439.88
#Mann= 3 ,-1 , 0
  4566.8     .07       0    4998     .07       0    5002     .07       0
Bank Sta=4998,5002
XS Rating Curve= 0 ,0
Exp/Cntr=0.3,0.1

Type RM Length L Ch R = 1 ,320261  ,743,743,743
BEGIN DESCRIPTION:
Mapping XS 463aeb8a
END DESCRIPTION:
XS GIS Cut Line= 3
      1450106.91      6797536.61      1450784.04      6797470.64
      1451318.79      6797237.99
#Sta/Elev= 30
  4297.1 2460.85  4395.7 2457.18  4434.2  2451.7  4439.2 2452.85  4455.9 2446.72
  4496.1 2440.11  4566.5 2437.62  4626.7 2429.68    4687 2415.91  4707.1    2407
  4744.6 2395.71  4807.6 2381.81  4867.9 2375.93  4968.4 2373.73  5017.1 2366.67
  5017.4 2366.17  5021.1 2366.67  5038.4 2368.63    5048 2368.97  5054.8 2372.58
  5071.5 2375.72  5100.4 2378.48  5147.2 2393.39  5152.7 2397.23  5199.6  2417.5
  5229.3 2423.35    5398 2433.76  5468.3 2435.82  5526.1 2451.49  5560.6 2456.72
#Mann= 5 ,-1 , 0
  4297.1     .07       0  5017.1     .07       0  5021.1     .07       0
  5038.4     .16       0  5152.7     .07       0
Bank Sta=5017.1,5021.1
XS Rating Curve= 0 ,0
Exp/Cntr=0.3,0.1

Type RM Length L Ch R = 1 ,319518  ,558,558,558
BEGIN DESCRIPTION:
Mapping XS 2a2af85a
END DESCRIPTION:
XS GIS Cut Line= 3
      1450221.53      6798182.44      1450721.54      6798008.83
       1451325.7       6797675.5
#Sta/Elev= 30
  4467.5 2475.62    4585 2463.88  4683.7 2436.47  4771.8 2420.37  4828.7 2399.62
  4865.1 2392.89  4922.1 2377.82  4953.2 2372.36  4984.3 2370.21  5021.6 2358.13
  5021.8 2357.63  5025.6 2358.13  5035.1 2361.73  5057.8 2365.42  5170.4 2365.76
  5279.3 2372.16    5301 2376.55  5317.1 2382.79  5382.4 2395.08  5398.5 2403.38
    5426 2412.33    5442 2420.35  5485.6  2428.7  5545.2  2445.4  5550.9 2445.47
  5566.9  2451.5  5588.7 2454.72  5626.5 2464.91  5648.3 2467.97  5686.8 2469.61
#Mann= 3 ,-1 , 0
  4467.5     .07       0  5021.6     .07       0  5025.6     .07       0
Bank Sta=5021.6,5025.6
XS Rating Curve= 0 ,0
Exp/Cntr=0.3,0.1

Type RM Length L Ch R = 1 ,318960  ,512,512,512
BEGIN DESCRIPTION:
Mapping XS fab5878d
END DESCRIPTION:
XS GIS Cut Line= 3
      1450350.01      6798369.94      1450839.59      6798456.75
      1451741.21      6798446.35
#Sta/Elev= 30
  4487.4 2469.97  4506.3 2468.89  4553.4 2461.08  4614.3 2442.98  4619.4 2439.83
  4715.9 2422.64  4776.8 2398.45  4786.6 2395.19  4791.7 2395.99  4797.1 2390.94
  4845.7 2380.04  4850.8 2380.56  4904.8 2363.49  4909.9 2364.14  4929.2 2359.31
  4963.9 2357.76  4984.6 2353.86    4988 2351.03  4988.3 2350.53    4992 2351.03
    5030 2357.84    5270    2370  5400.1 2382.49  5460.1 2390.34  5530.1 2405.02
  5580.1 2421.84  5660.1 2437.33  5750.1 2458.83  5810.1 2465.76  5886.3 2471.41
#Mann= 3 ,-1 , 0
  4487.4     .07       0    4988     .07       0    4992     .07       0
Bank Sta=4988,4992
XS Rating Curve= 0 ,0
Exp/Cntr=0.3,0.1

Type RM Length L Ch R = 1 ,318448  ,1003,1003,1003
BEGIN DESCRIPTION:
Mapping XS e7e2a8f8
END DESCRIPTION:
XS GIS Cut Line= 3
      1450450.44      6799518.36       1451096.3      6798809.99
      1451636.24      6798602.32
#Sta/Elev= 30
  4054.7 2469.72  4114.7 2460.98  4199.9  2437.7  4256.6 2432.81  4298.8 2426.01
  4326.9 2418.91  4355.3 2406.58  4419.5 2390.05  4518.1 2380.15  4560.7 2372.62
  4723.5 2356.55  4851.2 2355.21  4872.1 2354.38  4893.7 2349.87  4949.8 2347.37
  4971.5 2349.68  5027.6 2344.88  5028.1 2344.38  5033.1 2344.88  5044.1 2346.37
  5054.8 2351.01  5076.2 2354.02  5108.3 2364.03    5175 2370.81  5301.2 2391.31
  5376.2 2419.94  5440.5 2436.81  5515.5 2460.91  5538.2 2465.96  5591.8 2469.33
#Mann= 3 ,-1 , 0
  4054.7     .07       0  5027.6     .07       0  5033.1     .07       0
Bank Sta=5027.6,5033.1
XS Rating Curve= 0 ,0
Exp/Cntr=0.3,0.1

Type RM Length L Ch R = 1 ,317445  ,595,595,595
BEGIN DESCRIPTION:
Mapping XS cb794d89
END DESCRIPTION:
XS GIS Cut Line= 3
      1450509.52       6799632.9      1451113.67      6799528.74
      1451878.97      6799092.41
#Sta/Elev= 30
  4363.4 2460.26  4418.1 2450.08  4423.2 2451.32    4478  2437.7  4483.1 2438.64
    4543 2431.62  4602.8 2420.81  4683.5 2393.46  4703.8  2388.4  4777.4 2378.71
  4832.2    2369  4927.1    2361  4951.9 2355.33  4957.5 2351.98  5010.5 2334.63
  5010.9 2334.13  5016.1 2334.63  5017.2  2334.8  5029.1 2338.64    5045 2337.59
  5116.1 2344.03  5190.4  2343.6  5271.1    2347  5378.1 2358.87  5513.1 2373.46
    5588 2387.31    5637 2403.46  5680.2 2422.21  5783.8 2432.83  5857.4 2454.44
#Mann= 5 ,-1 , 0
  4363.4     .07       0  5010.5     .07       0  5016.1     .07       0
  5017.2     .16       0  5378.1     .07       0
Bank Sta=5010.5,5016.1
XS Rating Curve= 0 ,0
Exp/Cntr=0.3,0.1

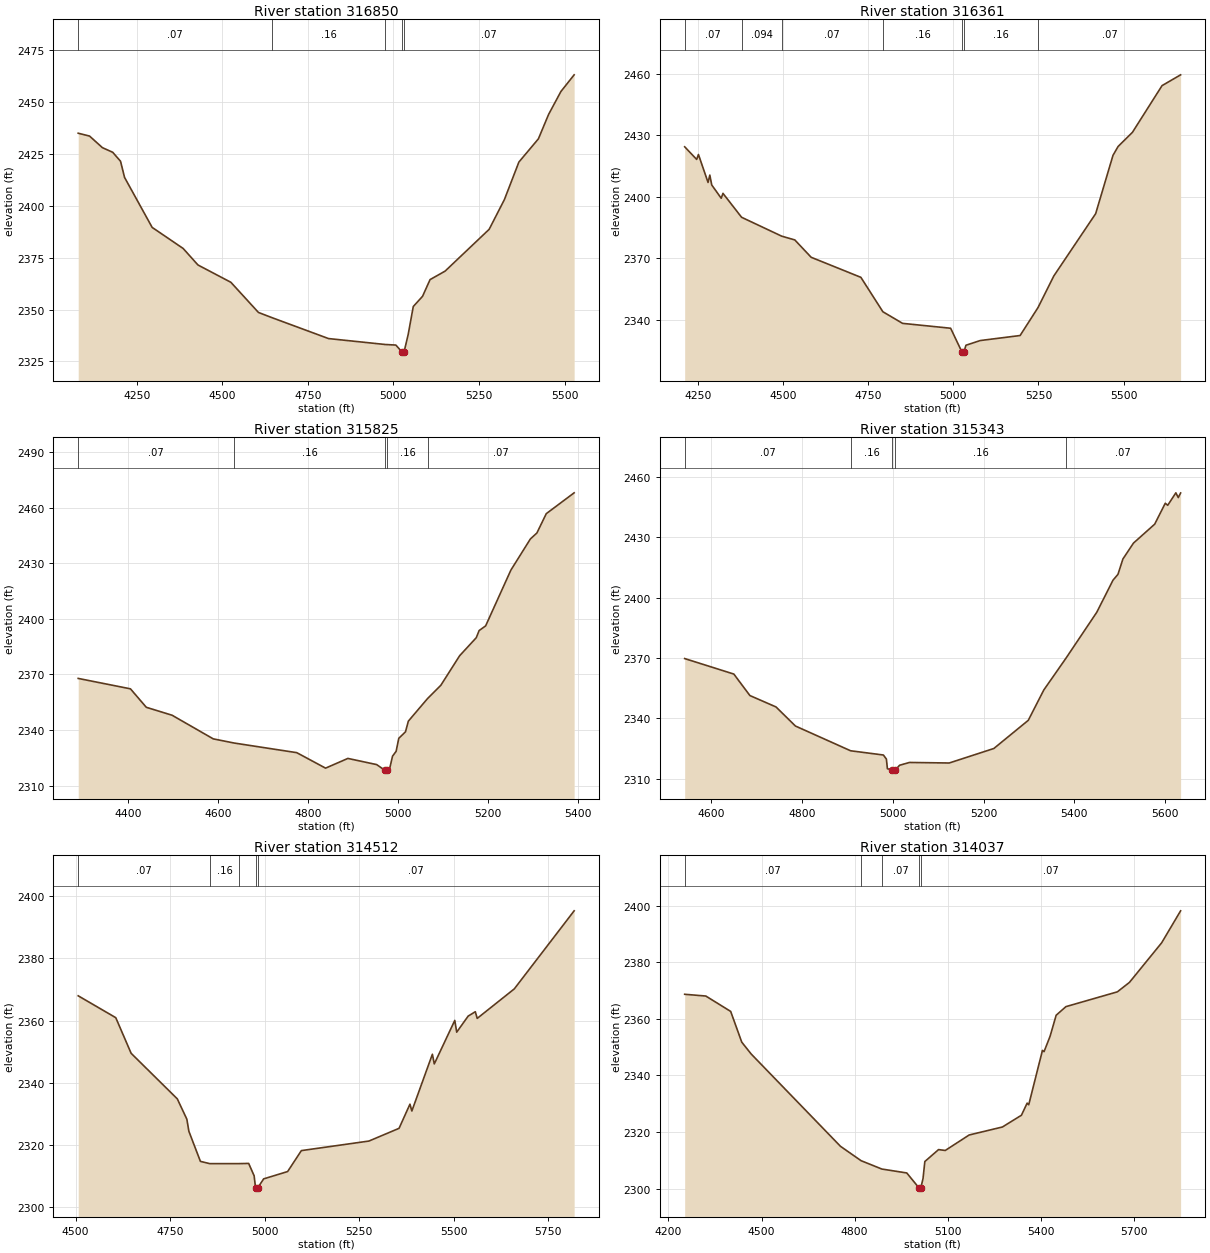
Type RM Length L Ch R = 1 ,316850  ,489,489,489
BEGIN DESCRIPTION:
Mapping XS dc6dd4d8
END DESCRIPTION:
XS GIS Cut Line= 3
      1450747.55       6800237.4      1451518.35      6799797.32
      1451983.88      6799482.63
#Sta/Elev= 30
  4078.7 2434.86  4111.9 2433.49  4149.4 2427.91  4179.4  2425.7  4202.4 2421.37
  4214.2 2413.57  4294.8 2389.53  4385.5 2379.37  4428.7 2371.43  4524.9  2363.1
  4605.5 2348.58  4645.3 2346.06  4810.3 2336.01  4975.7 2333.16  5007.1 2332.88
  5025.3  2329.5  5025.7    2329    5031  2329.5  5043.1 2337.96    5058 2351.43
  5085.1 2356.35  5107.1  2364.4  5150.9 2368.46  5279.8  2388.6  5324.4 2402.93
  5366.7 2420.98  5423.7 2432.15  5453.6 2443.93  5489.6 2454.97  5528.2 2462.97
#Mann= 5 ,-1 , 0
  4078.7     .07       0  4645.3     .16       0  4975.7     .07       0
  5025.3     .07       0    5031     .07       0
Bank Sta=5025.3,5031
XS Rating Curve= 0 ,0
Exp/Cntr=0.3,0.1

Type RM Length L Ch R = 1 ,316361  ,536,536,536
BEGIN DESCRIPTION:
Mapping XS 3a8dadd4
END DESCRIPTION:
XS GIS Cut Line= 3
      1450778.78      6800393.67      1451515.75      6800177.52
      1452085.36      6799792.58
#Sta/Elev= 30
  4211.6 2424.32  4246.8 2418.15    4252 2420.56  4280.2 2406.93  4285.4 2410.51
    4291  2405.7  4318.8 2399.22    4324  2401.6  4378.6 2389.93  4496.3 2380.72
  4534.8 2378.88  4582.8 2370.41  4728.7 2360.63  4793.3 2343.84  4851.1 2338.17
  4992.2 2335.79  5025.4 2324.15  5025.8 2323.65  5031.1 2324.15  5037.1  2327.5
  5079.1 2329.79    5196 2332.24  5248.6 2345.88  5294.9 2361.28  5417.8  2391.7
  5468.7 2420.17  5483.7 2424.49  5525.7 2431.38  5612.6 2454.16  5667.1 2459.43
#Mann= 7 ,-1 , 0
  4211.6     .07       0  4378.6    .094       0  4496.3     .07       0
  4793.3     .16       0  5025.4     .07       0  5031.1     .16       0
  5248.6     .07       0
Bank Sta=5025.4,5031.1
XS Rating Curve= 0 ,0
Exp/Cntr=0.3,0.1

Type RM Length L Ch R = 1 ,315825  ,482,482,482
BEGIN DESCRIPTION:
Mapping XS b32171b4
END DESCRIPTION:
XS GIS Cut Line= 3
       1451505.3       6800891.1      1451950.64      6800333.77
      1452190.13      6800026.61
#Sta/Elev= 30
  4288.6 2367.88  4404.8 2362.25    4440 2352.29  4497.4    2348  4588.9 2335.25
  4635.3    2333  4774.6  2327.8  4838.7 2319.44  4888.3 2324.69  4952.4 2321.35
  4970.3 2318.33  4970.8 2317.83    4976 2318.33  4981.2 2319.19  4987.6 2325.91
  4995.6 2328.53  5001.5 2335.54  5016.4 2339.05  5022.8 2344.82  5065.5 2357.01
  5095.1  2364.2  5136.8 2380.11  5173.8 2389.85  5180.2 2393.72  5194.7 2396.26
  5250.8 2426.35  5294.2 2443.17  5308.6 2446.37  5329.5 2456.82  5391.5 2468.07
#Mann= 5 ,-1 , 0
  4288.6     .07       0  4635.3     .16       0  4970.3     .07       0
    4976     .16       0  5065.5     .07       0
Bank Sta=4970.3,4976
XS Rating Curve= 0 ,0
Exp/Cntr=0.3,0.1

Type RM Length L Ch R = 1 ,315343  ,831,831,831
BEGIN DESCRIPTION:
Mapping XS 499e675b
END DESCRIPTION:
XS GIS Cut Line= 3
      1451623.41      6801047.74      1451983.63      6800780.82
      1452243.52      6800191.74
#Sta/Elev= 30
  4541.8 2369.65  4650.1 2361.94  4685.5 2351.26  4742.9 2345.61  4785.7 2336.12
  4907.2 2323.82  4979.4 2321.71    4986 2319.71  4988.3  2314.9  4999.1  2314.2
  4999.6  2313.7  5005.4  2314.2  5015.1 2316.62  5036.9 2318.01  5124.4 2317.74
  5222.7 2324.95  5298.5 2338.95  5332.7 2354.03  5381.5 2369.82  5449.3 2392.64
  5485.1 2408.61    5496  2411.5  5506.9 2419.13  5530.2 2427.05  5576.9 2436.45
  5600.2 2446.85  5605.6 2445.83  5623.5 2452.03  5628.9 2449.68    5634 2451.96
#Mann= 5 ,-1 , 0
  4541.8     .07       0  4907.2     .16       0  4999.1     .07       0
  5005.4     .16       0  5381.5     .07       0
Bank Sta=4999.1,5005.4
XS Rating Curve= 0 ,0
Exp/Cntr=0.3,0.1

Type RM Length L Ch R = 1 ,314512  ,475,475,475
BEGIN DESCRIPTION:
Mapping XS c74a5bec
END DESCRIPTION:
XS GIS Cut Line= 4
      1451791.76      6801242.21      1452257.07      6801072.06
      1452472.35      6800933.17       1452375.3      6800382.08
#Sta/Elev= 30
  4506.9 2367.96  4606.2 2360.92  4646.8 2349.46  4768.9 2334.79  4794.1 2328.26
  4799.5 2324.36    4830 2314.67  4854.8 2313.94  4933.3 2313.95  4957.6 2314.01
    4972 2310.03  4975.7 2306.24  4976.2 2305.74    4982 2306.24  4997.2 2309.04
  5060.6  2311.4  5096.9 2318.14  5275.5 2321.21  5355.2 2325.31    5384 2333.09
    5389 2330.88  5443.3 2349.15  5448.3 2346.03  5502.5 2360.04  5507.6 2356.26
  5537.9 2361.43  5556.8 2362.84  5561.8 2360.69  5659.8 2370.18  5818.1 2395.31
#Mann= 5 ,-1 , 0
  4506.9     .07       0  4854.8     .16       0  4933.3     .07       0
  4975.7     .07       0    4982     .07       0
Bank Sta=4975.7,4982
XS Rating Curve= 0 ,0
Exp/Cntr=0.3,0.1

Type RM Length L Ch R = 1 ,314037  ,310,310,310
BEGIN DESCRIPTION:
Mapping XS d8186037
END DESCRIPTION:
XS GIS Cut Line= 3
      1452326.53      6801887.99      1452586.93      6801193.58
      1452406.37      6800356.77
#Sta/Elev= 30
  4252.4 2368.72  4320.5  2368.1  4400.6 2362.66  4436.2 2351.81  4466.5 2347.62
  4754.3 2314.96  4820.8 2309.87  4887.7 2306.92  4967.9 2305.54  5006.8 2300.32
  5007.3 2299.82  5013.2 2300.32  5020.2 2303.53  5026.1 2309.58  5070.3  2313.8
  5091.8 2313.49  5168.8 2318.96    5276 2321.79  5337.3 2325.95  5355.7 2330.24
  5360.8 2329.65    5405 2348.89  5410.1 2348.42  5429.4 2353.82  5449.2 2361.31
  5480.6 2364.35  5646.3 2369.58  5685.2 2372.92    5789 2386.92  5850.1 2398.23
#Mann= 5 ,-1 , 0
  4252.4     .07       0  4820.8     .16       0  4887.7     .07       0
  5006.8     .07       0  5013.2     .07       0
Bank Sta=5006.8,5013.2
XS Rating Curve= 0 ,0
Exp/Cntr=0.3,0.1

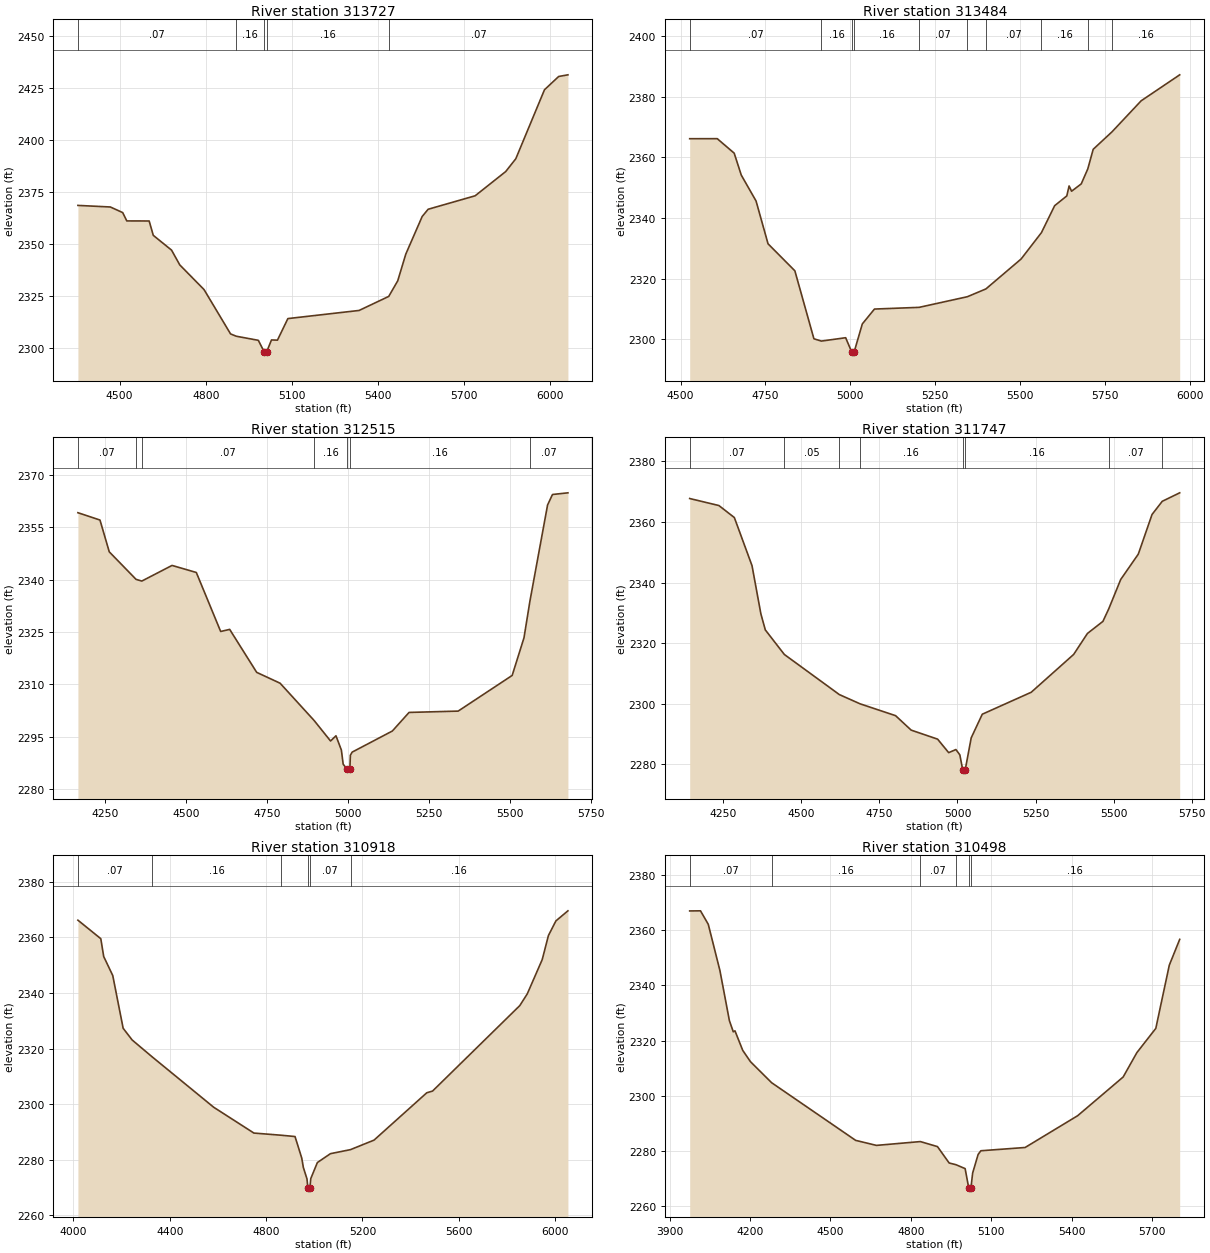
Type RM Length L Ch R = 1 ,313727  ,243,243,243
BEGIN DESCRIPTION:
Mapping XS 209a00ec
END DESCRIPTION:
XS GIS Cut Line= 3
      1452329.96      6801922.78      1452736.23      6801443.58
      1453555.17      6800742.63
#Sta/Elev= 30
  4354.7 2368.68  4467.7 2367.92  4510.6 2365.23  4524.9 2361.22  4602.8 2361.19
  4617.1 2354.29  4680.8 2347.17  4709.4 2340.07  4793.9  2328.2  4886.2 2306.89
  4905.9 2305.78  4982.9 2303.81  5003.7 2298.15  5004.2 2297.65  5011.6 2298.15
  5028.7 2303.98  5049.5 2303.89  5085.8 2314.26  5333.8 2318.17    5437 2324.92
  5468.3 2332.42  5496.3 2345.23  5553.4 2363.34  5574.2 2366.83  5737.8  2373.3
  5844.3 2384.96  5879.4 2391.11  5979.3 2424.29  6028.7 2430.67  6060.9 2431.47
#Mann= 5 ,-1 , 0
  4354.7     .07       0  4905.9     .16       0  5003.7     .07       0
  5011.6     .16       0    5437     .07       0
Bank Sta=5003.7,5011.6
XS Rating Curve= 0 ,0
Exp/Cntr=0.3,0.1

Type RM Length L Ch R = 1 ,313484  ,969,969,969
BEGIN DESCRIPTION:
Mapping XS 5bbba57c
END DESCRIPTION:
XS GIS Cut Line= 3
       1452600.1      6801996.75      1452881.37      6801628.65
      1453609.91      6800972.97
#Sta/Elev= 30
  4526.8 2366.13    4608 2366.14  4657.9 2361.36  4678.7 2354.14  4722.3 2345.59
  4757.6 2331.48  4836.6 2322.58  4892.7 2300.17  4914.7 2299.41  4986.2 2300.52
  5003.6 2295.94  5004.1 2295.44  5011.5 2295.94  5035.3 2305.07  5071.1 2309.97
  5202.7 2310.53  5344.8 2314.04  5399.3  2316.6  5503.1 2326.48  5562.9 2335.16
  5601.8 2344.04  5637.6 2347.27  5644.4 2350.55  5651.8 2348.82  5680.2 2351.24
  5699.4 2356.16  5715.4 2362.64    5771 2368.42  5856.6 2378.62  5970.2 2387.19
#Mann= 10 ,-1 , 0
  4526.8     .07       0  4914.7     .16       0  5003.6     .07       0
  5011.5     .16       0  5202.7     .07       0  5344.8     .16       0
  5399.3     .07       0  5562.9     .16       0  5699.4     .07       0
    5771     .16       0
Bank Sta=5003.6,5011.5
XS Rating Curve= 0 ,0
Exp/Cntr=0.3,0.1

Type RM Length L Ch R = 1 ,312515  ,768,768,768
BEGIN DESCRIPTION:
Mapping XS 1f1d3b1f
END DESCRIPTION:
XS GIS Cut Line= 3
       1452478.6      6802333.51      1453239.01       6801948.1
      1453593.19      6801389.05
#Sta/Elev= 30
  4165.9 2359.13  4234.1 2357.03  4262.8 2347.93  4345.6 2340.05  4363.4 2339.56
  4456.8 2344.04  4531.8 2342.02  4607.1 2325.13  4634.9 2325.73  4718.4 2313.43
  4790.8 2310.32  4895.9 2299.65  4946.7 2293.78  4963.4 2295.28  4980.1 2291.19
  4985.7 2287.13  4998.4 2285.66  4998.9 2285.16  5006.3 2285.66  5007.9 2289.71
  5013.4  2290.6  5137.6 2296.64  5189.3 2301.96    5341 2302.34  5507.9 2312.55
  5544.4 2323.31  5562.8 2333.83  5617.3 2361.33  5632.5 2364.34  5680.2 2364.82
#Mann= 7 ,-1 , 0
  4165.9     .07       0  4345.6     .16       0  4363.4     .07       0
  4895.9     .16       0  4998.4     .07       0  5006.3     .16       0
  5562.8     .07       0
Bank Sta=4998.4,5006.3
XS Rating Curve= 0 ,0
Exp/Cntr=0.3,0.1

Type RM Length L Ch R = 1 ,311747  ,829,829,829
BEGIN DESCRIPTION:
Mapping XS e4f48258
END DESCRIPTION:
XS GIS Cut Line= 3
       1453252.9       6802698.1       1453877.9      6802118.24
      1454300.76      6801539.41
#Sta/Elev= 30
  4142.4 2367.73    4236 2365.41  4285.4 2361.45    4342 2345.57  4370.4 2329.64
  4384.6 2324.35  4445.5 2316.25  4621.9 2302.99  4687.9 2299.96  4801.8 2296.04
  4851.7 2291.27  4936.4 2288.29  4971.9 2283.83    4995 2284.86  5007.6 2283.11
  5016.7 2278.23  5017.2 2277.73    5025 2278.23    5044 2288.71  5079.5 2296.52
  5236.3 2303.77  5372.2 2316.26  5416.2 2323.17  5465.9 2327.17  5484.7 2331.34
  5522.8 2340.99  5579.2 2349.37  5623.2 2362.46  5655.9 2366.81  5711.8 2369.61
#Mann= 8 ,-1 , 0
  4142.4     .07       0  4445.5     .05       0  4621.9     .07       0
  4687.9     .16       0  5016.7     .07       0    5025     .16       0
  5484.7     .07       0  5655.9     .16       0
Bank Sta=5016.7,5025
XS Rating Curve= 0 ,0
Exp/Cntr=0.3,0.1

Type RM Length L Ch R = 1 ,310918  ,420,420,420
BEGIN DESCRIPTION:
Mapping XS 02e84068
END DESCRIPTION:
XS GIS Cut Line= 3
      1453402.51      6803093.61      1454277.55      6802593.58
      1454616.09      6801624.86
#Sta/Elev= 30
  4018.9 2366.21  4113.9 2359.55    4126 2353.12  4163.5  2346.3  4206.7  2327.3
  4244.1 2323.09    4325 2317.17  4582.4 2298.89  4749.4 2289.59  4862.5 2288.81
  4920.1 2288.34  4948.1 2280.57  4954.7  2277.2  4969.7 2273.11  4973.5 2269.91
    4974 2269.41  4981.9 2269.91  4985.5  2273.2  5012.9 2278.98  5067.1 2282.17
  5150.5 2283.63  5248.1 2287.05    5467 2304.09  5491.1 2304.71  5853.1 2335.47
  5884.1 2339.68  5946.2 2352.03    5972 2360.69    6003 2365.95  6052.9 2369.58
#Mann= 6 ,-1 , 0
  4018.9     .07       0    4325     .16       0  4862.5     .07       0
  4973.5     .07       0  4981.9     .07       0  5150.5     .16       0
Bank Sta=4973.5,4981.9
XS Rating Curve= 0 ,0
Exp/Cntr=0.3,0.1

Type RM Length L Ch R = 1 ,310498  ,429,429,429
BEGIN DESCRIPTION:
MULBERRY CREEK 139.0
END DESCRIPTION:
XS GIS Cut Line= 3
      1453743.44      6803414.01        1454555.        6802788.
      1454717.11      6802001.47
#Sta/Elev= 30
    3975 2366.84  4015.3 2366.88  4044.3 2362.01  4087.8 2345.27  4123.1 2327.19
  4137.6 2323.15  4143.9  2323.5  4172.9 2316.43  4201.9 2312.32  4280.8 2304.73
  4594.1  2283.9  4671.6 2282.08  4835.6 2283.46  4899.4 2281.64  4942.9 2275.72
  4968.3  2275.1  5002.5 2273.69  5015.8 2266.77  5016.3 2266.27  5024.2 2266.77
  5030.6 2272.09    5051  2278.8  5061.2 2280.14  5226.3 2281.32  5422.3 2292.81
  5592.1 2306.81  5643.2 2315.61  5713.9 2324.39  5764.2 2347.23    5803 2356.56
#Mann= 6 ,-1 , 0
    3975     .07       0  4280.8     .16       0  4835.6     .07       0
  4968.3     .16       0  5015.8     .07       0  5024.2     .16       0
Bank Sta=5015.8,5024.2
XS Rating Curve= 0 ,0
Exp/Cntr=0.3,0.1

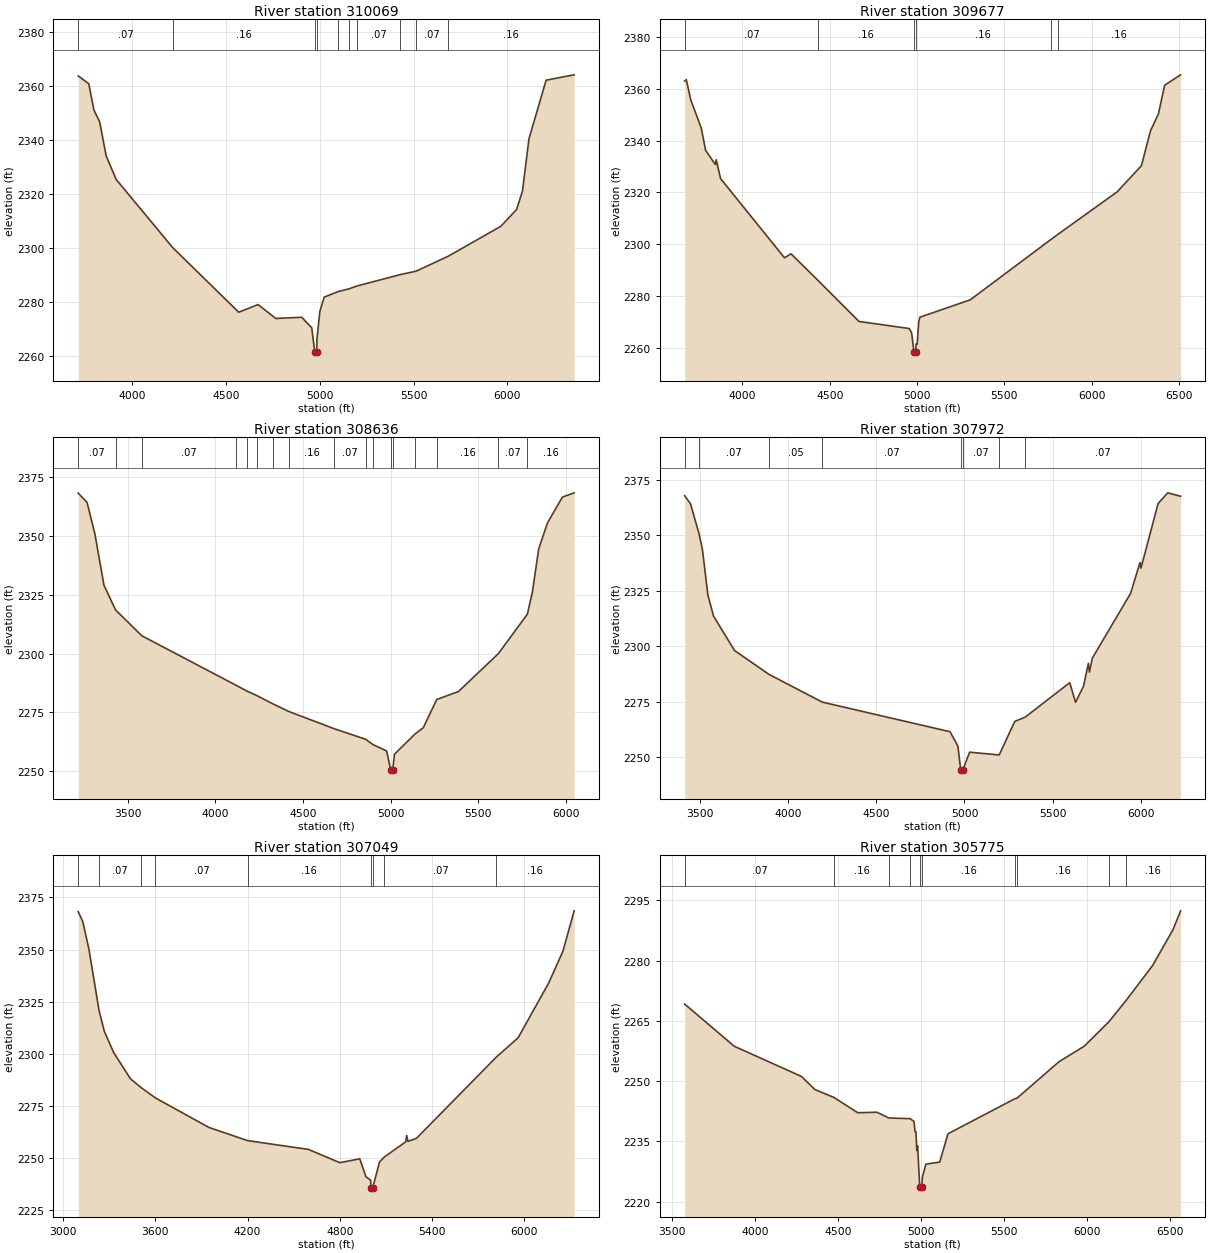
Type RM Length L Ch R = 1 ,310069  ,392,392,392
BEGIN DESCRIPTION:
Mapping XS 400c56a8
END DESCRIPTION:
XS GIS Cut Line= 3
       1453715.1      6803702.93      1454840.05      6803072.75
      1456074.39      6802510.27
#Sta/Elev= 30
  3710.7 2363.74  3767.1 2360.84  3794.5 2351.08  3825.2 2346.71  3859.6 2334.14
  3913.2 2325.35  4214.3 2300.11  4567.2 2276.11    4670 2278.95  4765.1 2273.79
  4902.9 2274.24  4956.5 2270.35  4972.7 2261.44  4973.2 2260.94  4983.6 2261.44
  4983.9 2265.83  4999.9 2276.37  5022.9 2281.71  5098.1 2283.77    5154 2284.75
  5197.5 2285.82  5426.2 2290.01  5514.3 2291.35    5685 2296.88  5965.7 2307.98
  6049.6 2314.23  6080.9 2321.02  6115.5 2340.39  6207.1 2362.16  6356.6 2364.14
#Mann= 10 ,-1 , 0
  3710.7     .07       0  4214.3     .16       0  4972.7     .07       0
  4983.6     .16       0  5098.1     .07       0    5154     .16       0
  5197.5     .07       0  5426.2     .16       0  5514.3     .07       0
    5685     .16       0
Bank Sta=4972.7,4983.6
XS Rating Curve= 0 ,0
Exp/Cntr=0.3,0.1

Type RM Length L Ch R = 1 ,309677  ,1041,1041,1041
BEGIN DESCRIPTION:
Mapping XS bafd2d0d
END DESCRIPTION:
XS GIS Cut Line= 3
      1453699.47      6803895.65      1454944.22      6803432.12
      1456287.93      6802739.44
#Sta/Elev= 30
  3669.5 2362.94  3678.9  2363.5  3703.9 2355.79  3764.6 2344.76  3789.6 2336.23
  3844.9 2330.79  3850.2 2332.61  3875.2 2325.33    4241 2294.79  4278.6 2296.33
  4434.2 2285.99  4667.8 2270.25  4955.9 2267.51  4969.2  2265.8  4982.4 2258.53
  4982.9 2258.03  4993.5 2258.53  4994.2 2261.56    5001 2261.43  5009.9 2270.04
  5016.6 2271.89  5304.7 2278.58  5765.7 2301.81  5806.3 2303.81  6146.2 2320.24
  6285.1 2330.31  6337.4 2343.85  6382.4 2350.26  6418.1 2361.36  6509.5 2365.36
#Mann= 6 ,-1 , 0
  3669.5     .07       0  4434.2     .16       0  4982.4     .07       0
  4993.5     .16       0  5765.7     .07       0  5806.3     .16       0
Bank Sta=4982.4,4993.5
XS Rating Curve= 0 ,0
Exp/Cntr=0.3,0.1

Type RM Length L Ch R = 1 ,308636  ,664,664,664
BEGIN DESCRIPTION:
Mapping XS 2a154490
END DESCRIPTION:
XS GIS Cut Line= 3
      1453779.81      6804698.74      1455389.21      6803907.06
      1456222.52      6803292.49
#Sta/Elev= 30
  3218.3 2368.32  3268.7 2364.35  3313.2 2351.04  3365.3 2329.09  3431.3 2318.58
  3581.6 2307.56  4117.2 2286.58  4182.9 2283.96  4237.2 2282.13    4327 2278.67
  4423.3 2275.24  4677.4 2268.06  4857.9 2263.52  4900.3 2261.24  4977.5 2258.55
  5001.1 2250.47  5001.6 2249.97  5012.4 2250.47    5022 2257.12  5137.8 2265.65
    5187 2268.48  5263.4 2280.46  5387.5 2283.86  5614.8 2299.96  5780.4 2316.76
  5809.3 2326.27  5844.8 2344.45  5894.9 2355.58  5980.5 2366.61  6047.3 2368.42
#Mann= 17 ,-1 , 0
  3218.3     .07       0  3431.3     .16       0  3581.6     .07       0
  4117.2     .16       0  4182.9     .07       0  4237.2     .16       0
    4327     .07       0  4423.3     .16       0  4677.4     .07       0
  4857.9     .16       0  4900.3     .07       0  5001.1     .07       0
  5012.4     .07       0  5137.8     .07       0  5263.4     .16       0
  5614.8     .07       0  5780.4     .16       0
Bank Sta=5001.1,5012.4
XS Rating Curve= 0 ,0
Exp/Cntr=0.3,0.1

Type RM Length L Ch R = 1 ,307972  ,923,923,923
BEGIN DESCRIPTION:
Mapping XS bad10022
END DESCRIPTION:
XS GIS Cut Line= 3
      1454066.31      6805115.39      1455519.42      6804422.68
      1456599.74      6803892.91
#Sta/Elev= 30
  3413.1 2367.78  3446.2 2364.17  3494.8  2350.6  3514.2 2343.36  3544.6 2323.07
  3576.8 2313.56  3695.8 2298.06  3890.8 2287.33  4193.5 2274.81  4918.3 2261.47
  4962.6 2255.04    4979 2244.22  4979.5 2243.72  4990.4 2244.22  5029.1 2252.25
    5197 2251.01  5285.3  2266.1  5344.6 2268.04  5597.1 2283.57  5630.2 2274.73
  5675.1 2281.92  5703.2 2292.28  5708.8 2288.32  5725.7 2294.66  5942.4  2323.8
  5995.6 2337.69  6001.2 2335.16  6098.3 2364.24  6153.1 2369.09  6226.1 2367.54
#Mann= 8 ,-1 , 0
  3413.1     .16       0  3494.8     .07       0  3890.8     .05       0
  4193.5     .07       0    4979     .07       0  4990.4     .07       0
    5197     .16       0  5344.6     .07       0
Bank Sta=4979,4990.4
XS Rating Curve= 0 ,0
Exp/Cntr=0.3,0.1

Type RM Length L Ch R = 1 ,307049  ,1274,1274,1274
BEGIN DESCRIPTION:
Mapping XS 624442e2
END DESCRIPTION:
XS GIS Cut Line= 3
      1454045.48      6805157.06      1455920.46      6805089.35
      1456950.88      6804220.26
#Sta/Elev= 30
  3098.9  2368.2  3128.4 2363.51  3168.5 2350.27  3234.6 2320.75  3268.5 2310.88
  3328.6 2300.79  3438.6 2288.11  3506.9 2283.94  3601.2 2278.92    3949 2264.77
  4200.9 2258.46  4595.6 2254.26  4799.5  2247.9  4929.6 2249.74  4969.6 2241.12
  5000.6 2239.51  5001.5 2235.72    5002 2235.22    5013 2235.72  5057.7 2248.21
  5089.3 2250.64  5228.1 2257.88  5234.6 2260.95  5242.4  2258.1  5298.4  2259.6
  5817.3 2298.52  5958.9 2307.77  6157.8 2334.05    6250 2349.21  6323.1 2368.61
#Mann= 9 ,-1 , 0
  3098.9     .16       0  3234.6     .07       0  3506.9     .05       0
  3601.2     .07       0  4200.9     .16       0  5001.5     .07       0
    5013     .16       0  5089.3     .07       0  5817.3     .16       0
Bank Sta=5001.5,5013
XS Rating Curve= 0 ,0
Exp/Cntr=0.3,0.1

Type RM Length L Ch R = 1 ,305775  ,878,878,878
BEGIN DESCRIPTION:
Mapping XS 7388a1de
END DESCRIPTION:
XS GIS Cut Line= 3
      1454509.44      6805826.77      1455884.43       6806035.1
      1457439.98      6805673.99
#Sta/Elev= 30
  3577.2 2269.16  3876.1 2258.66  4280.7 2251.16  4361.6  2247.9  4477.6  2245.9
  4619.8 2242.13  4735.8 2242.25  4807.2 2240.82    4935 2240.65  4958.6 2239.96
  4965.6 2237.33  4970.7 2237.33  4975.4 2232.71  4980.5 2233.83  4993.3 2223.62
  4993.8 2223.12  5005.3 2223.62  5009.5 2226.16  5030.1 2229.33  5113.6 2229.85
  5163.5 2236.89  5569.3 2245.67  5577.4 2245.68  5830.8 2254.77  5984.8  2258.7
  6132.7 2264.76    6235 2269.99  6396.4 2278.78  6518.6 2287.64  6564.8 2292.36
#Mann= 10 ,-1 , 0
  3577.2     .07       0  4477.6     .16       0  4807.2     .05       0
    4935     .16       0  4993.3     .07       0  5005.3     .16       0
  5569.3     .07       0  5577.4     .16       0  6132.7     .07       0
    6235     .16       0
Bank Sta=4993.3,5005.3
XS Rating Curve= 0 ,0
Exp/Cntr=0.3,0.1