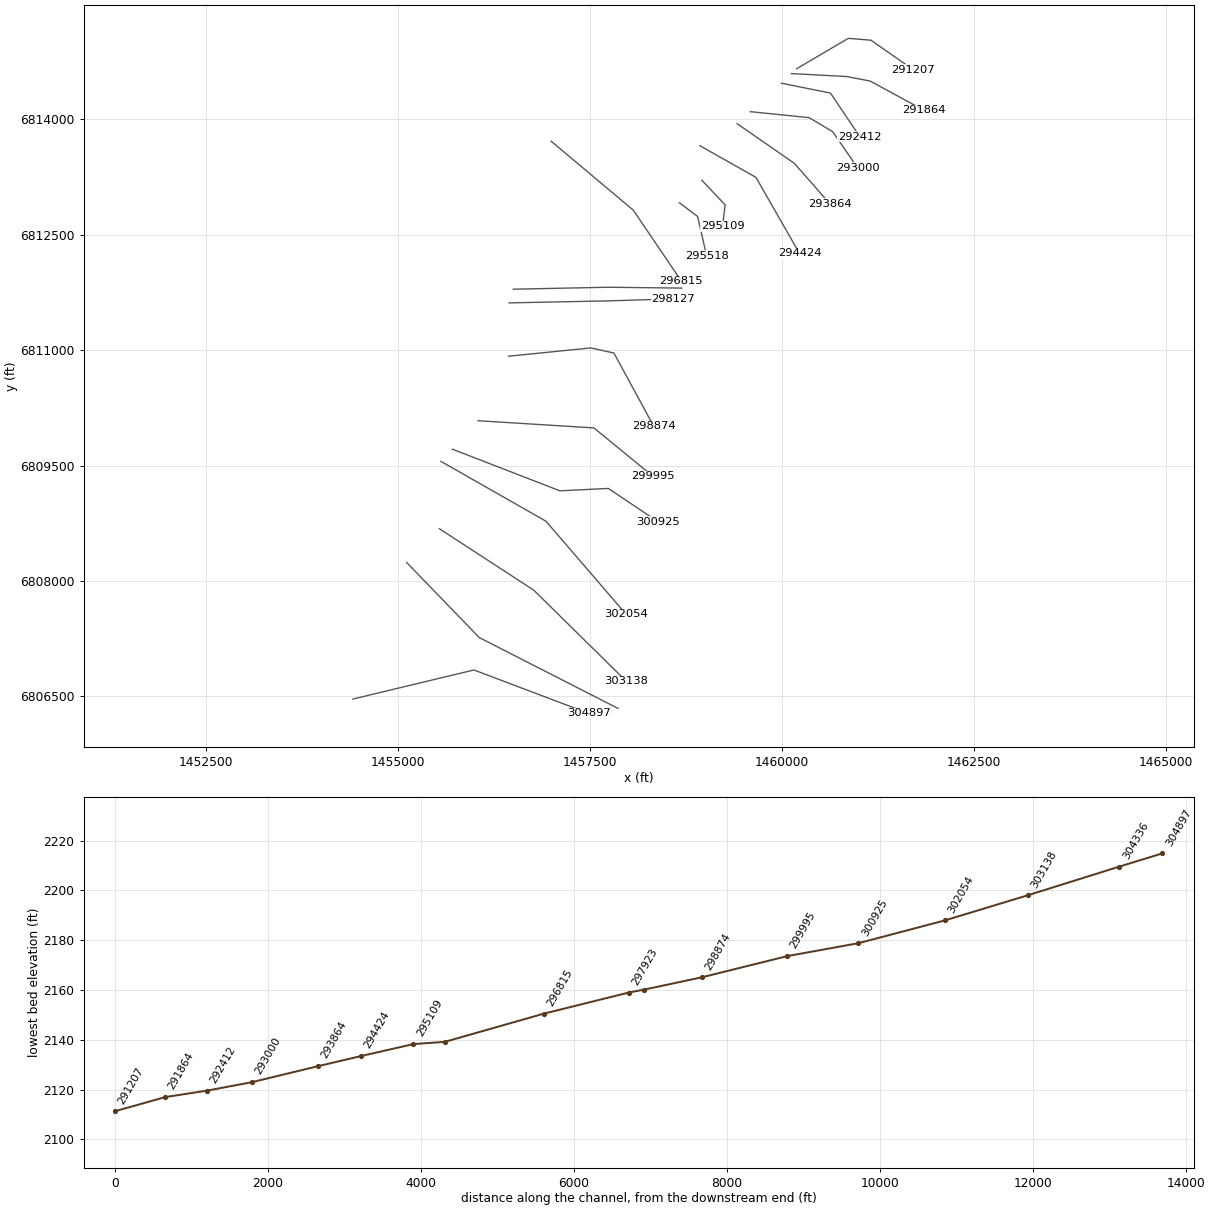
HEC-RAS study MULBERRY CREEK.prj: MULBERRY CREEK Base Level Engineering

--- MULBERRY CREEK.g01 (geometry) --- (continued)

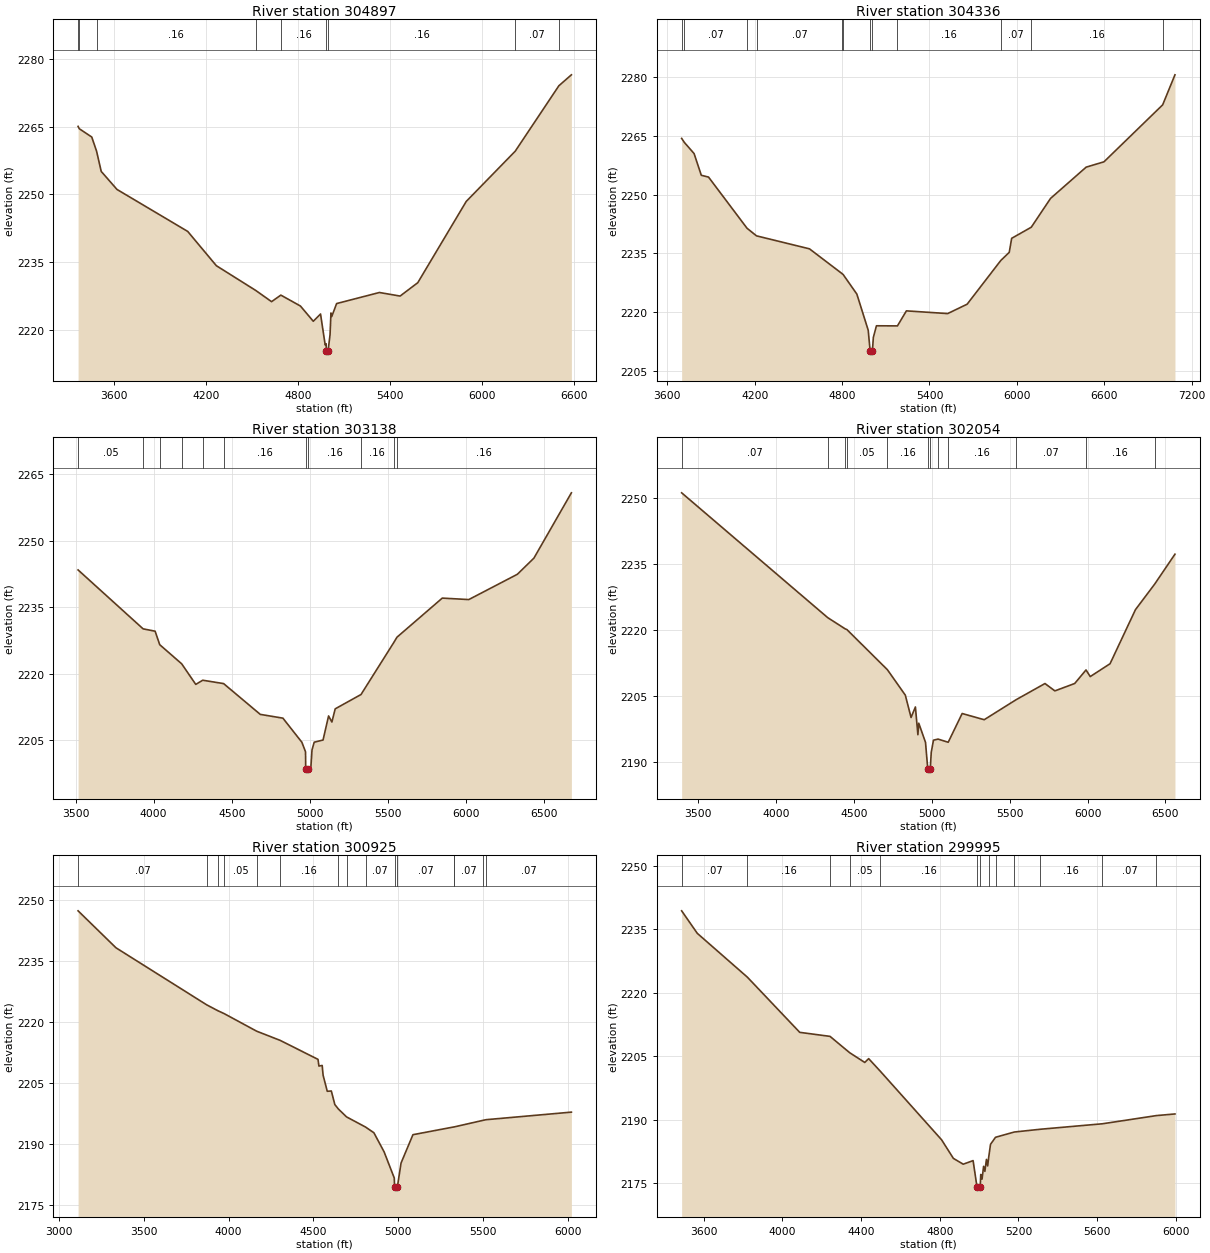
Type RM Length L Ch R = 1 ,304897  ,561,561,561
BEGIN DESCRIPTION:
Mapping XS 6a5c3aa9
END DESCRIPTION:
XS GIS Cut Line= 3
      1454418.27      6806465.65      1455993.81      6806843.26
       1457486.9      6806279.01
#Sta/Elev= 30
  3367.5 2265.07  3375.2 2264.55  3456.7 2262.71    3488 2259.59  3518.4  2255.1
  3621.2 2251.11  4082.2 2241.82  4269.1 2234.23  4526.5 2228.74    4629 2226.27
  4689.5 2227.72  4817.1 2225.31  4901.1 2221.93  4948.3 2223.54  4978.6  2216.7
  4985.1 2216.95  4985.2 2215.38  4985.7 2214.88  4997.4 2215.38  5010.3 2218.96
  5016.2 2223.77  5021.5 2222.99  5053.1 2225.85  5332.1  2228.3    5467 2227.51
  5582.3 2230.47  5898.3 2248.46  6217.7 2259.58  6502.2 2274.06  6583.8 2276.48
#Mann= 9 ,-1 , 0
  3367.5     .16       0  3375.2     .07       0    3488     .16       0
  4526.5     .05       0  4689.5     .16       0  4985.2     .07       0
  4997.4     .16       0  6217.7     .07       0  6502.2     .16       0
Bank Sta=4985.2,4997.4
XS Rating Curve= 0 ,0
Exp/Cntr=0.3,0.1

Type RM Length L Ch R = 1 ,304336  ,1198,1198,1198
BEGIN DESCRIPTION:
Mapping XS bb62bed0
END DESCRIPTION:
XS GIS Cut Line= 3
       1455117.1       6808240.8      1456063.25      6807264.26
       1457868.8      6806344.13
#Sta/Elev= 30
  3698.8 2264.32  3716.8 2263.32  3784.2 2260.45  3833.6 2254.92  3883.3 2254.46
  4147.8 2241.41  4212.6 2239.48  4576.3 2236.17  4800.4 2229.84  4807.9  2229.6
  4901.4 2224.64  4979.4 2215.43  4992.7 2210.09  4993.2 2209.59  5008.2 2210.09
  5014.6 2213.59  5035.9 2216.56    5180 2216.53  5241.6 2220.36    5525 2219.67
  5658.4 2222.06    5889 2233.18  5947.5 2235.28  5964.1 2238.85  6098.7 2241.68
    6231 2249.02  6475.5 2256.99  6597.7 2258.35  7000.6 2272.87    7085 2280.52
#Mann= 12 ,-1 , 0
  3698.8     .16       0  3716.8     .07       0  4147.8     .05       0
  4212.6     .07       0  4800.4     .05       0  4807.9     .07       0
  4992.7     .07       0  5008.2     .07       0    5180     .16       0
    5889     .07       0  6098.7     .16       0  7000.6     .07       0
Bank Sta=4992.7,5008.2
XS Rating Curve= 0 ,0
Exp/Cntr=0.3,0.1

Type RM Length L Ch R = 1 ,303138  ,1084,1084,1084
BEGIN DESCRIPTION:
Mapping XS 57f31b2c
END DESCRIPTION:
XS GIS Cut Line= 3
      1455543.02      6808679.76      1456772.17      6807881.16
      1457980.24      6806693.92
#Sta/Elev= 30
  3515.9 2243.41  3932.4 2230.13  4009.3  2229.6  4038.8 2226.56  4179.5 2222.25
  4269.6 2217.61  4314.4 2218.55    4448 2217.79  4682.8 2210.85  4827.8    2210
  4949.3 2204.57  4972.8 2202.41  4973.8 2198.56  4974.3 2198.06  4989.5 2198.56
  5007.2 2199.08  5014.2 2202.85  5028.3 2204.58  5084.9 2205.07  5120.3  2210.5
  5141.5 2209.13  5162.7  2212.1  5328.1 2215.33  5536.9 2226.99  5558.5 2228.25
  5848.6 2237.06  6018.4 2236.73  6329.5 2242.43  6435.5 2246.07  6675.5 2260.79
#Mann= 11 ,-1 , 0
  3515.9     .05       0  3932.4     .07       0  4038.8     .05       0
  4179.5     .16       0  4314.4     .05       0    4448     .16       0
  4973.8     .07       0  4989.5     .16       0  5328.1     .16       0
  5536.9     .07       0  5558.5     .16       0
Bank Sta=4973.8,4989.5
XS Rating Curve= 0 ,0
Exp/Cntr=0.3,0.1

Type RM Length L Ch R = 1 ,302054  ,1129,1129,1129
BEGIN DESCRIPTION:
Mapping XS afd968af
END DESCRIPTION:
XS GIS Cut Line= 3
      1455563.79       6809554.8      1456931.89        6808777.
      1457973.56      6807568.66
#Sta/Elev= 30
  3392.6 2251.19  4330.6 2222.84  4442.4  2220.3  4454.3 2220.12  4714.4    2211
  4829.5 2205.22  4866.4 2200.15  4894.3 2202.54  4910.2 2196.24  4915.9 2198.85
  4959.2 2194.49  4973.7 2188.46  4974.2 2187.96  4989.8 2188.46  4996.1 2192.25
  5010.3 2194.99  5039.7 2195.24    5105 2194.52  5194.6 2201.05  5336.2 2199.64
  5542.3 2204.21  5726.7 2207.86  5790.3 2206.19  5917.6 2207.87  5990.4 2210.95
  6017.4 2209.44  6144.7 2212.36  6308.2 2224.66  6430.8 2230.42  6561.7 2237.25
#Mann= 12 ,-1 , 0
  3392.6     .07       0  4330.6     .05       0  4442.4     .16       0
  4454.3     .05       0  4714.4     .16       0  4973.7     .07       0
  4989.8     .16       0  5039.7     .07       0    5105     .16       0
  5542.3     .07       0  5990.4     .16       0  6430.8     .07       0
Bank Sta=4973.7,4989.8
XS Rating Curve= 0 ,0
Exp/Cntr=0.3,0.1

Type RM Length L Ch R = 1 ,300925  ,930,930,930
BEGIN DESCRIPTION:
Mapping XS ce511c37
END DESCRIPTION:
XS GIS Cut Line= 4
      1455712.26      6809713.85      1457113.31      6809172.17
      1457743.52      6809203.42      1458387.97      6808772.06
#Sta/Elev= 30
  3112.2 2247.39  3335.7 2238.28  3870.8 2224.22  3937.3 2222.76  3974.1 2222.05
  4165.3 2217.73  4303.1 2215.48  4526.9 2210.79  4532.3 2209.14  4551.5 2209.29
  4556.9 2206.89  4581.4 2202.93  4605.4    2203    4626 2199.66    4647 2198.56
  4695.1 2196.62  4806.9 2194.12  4856.3 2192.71  4916.4 2188.02  4976.5 2181.56
  4978.4 2179.32  4978.9 2178.82  4994.6 2179.32  5016.5 2185.25  5086.6 2192.23
  5326.4 2194.13  5328.9 2194.14  5500.2 2195.77  5518.4 2195.93  6020.8 2197.79
#Mann= 15 ,-1 , 0
  3112.2     .07       0  3870.8     .16       0  3937.3     .07       0
  3974.1     .05       0  4165.3     .07       0  4303.1     .16       0
    4647     .07       0  4695.1     .16       0  4806.9     .07       0
  4978.4     .07       0  4994.6     .07       0  5326.4     .16       0
  5328.9     .07       0  5500.2     .16       0  5518.4     .07       0
Bank Sta=4978.4,4994.6
XS Rating Curve= 0 ,0
Exp/Cntr=0.3,0.1

Type RM Length L Ch R = 1 ,299995  ,1121,1121,1121
BEGIN DESCRIPTION:
Mapping XS bc011a73
END DESCRIPTION:
XS GIS Cut Line= 3
      1456045.59      6810083.63      1457556.02      6809989.88
      1458326.85      6809359.68
#Sta/Elev= 30
  3487.2 2239.38  3566.8 2234.06  3821.4 2223.71  4087.8 2210.67  4241.9 2209.72
  4341.2 2205.88  4418.4 2203.56  4438.4 2204.46  4497.8 2201.47  4809.2 2185.29
  4869.3 2180.89  4919.4 2179.52  4969.5 2180.37  4989.4 2174.13  4989.9 2173.63
  5005.6 2174.13  5008.5 2177.09    5015 2175.99  5022.9 2179.02  5029.4 2177.83
  5037.3 2180.65  5043.7 2179.11  5048.1  2180.9  5058.1 2184.21  5083.6 2185.88
    5179 2187.12  5309.9 2187.77  5627.4 2189.07  5901.4    2191  5996.2 2191.39
#Mann= 13 ,-1 , 0
  3487.2     .07       0  3821.4     .16       0  4241.9     .07       0
  4341.2     .05       0  4497.8     .16       0  4989.4     .07       0
  5005.6     .16       0  5048.1     .07       0  5083.6     .16       0
    5179     .07       0  5309.9     .16       0  5627.4     .07       0
  5901.4     .16       0
Bank Sta=4989.4,5005.6
XS Rating Curve= 0 ,0
Exp/Cntr=0.3,0.1

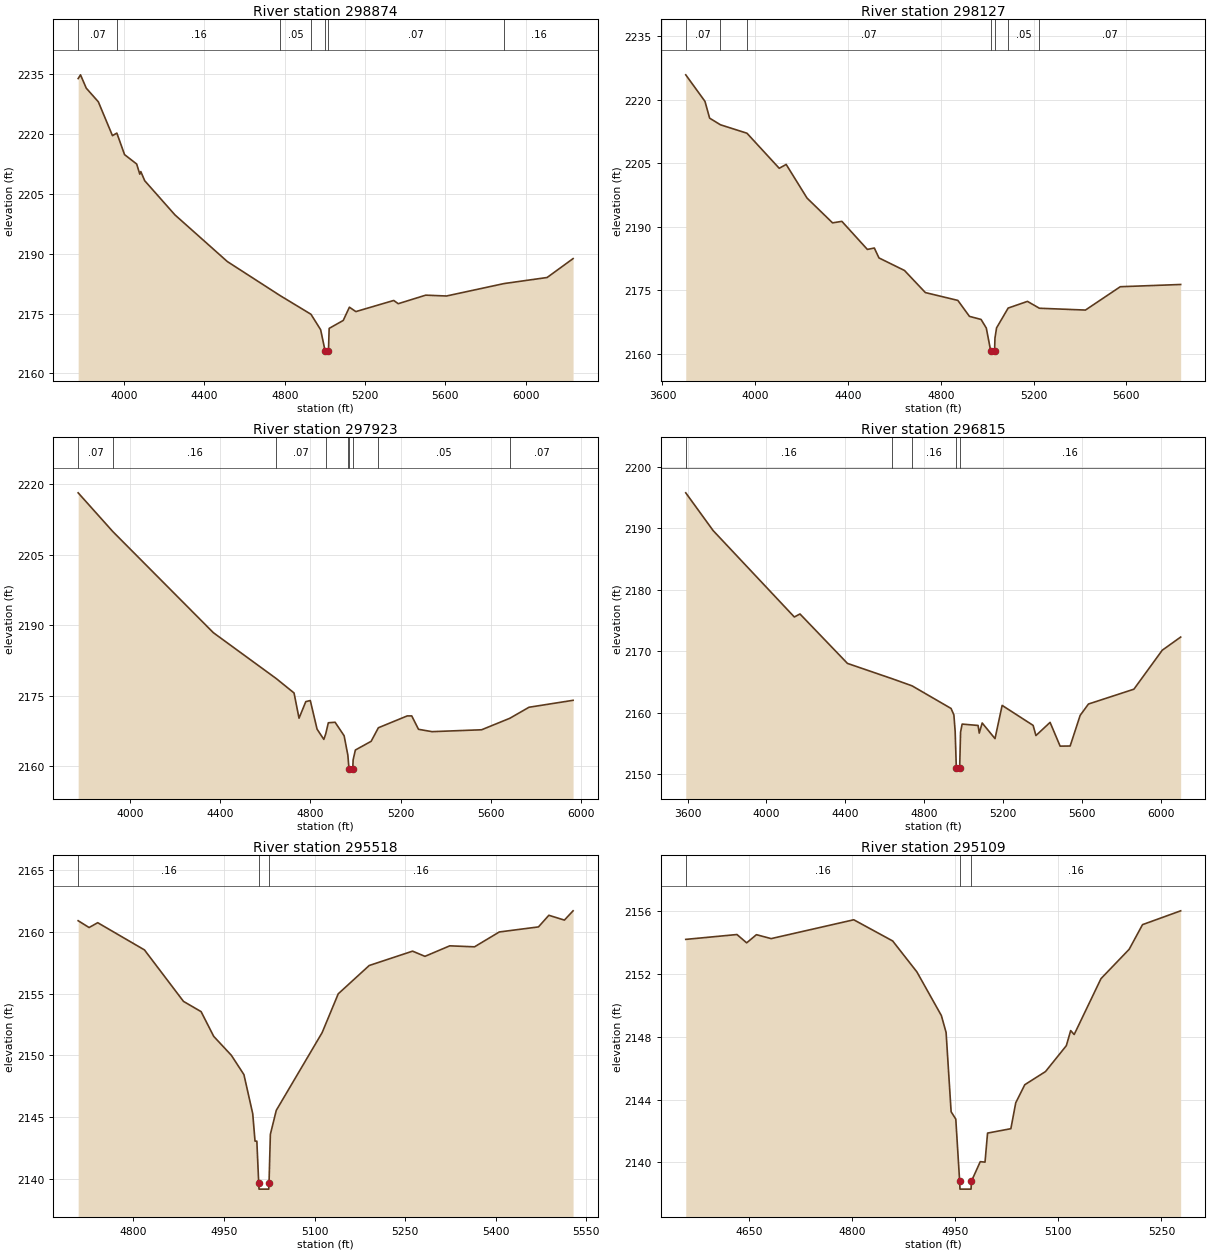
Type RM Length L Ch R = 1 ,298874  ,747,747,747
BEGIN DESCRIPTION:
Mapping XS 10d38fb1
END DESCRIPTION:
XS GIS Cut Line= 4
      1456444.89      6810922.17      1457514.35      6811029.81
      1457816.44      6810963.84      1458333.64      6810012.74
#Sta/Elev= 30
  3770.4 2233.96  3782.1  2234.9  3810.7 2231.56    3871 2228.13  3941.4 2219.64
  3963.2 2220.29  4001.7 2214.88    4062 2212.53  4077.6 2209.98  4082.7 2210.63
  4102.2 2208.33  4252.9 2199.76  4514.2 2188.05  4776.7 2179.53  4930.7 2174.84
    4979 2170.96  5001.4 2165.59  5001.9 2165.09  5017.9 2165.59  5021.4  2171.3
  5091.6 2173.29  5122.3 2176.61  5154.5 2175.51  5343.2  2178.3  5365.8 2177.49
  5502.6 2179.63  5606.1 2179.42  5893.1 2182.54  6107.7 2184.06  6237.1  2188.8
#Mann= 7 ,-1 , 0
  3770.4     .07       0  3963.2     .16       0  4776.7     .05       0
  4930.7     .07       0  5001.4     .07       0  5017.9     .07       0
  5893.1     .16       0
Bank Sta=5001.4,5017.9
XS Rating Curve= 0 ,0
Exp/Cntr=0.3,0.1

Type RM Length L Ch R = 1 ,298127  ,204,204,204
BEGIN DESCRIPTION:
Mapping XS 81e9af2f
END DESCRIPTION:
XS GIS Cut Line= 3
      1456452.08      6811615.46      1457745.47       6811641.5
      1458585.31      6811667.54
#Sta/Elev= 30
  3700.6 2225.92  3783.5 2219.65  3803.5 2215.69  3850.3 2214.12  3964.5 2212.13
  4103.6 2203.85  4133.6 2204.76  4223.6 2196.81  4333.6 2190.96  4373.7 2191.32
  4483.7 2184.69  4513.7 2185.02  4533.7 2182.68  4643.7 2179.72  4733.7  2174.5
  4873.8 2172.65  4923.8 2168.88  4973.8 2168.16  4996.5 2166.12  5015.5  2160.7
    5016  2160.2  5032.1  2160.7  5033.8 2163.75  5040.7 2166.16  5090.7 2170.84
  5173.9 2172.42  5225.3  2170.8    5424 2170.37  5574.1 2175.88  5834.5 2176.41
#Mann= 7 ,-1 , 0
  3700.6     .07       0  3850.3     .16       0  3964.5     .07       0
  5015.5     .07       0  5032.1     .07       0  5090.7     .05       0
  5225.3     .07       0
Bank Sta=5015.5,5032.1
XS Rating Curve= 0 ,0
Exp/Cntr=0.3,0.1

Type RM Length L Ch R = 1 ,297923  ,1108,1108,1108
BEGIN DESCRIPTION:
Mapping XS 6aed492c
END DESCRIPTION:
XS GIS Cut Line= 3
      1456505.45      6811793.41      1457739.83      6811818.59
      1458700.63      6811807.74
#Sta/Elev= 30
  3769.9 2218.21    3924 2209.95  4369.6 2188.45  4649.1 2178.67  4727.6 2175.62
  4749.7 2170.25  4779.7 2173.78  4799.7 2174.01  4829.7 2167.93  4859.7 2165.74
    4868  2166.9  4879.7 2169.28  4909.7 2169.39  4949.7 2166.52  4966.3  2162.4
  4971.4 2159.49  4971.9 2158.99    4988 2159.49  4989.7 2161.39  4999.6 2163.48
  5069.7 2165.34  5101.7 2168.22  5229.7 2170.74  5249.7 2170.74  5279.7 2167.89
  5339.7 2167.39  5559.7 2167.79    5685 2170.24  5769.8 2172.58  5965.4 2174.06
#Mann= 9 ,-1 , 0
  3769.9     .07       0    3924     .16       0  4649.1     .07       0
    4868     .16       0  4966.3     .07       0  4971.4     .07       0
    4988     .07       0  5101.7     .05       0    5685     .07       0
Bank Sta=4971.4,4988
XS Rating Curve= 0 ,0
Exp/Cntr=0.3,0.1

Type RM Length L Ch R = 1 ,296815  ,1297,1297,1297
BEGIN DESCRIPTION:
Mapping XS 4eeb913a
END DESCRIPTION:
XS GIS Cut Line= 3
      1456998.63      6813717.45      1458068.09      6812821.61
      1458694.71      6811898.85
#Sta/Elev= 30
  3590.9 2195.75  3729.7 2189.62  4141.7 2175.58  4170.3 2176.07  4411.1 2168.04
    4639 2165.54  4738.6  2164.4  4936.7 2160.72    4951 2159.68  4957.5    2157
  4963.4 2151.04  4963.9 2150.54  4980.3 2151.04  4984.9 2156.88  4992.9 2158.18
  5073.7 2157.96  5079.7 2156.72  5094.6 2158.36  5159.6 2155.82  5195.8 2161.22
    5353 2157.97  5367.2 2156.32    5439 2158.46  5489.9  2154.6  5540.8 2154.62
  5591.6  2159.6  5633.6 2161.44  5864.2 2163.85  6007.9 2170.18  6101.4 2172.32
#Mann= 5 ,-1 , 0
  3590.9     .16       0    4639     .07       0  4738.6     .16       0
  4963.4     .07       0  4980.3     .16       0
Bank Sta=4963.4,4980.3
XS Rating Curve= 0 ,0
Exp/Cntr=0.3,0.1

Type RM Length L Ch R = 1 ,295518  ,409,409,409
BEGIN DESCRIPTION:
Mapping XS 480aad9f
END DESCRIPTION:
XS GIS Cut Line= 3
      1458669.03      6812916.49      1458906.04      6812739.38
      1459023.23      6812228.94
#Sta/Elev= 30
  4708.5 2160.89  4726.6 2160.34  4740.9 2160.73  4818.3 2158.53  4882.9 2154.37
  4912.1 2153.54    4933 2151.54  4962.2 2150.01    4983 2148.45  4997.6 2145.29
  5001.4 2143.07  5004.4 2143.07  5007.5 2139.69    5008 2139.19  5024.1 2139.19
  5024.6 2139.69  5026.8 2143.62  5036.6 2145.56  5112.5 2151.84  5139.2 2154.98
  5190.5 2157.27  5262.3 2158.43  5282.8 2158.01  5323.9 2158.86  5364.9 2158.78
  5405.9 2159.98  5470.8 2160.39    5488 2161.33  5513.7 2160.94  5528.1 2161.69
#Mann= 3 ,-1 , 0
  4708.5     .16       0  5007.5     .07       0  5024.6     .16       0
Bank Sta=5007.5,5024.6
XS Rating Curve= 0 ,0
Exp/Cntr=0.3,0.1

Type RM Length L Ch R = 1 ,295109  ,685,685,685
BEGIN DESCRIPTION:
Mapping XS f5f8d061
END DESCRIPTION:
XS GIS Cut Line= 3
      1458961.35      6813209.76      1459265.05      6812888.77
        1459230.      6812612.99
#Sta/Elev= 30
  4558.1 2154.21  4632.6 2154.52  4646.7 2153.99  4660.9 2154.51  4682.3 2154.26
  4802.5 2155.46  4859.1 2154.11  4894.3 2152.14  4929.9 2149.36  4936.8 2148.28
  4944.1 2143.23  4950.9 2142.76  4956.5  2138.8    4957  2138.3  4973.1  2138.3
  4973.6  2138.8  4986.5 2140.05  4993.4 2140.02  4997.1 2141.87    5031 2142.15
  5038.1  2143.8  5051.2 2144.95  5081.4 2145.79  5111.7 2147.44    5118  2148.4
  5123.1 2148.15  5162.1 2151.71  5203.1 2153.58  5222.5 2155.15    5278 2156.03
#Mann= 3 ,-1 , 0
  4558.1     .16       0  4956.5     .07       0  4973.6     .16       0
Bank Sta=4956.5,4973.6
XS Rating Curve= 0 ,0
Exp/Cntr=0.3,0.1

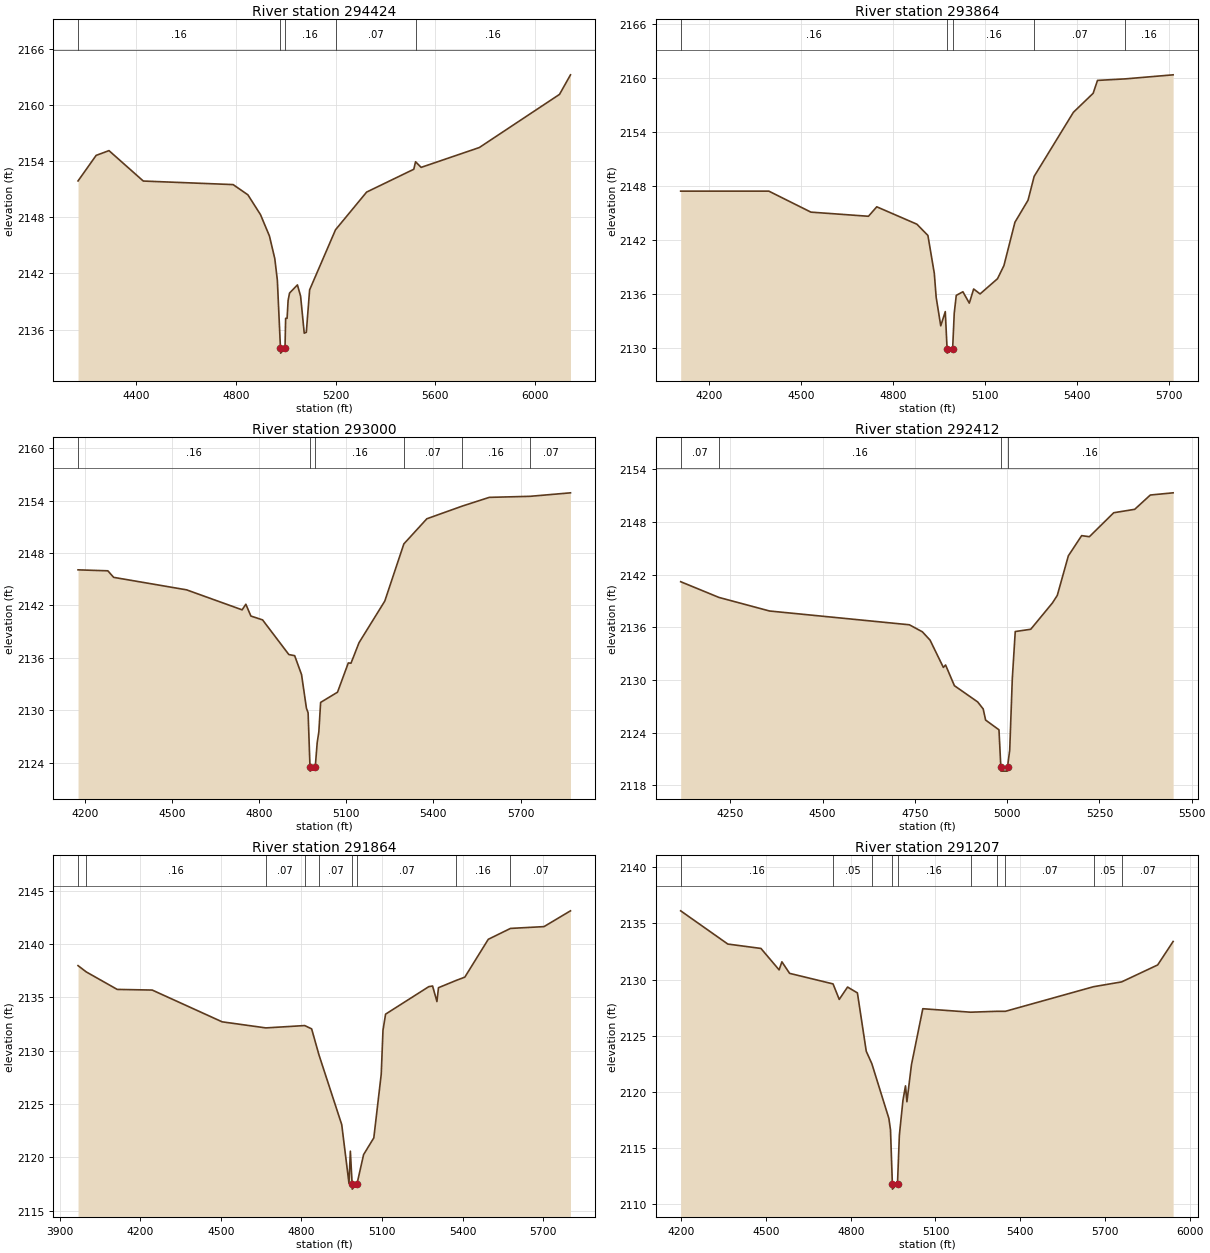
Type RM Length L Ch R = 1 ,294424  ,560,560,560
BEGIN DESCRIPTION:
Mapping XS 94bbcc64
END DESCRIPTION:
XS GIS Cut Line= 3
      1458936.71       6813658.7      1459665.83      6813247.26
      1460233.56      6812257.64
#Sta/Elev= 30
  4165.2 2151.89  4237.9 2154.62  4289.5 2155.13  4427.3 2151.88  4788.1  2151.5
  4847.4 2150.41  4898.1 2148.29    4934 2146.01  4955.6 2143.58  4965.8 2141.29
  4978.4 2133.99  4978.9 2133.49  4996.5 2133.99  4999.1 2137.21  5004.9 2137.21
    5009 2139.12  5014.8 2139.91  5046.4 2140.78  5059.2 2139.58  5073.8 2135.62
  5082.2 2135.72  5095.4 2140.25  5199.4 2146.67  5324.4  2150.7  5513.9 2153.14
  5520.9 2153.94  5543.4 2153.34  5777.1 2155.46  6099.2 2161.14  6143.3 2163.23
#Mann= 5 ,-1 , 0
  4165.2     .16       0  4978.4     .07       0  4996.5     .16       0
  5199.4     .07       0  5520.9     .16       0
Bank Sta=4978.4,4996.5
XS Rating Curve= 0 ,0
Exp/Cntr=0.3,0.1

Type RM Length L Ch R = 1 ,293864  ,864,864,864
BEGIN DESCRIPTION:
Mapping XS f4dff2ac
END DESCRIPTION:
XS GIS Cut Line= 3
        1459421.       6813945.2      1460165.83      6813429.55
      1460629.35      6812903.54
#Sta/Elev= 30
  4107.5 2147.43  4395.3 2147.43  4532.5  2145.1  4720.3 2144.64  4747.4 2145.69
  4878.4 2143.76  4914.3 2142.51  4935.2  2138.3  4941.3 2135.63  4956.2 2132.48
    4971 2134.06  4976.8 2129.95  4977.3 2129.45    4995 2129.95  5000.2 2133.88
  5006.8 2135.86  5028.5 2136.26  5049.4    2135  5063.6 2136.57  5084.5 2136.02
  5141.4 2137.71  5162.3 2139.16  5198.3 2143.98    5241 2146.42    5261 2149.07
    5389 2156.18  5453.5 2158.29  5467.7 2159.72  5558.3 2159.89  5714.5 2160.34
#Mann= 5 ,-1 , 0
  4107.5     .16       0  4976.8     .07       0    4995     .16       0
    5261     .07       0  5558.3     .16       0
Bank Sta=4976.8,4995
XS Rating Curve= 0 ,0
Exp/Cntr=0.3,0.1

Type RM Length L Ch R = 1 ,293000  ,588,588,588
BEGIN DESCRIPTION:
Mapping XS 8861111e
END DESCRIPTION:
XS GIS Cut Line= 4
      1459592.89      6814101.43      1460358.54       6814023.3
      1460665.83      6813841.01      1460988.51      6813372.61
#Sta/Elev= 30
  4176.3 2146.07  4278.9 2145.96    4299 2145.21  4550.1 2143.78  4741.3 2141.49
  4754.1 2142.13  4771.5 2140.78  4811.7 2140.34  4902.2 2136.37  4922.3 2136.24
  4945.9 2134.08  4962.7 2130.23  4968.5  2129.7    4975 2123.52  4975.5 2123.02
  4993.2 2123.52  4999.7 2126.26  5005.5 2127.53  5011.6 2130.89  5069.8 2132.06
  5106.9 2135.41  5116.2 2135.38  5143.9 2137.73  5232.5 2142.49  5298.2 2149.04
  5377.4 2151.92  5500.1 2153.38  5592.4 2154.37  5733.1 2154.49    5872 2154.89
#Mann= 6 ,-1 , 0
  4176.3     .16       0    4975     .07       0  4993.2     .16       0
  5298.2     .07       0  5500.1     .16       0  5733.1     .07       0
Bank Sta=4975,4993.2
XS Rating Curve= 0 ,0
Exp/Cntr=0.3,0.1

Type RM Length L Ch R = 1 ,292412  ,548,548,548
BEGIN DESCRIPTION:
Mapping XS 9e72d154
END DESCRIPTION:
XS GIS Cut Line= 3
      1459997.47      6814471.21      1460636.32      6814342.75
      1461018.24       6813776.8
#Sta/Elev= 30
  4115.4  2141.2    4219 2139.41  4356.3 2137.86  4735.1 2136.29  4770.3 2135.49
  4791.2 2134.54  4827.2 2131.43  4833.2 2131.71  4857.1 2129.35  4920.1  2127.5
  4935.1  2126.7  4941.7 2125.43  4977.9 2124.32  4982.9 2120.11  4983.4 2119.61
  5000.6 2119.61  5001.1 2120.11    5007    2122    5014 2130.13    5022 2135.52
    5064 2135.78  5122.6 2138.77  5135.9 2139.64  5165.9 2144.15  5201.9 2146.45
  5222.9 2146.33  5288.8 2149.06  5345.7 2149.45    5388 2151.08  5449.8 2151.33
#Mann= 4 ,-1 , 0
  4115.4     .07       0    4219     .16       0  4982.9     .07       0
  5001.1     .16       0
Bank Sta=4982.9,5001.1
XS Rating Curve= 0 ,0
Exp/Cntr=0.3,0.1

Type RM Length L Ch R = 1 ,291864  ,657,657,657
BEGIN DESCRIPTION:
Mapping XS fa74b9ac
END DESCRIPTION:
XS GIS Cut Line= 4
      1460129.42      6814596.22      1460848.12      6814558.02
      1461153.68        6814499.      1461858.52      6814117.06
#Sta/Elev= 30
  3968.7 2137.97  3999.4 2137.38  4114.5 2135.74  4244.7 2135.68    4505  2132.7
  4667.8 2132.13  4812.2 2132.35    4838 2132.04  4865.4 2129.59    4950 2123.06
    4977 2117.55  4982.1 2120.57  4988.6 2117.51  4989.1 2117.01  5006.9 2117.51
  5031.4 2120.25  5069.4 2121.82    5097 2127.79  5103.5 2131.91  5113.2 2133.42
  5274.1    2136  5288.1 2136.06  5304.3  2134.6    5310  2135.9  5375.5 2136.58
    5408 2136.89  5495.4 2140.44    5578 2141.46  5702.7 2141.63  5801.3 2143.11
#Mann= 9 ,-1 , 0
  3968.7     .07       0  3999.4     .16       0  4667.8     .07       0
  4812.2     .16       0  4865.4     .07       0  4988.6     .07       0
  5006.9     .07       0  5375.5     .16       0    5578     .07       0
Bank Sta=4988.6,5006.9
XS Rating Curve= 0 ,0
Exp/Cntr=0.3,0.1

Type RM Length L Ch R = 1 ,291207  ,736,736,736
BEGIN DESCRIPTION:
Mapping XS 3ecf19a4
END DESCRIPTION:
XS GIS Cut Line= 4
      1460195.37      6814658.73      1460868.96      6815054.55
      1461164.09      6815030.25      1461711.32      6814649.27
#Sta/Elev= 30
  4197.5 2136.12  4364.5 2133.16  4481.8 2132.77  4546.2 2130.86    4556 2131.58
  4583.3 2130.55  4737.2 2129.61  4759.1 2128.23  4788.6 2129.33  4823.5 2128.81
  4854.8 2123.61  4874.5 2122.51  4934.9 2117.63  4940.7  2116.6  4947.2 2111.83
  4947.7 2111.33  4965.5 2111.83  4972.1 2116.15  4984.8 2119.24  4993.8 2120.53
  4998.8 2119.11  5014.9 2122.41  5055.1  2127.4  5224.7 2127.09  5316.5 2127.17
  5347.7 2127.17  5659.7 2129.36  5759.4 2129.79    5887  2131.3  5941.7 2133.39
#Mann= 10 ,-1 , 0
  4197.5     .16       0  4737.2     .05       0  4874.5     .16       0
  4947.2     .07       0  4965.5     .16       0  5224.7     .07       0
  5316.5     .16       0  5347.7     .07       0  5659.7     .05       0
  5759.4     .07       0
Bank Sta=4947.2,4965.5
XS Rating Curve= 0 ,0
Exp/Cntr=0.3,0.1