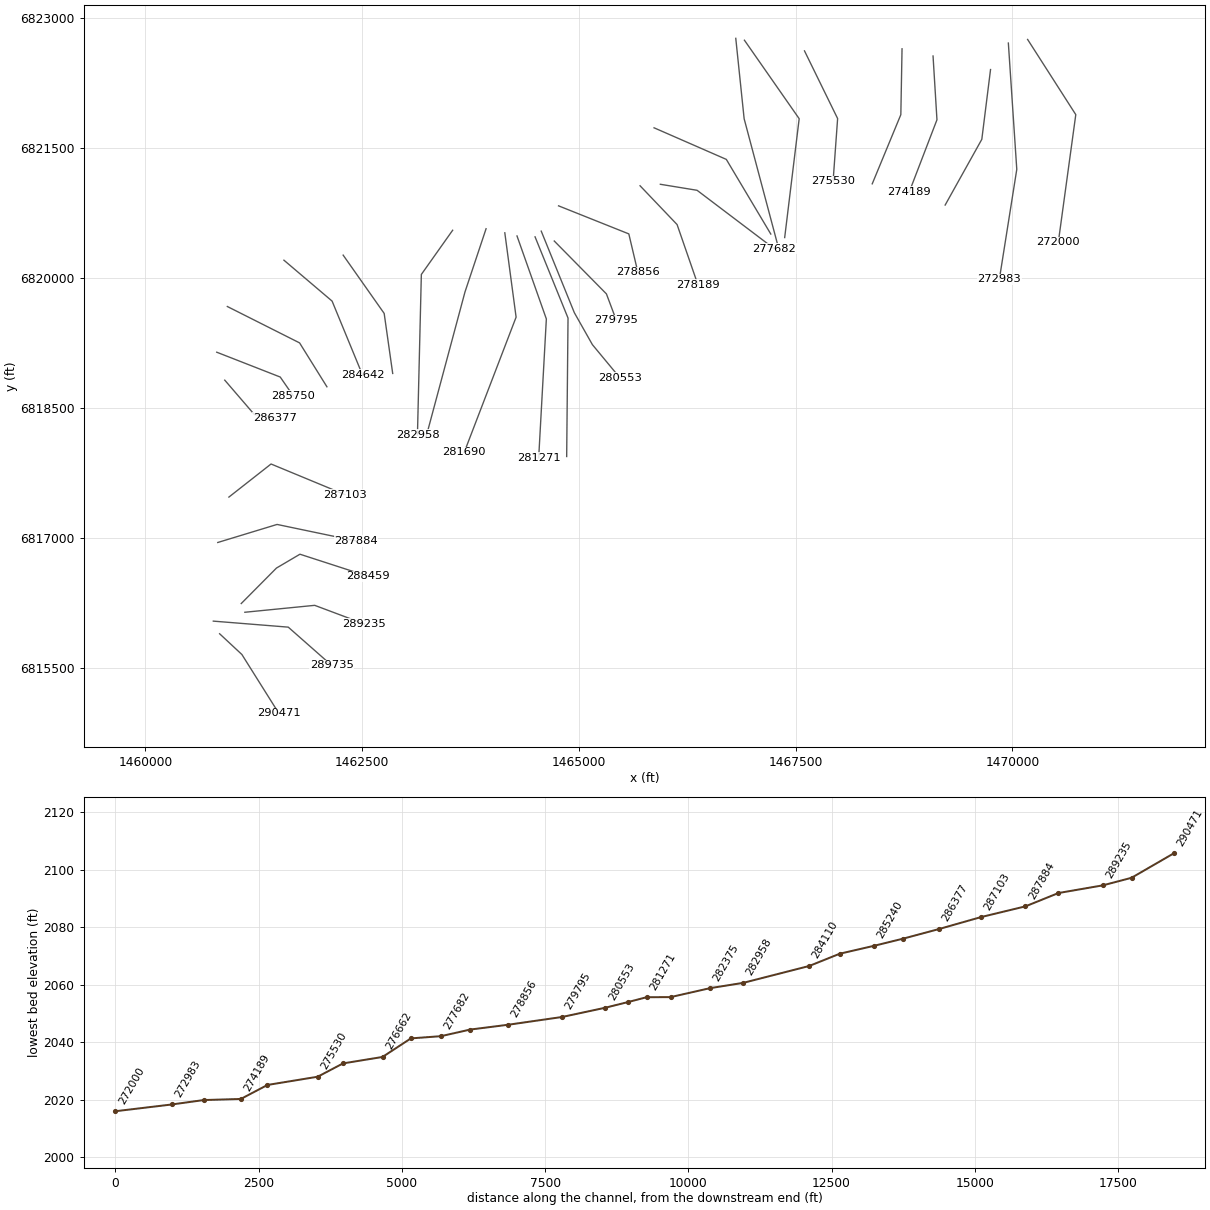
HEC-RAS study MULBERRY CREEK.prj: MULBERRY CREEK Base Level Engineering

--- MULBERRY CREEK.g01 (geometry) --- (continued)

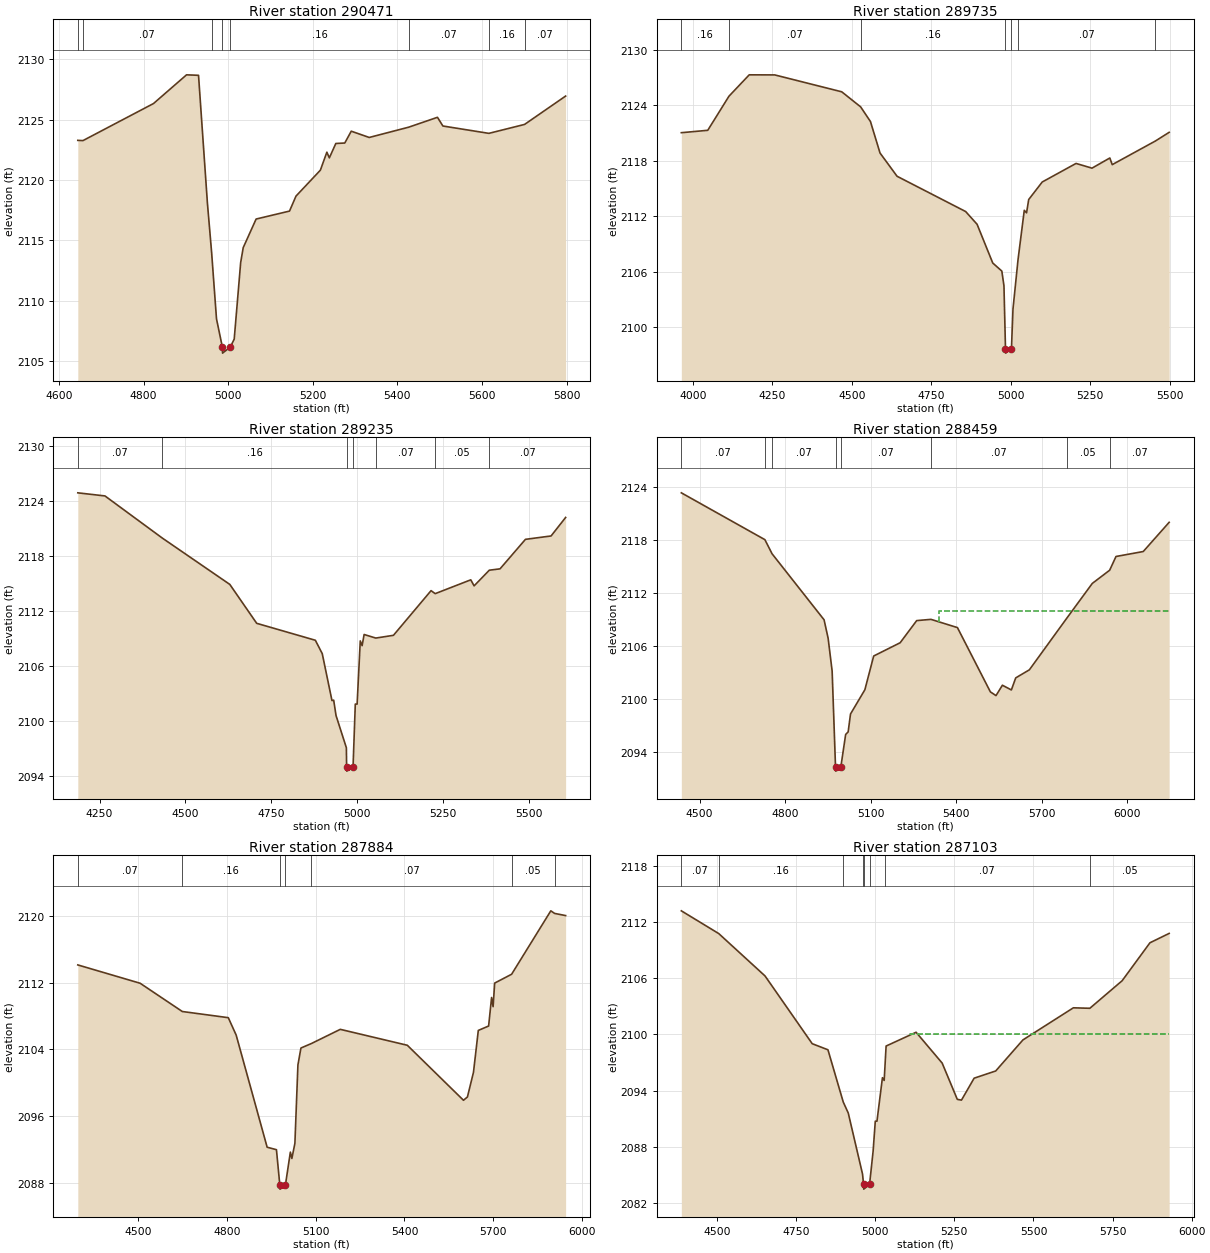
Type RM Length L Ch R = 1 ,290471  ,736,736,736
BEGIN DESCRIPTION:
Mapping XS 80bc9037
END DESCRIPTION:
XS GIS Cut Line= 3
      1460855.09      6815891.34      1461112.01      6815651.77
      1461538.54      6814972.11
#Sta/Elev= 30
  4644.2 2123.29  4656.4 2123.27  4823.2 2126.34  4901.4 2128.72  4929.7 2128.68
  4950.7  2118.1  4960.7 2113.99  4972.2  2108.5  4986.1 2106.16  4986.6 2105.66
  5004.8 2106.16  5014.1 2106.82  5029.4 2113.17  5035.4  2114.4  5065.9 2116.77
  5144.9 2117.43  5160.2 2118.67  5217.9 2120.82  5233.2 2122.31  5239.1 2121.84
  5254.4 2123.03  5275.6 2123.07  5290.9 2124.05  5333.4 2123.53  5426.6 2124.38
  5494.8  2125.2  5507.6 2124.48  5616.4 2123.87  5700.8 2124.61  5797.9 2126.96
#Mann= 8 ,-1 , 0
  4644.2     .16       0  4656.4     .07       0  4960.7     .16       0
  4986.1     .07       0  5004.8     .16       0  5426.6     .07       0
  5616.4     .16       0  5700.8     .07       0
Bank Sta=4986.1,5004.8
XS Rating Curve= 0 ,0
Exp/Cntr=0.3,0.1

Type RM Length L Ch R = 1 ,289735  ,500,500,500
BEGIN DESCRIPTION:
Mapping XS 1654d748
END DESCRIPTION:
XS GIS Cut Line= 3
      1460782.18      6816037.19      1461646.73      6815967.75
      1462146.73      6815526.78
#Sta/Elev= 30
  3963.9 2121.05    4047 2121.31  4113.6    2125  4177.4 2127.32  4257.7 2127.31
  4468.3 2125.48  4527.7 2123.85  4558.6 2122.26  4588.7 2118.85  4642.3 2116.33
  4857.9 2112.51  4893.9 2111.13  4943.2 2106.93  4971.7 2106.06  4978.4 2104.47
  4983.2 2097.67  4983.7 2097.17    5002 2097.67  5006.8 2101.95  5022.7 2107.31
  5042.3 2112.64  5049.5 2112.37  5056.2 2113.81  5098.8 2115.71  5205.1 2117.72
  5255.3 2117.21  5311.3 2118.31  5318.9 2117.59  5454.6 2120.15  5497.9 2121.09
#Mann= 7 ,-1 , 0
  3963.9     .16       0  4113.6     .07       0  4527.7     .16       0
  4983.2     .07       0    5002     .16       0  5022.7     .07       0
  5454.6     .05       0
Bank Sta=4983.2,5002
XS Rating Curve= 0 ,0
Exp/Cntr=0.3,0.1

Type RM Length L Ch R = 1 ,289235  ,776,776,776
BEGIN DESCRIPTION:
Mapping XS bd70f3cf
END DESCRIPTION:
XS GIS Cut Line= 3
      1461146.21      6816139.62      1461951.77      6816219.48
      1462524.65      6816004.21
#Sta/Elev= 30
  4186.6 2124.94  4265.8  2124.6  4432.8    2120  4629.5 2114.94  4707.9 2110.69
  4878.8 2108.84  4898.9 2107.38  4927.2 2102.26  4932.2  2102.3  4939.1 2100.62
  4969.2  2097.1  4969.9 2095.05  4970.4 2094.55  4988.7 2095.05  4995.2 2101.87
  5000.5 2101.87  5009.7 2108.77  5015.1 2108.25  5020.9 2109.47  5054.9 2109.08
  5106.4 2109.38    5216 2114.26    5228 2113.93  5331.7 2115.44  5341.4 2114.78
  5385.7 2116.49    5417 2116.64    5491 2119.86  5565.7 2120.23  5608.1 2122.25
#Mann= 7 ,-1 , 0
  4186.6     .07       0  4432.8     .16       0  4969.9     .07       0
  4988.7     .16       0  5054.9     .07       0    5228     .05       0
  5385.7     .07       0
Bank Sta=4969.9,4988.7
XS Rating Curve= 0 ,0
Exp/Cntr=0.3,0.1

Type RM Length L Ch R = 1 ,288459  ,575,575,575
BEGIN DESCRIPTION:
Mapping XS 770ee70b
END DESCRIPTION:
XS GIS Cut Line= 4
      1461104.58      6816240.34       1461510.8      6816650.03
      1461781.63      6816809.75      1462561.45      6816556.75
#Sta/Elev= 30
  4435.9  2123.3    4729 2118.01  4754.1 2116.42  4936.6 2108.96  4950.8 2106.88
  4964.9 2103.17  4976.7 2092.37  4977.2 2091.87  4995.5 2092.37  5012.3 2096.01
  5021.1  2096.3  5029.3 2098.32  5079.7 2101.06  5110.6 2104.87  5203.5 2106.37
  5261.5 2108.87  5311.5 2109.01  5404.4 2108.08    5520 2100.82  5539.7  2100.4
  5562.1 2101.57  5593.6 2101.04  5608.9  2102.4  5656.7 2103.31  5787.3 2109.11
  5877.5 2113.07  5938.4 2114.56  5960.6 2116.11  6056.2 2116.67  6147.1 2119.97
#Mann= 8 ,-1 , 0
  4435.9     .07       0    4729     .16       0  4754.1     .07       0
  4976.7     .07       0  4995.5     .07       0  5311.5     .07       0
  5787.3     .05       0  5938.4     .07       0
#XS Ineff= 2 , 0
       0                  5341.3       0    2110
Permanent Ineff=
       F       F
Bank Sta=4976.7,4995.5
XS Rating Curve= 0 ,0
Exp/Cntr=0.3,0.1

Type RM Length L Ch R = 1 ,287884  ,781,781,781
BEGIN DESCRIPTION:
Mapping XS b43d58bc
END DESCRIPTION:
XS GIS Cut Line= 3
      1460833.73      6816945.17      1461517.75       6817153.5
      1462429.38      6816962.86
#Sta/Elev= 30
  4297.5 2114.14  4507.9 2111.94  4650.2 2108.55  4805.4 2107.81    4832 2105.72
  4936.5 2092.27  4967.9 2091.97  4979.3 2087.74  4979.8 2087.24  4998.2 2087.74
  5014.9 2091.68    5020 2090.92  5030.2 2092.74  5040.4 2102.14  5050.6 2104.17
    5086 2104.71  5183.4 2106.41  5409.6  2104.5  5599.2  2097.9  5612.5  2098.3
  5632.9 2101.26  5649.2 2106.28    5684 2106.81    5694 2110.23  5699.1 2109.13
  5704.4 2111.96  5761.6 2113.02  5893.9 2120.63  5906.7 2120.32  5943.9 2120.06
#Mann= 7 ,-1 , 0
  4297.5     .07       0  4650.2     .16       0  4979.3     .07       0
  4998.2     .16       0    5086     .07       0  5761.6     .05       0
  5906.7     .07       0
#XS Ineff= 2 , 0
       0                  5183.4       0 2106.41
Permanent Ineff=
       F       F
Bank Sta=4979.3,4998.2
XS Rating Curve= 0 ,0
Exp/Cntr=0.3,0.1

Type RM Length L Ch R = 1 ,287103  ,726,726,726
BEGIN DESCRIPTION:
Mapping XS 3c3ed872
END DESCRIPTION:
XS GIS Cut Line= 3
      1460962.19      6817469.48       1461448.3      6817851.42
      1462301.27      6817497.75
#Sta/Elev= 30
  4387.3 2113.18  4505.6 2110.75  4651.8 2106.23  4800.9    2099  4850.6 2098.35
    4899 2092.77  4914.8  2091.6  4959.9 2085.09  4963.2 2083.98  4963.7 2083.48
  4982.1 2083.98  4993.4 2087.55  5000.2 2090.73  5005.5 2090.73  5022.8 2095.37
  5028.3 2095.08    5030  2096.1  5034.4 2098.75  5129.2 2100.22  5211.6 2096.93
  5259.4 2093.06  5272.6 2092.98  5312.6 2095.32  5380.8 2096.09  5466.7  2099.4
  5626.2 2102.83  5678.3 2102.78  5780.3 2105.72  5868.2 2109.77  5928.9 2110.77
#Mann= 8 ,-1 , 0
  4387.3     .07       0  4505.6     .16       0    4899     .07       0
  4959.9     .16       0  4963.2     .07       0  4982.1     .16       0
    5030     .07       0  5678.3     .05       0
#XS Ineff= 2 , 0
       0                  5110.7       0 2100.01
Permanent Ineff=
       F       F
Bank Sta=4963.2,4982.1
XS Rating Curve= 0 ,0
Exp/Cntr=0.3,0.1

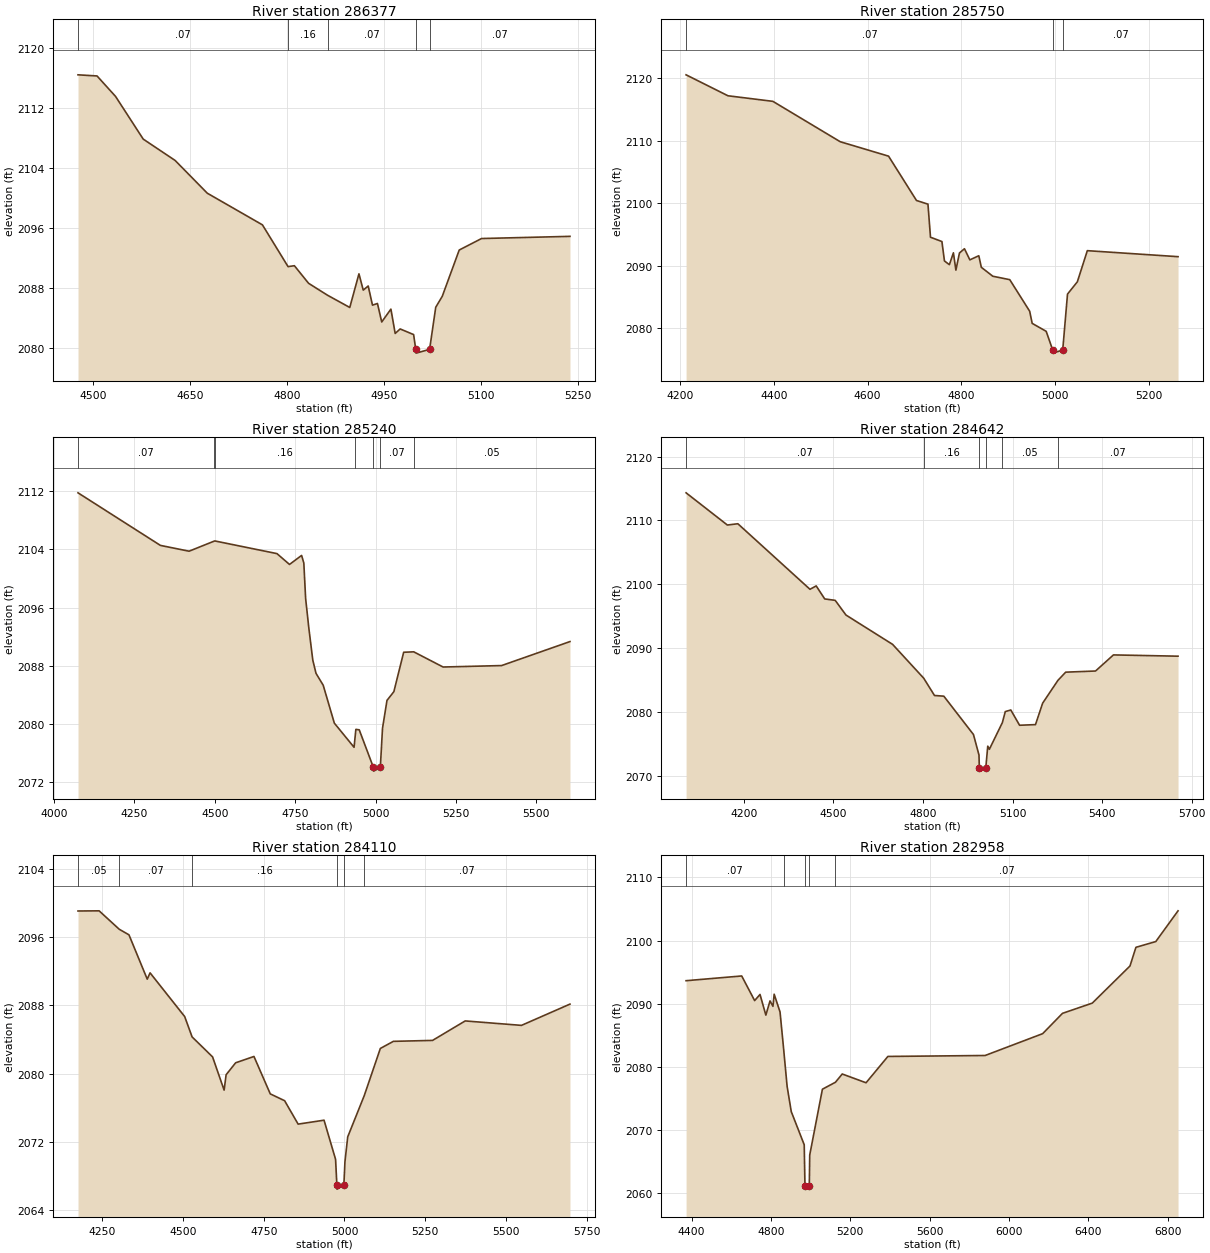
Type RM Length L Ch R = 1 ,286377  ,627,627,627
BEGIN DESCRIPTION:
Mapping XS 41522f7e
END DESCRIPTION:
XS GIS Cut Line= 3
      1460914.36      6818819.46      1461255.41      6818422.83
      1461490.24      6818388.01
#Sta/Elev= 30
  4476.9 2116.42  4506.3 2116.27  4534.9 2113.55  4577.7 2107.86    4627 2105.02
  4676.7 2100.66    4762 2096.44  4801.6 2090.88  4811.4    2091  4833.3 2088.66
  4862.6 2087.07    4897 2085.44  4911.2 2089.92  4917.8 2087.75  4925.5  2088.3
  4932.1 2085.75  4939.8 2085.97  4946.4 2083.51  4960.6 2085.22  4967.2 2081.98
  4974.9 2082.58  4995.7 2081.83    4999 2079.86  4999.5 2079.36  5020.4 2079.86
  5029.9 2085.47    5040 2086.93  5066.2 2093.09  5100.7 2094.62  5237.4 2094.91
#Mann= 5 ,-1 , 0
  4476.9     .07       0  4801.6     .16       0  4862.6     .07       0
    4999     .07       0  5020.4     .07       0
#XS Ineff= 2 , 0
       0                  5238.6       0 2095.31
Permanent Ineff=
       F       F
Bank Sta=4999,5020.4
XS Rating Curve= 0 ,0
Exp/Cntr=0.3,0.1

Type RM Length L Ch R = 1 ,285750  ,510,510,510
BEGIN DESCRIPTION:
Mapping XS c5e1f0d1
END DESCRIPTION:
XS GIS Cut Line= 3
       1460821.8      6819142.17      1461554.34      6818855.32
      1461703.79      6818638.67
#Sta/Elev= 30
  4212.8 2120.53  4302.1 2117.18    4398 2116.29  4541.7 2109.83  4644.9 2107.52
  4704.5 2100.43    4729 2099.84  4734.4 2094.55  4758.8 2093.86  4764.2 2090.75
  4774.7 2090.16  4783.3 2092.06  4788.6 2089.29  4796.2 2092.03  4806.9 2092.71
  4818.4 2090.93  4837.5 2091.59  4842.9 2089.74  4867.4 2088.31  4903.6 2087.76
  4946.1 2082.71  4951.4 2080.77  4981.3  2079.5  4995.2 2076.51  4995.7 2076.01
  5016.6 2076.51  5026.8 2085.45  5047.8 2087.42  5069.1  2092.4  5262.7 2091.44
#Mann= 3 ,-1 , 0
  4212.8     .07       0  4995.2     .07       0  5016.6     .07       0
Bank Sta=4995.2,5016.6
XS Rating Curve= 0 ,0
Exp/Cntr=0.3,0.1

Type RM Length L Ch R = 1 ,285240  ,598,598,598
BEGIN DESCRIPTION:
Mapping XS b2e9a759
END DESCRIPTION:
XS GIS Cut Line= 3
      1460944.07      6819669.79      1461777.43      6819249.64
      1462092.61      6818742.95
#Sta/Elev= 30
  4074.7 2111.79  4330.9 2104.56  4420.1 2103.76  4498.9 2105.16  4501.4 2105.16
  4693.4 2103.43  4732.4 2101.94  4770.1 2103.18    4777 2102.12  4782.6 2097.25
  4792.5 2093.21  4804.9 2088.77  4814.9 2086.96  4837.3 2085.32  4871.9 2080.11
  4933.2 2076.79  4935.5  2077.8  4938.8 2079.25  4949.3 2079.19  4993.5 2074.01
    4994 2073.51  5014.9 2074.01  5021.7 2079.41  5035.6 2083.24    5057 2084.44
  5087.5 2089.86  5118.8 2089.92  5210.1 2087.83  5392.1 2088.03  5604.7 2091.33
#Mann= 7 ,-1 , 0
  4074.7     .07       0  4498.9     .16       0  4501.4     .16       0
  4935.5     .16       0  4993.5     .07       0  5014.9     .07       0
  5118.8     .05       0
Bank Sta=4993.5,5014.9
XS Rating Curve= 0 ,0
Exp/Cntr=0.3,0.1

Type RM Length L Ch R = 1 ,284642  ,532,532,532
BEGIN DESCRIPTION:
Mapping XS 6a5625c7
END DESCRIPTION:
XS GIS Cut Line= 3
      1461596.86      6820204.51      1462152.43      6819732.28
      1462502.14      6818882.36
#Sta/Elev= 30
  4006.3 2114.32  4144.6 2109.28  4179.8 2109.48  4421.4 2099.22  4442.2 2099.75
  4470.8 2097.71  4505.9 2097.49    4542 2095.19  4698.2  2090.6  4802.5  2085.3
  4838.5  2082.6  4869.8 2082.49  4969.1 2076.49  4987.6 2073.28  4988.8 2071.26
  4989.3 2070.76  5010.4 2071.26    5017 2074.67  5022.4 2074.18    5066 2078.36
  5075.7 2080.08  5094.2 2080.33  5123.6 2077.94  5176.9 2078.04  5200.9  2081.4
    5252 2084.96  5278.1 2086.25  5378.1 2086.43  5438.1 2088.95  5654.5 2088.75
#Mann= 6 ,-1 , 0
  4006.3     .07       0  4802.5     .16       0  4988.8     .07       0
  5010.4     .16       0    5066     .05       0    5252     .07       0
Bank Sta=4988.8,5010.4
XS Rating Curve= 0 ,0
Exp/Cntr=0.3,0.1

Type RM Length L Ch R = 1 ,284110  ,1152,1152,1152
BEGIN DESCRIPTION:
Mapping XS f8ae7f6a
END DESCRIPTION:
XS GIS Cut Line= 3
        1462280.        6820263.      1462753.13      6819589.92
      1462851.45      6818896.89
#Sta/Elev= 30
  4175.3 2099.06  4240.6 2099.08    4303 2096.92    4333 2096.27  4389.6 2091.08
  4398.3 2091.82  4505.5  2086.7  4528.4 2084.32  4591.8 2081.98  4627.5 2078.09
  4633.7 2079.89  4663.2 2081.29  4719.9 2082.03  4770.4 2077.65  4814.8 2076.85
  4856.6 2074.11  4936.8 2074.57  4972.5 2069.99  4976.5    2067    4977  2066.5
  4998.2    2067  5001.5  2069.7  5010.1 2072.62  5061.2 2077.44  5111.1 2082.97
  5151.5  2083.8  5272.7 2083.91  5373.7 2086.19  5547.9 2085.67    5698 2088.16
#Mann= 6 ,-1 , 0
  4175.3     .05       0    4303     .07       0  4528.4     .16       0
  4976.5     .07       0  4998.2     .16       0  5061.2     .07       0
Bank Sta=4976.5,4998.2
XS Rating Curve= 0 ,0
Exp/Cntr=0.3,0.1

Type RM Length L Ch R = 1 ,282958  ,583,583,583
BEGIN DESCRIPTION:
Mapping XS 2117d0af
END DESCRIPTION:
XS GIS Cut Line= 3
      1463543.05      6820550.32      1463181.95      6820039.92
      1463136.81      6818185.79
#Sta/Elev= 30
  4372.6 2093.65    4653  2094.4  4718.2  2090.5  4745.3 2091.47  4774.8  2088.2
  4795.7 2090.45  4810.5 2089.59  4816.6 2091.51  4846.2  2088.7  4864.2 2082.88
  4881.9 2076.91  4902.8 2072.91  4968.1 2067.66  4971.9 2061.13  4972.4 2060.63
  4993.7 2061.13  4995.9 2066.04  5059.8 2076.46  5125.4 2077.56  5159.8 2078.87
  5279.8 2077.48  5389.9 2081.65    5880  2081.8  6170.1 2085.26  6270.1 2088.48
  6420.2  2090.1  6610.2 2095.98  6640.2 2098.94  6740.3 2099.85  6852.5 2104.72
#Mann= 5 ,-1 , 0
  4372.6     .07       0  4864.2     .16       0  4971.9     .07       0
  4993.7     .16       0  5125.4     .07       0
Bank Sta=4971.9,4993.7
XS Rating Curve= 0 ,0
Exp/Cntr=0.3,0.1

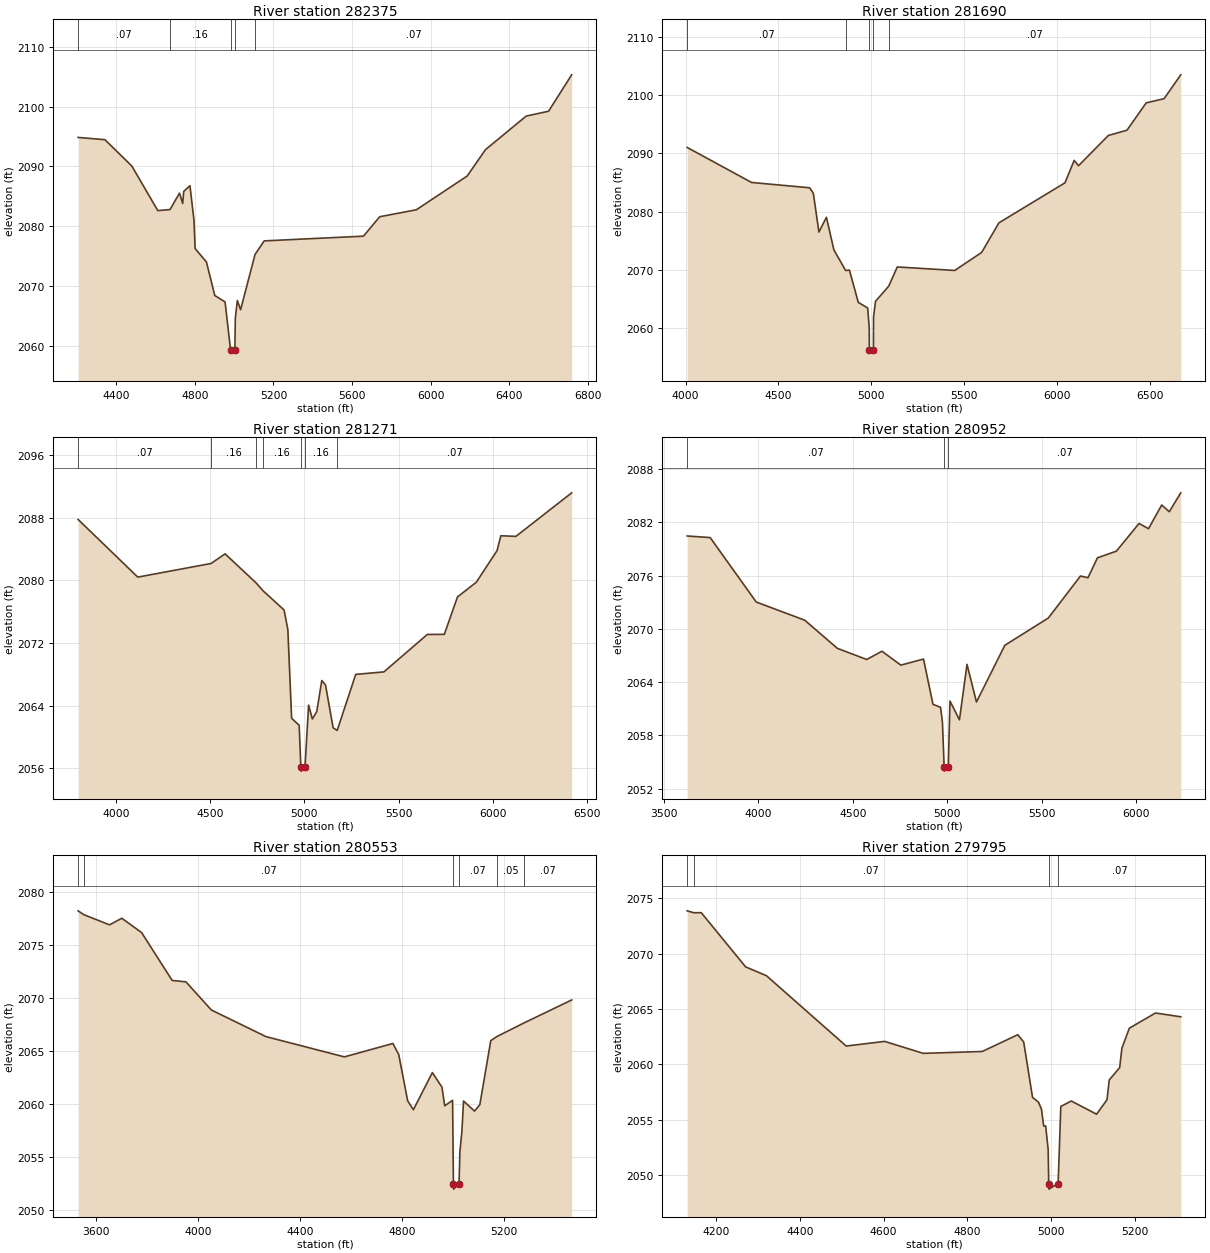
Type RM Length L Ch R = 1 ,282375  ,685,685,685
BEGIN DESCRIPTION:
Mapping XS b7bf269c
END DESCRIPTION:
XS GIS Cut Line= 3
      1463928.47      6820567.68      1463685.42      6819838.53
      1463234.02      6818154.47
#Sta/Elev= 30
  4205.8 2094.84  4342.5 2094.46  4479.5 2090.05  4611.7  2082.6  4673.7 2082.78
    4722 2085.53  4738.2 2083.79  4743.4  2085.8  4775.1 2086.77  4795.8 2080.95
  4801.4 2076.26    4859 2074.01  4901.5 2068.41  4953.9 2067.33    4982 2059.27
  4982.5 2058.77  5003.8 2059.27    5006 2064.61  5016.3 2067.56  5032.9 2066.03
  5106.4 2075.27    5153 2077.54  5658.2 2078.33  5741.1 2081.58  5927.4 2082.74
  6186.2 2088.39  6279.4  2092.8  6486.5 2098.41  6600.4 2099.22  6717.9 2105.31
#Mann= 5 ,-1 , 0
  4205.8     .07       0  4673.7     .16       0    4982     .07       0
  5003.8     .16       0  5106.4     .07       0
Bank Sta=4982,5003.8
XS Rating Curve= 0 ,0
Exp/Cntr=0.3,0.1

Type RM Length L Ch R = 1 ,281690  ,419,419,419
BEGIN DESCRIPTION:
Mapping XS 60c3841a
END DESCRIPTION:
XS GIS Cut Line= 3
      1464144.63      6820520.77      1464274.83      6819546.86
      1463675.88       6817984.4
#Sta/Elev= 30
  4008.9 2091.02  4355.5    2085  4667.5 2084.09  4687.7 2083.17  4717.9 2076.48
  4758.3 2079.02  4798.6 2073.39  4861.7 2069.87    4882 2069.94  4929.8 2064.39
  4980.2 2063.43  4988.4 2060.08  4989.4 2056.17  4989.9 2055.67  5011.2 2056.17
  5011.7 2061.87  5022.4 2064.57  5093.3 2067.18  5139.7 2070.48  5448.7 2069.88
  5593.5 2072.97  5686.4 2078.06  6041.9 2084.94  6091.3 2088.79  6114.8 2087.88
  6275.4 2093.08  6375.5 2093.98  6478.9 2098.68  6575.3  2099.4  6664.8  2103.5
#Mann= 5 ,-1 , 0
  4008.9     .07       0  4861.7     .16       0  4989.4     .07       0
  5011.2     .16       0  5093.3     .07       0
Bank Sta=4989.4,5011.2
XS Rating Curve= 0 ,0
Exp/Cntr=0.3,0.1

Type RM Length L Ch R = 1 ,281271  ,319,319,319
BEGIN DESCRIPTION:
Mapping XS e0e18d05
END DESCRIPTION:
XS GIS Cut Line= 3
      1464285.26      6820484.32      1464623.79      6819526.03
      1464535.27       6817922.4
#Sta/Elev= 30
  3797.5 2087.76  4114.5  2080.4  4504.1 2082.14  4578.4 2083.37  4743.8 2079.65
  4778.6 2078.69    4892  2076.2    4912  2073.7    4932 2062.38  4972.1 2061.48
  4981.2 2056.13  4981.7 2055.63    5003 2056.13  5022.2 2064.06  5042.2 2062.29
  5065.6 2063.23  5092.3  2067.2  5112.3 2066.61  5152.4 2061.17  5174.1 2060.82
  5272.6 2067.98  5422.3  2068.3  5653.1 2073.08  5743.3 2073.09  5813.4 2077.87
  5913.5 2079.75  6023.7 2083.79  6043.7 2085.68  6123.8  2085.6  6419.9 2091.16
#Mann= 7 ,-1 , 0
  3797.5     .07       0  4504.1     .16       0  4743.8     .07       0
  4778.6     .16       0  4981.2     .07       0    5003     .16       0
  5174.1     .07       0
Bank Sta=4981.2,5003
XS Rating Curve= 0 ,0
Exp/Cntr=0.3,0.1

Type RM Length L Ch R = 1 ,280952  ,399,399,399
BEGIN DESCRIPTION:
Mapping XS 76db4d79
END DESCRIPTION:
XS GIS Cut Line= 3
      1464493.56      6820473.99      1464873.79      6819536.44
      1464858.16      6817937.53
#Sta/Elev= 30
    3624 2080.45  3745.7 2080.27  3989.5 2073.01  4245.6 2070.97  4418.2  2067.8
  4573.6 2066.54  4654.2 2067.47  4754.2 2065.91  4874.2 2066.59  4924.2 2061.49
  4964.2 2061.16  4974.2  2059.5  4983.2 2054.47  4983.7 2053.97  5005.2 2054.47
  5014.2 2061.86  5064.2 2059.75  5104.2 2065.99  5154.2 2061.75  5304.2 2068.14
  5534.2 2071.21  5704.2 2075.94  5744.2 2075.75  5794.2 2077.99  5894.2 2078.74
  6014.2 2081.86  6064.2 2081.27  6134.2 2083.94  6174.2 2083.18  6234.7 2085.31
#Mann= 3 ,-1 , 0
    3624     .07       0  4983.2     .07       0  5005.2     .07       0
Bank Sta=4983.2,5005.2
XS Rating Curve= 0 ,0
Exp/Cntr=0.3,0.1

Type RM Length L Ch R = 1 ,280553  ,758,758,758
BEGIN DESCRIPTION:
Mapping XS 69251240
END DESCRIPTION:
XS GIS Cut Line= 4
      1464564.76      6820539.91       1464946.7      6819598.08
      1465155.04      6819229.15      1465471.18      6818847.37
#Sta/Elev= 30
  3530.8 2078.21  3552.2 2077.86  3654.1 2076.89  3702.3 2077.51  3779.9 2076.16
  3899.8 2071.65  3953.7 2071.52  4053.3 2068.87  4267.6 2066.36  4575.1 2064.45
  4765.4 2065.71  4788.4 2064.66  4823.4 2060.31  4845.8 2059.47  4920.2 2062.97
  4957.7  2061.6  4968.6 2059.84  4999.5 2060.36  5002.8 2052.49  5003.3 2051.99
  5024.9 2052.49  5028.2 2055.53    5036 2057.41  5042.5 2060.29  5085.5 2059.34
  5106.3 2059.94  5149.3 2065.98    5173 2066.36  5279.8 2067.65  5466.5 2069.81
#Mann= 6 ,-1 , 0
  3530.8     .16       0  3552.2     .07       0  5002.8     .07       0
  5024.9     .07       0    5173     .05       0  5279.8     .07       0
Bank Sta=5002.8,5024.9
XS Rating Curve= 0 ,0
Exp/Cntr=0.3,0.1

Type RM Length L Ch R = 1 ,279795  ,939,939,939
BEGIN DESCRIPTION:
Mapping XS d6d42d21
END DESCRIPTION:
XS GIS Cut Line= 3
      1464715.05      6820425.81      1465316.69      6819815.35
        1465430.      6819512.99
#Sta/Elev= 30
  4130.4 2073.86    4146 2073.69  4164.2 2073.69  4270.2  2068.8  4319.8 2068.01
  4510.6 2061.66  4602.6 2062.08  4694.5    2061  4835.9 2061.17  4920.8 2062.68
  4934.9 2062.03  4956.1 2057.03  4970.2  2056.6  4977.4 2055.97  4982.7 2054.45
  4987.5 2054.45  4993.5  2052.3  4994.8 2049.25  4995.3 2048.75  5017.3 2049.25
  5023.7 2056.21  5048.7  2056.7  5109.2 2055.51  5134.1 2056.81  5139.5  2058.6
  5164.4 2059.71  5169.7 2061.46  5187.6 2063.27  5249.9 2064.64  5310.4  2064.3
#Mann= 4 ,-1 , 0
  4130.4     .16       0    4146     .07       0  4994.8     .07       0
  5017.3     .07       0
Bank Sta=4994.8,5017.3
XS Rating Curve= 0 ,0
Exp/Cntr=0.3,0.1

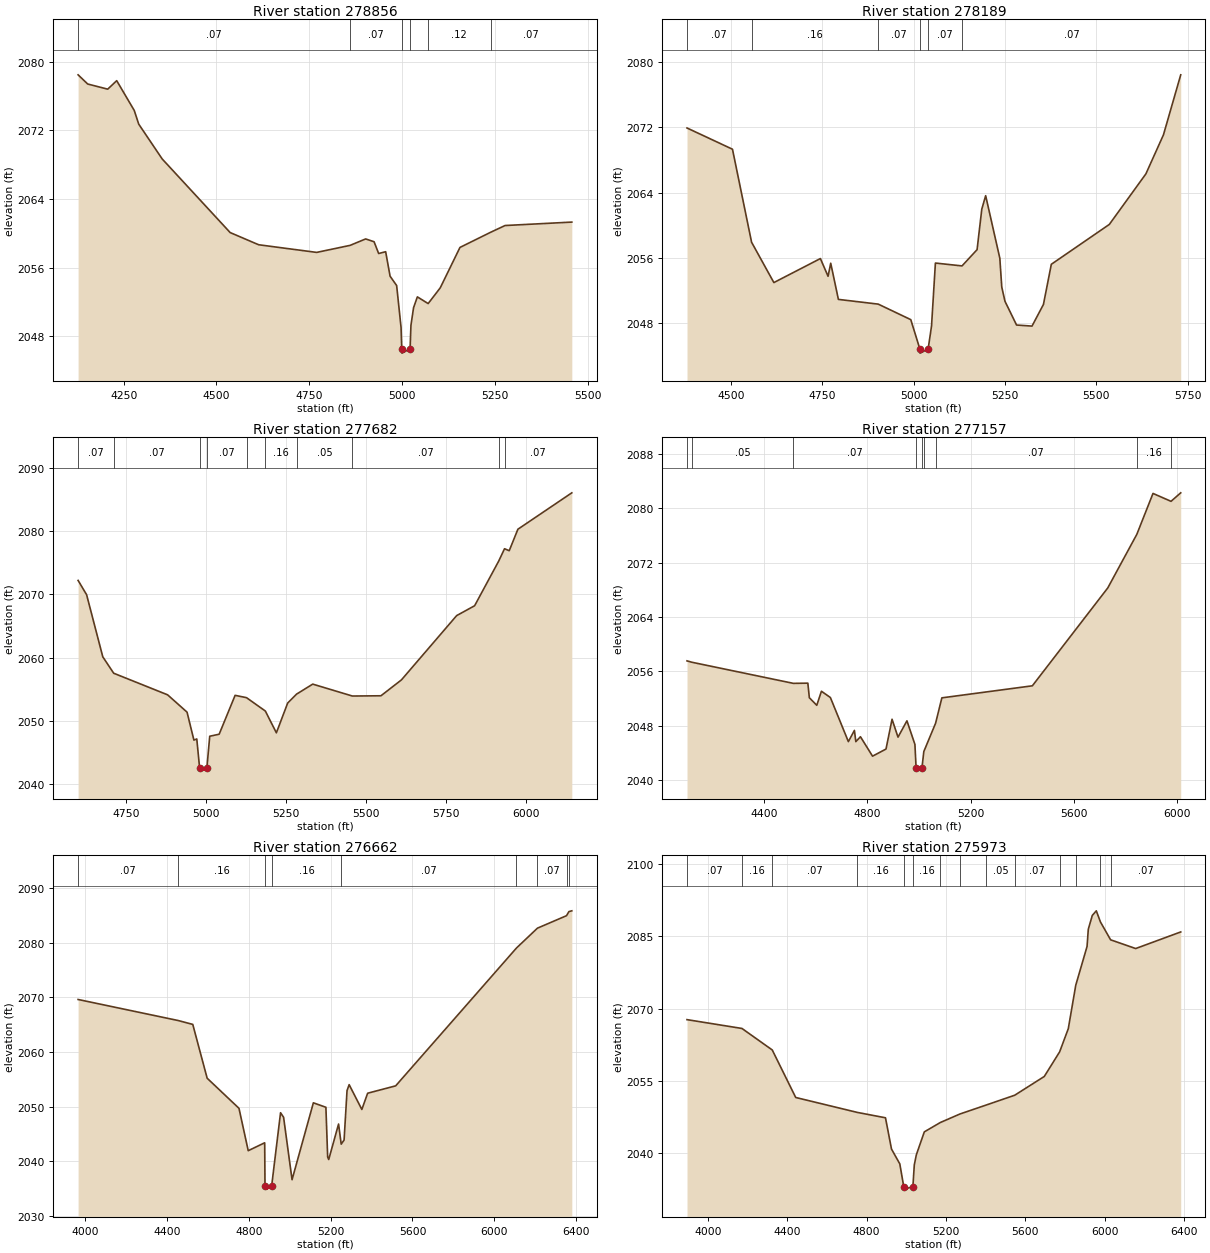
Type RM Length L Ch R = 1 ,278856  ,667,667,667
BEGIN DESCRIPTION:
Mapping XS bd85dc9f
END DESCRIPTION:
XS GIS Cut Line= 3
      1464764.54      6820832.05      1465574.92      6820508.18
        1465680.      6820063.02
#Sta/Elev= 30
  4127.3 2078.47  4153.2  2077.4  4207.1  2076.8  4231.3 2077.79  4278.6 2074.32
  4290.6 2072.73  4353.9 2068.67    4537  2060.1  4613.8 2058.68    4770 2057.79
  4860.2 2058.61    4902 2059.36  4924.7 2059.03    4937 2057.66  4955.9 2057.87
  4967.8 2055.02  4985.5 2053.93  4997.4 2049.04  4999.2 2046.56  4999.7 2046.06
  5021.7 2046.56    5024 2049.29    5031 2051.34  5041.3 2052.61  5070.4 2051.83
  5102.9 2053.66  5156.1 2058.37  5238.5 2060.13  5277.6 2060.92  5457.4 2061.32
#Mann= 6 ,-1 , 0
  4127.3     .07       0  4860.2     .07       0  4999.2     .07       0
  5021.7     .07       0  5070.4     .12       0  5238.5     .07       0
Bank Sta=4999.2,5021.7
XS Rating Curve= 0 ,0
Exp/Cntr=0.3,0.1

Type RM Length L Ch R = 1 ,278189  ,507,507,507
BEGIN DESCRIPTION:
Mapping XS 6edd0f59
END DESCRIPTION:
XS GIS Cut Line= 3
      1465704.68      6821063.78      1466131.74       6820615.9
      1466371.31      6819923.21
#Sta/Elev= 30
  4379.1 2071.94  4503.6 2069.34  4555.9 2057.95  4616.9 2053.01  4744.3 2055.95
  4765.3 2053.78  4772.6 2055.38  4793.6 2050.95  4902.7 2050.37  4991.8 2048.47
  5016.7 2044.87  5017.2 2044.37  5039.3 2044.87  5048.6 2047.69  5059.2  2055.4
  5132.1 2055.05  5173.3 2057.04  5186.2    2062  5196.8 2063.65  5235.6 2055.99
  5240.9 2052.46  5249.7 2050.72  5281.4 2047.81  5323.7 2047.68    5355 2050.33
  5376.6 2055.25  5535.4 2060.13  5635.5 2066.32  5683.5 2071.09  5730.9 2078.45
#Mann= 6 ,-1 , 0
  4379.1     .07       0  4555.9     .16       0  4902.7     .07       0
  5016.7     .07       0  5039.3     .07       0  5132.1     .07       0
#XS Ineff= 2 , 0
       0                  5196.8       0 2063.65
Permanent Ineff=
       F       F
Bank Sta=5016.7,5039.3
XS Rating Curve= 0 ,0
Exp/Cntr=0.3,0.1

Type RM Length L Ch R = 1 ,277682  ,525,525,525
BEGIN DESCRIPTION:
Mapping XS 942795eb
END DESCRIPTION:
XS GIS Cut Line= 3
      1465938.78      6821080.93      1466362.39      6821011.49
      1467250.67      6820338.34
#Sta/Elev= 30
  4600.9  2072.2  4627.5 2069.94  4678.1 2060.13  4712.2 2057.54  4880.8 2054.13
  4941.6 2051.39    4963 2046.98    4972 2047.16  4980.9 2042.58  4981.4 2042.08
  5003.6 2042.58  5012.5 2047.59    5042 2047.91  5091.9 2054.05  5127.5 2053.68
  5186.4 2051.57  5220.9 2048.13  5256.2 2052.83    5284 2054.24  5334.6 2055.82
  5458.5 2053.94  5547.9 2053.98    5612 2056.49  5784.6 2066.64  5840.8  2068.2
  5916.1 2075.25  5934.3  2077.2    5949 2076.89  5976.1 2080.28  6144.7 2086.03
#Mann= 10 ,-1 , 0
  4600.9     .07       0  4712.2     .07       0  4980.9     .07       0
  5003.6     .07       0  5127.5     .07       0  5186.4     .16       0
    5284     .05       0  5458.5     .07       0  5916.1     .16       0
  5934.3     .07       0
Bank Sta=4980.9,5003.6
XS Rating Curve= 0 ,0
Exp/Cntr=0.3,0.1

Type RM Length L Ch R = 1 ,277157  ,495,495,495
BEGIN DESCRIPTION:
Mapping XS 8dcffd0c
END DESCRIPTION:
XS GIS Cut Line= 3
      1465866.15      6821733.07      1466699.44       6821368.5
      1467212.44      6820506.56
#Sta/Elev= 30
    4101 2057.53  4119.5 2057.33  4513.1 2054.22  4569.1 2054.25  4574.9 2052.11
  4603.7 2050.99  4621.7 2053.06  4656.4 2052.14  4726.1 2045.65  4749.5  2047.3
    4755 2045.65  4772.9 2046.37  4819.7 2043.51  4871.9 2044.56  4895.3 2048.94
  4918.4 2046.31    4953 2048.71  4983.9 2045.24  4988.4 2041.81  4988.9 2041.31
  5011.2 2041.81  5018.4 2044.19    5064 2048.36  5088.3 2052.09  5438.8 2053.86
    5731 2068.26  5843.5 2076.14  5906.2 2082.16    5976    2081  6013.6 2082.25
#Mann= 9 ,-1 , 0
    4101     .07       0  4119.5     .05       0  4513.1     .07       0
  4988.4     .07       0  5011.2     .07       0  5018.4     .16       0
    5064     .07       0  5843.5     .16       0    5976     .07       0
Bank Sta=4988.4,5011.2
XS Rating Curve= 0 ,0
Exp/Cntr=0.3,0.1

Type RM Length L Ch R = 1 ,276662  ,689,689,689
BEGIN DESCRIPTION:
MULBERRY CREEK 86.0
END DESCRIPTION:
XS GIS Cut Line= 3
      1466808.58      6822766.07       1466905.1       6821837.9
      1467285.99      6820405.04
#Sta/Elev= 30
    3964 2069.63  4453.7 2065.77  4525.1 2065.06  4595.5 2055.19  4751.2 2049.67
  4796.5  2041.9    4877 2043.35  4878.5 2035.35    4879 2034.85  4910.8 2035.35
  4954.6 2048.86  4969.5 2048.03  5010.9 2036.58  5115.2 2050.68  5176.5 2049.86
  5185.2 2040.73  5190.3 2040.28  5238.5 2046.79  5251.4  2043.1  5265.5 2043.85
  5279.9 2052.92  5290.3 2054.01  5352.4 2049.46  5380.8 2052.44  5517.9 2053.79
    6109 2079.07  6211.6 2082.71  6353.9    2085  6365.7 2085.75  6379.8 2085.89
#Mann= 9 ,-1 , 0
    3964     .07       0  4453.7     .16       0  4878.5     .07       0
  4910.8     .16       0  5251.4     .07       0    6109     .16       0
  6211.6     .07       0  6353.9     .05       0  6365.7     .07       0
#XS Ineff= 2 , 0
       0                    4980       0    2045
Permanent Ineff=
       F       T
Bank Sta=4878.5,4910.8
XS Rating Curve= 0 ,0
Exp/Cntr=0.3,0.1

Type RM Length L Ch R = 1 ,275973  ,443,443,443
BEGIN DESCRIPTION:
MULBERRY CREEK 85.0
END DESCRIPTION:
XS GIS Cut Line= 3
      1466908.41       6822744.4      1467539.94      6821838.14
      1467372.81      6820465.78
#Sta/Elev= 30
  3895.4 2067.75  4172.3 2065.92  4324.8 2061.46    4443 2051.61  4752.8 2048.52
  4895.2  2047.4  4925.5 2040.92  4967.4 2037.84  4987.2 2033.11  4988.2 2032.61
  5033.2 2033.11  5040.4 2037.64  5050.5 2039.71  5090.8 2044.48  5171.5 2046.42
  5270.5 2048.19  5403.6 2050.06  5546.3 2052.08  5695.2 2055.97  5772.5 2061.07
  5816.1 2065.87  5853.8  2074.9  5910.6 2082.92  5916.9  2086.5    5937 2089.35
  5957.2 2090.31    5978 2088.01  6029.3  2084.3  6155.6 2082.49  6382.5 2085.93
#Mann= 14 ,-1 , 0
  3895.4     .07       0  4172.3     .16       0  4324.8     .07       0
  4752.8     .16       0  4987.2     .07       0  5033.2     .16       0
  5171.5     .05       0  5270.5     .07       0  5403.6     .05       0
  5546.3     .07       0  5772.5     .05       0  5853.8     .07       0
    5978     .05       0  6029.3     .07       0
Bank Sta=4987.2,5033.2
XS Rating Curve= 0 ,0
Exp/Cntr=0.3,0.1

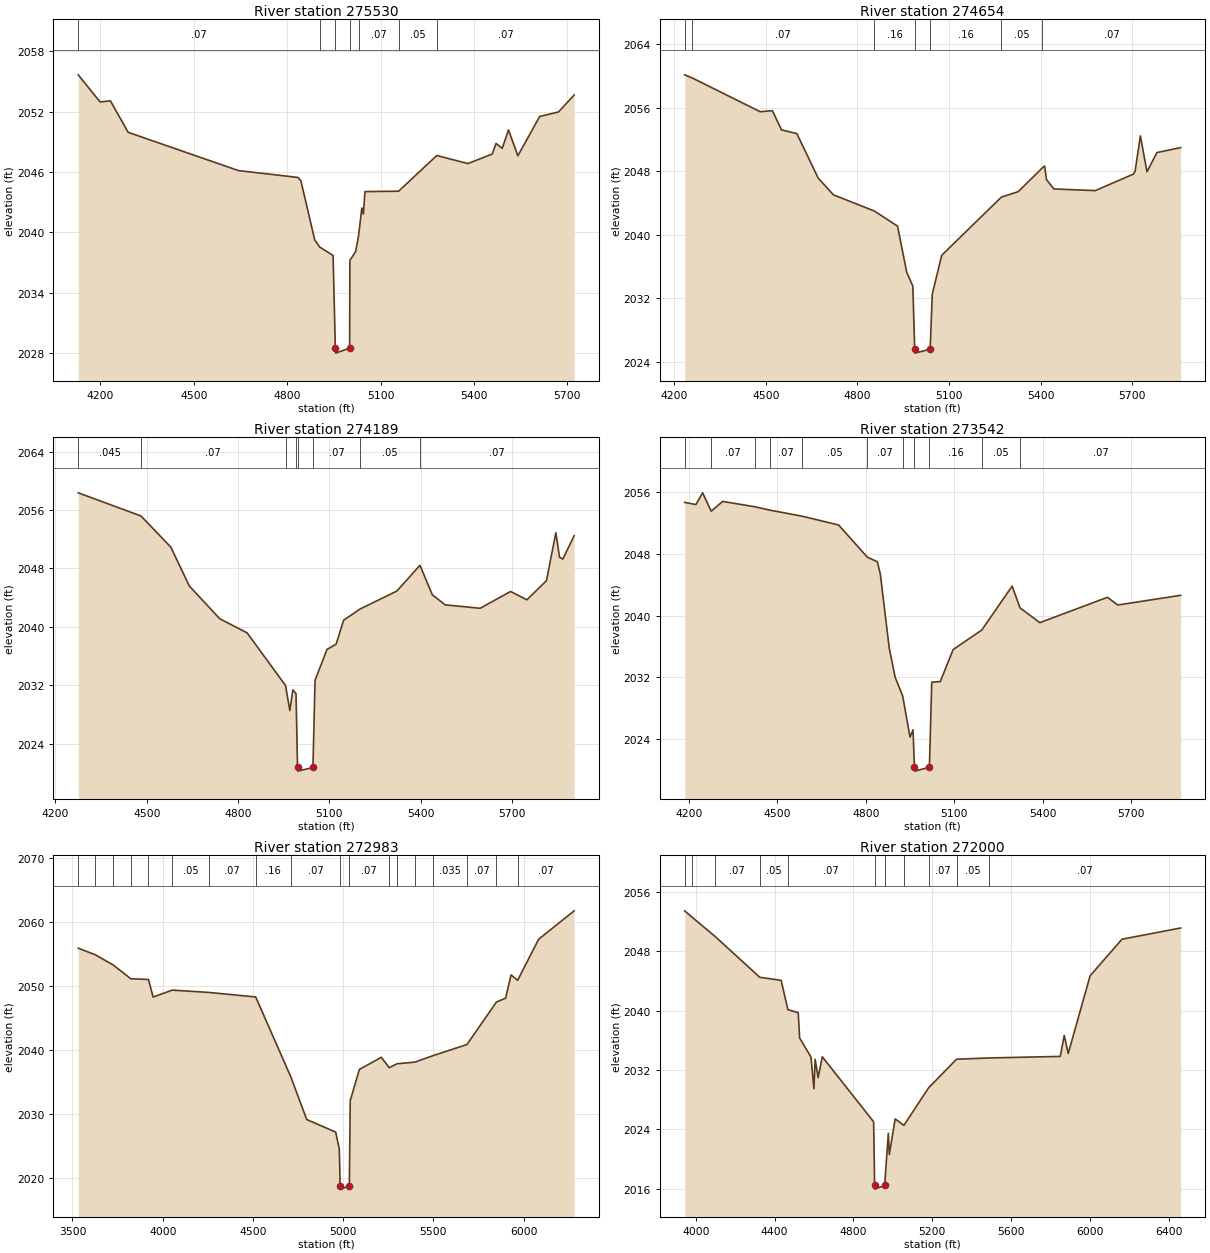
Type RM Length L Ch R = 1 ,275530  ,876,876,876
BEGIN DESCRIPTION:
Mapping XS b1f48c0c
END DESCRIPTION:
XS GIS Cut Line= 3
      1467601.41        6822621.      1467983.36      6821839.74
      1467931.27      6821117.54
#Sta/Elev= 30
  4128.5 2055.66  4198.9 2052.96    4232 2053.07    4289 2049.94  4643.6 2046.13
  4834.9 2045.45  4844.2  2045.1  4888.7 2039.21  4904.8 2038.52  4947.5 2037.69
  4954.8 2028.47  4955.8 2027.97  5000.8 2028.47  5001.5 2037.19  5019.9 2038.07
  5029.5 2039.65  5039.9 2042.41  5044.9 2041.81    5050 2044.04    5158 2044.08
  5280.7 2047.63  5380.9 2046.83    5459 2047.78  5471.1 2048.83  5491.1 2048.34
  5511.2 2050.18  5541.3  2047.6  5611.5 2051.52  5671.6 2051.96  5722.2 2053.65
#Mann= 7 ,-1 , 0
  4128.5     .07       0  4904.8     .16       0  4954.8     .07       0
  5000.8     .16       0  5029.5     .07       0    5158     .05       0
  5280.7     .07       0
Bank Sta=4954.8,5000.8
XS Rating Curve= 0 ,0
Exp/Cntr=0.3,0.1

Type RM Length L Ch R = 1 ,274654  ,465,465,465
BEGIN DESCRIPTION:
Mapping XS 868f5ed7
END DESCRIPTION:
XS GIS Cut Line= 3
      1468726.41      6822645.25      1468712.52      6821884.88
      1468382.64      6821086.22
#Sta/Elev= 30
  4234.4 2060.13    4258 2059.76  4481.7 2055.49  4521.7 2055.62  4551.7  2053.2
  4601.7 2052.74  4671.7 2047.14  4721.7 2045.03  4855.7 2042.99  4931.8 2041.09
  4961.8 2035.28  4981.8 2033.54  4987.9 2025.61  4988.9 2025.11  5038.5 2025.61
  5045.6 2032.56  5076.4 2037.42  5271.8 2044.74  5326.9 2045.43  5405.9 2048.41
  5413.5 2048.65  5419.8 2046.94  5443.7 2045.77  5579.5 2045.56  5704.5 2047.64
  5709.9    2048  5727.2 2052.44  5748.9 2047.93  5781.3 2050.35    5859 2050.97
#Mann= 7 ,-1 , 0
  4234.4    .045       0    4258     .07       0  4855.7     .16       0
  4987.9     .07       0  5038.5     .16       0  5271.8     .05       0
  5405.9     .07       0
Bank Sta=4987.9,5038.5
XS Rating Curve= 0 ,0
Exp/Cntr=0.3,0.1

Type RM Length L Ch R = 1 ,274189  ,647,647,647
BEGIN DESCRIPTION:
Mapping XS 0ad67336
END DESCRIPTION:
XS GIS Cut Line= 3
      1469084.05        6822562.      1469129.19      6821825.85
      1468809.96      6820993.07
#Sta/Elev= 30
    4275 2058.35  4481.3 2055.18  4579.6  2050.9  4639.7 2045.61  4739.9 2041.11
    4830 2039.17  4956.1 2031.97  4970.3 2028.53  4980.3 2031.37  4990.6 2030.85
  4995.6 2020.74  4996.6 2020.24  5046.2 2020.74  5053.1 2032.68  5092.3  2036.9
  5122.4 2037.63    5147 2040.91  5201.6 2042.45  5321.9  2044.9  5397.8 2048.42
  5438.6 2044.38  5480.7 2043.01  5595.4 2042.54  5695.6 2044.84  5749.2  2043.7
  5813.4 2046.32  5844.3 2052.89  5856.3 2049.54    5867 2049.27  5904.4 2052.47
#Mann= 8 ,-1 , 0
    4275    .045       0  4481.3     .07       0  4956.1     .16       0
  4990.6     .07       0  4995.6     .07       0  5046.2     .07       0
  5201.6     .05       0  5397.8     .07       0
Bank Sta=4995.6,5046.2
XS Rating Curve= 0 ,0
Exp/Cntr=0.3,0.1

Type RM Length L Ch R = 1 ,273542  ,559,559,559
BEGIN DESCRIPTION:
Mapping XS 7d8516e1
END DESCRIPTION:
XS GIS Cut Line= 3
      1469747.25      6822405.74      1469646.55      6821600.16
      1469223.86       6820841.4
#Sta/Elev= 30
  4186.3 2054.66  4224.3 2054.38  4247.1  2055.9  4276.3 2053.52    4315 2054.79
  4423.4  2054.1  4474.4 2053.66  4584.8 2052.87  4708.1 2051.73  4805.3 2047.56
  4839.1 2046.98  4849.2 2045.38  4879.4 2035.79  4899.5 2032.01  4924.8 2029.62
  4949.9 2024.26    4960 2025.21  4964.9 2020.36  4965.9 2019.86  5015.5 2020.36
  5023.5 2031.38  5052.4 2031.46  5095.9  2035.6    5193 2038.13  5295.9 2043.82
  5322.6    2041  5389.8 2039.09  5618.8 2042.37  5653.7 2041.37  5866.7 2042.63
#Mann= 11 ,-1 , 0
  4186.3     .05       0  4276.3     .07       0  4423.4     .05       0
  4474.4     .07       0  4584.8     .05       0  4805.3     .07       0
  4924.8     .16       0  4964.9     .07       0  5015.5     .16       0
    5193     .05       0  5322.6     .07       0
Bank Sta=4964.9,5015.5
XS Rating Curve= 0 ,0
Exp/Cntr=0.3,0.1

Type RM Length L Ch R = 1 ,272983  ,983,983,983
BEGIN DESCRIPTION:
Mapping XS 086bc2d0
END DESCRIPTION:
XS GIS Cut Line= 3
      1469952.67      6822711.52      1470049.89      6821253.18
      1469848.56      6819982.71
#Sta/Elev= 30
  3531.9 2055.89  3627.3 2054.85  3725.3 2053.28  3823.3 2051.12  3921.2 2051.01
  3947.1 2048.27  4052.9 2049.35  4254.1 2048.99  4515.3 2048.28  4708.6 2035.91
  4798.2 2029.17  4958.6 2027.21  4978.6 2024.56  4983.4 2018.82  4984.4 2018.32
  5034.2 2018.82  5039.2 2032.13  5089.8 2036.98  5211.3 2038.87  5255.1 2037.25
  5297.8 2037.86  5397.3 2038.12  5496.9 2039.12    5686 2040.87  5849.5  2047.5
  5899.8 2048.08  5930.2 2051.72  5966.7 2050.88    6083 2057.28  6279.8 2061.71
#Mann= 18 ,-1 , 0
  3531.9     .07       0  3627.3    .045       0  3725.3     .07       0
  3823.3     .05       0  3921.2     .07       0  4052.9     .05       0
  4254.1     .07       0  4515.3     .16       0  4708.6     .07       0
  4983.4    .035       0  5034.2     .07       0  5255.1     .07       0
  5297.8     .05       0  5397.3     .07       0  5496.9    .035       0
    5686     .07       0  5849.5    .035       0  5966.7     .07       0
Bank Sta=4983.4,5034.2
XS Rating Curve= 0 ,0
Exp/Cntr=0.3,0.1

Type RM Length L Ch R = 1 ,272000  ,567,567,567
BEGIN DESCRIPTION:
Mapping XS c95302dc
END DESCRIPTION:
XS GIS Cut Line= 3
      1470174.87      6822753.22      1470730.45      6821885.13
      1470529.07      6820412.99
#Sta/Elev= 30
  3943.9 2053.42  3982.5 2052.54  4096.7 2050.01  4325.2 2044.47  4433.3 2044.07
  4467.7 2040.12    4520 2039.72  4527.2 2036.31  4584.7 2033.75  4599.9 2029.47
  4605.9 2033.44  4621.1 2030.98  4642.2 2033.78  4902.7 2025.03  4907.7 2016.47
  4908.7 2015.97  4958.6 2016.47  4977.3 2023.48  4982.3 2020.63    5012 2025.42
  5056.3 2024.55  5181.6  2029.6  5323.3 2033.45  5487.7 2033.62  5849.8 2033.83
  5869.9 2036.66  5890.1 2034.22  6001.2 2044.68    6163  2049.6  6460.4 2051.11
#Mann= 11 ,-1 , 0
  3943.9     .07       0  3982.5    .045       0  4096.7     .07       0
  4325.2     .05       0  4467.7     .07       0  4907.7     .07       0
  4958.6     .07       0  5056.3     .16       0  5181.6     .07       0
  5323.3     .05       0  5487.7     .07       0
Bank Sta=4907.7,4958.6
XS Rating Curve= 0 ,0
Exp/Cntr=0.3,0.1