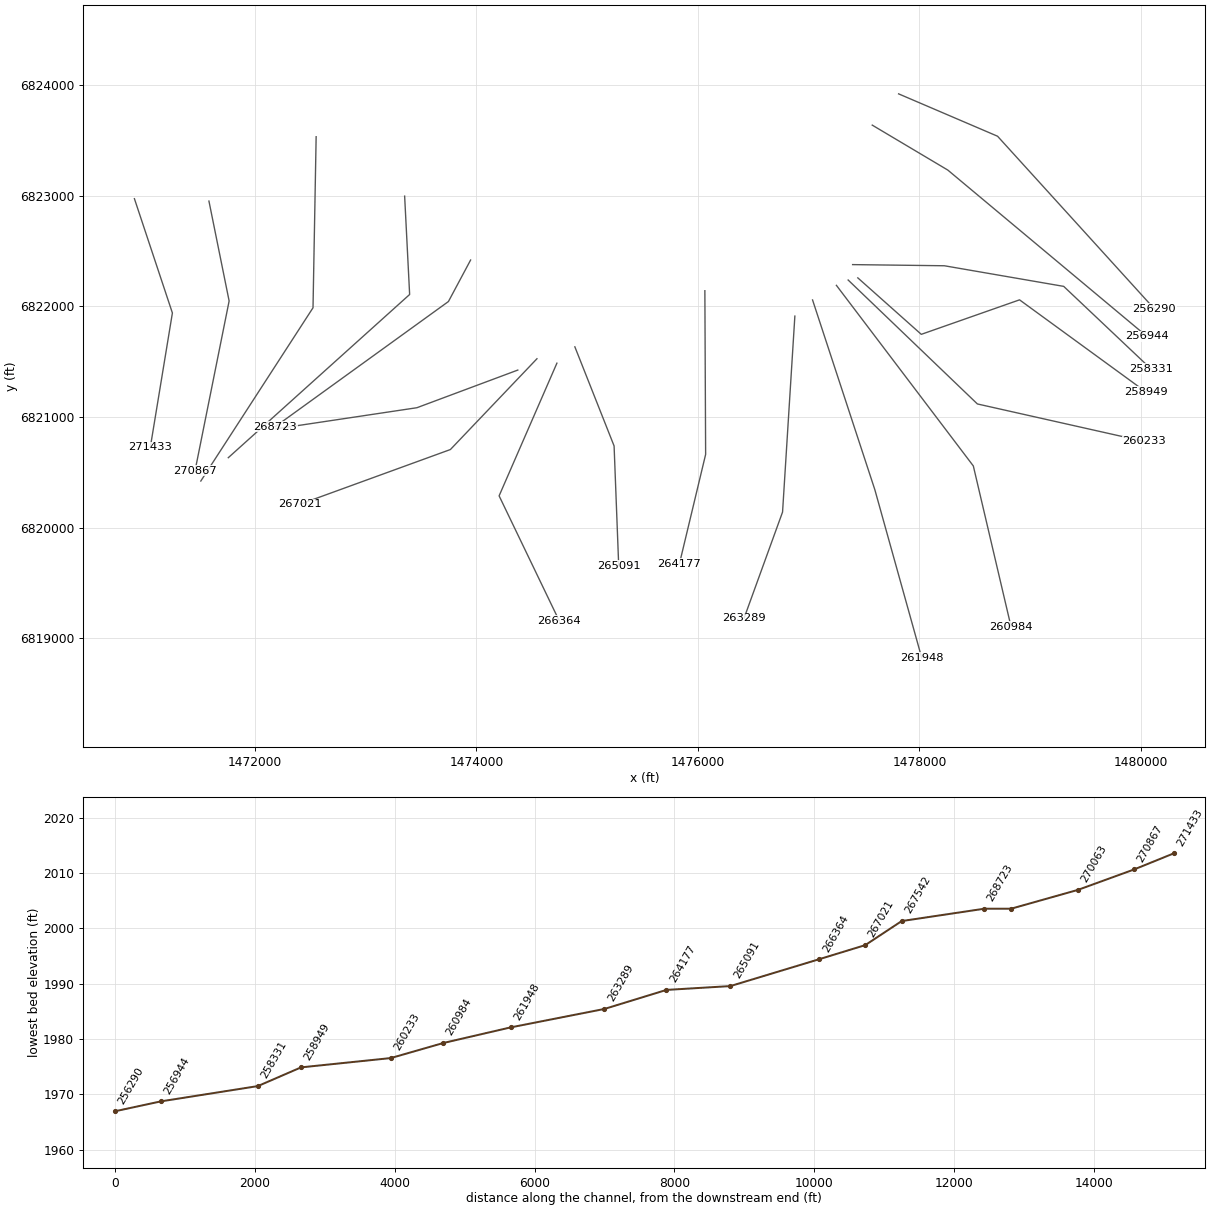
HEC-RAS study MULBERRY CREEK.prj: MULBERRY CREEK Base Level Engineering

--- MULBERRY CREEK.g01 (geometry) --- (continued)

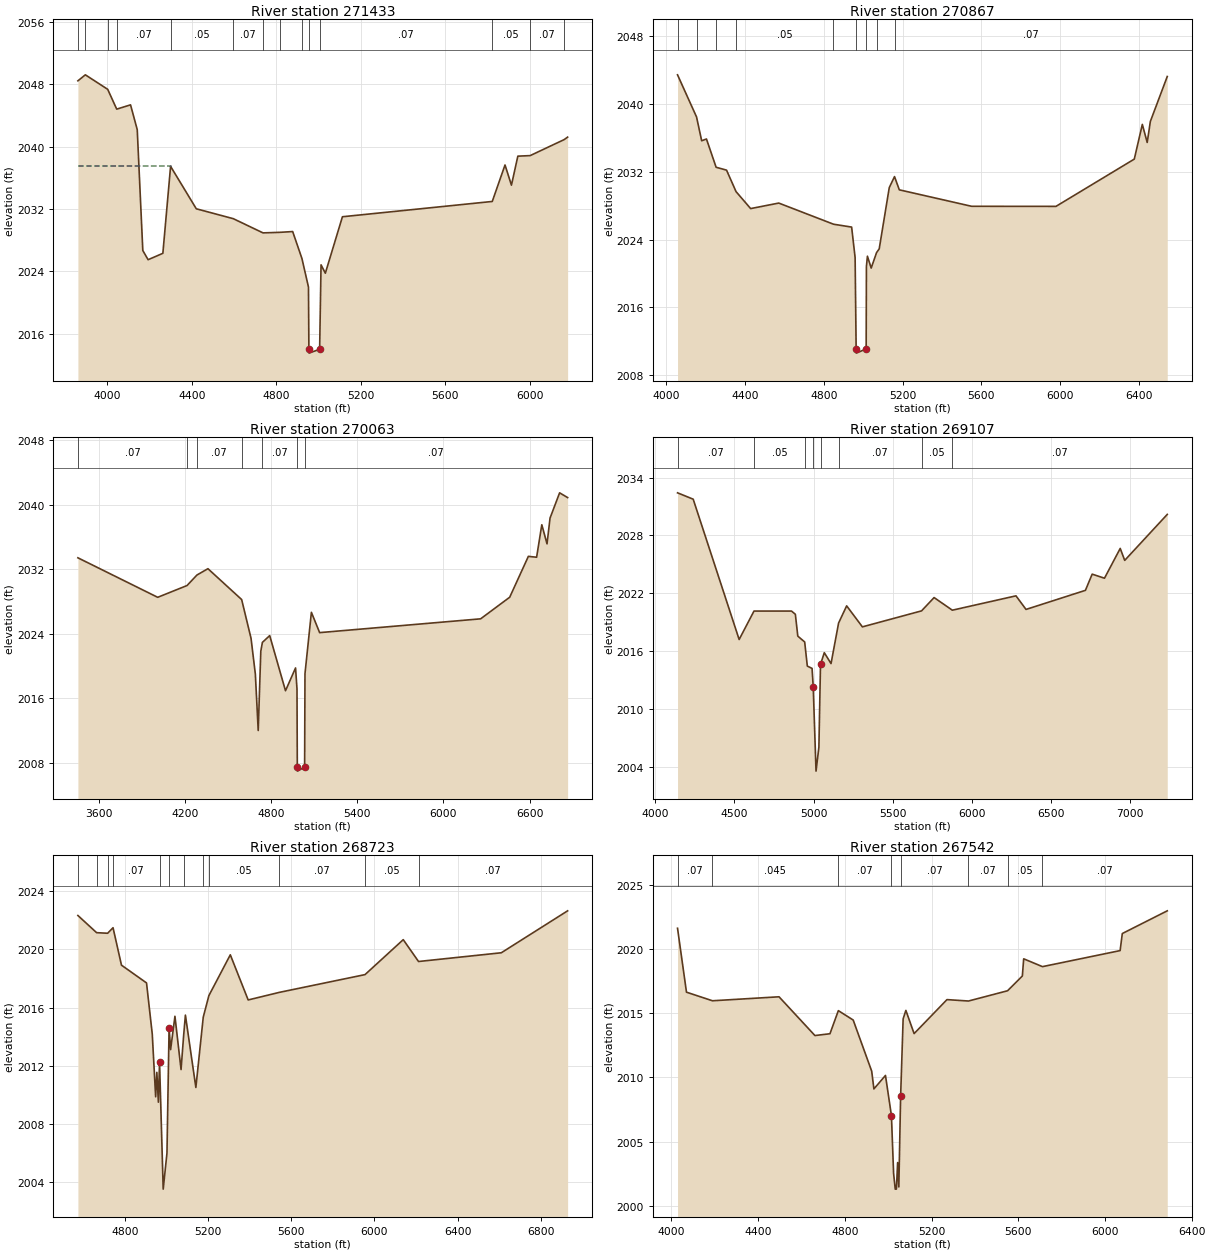
Type RM Length L Ch R = 1 ,271433  ,566,566,566
BEGIN DESCRIPTION:
Mapping XS 0580796a
END DESCRIPTION:
XS GIS Cut Line= 3
      1470912.75      6822973.65      1471255.62      6821940.68
      1471055.96      6820725.36
#Sta/Elev= 30
  3860.1 2048.44  3895.4 2049.21  4001.3 2047.35    4044 2044.81  4109.5 2045.36
  4141.2 2042.18  4167.6 2026.68  4192.7  2025.5  4262.6 2026.32  4299.2 2037.47
    4421 2032.03  4596.4 2030.76    4737 2028.94    4816 2029.01  4877.6 2029.11
  4921.6 2025.64  4952.4 2021.99  4954.4 2014.02  4955.4 2013.52  5005.3 2014.02
    5012 2024.84  5032.3 2023.77  5113.3 2031.01  5823.1 2032.97  5883.5 2037.65
  5913.9 2035.06  5944.3 2038.78  6002.6 2038.85  6163.4  2040.9  6180.1 2041.22
#Mann= 14 ,-1 , 0
  3860.1     .05       0  3895.4     .07       0  4001.3     .05       0
    4044     .07       0  4299.2     .05       0  4596.4     .07       0
    4737     .16       0    4816     .12       0  4921.6     .07       0
  4954.4     .07       0  5005.3     .07       0  5823.1     .05       0
  6002.6     .07       0  6163.4     .05       0
#XS Ineff= 2 , 0
       0  4299.6 2037.55               0
Permanent Ineff=
       F       F
Bank Sta=4954.4,5005.3
XS Rating Curve= 0 ,0
Exp/Cntr=0.3,0.1

Type RM Length L Ch R = 1 ,270867  ,804,804,804
BEGIN DESCRIPTION:
Mapping XS ac895dd6
END DESCRIPTION:
XS GIS Cut Line= 3
      1471585.48      6822951.97      1471767.77      6822049.19
      1471459.84      6820513.87
#Sta/Elev= 30
  4057.2 2043.41  4153.7 2038.45  4179.8 2035.64  4204.1 2035.85  4253.1 2032.52
  4306.1 2032.18  4354.3 2029.65  4428.5 2027.65  4571.3  2028.3  4849.2 2025.81
  4941.3 2025.47    4959 2021.88  4964.2 2011.12  4965.2 2010.62  5015.1 2011.12
  5016.4 2020.84  5021.5 2022.04  5040.6 2020.64  5067.9 2022.46  5081.4 2022.91
  5132.4 2030.12  5159.1 2031.42  5183.4 2029.86  5550.6 2027.92  5978.9 2027.91
  6376.7 2033.48  6417.5 2037.57  6442.3 2035.44  6458.3 2037.92  6544.1 2043.21
#Mann= 9 ,-1 , 0
  4057.2     .07       0  4153.7     .05       0  4253.1     .07       0
  4354.3     .05       0  4849.2     .07       0  4964.2     .07       0
  5015.1     .07       0  5067.9     .16       0  5159.1     .07       0
Bank Sta=4964.2,5015.1
XS Rating Curve= 0 ,0
Exp/Cntr=0.3,0.1

Type RM Length L Ch R = 1 ,270063  ,956,956,956
BEGIN DESCRIPTION:
Mapping XS 94d278f6
END DESCRIPTION:
XS GIS Cut Line= 3
      1472553.36      6823533.57      1472525.07      6821987.82
      1471512.18      6820422.33
#Sta/Elev= 30
    3454 2033.39  4009.7 2028.49    4214 2029.95  4282.8 2031.25  4359.7 2032.04
  4594.5 2028.21  4659.8  2023.4  4689.8 2018.97  4709.8 2011.97  4727.8  2021.8
  4738.9  2022.9  4789.8 2023.74  4899.8  2016.9  4969.8 2019.73  4979.8 2017.13
    4982 2007.43    4983 2006.93    5033 2007.43  5035.5 2019.02  5080.1 2026.63
  5137.5 2024.11  6258.7 2025.82  6461.2  2028.5  6591.2 2033.57  6648.6 2033.46
  6684.8 2037.49  6721.1 2035.12  6742.2 2038.32  6808.8 2041.45  6864.6 2040.86
#Mann= 7 ,-1 , 0
    3454     .07       0    4214     .16       0  4282.8     .07       0
  4594.5     .05       0  4738.9     .07       0    4982     .07       0
    5033     .07       0
Bank Sta=4982,5033
XS Rating Curve= 0 ,0
Exp/Cntr=0.3,0.1

Type RM Length L Ch R = 1 ,269107  ,384,384,384
BEGIN DESCRIPTION:
Mapping XS 5f64c693
END DESCRIPTION:
XS GIS Cut Line= 3
      1473352.28      6822996.73      1473397.42      6822107.87
      1471760.29      6820633.17
#Sta/Elev= 30
  4140.2 2032.41  4239.1 2031.75  4529.4 2017.19  4623.2 2020.14  4859.9 2020.14
  4884.4 2019.81  4899.9 2017.54  4943.4 2016.93    4960 2014.43    4990 2014.19
  4997.4 2012.23    5015 2003.53  5033.1 2006.01  5043.3  2014.6  5067.2 2015.82
  5109.8 2014.69  5157.6  2018.9  5208.5 2020.68  5307.9  2018.5  5681.6 2020.16
  5760.8 2021.54    5876 2020.23    6278 2021.72  6341.5 2020.31  6716.7 2022.29
  6759.3 2023.97  6837.1 2023.55  6936.5 2026.64  6964.9  2025.4  7233.6 2030.17
#Mann= 8 ,-1 , 0
  4140.2     .07       0  4623.2     .05       0  4943.4     .16       0
  4997.4     .05       0  5043.3     .07       0  5157.6     .07       0
  5681.6     .05       0    5876     .07       0
Bank Sta=4997.4,5043.3
XS Rating Curve= 0 ,0
Exp/Cntr=0.3,0.1

Type RM Length L Ch R = 1 ,268723  ,1181,1181,1181
BEGIN DESCRIPTION:
Mapping XS a1fa4380
END DESCRIPTION:
XS GIS Cut Line= 3
      1473947.78      6822419.26      1473747.66      6822044.33
      1472184.75      6820914.03
#Sta/Elev= 30
    4575 2022.32  4664.9 2021.14  4717.9  2021.1  4743.9 2021.48  4784.4 2018.91
  4904.8 2017.69  4932.4 2014.18  4948.7 2009.87  4954.4 2011.55  4961.8  2009.5
  4967.4 2012.23    4985 2003.53  5003.1 2006.01  5013.3  2014.6  5020.6 2013.11
  5041.4  2015.4  5070.8 2011.74  5083.2 2014.07  5091.7 2015.48    5142 2010.51
  5177.5 2015.34  5204.6 2016.82  5307.5 2019.62  5393.4 2016.52    5543 2017.04
    5955 2018.26  6138.7 2020.66  6212.2 2019.16  6610.1 2019.76  6928.8 2022.64
#Mann= 12 ,-1 , 0
    4575     .05       0  4664.9     .07       0  4717.9     .05       0
  4743.9     .07       0  4967.4     .05       0  5013.3     .07       0
  5083.2     .05       0  5177.5     .07       0  5204.6     .05       0
    5543     .07       0    5955     .05       0  6212.2     .07       0
Bank Sta=4967.4,5013.3
XS Rating Curve= 0 ,0
Exp/Cntr=0.3,0.1

Type RM Length L Ch R = 1 ,267542  ,521,521,521
BEGIN DESCRIPTION:
Mapping XS 893cf01d
END DESCRIPTION:
XS GIS Cut Line= 3
      1474373.71      6821424.89      1473463.08       6821084.7
      1472189.95      6820893.56
#Sta/Elev= 30
  4027.9 2021.63  4069.2 2016.65    4189 2015.98  4496.2 2016.29  4661.8 2013.27
  4731.1 2013.41  4769.9 2015.21  4838.3 2014.48  4923.8 2010.49  4933.9 2009.11
  4987.3 2010.16  5014.8 2007.03  5024.8 2002.52  5032.4  2001.3  5037.7  2001.3
  5043.3 2003.37  5048.9 2001.47  5057.2 2008.52  5068.8 2014.57  5081.4 2015.23
  5119.4 2013.42  5271.1 2016.07  5370.3 2015.96  5550.6 2016.76  5618.8 2017.91
    5625 2019.25  5711.7 2018.64  6069.9 2019.89    6080 2021.22  6287.4 2022.99
#Mann= 8 ,-1 , 0
  4027.9     .07       0    4189    .045       0  4769.9     .07       0
  5014.8     .05       0  5057.2     .07       0  5370.3     .07       0
  5550.6     .05       0  5711.7     .07       0
Bank Sta=5014.8,5057.2
XS Rating Curve= 0 ,0
Exp/Cntr=0.3,0.1

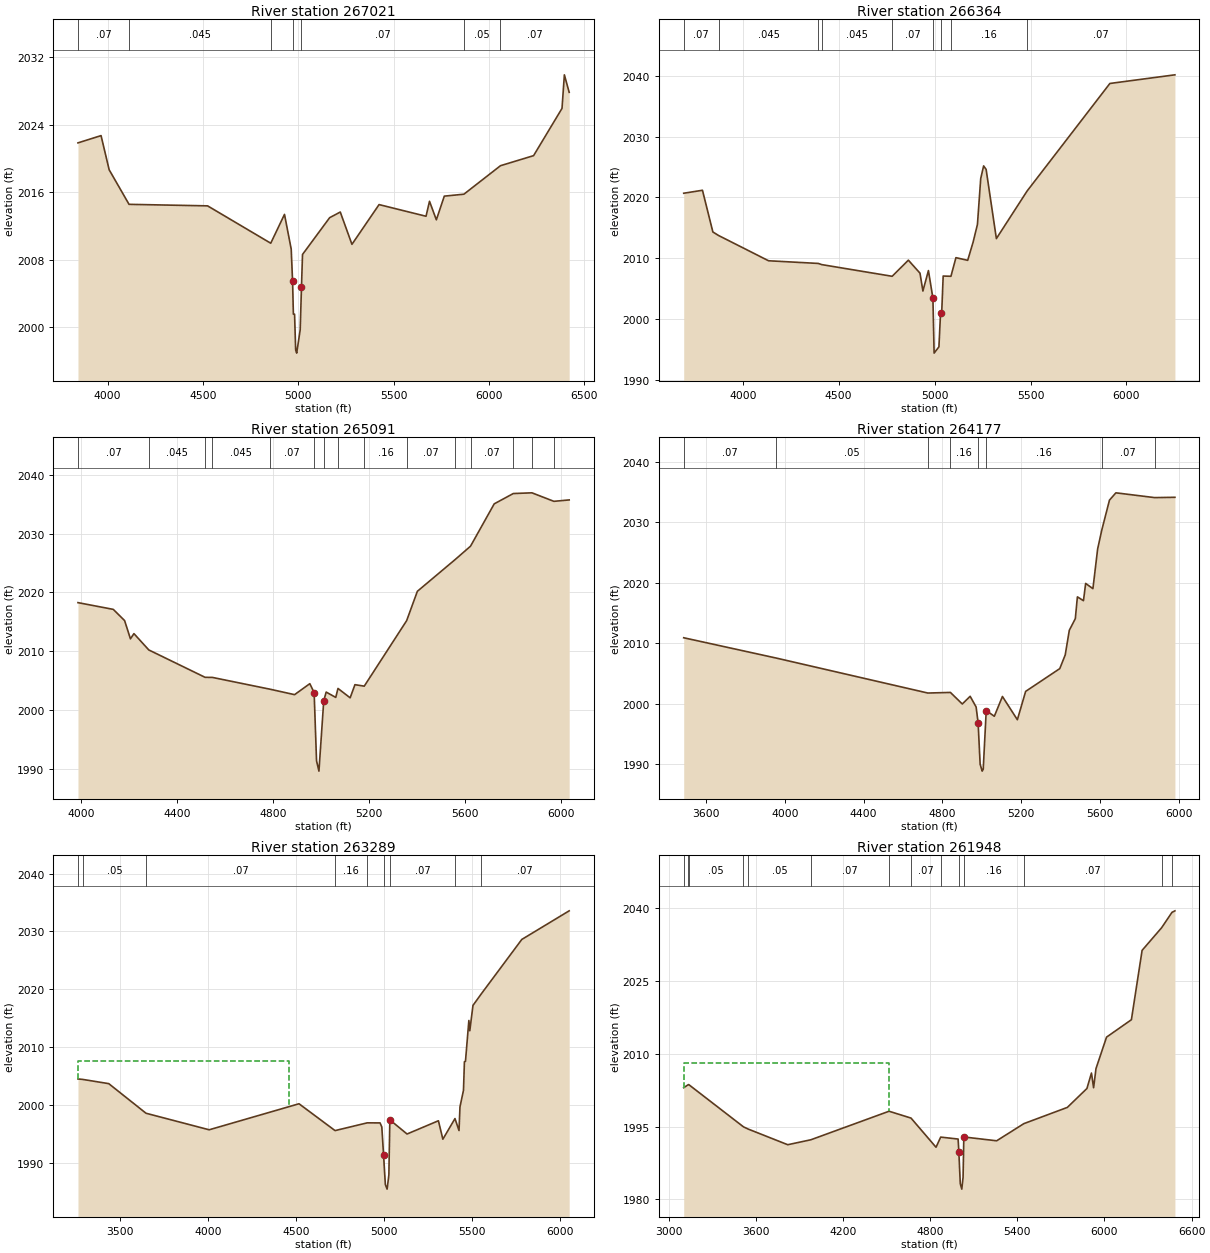
Type RM Length L Ch R = 1 ,267021  ,657,657,657
BEGIN DESCRIPTION:
Mapping XS c09994cf
END DESCRIPTION:
XS GIS Cut Line= 3
      1474546.73      6821527.24      1473765.47      6820706.93
      1472409.71      6820213.14
#Sta/Elev= 30
  3844.3 2021.83  3965.3 2022.69  4007.8 2018.65  4112.1 2014.56  4523.9 2014.38
  4855.1 2009.96  4927.2 2013.37  4962.4 2009.27  4969.6 2005.45  4973.8 2001.57
    4980 2001.57  4985.8 1997.33  4991.1 1996.96  5009.5 1999.71  5016.3  2004.8
  5021.7 2008.63  5163.9 2012.98  5219.7 2013.65  5280.9 2009.83  5423.1 2014.53
  5669.4 2013.15  5687.6 2014.92  5723.5 2012.73  5765.2 2015.53    5868 2015.76
  6059.8 2019.13  6233.4 2020.32  6382.4 2025.91  6394.8 2029.88    6420 2027.81
#Mann= 7 ,-1 , 0
  3844.3     .07       0  4112.1    .045       0  4855.1     .07       0
  4969.6     .05       0  5016.3     .07       0    5868     .05       0
  6059.8     .07       0
Bank Sta=4969.6,5016.3
XS Rating Curve= 0 ,0
Exp/Cntr=0.3,0.1

Type RM Length L Ch R = 1 ,266364  ,1273,1273,1273
BEGIN DESCRIPTION:
Mapping XS 702ccfca
END DESCRIPTION:
XS GIS Cut Line= 3
       1474726.9      6821487.34      1474205.14      6820288.35
      1474747.72      6819159.25
#Sta/Elev= 30
  3692.4 2020.68  3790.1 2021.17  3844.4 2014.32  3874.1 2013.74  4134.6 2009.59
    4394 2009.15  4411.7 2008.96  4778.9 2007.04  4863.3 2009.69    4924 2007.55
  4939.1 2004.62  4967.9 2007.98  4991.4 2003.42  4997.5 1994.42  5022.6 1995.45
  5031.2 2001.03  5036.8  2000.8  5044.8 2007.08  5085.2 2007.04  5111.3  2010.1
  5172.6 2009.66  5200.8 2012.65  5223.4 2015.56  5240.5 2023.09  5255.6 2025.17
  5268.7 2024.59  5322.1 2013.23  5481.9 2021.03  5913.7 2038.71  6252.7 2040.13
#Mann= 9 ,-1 , 0
  3692.4     .07       0  3874.1    .045       0    4394     .07       0
  4411.7    .045       0  4778.9     .07       0  4991.4     .05       0
  5031.2     .07       0  5085.2     .16       0  5481.9     .07       0
Bank Sta=4991.4,5031.2
XS Rating Curve= 0 ,0
Exp/Cntr=0.3,0.1

Type RM Length L Ch R = 1 ,265091  ,914,914,914
BEGIN DESCRIPTION:
Mapping XS 599b187f
END DESCRIPTION:
XS GIS Cut Line= 3
        1474889.      6821634.93      1475243.18      6820739.08
      1475284.85       6819655.7
#Sta/Elev= 30
  3985.7 2018.27  4132.9 2017.12  4180.1 2015.21  4204.4  2012.1    4219 2012.99
  4280.9 2010.21  4515.7 2005.54  4545.7 2005.53  4786.1 2003.52  4888.5 2002.59
  4952.1 2004.46  4970.1 2002.94  4980.1 1991.32  4990.1 1989.56  5010.1 2001.52
  5020.2 2003.03  5060.2 2002.12  5069.5 2003.65  5120.2 2002.05  5140.2 2004.29
    5179 2004.04  5355.7  2015.2  5400.4  2020.2  5558.2 2025.62    5622 2027.89
  5720.7  2035.1  5800.3 2036.86    5878 2036.98  5969.5 2035.53  6033.2 2035.77
#Mann= 15 ,-1 , 0
  3985.7     .07       0  4280.9    .045       0  4515.7     .07       0
  4545.7    .045       0  4786.1     .07       0  4970.1     .05       0
  5010.1     .07       0  5069.5     .07       0    5179     .16       0
  5355.7     .07       0  5558.2     .16       0    5622     .07       0
  5800.3     .05       0    5878     .07       0  5969.5     .05       0
Bank Sta=4970.1,5010.1
XS Rating Curve= 0 ,0
Exp/Cntr=0.3,0.1

Type RM Length L Ch R = 1 ,264177  ,888,888,888
BEGIN DESCRIPTION:
Mapping XS 85964768
END DESCRIPTION:
XS GIS Cut Line= 3
      1476062.62       6822141.9      1476069.57      6820662.69
      1475833.46      6819676.59
#Sta/Elev= 30
  3486.6 2010.92  3956.5 2007.56  4725.8 2001.78  4840.3 2001.88  4900.5 1999.97
  4940.5 2001.24  4970.8 1999.47  4980.9 1996.86  4991.2    1990  5001.5 1988.87
  5006.8 1989.18  5022.1 1998.88  5063.2 1997.94  5104.3 2001.21  5180.1 1997.37
  5222.1 2002.05  5395.4 2005.82  5423.1 2008.09  5443.7 2012.15  5474.3 2014.08
  5484.8 2017.68  5515.6 2017.05  5526.7  2019.9  5563.6 2019.04  5587.6  2025.6
  5608.2 2028.67  5647.6 2033.67  5680.2 2034.88  5876.7 2034.09  5979.8 2034.14
#Mann= 8 ,-1 , 0
  3486.6     .07       0  3956.5     .05       0  4725.8     .07       0
  4840.3     .16       0  4980.9     .05       0  5022.1     .16       0
  5608.2     .07       0  5876.7     .05       0
Bank Sta=4980.9,5022.1
XS Rating Curve= 0 ,0
Exp/Cntr=0.3,0.1

Type RM Length L Ch R = 1 ,263289  ,1341,1341,1341
BEGIN DESCRIPTION:
Mapping XS 7cfbbbba
END DESCRIPTION:
XS GIS Cut Line= 3
      1476875.12      6821912.65      1476764.01      6820141.85
      1476416.78       6819183.5
#Sta/Elev= 30
  3260.7 2004.48  3287.7  2004.4  3435.7 2003.67  3647.7 1998.55  4006.8 1995.69
  4517.8 2000.19  4722.8 1995.55  4905.7 1996.89  4978.7 1996.88  4988.7 1996.18
  4998.8 1991.29  5008.8 1986.22  5018.8 1985.43  5028.8 1987.87  5034.4 1997.41
  5132.2 1994.96  5310.6 1997.25  5335.9 1994.06  5404.8 1997.63  5427.8 1995.56
  5433.2 1999.65  5453.2 2002.52  5458.5 2007.45  5464.5 2007.54  5483.8 2014.59
  5489.1 2012.81  5507.1 2017.19  5553.7 2019.16  5784.8  2028.6  6054.3 2033.55
#Mann= 9 ,-1 , 0
  3260.7     .07       0  3287.7     .05       0  3647.7     .07       0
  4722.8     .16       0  4905.7     .07       0  4998.8     .05       0
  5034.4     .07       0  5404.8     .16       0  5553.7     .07       0
#XS Ineff= 2 , 0
       0  4461.3 2007.63               0
Permanent Ineff=
       F       F
Bank Sta=4998.8,5034.4
XS Rating Curve= 0 ,0
Exp/Cntr=0.3,0.1

Type RM Length L Ch R = 1 ,261948  ,964,964,964
BEGIN DESCRIPTION:
Mapping XS b31ee7b2
END DESCRIPTION:
XS GIS Cut Line= 3
      1477034.83      6822058.56      1477597.35      6820343.24
      1478020.39      6818824.46
#Sta/Elev= 30
  3103.1    2003  3134.9 2003.63  3138.2 2003.63  3514.3 1994.94  3546.8 1994.48
  3819.3 1991.25  3978.4 1992.27  4516.7 1998.15    4668 1996.74  4840.2 1990.73
  4872.3 1992.82  4992.2 1992.42  4997.4 1989.81  5007.2 1983.21  5017.5  1982.1
  5026.4 1984.53  5031.6 1992.85  5257.6 1992.06  5445.2  1995.6  5744.2 1998.94
  5879.1 2002.84  5910.3 2006.02  5925.1 2002.99  5941.4 2006.93  6014.1 2013.42
  6185.3 2017.01  6258.9  2031.3  6393.2 2035.96  6464.5 2039.13  6484.9 2039.45
#Mann= 14 ,-1 , 0
  3103.1     .05       0  3134.9     .07       0  3138.2     .05       0
  3514.3     .07       0  3546.8     .05       0  3978.4     .07       0
  4516.7     .05       0    4668     .07       0  4872.3     .16       0
  4997.4     .05       0  5031.6     .16       0  5445.2     .07       0
  6393.2     .05       0  6464.5     .07       0
#XS Ineff= 2 , 0
       0  4513.2 2008.14               0
Permanent Ineff=
       F       F
Bank Sta=4997.4,5031.6
XS Rating Curve= 0 ,0
Exp/Cntr=0.3,0.1

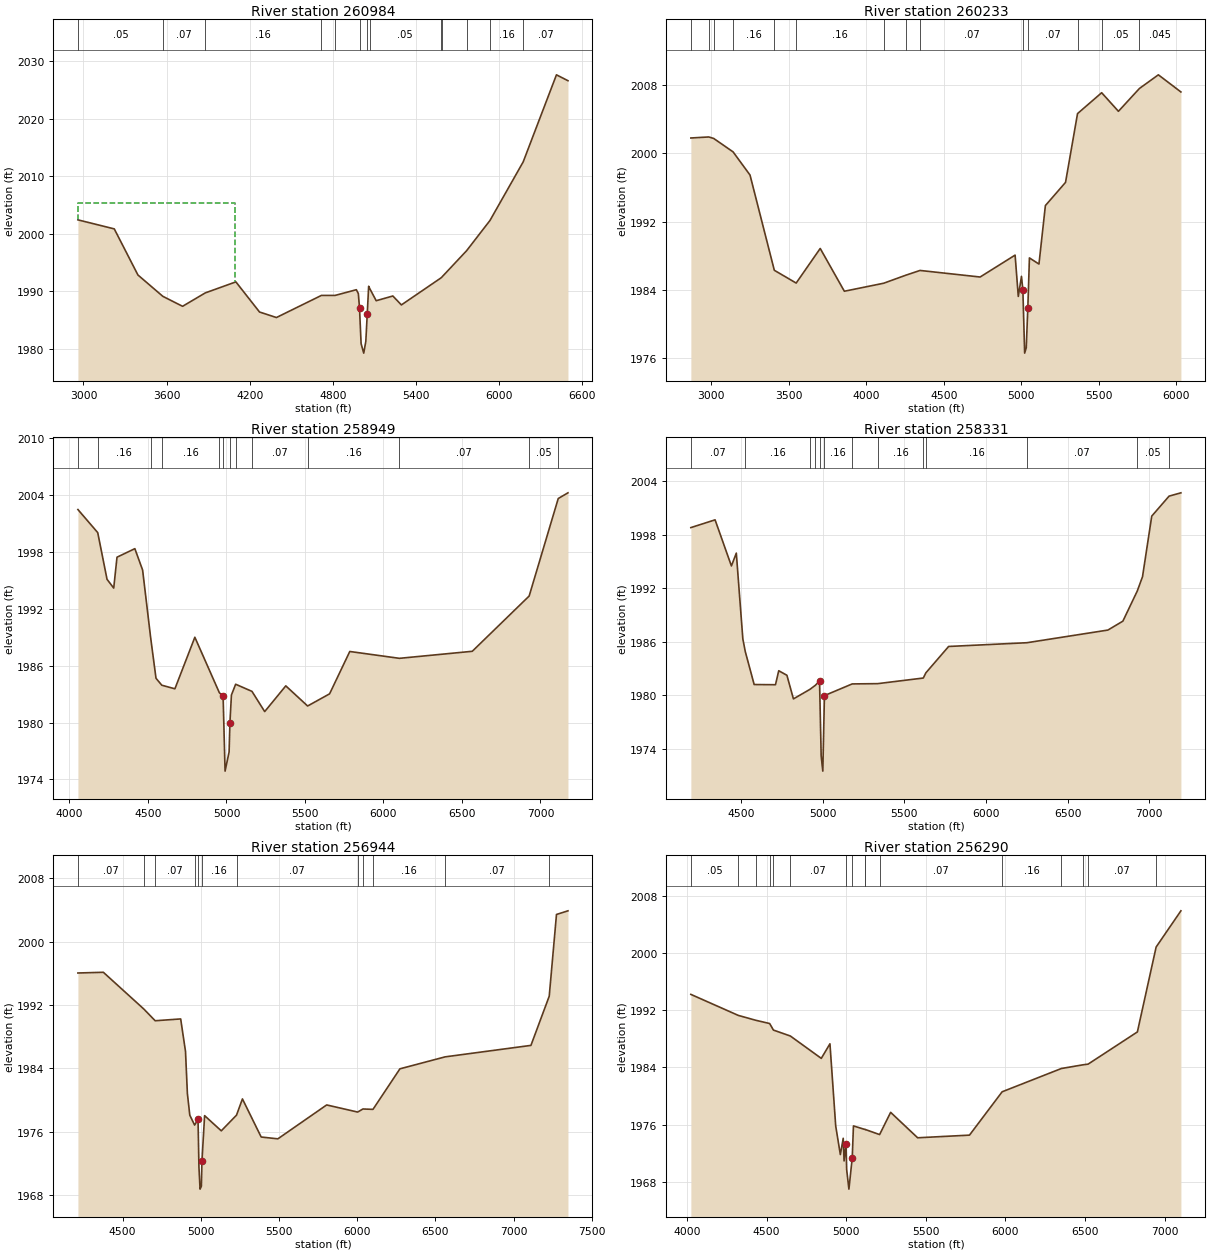
Type RM Length L Ch R = 1 ,260984  ,751,751,751
BEGIN DESCRIPTION:
Mapping XS f24e713e
END DESCRIPTION:
XS GIS Cut Line= 3
      1477250.12      6822190.48      1478486.23      6820558.52
      1478826.51      6819107.13
#Sta/Elev= 30
  2960.1 2002.42  3222.6 2000.85  3393.3 1992.85  3573.2 1989.14  3715.7 1987.41
  3879.9 1989.74  4100.6 1991.65  4271.2 1986.42  4393.3 1985.46  4718.1  1989.3
  4816.7  1989.3  4970.4 1990.29  4984.8 1989.61  4993.1 1987.13  5004.5 1980.94
  5023.6 1979.28  5038.7 1981.33    5049 1986.09  5059.2 1990.89    5067 1990.49
  5113.6 1988.38  5233.9  1989.2  5295.5 1987.65  5580.2 1992.32    5586 1992.44
  5766.6 1997.07    5935 2002.31  6174.8 2012.48    6415  2027.6  6498.1 2026.58
#Mann= 13 ,-1 , 0
  2960.1     .05       0  3573.2     .07       0  3879.9     .16       0
  4718.1     .07       0  4816.7     .16       0  4993.1     .05       0
    5049     .16       0    5067     .05       0  5580.2     .07       0
    5586     .05       0  5766.6     .07       0    5935     .16       0
  6174.8     .07       0
#XS Ineff= 2 , 0
       0  4092.6 2005.28               0
Permanent Ineff=
       F       F
Bank Sta=4993.1,5049
XS Rating Curve= 0 ,0
Exp/Cntr=0.3,0.1

Type RM Length L Ch R = 1 ,260233  ,1284,1284,1284
BEGIN DESCRIPTION:
Mapping XS 916804fb
END DESCRIPTION:
XS GIS Cut Line= 3
      1477356.19      6822238.57      1478522.87      6821118.76
      1480028.04      6820780.23
#Sta/Elev= 30
  2869.4  2001.8  2984.3 2001.92  3016.3 2001.75  3141.6 2000.17  3250.9 1997.45
  3407.5 1986.28  3548.5 1984.78  3703.5 1988.84  3859.1 1983.82  4112.7 1984.76
  4253.7 1985.69  4347.2 1986.26  4734.7 1985.49  4960.2 1988.06  4980.7 1983.21
  5001.2 1985.57  5010.2    1984  5021.7 1976.56    5032 1977.19  5042.2 1981.88
  5052.5 1987.73    5114 1987.01  5155.4 1993.87  5285.3 1996.59  5362.7 2004.66
  5518.3 2007.11  5626.4 2004.93  5761.9 2007.61  5883.9 2009.21  6029.3  2007.2
#Mann= 14 ,-1 , 0
  2869.4     .05       0  2984.3     .07       0  3016.3     .05       0
  3141.6     .16       0  3407.5     .07       0  3548.5     .16       0
  4112.7     .07       0  4253.7     .16       0  4347.2     .07       0
  5010.2    .045       0  5042.2     .07       0  5362.7     .07       0
  5518.3     .05       0  5761.9    .045       0
Bank Sta=5010.2,5042.2
XS Rating Curve= 0 ,0
Exp/Cntr=0.3,0.1

Type RM Length L Ch R = 1 ,258949  ,618,618,618
BEGIN DESCRIPTION:
Mapping XS acecafc5
END DESCRIPTION:
XS GIS Cut Line= 4
      1477443.45      6822258.12      1478016.34      6821747.73
      1478903.42      6822059.52       1480045.8      6821226.16
#Sta/Elev= 30
  4053.8 2002.43    4180    2000  4239.3 1995.08  4281.9 1994.16  4302.8 1997.41
  4416.5 1998.31  4465.9 1996.06  4517.1 1988.94  4551.2 1984.66    4588 1983.93
  4671.6 1983.55  4798.7 1988.98  4954.7 1983.14  4978.7 1982.75  4991.2 1974.88
  5016.8  1976.9  5022.1 1979.98  5031.7  1982.9  5058.6 1984.03  5162.5 1983.28
  5243.6 1981.15    5378 1983.86    5517 1981.74    5657 1983.02  5785.6 1987.48
  6101.6 1986.76  6565.8  1987.5  6928.2 1993.32  7113.5 2003.59  7175.4 2004.19
#Mann= 13 ,-1 , 0
  4053.8     .07       0    4180     .16       0  4517.1     .07       0
    4588     .16       0  4954.7     .07       0  4978.7     .05       0
  5022.1     .07       0  5058.6     .16       0  5162.5     .07       0
    5517     .16       0  6101.6     .07       0  6928.2     .05       0
  7113.5    .045       0
Bank Sta=4978.7,5022.1
XS Rating Curve= 0 ,0
Exp/Cntr=0.3,0.1

Type RM Length L Ch R = 1 ,258331  ,1387,1387,1387
BEGIN DESCRIPTION:
Mapping XS 1dcfab75
END DESCRIPTION:
XS GIS Cut Line= 4
      1477396.57      6822377.93      1478224.68      6822367.52
      1479302.15      6822181.22      1480087.46      6821437.97
#Sta/Elev= 30
  4191.4 1998.81  4339.8 1999.68  4439.9 1994.51  4469.9 1995.95  4509.9 1986.33
  4524.8 1984.91  4579.3 1981.21  4709.9 1981.19  4729.9 1982.76  4779.9 1982.25
  4819.9  1979.6    4921 1980.67  4954.5 1981.13  4979.9 1981.61  4989.9 1973.21
  4999.9  1971.5  5009.9 1979.97  5180.1 1981.28  5335.9 1981.31  5615.7 1981.94
  5631.4 1982.52  5770.9 1985.48  6250.7  1985.9    6747 1987.32  6838.8 1988.32
  6926.9  1991.7    6959  1993.3  7015.6  2000.1  7121.8 2002.34  7194.3 2002.71
#Mann= 13 ,-1 , 0
  4191.4     .07       0  4524.8     .16       0    4921     .07       0
  4954.5     .16       0  4979.9     .05       0  5009.9     .16       0
  5180.1     .07       0  5335.9     .16       0  5615.7     .07       0
  5631.4     .16       0  6250.7     .07       0  6926.9     .05       0
  7121.8    .045       0
Bank Sta=4979.9,5009.9
XS Rating Curve= 0 ,0
Exp/Cntr=0.3,0.1

Type RM Length L Ch R = 1 ,256944  ,654,654,654
BEGIN DESCRIPTION:
Mapping XS 490fb635
END DESCRIPTION:
XS GIS Cut Line= 3
      1477573.67      6823638.33      1478255.93       6823232.1
      1480051.32      6821730.82
#Sta/Elev= 30
  4213.9 1996.03  4376.6 1996.12  4634.9 1991.49    4708    1990  4871.2 1990.23
  4902.1 1986.12    4914 1980.83  4929.6 1978.07  4960.3 1976.83  4982.2 1977.54
    4988 1971.53  4995.2 1968.74  5003.6 1969.11  5007.1 1972.23  5024.2 1978.02
  5130.9  1976.1  5228.3 1978.08  5266.2 1980.13    5386 1975.32  5492.7 1975.09
    5805 1979.37  6003.2 1978.47  6036.9 1978.86  6101.1 1978.81  6273.5 1983.93
  6562.6 1985.44  7111.5 1986.89  7228.5  1993.1  7274.9 2003.42  7348.3 2003.88
#Mann= 12 ,-1 , 0
  4213.9     .07       0  4634.9     .05       0    4708     .07       0
  4960.3     .16       0  4982.2     .05       0  5007.1     .16       0
  5228.3     .07       0  6003.2     .16       0  6036.9     .07       0
  6101.1     .16       0  6562.6     .07       0  7228.5     .05       0
Bank Sta=4982.2,5007.1
XS Rating Curve= 0 ,0
Exp/Cntr=0.3,0.1

Type RM Length L Ch R = 1 ,256290  ,642,642,642
BEGIN DESCRIPTION:
MULBERRY CREEK 68.0
END DESCRIPTION:
XS GIS Cut Line= 3
      1477811.78      6823920.81        1478705.        6823538.
      1480121.07      6821977.39
#Sta/Elev= 30
  4023.7 1994.23  4321.3 1991.29  4430.4 1990.61  4518.7 1990.15  4542.5 1989.23
  4648.9  1988.4  4843.2 1985.27  4897.6 1987.31  4933.8  1975.8  4962.9  1971.8
    4981 1974.08  4986.4 1970.91  4998.9 1973.34  5002.6 1969.69  5016.8 1966.96
  5037.7 1971.34  5045.2 1975.81  5119.3  1975.3  5119.6 1975.31  5209.6  1974.6
    5279 1977.71  5448.6 1974.15  5774.3 1974.52  5979.6 1980.59  6351.8 1983.85
  6488.2 1984.37  6519.5 1984.46  6829.3 1988.97  6947.1 2000.86  7102.8 2005.93
#Mann= 16 ,-1 , 0
  4023.7     .05       0  4321.3     .07       0  4430.4     .05       0
  4518.7     .07       0  4542.5     .05       0  4648.9     .07       0
  4998.9     .05       0  5037.7     .07       0  5119.3     .12       0
  5119.6     .16       0  5209.6     .07       0  5979.6     .16       0
  6351.8     .07       0  6488.2     .16       0  6519.5     .07       0
  6947.1     .05       0
Bank Sta=4998.9,5037.7
XS Rating Curve= 0 ,0
Exp/Cntr=0.3,0.1