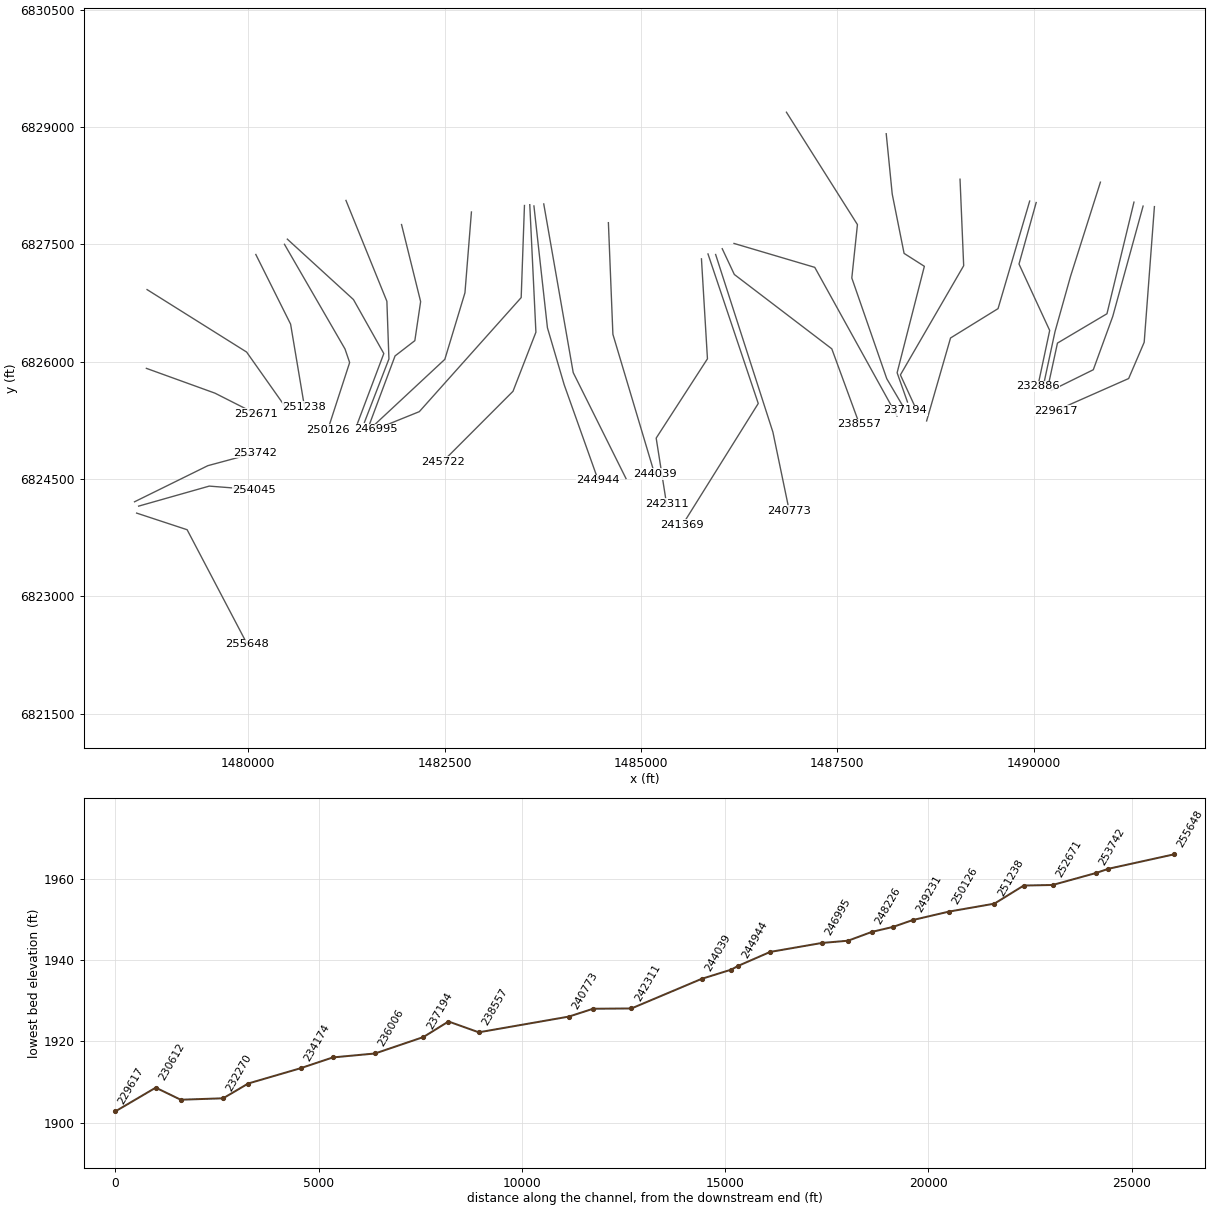
HEC-RAS study MULBERRY CREEK.prj: MULBERRY CREEK Base Level Engineering

--- MULBERRY CREEK.g01 (geometry) --- (continued)

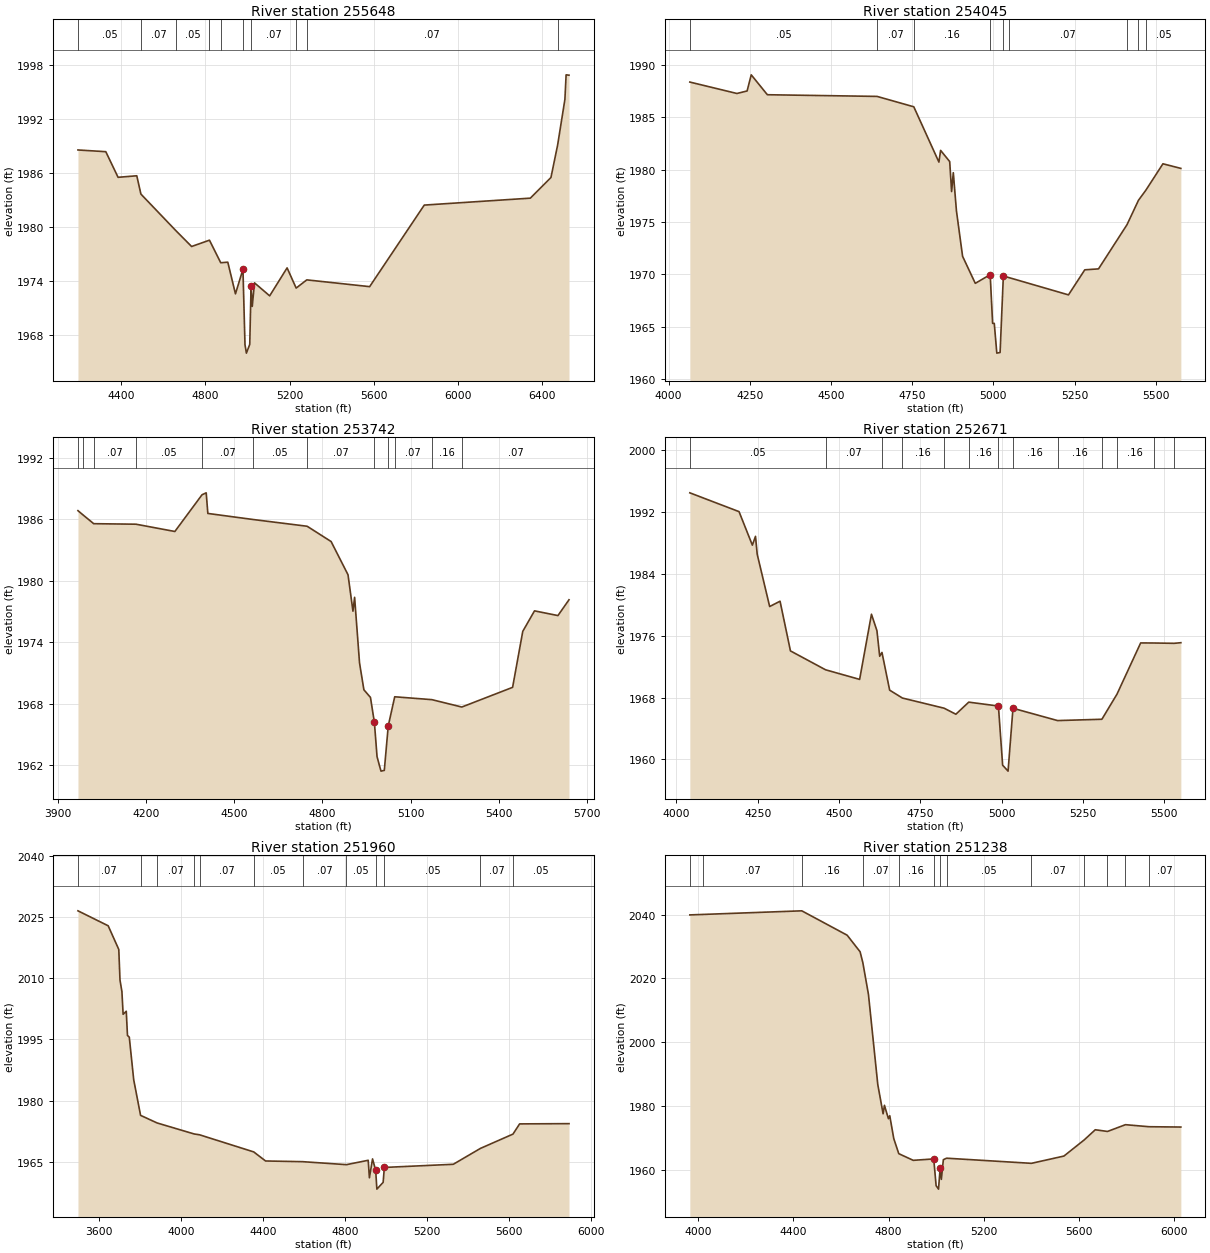
Type RM Length L Ch R = 1 ,255648  ,1603,1603,1603
BEGIN DESCRIPTION:
Mapping XS 435b0bb0
END DESCRIPTION:
XS GIS Cut Line= 3
        1478580.        6824063.      1479222.86      6823850.31
      1479988.79       6822385.5
#Sta/Elev= 30
  4196.2 1988.53  4328.3 1988.34  4386.5  1985.5  4475.3 1985.67  4494.9 1983.64
  4661.5 1979.57  4735.4 1977.83  4820.2 1978.53  4873.7 1976.03  4907.2 1976.09
  4943.6 1972.58  4979.1 1975.31  4988.8 1966.94  4995.5 1966.01  5011.4 1966.98
  5017.6 1973.43  5023.3 1971.19  5033.9  1973.8  5105.9 1972.36  5188.6 1975.46
  5231.6 1973.22    5282 1974.13  5580.3 1973.38  5839.5 1982.42  6342.9 1983.19
  6440.7 1985.48  6472.3 1989.07  6506.9 1994.14  6512.6 1996.86  6526.3 1996.82
#Mann= 10 ,-1 , 0
  4196.2     .05       0  4494.9     .07       0  4661.5     .05       0
  4820.2     .16       0  4873.7     .07       0  4979.1     .05       0
  5017.6     .07       0  5231.6     .16       0    5282     .07       0
  6472.3     .05       0
Bank Sta=4979.1,5017.6
XS Rating Curve= 0 ,0
Exp/Cntr=0.3,0.1

Type RM Length L Ch R = 1 ,254045  ,303,303,303
BEGIN DESCRIPTION:
Mapping XS cf960eee
END DESCRIPTION:
XS GIS Cut Line= 3
      1478605.34      6824151.99      1479504.39      6824408.04
      1480080.03        6824363.
#Sta/Elev= 30
  4065.2 1988.35  4210.1 1987.26  4241.6  1987.5  4254.3 1989.04    4304 1987.14
  4641.8 1986.98  4754.9 1985.99  4832.3 1980.71  4837.5 1981.83  4865.5 1980.76
  4871.4  1977.9  4876.6  1979.7  4886.3 1976.05  4905.2 1971.72  4944.3 1969.14
  4990.2 1969.97  4997.7 1965.32  5002.8 1965.32  5010.6 1962.48  5020.7 1962.54
  5030.7 1969.84  5048.9 1969.68  5231.3 1968.04  5281.5 1970.43  5323.8 1970.52
  5411.6 1974.74  5446.9 1977.07  5469.4 1978.02  5522.2 1980.55  5577.4 1980.11
#Mann= 9 ,-1 , 0
  4065.2     .05       0  4641.8     .07       0  4754.9     .16       0
  4990.2     .05       0  5030.7     .16       0  5048.9     .07       0
  5411.6     .16       0  5446.9     .07       0  5469.4     .05       0
Bank Sta=4990.2,5030.7
XS Rating Curve= 0 ,0
Exp/Cntr=0.3,0.1

Type RM Length L Ch R = 1 ,253742  ,1071,1071,1071
BEGIN DESCRIPTION:
Mapping XS d9ce27ff
END DESCRIPTION:
XS GIS Cut Line= 3
      1478553.37      6824207.55      1479487.19      6824669.46
      1480093.45      6824833.61
#Sta/Elev= 30
  3968.4 1986.85  3985.4 1986.44    4022 1985.58  4165.7 1985.53  4297.9 1984.82
  4390.3  1988.4  4404.5 1988.59  4410.1 1986.58  4563.5 1985.99  4747.8 1985.33
  4829.3 1983.84  4886.8  1980.6  4903.6 1977.05  4909.2  1978.4    4926 1971.99
  4940.8 1969.38  4963.1 1968.64  4976.5  1966.2  4985.5 1962.86  4998.9 1961.45
  5010.2 1961.52  5023.6 1965.86  5045.6  1968.7    5172 1968.42  5273.8  1967.7
  5446.5 1969.62  5481.1 1975.08    5521 1977.08  5600.7 1976.62  5638.3 1978.16
#Mann= 12 ,-1 , 0
  3968.4     .07       0  3985.4     .05       0    4022     .07       0
  4165.7     .05       0  4390.3     .07       0  4563.5     .05       0
  4747.8     .07       0  4976.5     .05       0  5023.6     .07       0
  5045.6     .07       0    5172     .16       0  5273.8     .07       0
Bank Sta=4976.5,5023.6
XS Rating Curve= 0 ,0
Exp/Cntr=0.3,0.1

Type RM Length L Ch R = 1 ,252671  ,711,711,711
BEGIN DESCRIPTION:
Mapping XS 35f0cd54
END DESCRIPTION:
XS GIS Cut Line= 3
      1478704.23      6825913.37       1479576.6      6825596.54
       1480095.2      6825333.09
#Sta/Elev= 30
  4041.3 1994.44  4192.6 1992.01  4233.6 1987.68  4243.2 1988.82  4248.5  1986.5
  4286.8 1979.75  4318.7 1980.44  4350.7 1974.02  4458.7 1971.58  4563.4 1970.34
  4599.8 1978.76  4616.6 1976.63  4625.1 1973.33  4632.1 1973.82  4655.7 1968.95
    4695 1967.93  4823.1 1966.62  4859.3 1965.84  4898.9  1967.4  4990.1  1966.9
  5003.1 1959.26  5019.8 1958.49  5034.9 1966.61    5172 1965.02  5308.3 1965.19
  5354.8 1968.44  5427.5 1975.05  5467.5 1975.04  5530.6    1975  5551.1 1975.08
#Mann= 13 ,-1 , 0
  4041.3     .05       0  4458.7     .07       0  4632.1     .05       0
    4695     .16       0  4823.1     .07       0  4898.9     .16       0
  4990.1     .05       0  5034.9     .16       0    5172     .16       0
  5308.3     .07       0  5354.8     .16       0  5467.5     .05       0
  5530.6     .07       0
Bank Sta=4990.1,5034.9
XS Rating Curve= 0 ,0
Exp/Cntr=0.3,0.1

Type RM Length L Ch R = 1 ,251960  ,722,722,722
BEGIN DESCRIPTION:
Mapping XS 699f50b6
END DESCRIPTION:
XS GIS Cut Line= 3
      1478712.93       6826920.3      1479980.25      6826121.72
      1480498.07      6825384.93
#Sta/Elev= 30
    3496 2026.48  3643.6 2022.82  3695.4 2017.02  3701.3 2009.53  3710.7  2006.7
  3716.6 2001.15  3731.9  2001.9  3737.8 1995.98  3746.7 1995.55  3768.3 1985.12
  3801.8 1976.41  3882.5 1974.55  4063.9 1971.85    4090 1971.65  4354.6 1967.46
  4412.3 1965.24  4593.6 1965.07  4807.5 1964.34  4913.7 1965.41  4919.6 1961.13
  4934.9 1965.75  4950.2 1962.94  4956.1 1958.35  4986.7 1960.01  4992.6 1963.66
  5329.3 1964.43  5461.9 1968.32  5620.8 1971.82  5653.4 1974.32  5894.5 1974.38
#Mann= 12 ,-1 , 0
    3496     .07       0  3801.8     .05       0  3882.5     .07       0
  4063.9     .05       0    4090     .07       0  4354.6     .05       0
  4593.6     .07       0  4807.5     .05       0  4950.2    .045       0
  4992.6     .05       0  5461.9     .07       0  5620.8     .05       0
Bank Sta=4950.2,4992.6
XS Rating Curve= 0 ,0
Exp/Cntr=0.3,0.1

Type RM Length L Ch R = 1 ,251238  ,1112,1112,1112
BEGIN DESCRIPTION:
Mapping XS 0460dcec
END DESCRIPTION:
XS GIS Cut Line= 3
      1480097.45      6827369.08      1480540.14      6826478.49
      1480716.71        6825423.
#Sta/Elev= 30
  3964.5 2039.89  4020.7 2040.04  4435.3 2041.17    4626 2033.53  4680.4 2028.33
    4692 2024.91  4715.6 2014.96  4754.8  1986.7  4777.2 1977.52  4782.8 1980.18
  4799.6 1975.97  4805.2  1976.9    4822 1969.75  4843.1 1965.01  4903.8 1962.92
    4990 1963.36  5000.1 1954.98  5010.2 1953.89  5017.1 1960.53  5022.1 1956.95
  5030.5 1963.12  5044.2 1963.59    5401 1961.98  5537.5 1964.26  5622.4  1969.3
  5669.3 1972.51  5720.7 1971.98  5796.3  1974.1  5895.2 1973.46  6029.2 1973.36
#Mann= 13 ,-1 , 0
  3964.5     .16       0  4020.7     .07       0  4435.3     .16       0
    4692     .07       0  4843.1     .16       0    4990     .05       0
  5017.1     .16       0  5044.2     .05       0    5401     .07       0
  5622.4    .035       0  5720.7     .07       0  5796.3     .05       0
  5895.2     .07       0
Bank Sta=4990,5017.1
XS Rating Curve= 0 ,0
Exp/Cntr=0.3,0.1

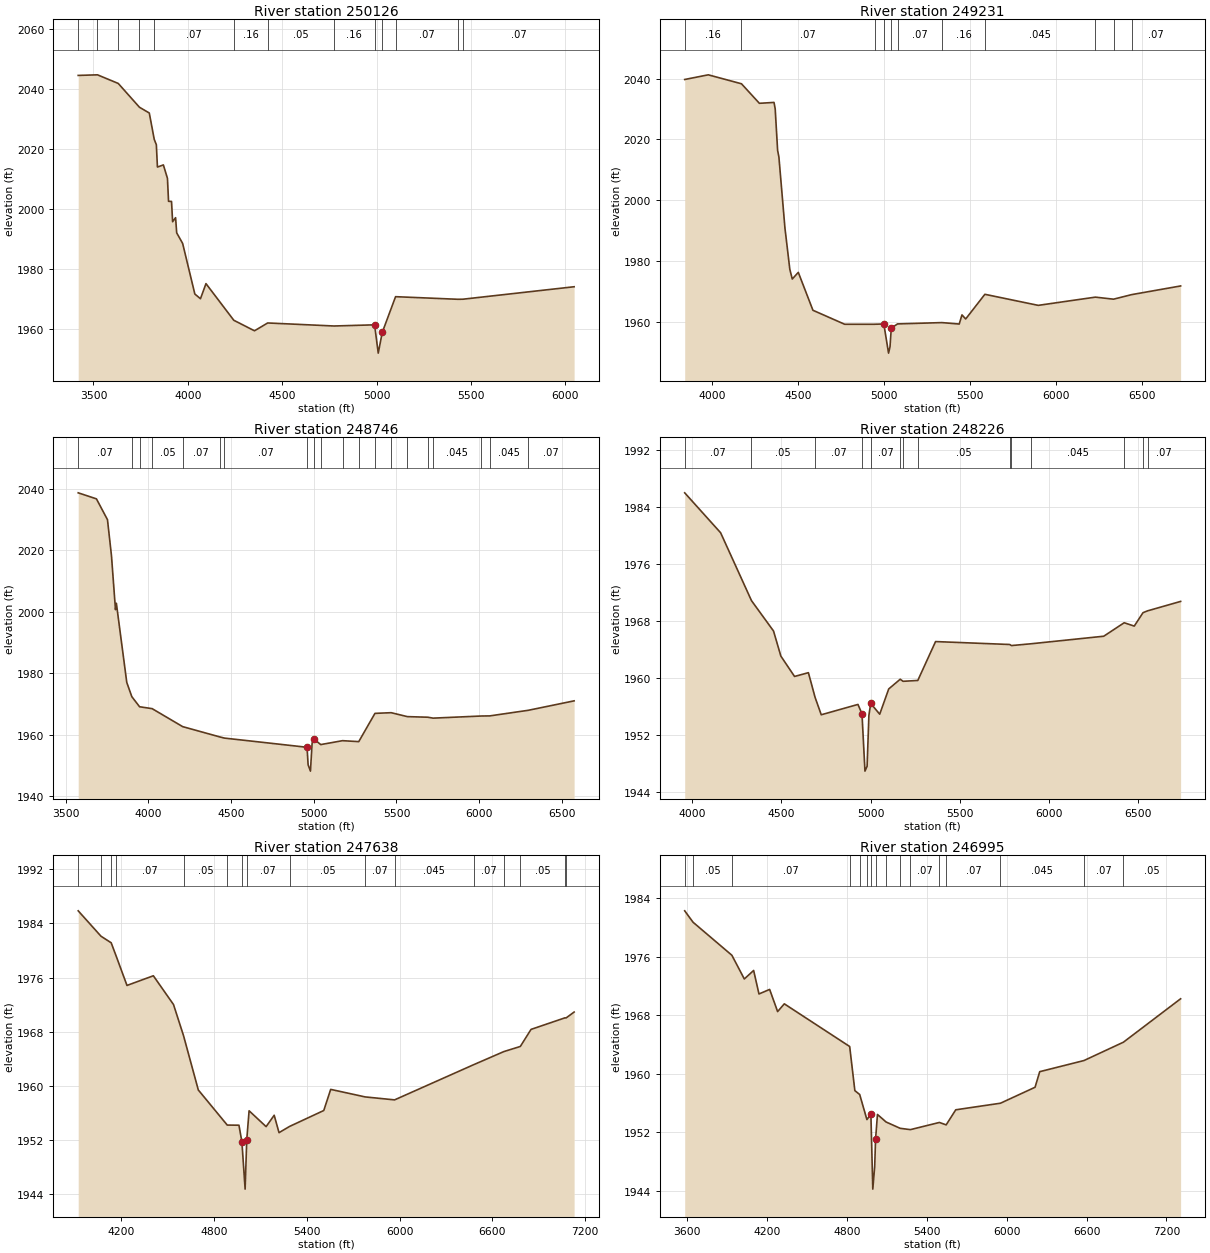
Type RM Length L Ch R = 1 ,250126  ,895,895,895
BEGIN DESCRIPTION:
Mapping XS 658aebf3
END DESCRIPTION:
XS GIS Cut Line= 4
        1480462.      6827499.34      1481232.85      6826160.78
       1481291.8      6825987.81      1481014.65      6825131.22
#Sta/Elev= 30
  3419.2 2044.49  3521.3 2044.69  3631.3 2041.82  3743.8 2033.88  3795.8 2031.97
  3822.1 2023.18  3833.2  2021.4    3839 2013.96  3870.5 2014.67  3892.1 2010.18
  3897.9 2002.53  3913.7  2002.5  3919.4 1995.74  3935.2 1997.09    3941 1992.03
  3972.6  1988.5  4037.2 1971.65    4067 1970.07  4096.2 1975.11  4243.6  1962.9
  4353.3 1959.39  4423.1    1962  4774.8 1960.99  4989.6 1961.38    5009 1951.95
  5030.2 1958.84  5100.8 1970.76  5431.4 1969.89  5457.8 1969.92  6046.9 1974.07
#Mann= 13 ,-1 , 0
  3419.2     .07       0  3521.3     .16       0  3631.3     .07       0
  3743.8     .16       0  3822.1     .07       0  4243.6     .16       0
  4423.1     .05       0  4774.8     .16       0  4989.6    .045       0
  5030.2     .16       0  5100.8     .07       0  5431.4    .045       0
  5457.8     .07       0
Bank Sta=4989.6,5030.2
XS Rating Curve= 0 ,0
Exp/Cntr=0.3,0.1

Type RM Length L Ch R = 1 ,249231  ,485,485,485
BEGIN DESCRIPTION:
Mapping XS 06d0c801
END DESCRIPTION:
XS GIS Cut Line= 4
      1480498.49      6827565.28      1481340.49      6826792.72
      1481726.77      6826102.62      1481392.58      6825212.89
#Sta/Elev= 30
  3841.9 2039.69    3979 2041.22  4172.1 2038.28  4276.2 2031.87  4361.3 2032.16
  4368.1 2030.08  4382.3 2016.37  4389.7 2014.25  4424.8 1990.94  4453.2 1977.37
  4467.4 1974.19  4502.5 1976.37  4587.6 1963.93    4772 1959.34  4945.9 1959.34
  4999.9 1959.43  5027.4 1949.86  5035.9 1951.95  5043.3  1958.1  5079.9 1959.45
  5337.4 1959.88  5438.4 1959.41  5454.3 1962.41    5476 1961.08  5587.6 1969.17
  5897.9 1965.54  6230.1 1968.24  6335.8 1967.57  6441.5 1969.07  6725.9 1971.91
#Mann= 11 ,-1 , 0
  3841.9     .16       0  4172.1     .07       0  4945.9     .05       0
  4999.9    .035       0  5043.3     .05       0  5079.9     .07       0
  5337.4     .16       0  5587.6    .045       0  6230.1     .07       0
  6335.8    .045       0  6441.5     .07       0
Bank Sta=4999.9,5043.3
XS Rating Curve= 0 ,0
Exp/Cntr=0.3,0.1

Type RM Length L Ch R = 1 ,248746  ,520,520,520
BEGIN DESCRIPTION:
Mapping XS ed4e73e2
END DESCRIPTION:
XS GIS Cut Line= 4
      1481244.99      6828060.12      1481765.84      6826771.02
      1481791.88      6826033.17      1481479.98       6825223.1
#Sta/Elev= 30
  3576.8 2038.66  3686.9  2036.7  3753.7 2029.92  3777.8 2018.23    3802 2000.67
  3807.4 2002.75  3870.3    1977  3900.7 1972.39  3947.6  1969.1  4023.4 1968.49
  4207.9 1962.64  4433.1 1959.28  4460.6 1958.91  4959.6 1955.92  4966.1 1950.21
  4980.2 1948.17  4990.2  1957.3  5000.2 1958.64  5042.4  1956.8  5174.2 1958.07
  5272.1 1957.76    5370 1966.95  5467.9 1967.17  5565.8 1965.89  5688.9  1965.7
  5721.8  1965.4  6012.7 1966.09    6064 1966.13  6296.6 1967.95  6573.5 1971.02
#Mann= 20 ,-1 , 0
  3576.8     .07       0  3900.7     .05       0  3947.6     .07       0
  4023.4     .05       0  4207.9     .07       0  4433.1     .05       0
  4460.6     .07       0  4959.6    .045       0  5000.2     .07       0
  5042.4     .07       0  5174.2     .05       0  5272.1     .07       0
    5370     .05       0  5467.9     .07       0  5565.8    .045       0
  5688.9     .05       0  5721.8    .045       0  6012.7     .07       0
    6064    .045       0  6296.6     .07       0
Bank Sta=4959.6,5000.2
XS Rating Curve= 0 ,0
Exp/Cntr=0.3,0.1

Type RM Length L Ch R = 1 ,248226  ,588,588,588
BEGIN DESCRIPTION:
Mapping XS cd055f90
END DESCRIPTION:
XS GIS Cut Line= 5
      1481952.47       6827751.9      1482195.52      6826766.68
      1482121.74      6826267.55        1481870.      6826072.24
      1481540.14      6825186.82
#Sta/Elev= 30
    3957 1985.96  4158.6 1980.36  4331.7 1970.85  4455.4 1966.59  4496.6 1963.07
  4573.4 1960.22  4651.1 1960.75  4688.6 1957.29  4723.2 1954.85  4929.2  1956.3
  4951.8 1954.99  4968.5 1946.95  4980.5 1947.63  4990.6 1954.77  5000.8 1956.44
  5051.3 1954.93  5101.8 1958.47  5166.3 1959.83  5182.5 1959.54    5265 1959.66
  5364.7 1965.11  5780.7  1964.7  5790.4 1964.55  5900.1  1964.8  6308.4 1965.86
  6423.2 1967.75  6479.7 1967.28  6528.8 1969.16  6554.7 1969.42  6739.8 1970.74
#Mann= 14 ,-1 , 0
    3957     .07       0  4331.7     .05       0  4688.6     .07       0
  4951.8    .045       0  5000.8     .07       0  5166.3     .05       0
  5182.5     .07       0    5265     .05       0  5780.7    .045       0
  5790.4     .05       0  5900.1    .045       0  6423.2     .07       0
  6528.8     .05       0  6554.7     .07       0
Bank Sta=4951.8,5000.8
XS Rating Curve= 0 ,0
Exp/Cntr=0.3,0.1

Type RM Length L Ch R = 1 ,247638  ,643,643,643
BEGIN DESCRIPTION:
Mapping XS 445167ee
END DESCRIPTION:
XS GIS Cut Line= 4
      1482842.22      6827912.49      1482759.76      6826879.53
      1482503.68      6826028.83      1481566.64      6825152.52
#Sta/Elev= 30
  3920.4 1985.87  4067.8 1982.12  4133.7 1981.15  4162.3 1979.41  4235.9 1974.85
  4406.4 1976.28  4536.8 1972.03  4601.7 1967.43  4697.3 1959.41  4884.4 1954.23
  4960.1 1954.21  4979.1 1951.76    5000 1944.77  5010.5 1952.06  5025.7 1956.34
  5135.8    1954    5188 1955.68  5219.3 1953.11  5287.6 1954.03  5508.7 1956.38
  5553.5  1959.5  5775.9 1958.39  5966.6 1957.95  6477.6 1963.14  6673.2 1965.08
    6780 1965.84  6849.4 1968.36  7069.3 1970.07  7075.4 1970.04    7128 1970.92
#Mann= 16 ,-1 , 0
  3920.4     .05       0  4067.8     .07       0  4133.7     .05       0
  4162.3     .07       0  4601.7     .05       0  4884.4     .07       0
  4979.1    .045       0  5010.5     .07       0  5287.6     .05       0
  5775.9     .07       0  5966.6    .045       0  6477.6     .07       0
  6673.2    .045       0    6780     .05       0  7069.3     .07       0
  7075.4     .05       0
Bank Sta=4979.1,5010.5
XS Rating Curve= 0 ,0
Exp/Cntr=0.3,0.1

Type RM Length L Ch R = 1 ,246995  ,1273,1273,1273
BEGIN DESCRIPTION:
Mapping XS c4ceff5a
END DESCRIPTION:
XS GIS Cut Line= 4
      1483517.28       6827995.3      1483475.62      6826818.19
      1482178.74      6825359.85      1481628.32      6825136.57
#Sta/Elev= 30
  3583.2 1982.25    3646 1980.69  3937.3 1976.18  4030.8 1972.94  4100.8  1974.1
  4140.8 1970.89  4220.9 1971.51  4280.9 1968.48    4331 1969.54  4821.8 1963.71
  4860.7 1957.68    4897 1957.15  4951.3 1953.72  4981.1 1954.48  4995.4 1944.22
  5009.6  1947.3  5016.3 1951.06  5030.5 1954.42  5095.6 1953.39  5200.9 1952.53
  5277.7 1952.35  5495.4 1953.33  5546.2    1953  5618.3 1955.06    5954 1955.96
  6213.7 1958.14  6248.8 1960.27  6580.8 1961.79  6877.3  1964.3  7306.6 1970.23
#Mann= 16 ,-1 , 0
  3583.2     .07       0    3646     .05       0  3937.3     .07       0
  4821.8     .16       0    4897     .07       0  4951.3     .16       0
  4981.1    .045       0  5016.3     .16       0  5095.6     .07       0
  5200.9     .16       0  5277.7     .07       0  5495.4     .16       0
  5546.2     .07       0    5954    .045       0  6580.8     .07       0
  6877.3     .05       0
Bank Sta=4981.1,5016.3
XS Rating Curve= 0 ,0
Exp/Cntr=0.3,0.1

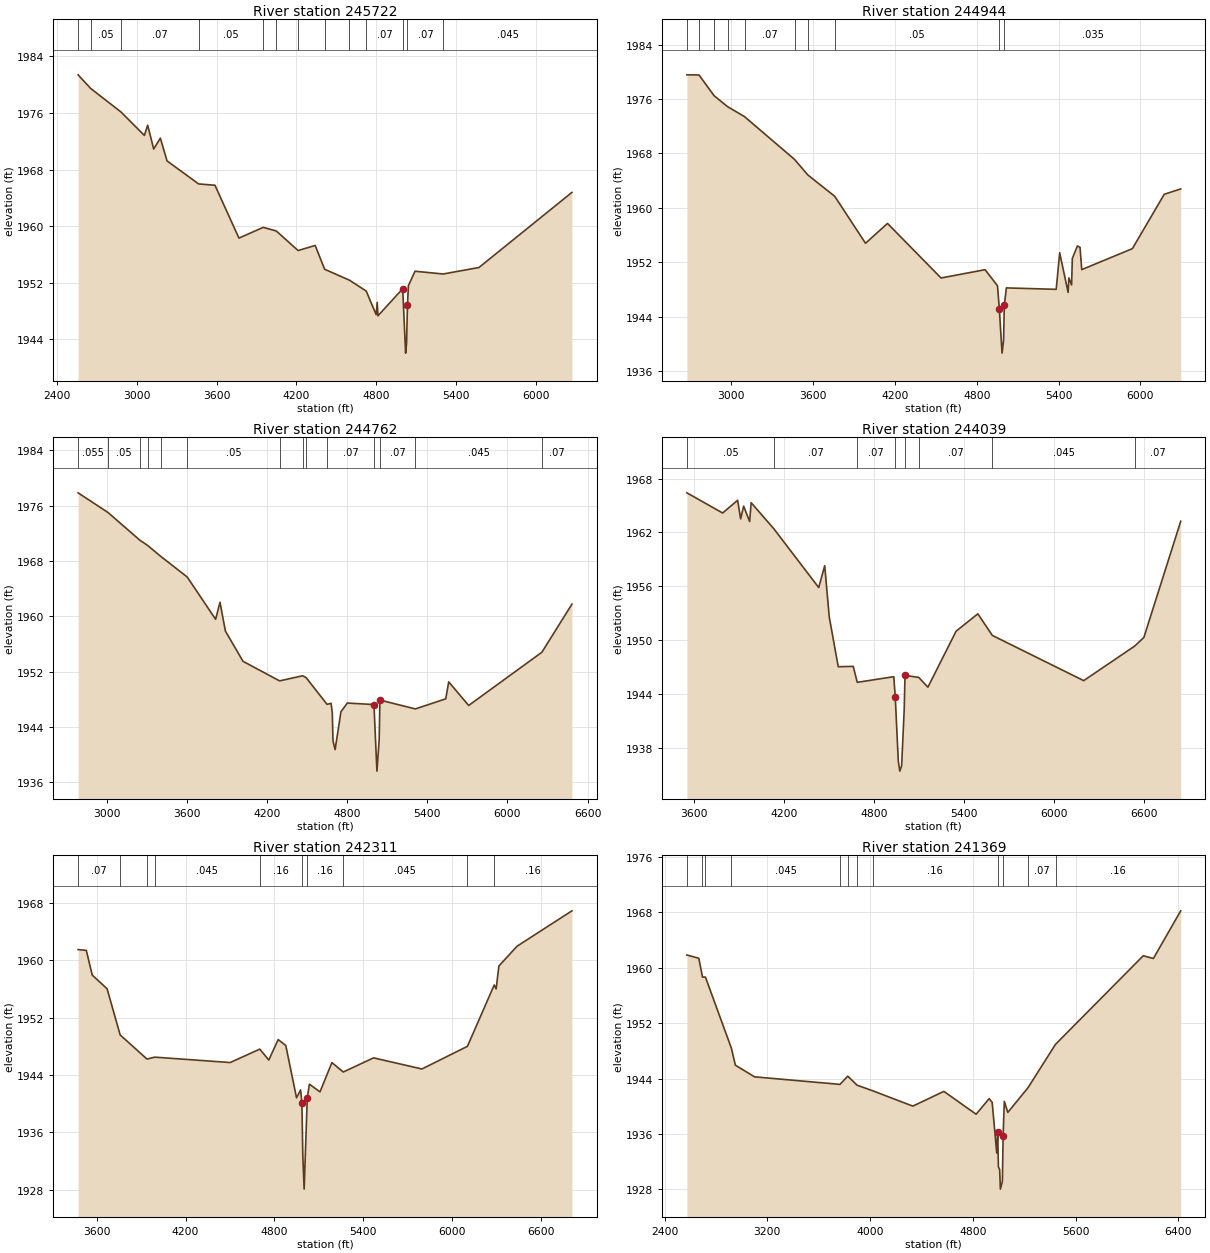
Type RM Length L Ch R = 1 ,245722  ,778,778,778
BEGIN DESCRIPTION:
Mapping XS 026d75a2
END DESCRIPTION:
XS GIS Cut Line= 4
      1483584.99      6828005.69      1483663.12      6826375.48
      1483371.45      6825620.27      1482475.65      6824719.26
#Sta/Elev= 30
  2559.3  1981.4    2654 1979.47  2881.1 1976.15  3057.6 1972.82  3082.2 1974.27
  3127.6  1970.9  3177.7 1972.44  3227.8 1969.22  3465.3 1965.96  3588.2 1965.77
  3768.4 1958.29    3951 1959.81  4048.9  1959.3  4213.1 1956.53  4341.5 1957.25
  4412.6 1953.88  4599.4 1952.33  4725.1  1950.8  4799.7 1947.46  4807.9 1949.19
  4813.2 1947.29  4999.5 1951.13  5021.3 1942.01  5028.3 1943.34  5035.4 1948.87
  5042.5 1951.57    5092  1953.6  5303.8 1953.21  5572.8 1954.13  6271.5 1964.76
#Mann= 13 ,-1 , 0
  2559.3     .07       0    2654     .05       0  2881.1     .07       0
  3465.3     .05       0    3951     .16       0  4048.9     .05       0
  4213.1     .16       0  4412.6     .07       0  4599.4     .16       0
  4725.1     .07       0  4999.5    .045       0  5035.4     .07       0
  5303.8    .045       0
Bank Sta=4999.5,5035.4
XS Rating Curve= 0 ,0
Exp/Cntr=0.3,0.1

Type RM Length L Ch R = 1 ,244944  ,182,182,182
BEGIN DESCRIPTION:
Mapping XS b2741299
END DESCRIPTION:
XS GIS Cut Line= 4
      1483637.94      6827989.43      1483809.82      6826432.12
      1484023.36      6825702.95      1484455.65       6824484.2
#Sta/Elev= 30
  2675.9 1979.57  2764.7 1979.55  2875.5 1976.49  2973.8 1974.89  3098.1 1973.42
  3464.9 1967.12  3563.1 1964.82  3759.6 1961.69  3985.2 1954.78  4146.2  1957.7
  4538.7 1949.67  4861.7 1950.89  4952.6 1948.52  4965.9 1945.15    4986 1938.61
  4997.2  1940.5  5002.4 1945.67  5017.7 1948.21  5382.8    1948  5408.4 1953.39
  5470.1 1947.55  5475.5 1949.68  5495.7 1948.65    5501 1952.54  5538.2 1954.38
  5557.5 1954.19  5570.1  1950.9  5941.4 1953.99  6174.9 1961.99  6295.6 1962.78
#Mann= 10 ,-1 , 0
  2675.9     .07       0  2764.7     .05       0  2875.5     .07       0
  2973.8     .05       0  3098.1     .07       0  3464.9     .05       0
  3563.1     .07       0  3759.6     .05       0  4965.9    .035       0
  5002.4    .035       0
Bank Sta=4965.9,5002.4
XS Rating Curve= 0 ,0
Exp/Cntr=0.3,0.1

Type RM Length L Ch R = 1 ,244762  ,723,723,723
BEGIN DESCRIPTION:
Mapping XS 7f8c9205
END DESCRIPTION:
XS GIS Cut Line= 3
      1483762.94      6828015.46      1484137.94       6825859.2
      1484809.81      6824505.04
#Sta/Elev= 30
  2782.8 1977.86  3006.7 1975.02  3244.6 1971.03  3303.5 1970.26  3402.4 1968.67
  3600.3  1965.7  3813.3 1959.58    3846 1962.04  3886.6 1957.88  4018.5 1953.51
  4292.7 1950.68  4464.9 1951.42  4490.6 1951.17  4648.4 1947.29  4678.3 1947.44
  4687.5 1946.09  4692.6 1942.07  4708.7 1940.75  4752.2 1946.21  4800.1 1947.48
  4999.6 1947.26    5022 1937.64  5038.9 1942.19  5044.4 1947.91    5310 1946.63
  5537.5 1948.09  5559.9 1950.54  5709.5 1947.13  6258.5 1954.83  6483.1 1961.77
#Mann= 14 ,-1 , 0
  2782.8    .055       0  3006.7     .05       0  3244.6     .07       0
  3303.5     .05       0  3402.4     .07       0  3600.3     .05       0
  4292.7     .16       0  4464.9     .07       0  4490.6     .16       0
  4648.4     .07       0  4999.6    .035       0  5044.4     .07       0
    5310    .045       0  6258.5     .07       0
Bank Sta=4999.6,5044.4
XS Rating Curve= 0 ,0
Exp/Cntr=0.3,0.1

Type RM Length L Ch R = 1 ,244039  ,1728,1728,1728
BEGIN DESCRIPTION:
Mapping XS 744429d5
END DESCRIPTION:
XS GIS Cut Line= 3
      1484585.86      6827775.86      1484643.15      6826348.78
      1485174.29      6824562.71
#Sta/Elev= 30
  3553.6 1966.42  3791.6 1964.17  3891.7 1965.59  3911.7 1963.52  3931.8 1964.94
  3971.8 1963.22  3981.8 1965.32  4132.2 1962.43  4432.2 1955.86  4472.2  1958.3
  4502.2  1952.6  4562.3 1947.03  4662.3 1947.07    4689 1945.29  4932.6 1945.92
  4942.6  1943.6  4962.6 1936.52  4972.6 1935.39  4984.8 1935.98  5002.1 1942.29
  5007.3 1946.06  5098.8 1945.84    5160 1944.75  5347.8 1950.99  5492.8 1952.93
  5589.6 1950.52  6198.4 1945.48  6538.1 1949.33  6599.7  1950.3  6845.2 1963.25
#Mann= 8 ,-1 , 0
  3553.6     .05       0  4132.2     .07       0    4689     .07       0
  4942.6    .035       0  5007.3     .05       0  5098.8     .07       0
  5589.6    .045       0  6538.1     .07       0
Bank Sta=4942.6,5007.3
XS Rating Curve= 0 ,0
Exp/Cntr=0.3,0.1

Type RM Length L Ch R = 1 ,242311  ,942,942,942
BEGIN DESCRIPTION:
Mapping XS 9f3178a9
END DESCRIPTION:
XS GIS Cut Line= 4
      1485770.54      6827313.34      1485846.93      6826035.52
      1485194.15      6825021.64      1485325.97      6824182.17
#Sta/Elev= 30
  3474.3  1961.5  3529.7 1961.38  3569.8 1957.94    3670 1956.04  3758.4  1949.6
  3939.8 1946.23    3992  1946.5  4501.5 1945.75  4701.6 1947.62  4762.3  1946.1
  4825.7 1948.95  4877.2 1948.13  4949.8 1940.83  4977.4 1941.93  4986.1 1940.07
  4992.1 1932.86  5001.2  1928.1  5022.4 1940.85  5036.9 1942.73  5108.3 1941.66
  5188.8 1945.74  5265.5 1944.43  5470.1  1946.4  5796.9 1944.85  6104.2 1948.01
  6285.1 1956.56    6298 1956.01  6316.7 1959.21  6439.7 1961.97    6810  1966.9
#Mann= 10 ,-1 , 0
  3474.3     .07       0  3758.4    .045       0  3939.8     .07       0
    3992    .045       0  4701.6     .16       0  4986.1    .045       0
  5022.4     .16       0  5265.5    .045       0  6104.2     .07       0
  6285.1     .16       0
Bank Sta=4986.1,5022.4
XS Rating Curve= 0 ,0
Exp/Cntr=0.3,0.1

Type RM Length L Ch R = 1 ,241369  ,596,596,596
BEGIN DESCRIPTION:
Mapping XS aa65cbe5
END DESCRIPTION:
XS GIS Cut Line= 3
      1485853.86      6827375.84      1486493.63      6825464.34
      1485528.23      6823911.72
#Sta/Elev= 30
  2573.8 1961.85  2666.4 1961.38  2695.1 1958.66    2718 1958.66  2920.2 1948.38
  2951.1 1945.93  3100.7 1944.25  3765.4 1943.16  3825.9 1944.35  3898.8 1943.04
  4019.4 1942.24  4332.6 1940.02    4574 1942.15  4825.1 1938.85  4926.7  1941.1
  4950.2 1940.56  4985.6 1933.25  4992.8  1936.3  4998.7 1931.25  5008.1 1930.88
    5014 1928.03  5029.4 1929.11  5035.3 1935.73  5044.5 1940.71  5071.9 1939.11
  5228.6 1942.67  5443.3 1948.95  6126.1 1961.74  6205.2 1961.35  6417.8 1968.23
#Mann= 12 ,-1 , 0
  2573.8     .07       0  2695.1     .05       0    2718     .07       0
  2920.2    .045       0  3765.4     .07       0  3825.9     .16       0
  3898.8     .07       0  4019.4     .16       0  4992.8    .045       0
  5035.3     .16       0  5228.6     .07       0  5443.3     .16       0
Bank Sta=4992.8,5035.3
XS Rating Curve= 0 ,0
Exp/Cntr=0.3,0.1

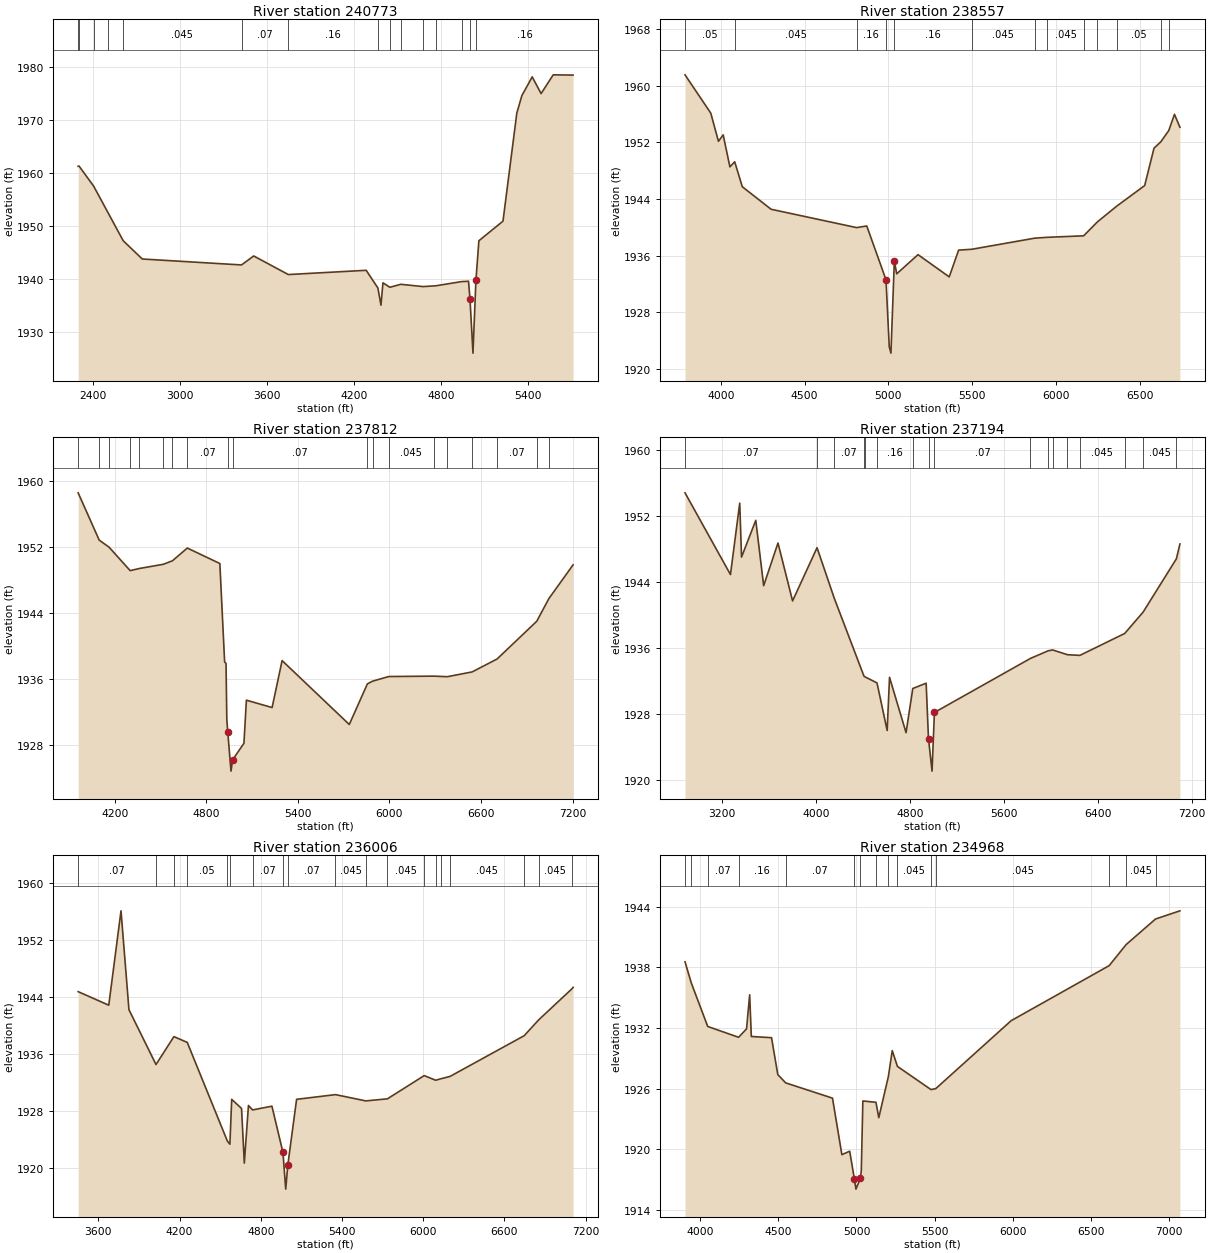
Type RM Length L Ch R = 1 ,240773  ,2216,2216,2216
BEGIN DESCRIPTION:
Mapping XS 584736ca
END DESCRIPTION:
XS GIS Cut Line= 3
      1485951.09      6827368.87      1486680.26      6825098.02
      1486888.39      6824092.07
#Sta/Elev= 30
  2297.9 1961.31  2303.9 1961.36  2404.7 1957.57  2506.7 1952.42  2608.6 1947.28
  2739.9 1943.84  3424.3 1942.72  3508.2 1944.41  3746.9 1940.91  4283.9 1941.71
  4364.5 1938.37  4385.7 1935.14  4399.4 1939.35    4447 1938.51  4522.3 1939.07
  4675.8 1938.64    4764 1938.79  4941.6 1939.58  4989.3 1939.65  4999.5  1936.3
    5020  1926.1  5040.4 1939.85  5060.8 1947.28  5226.9 1950.97  5322.3 1971.34
  5356.9 1974.62  5428.4 1978.16  5489.7 1975.02  5573.3 1978.55  5710.2  1978.5
#Mann= 15 ,-1 , 0
  2297.9     .07       0  2303.9     .05       0  2404.7     .07       0
  2506.7     .05       0  2608.6    .045       0  3424.3     .07       0
  3746.9     .16       0  4364.5    .045       0    4447     .16       0
  4522.3    .045       0  4675.8     .16       0    4764    .045       0
  4941.6     .16       0  4999.5    .045       0  5040.4     .16       0
Bank Sta=4999.5,5040.4
XS Rating Curve= 0 ,0
Exp/Cntr=0.3,0.1

Type RM Length L Ch R = 1 ,238557  ,745,745,745
BEGIN DESCRIPTION:
Mapping XS c282e67e
END DESCRIPTION:
XS GIS Cut Line= 4
      1486035.03      6827442.89      1486189.06      6827113.54
        1487430.        6826163.      1487782.81      6825196.85
#Sta/Elev= 30
  3785.5 1961.54  3939.4 1956.13  3985.1 1952.15  4013.4 1953.06  4053.6 1948.54
  4082.2 1949.26  4127.7 1945.73  4299.7 1942.55  4810.1 1939.96  4870.9 1940.19
  4985.7 1932.59  5005.1 1923.12  5015.2 1922.23  5035.4 1935.26  5049.5 1933.43
  5176.9 1936.14  5363.2    1933  5419.4 1936.78  5498.3  1936.9    5874 1938.47
  5949.8 1938.59  6165.8  1938.8  6248.5 1940.78  6364.6 1943.01  6530.3  1945.9
    6586 1951.18  6626.4 1952.07  6674.3 1953.67  6708.2 1955.96  6740.8 1954.14
#Mann= 13 ,-1 , 0
  3785.5     .05       0  4082.2    .045       0  4810.1     .16       0
  4985.7    .045       0  5035.4     .16       0  5498.3    .045       0
    5874     .07       0  5949.8    .045       0  6165.8     .07       0
  6248.5    .045       0  6364.6     .05       0  6626.4    .045       0
  6674.3     .16       0
Bank Sta=4985.7,5035.4
XS Rating Curve= 0 ,0
Exp/Cntr=0.3,0.1

Type RM Length L Ch R = 1 ,237812  ,618,618,618
BEGIN DESCRIPTION:
Mapping XS 6095aa73
END DESCRIPTION:
XS GIS Cut Line= 3
      1486185.21       6827510.2      1487212.96      6827204.65
      1488260.46      6825303.88
#Sta/Elev= 30
  3961.1 1958.55    4099 1952.83  4163.5 1951.98  4301.8 1949.14  4362.8  1949.4
  4519.8 1949.91  4578.8 1950.33  4676.2 1951.87  4889.4    1950  4920.7  1938.1
  4929.9 1937.92  4935.1 1931.08  4941.5 1929.57  4962.4 1924.89  4973.5 1926.27
  5047.2 1928.26  5063.3 1933.47  5231.8 1932.58  5297.2 1938.26  5737.4 1930.53
  5855.9 1935.44    5890 1935.77  5995.8 1936.33  6290.9 1936.38  6379.5 1936.31
  6542.5 1936.89  6705.6 1938.45  6965.8 1943.02  7044.8 1945.75  7203.6 1949.84
#Mann= 19 ,-1 , 0
  3961.1     .05       0    4099     .07       0  4163.5     .05       0
  4301.8     .07       0  4362.8     .05       0  4519.8     .07       0
  4578.8     .05       0  4676.2     .07       0  4941.5    .045       0
  4973.5     .07       0  5855.9    .045       0    5890     .07       0
  5995.8    .045       0  6290.9     .07       0  6379.5    .045       0
  6542.5     .07       0  6705.6     .07       0  6965.8    .045       0
  7044.8     .07       0
Bank Sta=4941.5,4973.5
XS Rating Curve= 0 ,0
Exp/Cntr=0.3,0.1

Type RM Length L Ch R = 1 ,237194  ,1188,1188,1188
BEGIN DESCRIPTION:
Mapping XS 30b790fd
END DESCRIPTION:
XS GIS Cut Line= 5
      1486852.34       6829187.9      1487756.36      6827751.09
      1487684.68      6827068.63      1488129.62      6825781.04
      1488365.71       6825378.3
#Sta/Elev= 30
  2887.2 1954.84  3274.1 1944.92    3353 1953.59  3368.3 1947.04  3489.6  1951.5
  3556.7 1943.57  3678.7 1948.75  3802.8 1941.72  4011.1 1948.18  4157.8 1942.04
  4410.8 1932.58  4423.3 1932.47  4521.6 1931.77    4608 1925.99  4628.1 1932.45
  4768.8 1925.73  4826.2 1931.09  4939.8 1931.73  4959.9 1924.98  4990.1 1921.06
  5010.2 1928.18  5827.8 1934.74  5977.6 1935.66  6016.4 1935.77    6143 1935.19
  6248.4 1935.11  6630.3 1937.77  6786.7 1940.36  7069.9 1946.83  7100.1 1948.63
#Mann= 17 ,-1 , 0
  2887.2     .07       0  4011.1     .05       0  4157.8     .07       0
  4410.8     .05       0  4423.3     .07       0  4521.6     .16       0
  4826.2     .07       0  4959.9    .045       0  5010.2     .07       0
  5827.8    .045       0  5977.6     .07       0  6016.4    .045       0
    6143     .07       0  6248.4    .045       0  6630.3     .07       0
  6786.7    .045       0  7069.9     .07       0
Bank Sta=4959.9,5010.2
XS Rating Curve= 0 ,0
Exp/Cntr=0.3,0.1

Type RM Length L Ch R = 1 ,236006  ,1038,1038,1038
BEGIN DESCRIPTION:
Mapping XS 58598fb5
END DESCRIPTION:
XS GIS Cut Line= 6
      1488122.67      6828913.03      1488199.07      6828142.15
      1488350.22      6827383.01      1488608.29      6827217.93
      1488261.57      6825857.43      1488393.42      6825482.69
#Sta/Elev= 30
  3451.3 1944.73  3677.4 1942.83  3767.9 1956.07  3826.5  1942.2  4026.5  1934.5
  4158.7 1938.42  4257.2 1937.61  4553.5 1923.77  4572.3 1923.32  4585.6 1929.62
  4658.4 1928.34  4678.8 1920.67  4709.4 1928.76  4739.7 1928.13  4882.8 1928.66
  4964.3 1922.16  4984.7 1917.02  5000.4 1920.43    5065 1929.62  5352.3 1930.28
  5576.5  1929.4    5736 1929.69    6008 1932.95  6092.2  1932.3    6130  1932.5
  6198.1 1932.83  6746.5 1938.55  6853.5 1940.77  7100.4 1945.15  7107.6 1945.33
#Mann= 19 ,-1 , 0
  3451.3     .07       0  4026.5     .05       0  4158.7     .07       0
  4257.2     .05       0  4553.5     .07       0  4572.3     .16       0
  4739.7     .07       0  4964.3    .045       0  5000.4     .07       0
  5352.3    .045       0  5576.5     .07       0    5736    .045       0
    6008     .07       0  6092.2    .045       0    6130     .07       0
  6198.1    .045       0  6746.5     .07       0  6853.5    .045       0
  7100.4     .07       0
#XS Ineff= 2 , 0
       0    4900    1927               0
Permanent Ineff=
       T       F
Bank Sta=4964.3,5000.4
XS Rating Curve= 0 ,0
Exp/Cntr=0.3,0.1

Type RM Length L Ch R = 1 ,234968  ,794,794,794
BEGIN DESCRIPTION:
Mapping XS 51a59f51
END DESCRIPTION:
XS GIS Cut Line= 4
      1489062.38      6828331.63      1489108.79      6827225.48
      1488303.23      6825829.65      1488490.73      6825419.94
#Sta/Elev= 30
    3902 1938.54  3942.6 1936.43  4047.5 1932.14    4245 1931.07    4296  1931.9
    4316 1935.27  4326.7 1931.15  4456.1 1931.03  4496.2 1927.38  4546.7 1926.56
  4846.5 1925.05  4906.5 1919.46  4956.6  1919.8  4986.6 1917.05  4996.6 1916.05
  5025.1 1917.11  5030.9 1917.87  5040.9 1924.77  5124.7 1924.64  5142.9 1923.12
  5204.3 1927.19  5229.1 1929.75  5262.4 1928.19  5476.9  1925.9  5507.7 1925.99
  5990.2 1932.71  6618.4 1938.16  6726.8 1940.24  6914.9 1942.77  7071.3 1943.58
#Mann= 15 ,-1 , 0
    3902     .07       0  3942.6     .05       0  4047.5     .07       0
    4245     .16       0  4546.7     .07       0  4986.6    .045       0
  5025.1     .07       0  5124.7     .16       0  5204.3     .07       0
  5262.4    .045       0  5476.9     .07       0  5507.7    .045       0
  6618.4     .07       0  6726.8    .045       0  6914.9     .07       0
Bank Sta=4986.6,5025.1
XS Rating Curve= 0 ,0
Exp/Cntr=0.3,0.1

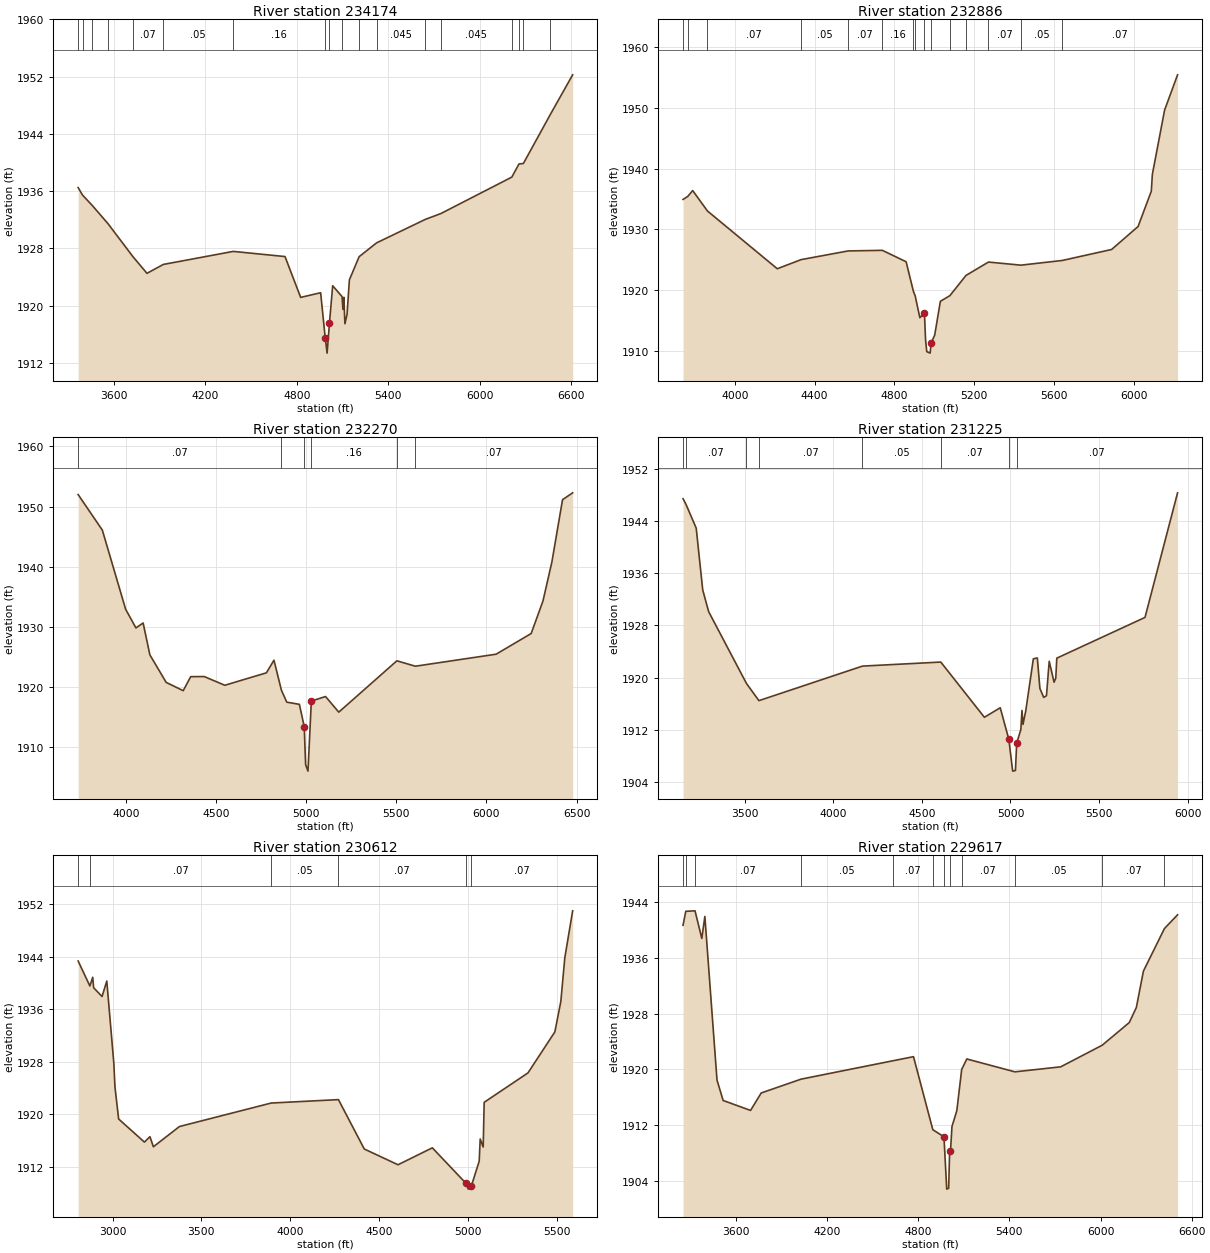
Type RM Length L Ch R = 1 ,234174  ,1288,1288,1288
BEGIN DESCRIPTION:
Mapping XS 8656c4c3
END DESCRIPTION:
XS GIS Cut Line= 4
      1489949.08      6828051.91      1489546.29      6826676.87
      1488941.62       6826301.7      1488637.09      6825241.18
#Sta/Elev= 30
  3363.9  1936.5  3392.8 1935.45  3456.8    1934  3559.7 1931.47  3723.7 1926.86
    3816 1924.53  3923.2 1925.77  4382.6 1927.59  4722.6 1926.87  4825.3 1921.17
  4956.5 1921.82  4986.5 1915.56    4999 1913.39  5014.3 1917.56  5035.6  1922.8
  5097.2 1921.28  5102.9  1919.5  5108.8 1921.18    5116 1917.49  5130.1 1918.81
  5145.4 1923.62  5209.3 1926.85  5323.8 1928.78  5643.1 1932.05  5745.8 1932.87
  6212.1 1937.96  6259.3  1939.8    6288 1939.86  6464.7 1946.69  6611.7 1952.24
#Mann= 18 ,-1 , 0
  3363.9     .07       0  3392.8     .05       0  3456.8     .07       0
  3559.7     .05       0  3723.7     .07       0  3923.2     .05       0
  4382.6     .16       0  4986.5    .045       0  5014.3     .16       0
  5097.2     .16       0  5209.3     .07       0  5323.8    .045       0
  5643.1     .07       0  5745.8    .045       0  6212.1     .05       0
  6259.3    .045       0    6288     .07       0  6464.7     .16       0
Bank Sta=4986.5,5014.3
XS Rating Curve= 0 ,0
Exp/Cntr=0.3,0.1

Type RM Length L Ch R = 1 ,232886  ,616,616,616
BEGIN DESCRIPTION:
Mapping XS d4be6eb5
END DESCRIPTION:
XS GIS Cut Line= 4
      1490031.88      6828033.31      1489813.13      6827246.84
      1490203.76      6826397.88      1490052.71      6825684.34
#Sta/Elev= 30
  3739.8 1934.93  3763.4 1935.42  3788.1 1936.39  3862.4 1933.02  4212.4 1923.52
  4331.9 1925.02  4567.7 1926.45  4739.3 1926.55  4858.6 1924.67  4895.3 1919.78
    4904 1919.06  4927.5 1915.47  4950.5 1916.19    4956  1911.9  4962.1 1909.88
    4979 1909.63  4984.5 1911.34  5001.9 1912.59  5030.4 1918.16  5078.1 1919.09
  5158.9 1922.42  5271.5 1924.62  5434.1 1924.11  5641.5 1924.88  5889.2 1926.69
    6022 1930.47  6088.4  1936.3  6093.6 1939.05  6154.9 1949.63    6220 1955.44
#Mann= 15 ,-1 , 0
  3739.8     .07       0  3763.4     .05       0  3862.4     .07       0
  4331.9     .05       0  4567.7     .07       0  4739.3     .16       0
  4895.3     .07       0    4904     .16       0  4950.5    .045       0
  4984.5     .16       0  5078.1     .07       0  5158.9     .16       0
  5271.5     .07       0  5434.1     .05       0  5641.5     .07       0
Bank Sta=4950.5,4984.5
XS Rating Curve= 0 ,0
Exp/Cntr=0.3,0.1

Type RM Length L Ch R = 1 ,232270  ,1045,1045,1045
BEGIN DESCRIPTION:
Mapping XS 0982a531
END DESCRIPTION:
XS GIS Cut Line= 4
      1490849.58      6828293.68      1490469.38      6827090.59
      1490271.46      6826382.26      1490115.22       6825653.1
#Sta/Elev= 30
  3735.8 1951.99    3870 1946.08  3999.3 1932.91  4056.4 1929.81  4096.3 1930.63
  4133.8 1925.32  4224.2 1920.75  4318.6 1919.37  4360.1  1921.7  4435.2 1921.72
  4549.3 1920.27    4780 1922.34    4822 1924.44  4863.2 1919.46    4893 1917.46
  4962.9  1917.1  4989.8 1913.41  4997.5 1907.07  5010.6 1905.99  5029.3 1917.64
    5108  1918.4  5181.5  1915.8  5503.8 1924.34  5606.3 1923.44  6054.4 1925.44
  6248.7 1928.88  6313.9 1934.28  6363.4 1940.76  6422.6 1951.14  6478.7 1952.28
#Mann= 6 ,-1 , 0
  3735.8     .07       0  4863.2     .16       0  4989.8    .045       0
  5029.3     .16       0  5503.8     .05       0  5606.3     .07       0
Bank Sta=4989.8,5029.3
XS Rating Curve= 0 ,0
Exp/Cntr=0.3,0.1

Type RM Length L Ch R = 1 ,231225  ,613,613,613
BEGIN DESCRIPTION:
Mapping XS 8d5d4acd
END DESCRIPTION:
XS GIS Cut Line= 4
      1491276.68      6828038.52      1490932.92      6826611.42
      1490302.71      6826236.42      1490177.72      6825658.34
#Sta/Elev= 30
  3150.8 1947.43  3168.2 1946.52  3225.2 1942.91    3262 1933.43  3295.3 1930.11
  3508.5 1919.11  3579.3 1916.45    4164 1921.75  4606.4 1922.37  4852.6  1913.9
  4942.1 1915.36  4990.8  1910.5  5012.3 1905.64  5027.9 1905.74  5035.2 1909.97
  5058.5    1912  5064.9 1914.95  5070.7 1912.81  5086.3  1914.9  5129.1 1922.87
  5151.6    1923  5166.1 1918.32  5187.5 1916.95  5203.1  1917.2  5218.7 1922.49
    5246 1919.28  5255.7 1919.89  5261.5 1922.97  5759.7 1929.22  5943.5 1948.33
#Mann= 8 ,-1 , 0
  3150.8     .05       0  3168.2     .07       0  3508.5     .05       0
  3579.3     .07       0    4164     .05       0  4606.4     .07       0
  4990.8    .045       0  5035.2     .07       0
Bank Sta=4990.8,5035.2
XS Rating Curve= 0 ,0
Exp/Cntr=0.3,0.1

Type RM Length L Ch R = 1 ,230612  ,995,995,995
BEGIN DESCRIPTION:
Mapping XS 9c8ab12c
END DESCRIPTION:
XS GIS Cut Line= 4
      1491392.83      6827987.81      1491006.55      6826577.22
      1490759.16       6825895.8      1490225.27      6825631.03
#Sta/Elev= 30
  2806.2 1943.35  2872.3 1939.54  2888.2 1940.87  2893.4 1939.28  2940.8 1937.94
  2967.5  1940.3  3007.2 1927.73  3013.4 1924.18  3034.1 1919.29  3179.3 1915.77
  3210.4  1916.6  3229.7 1915.06  3376.2 1918.14  3892.9 1921.72  4271.3 1922.24
  4416.8 1914.72  4606.6 1912.32  4799.8  1914.9  4988.6 1909.51  5001.9 1908.61
  5018.8 1909.04  5063.6 1912.86  5069.2 1916.25    5086 1915.02  5091.6 1921.83
  5338.2 1926.31  5489.4 1932.55  5523.1  1937.2  5545.5 1943.86  5589.6 1950.99
#Mann= 6 ,-1 , 0
  2806.2     .05       0  2872.3     .07       0  3892.9     .05       0
  4271.3     .07       0  4988.6    .045       0  5018.8     .07       0
Bank Sta=4988.6,5018.8
XS Rating Curve= 0 ,0
Exp/Cntr=0.3,0.1

Type RM Length L Ch R = 1 ,229617  ,614,614,614
BEGIN DESCRIPTION:
Mapping XS c2f41728
END DESCRIPTION:
XS GIS Cut Line= 4
      1491537.09      6827981.26      1491406.88      6826246.84
      1491208.96       6825783.3      1490283.18      6825372.41
#Sta/Elev= 30
  3251.1 1940.71  3269.1 1942.72    3330 1942.79  3374.7 1938.82  3394.8 1941.98
  3474.7 1918.45  3515.1 1915.51  3695.6 1914.08  3765.8 1916.59  4028.4 1918.58
  4632.5 1921.22  4768.6 1921.81  4895.7 1911.31  4969.2 1910.28  4987.3 1902.76
    5000 1902.88  5006.7  1908.3  5012.1 1908.19  5021.8 1911.76  5053.9 1914.05
  5085.9 1919.98  5119.6 1921.48  5436.1 1919.63  5737.8 1920.35  6011.2 1923.46
  6189.4 1926.72    6236 1928.89  6282.5 1934.12  6420.9 1940.24  6507.3 1942.22
#Mann= 12 ,-1 , 0
  3251.1     .07       0  3269.1     .05       0    3330     .07       0
  4028.4     .05       0  4632.5     .07       0  4895.7     .16       0
  4969.2    .045       0  5006.7     .16       0  5085.9     .07       0
  5436.1     .05       0  6011.2     .07       0  6420.9     .05       0
Bank Sta=4969.2,5006.7
XS Rating Curve= 0 ,0
Exp/Cntr=0.3,0.1