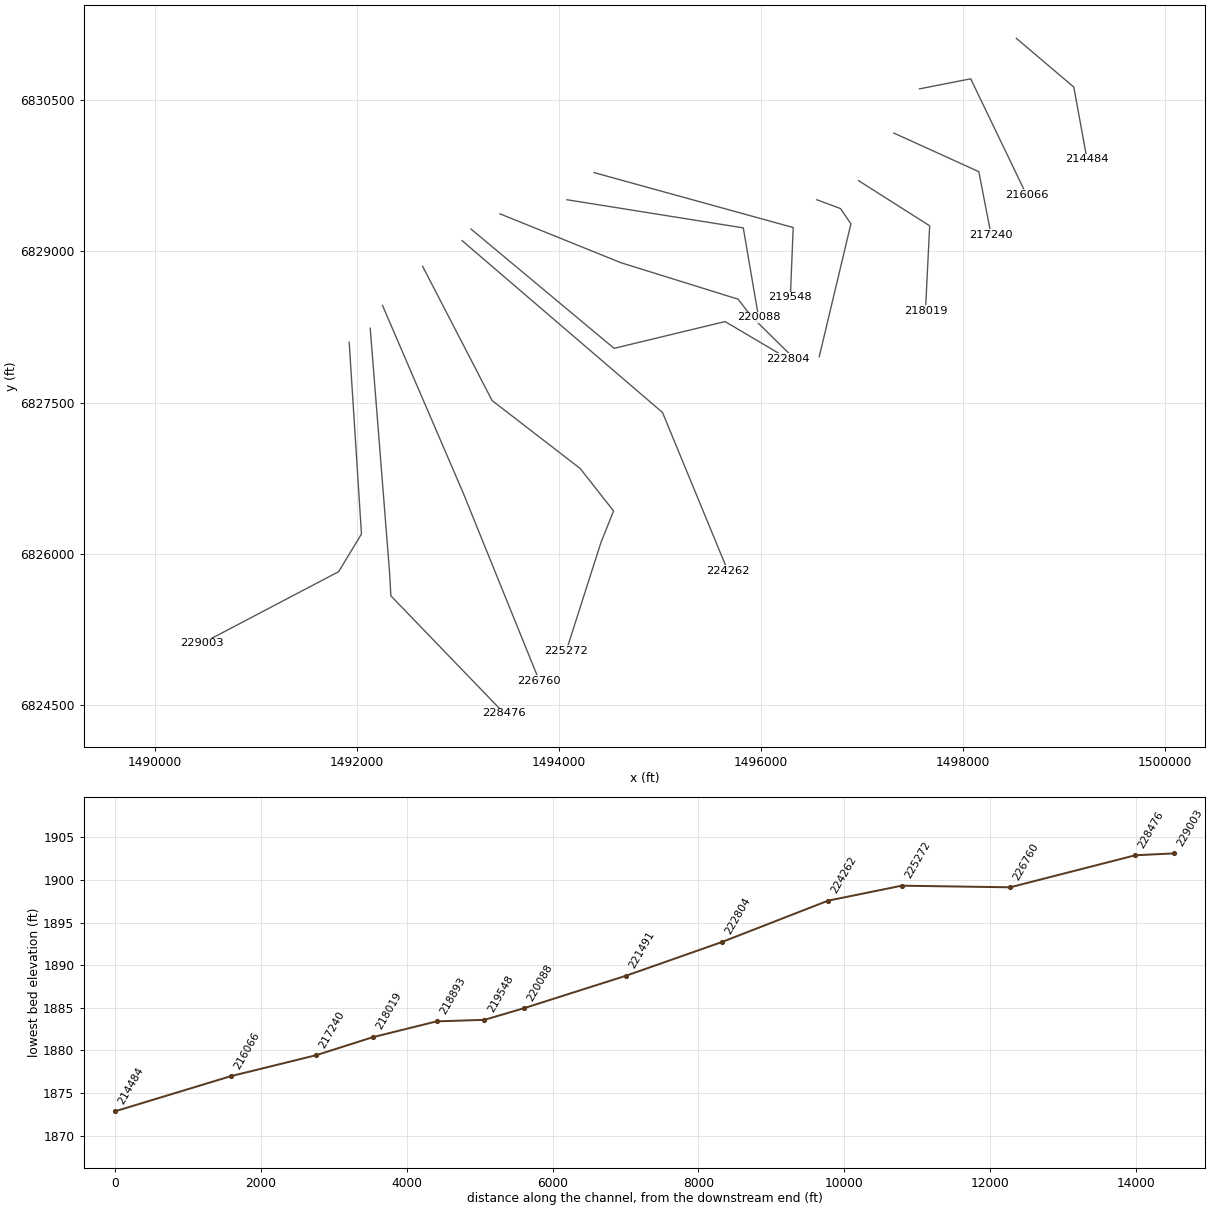
HEC-RAS study MULBERRY CREEK.prj: MULBERRY CREEK Base Level Engineering

--- MULBERRY CREEK.g01 (geometry) --- (continued)

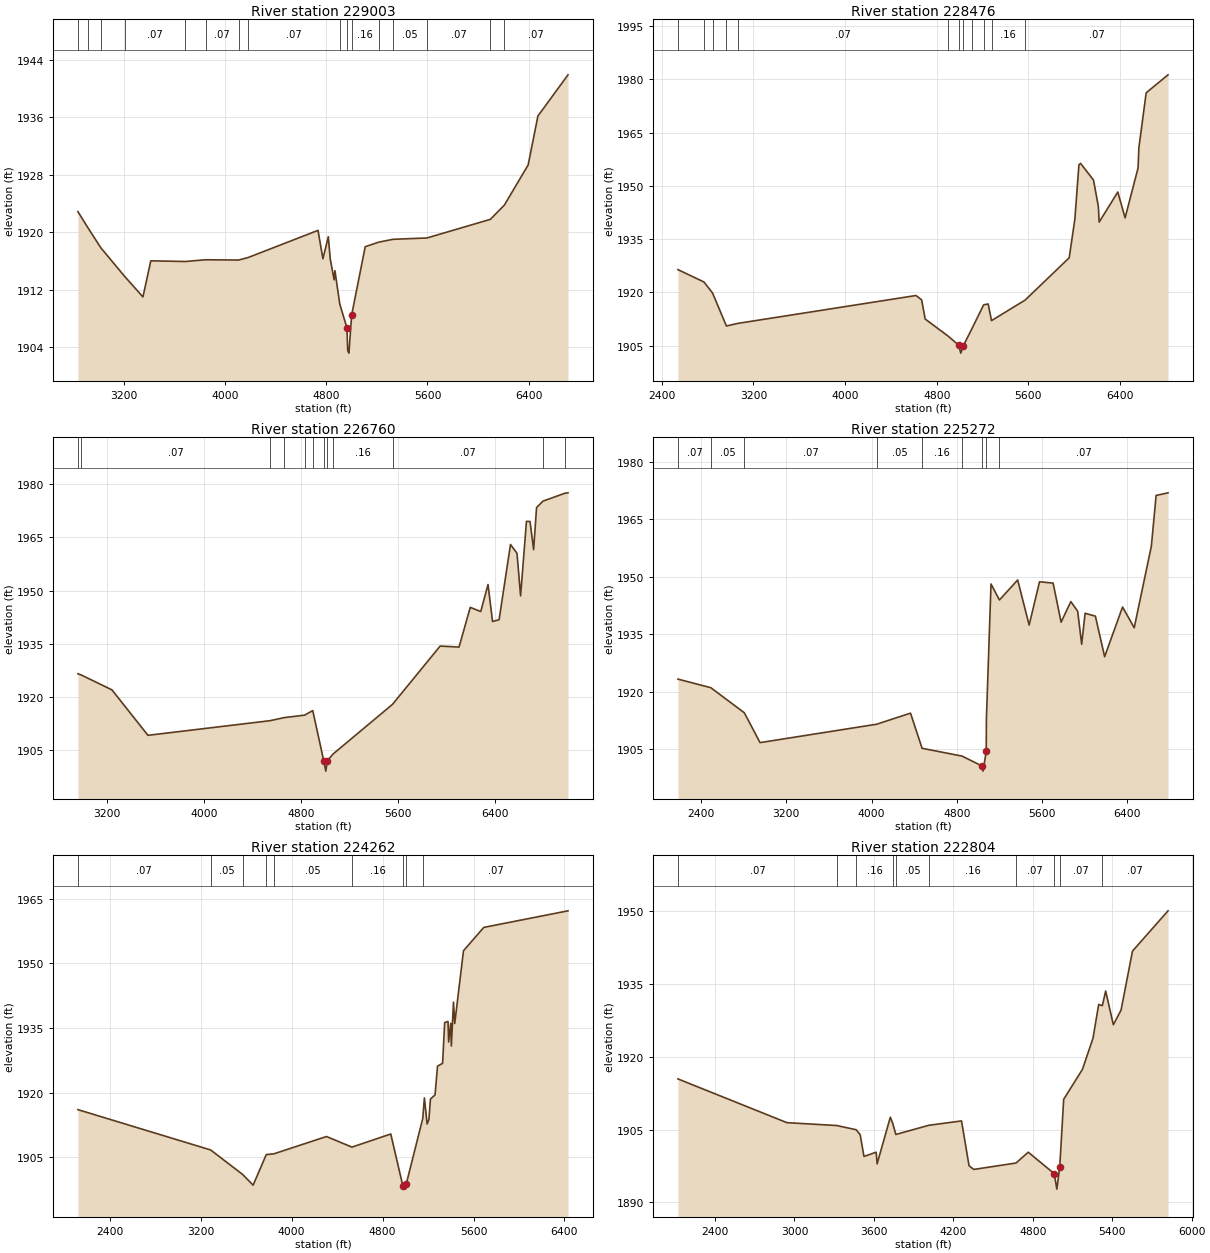
Type RM Length L Ch R = 1 ,229003  ,527,527,527
BEGIN DESCRIPTION:
Mapping XS 90adaeb6
END DESCRIPTION:
XS GIS Cut Line= 4
      1491923.48      6828100.66      1492045.01      6826199.64
      1491819.32      6825826.37      1490465.18      6825114.59
#Sta/Elev= 30
    2839 1922.86  2922.1  1920.5    3020 1917.82  3207.6 1913.84  3352.7 1910.97
  3414.6    1916  3688.7 1915.91  3847.3 1916.15  4107.7 1916.11  4184.8 1916.47
  4735.5 1920.25    4774 1916.28  4816.7 1919.36  4832.2 1916.23  4862.7 1913.35
    4869 1914.63  4907.1 1909.99  4964.1 1906.63  4969.9 1903.47  4979.5 1903.13
  5000.9 1908.42  5108.1 1917.97  5215.8 1918.61  5325.9    1919    5596 1919.19
  6097.3 1921.79  6207.5 1923.78  6395.2 1929.37  6472.1 1936.19  6709.9 1941.94
#Mann= 16 ,-1 , 0
    2839     .16       0  2922.1     .07       0    3020     .05       0
  3207.6     .07       0  3688.7     .05       0  3847.3     .07       0
  4107.7     .05       0  4184.8     .07       0  4907.1     .16       0
  4964.1    .045       0  5000.9     .16       0  5215.8     .07       0
  5325.9     .05       0    5596     .07       0  6097.3     .05       0
  6207.5     .07       0
Bank Sta=4964.1,5000.9
XS Rating Curve= 0 ,0
Exp/Cntr=0.3,0.1

Type RM Length L Ch R = 1 ,228476  ,1716,1716,1716
BEGIN DESCRIPTION:
Mapping XS 646a509f
END DESCRIPTION:
XS GIS Cut Line= 4
      1492131.82      6828239.56      1492322.79      6825826.37
      1492336.41      6825586.66      1493458.53      6824421.59
#Sta/Elev= 30
  2541.1 1926.42  2768.6 1922.93  2843.1 1919.84  2964.3 1910.55  3063.7 1911.28
  4619.1 1919.13  4668.6 1917.92  4699.4 1912.51  4895.7  1907.8  4990.3 1905.22
  5010.3 1902.91  5030.3 1904.85    5110 1909.96    5210 1916.51  5249.5 1916.75
  5278.5 1912.06  5572.6 1917.86  5956.7 1929.75  6006.1  1940.6  6041.6  1955.9
  6055.8 1956.34    6169 1951.63  6211.4 1944.17  6218.4  1939.8  6380.9 1948.26
  6444.8 1940.99  6557.9 1955.05  6564.9 1960.68  6628.7  1976.2  6819.5 1981.26
#Mann= 12 ,-1 , 0
  2541.1     .07       0  2768.6     .05       0  2843.1     .07       0
  2964.3     .05       0  3063.7     .07       0  4895.7     .05       0
  4990.3    .035       0  5030.3     .05       0    5110     .16       0
    5210     .07       0  5278.5     .16       0  5572.6     .07       0
Bank Sta=4990.3,5030.3
XS Rating Curve= 0 ,0
Exp/Cntr=0.3,0.1

Type RM Length L Ch R = 1 ,226760  ,1488,1488,1488
BEGIN DESCRIPTION:
Mapping XS 683a6225
END DESCRIPTION:
XS GIS Cut Line= 3
      1492253.34      6828465.26      1493051.95      6826607.62
      1493806.81      6824742.19
#Sta/Elev= 30
  2963.2 1926.58  2991.5 1926.23  3243.2 1922.05  3539.8 1909.24  4544.4 1913.36
  4663.2 1914.24  4828.7 1914.92  4896.4  1916.2  4987.7 1901.93  5003.8 1899.15
  5017.2 1902.09  5062.5 1903.94  5552.9 1917.97    5945 1934.39  6100.5 1934.11
    6193 1945.29  6279.3 1944.12  6339.2 1951.73  6376.4 1941.32  6430.4 1941.82
  6524.2 1963.01  6577.8 1960.53  6607.3 1948.55  6655.5 1969.53    6685 1969.49
  6714.6 1961.57  6738.7 1973.42  6791.4 1975.23  6971.6 1977.45  6997.6 1977.57
#Mann= 12 ,-1 , 0
  2963.2     .05       0  2991.5     .07       0  4544.4     .05       0
  4663.2     .07       0  4828.7     .05       0  4896.4     .07       0
  4987.7    .045       0  5017.2     .07       0  5062.5     .16       0
  5552.9     .07       0  6791.4     .05       0  6971.6     .07       0
Bank Sta=4987.7,5017.2
XS Rating Curve= 0 ,0
Exp/Cntr=0.3,0.1

Type RM Length L Ch R = 1 ,225272  ,1010,1010,1010
BEGIN DESCRIPTION:
Mapping XS c6faefb6
END DESCRIPTION:
XS GIS Cut Line= 6
      1492650.93      6828852.38       1493338.7      6827522.48
       1494211.1      6826848.87      1494541.54      6826427.69
      1494416.29      6826114.88      1494073.28      6825041.45
#Sta/Elev= 30
  2183.2 1923.32  2491.9 1921.08    2806 1914.55  2953.7 1906.77  4047.3 1911.56
  4365.5 1914.45  4474.1 1905.29  4849.1 1903.26  5035.8 1900.68  5045.8 1899.34
    5076 1904.46  5077.4 1912.81  5120.8 1948.11    5200 1943.94    5371 1949.16
  5478.6 1937.42  5576.1 1948.69  5703.6 1948.34  5778.5 1938.16  5869.8 1943.52
  5934.1    1941  5971.5 1932.41  6003.7 1940.48  6100.2 1939.73    6187 1929.16
    6355 1942.11  6464.6 1936.71  6625.5    1958  6669.9 1971.19  6781.8 1971.87
#Mann= 9 ,-1 , 0
  2183.2     .07       0  2491.9     .05       0    2806     .07       0
  4047.3     .05       0  4474.1     .16       0  4849.1     .07       0
  5035.8    .045       0    5076     .16       0    5200     .07       0
Bank Sta=5035.8,5076
XS Rating Curve= 0 ,0
Exp/Cntr=0.3,0.1

Type RM Length L Ch R = 1 ,224262  ,1458,1458,1458
BEGIN DESCRIPTION:
Mapping XS ddf52351
END DESCRIPTION:
XS GIS Cut Line= 3
      1493041.57       6829107.6      1495025.91       6827404.5
      1495671.74       6825836.8
#Sta/Elev= 30
  2120.6 1916.03    3288 1906.67  3568.7    1901  3661.7  1898.5  3777.1  1905.6
  3842.6 1905.76    4307 1909.79  4530.6 1907.33  4872.3 1910.37  4978.9  1898.3
  5002.2 1897.58  5008.2 1898.75  5153.6 1913.98  5168.1 1918.75    5192 1912.69
  5207.7 1913.74  5221.4  1918.5  5261.8 1919.45  5283.4 1926.12    5328 1926.78
  5346.5 1936.24  5375.9 1936.49  5381.3 1931.73  5399.8 1936.06  5405.2  1930.8
  5423.7 1940.97  5434.8 1936.03  5511.8  1952.9  5690.2 1958.32  6431.1 1962.17
#Mann= 9 ,-1 , 0
  2120.6     .07       0    3288     .05       0  3568.7     .16       0
  3777.1     .07       0  3842.6     .05       0  4530.6     .16       0
  4978.9    .045       0  5008.2     .16       0  5153.6     .07       0
Bank Sta=4978.9,5008.2
XS Rating Curve= 0 ,0
Exp/Cntr=0.3,0.1

Type RM Length L Ch R = 1 ,222804  ,1313,1313,1313
BEGIN DESCRIPTION:
Mapping XS 49636828
END DESCRIPTION:
XS GIS Cut Line= 4
      1493130.05      6829222.23      1494546.75      6828039.92
       1495645.7      6828305.54      1496270.32      6827935.98
#Sta/Elev= 30
  2119.9 1915.44  2943.1 1906.42  3319.6 1905.83  3466.3 1904.96  3496.3 1903.94
  3524.9 1899.46  3617.3 1900.33  3624.2 1897.93  3724.1 1907.55  3742.3 1906.26
  3765.7 1903.99  4014.7 1905.88  4261.7 1906.78  4318.5 1897.55  4354.3 1896.78
  4673.2  1898.1  4765.8 1900.33  4961.8 1895.92  4981.9 1892.72  5003.7 1897.34
  5033.3 1911.23  5174.9  1917.4  5254.8 1923.83  5297.7 1930.78  5325.5 1930.55
  5350.4 1933.56  5408.6 1926.61  5466.7 1929.62  5553.1 1941.79  5821.5 1950.09
#Mann= 10 ,-1 , 0
  2119.9     .07       0  3319.6     .05       0  3466.3     .16       0
  3742.3     .07       0  3765.7     .05       0  4014.7     .16       0
  4673.2     .07       0  4961.8    .045       0  5003.7     .07       0
  5325.5     .07       0
Bank Sta=4961.8,5003.7
XS Rating Curve= 0 ,0
Exp/Cntr=0.3,0.1

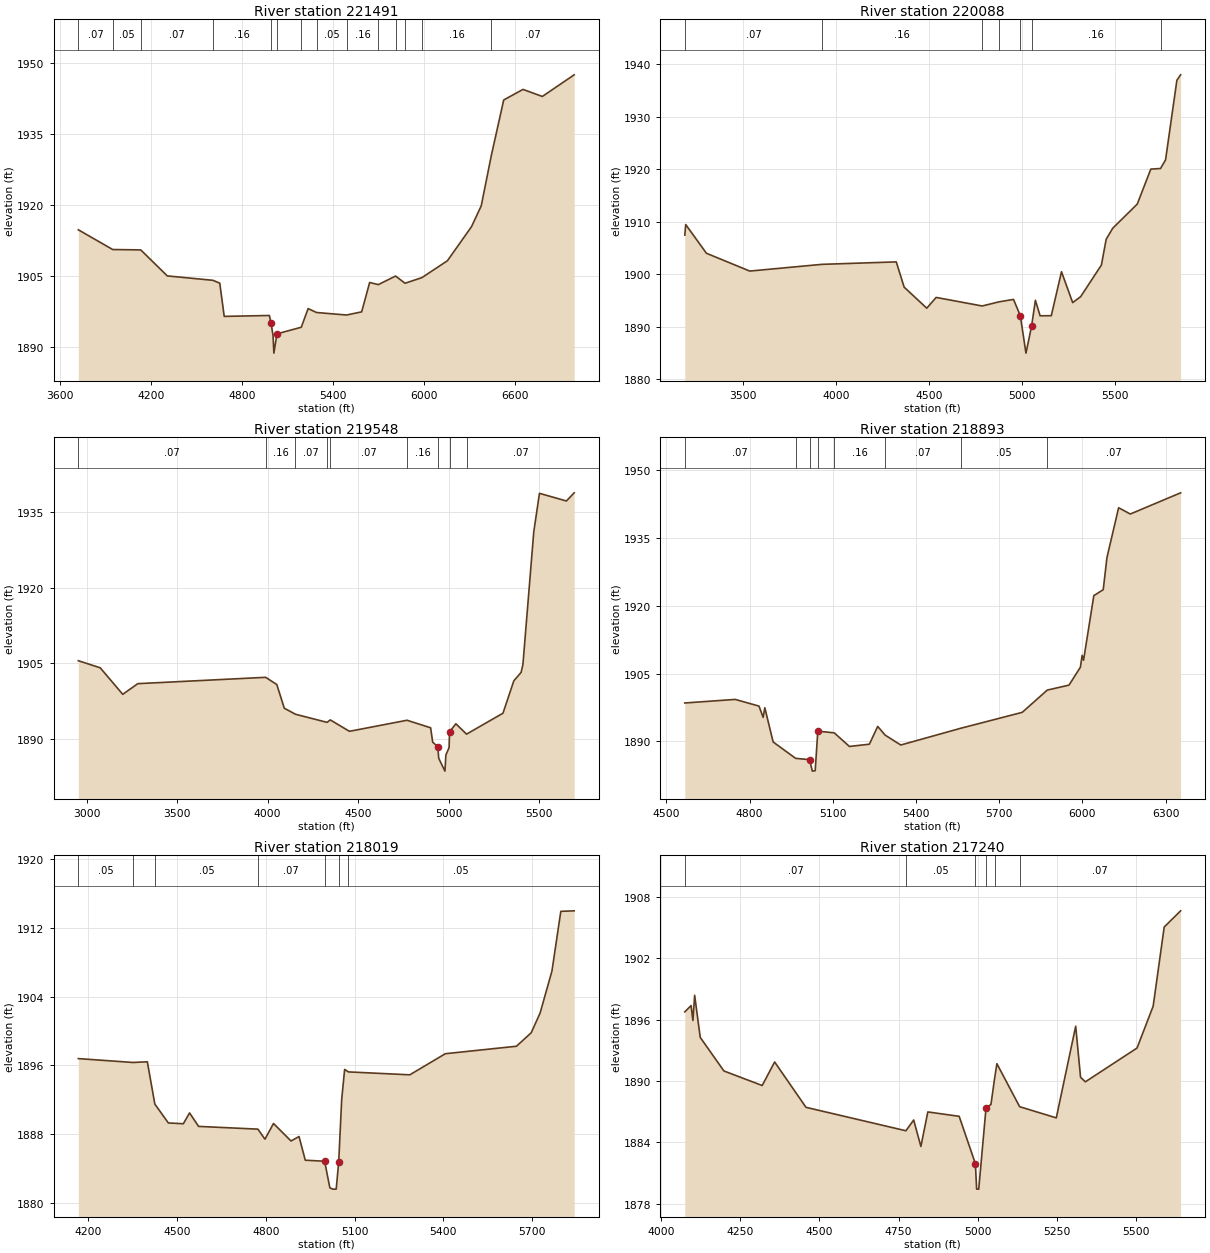
Type RM Length L Ch R = 1 ,221491  ,1403,1403,1403
BEGIN DESCRIPTION:
Mapping XS fab89c47
END DESCRIPTION:
XS GIS Cut Line= 5
      1493416.56      6829373.24      1494614.45      6828888.87
      1495774.18      6828527.37      1495906.45      6828356.88
      1496296.28      6827972.24
#Sta/Elev= 30
    3719 1914.82  3945.8 1910.65  4130.8 1910.57  4305.8 1905.08  4606.8 1904.15
  4651.8 1903.55  4681.3 1896.53  4979.3 1896.72  4990.1 1895.07  5003.2 1892.53
  5008.7 1888.77  5029.1 1892.84  5189.5 1894.24  5234.7 1898.18  5289.9 1897.35
  5488.5 1896.82  5587.8 1897.49  5640.5 1903.69  5697.7 1903.24  5811.5 1905.05
  5873.7 1903.53  5985.4 1904.72  6153.4 1908.28  6312.1 1915.47  6376.4 1919.88
  6442.8 1930.49  6524.7 1942.24  6651.9 1944.47  6779.2 1942.98  6989.3 1947.55
#Mann= 14 ,-1 , 0
    3719     .07       0  3945.8     .05       0  4130.8     .07       0
  4606.8     .16       0  4990.1    .045       0  5029.1     .16       0
  5189.5     .16       0  5289.9     .05       0  5488.5     .16       0
  5697.7     .07       0  5811.5     .16       0  5873.7     .07       0
  5985.4     .16       0  6442.8     .07       0
Bank Sta=4990.1,5029.1
XS Rating Curve= 0 ,0
Exp/Cntr=0.3,0.1

Type RM Length L Ch R = 1 ,220088  ,540,540,540
BEGIN DESCRIPTION:
Mapping XS ac79ad73
END DESCRIPTION:
XS GIS Cut Line= 3
      1494080.04      6829512.99      1495825.82      6829234.02
      1495977.63      6828348.16
#Sta/Elev= 30
  3185.7 1907.43  3190.7 1909.44  3302.1 1903.97    3535 1900.58  3923.1 1901.86
  4323.1 1902.33  4365.4 1897.52    4487 1893.51  4537.6 1895.56    4785 1893.93
  4875.8 1894.72  4953.6 1895.18  4990.2 1892.09  5020.6 1884.95    5051 1890.12
  5071.3 1895.01  5096.7 1892.06  5156.8 1892.08  5211.7 1900.45  5271.8 1894.57
  5314.8 1895.71  5426.4 1901.73  5451.9 1906.63  5487.3 1908.74  5619.2 1913.34
  5692.1    1920  5744.4 1920.12  5771.4 1921.76  5832.3 1936.93  5852.4 1937.96
#Mann= 7 ,-1 , 0
  3185.7     .07       0  3923.1     .16       0    4785     .07       0
  4875.8     .16       0  4990.2    .045       0    5051     .16       0
  5744.4     .07       0
Bank Sta=4990.2,5051
XS Rating Curve= 0 ,0
Exp/Cntr=0.3,0.1

Type RM Length L Ch R = 1 ,219548  ,655,655,655
BEGIN DESCRIPTION:
Mapping XS 173b7ff8
END DESCRIPTION:
XS GIS Cut Line= 3
      1494348.48      6829782.01      1496320.19      6829237.55
      1496292.08      6828545.22
#Sta/Elev= 30
  2954.5 1905.53  3075.4 1904.12  3199.9 1898.85  3282.9 1900.97    3989 1902.23
  4050.6  1900.8  4092.1 1896.09  4153.8 1894.89  4328.5 1893.28    4346 1893.77
  4451.8  1891.5  4769.9  1893.7  4900.2  1892.2  4911.6 1889.35  4939.8 1888.43
  4944.9 1886.14  4979.3 1883.59  4984.5  1886.8  5002.3 1888.28  5004.6 1891.37
  5039.6    1893  5098.6 1890.94  5299.8  1895.1  5359.8 1901.54  5399.9 1903.21
  5409.9 1904.77  5469.9 1931.15  5501.3 1938.79  5650.1 1937.27  5692.9 1938.89
#Mann= 9 ,-1 , 0
  2954.5     .07       0    3989     .16       0  4153.8     .07       0
  4328.5     .16       0    4346     .07       0  4769.9     .16       0
  4939.8    .045       0  5004.6     .16       0  5098.6     .07       0
Bank Sta=4939.8,5004.6
XS Rating Curve= 0 ,0
Exp/Cntr=0.3,0.1

Type RM Length L Ch R = 1 ,218893  ,874,874,874
BEGIN DESCRIPTION:
Mapping XS 5b0f45b3
END DESCRIPTION:
XS GIS Cut Line= 4
      1496554.62      6829512.99      1496789.29      6829425.15
       1496891.7      6829273.82      1496577.99      6827956.56
#Sta/Elev= 30
  4566.7 1898.49  4748.6 1899.28  4834.2  1897.8  4849.1 1895.31  4855.2 1897.44
  4885.1 1889.87  4966.2 1886.24  5016.3 1885.95  5026.5 1883.41  5036.8 1883.51
  5046.2 1892.26  5105.4 1891.88  5160.2 1888.87  5232.1 1889.37  5262.1 1893.31
  5288.9 1891.38  5345.2 1889.19  5562.3 1892.91  5783.2 1896.42  5873.5 1901.35
  5951.7 1902.44  5992.8 1906.41    5999 1909.03  6004.2 1907.94  6041.2 1922.25
  6075.1 1923.56  6088.5 1930.66  6130.6  1941.7  6172.7 1940.31  6354.1    1945
#Mann= 8 ,-1 , 0
  4566.7     .07       0  4966.2     .16       0  5016.3    .045       0
  5046.2     .16       0  5105.4     .16       0  5288.9     .07       0
  5562.3     .05       0  5873.5     .07       0
Bank Sta=5016.3,5046.2
XS Rating Curve= 0 ,0
Exp/Cntr=0.3,0.1

Type RM Length L Ch R = 1 ,218019  ,779,779,779
BEGIN DESCRIPTION:
Mapping XS 988cf998
END DESCRIPTION:
XS GIS Cut Line= 3
      1496968.09      6829701.95      1497671.71      6829254.57
        1497630.        6828413.
#Sta/Elev= 30
  4166.2 1896.77  4350.8 1896.32  4399.5  1896.4  4424.9 1891.47  4470.6 1889.27
  4521.2 1889.18  4542.3 1890.44  4572.8 1888.87  4773.3 1888.55  4797.2 1887.38
  4826.1 1889.21  4885.3 1887.17  4912.4 1887.69  4933.5 1884.93    4999 1884.81
  5016.6 1881.71  5026.6 1881.56  5038.1 1881.56  5046.6 1884.77  5056.6    1892
  5066.6 1895.51  5079.5 1895.22  5286.9 1894.88  5407.1 1897.34  5647.4 1898.21
  5697.4 1899.78  5727.5 1902.08  5767.5 1906.97  5797.5 1913.93  5842.6 1913.99
#Mann= 7 ,-1 , 0
  4166.2     .05       0  4350.8     .07       0  4424.9     .05       0
  4773.3     .07       0    4999    .045       0  5046.6     .07       0
  5079.5     .05       0
Bank Sta=4999,5046.6
XS Rating Curve= 0 ,0
Exp/Cntr=0.3,0.1

Type RM Length L Ch R = 1 ,217240  ,1174,1174,1174
BEGIN DESCRIPTION:
Mapping XS 971f3413
END DESCRIPTION:
XS GIS Cut Line= 3
      1497316.99      6830173.77      1498158.35      6829791.33
        1498280.        6829163.
#Sta/Elev= 30
  4075.8 1896.75  4095.6 1897.37  4101.4 1895.91  4106.9 1898.37  4124.5 1894.26
  4199.2 1890.98    4320 1889.56  4359.2 1891.86  4458.1 1887.43  4773.4 1885.14
  4797.9 1886.19  4820.6 1883.61  4842.5 1886.98  4941.4 1886.55  4992.5 1881.93
  4996.5 1879.44  5003.1 1879.44  5026.2  1887.4  5041.6  1887.7  5052.9 1890.19
  5060.4 1891.69  5132.2 1887.49  5247.8  1886.4    5309 1895.35  5324.3 1890.36
  5339.5 1889.92  5502.5 1893.22  5553.4 1897.31  5588.2 1905.04    5640 1906.62
#Mann= 6 ,-1 , 0
  4075.8     .07       0  4773.4     .05       0  4992.5    .035       0
  5026.2     .05       0  5052.9     .05       0  5132.2     .07       0
Bank Sta=4992.5,5026.2
XS Rating Curve= 0 ,0
Exp/Cntr=0.3,0.1

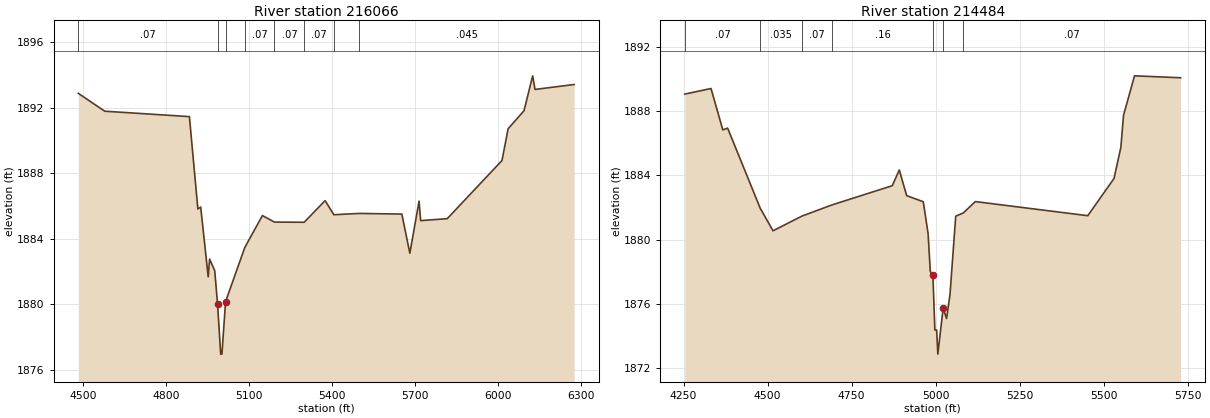
Type RM Length L Ch R = 1 ,216066  ,1582,1582,1582
BEGIN DESCRIPTION:
Mapping XS b2fbdeb2
END DESCRIPTION:
XS GIS Cut Line= 3
      1497571.32      6830612.22      1498078.12      6830711.84
      1498629.99      6829563.01
#Sta/Elev= 30
  4483.5 1892.89    4579  1891.8  4884.7 1891.47  4915.3 1885.83  4925.5 1885.95
  4952.6 1881.69  4957.7 1882.77  4976.1 1882.07  4986.4 1880.04  4997.7 1876.97
  5002.2 1876.97  5015.3 1880.17  5084.8 1883.48  5148.5 1885.43    5192 1885.03
  5299.2 1885.02  5374.9 1886.34  5406.5 1885.48  5498.4 1885.56  5652.1 1885.52
    5681 1883.13  5714.3 1886.31    5720 1885.12  5816.1 1885.24  6013.8 1888.79
    6036 1890.73  6093.4 1891.83  6124.7 1893.96  6133.1 1893.13  6274.5 1893.43
#Mann= 8 ,-1 , 0
  4483.5     .07       0  4986.4    .045       0  5015.3     .07       0
  5084.8     .07       0    5192     .07       0  5299.2     .07       0
  5406.5     .07       0  5498.4    .045       0
Bank Sta=4986.4,5015.3
XS Rating Curve= 0 ,0
Exp/Cntr=0.3,0.1

Type RM Length L Ch R = 1 ,214484  ,286,286,286
BEGIN DESCRIPTION:
Mapping XS 18708cd5
END DESCRIPTION:
XS GIS Cut Line= 3
        1498530.        6831113.      1499098.94      6830629.86
      1499229.99      6829913.04
#Sta/Elev= 30
  4253.6 1889.07  4331.6 1889.42  4366.7 1886.84    4381 1886.95  4478.1 1881.95
  4516.1 1880.55  4602.6 1881.47  4691.2 1882.16  4870.9 1883.36  4891.7 1884.34
  4913.7 1882.74  4963.1 1882.36  4977.4 1880.38    4984 1878.02  4991.7 1877.77
  4997.6 1874.36  5002.9 1874.36  5006.4 1872.86  5022.2 1875.73  5032.4 1875.08
  5042.6 1876.58  5059.6 1881.46  5082.1 1881.66  5117.9 1882.37  5452.5 1881.49
  5530.5 1883.81  5550.8 1885.74  5558.9 1887.75  5591.5 1890.21  5728.7 1890.09
#Mann= 7 ,-1 , 0
  4253.6     .07       0  4478.1    .035       0  4602.6     .07       0
  4691.2     .16       0  4991.7    .045       0  5022.2     .16       0
  5082.1     .07       0
Bank Sta=4991.7,5022.2
XS Rating Curve= 0 ,0
Exp/Cntr=0.3,0.1