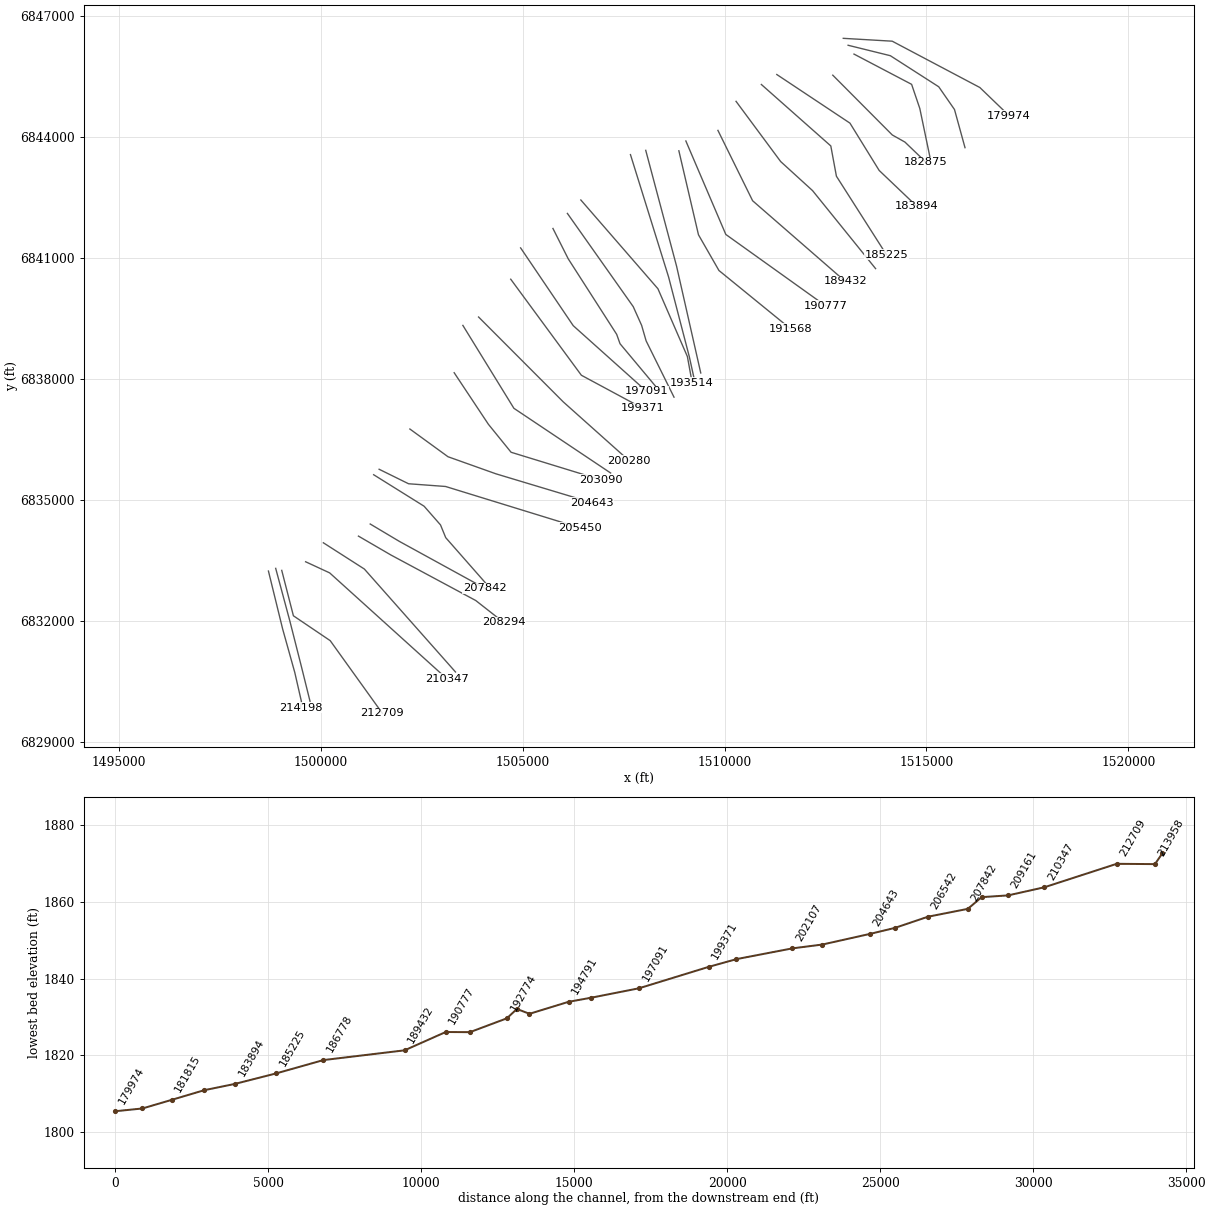
HEC-RAS study MULBERRY CREEK.prj: MULBERRY CREEK Base Level Engineering

--- MULBERRY CREEK.g01 (geometry) --- (continued)

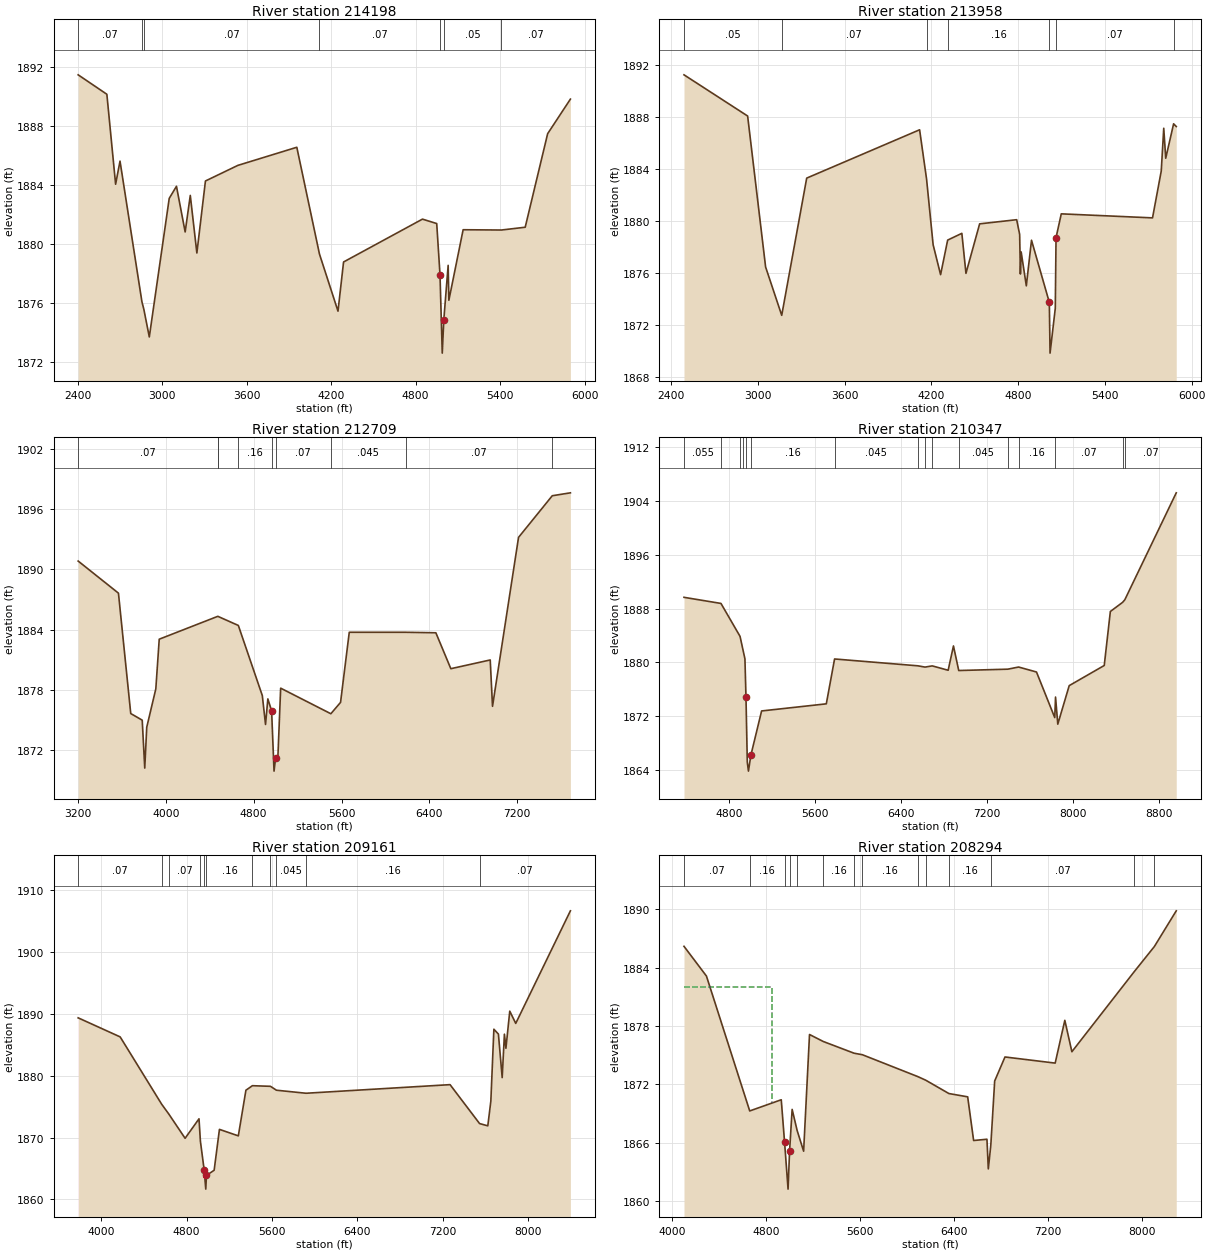
Type RM Length L Ch R = 1 ,214198  ,240,240,240
BEGIN DESCRIPTION:
Mapping XS 526dee00
END DESCRIPTION:
XS GIS Cut Line= 5
      1498700.34      6833246.57       1499052.7      6831808.09
      1499352.83      6830731.86      1499517.23      6830012.14
      1499493.39      6829852.57
#Sta/Elev= 30
  2401.7  1891.5  2605.7 1890.18  2667.9 1884.07  2699.2 1885.64  2854.8 1876.09
  2868.4 1875.58  2907.3  1873.7  3048.9 1883.11  3100.3 1883.93  3162.1 1880.83
  3198.5 1883.31  3245.3  1879.4  3306.2 1884.29  3536.5 1885.35  3955.5 1886.58
  4116.4 1879.33  4248.1 1875.45  4287.7 1878.79  4848.3  1881.7  4949.6  1881.4
  4972.9 1877.93    4989  1872.6  5000.1 1874.88  5030.9 1878.56    5036 1876.19
  5137.3 1880.98  5409.1 1880.96  5578.4 1881.15  5737.8  1887.5  5899.6 1889.85
#Mann= 7 ,-1 , 0
  2401.7     .07       0  2854.8     .16       0  2868.4     .07       0
  4116.4     .07       0  4972.9    .035       0  5000.1     .05       0
  5409.1     .07       0
Bank Sta=4972.9,5000.1
XS Rating Curve= 0 ,0
Exp/Cntr=0.3,0.1

Type RM Length L Ch R = 1 ,213958  ,1249,1249,1249
BEGIN DESCRIPTION:
Mapping XS df4dfdac
END DESCRIPTION:
XS GIS Cut Line= 4
      1498880.01      6833312.97      1499230.72      6832007.81
       1499515.5      6830883.67      1499730.39      6830017.34
#Sta/Elev= 30
    2490 1891.23    2930 1888.06  3054.3 1876.44  3165.7 1872.72  3338.4 1883.28
  4119.1    1887  4167.1 1883.22  4212.6 1878.15  4264.2 1875.85  4313.1 1878.51
  4411.2 1879.03  4439.6 1875.95  4534.2 1879.76  4790.3 1880.08  4810.8 1878.95
    4816  1875.9  4821.3  1877.6    4857 1874.99  4892.8  1878.5    5016 1873.72
  5021.1 1869.81  5057.3 1873.26  5062.5  1878.7  5098.7 1880.53  5729.6 1880.22
    5790 1883.83  5807.2 1887.12  5820.9 1884.81  5875.4 1887.46  5893.7 1887.25
#Mann= 7 ,-1 , 0
    2490     .05       0  3165.7     .07       0  4167.1     .16       0
  4313.1     .16       0    5016    .045       0  5062.5     .07       0
  5875.4     .05       0
Bank Sta=5016,5062.5
XS Rating Curve= 0 ,0
Exp/Cntr=0.3,0.1

Type RM Length L Ch R = 1 ,212709  ,2362,2362,2362
BEGIN DESCRIPTION:
Mapping XS 0b0b0225
END DESCRIPTION:
XS GIS Cut Line= 4
      1499029.99      6833263.02      1499318.86      6832137.18
      1500230.36      6831520.66      1501523.64      6829717.17
#Sta/Elev= 30
  3201.8 1890.83  3568.7 1887.63  3680.7 1875.63  3785.1 1874.97  3808.2 1870.19
  3826.4 1874.27    3909 1878.09    3940 1883.04  4473.4 1885.32  4475.5 1885.31
  4660.3 1884.41  4878.6 1877.42  4907.9 1874.54  4928.9 1877.09  4963.3  1875.9
  4985.3 1869.89  5000.1 1871.24  5020.9 1871.44  5045.7 1878.16  5502.7 1875.61
  5590.9 1876.74  5670.3 1883.73  6182.5 1883.73  6458.8 1883.68  6595.1  1880.1
  6953.7 1880.97  6974.6 1876.35  7211.6 1893.19  7518.7 1897.34  7683.8 1897.63
#Mann= 9 ,-1 , 0
  3201.8     .07       0  4473.4     .16       0  4475.5     .07       0
  4660.3     .16       0  4963.3    .045       0  5000.1     .07       0
  5502.7    .045       0  6182.5     .07       0  7518.7     .05       0
Bank Sta=4963.3,5000.1
XS Rating Curve= 0 ,0
Exp/Cntr=0.3,0.1

Type RM Length L Ch R = 1 ,210347  ,1186,1186,1186
BEGIN DESCRIPTION:
Mapping XS a164e18f
END DESCRIPTION:
XS GIS Cut Line= 3
      1499621.05       6833477.1      1500217.43       6833200.7
      1503124.05      6830571.72
#Sta/Elev= 30
  4380.4 1889.67  4724.1 1888.76  4901.3 1883.86  4927.7 1881.92  4946.9 1880.51
  4956.6 1874.83  4968.9 1865.13  4979.6 1863.79    5002 1866.15  5101.9 1872.75
  5703.5 1873.81  5780.3 1880.49  6555.3 1879.47  6621.2 1879.28  6688.2 1879.46
  6836.3 1878.81  6885.6 1882.43  6934.6 1878.77    7391 1878.97    7491 1879.29
  7657.5 1878.55  7827.3 1871.76  7834.6 1874.82  7855.5 1870.78  7961.7 1876.52
  8287.4 1879.52  8344.2 1887.56  8457.9 1888.92  8478.5  1889.3  8956.9 1905.23
#Mann= 16 ,-1 , 0
  4380.4    .055       0  4724.1     .07       0  4901.3     .16       0
  4927.7     .07       0  4956.6    .045       0    5002     .16       0
  5780.3    .045       0  6555.3     .07       0  6621.2    .045       0
  6688.2     .07       0  6934.6    .045       0    7391     .07       0
    7491     .16       0  7827.3     .07       0  8457.9     .05       0
  8478.5     .07       0
Bank Sta=4956.6,5002
XS Rating Curve= 0 ,0
Exp/Cntr=0.3,0.1

Type RM Length L Ch R = 1 ,209161  ,867,867,867
BEGIN DESCRIPTION:
Mapping XS ae328cf3
END DESCRIPTION:
XS GIS Cut Line= 3
       1500061.2      6833947.21       1501076.8      6833296.19
      1503333.72      6830744.13
#Sta/Elev= 30
  3783.5 1889.36  4177.2 1886.28  4566.9 1875.38    4633 1873.81  4785.8 1869.89
  4916.1 1873.04  4929.1 1869.43  4964.3 1864.79  4979.5 1861.67  4985.8 1863.89
    5058 1864.72  5107.6 1871.33  5284.6 1870.28  5355.7 1877.66  5416.5 1878.39
  5585.7 1878.29  5641.7 1877.66  5919.1 1877.17  7268.8 1878.56  7545.4 1872.27
  7622.6  1871.9    7651 1875.89  7679.5 1887.52  7722.1 1886.73  7757.3  1879.7
  7778.2 1886.72  7792.4 1884.44  7828.4 1890.44  7884.4 1888.46  8396.7 1906.66
#Mann= 11 ,-1 , 0
  3783.5     .07       0  4566.9     .16       0    4633     .07       0
  4929.1     .16       0  4964.3    .045       0  4985.8     .16       0
  5416.5    .045       0  5585.7     .07       0  5641.7    .045       0
  5919.1     .16       0  7545.4     .07       0
Bank Sta=4964.3,4985.8
XS Rating Curve= 0 ,0
Exp/Cntr=0.3,0.1

Type RM Length L Ch R = 1 ,208294  ,452,452,452
BEGIN DESCRIPTION:
Mapping XS 98eeb79c
END DESCRIPTION:
XS GIS Cut Line= 4
      1500929.97      6834113.02      1501736.52      6833643.41
      1503834.48      6832516.69      1504521.45      6831977.94
#Sta/Elev= 30
  4103.3 1886.18  4294.3 1883.12  4662.4 1869.25  4930.7  1870.4  4958.8 1866.05
  4988.6 1861.21  5001.8 1865.18  5023.3 1869.41  5065.8 1867.24    5121 1865.11
  5171.1 1877.11  5288.6 1876.39  5549.6 1875.19  5621.1 1875.03  6092.7 1872.78
  6159.9 1872.41  6356.9 1871.04  6516.6  1870.7  6567.2 1866.21  6680.6 1866.34
  6692.1 1863.29  6713.4 1865.73  6746.3 1872.33    6834  1874.8    7261 1874.17
    7343 1878.57  7403.1 1875.34  7933.3 1883.57  8104.9 1886.16    8291 1889.83
#Mann= 14 ,-1 , 0
  4103.3     .07       0  4662.4     .16       0  4958.8    .045       0
  5001.8     .16       0  5065.8     .05       0  5288.6     .16       0
  5549.6     .07       0  5621.1     .16       0  6092.7     .07       0
  6159.9     .05       0  6356.9     .16       0  6713.4     .07       0
  7933.3     .16       0  8104.9     .07       0
#XS Ineff= 2 , 0
       0    4850 1882.03               0
Permanent Ineff=
       F       F
Bank Sta=4958.8,5001.8
XS Rating Curve= 0 ,0
Exp/Cntr=0.3,0.1

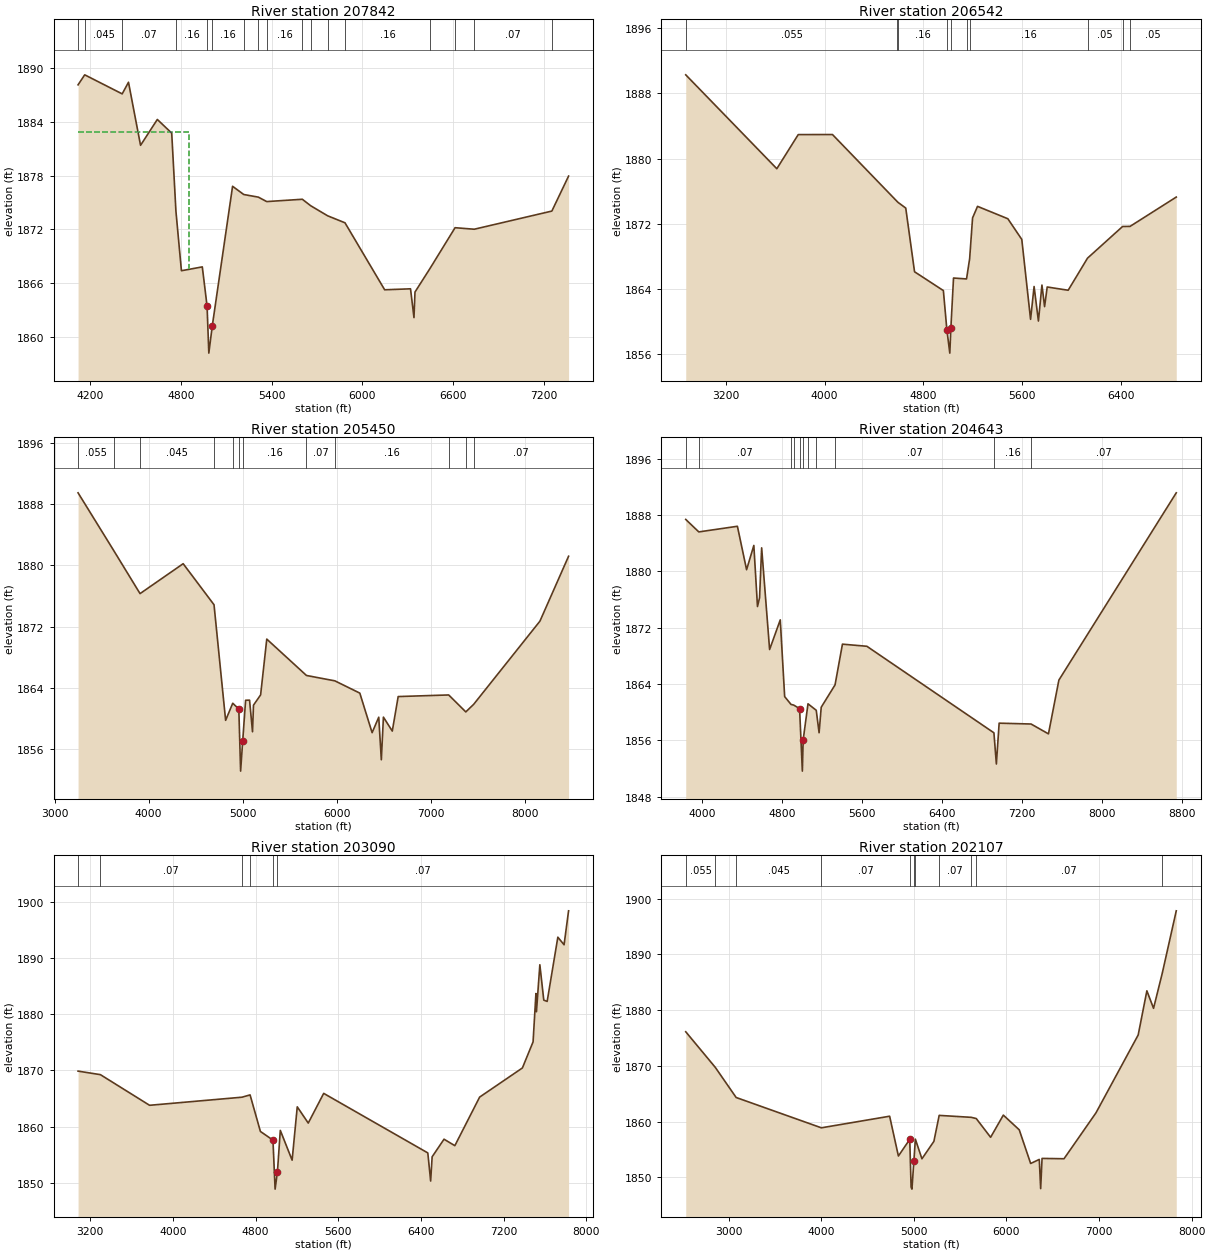
Type RM Length L Ch R = 1 ,207842  ,1300,1300,1300
BEGIN DESCRIPTION:
Mapping XS bebd26c9
END DESCRIPTION:
XS GIS Cut Line= 3
      1501221.58       6834412.9      1501942.34      6833982.82
      1504051.69      6832824.06
#Sta/Elev= 30
  4118.3 1888.15  4162.3 1889.27  4410.3 1887.14    4452 1888.44  4531.8 1881.39
  4642.8 1884.28  4738.1 1882.75  4765.9 1874.03  4802.3 1867.37  4940.5  1867.8
  4972.1  1863.4  4983.6 1858.16  5006.3 1861.18  5140.8 1876.81  5214.8 1875.89
    5311  1875.6  5366.9  1875.1  5602.3 1875.36  5657.4 1874.64  5769.9 1873.51
  5884.6 1872.73  6147.3 1865.24  6318.4 1865.35  6341.2 1862.13  6347.9 1864.99
  6446.4  1867.6  6613.2 1872.18  6740.1 1872.01  7253.7 1874.04  7364.3 1877.95
#Mann= 17 ,-1 , 0
  4118.3     .07       0  4162.3    .045       0  4410.3     .07       0
  4765.9     .16       0  4972.1    .035       0  5006.3     .16       0
  5214.8     .16       0    5311     .07       0  5366.9     .16       0
  5602.3     .07       0  5657.4     .16       0  5769.9     .07       0
  5884.6     .16       0  6446.4     .05       0  6613.2     .16       0
  6740.1     .07       0  7253.7    .035       0
#XS Ineff= 2 , 0
       0    4850 1882.86               0
Permanent Ineff=
       F       F
Bank Sta=4972.1,5006.3
XS Rating Curve= 0 ,0
Exp/Cntr=0.3,0.1

Type RM Length L Ch R = 1 ,206542  ,1092,1092,1092
BEGIN DESCRIPTION:
Mapping XS 9cd8a35d
END DESCRIPTION:
XS GIS Cut Line= 5
      1501306.71      6835635.38      1502556.71      6834854.13
      1502962.96      6834390.59      1503092.04      6834074.55
      1504108.81      6832916.61
#Sta/Elev= 30
  2875.2 1890.29  3612.9 1878.76  3786.2 1882.95  4063.4 1882.96  4588.4 1874.72
    4597  1874.6  4657.1 1873.93  4728.3 1866.11  4961.8  1863.8    4990 1859.01
  5013.9 1856.12  5022.4 1859.18    5044 1865.34  5149.4 1865.23  5174.6 1867.72
  5198.2 1872.72  5238.5 1874.14  5483.9 1872.62  5596.9 1870.08    5668 1860.27
  5696.5  1864.3  5731.6 1860.06  5760.1 1864.48  5781.5 1861.83  5802.8 1864.24
  5972.6 1863.84  6129.2 1867.78  6413.5 1871.67  6473.7 1871.68    6848 1875.28
#Mann= 10 ,-1 , 0
  2875.2    .055       0  4588.4     .07       0    4597     .16       0
    4990    .045       0  5022.4     .16       0  5149.4     .05       0
  5174.6     .16       0  6129.2     .05       0  6413.5     .07       0
  6473.7     .05       0
Bank Sta=4990,5022.4
XS Rating Curve= 0 ,0
Exp/Cntr=0.3,0.1

Type RM Length L Ch R = 1 ,205450  ,807,807,807
BEGIN DESCRIPTION:
Mapping XS ed9f5700
END DESCRIPTION:
XS GIS Cut Line= 4
      1501442.13      6835770.79      1502171.29      6835411.42
      1503087.96      6835343.71      1506416.11      6834317.66
#Sta/Elev= 30
  3250.1 1889.46  3630.5 1881.91  3909.1 1876.32  4367.5 1880.22  4695.5 1874.87
  4818.8  1859.8  4894.5 1862.03  4959.2 1861.27  4978.2 1853.18    5000 1857.05
  5031.4 1862.42  5073.3 1862.43  5104.7 1858.31  5115.1 1861.78  5190.9 1863.12
  5256.3 1870.39  5678.2 1865.65    5980 1864.95  6245.5 1863.35  6376.2 1858.19
  6446.7 1860.21  6474.2 1854.66  6496.4 1860.22  6590.6  1858.4  6653.4  1862.9
  7190.2 1863.11  7372.2  1860.9  7455.4 1861.88  8160.3 1872.73  8464.9 1881.19
#Mann= 12 ,-1 , 0
  3250.1    .055       0  3630.5     .05       0  3909.1    .045       0
  4695.5     .05       0  4894.5     .16       0  4959.2    .045       0
    5000     .16       0  5678.2     .07       0    5980     .16       0
  7190.2     .07       0  7372.2     .16       0  7455.4     .07       0
Bank Sta=4959.2,5000
XS Rating Curve= 0 ,0
Exp/Cntr=0.3,0.1

Type RM Length L Ch R = 1 ,204643  ,1553,1553,1553
BEGIN DESCRIPTION:
Mapping XS 482ebccc
END DESCRIPTION:
XS GIS Cut Line= 4
      1502204.28      6836768.63      1503148.72      6836081.13
      1504336.22      6835657.52      1506709.36       6834942.8
#Sta/Elev= 30
  3832.6 1887.38  3963.3 1885.61  4349.4 1886.41  4441.3 1880.24  4513.8 1883.69
  4550.3 1875.01  4571.1 1876.26    4592 1883.35  4671.6 1868.91  4778.2 1873.12
  4822.2 1862.22  4886.1 1861.11  4912.5 1861.02  4971.4 1860.52  4999.2 1851.64
  5007.4 1856.08  5055.7  1861.2  5138.1 1860.28  5166.7 1857.09  5187.9 1860.71
  5326.4 1863.89  5400.3 1869.67  5644.5 1869.37  6915.8 1857.08  6940.2 1852.65
    6968 1858.45  7287.5 1858.33  7461.4 1856.93  7565.8 1864.57    8740 1891.16
#Mann= 11 ,-1 , 0
  3832.6     .05       0  3963.3     .07       0  4886.1     .16       0
  4912.5     .07       0  4971.4    .045       0  5007.4     .07       0
  5055.7     .07       0  5138.1     .16       0  5326.4     .07       0
  6915.8     .16       0  7287.5     .07       0
Bank Sta=4971.4,5007.4
XS Rating Curve= 0 ,0
Exp/Cntr=0.3,0.1

Type RM Length L Ch R = 1 ,203090  ,983,983,983
BEGIN DESCRIPTION:
Mapping XS 8f1affd7
END DESCRIPTION:
XS GIS Cut Line= 4
      1503301.49      6838164.47      1504148.72      6836886.68
      1504711.22      6836192.24      1506926.52      6835511.68
#Sta/Elev= 30
  3083.4 1869.86  3299.5 1869.23  3775.1 1863.78  4668.8 1865.22  4747.1 1865.63
    4847 1859.13  4968.4 1857.59  4989.2 1848.87  5011.6  1851.9  5039.5 1859.32
  5153.8 1854.02  5203.4 1863.51  5309.8 1860.62  5459.2  1865.9  6466.2 1855.31
  6493.7 1850.31    6508 1854.62  6623.1 1857.75  6727.7  1856.6  6967.5 1865.24
    7381 1870.42  7484.4 1875.07  7511.9 1883.66  7517.1 1880.42  7549.8 1888.78
  7587.8 1882.49  7620.5 1882.26  7723.9 1893.68  7784.1 1892.33  7827.7 1898.37
#Mann= 6 ,-1 , 0
  3083.4     .05       0  3299.5     .07       0  4668.8     .05       0
  4747.1     .07       0  4968.4    .045       0  5011.6     .07       0
Bank Sta=4968.4,5011.6
XS Rating Curve= 0 ,0
Exp/Cntr=0.3,0.1

Type RM Length L Ch R = 1 ,202107  ,1827,1827,1827
BEGIN DESCRIPTION:
Mapping XS 2731ad98
END DESCRIPTION:
XS GIS Cut Line= 3
      1503516.78      6839338.06      1504780.66      6837282.52
      1507176.49      6835678.35
#Sta/Elev= 30
  2537.7  1876.1  2856.9 1869.71  3081.9 1864.31    4002 1858.87  4739.1 1860.95
  4833.8 1853.81  4956.3  1856.8  4970.9 1848.24  4979.9 1847.87  5000.9 1852.88
  5016.9 1856.84    5088 1853.31  5217.1 1856.44  5274.1  1861.1  5620.9 1860.75
  5674.5 1860.53  5829.5 1857.17  5966.8 1861.15  6138.7 1858.51  6261.8 1852.47
  6354.9  1853.2  6369.9 1847.96  6384.9 1853.38  6622.1 1853.32  6967.3 1861.56
    7423 1875.53  7516.7 1883.45  7588.7 1880.31  7682.1 1886.55    7834  1897.8
#Mann= 11 ,-1 , 0
  2537.7    .055       0  2856.9     .07       0  3081.9    .045       0
    4002     .07       0  4956.3    .045       0  5000.9     .07       0
  5016.9     .16       0  5274.1     .07       0  5620.9     .05       0
  5674.5     .07       0  7682.1     .05       0
Bank Sta=4956.3,5000.9
XS Rating Curve= 0 ,0
Exp/Cntr=0.3,0.1

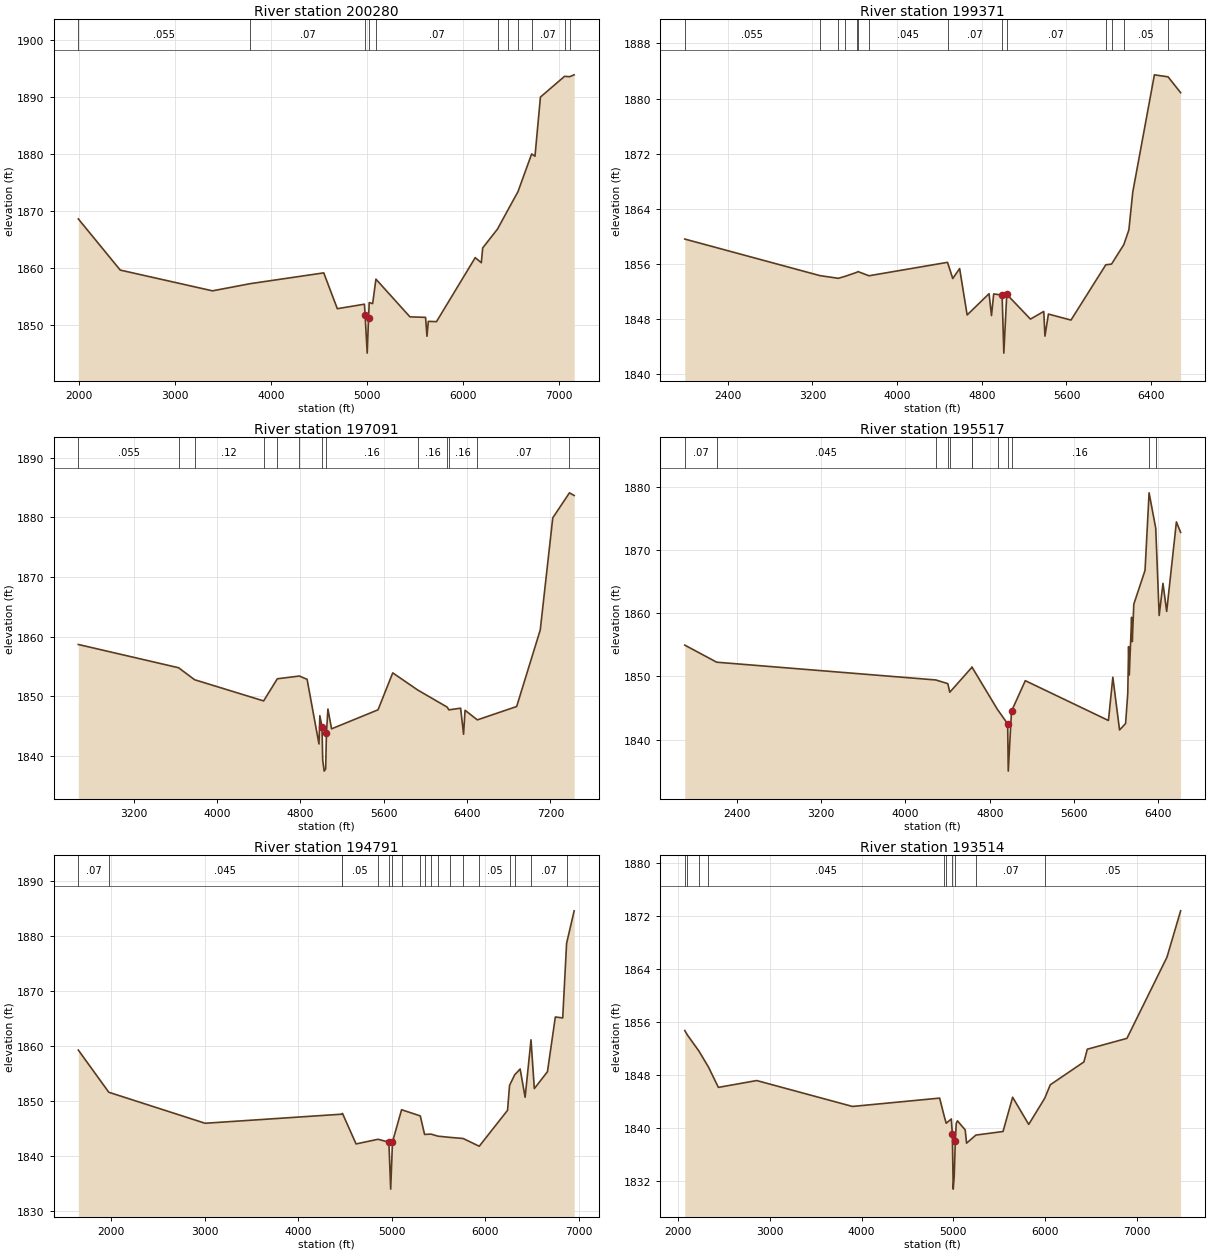
Type RM Length L Ch R = 1 ,200280  ,909,909,909
BEGIN DESCRIPTION:
Mapping XS cbd1cd65
END DESCRIPTION:
XS GIS Cut Line= 3
      1503905.66      6839546.41      1506002.89      6837442.24
      1507640.92      6835977.72
#Sta/Elev= 30
  1989.6  1868.6  2426.4 1859.63  3388.1 1855.99  3781.9 1857.25  4547.7 1859.14
  4689.2 1852.86  4972.1 1853.65  4978.8 1851.68  5000.6 1845.07  5014.8 1851.28
  5021.5 1853.93  5057.2 1853.75  5091.7 1858.04  5446.2 1851.43  5609.1 1851.34
  5623.4 1848.03  5637.6 1850.64  5722.8 1850.59  6126.6 1861.81  6190.1 1860.92
  6204.3 1863.51  6358.7 1866.82  6468.9 1870.22    6572 1873.37  6714.6 1879.99
  6749.4 1879.59  6806.2 1889.96  7057.9  1893.6    7110 1893.53  7157.7 1893.86
#Mann= 11 ,-1 , 0
  1989.6    .055       0  3781.9     .07       0  4978.8    .045       0
  5014.8     .07       0  5091.7     .07       0  6358.7     .05       0
  6468.9     .07       0    6572     .05       0  6714.6     .07       0
  7057.9     .05       0    7110     .07       0
Bank Sta=4978.8,5014.8
XS Rating Curve= 0 ,0
Exp/Cntr=0.3,0.1

Type RM Length L Ch R = 1 ,199371  ,2280,2280,2280
BEGIN DESCRIPTION:
Mapping XS 939394fc
END DESCRIPTION:
XS GIS Cut Line= 3
      1504702.21      6840483.93      1506452.19      6838102.02
      1507973.02      6837282.58
#Sta/Elev= 30
    1995 1859.61  3271.8  1854.3  3445.7 1853.91  3511.4 1854.21  3619.6 1854.78
  3630.5 1854.89  3734.3 1854.28  4476.4 1856.23  4526.1 1853.88  4590.9 1855.33
  4661.9 1848.59  4868.8 1851.68  4891.8  1848.5  4912.7 1851.64  4992.2 1851.48
  5008.4 1843.05    5036 1851.59  5259.8 1847.99  5385.5  1849.1  5396.9 1845.52
  5429.4 1848.72  5642.7 1847.85  5971.3 1855.87  6025.8 1855.98  6141.3 1858.79
  6189.4 1860.93  6226.1 1866.42  6430.5 1883.45  6559.4 1883.16  6678.2 1880.86
#Mann= 14 ,-1 , 0
    1995    .055       0  3271.8     .07       0  3445.7     .12       0
  3511.4     .07       0  3619.6     .12       0  3630.5     .07       0
  3734.3    .045       0  4476.4     .07       0  4992.2    .045       0
    5036     .07       0  5971.3     .05       0  6025.8     .07       0
  6141.3     .05       0  6559.4     .07       0
Bank Sta=4992.2,5036
XS Rating Curve= 0 ,0
Exp/Cntr=0.3,0.1

Type RM Length L Ch R = 1 ,197091  ,1574,1574,1574
BEGIN DESCRIPTION:
Mapping XS d692d577
END DESCRIPTION:
XS GIS Cut Line= 3
      1504947.26      6841260.07       1506250.8      6839331.18
      1508063.27      6837706.21
#Sta/Elev= 30
  2666.2  1858.7    3629  1854.8    3783 1852.79    4446 1849.24  4577.5 1852.95
  4789.4 1853.41  4863.5 1852.86  4977.5 1842.02    4986 1846.76  5006.6 1844.92
  5013.3 1839.31  5027.5 1837.47  5041.7 1837.84  5049.2 1843.83  5063.4 1847.88
  5098.5 1844.56  5544.8 1847.75  5686.1 1853.94  5925.7 1851.07  6207.9 1848.21
  6225.8 1847.74    6338 1848.02  6366.4 1843.65  6380.6 1847.67  6498.7 1846.06
  6876.2  1848.3  7102.8 1861.13  7223.1 1879.93  7383.4 1884.12  7428.5 1883.67
#Mann= 13 ,-1 , 0
  2666.2    .055       0    3629     .07       0    3783     .12       0
    4446    .045       0  4577.5     .07       0  4789.4     .16       0
  5006.6    .045       0  5049.2     .16       0  5925.7     .16       0
  6207.9     .07       0  6225.8     .16       0  6498.7     .07       0
  7383.4     .05       0
Bank Sta=5006.6,5049.2
XS Rating Curve= 0 ,0
Exp/Cntr=0.3,0.1

Type RM Length L Ch R = 1 ,195517  ,726,726,726
BEGIN DESCRIPTION:
Mapping XS 38a44390
END DESCRIPTION:
XS GIS Cut Line= 5
       1505748.2      6841741.77       1506125.8      6840990.91
      1507327.19      6839115.91      1507409.66      6838883.96
      1508305.25      6837811.67
#Sta/Elev= 30
  1903.3 1854.93  2206.2 1852.23  4287.9 1849.42  4402.2 1848.84  4420.8 1847.48
  4628.3 1851.37  4630.8 1851.48  4874.4 1844.74  4970.6 1842.49  4976.4    1835
  5007.2 1844.48  5138.2 1849.31  5928.1 1843.01  5969.9 1849.86  6033.7 1841.51
    6091 1842.53  6111.8 1847.31  6119.6 1854.69  6126.1 1850.19  6148.2 1859.34
  6154.7 1855.48    6169  1861.4  6275.8 1866.75  6314.3 1879.02  6377.5 1873.42
  6410.2 1859.62  6446.2  1864.7  6481.4 1860.27  6573.8 1874.42  6613.9 1872.77
#Mann= 12 ,-1 , 0
  1903.3     .07       0  2206.2    .045       0  4287.9     .07       0
  4402.2    .045       0  4420.8     .07       0  4628.3    .045       0
  4630.8     .07       0  4874.4     .16       0  4970.6    .045       0
  5007.2     .16       0  6314.3     .05       0  6377.5     .07       0
Bank Sta=4970.6,5007.2
XS Rating Curve= 0 ,0
Exp/Cntr=0.3,0.1

Type RM Length L Ch R = 1 ,194791  ,1277,1277,1277
BEGIN DESCRIPTION:
Mapping XS 7bf88ad9
END DESCRIPTION:
XS GIS Cut Line= 5
       1506106.1      6842115.13      1507736.91      6839803.41
      1507945.25      6839338.13      1508055.99      6838955.16
      1508747.04      6837558.49
#Sta/Elev= 30
  1651.4 1859.24  1976.9 1851.57  3005.7 1845.93  4463.2 1847.58  4472.6 1847.73
  4617.9 1842.17  4852.7 1843.02  4968.5 1842.48  4987.6 1833.95  5006.7 1842.52
  5103.8 1848.39  5303.7 1847.27  5349.6  1843.9  5417.8 1843.96  5493.5 1843.58
    5624 1843.36  5761.4 1843.16  5933.4 1841.75  6235.8 1848.29  6257.2 1852.82
  6312.3 1854.75  6370.4  1855.8  6423.4 1850.66  6486.4 1861.11  6521.8 1852.23
    6662 1855.31  6746.1 1865.26    6825 1865.09  6866.4 1878.66  6947.2 1884.57
#Mann= 19 ,-1 , 0
  1651.4     .07       0  1976.9    .045       0  4463.2     .07       0
  4472.6     .05       0  4852.7     .16       0  4968.5    .045       0
  5006.7     .16       0  5103.8     .16       0  5303.7     .07       0
  5349.6     .16       0  5417.8     .07       0  5493.5     .16       0
    5624     .05       0  5761.4     .07       0  5933.4     .05       0
  6257.2     .07       0  6312.3     .05       0  6486.4     .07       0
  6866.4     .05       0
Bank Sta=4968.5,5006.7
XS Rating Curve= 0 ,0
Exp/Cntr=0.3,0.1

Type RM Length L Ch R = 1 ,193514  ,409,409,409
BEGIN DESCRIPTION:
Mapping XS 5564cd61
END DESCRIPTION:
XS GIS Cut Line= 4
      1506439.19      6842448.35      1508348.89      6840246.98
      1509078.06      6838566.43       1509195.9       6837921.8
#Sta/Elev= 30
  2074.3 1854.76  2102.6  1854.1  2228.2 1851.67  2330.7  1849.3  2440.3 1846.19
  2858.1 1847.22  3900.9 1843.31  4850.6 1844.57  4898.9 1841.92  4921.8 1840.77
  4977.8 1841.42  4988.6 1839.18  4998.4 1830.83  5009.3 1832.75    5021 1838.02
  5031.1 1840.73  5044.5 1841.14  5129.2 1839.77  5143.8 1837.77  5245.4 1838.99
    5541 1839.53  5645.8  1844.7  5820.9  1840.6  5995.8 1844.56  6055.7 1846.58
  6422.1 1850.03  6459.1 1851.95    6891 1853.59  7326.9 1865.84  7475.8 1872.84
#Mann= 10 ,-1 , 0
  2074.3     .07       0  2102.6    .045       0  2228.2     .07       0
  2330.7    .045       0  4898.9     .07       0  4921.8    .045       0
  4988.6    .045       0    5021    .045       0  5245.4     .07       0
  5995.8     .05       0
Bank Sta=4988.6,5021
XS Rating Curve= 0 ,0
Exp/Cntr=0.3,0.1

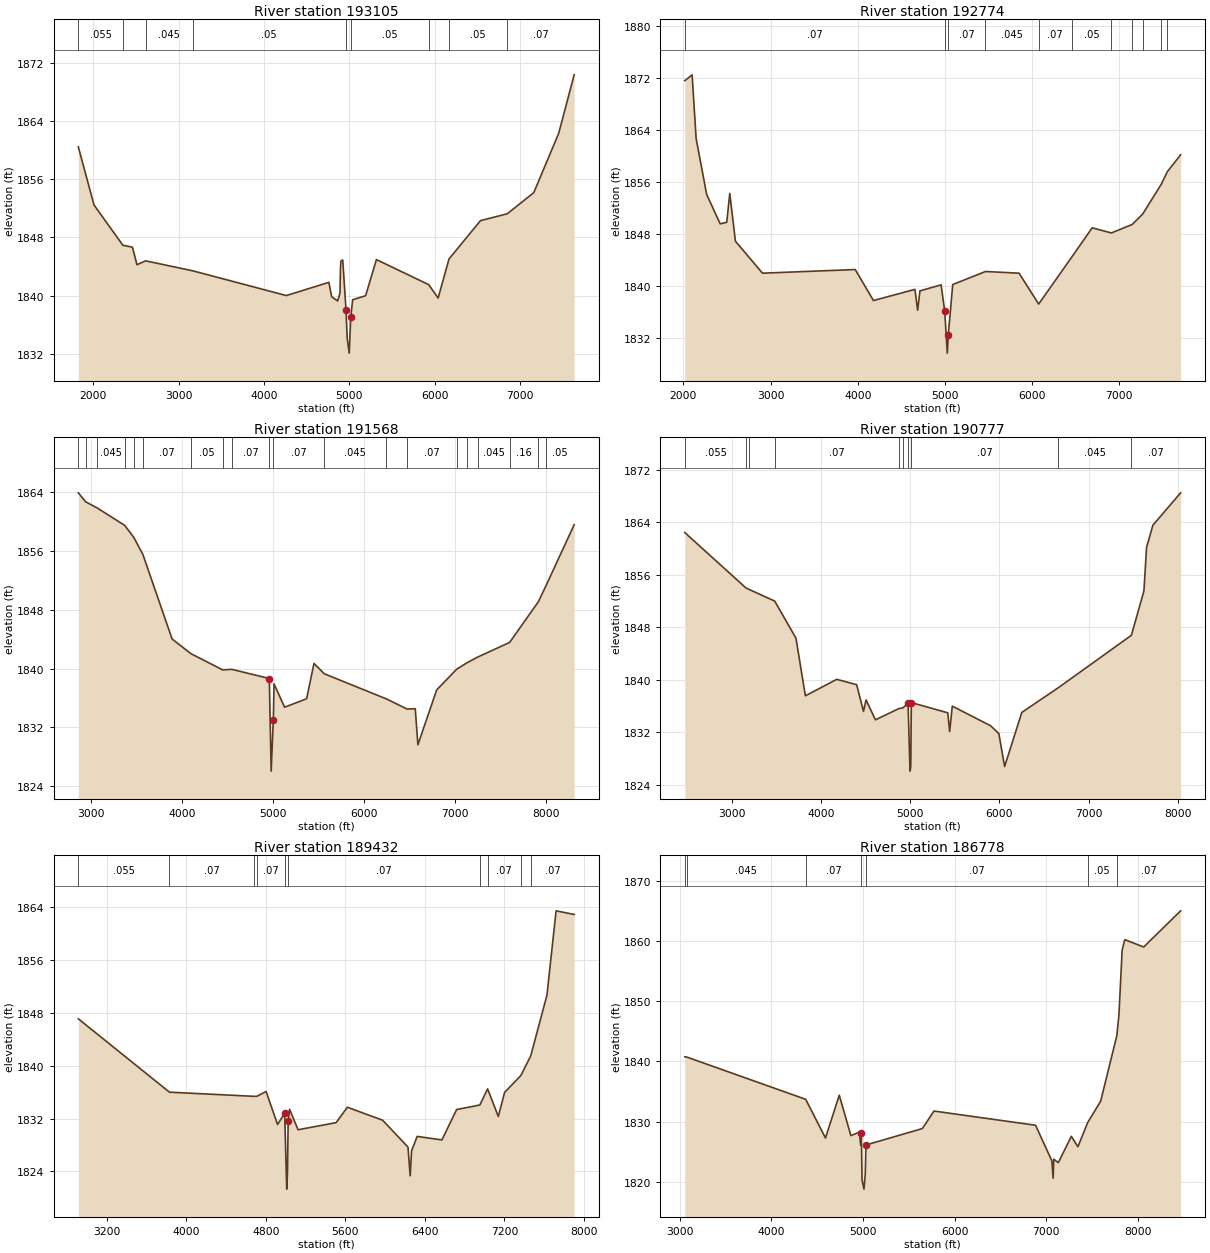
Type RM Length L Ch R = 1 ,193105  ,331,331,331
BEGIN DESCRIPTION:
Mapping XS 98ce9872
END DESCRIPTION:
XS GIS Cut Line= 4
      1507668.34      6843573.37      1508612.78      6840538.65
      1509126.67      6838559.48      1509251.35      6837991.48
#Sta/Elev= 30
  1827.1 1860.46  2010.8 1852.47    2348 1846.94  2461.1 1846.66  2513.5 1844.25
    2614 1844.79    3165 1843.42  4262.5 1840.01  4760.2 1841.83  4792.7 1839.85
    4863 1839.27  4890.3 1840.34  4895.6 1843.72  4901.3 1844.77  4922.3 1844.91
  4960.6 1838.08  4974.6 1834.16  4998.4 1832.09  5016.4 1837.02  5038.2 1839.43
  5190.1 1839.99  5316.9 1844.96  5929.4 1841.51  6039.2 1839.67  6166.9 1845.05
  6535.1 1850.32  6848.2 1851.26  7159.1 1854.17    7451 1862.34  7631.7 1870.38
#Mann= 9 ,-1 , 0
  1827.1    .055       0    2348     .05       0    2614    .045       0
    3165     .05       0  4960.6    .035       0  5016.4     .05       0
  5929.4     .07       0  6166.9     .05       0  6848.2     .07       0
Bank Sta=4960.6,5016.4
XS Rating Curve= 0 ,0
Exp/Cntr=0.3,0.1

Type RM Length L Ch R = 1 ,192774  ,1206,1206,1206
BEGIN DESCRIPTION:
Mapping XS 2f27bd4f
END DESCRIPTION:
XS GIS Cut Line= 3
       1508046.8      6843679.31       1508810.7      6840806.01
      1509409.66      6838158.43
#Sta/Elev= 30
  2016.6 1871.57  2100.7 1872.47  2146.6 1862.67    2267 1854.08  2422.5 1849.54
  2497.6 1849.78  2532.6 1854.23  2597.4 1846.88  2907.8 1841.95  3971.8 1842.51
  4180.6 1837.74  4656.5 1839.46  4687.6 1836.25    4714 1839.23  4956.6 1840.15
  4997.9 1836.13  5027.7 1829.65  5038.9 1832.48  5090.2  1840.2  5465.4 1842.21
  5850.8 1841.95    6076  1837.2  6457.1 1844.46  6689.6 1848.93  6910.6 1848.14
  7149.2 1849.45  7269.9 1851.07  7482.5 1855.64  7550.8 1857.54  7704.2 1860.17
#Mann= 11 ,-1 , 0
  2016.6     .07       0  4997.9    .045       0  5038.9     .07       0
  5465.4    .045       0    6076     .07       0  6457.1     .05       0
  6910.6     .07       0  7149.2     .05       0  7269.9     .07       0
  7482.5     .05       0  7550.8     .07       0
Bank Sta=4997.9,5038.9
XS Rating Curve= 0 ,0
Exp/Cntr=0.3,0.1

Type RM Length L Ch R = 1 ,191568  ,791,791,791
BEGIN DESCRIPTION:
Mapping XS fdd9caad
END DESCRIPTION:
XS GIS Cut Line= 4
      1508867.12      6843668.43      1509353.23      6841585.09
       1509860.4      6840699.34      1511627.51      6839258.73
#Sta/Elev= 30
  2863.8 1863.88  2944.3 1862.66  3072.4 1861.81  3372.1 1859.46    3472 1857.83
  3571.9 1855.51  3892.5 1844.01  4099.1 1842.02  4447.8 1839.81  4546.5 1839.89
    4959 1838.64  4979.6 1826.05  5003.1 1833.06  5011.1 1837.91  5126.5 1834.74
  5368.5 1835.89  5449.2 1840.69  5561.6 1839.29  6244.8 1835.86  6470.4 1834.49
  6560.6 1834.53  6589.3 1829.63  6795.4 1837.09  7015.2 1839.91  7132.6 1840.81
  7246.9 1841.56  7596.5 1843.55  7912.3  1849.1  7993.9 1851.23  8303.7 1859.54
#Mann= 20 ,-1 , 0
  2863.8    .055       0  2944.3     .07       0  3072.4    .045       0
  3372.1     .07       0    3472    .045       0  3571.9     .07       0
  4099.1     .05       0  4447.8     .05       0  4546.5     .07       0
    4959    .045       0  5003.1     .07       0  5561.6    .045       0
  6244.8    .045       0  6470.4     .07       0  7015.2    .045       0
  7132.6     .07       0  7246.9    .045       0  7596.5     .16       0
  7912.3     .16       0  7993.9     .05       0
Bank Sta=4959,5003.1
XS Rating Curve= 0 ,0
Exp/Cntr=0.3,0.1

Type RM Length L Ch R = 1 ,190777  ,1345,1345,1345
BEGIN DESCRIPTION:
Mapping XS 01efab81
END DESCRIPTION:
XS GIS Cut Line= 3
      1509040.74      6843911.46      1510030.32      6841593.77
      1512504.25      6839822.95
#Sta/Elev= 30
    2471 1862.42  3158.5 1853.97  3194.2 1853.75  3479.9 1851.98  3718.4 1846.33
  3823.7 1837.56  4175.9 1840.07  4399.2 1839.25  4475.5 1835.18  4504.5 1836.94
  4609.8  1833.9  4870.2  1835.6  4919.2 1835.73  4975.6 1836.46  4997.7 1826.09
  5006.3 1826.81  5012.5 1836.53  5421.5 1834.97  5442.4 1832.12  5471.9 1835.99
  5901.9    1833    5994 1831.81  6059.1  1826.8    6252 1835.03  6663.3 1838.81
  7481.5 1846.78  7621.8 1853.53  7651.2 1860.14  7722.5 1863.54  8033.5 1868.47
#Mann= 10 ,-1 , 0
    2471    .055       0  3158.5    .035       0  3194.2    .045       0
  3479.9     .07       0  4870.2     .05       0  4919.2     .07       0
  4975.6    .045       0  5012.5     .07       0  6663.3    .045       0
  7481.5     .07       0
Bank Sta=4975.6,5012.5
XS Rating Curve= 0 ,0
Exp/Cntr=0.3,0.1

Type RM Length L Ch R = 1 ,189432  ,2654,2654,2654
BEGIN DESCRIPTION:
Mapping XS 2838b448
END DESCRIPTION:
XS GIS Cut Line= 3
      1509835.01      6844174.06      1510694.38      6842429.27
      1512985.87       6840432.9
#Sta/Elev= 30
  2916.2 1847.11  3832.3    1836  4684.8 1835.37  4711.4 1835.38  4803.6  1836.1
    4919 1831.11  4990.2 1832.81  5011.1 1821.32  5018.7 1823.89  5025.3 1831.58
  5039.6 1833.41    5125 1830.31  5507.6 1831.39  5620.6 1833.72  5975.7 1831.75
  6230.1 1827.68    6252 1823.33  6266.2 1827.12  6322.2  1829.3    6571 1828.77
  6719.1 1833.37  6952.4 1834.06  7030.3  1836.5  7137.8 1832.32  7201.4 1835.97
  7364.1 1838.51  7463.6 1841.49  7626.7 1850.68  7718.8 1863.46  7900.3 1862.91
#Mann= 10 ,-1 , 0
  2916.2    .055       0  3832.3     .07       0  4684.8     .05       0
  4711.4     .07       0  4990.2    .045       0  5025.3     .07       0
  6952.4     .05       0  7030.3     .07       0  7364.1     .05       0
  7463.6     .07       0
Bank Sta=4990.2,5025.3
XS Rating Curve= 0 ,0
Exp/Cntr=0.3,0.1

Type RM Length L Ch R = 1 ,186778  ,1553,1553,1553
BEGIN DESCRIPTION:
Mapping XS 101c8131
END DESCRIPTION:
XS GIS Cut Line= 4
      1510283.77      6844894.35      1511388.82       6843401.5
      1512178.76      6842681.01      1513740.63      6840746.02
#Sta/Elev= 30
  3054.7 1840.76  3076.2 1840.72  4374.5  1833.7  4590.7 1827.27    4741 1834.39
  4868.2 1827.67  4961.1 1828.24  4975.2 1826.05  4982.7 1828.03  4989.4 1820.32
    5011 1818.78  5025.2 1821.36    5032 1826.11  5648.2 1828.84  5775.2 1831.75
  6884.5 1829.39    7062 1823.48  7076.4 1820.61  7082.8 1823.76  7132.4 1823.17
  7274.7 1827.55  7346.6 1825.82  7453.4 1829.85  7594.6 1833.37  7771.9  1844.3
  7794.4 1847.72  7829.6  1858.5  7858.4 1860.22  8064.7    1859  8467.9 1865.01
#Mann= 7 ,-1 , 0
  3054.7     .07       0  3076.2    .045       0  4374.5     .07       0
  4982.7    .045       0    5032     .07       0  7453.4     .05       0
  7771.9     .07       0
Bank Sta=4982.7,5032
XS Rating Curve= 0 ,0
Exp/Cntr=0.3,0.1

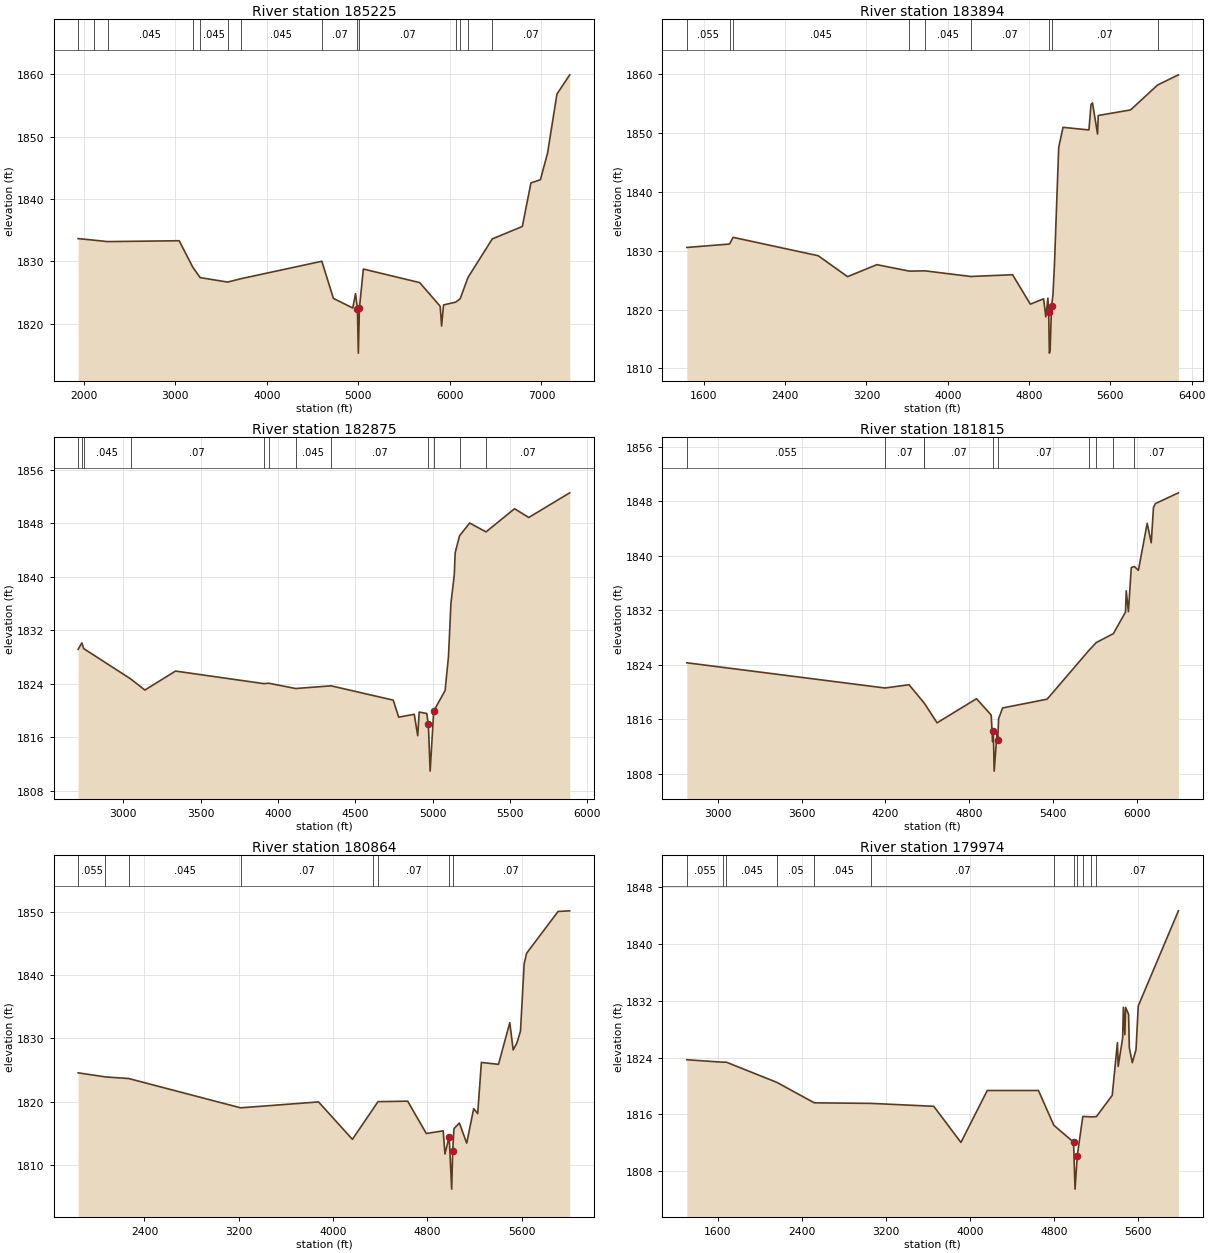
Type RM Length L Ch R = 1 ,185225  ,1331,1331,1331
BEGIN DESCRIPTION:
Mapping XS 903fc2af
END DESCRIPTION:
XS GIS Cut Line= 4
      1510910.86      6845312.46      1512631.01      6843788.65
      1512770.18      6843037.56      1514010.63      6841089.93
#Sta/Elev= 30
  1938.1 1833.65  2111.5  1833.4  2260.9 1833.17    3042 1833.31  3192.3 1829.03
  3271.2  1827.4  3572.4 1826.68  3713.5 1827.21  4600.6 1830.02  4727.3 1824.06
  4938.5 1822.53    4969 1824.82  4989.4 1822.41  4999.5 1815.29  5011.3 1822.51
  5054.2 1828.77  5669.6  1826.6  5893.9  1822.8  5909.1 1819.64  5930.3 1823.02
  6062.8 1823.46  6112.2 1824.01    6197 1827.41  6462.7  1833.6  6791.2  1835.6
  6885.1 1842.58  6988.4 1843.09  7067.1 1847.38  7169.1 1856.82  7309.1 1859.91
#Mann= 14 ,-1 , 0
  1938.1    .055       0  2111.5     .07       0  2260.9    .045       0
  3192.3     .07       0  3271.2    .045       0  3572.4     .07       0
  3713.5    .045       0  4600.6     .07       0  4989.4    .045       0
  5011.3     .07       0  6062.8     .05       0  6112.2     .07       0
    6197     .05       0  6462.7     .07       0
Bank Sta=4989.4,5011.3
XS Rating Curve= 0 ,0
Exp/Cntr=0.3,0.1

Type RM Length L Ch R = 1 ,183894  ,1019,1019,1019
BEGIN DESCRIPTION:
Mapping XS b808c263
END DESCRIPTION:
XS GIS Cut Line= 4
      1511293.35      6845559.59      1513105.27      6844354.15
      1513828.93      6843181.01      1514757.77      6842295.57
#Sta/Elev= 30
  1432.1 1830.57  1852.6 1831.15    1888 1832.29  2725.5 1829.16  3014.1  1825.6
  3302.6 1827.64  3621.9 1826.54    3776 1826.59  4227.1 1825.63  4637.8 1825.93
  4812.8 1820.92  4943.3 1821.83  4965.3 1818.75  4985.6 1821.95  4993.3 1819.64
  5000.2 1812.59  5007.4 1813.07  5021.6 1820.63  5035.8 1822.55  5049.9 1827.53
    5092 1847.58  5134.5 1851.01  5389.3 1850.56  5410.3 1854.91  5424.5 1855.17
  5474.2 1849.87  5481.1 1853.02  5799.4 1853.97  6065.4 1858.21    6270 1859.94
#Mann= 9 ,-1 , 0
  1432.1    .055       0  1852.6     .07       0    1888    .045       0
  3621.9     .07       0    3776    .045       0  4227.1     .07       0
  4993.3    .045       0  5021.6     .07       0  6065.4    .045       0
Bank Sta=4993.3,5021.6
XS Rating Curve= 0 ,0
Exp/Cntr=0.3,0.1

Type RM Length L Ch R = 1 ,182875  ,1060,1060,1060
BEGIN DESCRIPTION:
Mapping XS bd5f3013
END DESCRIPTION:
XS GIS Cut Line= 4
        1512680.      6845543.38      1514153.54      6844061.04
      1514467.56      6843884.24      1514992.15      6843380.63
#Sta/Elev= 30
  2708.3 1829.15  2732.8 1830.12  2744.1 1829.27    3048 1824.73  3139.9 1823.06
  3337.9  1825.9  3909.2 1824.02  3940.9 1824.08  4113.6 1823.29  4343.5 1823.69
  4745.1 1821.55  4780.4    1819  4881.1 1819.43  4903.4 1816.22  4912.9 1819.76
    4962 1819.55  4972.2 1817.91  4983.7 1810.92  5006.7 1819.91  5080.5 1822.99
  5102.2 1828.09  5118.1 1836.05  5139.8 1840.35  5145.5 1843.62  5173.8 1846.16
  5239.1 1848.07  5344.9 1846.74  5529.3 1850.21  5621.2  1848.9    5886 1852.59
#Mann= 12 ,-1 , 0
  2708.3    .055       0  2732.8     .07       0  2744.1    .045       0
    3048     .07       0  3909.2    .045       0  3940.9     .07       0
  4113.6    .045       0  4343.5     .07       0  4972.2    .045       0
  5006.7     .07       0  5173.8     .05       0  5344.9     .07       0
Bank Sta=4972.2,5006.7
XS Rating Curve= 0 ,0
Exp/Cntr=0.3,0.1

Type RM Length L Ch R = 1 ,181815  ,951,951,951
BEGIN DESCRIPTION:
Mapping XS 58f13765
END DESCRIPTION:
XS GIS Cut Line= 4
      1513205.63      6846066.25      1514632.71      6845316.25
      1514835.87      6844717.47      1515096.29      6843467.48
#Sta/Elev= 30
  2777.2 1824.31  4196.6 1820.61  4369.3 1821.09  4476.6 1818.42    4479 1818.36
    4570  1815.5  4852.6 1819.04  4957.7 1816.63  4967.6 1812.73  4972.9 1814.31
  4978.9 1808.41    4999 1813.94  5004.3 1813.03  5010.5  1816.1  5039.2 1817.68
  5358.2 1818.97  5660.3 1826.19  5709.6 1827.27  5832.9 1828.59  5919.7 1831.76
  5924.8 1834.87  5940.4 1831.81  5960.9 1838.29  5982.5 1838.44    6012 1837.88
  6074.9 1844.78  6103.9 1841.92  6119.9 1847.12  6134.5 1847.68  6298.5 1849.25
#Mann= 10 ,-1 , 0
  2777.2    .055       0  4196.6     .07       0  4476.6    .045       0
    4479     .07       0  4972.9    .045       0  5004.3     .07       0
  5660.3     .05       0  5709.6     .07       0  5832.9     .05       0
  5982.5     .07       0
Bank Sta=4972.9,5004.3
XS Rating Curve= 0 ,0
Exp/Cntr=0.3,0.1

Type RM Length L Ch R = 1 ,180864  ,890,890,890
BEGIN DESCRIPTION:
Mapping XS 6eb1561b
END DESCRIPTION:
XS GIS Cut Line= 5
      1513059.84      6846284.99      1514106.15      6846026.11
      1515304.62      6845255.66      1515695.25      6844691.43
      1515955.65      6843745.28
#Sta/Elev= 30
  1837.3 1824.56  2069.5 1823.91  2265.5 1823.66  3214.9 1819.03  3876.7 1819.96
    4164 1814.05  4336.3 1818.77  4380.9    1820  4632.8 1820.08  4790.9 1814.97
  4934.1 1815.39    4949 1811.73  4984.8 1814.49    5006 1806.18  5014.5 1812.17
  5025.2 1815.72  5071.2 1816.63  5133.4 1813.45  5192.7  1818.9  5226.8 1818.11
  5257.9  1826.2  5403.1  1825.9    5499 1832.49  5527.6 1828.18  5558.7 1829.24
  5589.8 1831.17  5620.9  1841.8  5641.7 1843.46  5908.5 1850.06  6007.5 1850.16
#Mann= 8 ,-1 , 0
  1837.3    .055       0  2069.5    .035       0  2265.5    .045       0
  3214.9     .07       0  4336.3     .05       0  4380.9     .07       0
  4984.8    .045       0  5014.5     .07       0
Bank Sta=4984.8,5014.5
XS Rating Curve= 0 ,0
Exp/Cntr=0.3,0.1

Type RM Length L Ch R = 1 ,179974  ,1575,1575,1575
BEGIN DESCRIPTION:
Mapping XS 23664138
END DESCRIPTION:
XS GIS Cut Line= 4
      1512939.96      6846456.88      1514152.29      6846386.24
      1516322.85      6845237.65      1517046.81      6844539.73
#Sta/Elev= 30
  1307.4 1823.69  1650.9 1823.34  1682.5 1823.35  2164.3  1820.5  2519.4 1817.62
  3061.7 1817.54  3656.2 1817.13  3914.6 1812.04  4165.3 1819.36  4651.8 1819.36
  4798.2 1814.46  4985.8 1812.08    5000 1805.46  5021.3 1810.18  5073.7  1815.7
  5153.7 1815.64  5202.8 1815.67  5353.7 1818.68  5403.1 1826.11  5410.3 1822.75
  5452.8 1826.77  5459.7 1831.08  5473.8 1827.22  5480.8 1831.07  5509.1  1830.1
  5516.3 1825.36  5544.6 1823.28  5579.8  1825.1  5601.2 1831.27  5983.1 1844.67
#Mann= 12 ,-1 , 0
  1307.4    .055       0  1650.9    .035       0  1682.5    .045       0
  2164.3     .05       0  2519.4    .045       0  3061.7     .07       0
  4798.2     .16       0  4985.8    .045       0  5021.3     .16       0
  5073.7     .07       0  5153.7     .05       0  5202.8     .07       0
Bank Sta=4985.8,5021.3
XS Rating Curve= 0 ,0
Exp/Cntr=0.3,0.1