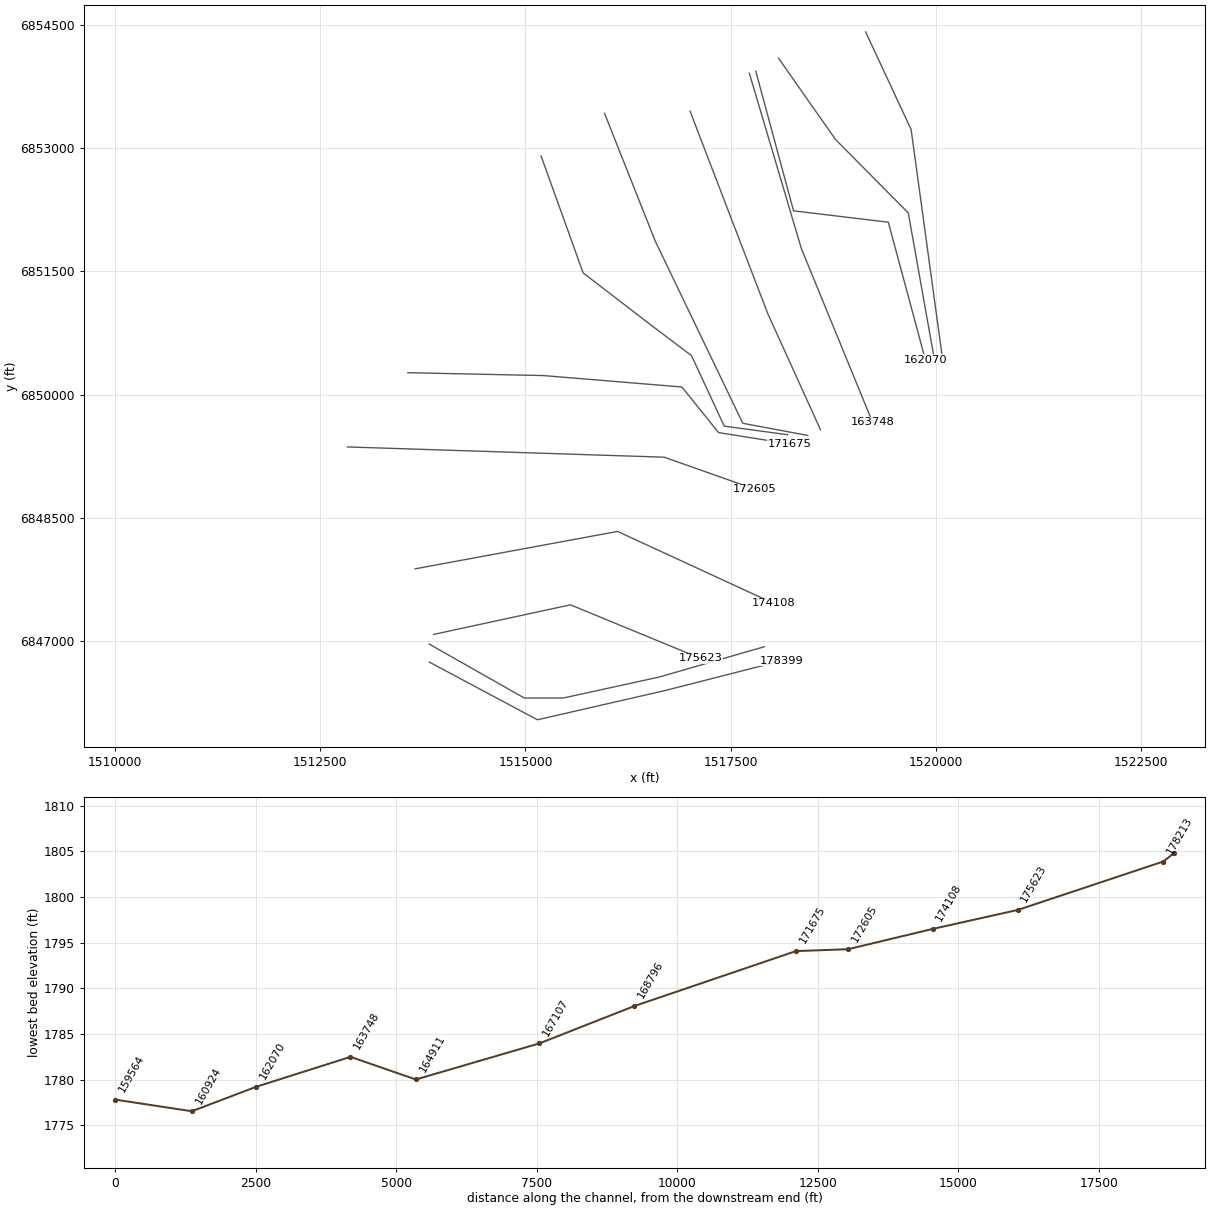
HEC-RAS study MULBERRY CREEK.prj: MULBERRY CREEK Base Level Engineering

--- MULBERRY CREEK.g01 (geometry) --- (continued)

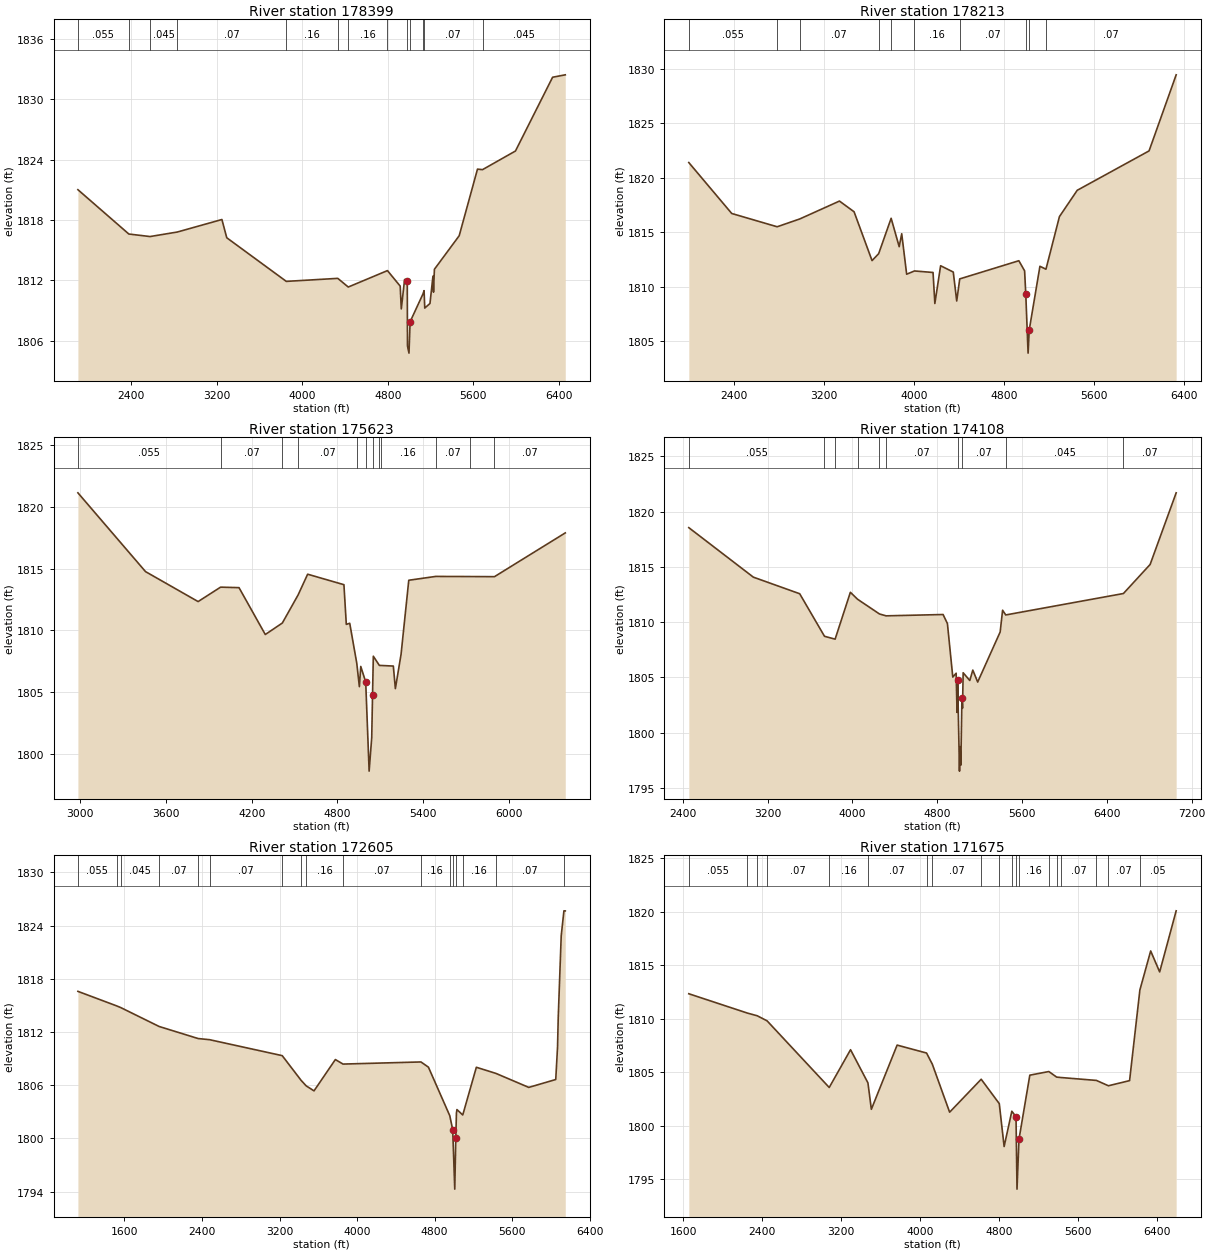
Type RM Length L Ch R = 1 ,178399  ,186,186,186
BEGIN DESCRIPTION:
Mapping XS 10347bfc
END DESCRIPTION:
XS GIS Cut Line= 4
      1513828.02      6846742.88      1515145.77      6846039.73
      1516692.64       6846393.9      1518119.69      6846758.48
#Sta/Elev= 30
    1905 1821.01    2381 1816.61    2579 1816.36  2834.2 1816.81  3250.4 1818.05
  3295.7 1816.24  3852.1 1811.91  4332.9 1812.21  4430.9 1811.35  4797.1 1812.98
  4916.1 1811.44  4926.4 1809.18  4957.2  1812.1  4982.1 1811.97  4984.2 1805.49
  4998.3 1804.79  5008.6  1807.9  5129.7 1810.68  5139.2 1810.99  5145.7 1809.26
  5194.4 1809.72  5222.2 1812.43  5227.4 1810.84  5235.7 1813.11  5467.3 1816.44
  5638.2 1823.05  5685.4    1823  5993.1 1824.85    6340 1832.17  6458.4 1832.41
#Mann= 13 ,-1 , 0
    1905    .055       0    2381    .035       0    2579    .045       0
  2834.2     .07       0  3852.1     .16       0  4332.9     .07       0
  4430.9     .16       0  4797.1     .07       0  4982.1    .045       0
  5008.6     .07       0  5129.7     .05       0  5139.2     .07       0
  5685.4    .045       0
Bank Sta=4982.1,5008.6
XS Rating Curve= 0 ,0
Exp/Cntr=0.3,0.1

Type RM Length L Ch R = 1 ,178213  ,2590,2590,2590
BEGIN DESCRIPTION:
Mapping XS 36751e4f
END DESCRIPTION:
XS GIS Cut Line= 5
      1513828.05      6846961.61      1514984.31      6846305.36
      1515463.48      6846305.36      1516630.14      6846560.57
      1517910.74      6846930.17
#Sta/Elev= 30
  1994.8 1821.41  2376.7 1816.73  2780.8 1815.51  2982.5 1816.23    3335 1817.87
    3465 1816.89    3625  1812.4    3684 1813.04  3794.9 1816.29  3866.5 1813.68
    3889 1814.87  3932.9 1811.15  4002.3 1811.45  4167.6 1811.31  4183.8 1808.46
    4235 1811.93  4347.6 1811.35  4378.3 1808.69  4405.2 1810.72    4931 1812.39
  4982.2 1811.46  4992.5 1809.37  5013.2  1803.9  5023.6 1806.04  5118.6 1811.88
  5172.2 1811.61    5292 1816.44  5450.3 1818.86  6089.4 1822.48  6330.6 1829.47
#Mann= 10 ,-1 , 0
  1994.8    .055       0  2780.8    .035       0  2982.5     .07       0
    3684     .16       0  3794.9     .07       0  4002.3     .16       0
  4405.2     .07       0  4992.5    .045       0  5023.6     .07       0
  5172.2     .07       0
Bank Sta=4992.5,5023.6
XS Rating Curve= 0 ,0
Exp/Cntr=0.3,0.1

Type RM Length L Ch R = 1 ,175623  ,1515,1515,1515
BEGIN DESCRIPTION:
Mapping XS 72008d7f
END DESCRIPTION:
XS GIS Cut Line= 3
      1513882.01      6847079.59      1515548.69      6847439.84
      1517128.54       6846788.8
#Sta/Elev= 30
  2982.5 1821.16  3456.2 1814.77  3824.5 1812.34  3981.9 1813.51    4111 1813.47
  4295.1 1809.67  4414.4  1810.6    4525 1812.88  4591.8 1814.56  4845.9 1813.71
  4862.6 1810.49  4886.6 1810.58  4935.9 1807.34  4954.1 1805.44  4963.8 1807.08
  4998.5 1805.82  5022.5 1798.59  5040.6 1801.31  5046.4 1804.78  5051.8 1807.91
  5094.4 1807.16  5104.4 1807.16    5192 1807.11  5206.3 1805.28  5246.1 1808.06
  5300.2 1814.07  5488.3 1814.38  5729.2 1814.37  5900.5 1814.36  6396.4 1817.91
#Mann= 12 ,-1 , 0
  2982.5    .055       0  3981.9     .07       0  4414.4     .16       0
    4525     .07       0  4935.9     .16       0  4998.5    .045       0
  5046.4     .16       0  5094.4     .07       0  5104.4     .16       0
  5488.3     .07       0  5729.2     .05       0  5900.5     .07       0
Bank Sta=4998.5,5046.4
XS Rating Curve= 0 ,0
Exp/Cntr=0.3,0.1

Type RM Length L Ch R = 1 ,174108  ,1503,1503,1503
BEGIN DESCRIPTION:
Mapping XS dbb689de
END DESCRIPTION:
XS GIS Cut Line= 3
      1513656.38      6847878.21      1516121.61      6848333.93
      1518019.49      6847458.63
#Sta/Elev= 30
  2456.4 1818.54  3065.2 1814.06  3502.4 1812.56  3736.3 1808.71  3836.5 1808.45
  3980.4 1812.69  4048.4 1812.06  4254.8 1810.73  4317.3 1810.56    4855 1810.68
  4895.7 1809.86  4946.5 1805.02  4978.1 1805.37  4986.6 1801.82  4992.1 1804.78
  5009.5 1796.51    5015 1798.73  5022.2 1797.05  5032.5 1803.13    5038  1802.2
  5044.2 1805.41  5106.8 1804.71  5135.3 1805.65  5181.2 1804.57  5393.3  1809.1
  5416.2 1811.07  5445.8 1810.64    6556 1812.58  6807.9 1815.21  7053.4 1821.69
#Mann= 10 ,-1 , 0
  2456.4    .055       0  3736.3     .07       0  3836.5     .16       0
  4048.4     .07       0  4254.8     .16       0  4317.3     .07       0
  4992.1    .045       0  5032.5     .07       0  5445.8    .045       0
    6556     .07       0
Bank Sta=4992.1,5032.5
XS Rating Curve= 0 ,0
Exp/Cntr=0.3,0.1

Type RM Length L Ch R = 1 ,172605  ,930,930,930
BEGIN DESCRIPTION:
Mapping XS 30b6fc36
END DESCRIPTION:
XS GIS Cut Line= 3
      1512830.01        6849363.      1516689.61      6849238.16
      1517790.12      6848849.33
#Sta/Elev= 30
  1119.9 1816.59  1519.9 1814.95  1562.1 1814.76  1957.8 1812.63  2360.2 1811.27
  2478.5 1811.14  3228.2 1809.34  3423.4 1806.55  3475.8 1805.93  3556.2 1805.37
  3776.3  1808.9  3855.5 1808.39  4659.5 1808.63  4736.8 1808.04  4956.9 1802.57
  4987.2    1801  5008.4 1794.29  5019.1 1800.06  5025.7 1802.87    5031 1803.26
  5090.9 1802.65  5231.2 1808.03  5432.9 1807.34  5772.1 1805.76  6050.4 1806.65
    6069 1810.33    6076 1813.62  6106.9 1822.87  6134.9 1825.67  6148.7 1825.66
#Mann= 17 ,-1 , 0
  1119.9    .055       0  1519.9     .07       0  1562.1    .045       0
  1957.8     .07       0  2360.2    .045       0  2478.5     .07       0
  3228.2     .16       0  3423.4     .07       0  3475.8     .16       0
  3855.5     .07       0  4659.5     .16       0  4956.9     .07       0
  4987.2    .045       0  5019.1     .07       0  5090.9     .16       0
  5432.9     .07       0  6134.9     .05       0
Bank Sta=4987.2,5019.1
XS Rating Curve= 0 ,0
Exp/Cntr=0.3,0.1

Type RM Length L Ch R = 1 ,171675  ,2879,2879,2879
BEGIN DESCRIPTION:
Mapping XS 4660cccb
END DESCRIPTION:
XS GIS Cut Line= 5
      1513567.23      6850267.16      1515216.52      6850232.44
      1516905.12      6850093.12      1517351.93        6849538.
      1518219.99      6849399.11
#Sta/Elev= 30
    1656 1812.34  2250.3 1810.53  2349.4 1810.28  2448.5 1809.81    3078 1803.58
  3294.1 1807.11  3470.2 1804.01  3504.8 1801.54  3765.7 1807.54  4063.7  1806.8
    4122 1805.76  4297.5 1801.27  4617.2 1804.35  4800.3 1802.07  4849.4 1798.06
  4927.3 1801.36  4969.8 1800.84  4979.8 1794.08    5000 1798.75  5109.6 1804.73
  5301.9 1805.07  5381.4 1804.55  5424.9 1804.51  5783.8 1804.24  5905.7 1803.74
  6119.9 1804.22  6224.2 1812.69  6333.5 1816.34  6424.6 1814.38  6591.7 1820.09
#Mann= 19 ,-1 , 0
    1656    .055       0  2250.3     .07       0  2349.4    .045       0
  2448.5     .07       0    3078     .16       0  3470.2     .07       0
  4063.7     .16       0    4122     .07       0  4617.2     .16       0
  4800.3     .07       0  4927.3     .16       0  4969.8    .045       0
    5000     .16       0  5301.9     .07       0  5381.4     .16       0
  5424.9     .07       0  5783.8     .16       0  5905.7     .07       0
  6224.2     .05       0
Bank Sta=4969.8,5000
XS Rating Curve= 0 ,0
Exp/Cntr=0.3,0.1

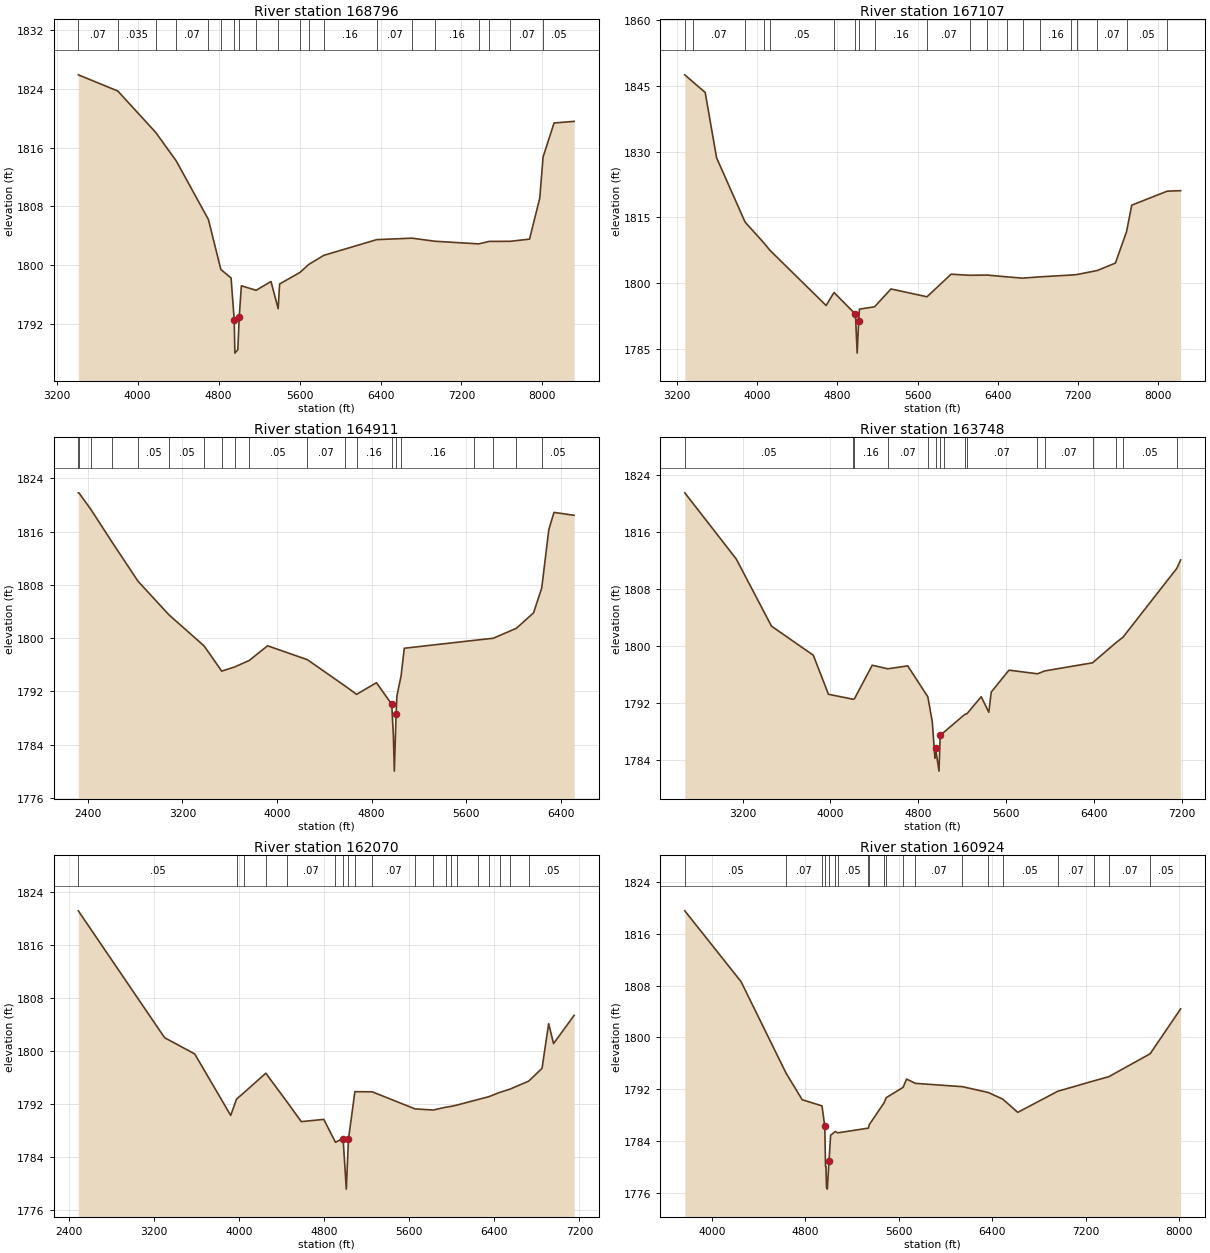
Type RM Length L Ch R = 1 ,168796  ,1689,1689,1689
BEGIN DESCRIPTION:
Mapping XS 5720123f
END DESCRIPTION:
XS GIS Cut Line= 6
      1515190.47      6852906.07      1515702.63      6851482.44
      1516527.28      6850848.76      1517022.07       6850475.5
      1517421.38      6849616.12      1518191.95      6849512.23
#Sta/Elev= 30
    3415 1825.91  3804.6 1823.71  4178.3 1818.09  4381.3 1814.22    4700 1806.23
  4822.8 1799.43  4923.8 1798.28  4954.9 1792.58  4961.2 1788.05  4990.2 1788.51
  5004.7 1793.02  5025.5 1797.21    5171  1796.6  5318.3 1797.79  5388.9  1794.1
  5403.4 1797.46  5605.9 1799.04  5689.2  1800.1  5839.7 1801.35  6362.2 1803.49
  6710.6 1803.69  6937.7 1803.27    7369 1802.91  7474.9 1803.25  7681.2 1803.26
    7872 1803.56  7972.9 1809.12  8005.9 1814.73  8114.2 1819.36  8312.9 1819.58
#Mann= 20 ,-1 , 0
    3415     .07       0  3804.6    .035       0  4178.3     .05       0
  4381.3     .07       0    4700     .05       0  4822.8     .16       0
  4954.9    .045       0  5004.7     .16       0    5171     .16       0
  5388.9     .07       0  5605.9     .16       0  5689.2     .07       0
  5839.7     .16       0  6362.2     .07       0  6710.6     .16       0
  6937.7     .16       0    7369     .07       0  7474.9     .16       0
  7681.2     .07       0  8005.9     .05       0
Bank Sta=4954.9,5004.7
XS Rating Curve= 0 ,0
Exp/Cntr=0.3,0.1

Type RM Length L Ch R = 1 ,167107  ,2196,2196,2196
BEGIN DESCRIPTION:
Mapping XS bbc44844
END DESCRIPTION:
XS GIS Cut Line= 4
      1515963.06      6853426.86      1516579.36      6851873.07
      1517647.07      6849650.85      1518437.03      6849503.27
#Sta/Elev= 30
  3281.2 1847.53  3360.9 1845.94  3484.4  1843.5  3597.9 1828.58  3881.9  1813.9
  4070.1 1809.11  4128.7 1807.47  4689.3 1794.84  4767.9 1797.81  4981.7 1792.86
  4998.8 1783.96  5013.9 1791.34  5021.4 1794.01  5171.9 1794.54  5335.6 1798.62
  5694.5 1796.83  5934.7 1801.99  6119.5 1801.74  6295.1 1801.79  6490.3 1801.38
  6646.4 1801.09  6818.5 1801.38  7132.6  1801.8  7190.9 1801.92  7392.9 1802.84
  7571.8 1804.53  7682.5 1811.66  7734.8 1817.76  8087.8 1820.95  8221.8 1821.07
#Mann= 20 ,-1 , 0
  3281.2     .05       0  3360.9     .07       0  3881.9     .05       0
  4070.1     .07       0  4128.7     .05       0  4767.9     .16       0
  4981.7    .045       0  5013.9     .16       0  5171.9     .16       0
  5694.5     .07       0  6119.5     .16       0  6295.1     .07       0
  6490.3     .16       0  6646.4     .07       0  6818.5     .16       0
  7132.6     .07       0  7190.9     .16       0  7392.9     .07       0
  7682.5     .05       0  8087.8     .05       0
Bank Sta=4981.7,5013.9
XS Rating Curve= 0 ,0
Exp/Cntr=0.3,0.1

Type RM Length L Ch R = 1 ,164911  ,1163,1163,1163
BEGIN DESCRIPTION:
Mapping XS d5652907
END DESCRIPTION:
XS GIS Cut Line= 3
       1517004.7      6853452.97      1517950.89      6850987.65
      1518593.18      6849572.88
#Sta/Elev= 30
  2319.2 1821.84  2324.2 1821.84  2427.9 1819.28  2603.6 1814.46  2823.4 1808.57
  3084.8 1803.52  3383.2 1798.83  3532.2 1795.04  3640.8 1795.66  3764.9 1796.64
    3920 1798.85  4256.9 1796.76  4575.7 1792.81    4673 1791.55    4841  1793.3
  4970.5 1790.05  4984.4 1785.28  4992.4 1780.01  5007.5 1788.66  5014.4 1791.33
  5049.7 1794.35  5076.7 1798.48  5669.3 1799.67  5829.2 1799.98    6025 1801.48
  6170.1  1803.8  6239.4 1807.54  6299.3 1816.31  6343.2  1818.9  6513.6 1818.46
#Mann= 20 ,-1 , 0
  2319.2     .05       0  2324.2     .07       0  2427.9     .05       0
  2603.6     .07       0  2823.4     .05       0  3084.8     .05       0
  3383.2     .07       0  3532.2     .05       0  3640.8     .07       0
  3764.9     .05       0  4256.9     .07       0  4575.7     .05       0
    4673     .16       0  4970.5    .045       0  5007.5     .16       0
  5049.7     .16       0  5669.3     .07       0  5829.2     .16       0
    6025     .07       0  6239.4     .05       0
Bank Sta=4970.5,5007.5
XS Rating Curve= 0 ,0
Exp/Cntr=0.3,0.1

Type RM Length L Ch R = 1 ,163748  ,1678,1678,1678
BEGIN DESCRIPTION:
Mapping XS 11c6dd85
END DESCRIPTION:
XS GIS Cut Line= 3
      1517726.93      6853914.31      1518360.61      6851778.88
      1519228.21      6849661.94
#Sta/Elev= 30
  2674.5 1821.46  3143.8 1812.18  3463.6  1802.8  3844.7 1798.72  3982.8 1793.25
  4209.3 1792.55  4219.6 1792.63  4381.3 1797.32  4523.5 1796.82  4704.7 1797.23
  4887.7  1792.9  4928.3  1789.4  4952.3  1784.3  4957.7 1785.76  4989.4 1782.49
  5000.2 1787.61  5034.3 1787.94  5223.8 1790.43  5243.6 1790.52    5374 1792.91
  5443.3 1790.73  5464.9 1793.56    5627 1796.63  5886.4 1796.12  5951.8 1796.52
  6387.9 1797.66  6597.3 1800.43  6664.8 1801.24  7155.8  1810.9  7189.8 1812.06
#Mann= 16 ,-1 , 0
  2674.5     .05       0  4209.3     .07       0  4219.6     .16       0
  4523.5     .07       0  4887.7     .16       0  4957.7    .045       0
  5000.2     .16       0  5034.3     .05       0  5223.8     .16       0
  5243.6     .07       0  5886.4     .16       0  5951.8     .07       0
  6387.9     .16       0  6597.3     .07       0  6664.8     .05       0
  7155.8     .07       0
Bank Sta=4957.7,5000.2
XS Rating Curve= 0 ,0
Exp/Cntr=0.3,0.1

Type RM Length L Ch R = 1 ,162070  ,1146,1146,1146
BEGIN DESCRIPTION:
Mapping XS aa153a98
END DESCRIPTION:
XS GIS Cut Line= 4
      1517805.05      6853940.37      1518265.13      6852238.95
      1519419.64      6852100.06      1519870.52       6850426.6
#Sta/Elev= 30
  2492.1 1821.22  3302.6 1802.07  3585.6 1799.62  3923.7 1790.34  3978.6  1792.8
  4052.3 1793.83  4253.6 1796.71  4452.8 1792.38  4586.9  1789.4  4798.4 1789.74
    4908 1786.28  4979.7 1786.85  5009.9 1779.21    5030 1786.73  5090.5 1793.92
  5253.2  1793.9  5655.4 1791.32  5828.2 1791.15  5942.4 1791.57    5995  1791.7
  6046.6 1791.89  6247.9 1792.74  6348.6 1793.16  6449.3  1793.8  6549.9 1794.32
  6723.3 1795.51  6848.8 1797.44    6911 1804.19    6957 1801.18  7150.6 1805.45
#Mann= 20 ,-1 , 0
  2492.1     .05       0  3978.6     .07       0  4052.3     .16       0
  4253.6     .05       0  4452.8     .07       0    4908     .07       0
  4979.7    .045       0    5030     .07       0  5090.5     .05       0
  5253.2     .07       0  5655.4     .05       0  5828.2     .07       0
  5942.4     .05       0    5995     .07       0  6046.6     .05       0
  6247.9     .07       0  6348.6     .16       0  6449.3     .16       0
  6549.9     .07       0  6723.3     .05       0
Bank Sta=4979.7,5030
XS Rating Curve= 0 ,0
Exp/Cntr=0.3,0.1

Type RM Length L Ch R = 1 ,160924  ,1360,1360,1360
BEGIN DESCRIPTION:
Mapping XS 38d7f9eb
END DESCRIPTION:
XS GIS Cut Line= 4
      1518082.86      6854096.55      1518777.28      6853107.01
       1519662.7      6852212.91      1519974.88      6850461.22
#Sta/Elev= 30
  3766.6 1819.55  4248.2 1808.61  4633.3 1794.48    4772 1790.35  4941.7  1789.4
  4965.5 1786.25  4971.8 1780.02  4975.5 1780.02  4980.2 1776.83  4987.3 1776.53
  5001.5 1780.81  5015.6 1784.87  5056.6 1785.44  5075.6 1785.23  5339.4 1785.96
  5346.2 1786.49  5473.6 1789.88  5491.1 1790.66  5635.9 1792.26  5666.1 1793.54
    5742 1792.88  6143.9 1792.37  6365.9 1791.47  6489.9 1790.44  6618.6  1788.4
  6959.7 1791.65  7270.2 1793.27  7398.2 1793.91  7751.8 1797.45  8013.1 1804.39
#Mann= 20 ,-1 , 0
  3766.6     .05       0  4633.3     .07       0  4941.7     .16       0
  4965.5    .045       0  5001.5     .16       0  5056.6     .07       0
  5075.6     .05       0  5339.4     .07       0  5346.2     .05       0
  5473.6     .07       0  5491.1     .05       0  5635.9     .16       0
    5742     .07       0  6143.9     .05       0  6365.9     .07       0
  6489.9     .05       0  6959.7     .07       0  7270.2     .16       0
  7398.2     .07       0  7751.8     .05       0
Bank Sta=4965.5,5001.5
XS Rating Curve= 0 ,0
Exp/Cntr=0.3,0.1

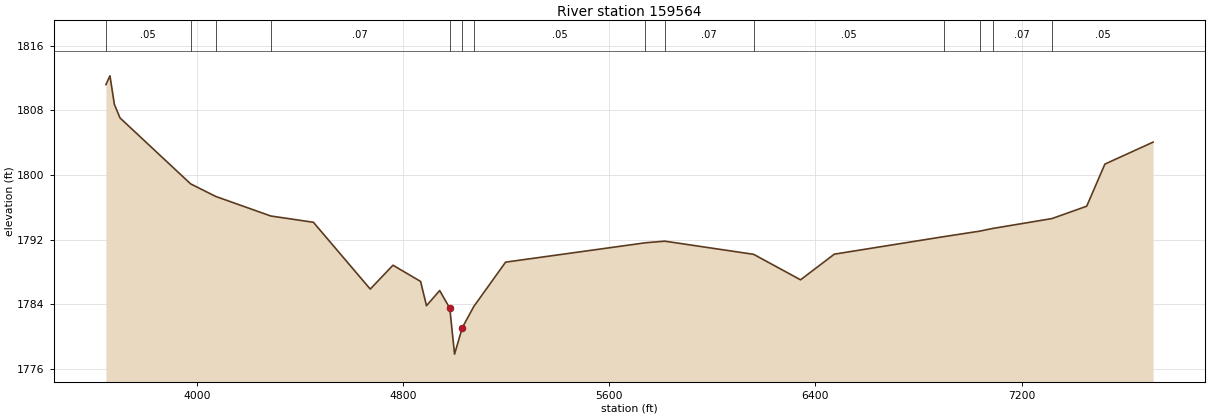
Type RM Length L Ch R = 1 ,159564  ,1673,1673,1673
BEGIN DESCRIPTION:
Mapping XS 4619ea80
END DESCRIPTION:
XS GIS Cut Line= 3
      1519143.57      6854417.79      1519697.42      6853228.54
      1520070.68      6850502.88
#Sta/Elev= 30
  3647.2  1811.2    3663 1812.29  3680.1 1808.75  3702.1 1807.07    3976  1798.9
  4073.5 1797.34  4286.8 1794.92  4452.3 1794.14  4672.9 1785.86  4761.1 1788.82
  4868.2 1786.81  4891.1  1783.8  4942.3 1785.68  4981.5 1783.49    5000  1777.8
  5030.3  1781.1  5074.6  1783.7    5198  1789.2  5740.7  1791.6  5815.4  1791.8
  6160.3 1790.17  6342.4 1787.01  6473.6 1790.19  6898.5 1792.36  7037.3 1793.04
  7087.3 1793.37    7318  1794.6  7452.7 1796.13  7523.3 1801.35  7710.2 1804.07
#Mann= 14 ,-1 , 0
  3647.2     .05       0    3976     .07       0  4073.5     .16       0
  4286.8     .07       0  4981.5    .045       0  5030.3     .07       0
  5074.6     .05       0  5740.7     .16       0  5815.4     .07       0
  6160.3     .05       0  6898.5     .07       0  7037.3     .16       0
  7087.3     .07       0    7318     .05       0
Bank Sta=4981.5,5030.3
XS Rating Curve= 0 ,0
Exp/Cntr=0.3,0.1