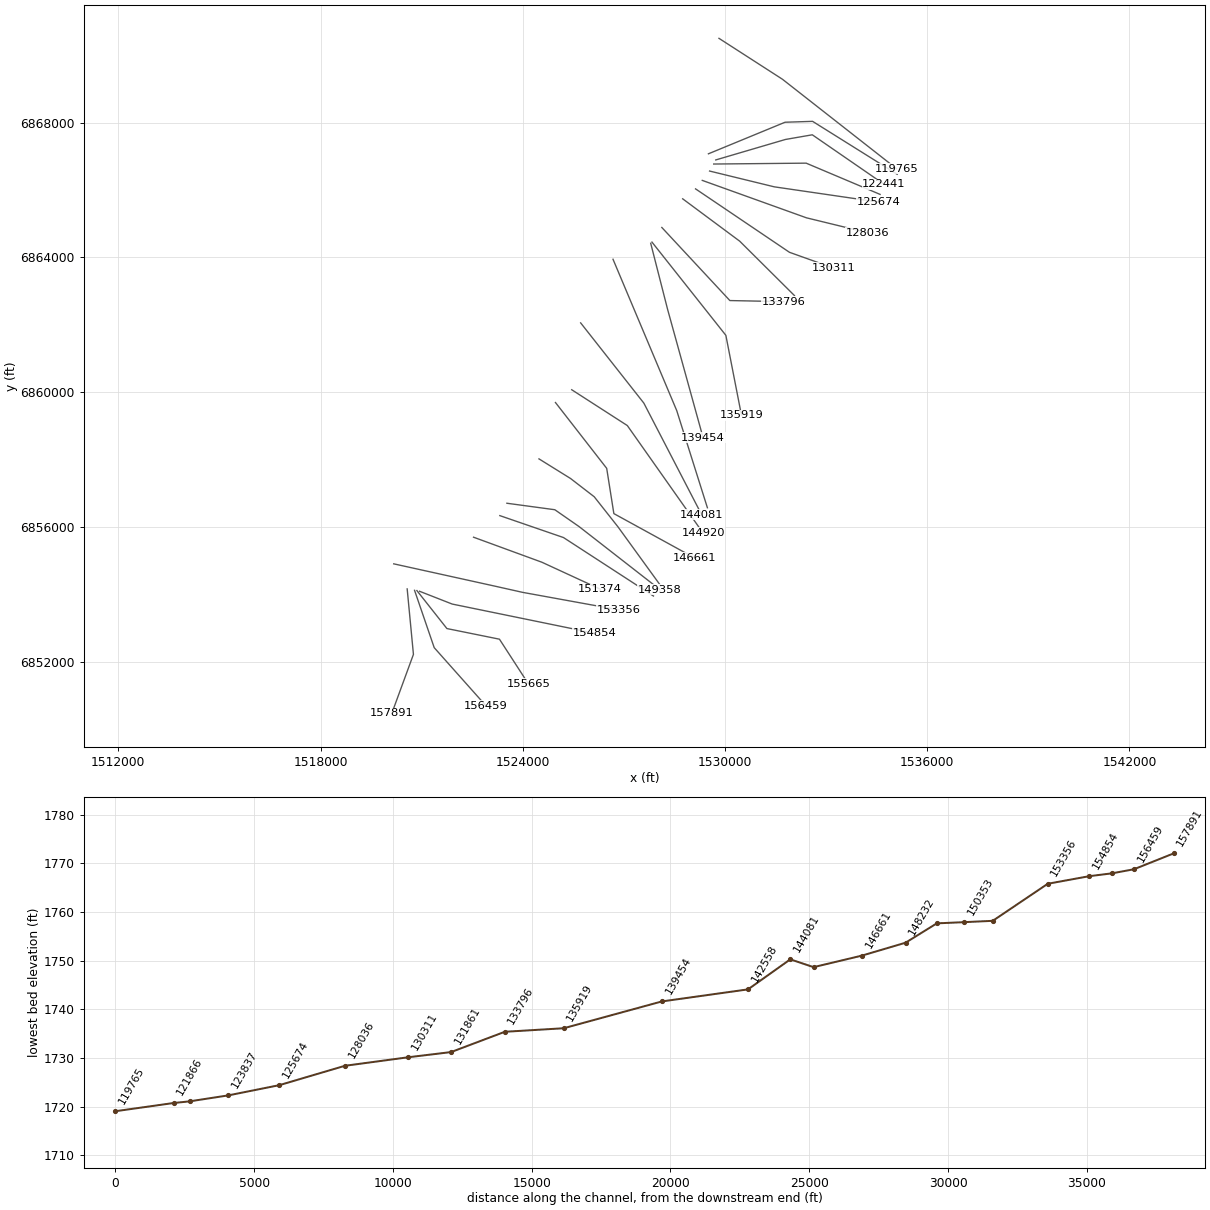
HEC-RAS study MULBERRY CREEK.prj: MULBERRY CREEK Base Level Engineering

--- MULBERRY CREEK.g01 (geometry) --- (continued)

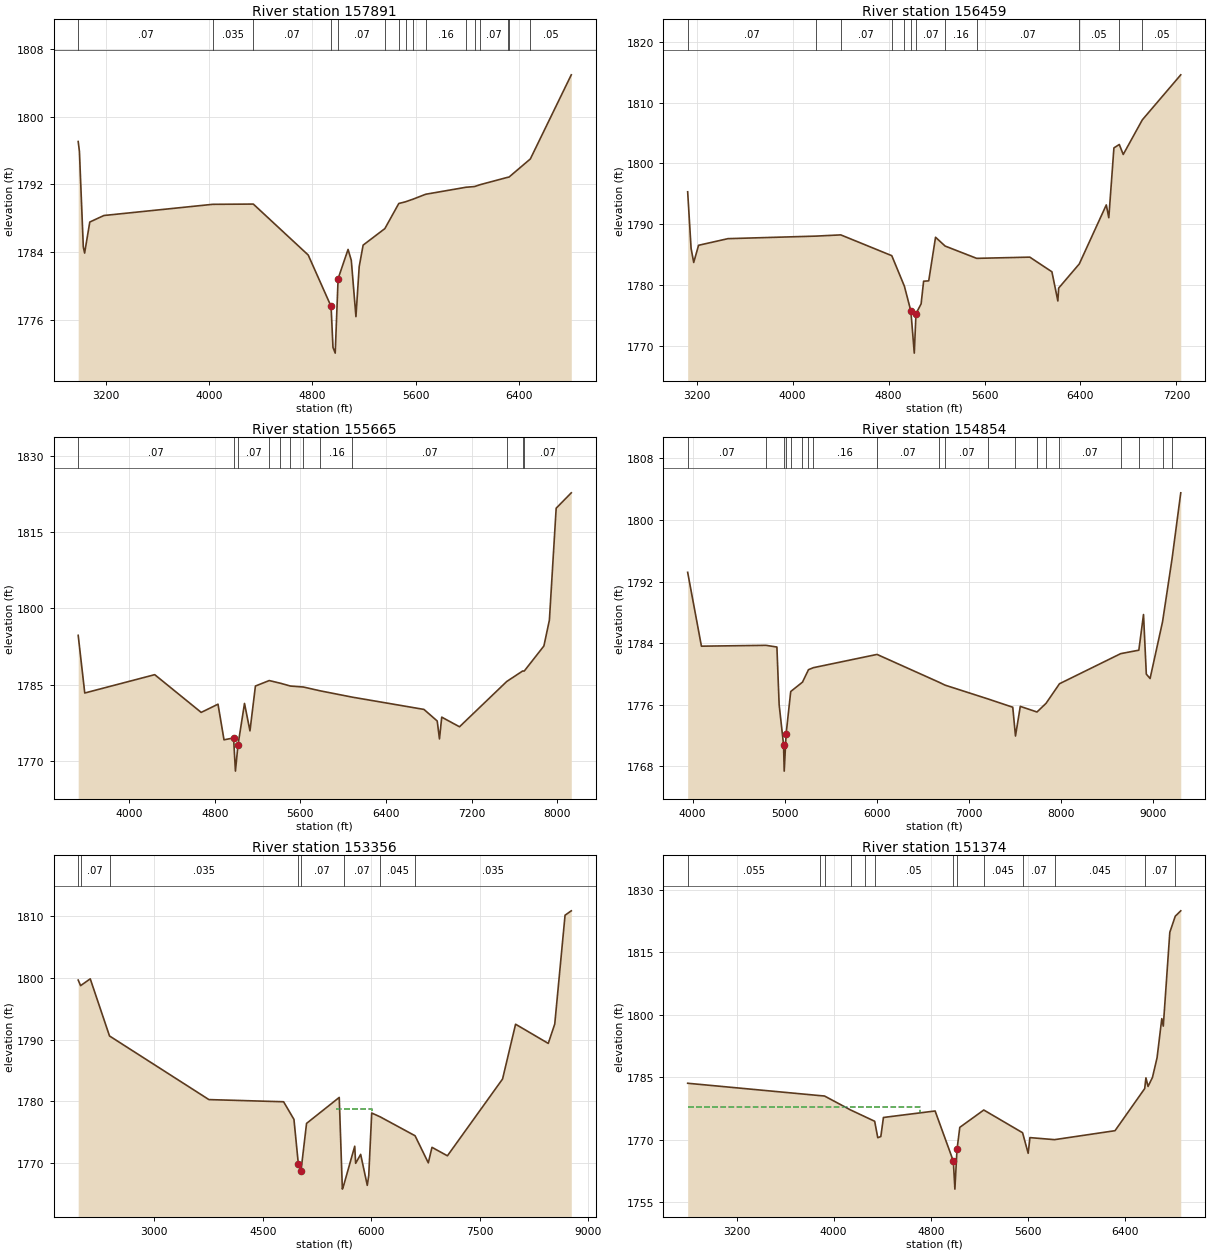
Type RM Length L Ch R = 1 ,157891  ,1432,1432,1432
BEGIN DESCRIPTION:
Mapping XS 9b4fe588
END DESCRIPTION:
XS GIS Cut Line= 3
      1520570.64      6854157.43      1520756.45      6852212.91
      1520114.74      6850461.22
#Sta/Elev= 30
  2987.1 1797.06  2996.6  1795.9  3026.7 1784.61  3036.8 1783.88  3076.9 1787.55
  3186.5 1788.32  4028.4 1789.64  4343.4 1789.67  4768.6 1783.65  4945.7 1777.58
  4960.4 1772.74  4977.7 1772.06  5000.1 1780.86  5077.2 1784.31  5102.3 1783.02
  5138.2 1776.37  5163.4 1782.28  5193.9 1784.82  5362.1 1786.77  5470.2 1789.74
  5522.2 1789.94  5582.2 1790.26  5678.4 1790.83  5991.7 1791.66  6056.6 1791.74
  6102.2 1791.97  6312.9 1792.83  6323.8 1792.86  6488.8    1795    6806 1804.94
#Mann= 16 ,-1 , 0
  2987.1     .07       0  4028.4    .035       0  4343.4     .07       0
  4945.7    .045       0  5000.1     .07       0  5362.1     .16       0
  5470.2     .07       0  5522.2     .16       0  5582.2     .07       0
  5678.4     .16       0  5991.7     .07       0  6056.6     .16       0
  6102.2     .07       0  6312.9     .16       0  6323.8     .07       0
  6488.8     .05       0
Bank Sta=4945.7,5000.1
XS Rating Curve= 0 ,0
Exp/Cntr=0.3,0.1

Type RM Length L Ch R = 1 ,156459  ,794,794,794
BEGIN DESCRIPTION:
Mapping XS 5a84227c
END DESCRIPTION:
XS GIS Cut Line= 3
       1520789.4      6854115.72      1521372.77      6852412.56
      1522909.25       6850685.1
#Sta/Elev= 30
  3124.4 1795.34  3152.8 1786.05  3174.8 1783.71  3215.3 1786.54  3460.2 1787.63
  4196.3 1788.05  4401.3 1788.25  4826.6 1784.83  4931.6 1779.82  4985.9 1775.71
  5014.3  1768.8  5028.5  1775.3  5071.2  1776.9  5092.1 1780.63  5134.7 1780.69
  5191.6 1787.86  5271.7 1786.41  5534.4 1784.39  5977.6 1784.59  6162.1 1782.18
  6211.7 1777.38  6218.4  1779.5  6390.2 1783.47  6615.6 1793.18  6636.5 1791.07
  6679.2 1802.56    6724 1803.12  6756.9 1801.48  6915.9 1807.17  7236.6 1814.58
#Mann= 12 ,-1 , 0
  3124.4     .07       0  4196.3     .16       0  4401.3     .07       0
  4826.6     .16       0  4931.6     .07       0  4985.9    .045       0
  5028.5     .07       0  5271.7     .16       0  5534.4     .07       0
  6390.2     .05       0    6724     .07       0  6915.9     .05       0
Bank Sta=4985.9,5028.5
XS Rating Curve= 0 ,0
Exp/Cntr=0.3,0.1

Type RM Length L Ch R = 1 ,155665  ,811,811,811
BEGIN DESCRIPTION:
Mapping XS 433411db
END DESCRIPTION:
XS GIS Cut Line= 4
      1520859.12      6854107.64      1521749.46      6852979.93
      1523308.53       6852664.3      1524167.89       6851336.2
#Sta/Elev= 30
  3523.2 1794.69  3584.6 1783.34  4238.6 1786.95  4673.1 1779.52  4830.2 1781.14
  4886.3 1774.12  4975.9  1774.5  4993.1 1767.96  5016.7 1773.06  5077.9 1781.29
  5128.9 1775.89  5179.9 1784.71  5308.8 1785.79  5414.2 1785.26    5507 1784.71
  5627.8 1784.52  5787.2 1783.76  6086.5 1782.52  6755.3 1780.11  6879.3 1777.83
  6900.4  1774.3  6921.5 1778.59  7087.7 1776.69  7529.4 1785.61  7677.8 1787.67
  7692.9 1787.66  7876.6  1792.6    7928 1797.69  7991.3 1819.72  8132.6 1822.75
#Mann= 12 ,-1 , 0
  3523.2     .07       0  4975.9    .045       0  5016.7     .07       0
  5308.8     .16       0  5414.2     .07       0    5507     .16       0
  5627.8     .07       0  5787.2     .16       0  6086.5     .07       0
  7529.4     .16       0  7677.8    .035       0  7692.9     .07       0
Bank Sta=4975.9,5016.7
XS Rating Curve= 0 ,0
Exp/Cntr=0.3,0.1

Type RM Length L Ch R = 1 ,154854  ,1498,1498,1498
BEGIN DESCRIPTION:
Mapping XS e279a1ee
END DESCRIPTION:
XS GIS Cut Line= 3
        1520939.      6854086.83      1521905.75       6853707.7
      1526131.19      6852840.75
#Sta/Elev= 30
  3945.7  1793.2  4095.1 1783.61  4794.9 1783.72  4914.2  1783.5  4938.6 1776.01
  4986.3 1770.82  4993.6 1767.38    5014 1772.19  5064.2 1777.72    5192 1778.94
  5257.1 1780.56  5310.9 1780.82  6001.1 1782.54  6678.6  1778.9  6739.2 1778.55
  7209.6 1776.74  7474.2 1775.68  7503.7 1771.94  7555.9 1775.79  7737.2 1775.06
  7835.5 1776.19  7981.3 1778.73  8645.5 1782.64  8842.7 1783.09  8893.3 1787.72
  8923.8 1779.98  8964.6 1779.41  9100.1 1786.79  9202.8 1794.93  9297.6 1803.53
#Mann= 20 ,-1 , 0
  3945.7     .07       0  4794.9    .035       0  4986.3    .035       0
    5014     .07       0  5064.2     .07       0    5192     .16       0
  5257.1     .07       0  5310.9     .16       0  6001.1     .07       0
  6678.6     .05       0  6739.2     .07       0  7209.6     .07       0
  7503.7     .05       0  7737.2     .07       0  7835.5     .05       0
  7981.3     .07       0  8645.5     .05       0  8842.7     .05       0
  9100.1     .07       0  9202.8     .05       0
Bank Sta=4986.3,5014
XS Rating Curve= 0 ,0
Exp/Cntr=0.3,0.1

Type RM Length L Ch R = 1 ,153356  ,1982,1982,1982
BEGIN DESCRIPTION:
Mapping XS e646df55
END DESCRIPTION:
XS GIS Cut Line= 4
      1520172.22      6854901.86       1523152.3      6854244.12
      1523991.57      6854055.65      1526849.74      6853535.43
#Sta/Elev= 30
  1948.2 1799.63  1981.5 1798.73  2114.9 1799.83  2381.2 1790.59  3755.5  1780.3
  4787.7 1779.95  4931.1  1777.1  4992.1 1769.84    5028 1768.74  5105.3 1776.45
  5557.1 1780.65  5600.4 1765.82    5617 1766.36  5771.4 1772.76  5783.9 1769.99
  5853.4 1771.44    5945 1766.43  5965.3 1768.04    6006 1778.13    6125  1777.5
  6605.7 1774.45  6788.6 1770.07  6839.4 1772.58  7052.9 1771.21  7815.2 1783.63
  7995.1 1792.49  8447.1 1789.39  8536.9 1792.53  8679.2 1810.12  8765.3 1810.83
#Mann= 8 ,-1 , 0
  1948.2     .05       0  1981.5     .07       0  2381.2    .035       0
  4992.1    .035       0    5028     .07       0    5617     .07       0
    6125    .045       0  6605.7    .035       0
#XS Ineff= 1 ,-1
  5511.1  6015.8 1778.72
Permanent Ineff=
       T
Bank Sta=4992.1,5028
XS Rating Curve= 0 ,0
Exp/Cntr=0.3,0.1

Type RM Length L Ch R = 1 ,151374  ,1021,1021,1021
BEGIN DESCRIPTION:
Mapping XS 52d194b4
END DESCRIPTION:
XS GIS Cut Line= 3
      1522539.96      6855692.55      1524567.75      6854949.49
       1526296.9      6854150.89
#Sta/Elev= 30
  2796.5  1783.6  3884.6 1780.64  3924.5 1780.54  4138.9  1777.2    4259 1775.56
  4337.9 1774.48  4363.4 1770.54  4388.6 1770.82  4410.1 1775.39  4836.1 1776.95
  4986.2 1764.92  4999.1  1758.2  5016.5 1767.71  5039.5 1773.02  5237.2 1777.18
    5557 1771.73    5603  1766.8  5617.6 1770.56  5820.3 1770.07    6319 1772.22
  6563.7 1782.33  6573.7  1784.9  6591.1 1782.84  6627.4 1784.99  6665.5 1789.72
  6704.5 1799.11  6716.8 1797.31  6770.6 1819.82  6815.5 1823.68  6860.8 1824.97
#Mann= 13 ,-1 , 0
  2796.5    .055       0  3884.6    .035       0  3924.5    .045       0
  4138.9     .05       0    4259     .07       0  4337.9     .05       0
  4986.2    .045       0  5016.5     .07       0  5237.2    .045       0
    5557     .07       0  5820.3    .045       0  6563.7     .07       0
  6815.5     .05       0
#XS Ineff= 2 , 0
       0  4708.2 1777.98               0
Permanent Ineff=
       F       F
Bank Sta=4986.2,5016.5
XS Rating Curve= 0 ,0
Exp/Cntr=0.3,0.1

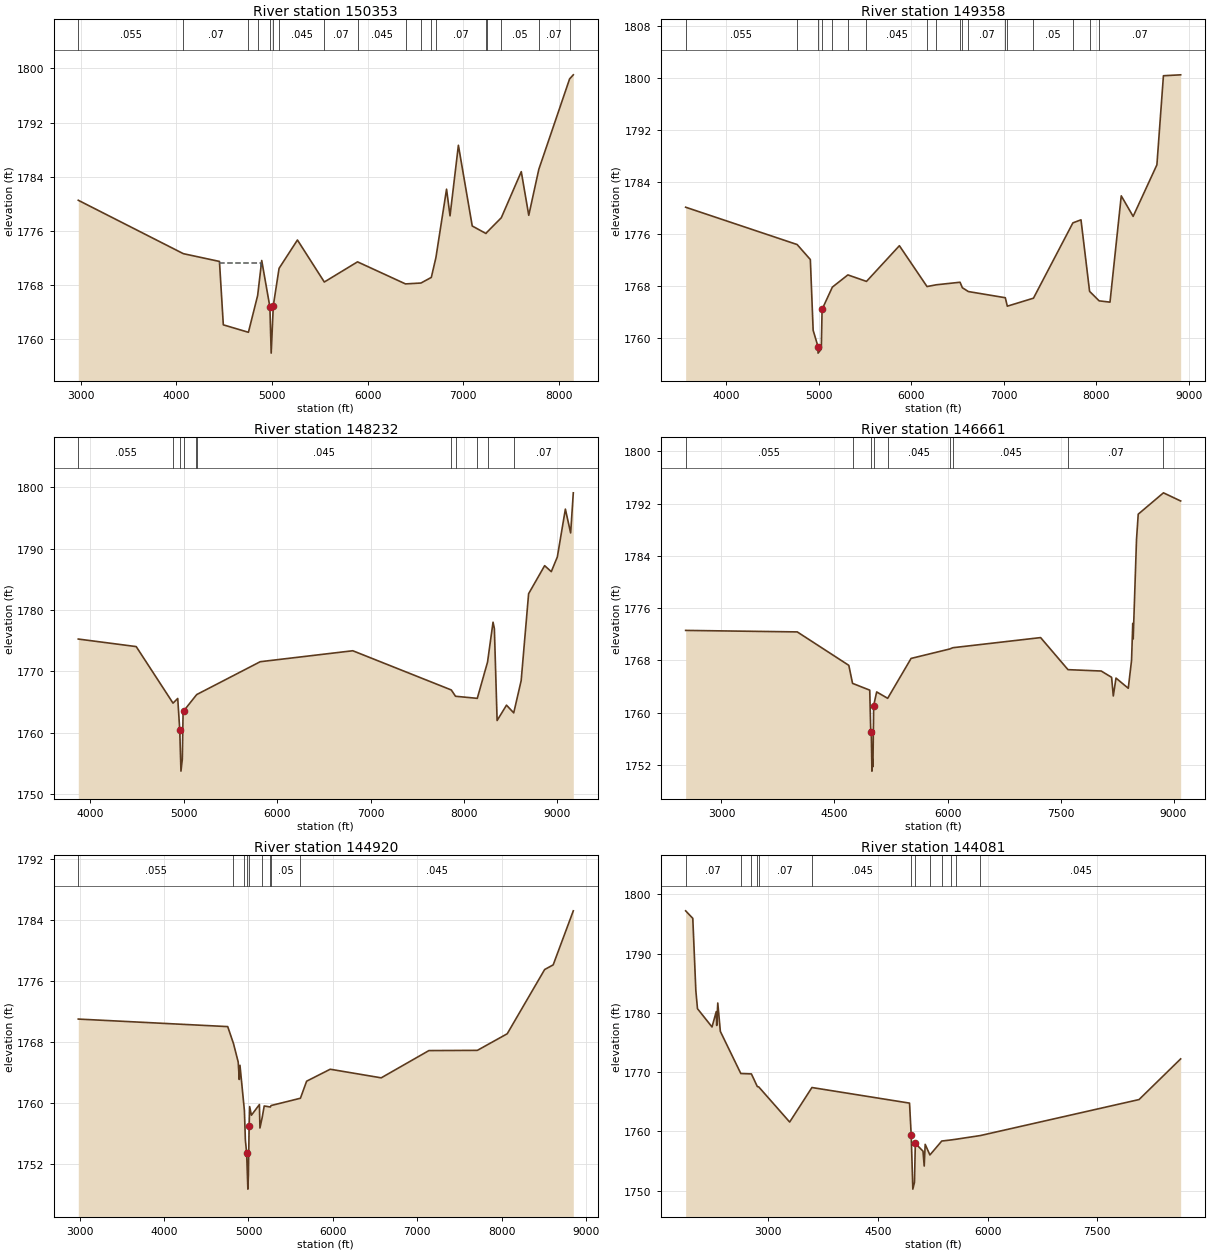
Type RM Length L Ch R = 1 ,150353  ,995,995,995
BEGIN DESCRIPTION:
Mapping XS 65b343c8
END DESCRIPTION:
XS GIS Cut Line= 3
      1523319.92      6856333.61      1525207.94      6855682.57
      1527877.21      6853946.46
#Sta/Elev= 30
  2972.7 1780.52    4072 1772.63  4450.3 1771.48  4490.7 1762.11  4753.4 1761.01
  4850.1 1766.45  4892.7 1771.62  4978.2 1764.75  4991.7 1757.93    5014 1764.95
  5074.3 1770.46  5266.5 1774.65  5547.8 1768.44  5895.3 1771.42  6397.6 1768.16
  6559.3 1768.29  6667.8 1769.12  6715.9 1772.05  6827.3 1782.16  6863.6 1778.22
  6951.2 1788.65  7096.1 1776.72  7239.7 1775.61  7251.8 1775.82  7400.4 1777.94
  7609.4 1784.75  7687.8  1778.3  7792.9 1785.09  8115.3 1798.46    8154 1799.06
#Mann= 18 ,-1 , 0
  2972.7    .055       0    4072     .07       0  4753.4     .16       0
  4850.1     .05       0  4978.2    .045       0    5014     .05       0
  5074.3    .045       0  5547.8     .07       0  5895.3    .045       0
  6397.6     .05       0  6559.3     .07       0  6667.8     .05       0
  6715.9     .07       0  7239.7     .05       0  7251.8     .07       0
  7400.4     .05       0  7792.9     .07       0  8115.3    .045       0
#XS Ineff= 1 ,-1
    4450  4882.1 1771.22
Permanent Ineff=
       T
Bank Sta=4978.2,5014
XS Rating Curve= 0 ,0
Exp/Cntr=0.3,0.1

Type RM Length L Ch R = 1 ,149358  ,1126,1126,1126
BEGIN DESCRIPTION:
Mapping XS d3f14f60
END DESCRIPTION:
XS GIS Cut Line= 4
      1523529.21      6856701.34      1524951.11      6856508.63
      1525669.86      6856008.63      1528067.41      6854138.85
#Sta/Elev= 30
  3560.9 1780.12    4766 1774.38  4908.9 1772.07  4939.2 1761.19  4991.8 1758.68
  4992.3 1757.68  5027.1  1758.3  5035.8 1764.41  5146.7 1767.83  5314.4 1769.71
  5515.8 1768.71  5871.4  1774.2  6170.1 1767.92  6270.5 1768.19  6527.2 1768.58
  6551.9 1767.74  6616.8 1767.15  7016.2  1766.2  7038.1  1764.9  7320.6 1766.13
  7746.8 1777.71  7834.5 1778.18  7927.3 1767.18  8030.5 1765.72  8147.9 1765.52
  8269.6 1781.87  8398.1 1778.71    8655 1786.64  8725.5 1800.34  8911.8 1800.48
#Mann= 18 ,-1 , 0
  3560.9    .055       0    4766     .07       0  4991.8    .035       0
  5035.8     .07       0  5146.7     .07       0  5314.4     .05       0
  5515.8    .045       0  6170.1     .05       0  6270.5     .12       0
  6527.2     .07       0  6551.9     .12       0  6616.8     .07       0
  7016.2    .045       0  7038.1     .07       0  7320.6     .05       0
  7746.8     .07       0  7927.3    .033       0  8030.5     .07       0
Bank Sta=4991.8,5035.8
XS Rating Curve= 0 ,0
Exp/Cntr=0.3,0.1

Type RM Length L Ch R = 1 ,148232  ,1571,1571,1571
BEGIN DESCRIPTION:
Mapping XS 5323fa2d
END DESCRIPTION:
XS GIS Cut Line= 5
      1524480.98      6858018.91      1525418.45       6857435.6
      1526119.84      6856893.94      1526821.22      6856005.05
      1528098.31      6854242.12
#Sta/Elev= 30
  3871.5 1775.26  4491.5 1774.03  4885.7  1764.8  4936.2 1765.56  4957.8  1760.4
  4970.6  1753.7  4985.1  1755.6  4993.2 1763.06  5000.1 1763.53  5134.5 1766.11
  5140.8 1766.21  5819.2 1771.56  6810.1 1773.35  7864.7 1766.95    7910 1765.92
    8143 1765.58  8252.8  1771.5  8311.7 1778.01  8325.9 1776.97  8355.3 1761.96
  8455.8 1764.47  8533.1 1763.21  8612.8 1768.47  8692.5 1782.66  8864.1 1787.24
  8935.3 1786.26  9000.2 1788.67  9086.1 1796.47  9142.5 1792.58    9171 1799.13
#Mann= 11 ,-1 , 0
  3871.5    .055       0  4885.7    .035       0  4957.8    .035       0
  5000.1     .05       0  5134.5     .05       0  5140.8    .045       0
  7864.7     .07       0    7910    .045       0    8143     .07       0
  8252.8    .033       0  8533.1     .07       0
Bank Sta=4957.8,5000.1
XS Rating Curve= 0 ,0
Exp/Cntr=0.3,0.1

Type RM Length L Ch R = 1 ,146661  ,1741,1741,1741
BEGIN DESCRIPTION:
Mapping XS f6ce05d3
END DESCRIPTION:
XS GIS Cut Line= 4
      1524970.14       6859692.2      1526490.02      6857737.96
      1526702.61      6856393.56      1529098.62      6855077.61
#Sta/Elev= 30
  2524.3  1772.6  4005.9 1772.37    4690 1767.25  4739.7 1764.49  4967.8 1763.45
  4982.3 1756.56  4988.6 1757.05  4996.8 1751.05    5000 1753.09  5010.1 1751.73
  5020.2  1761.1  5059.8 1763.18  5205.9  1762.2  5516.7 1768.31  6027.6 1769.75
  6071.6 1769.95  7235.7  1771.5  7599.3 1766.59  8040.1 1766.38  8177.9 1765.42
  8200.7 1762.56  8236.2  1765.3  8399.2 1763.74  8442.8    1768  8458.9 1773.68
  8464.6 1771.29  8508.7 1786.53  8531.5  1790.4  8866.3 1793.67  9094.7 1792.42
#Mann= 9 ,-1 , 0
  2524.3    .055       0  4739.7    .035       0  4988.6    .035       0
  5020.2     .05       0  5205.9    .045       0  6027.6     .07       0
  6071.6    .045       0  7599.3     .07       0  8866.3    .045       0
Bank Sta=4988.6,5020.2
XS Rating Curve= 0 ,0
Exp/Cntr=0.3,0.1

Type RM Length L Ch R = 1 ,144920  ,839,839,839
BEGIN DESCRIPTION:
Mapping XS 29fd8d63
END DESCRIPTION:
XS GIS Cut Line= 3
      1525452.21      6860072.11      1527101.51      6859008.75
      1529347.61      6855818.63
#Sta/Elev= 30
  2984.4 1771.02  4754.5 1770.03  4822.9  1767.8  4878.6 1765.38  4891.4 1763.08
  4899.7 1764.95  4952.2    1759  4963.8  1755.1  4978.6 1753.44  4993.4 1748.68
  4999.5 1750.62  5008.2 1756.93  5014.3 1759.52  5035.2 1758.39  5130.1 1759.79
  5136.2 1756.71  5162.6 1758.08  5186.8  1759.6  5259.9 1759.47    5268 1759.66
  5615.8 1760.62  5689.3 1762.86  5968.9 1764.43  6572.6  1763.3  7137.9 1766.88
  7711.9 1766.91  8065.5 1769.09  8508.9 1777.53  8609.9 1778.14  8848.3 1785.24
#Mann= 9 ,-1 , 0
  2984.4    .055       0  4822.9    .035       0  4952.2     .07       0
  4978.6    .045       0  5008.2     .07       0  5162.6    .045       0
  5259.9     .07       0    5268     .05       0  5615.8    .045       0
Bank Sta=4978.6,5008.2
XS Rating Curve= 0 ,0
Exp/Cntr=0.3,0.1

Type RM Length L Ch R = 1 ,144081  ,1523,1523,1523
BEGIN DESCRIPTION:
Mapping XS fd610889
END DESCRIPTION:
XS GIS Cut Line= 3
      1525717.47      6862057.26      1527592.44      6859674.48
      1529310.59      6856355.34
#Sta/Elev= 30
  1871.3  1797.2  1969.1 1795.93  2010.7 1783.75  2033.3  1780.7  2232.1 1777.62
  2289.9 1780.21  2296.2 1777.87  2310.7 1781.66  2345.9 1776.87  2625.8 1769.77
  2770.9  1769.7  2851.8 1767.56  2869.7 1767.53  3293.8 1761.59  3598.3 1767.41
  4933.1 1764.78  4955.7  1759.4  4978.2 1750.28  5000.7 1751.42  5012.2 1757.99
  5117.2 1756.68  5133.7 1754.17  5147.1 1757.83  5211.8 1756.04  5373.8 1758.39
  5505.7 1758.58  5568.2 1758.69  5900.7 1759.31  8071.6 1765.38  8640.8 1772.24
#Mann= 13 ,-1 , 0
  1871.3     .07       0  2625.8     .16       0  2770.9     .07       0
  2851.8     .16       0  2869.7     .07       0  3598.3    .045       0
  4955.7    .045       0  5012.2    .045       0  5211.8    .045       0
  5373.8     .07       0  5505.7    .045       0  5568.2     .07       0
  5900.7    .045       0
Bank Sta=4955.7,5012.2
XS Rating Curve= 0 ,0
Exp/Cntr=0.3,0.1

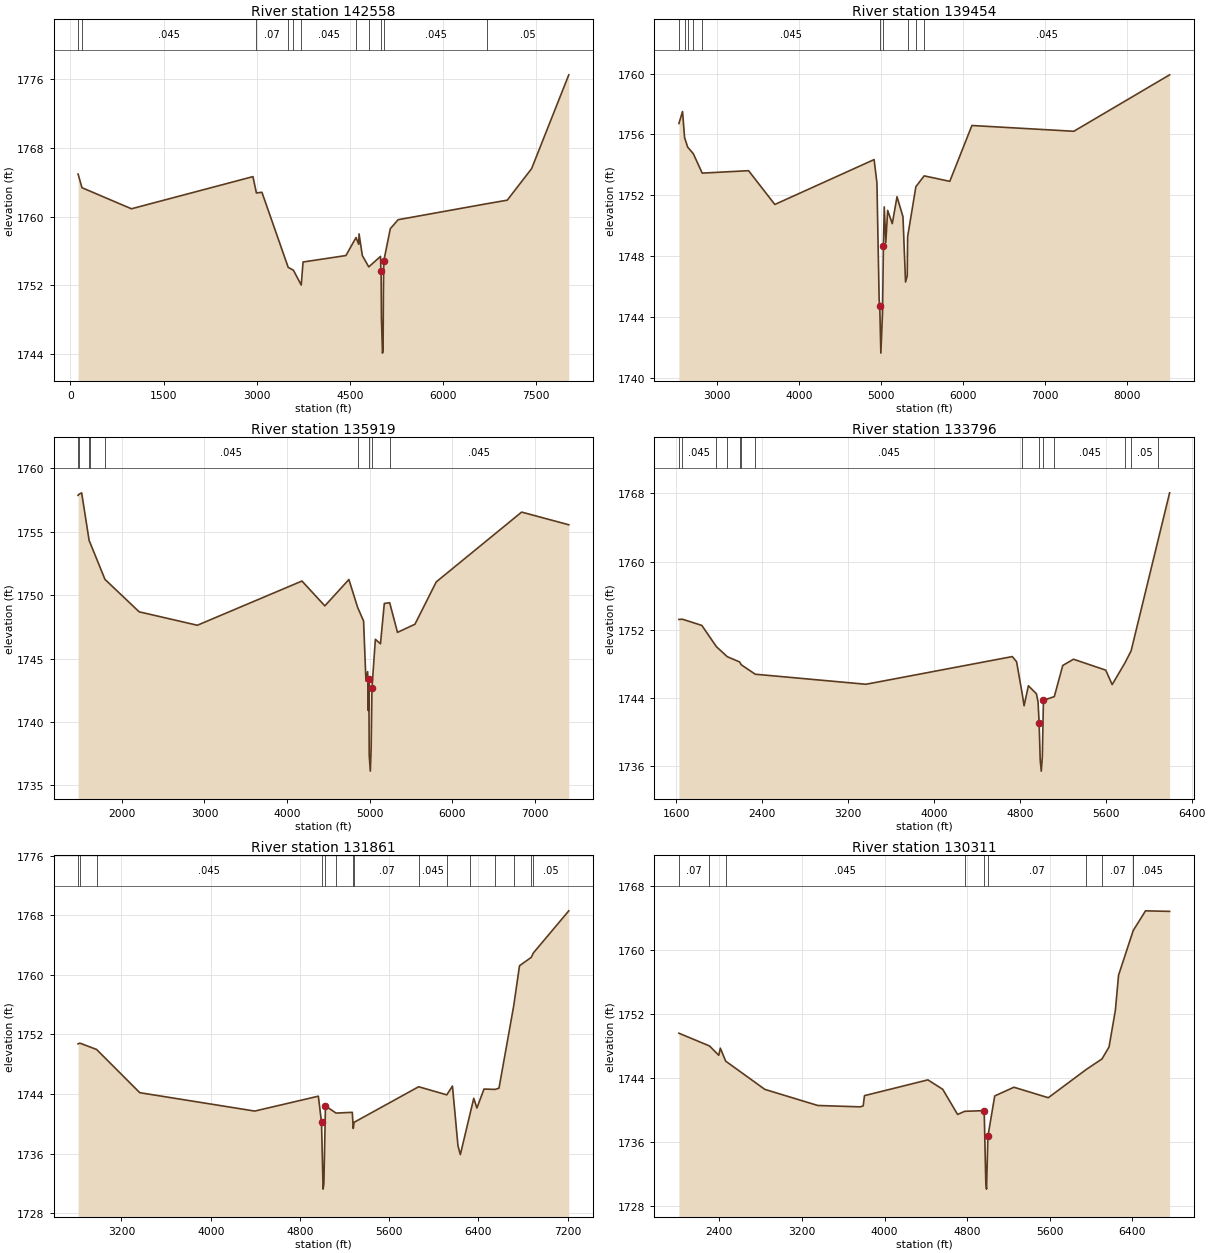
Type RM Length L Ch R = 1 ,142558  ,3104,3104,3104
BEGIN DESCRIPTION:
Mapping XS 32a3ab87
END DESCRIPTION:
XS GIS Cut Line= 3
       1526677.5       6863946.6      1528568.24      6859451.56
       1529477.8      6856567.38
#Sta/Elev= 30
   123.5 1764.94   186.6 1763.35   982.8  1760.9  2939.2 1764.64  2994.4 1762.74
  3083.7 1762.82  3506.5 1754.09  3590.9 1753.75  3716.5 1752.03  3745.8 1754.71
  4435.7 1755.46  4599.5 1757.56  4641.9 1756.77  4647.4 1757.98  4700.3 1755.46
  4803.5 1754.14    4993 1755.36  4999.2 1753.68  5002.9 1753.68  5007.4 1748.25
  5024.7 1744.11  5034.5 1744.53  5039.8 1751.42  5045.7 1754.83  5150.5 1758.58
  5276.7 1759.63  6714.1  1761.5  7033.4  1761.9  7425.9 1765.57  8024.2 1776.48
#Mann= 11 ,-1 , 0
   123.5     .05       0   186.6    .045       0  2994.4     .07       0
  3506.5    .045       0  3590.9     .12       0  3716.5    .045       0
  4599.5     .07       0  4803.5    .045       0  4999.2    .045       0
  5045.7    .045       0  6714.1     .05       0
Bank Sta=4999.2,5045.7
XS Rating Curve= 0 ,0
Exp/Cntr=0.3,0.1

Type RM Length L Ch R = 1 ,139454  ,3535,3535,3535
BEGIN DESCRIPTION:
Mapping XS f64e38e6
END DESCRIPTION:
XS GIS Cut Line= 3
       1527795.9      6864420.86      1528299.43      6862449.14
      1529350.34      6858645.14
#Sta/Elev= 30
    2537 1756.72  2581.2 1757.51  2606.4 1755.79  2643.7 1755.17  2712.2 1754.74
  2821.2 1753.46  3386.3 1753.62  3706.2  1751.4  4916.4 1754.35  4950.8 1752.82
  4977.8 1745.13  4985.1 1744.76  4998.5 1741.63  5019.3 1744.32  5029.8 1748.69
    5040 1751.24    5059  1748.9  5081.5 1751.01    5138 1750.14  5195.7 1751.91
  5268.3 1750.59  5299.4  1746.3  5320.1  1746.7  5324.9 1749.28  5425.7 1752.57
  5526.6 1753.28  5838.9 1752.92  6108.6 1756.59  7350.7 1756.21  8518.5 1759.92
#Mann= 10 ,-1 , 0
    2537    .055       0  2606.4     .07       0  2643.7    .045       0
  2712.2     .05       0  2821.2    .045       0  4985.1    .045       0
  5029.8    .045       0  5324.9     .05       0  5425.7     .07       0
  5526.6    .045       0
Bank Sta=4985.1,5029.8
XS Rating Curve= 0 ,0
Exp/Cntr=0.3,0.1

Type RM Length L Ch R = 1 ,135919  ,2123,2123,2123
BEGIN DESCRIPTION:
Mapping XS 1c43aed7
END DESCRIPTION:
XS GIS Cut Line= 3
      1527832.82      6864456.55      1530025.34      6861687.59
      1530487.85      6859317.19
#Sta/Elev= 30
  1468.1 1757.88    1478 1757.96  1511.4 1758.08  1602.6  1754.3  1609.3 1754.21
  1794.1 1751.25  2208.5 1748.69  2913.7 1747.63  4181.4 1751.12  4458.6 1749.16
  4750.3 1751.24  4856.6 1749.03  4928.1 1747.97    4957 1743.23  4977.8 1743.97
  4985.9 1740.89  4992.2 1743.39  4996.5 1737.38  5009.8 1736.12  5019.6  1737.8
  5030.1 1742.68  5070.9 1746.52  5132.9 1746.17  5179.4 1749.35  5244.5 1749.41
  5339.3 1747.07  5550.7 1747.71  5808.6 1751.05  6843.7 1756.56  7415.1 1755.56
#Mann= 9 ,-1 , 0
  1468.1    .055       0    1478     .07       0  1602.6    .045       0
  1609.3     .05       0  1794.1    .045       0  4856.6     .07       0
  4992.2    .045       0  5030.1     .07       0  5244.5    .045       0
Bank Sta=4992.2,5030.1
XS Rating Curve= 0 ,0
Exp/Cntr=0.3,0.1

Type RM Length L Ch R = 1 ,133796  ,1935,1935,1935
BEGIN DESCRIPTION:
Mapping XS 12721a81
END DESCRIPTION:
XS GIS Cut Line= 3
      1528125.79      6864890.57      1530144.04      6862720.41
      1531749.91      6862687.86
#Sta/Elev= 30
  1624.9  1753.2  1657.7 1753.23  1838.4  1752.5  1973.8 1750.01    2075 1748.83
  2190.3 1748.21  2205.4 1747.88  2335.8 1746.77  3366.7 1745.59  4729.5 1748.84
  4769.5 1748.24  4822.1 1744.46  4839.5 1743.06  4879.5 1745.42  4954.3 1744.47
  4969.5 1743.52  4979.5 1741.03  4989.5  1736.7  4999.5 1735.39  5009.5  1737.1
  5019.5 1743.71  5120.8 1744.14  5199.6  1747.8  5299.6 1748.53  5599.7 1747.25
  5659.7 1745.55  5777.8 1748.08    5836 1749.51  6087.9 1762.55  6194.7 1768.07
#Mann= 14 ,-1 , 0
  1624.9     .07       0  1657.7    .045       0  1973.8     .07       0
    2075    .045       0  2190.3     .07       0  2205.4     .05       0
  2335.8    .045       0  4822.1     .07       0  4979.5    .045       0
  5019.5     .07       0  5120.8    .045       0  5777.8     .07       0
    5836     .05       0  6087.9     .07       0
Bank Sta=4979.5,5019.5
XS Rating Curve= 0 ,0
Exp/Cntr=0.3,0.1

Type RM Length L Ch R = 1 ,131861  ,1550,1550,1550
BEGIN DESCRIPTION:
Mapping XS 450d7bb1
END DESCRIPTION:
XS GIS Cut Line= 3
      1528744.32      6865741.66      1530437.01        6864483.
      1532060.15      6862868.54
#Sta/Elev= 30
  2810.8 1750.74  2826.8 1750.84  2976.8 1749.99  3363.9 1744.18  4394.3 1741.71
  4964.7 1743.71    4993 1740.19  5007.1 1731.22  5014.2 1731.92  5028.4  1742.4
  5123.1 1741.44  5268.8 1741.54  5277.5 1739.37  5285.4  1740.2  5863.8 1744.98
  6115.8 1743.89  6166.8 1745.07  6216.3 1737.04  6237.5 1735.86  6324.9 1741.36
  6357.7 1743.42    6386 1742.12  6449.6 1744.67  6549.1 1744.62    6584 1744.79
  6715.4 1755.81  6767.8 1761.24  6873.4 1762.37  6892.2 1762.96  7209.5 1768.62
#Mann= 15 ,-1 , 0
  2810.8     .07       0  2826.8     .05       0  2976.8    .045       0
    4993    .045       0  5028.4    .045       0  5123.1     .07       0
  5277.5    .045       0  5285.4     .07       0  5863.8    .045       0
  6115.8     .07       0  6324.9     .05       0  6549.1     .07       0
  6715.4     .05       0  6873.4     .07       0  6892.2     .05       0
Bank Sta=4993,5028.4
XS Rating Curve= 0 ,0
Exp/Cntr=0.3,0.1

Type RM Length L Ch R = 1 ,130311  ,2275,2275,2275
BEGIN DESCRIPTION:
Mapping XS db2ada3d
END DESCRIPTION:
XS GIS Cut Line= 3
      1529126.25      6866036.82      1531912.71      6864153.14
       1533221.7      6863685.02
#Sta/Elev= 30
  2008.1 1749.63  2304.1 1748.04  2394.4 1746.87  2409.4 1747.76  2461.3 1746.14
  2840.9 1742.61  3353.3  1740.6  3763.8 1740.43    3793 1740.55  3805.8 1741.83
  4420.1  1743.8  4563.9 1742.62  4707.7 1739.48  4775.9 1739.87  4965.5 1739.96
  4980.5 1731.18    4988 1730.15  5001.5 1736.74  5067.4 1741.79  5253.6 1742.88
  5586.4 1741.57  5956.2 1745.12  6106.3 1746.41  6174.8 1747.91  6236.3  1752.5
  6267.1 1756.88  6405.9 1762.33  6409.7 1762.47  6528.2 1764.92  6761.7 1764.85
#Mann= 10 ,-1 , 0
  2008.1     .07       0  2304.1     .05       0  2461.3    .045       0
  4775.9     .07       0  4965.5    .045       0  5001.5     .07       0
  5956.2     .05       0  6106.3     .07       0  6405.9     .05       0
  6409.7    .045       0
Bank Sta=4965.5,5001.5
XS Rating Curve= 0 ,0
Exp/Cntr=0.3,0.1

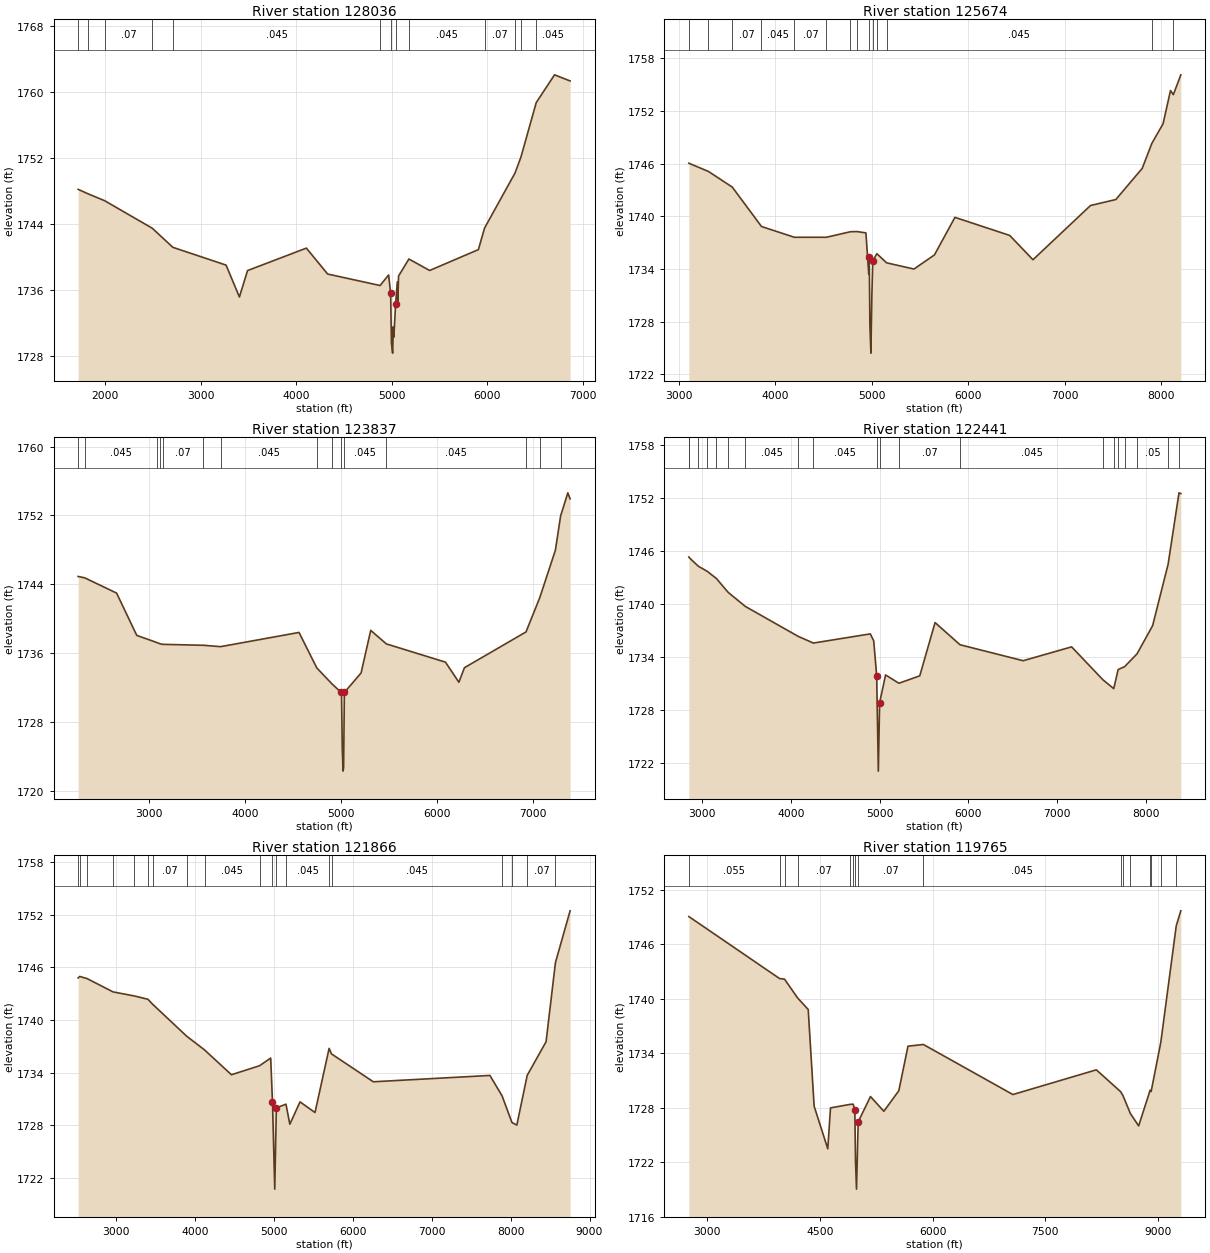
Type RM Length L Ch R = 1 ,128036  ,2362,2362,2362
BEGIN DESCRIPTION:
Mapping XS 622cc39a
END DESCRIPTION:
XS GIS Cut Line= 3
      1529325.93      6866288.54      1532416.18      6865177.44
      1534230.22      6864734.78
#Sta/Elev= 30
  1715.3 1748.24  1818.7  1747.7  1991.6 1746.87  2491.4 1743.53  2706.5 1741.22
  3264.5 1739.06    3404  1735.2    3489  1738.4  4105.3 1741.12  4327.9 1737.98
  4877.1 1736.59  4966.1 1737.87  4987.7 1735.64  4995.9 1729.61  5008.3  1728.4
  5015.7  1731.6  5020.9 1730.34  5039.2 1734.31  5057.4 1737.04  5062.5 1734.28
  5070.1 1737.73  5178.7  1739.8    5396 1738.41  5906.4 1740.94  5970.4 1743.54
  6290.1 1750.22  6351.8 1752.15  6511.7 1758.74  6703.4 1762.11  6866.5 1761.37
#Mann= 13 ,-1 , 0
  1715.3     .07       0  1818.7    .045       0  1991.6     .07       0
  2491.4     .05       0  2706.5    .045       0  4877.1     .07       0
  4987.7    .045       0  5039.2     .07       0  5178.7    .045       0
  5970.4     .07       0  6290.1    .045       0  6351.8     .07       0
  6511.7    .045       0
Bank Sta=4987.7,5039.2
XS Rating Curve= 0 ,0
Exp/Cntr=0.3,0.1

Type RM Length L Ch R = 1 ,125674  ,1837,1837,1837
BEGIN DESCRIPTION:
Mapping XS 6ddb6151
END DESCRIPTION:
XS GIS Cut Line= 3
      1529542.89      6866566.34      1531461.32      6866097.58
      1534550.77      6865646.31
#Sta/Elev= 30
  3105.7 1746.06  3308.9 1745.12  3555.4 1743.34  3858.1 1738.85    4199 1737.62
  4530.6 1737.62  4778.9 1738.25  4848.2 1738.27  4940.2 1738.12  4969.7 1733.44
  4974.9 1735.35  4981.4 1727.67  4991.7 1724.42    5002 1731.11  5011.4 1734.94
  5053.5 1735.75  5154.5 1734.71    5438    1734  5650.2 1735.61  5862.5 1739.89
  6430.1 1737.83  6670.9 1735.06  7267.2 1741.24  7529.4 1741.92  7802.8 1745.47
  7902.8 1748.32  8019.1 1750.56  8095.9 1754.34  8125.4 1753.87  8202.8 1756.13
#Mann= 14 ,-1 , 0
  3105.7     .07       0  3308.9    .045       0  3555.4     .07       0
  3858.1    .045       0    4199     .07       0  4530.6     .05       0
  4778.9     .07       0  4848.2    .045       0  4974.9    .045       0
  5011.4    .045       0  5053.5     .07       0  5154.5    .045       0
  7902.8     .07       0  8125.4    .045       0
Bank Sta=4974.9,5011.4
XS Rating Curve= 0 ,0
Exp/Cntr=0.3,0.1

Type RM Length L Ch R = 1 ,123837  ,1396,1396,1396
BEGIN DESCRIPTION:
Mapping XS 92357967
END DESCRIPTION:
XS GIS Cut Line= 3
      1529664.44      6866774.66       1532407.5      6866800.71
      1534600.55      6865873.21
#Sta/Elev= 30
  2259.7 1744.92  2328.3 1744.76  2660.3 1742.99  2870.3 1738.08    3079 1737.25
  3117.1 1737.09  3140.7 1737.04  3565.1 1736.93  3742.8 1736.77  4560.4 1738.42
  4745.8  1734.3  4901.8 1732.47  4999.1 1731.46  5002.9 1731.46    5011 1724.94
  5019.6 1722.32    5025 1722.79  5032.7 1731.45  5207.1 1733.72  5307.3 1738.66
  5470.3 1737.09  6085.9 1734.97  6225.5 1732.64  6283.7 1734.33  6924.8 1738.48
  7067.5 1742.44  7230.9 1747.97  7285.1 1751.94  7360.3 1754.63    7384 1753.93
#Mann= 15 ,-1 , 0
  2259.7     .07       0  2328.3    .045       0    3079     .07       0
  3117.1    .045       0  3140.7     .07       0  3565.1     .05       0
  3742.8    .045       0  4745.8     .07       0  4901.8    .045       0
  4999.1    .045       0  5032.7    .045       0  5470.3    .045       0
  6924.8     .07       0  7067.5     .05       0  7285.1    .045       0
Bank Sta=4999.1,5032.7
XS Rating Curve= 0 ,0
Exp/Cntr=0.3,0.1

Type RM Length L Ch R = 1 ,122441  ,575,575,575
BEGIN DESCRIPTION:
Mapping XS 33a7746e
END DESCRIPTION:
XS GIS Cut Line= 4
      1529725.22       6866896.2      1531791.18      6867503.83
      1532589.79      6867642.72      1534716.53       6866175.7
#Sta/Elev= 30
  2848.7 1745.34  2853.2 1745.26  2955.6 1744.29  3057.9  1743.7  3160.3 1742.89
    3291 1741.34  3485.3 1739.74  4081.4 1736.35  4253.3 1735.59  4894.8 1736.63
  4933.4 1735.84  4966.7  1731.9  4985.3 1721.09  5000.1 1728.84  5066.9 1731.98
  5217.5 1731.04  5452.6 1731.88  5625.2 1737.91  5906.5  1735.4  6618.6 1733.59
  7164.9 1735.16  7517.4 1731.44    7640 1730.43  7689.8 1732.59  7762.7 1732.92
  7902.7 1734.37  8078.4 1737.56  8253.3 1744.52    8376  1752.6  8396.4 1752.52
#Mann= 20 ,-1 , 0
  2848.7    .055       0  2853.2     .07       0  2955.6    .045       0
  3057.9     .07       0  3160.3    .045       0    3291     .07       0
  3485.3    .045       0  4081.4     .05       0  4253.3    .045       0
  4966.7    .045       0  5000.1    .045       0  5217.5     .07       0
  5906.5    .045       0  7517.4     .07       0    7640     .05       0
  7689.8     .07       0  7762.7     .05       0  7902.7     .05       0
  8253.3     .07       0    8376    .045       0
Bank Sta=4966.7,5000.1
XS Rating Curve= 0 ,0
Exp/Cntr=0.3,0.1

Type RM Length L Ch R = 1 ,121866  ,2101,2101,2101
BEGIN DESCRIPTION:
Mapping XS d8f22c2a
END DESCRIPTION:
XS GIS Cut Line= 4
      1529508.15      6867078.47       1531782.5      6868015.98
      1532598.47      6868042.03      1535107.18      6866470.83
#Sta/Elev= 30
  2517.5 1744.79  2537.1 1744.96  2630.3 1744.72  2960.5  1743.2  3229.5 1742.74
  3402.6 1742.36  3460.4 1741.81    3892 1738.17  4119.7  1736.6    4461 1733.77
  4818.2  1734.8  4958.6 1735.67  4981.2 1730.68    5010 1720.75    5030    1730
  5152.2 1730.42  5201.3 1728.14  5330.2 1730.68  5520.3 1729.47  5699.2 1736.77
  5729.6 1736.14  6259.5 1732.97  7737.6 1733.69  7891.6 1731.37  8017.1 1728.33
  8078.9 1728.04  8210.2  1733.7  8449.5 1737.53  8568.3 1746.54    8754 1752.43
#Mann= 19 ,-1 , 0
  2517.5     .07       0  2537.1    .045       0  2630.3     .07       0
  2960.5    .045       0  3229.5     .07       0  3402.6    .045       0
  3460.4     .07       0    3892     .05       0  4119.7    .045       0
  4818.2     .07       0  4981.2    .045       0    5030     .07       0
  5152.2    .045       0  5699.2     .07       0  5729.6    .045       0
  7891.6     .07       0  8017.1     .16       0  8210.2     .07       0
  8568.3    .045       0
Bank Sta=4981.2,5030
XS Rating Curve= 0 ,0
Exp/Cntr=0.3,0.1

Type RM Length L Ch R = 1 ,119765  ,943,943,943
BEGIN DESCRIPTION:
Mapping XS 557e92ad
END DESCRIPTION:
XS GIS Cut Line= 3
      1529820.68      6870507.31      1531704.37      6869292.03
      1535089.79      6866635.78
#Sta/Elev= 30
  2757.5 1749.06  3963.7 1742.24  4030.3 1742.17  4203.7 1740.11  4345.4 1738.83
  4424.2 1728.19  4605.7  1723.5    4642    1728  4903.4 1728.39  4944.1 1728.41
  4965.4 1727.77  4974.6 1722.13    4988 1719.06  5010.1 1726.46  5173.7 1729.25
  5351.8 1727.63  5550.7 1729.89  5672.7 1734.79  5877.7 1734.98  7068.3 1729.47
  8178.4 1732.19  8502.6 1729.78  8532.7 1729.35  8631.6 1727.38  8741.5 1726.02
  8893.9 1729.94  8907.5  1729.8  9036.2 1735.23  9241.6 1748.04  9302.3 1749.69
#Mann= 16 ,-1 , 0
  2757.5    .055       0  3963.7     .07       0  4030.3     .05       0
  4203.7     .07       0  4903.4    .045       0  4944.1     .07       0
  4965.4    .045       0  5010.1     .07       0  5877.7    .045       0
  8502.6     .07       0  8532.7    .045       0  8631.6     .07       0
  8893.9     .16       0  8907.5     .05       0  9036.2     .07       0
  9241.6    .045       0
Bank Sta=4965.4,5010.1
XS Rating Curve= 0 ,0
Exp/Cntr=0.3,0.1