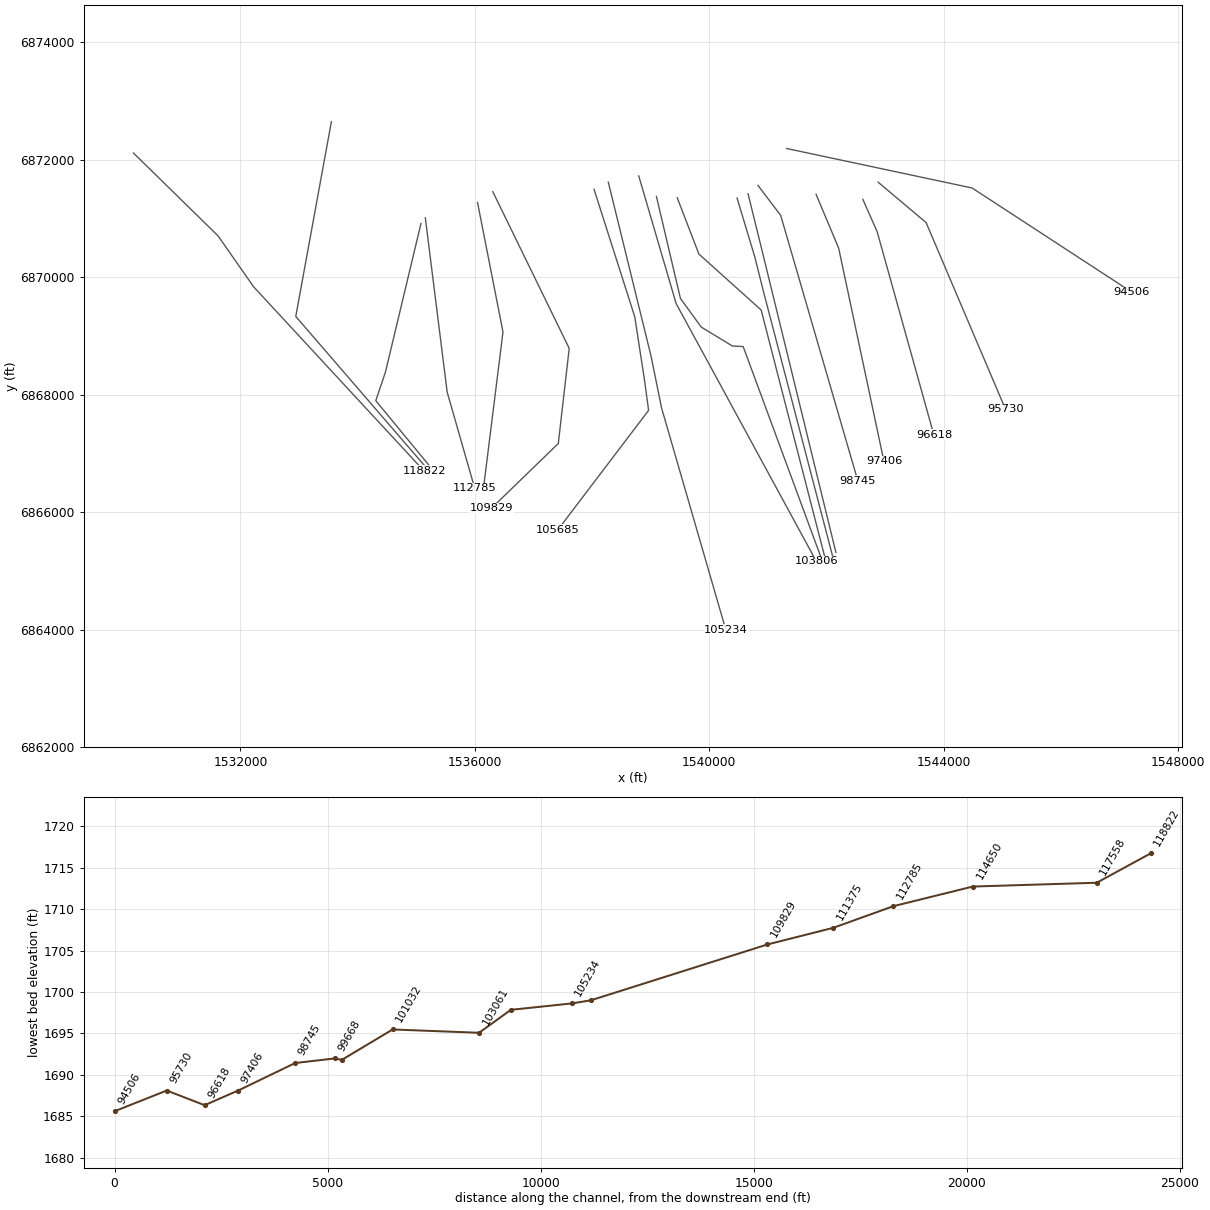
HEC-RAS study MULBERRY CREEK.prj: MULBERRY CREEK Base Level Engineering

--- MULBERRY CREEK.g01 (geometry) --- (continued)

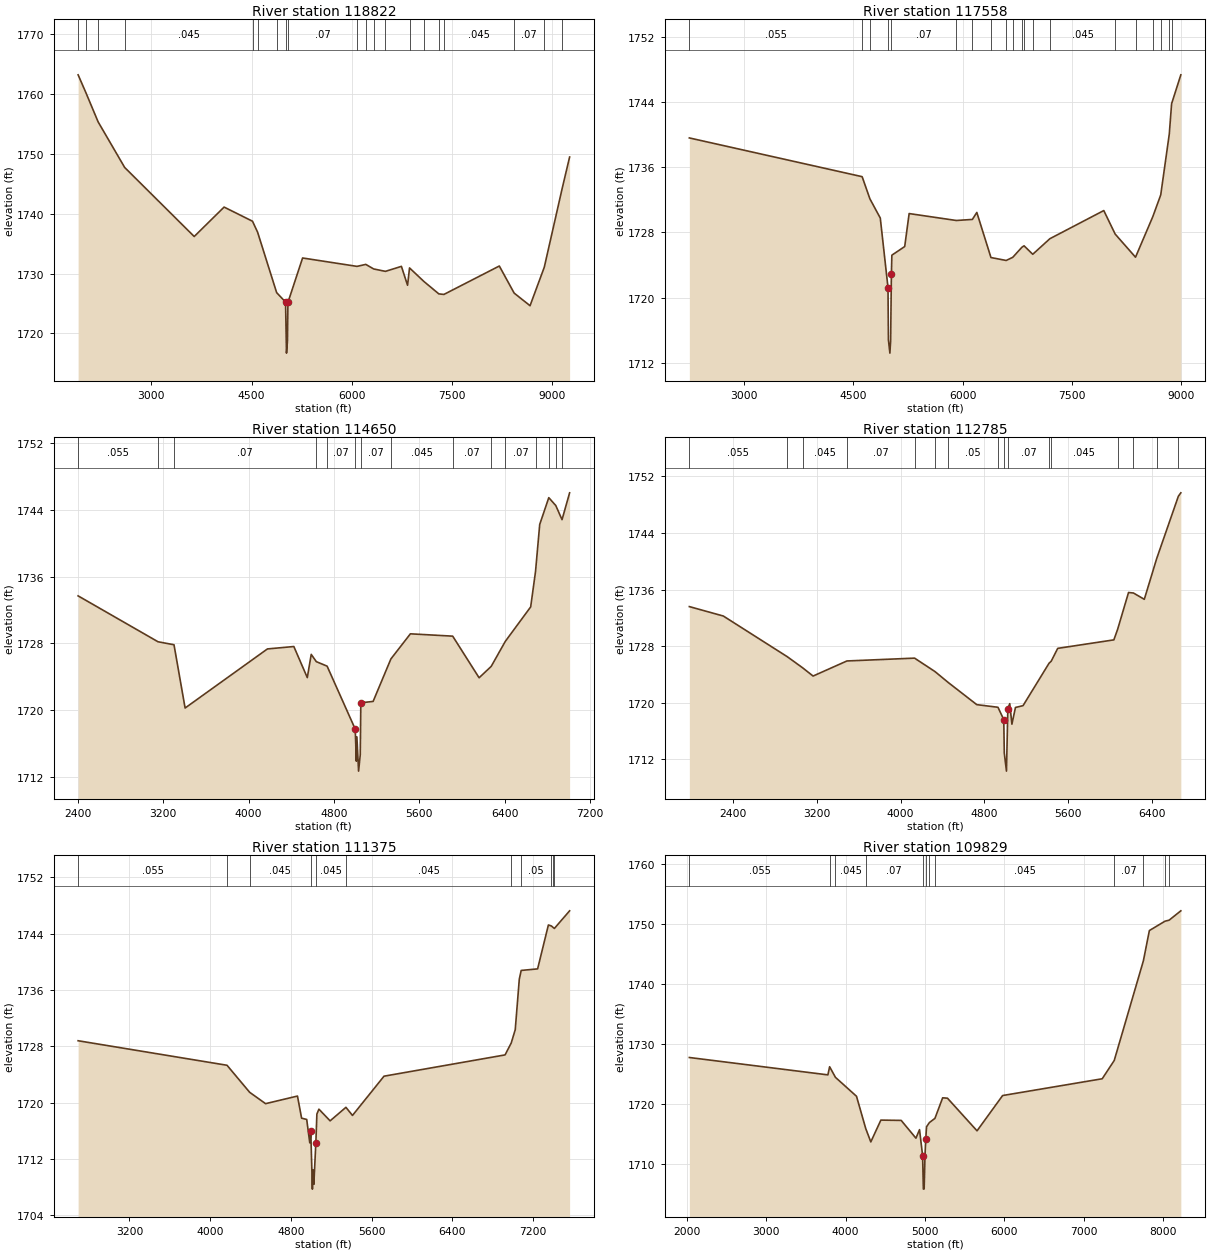
Type RM Length L Ch R = 1 ,118822  ,1264,1264,1264
BEGIN DESCRIPTION:
Mapping XS 86f8dd57
END DESCRIPTION:
XS GIS Cut Line= 4
       1530174.4       6872114.1      1531617.57      6870703.48
      1532225.21      6869835.43      1535133.17       6866699.6
#Sta/Elev= 30
  1903.2 1763.14    2019 1760.18  2202.3  1755.3  2599.8 1747.69  3640.4 1736.17
  4087.6 1741.08  4512.7 1738.72    4589 1736.89  4873.9 1726.81    5007 1725.24
  5021.2 1716.72  5035.4 1718.75  5042.7 1725.17  5262.1 1732.59  6075.9 1731.19
  6207.7 1731.52  6325.7 1730.76  6501.3 1730.36  6740.7 1731.19  6832.6 1728.04
  6862.4 1730.93  7076.5 1728.68  7300.7  1726.6  7376.8 1726.51  8205.7 1731.25
    8428 1726.73  8665.5 1724.63  8878.5 1731.05  9147.3 1744.24  9257.5 1749.43
#Mann= 20 ,-1 , 0
  1903.2    .055       0    2019     .07       0  2202.3    .045       0
  2599.8    .045       0  4512.7     .05       0    4589    .045       0
  4873.9     .05       0    5007    .045       0  5042.7     .07       0
  6075.9     .16       0  6207.7     .07       0  6325.7     .16       0
  6501.3     .07       0  6862.4    .045       0  7076.5     .07       0
  7300.7     .07       0  7376.8    .045       0    8428     .07       0
  8878.5     .07       0  9147.3    .045       0
Bank Sta=5007,5042.7
XS Rating Curve= 0 ,0
Exp/Cntr=0.3,0.1

Type RM Length L Ch R = 1 ,117558  ,2908,2908,2908
BEGIN DESCRIPTION:
Mapping XS c0bd88ba
END DESCRIPTION:
XS GIS Cut Line= 3
      1533551.65       6872647.6      1532944.01       6869331.6
       1535154.9      6866775.52
#Sta/Elev= 30
  2245.6 1739.61  4619.1 1734.85  4725.6 1732.13  4868.2 1729.77  4974.1 1721.24
    4980  1714.8  5000.3 1713.18  5010.5 1714.73  5020.7 1722.86  5027.2 1725.21
  5203.6 1726.27  5264.6 1730.32    5913 1729.47  6133.2  1729.6  6194.1 1730.46
  6388.3 1724.92  6597.5 1724.56  6688.2 1724.95  6814.1 1726.19    6843 1726.36
  6962.4 1725.32  7197.3 1727.23  7938.1 1730.69  8094.5  1727.8  8373.9 1724.96
  8611.8 1729.95  8720.2 1732.61  8837.6 1740.08  8869.6 1743.81  8996.4 1747.36
#Mann= 20 ,-1 , 0
  2245.6    .055       0  4619.1     .05       0  4725.6     .07       0
  4974.1    .045       0  5020.7     .07       0    5913     .16       0
  6133.2     .07       0  6388.3     .07       0  6597.5     .05       0
  6688.2     .07       0  6814.1     .05       0    6843     .07       0
  6962.4     .05       0  7197.3    .045       0  8094.5     .07       0
  8373.9     .07       0  8611.8     .05       0  8720.2     .05       0
  8837.6     .07       0  8869.6    .045       0
Bank Sta=4974.1,5020.7
XS Rating Curve= 0 ,0
Exp/Cntr=0.3,0.1

Type RM Length L Ch R = 1 ,114650  ,1865,1865,1865
BEGIN DESCRIPTION:
Mapping XS ce4215fa
END DESCRIPTION:
XS GIS Cut Line= 4
      1535079.99      6870912.97      1534474.96      6868387.74
      1534309.38      6867897.03      1535258.61      6866747.34
#Sta/Elev= 30
  2403.3 1733.69  3151.9  1728.2  3301.8 1727.84  3405.9 1720.27  4177.1 1727.34
  4424.7 1727.63  4550.8 1723.91  4587.7 1726.69  4635.2 1725.82  4736.5 1725.28
  4999.9 1717.75  5010.3 1713.91  5015.5 1716.82  5031.4 1712.72    5047 1714.69
  5052.5  1720.9  5167.6 1721.06    5334 1726.14  5516.9 1729.15  5913.3 1728.87
  6160.7 1723.89    6274 1725.25  6405.9 1728.24    6644 1732.37  6689.4 1736.61
  6728.7 1742.24  6813.6 1745.44  6879.2  1744.5  6937.8 1742.81  7008.8 1746.02
#Mann= 15 ,-1 , 0
  2403.3    .055       0  3151.9     .05       0  3301.8     .07       0
  4635.2     .16       0  4736.5     .07       0  4999.9    .045       0
  5052.5     .07       0    5334    .045       0  5913.3     .07       0
    6274     .05       0  6405.9     .07       0  6689.4     .05       0
  6813.6    .045       0  6879.2     .07       0  6937.8     .05       0
Bank Sta=4999.9,5052.5
XS Rating Curve= 0 ,0
Exp/Cntr=0.3,0.1

Type RM Length L Ch R = 1 ,112785  ,1410,1410,1410
BEGIN DESCRIPTION:
Mapping XS 851a436c
END DESCRIPTION:
XS GIS Cut Line= 3
      1535154.47      6871009.43      1535527.72      6868040.72
      1535996.47      6866408.79
#Sta/Elev= 30
  1983.6 1733.59  2307.6 1732.26  2916.4 1726.53  3065.9 1724.93  3164.3 1723.78
  3487.2 1725.91  4132.9 1726.31  4327.9 1724.41  4456.5 1722.84  4726.5 1719.74
  4928.6 1719.37  4983.8 1717.63    4989 1712.89  5009.7 1710.35  5022.7 1719.11
  5040.9 1719.88  5061.7 1716.98  5095.4 1719.34    5168  1719.6  5416.6  1725.6
  5436.9 1725.88  5498.7 1727.69  6034.5 1728.89    6070 1730.36  6174.5 1735.58
  6221.2 1735.51    6325 1734.62  6443.5 1740.39  6649.8 1749.17  6673.6 1749.66
#Mann= 16 ,-1 , 0
  1983.6    .055       0  2916.4     .05       0  3065.9    .045       0
  3487.2     .07       0  4132.9     .16       0  4327.9     .07       0
  4456.5     .05       0  4928.6     .07       0  4983.8    .045       0
  5022.7     .07       0  5416.6     .05       0  5436.9    .045       0
    6070     .07       0  6221.2     .05       0  6443.5     .07       0
  6649.8    .045       0
Bank Sta=4983.8,5022.7
XS Rating Curve= 0 ,0
Exp/Cntr=0.3,0.1

Type RM Length L Ch R = 1 ,111375  ,1546,1546,1546
BEGIN DESCRIPTION:
Mapping XS 19f6cafb
END DESCRIPTION:
XS GIS Cut Line= 3
      1536045.52      6871270.33      1536479.55      6869067.63
      1536154.02      6866463.45
#Sta/Elev= 30
  2692.1  1728.8  4167.3 1725.32  4391.9 1721.48  4549.5 1719.87  4865.4 1720.95
  4906.2 1717.81  4956.9 1717.63  4987.2 1714.31  4997.2 1715.94  5013.2 1707.74
  5018.3 1710.48  5027.5 1708.42  5047.6 1714.35  5057.7 1718.39  5077.9 1719.09
  5188.7 1717.43  5345.4 1719.35  5410.4  1718.2  5722.9 1723.77  6922.1 1726.79
  6983.2 1728.48  7022.9 1730.37  7063.2 1737.55  7081.9 1738.78  7244.6    1739
  7351.3 1745.23  7380.1  1745.1  7393.4 1744.94  7410.7 1744.74  7561.6 1747.24
#Mann= 11 ,-1 , 0
  2692.1    .055       0  4167.3     .05       0  4391.9    .045       0
  4997.2    .045       0  5047.6    .045       0  5345.4    .045       0
  6983.2     .07       0  7081.9     .05       0  7380.1     .07       0
  7393.4    .045       0  7410.7     .07       0
Bank Sta=4997.2,5047.6
XS Rating Curve= 0 ,0
Exp/Cntr=0.3,0.1

Type RM Length L Ch R = 1 ,109829  ,4144,4144,4144
BEGIN DESCRIPTION:
Mapping XS e5e7045d
END DESCRIPTION:
XS GIS Cut Line= 4
      1536305.96      6871454.74      1537609.69      6868787.97
      1537423.56      6867168.76        1536280.        6866063.
#Sta/Elev= 30
  2031.6  1727.7  3776.2  1724.8  3798.1 1726.16  3871.2 1724.39  4136.4 1721.23
  4253.1 1715.83  4316.5 1713.61  4443.4 1717.25  4699.3  1717.2    4885 1714.23
    4930 1715.66  4968.9 1711.33  4978.5 1705.73  4988.5 1705.77  4998.5 1711.16
  5008.5  1714.1  5018.5 1716.14  5054.5 1716.84  5124.2 1717.54  5221.4 1720.97
  5281.8 1720.91  5654.3 1715.46  5976.4 1721.35  7230.5 1724.15  7381.8  1727.2
  7748.8 1743.83  7824.5 1748.89  8021.4 1750.45  8073.1 1750.62  8220.6 1752.18
#Mann= 12 ,-1 , 0
  2031.6    .055       0  3798.1     .05       0  3871.2    .045       0
  4253.1     .07       0  4968.9    .045       0  5008.5     .07       0
  5054.5    .045       0  5124.2    .045       0  7381.8     .07       0
  7748.8    .045       0  8021.4     .07       0  8073.1    .045       0
Bank Sta=4968.9,5008.5
XS Rating Curve= 0 ,0
Exp/Cntr=0.3,0.1

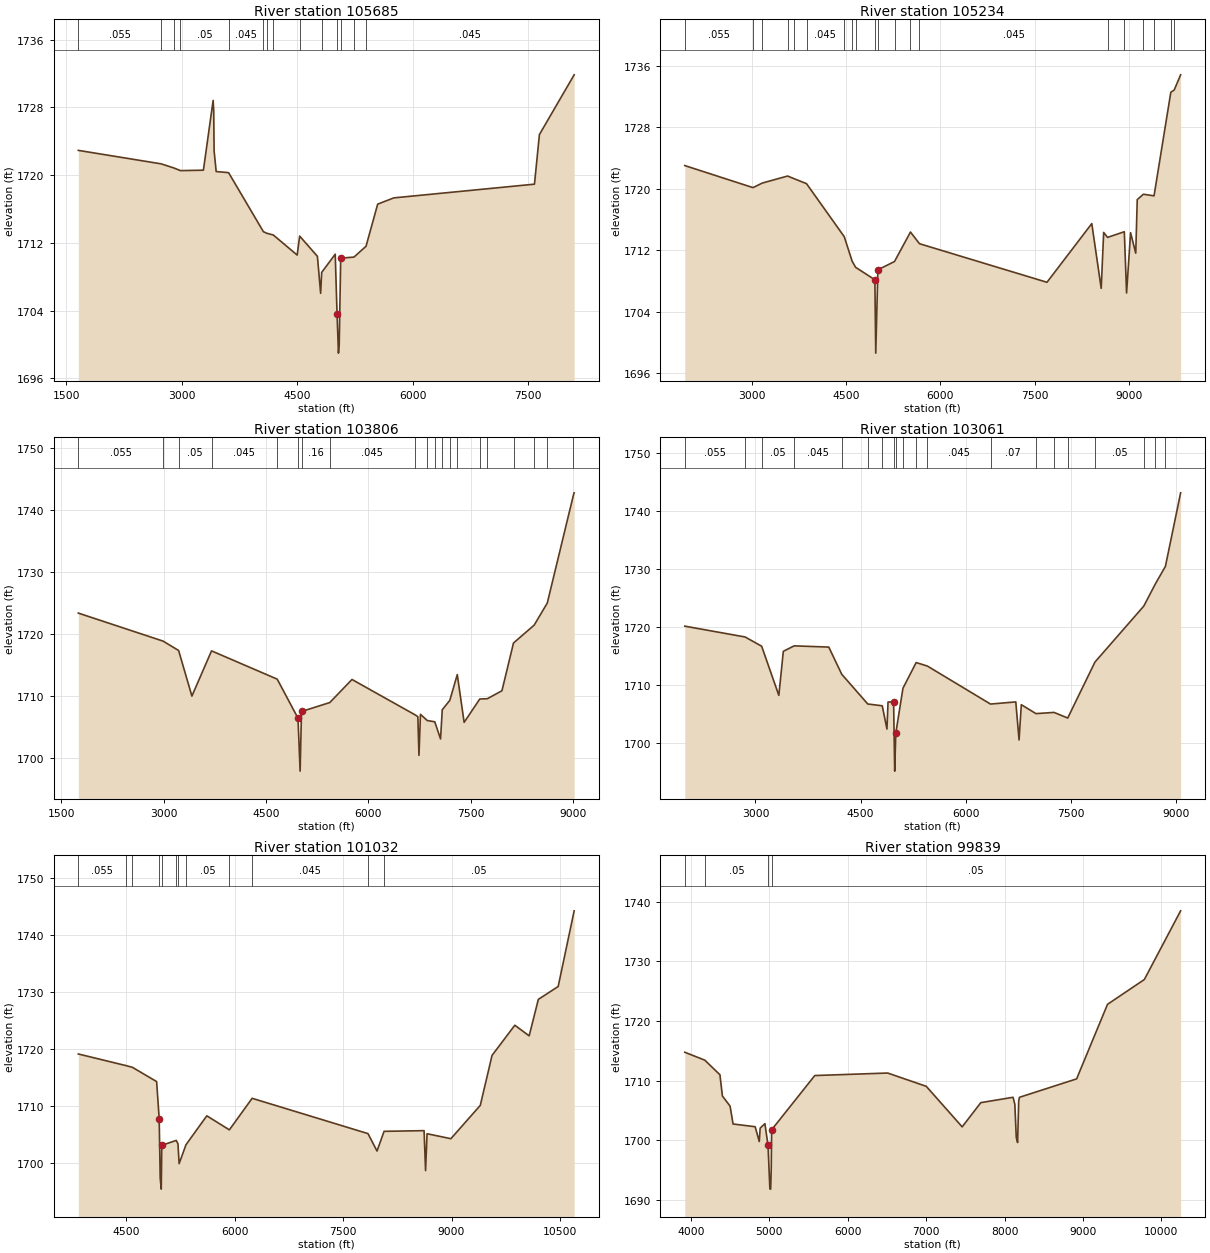
Type RM Length L Ch R = 1 ,105685  ,451,451,451
BEGIN DESCRIPTION:
Mapping XS ef30d866
END DESCRIPTION:
XS GIS Cut Line= 5
      1538033.37      6871496.02      1538727.81      6869325.88
      1538892.74      6868258.17      1538964.22      6867732.57
      1537418.56      6865701.59
#Sta/Elev= 30
  1656.4 1722.93  2731.8 1721.34  2895.2 1720.86  2983.4 1720.54  3281.2 1720.59
  3407.7 1728.83  3415.1 1727.65  3420.3 1722.87  3447.2 1720.43  3608.6  1720.3
  4060.7 1713.33  4106.2 1713.14  4189.6 1712.94  4499.4 1710.57    4532 1712.81
  4762.5 1710.42  4804.5 1706.05    4818 1708.52  4993.8 1710.67  5017.9 1703.56
  5035.7 1698.99  5045.8    1700    5065  1710.2  5237.5 1710.33    5394 1711.61
  5545.5 1716.58  5754.9 1717.32  7582.4 1718.94  7646.8  1724.8    8098 1731.85
#Mann= 14 ,-1 , 0
  1656.4    .055       0  2731.8     .07       0  2895.2    .045       0
  2983.4     .05       0  3608.6    .045       0  4060.7     .05       0
  4106.2     .07       0  4189.6     .05       0    4532     .07       0
    4818     .05       0  5017.9    .035       0    5065     .07       0
  5237.5     .05       0    5394    .045       0
Bank Sta=5017.9,5065
XS Rating Curve= 0 ,0
Exp/Cntr=0.3,0.1

Type RM Length L Ch R = 1 ,105234  ,1428,1428,1428
BEGIN DESCRIPTION:
Mapping XS 8debbc19
END DESCRIPTION:
XS GIS Cut Line= 4
      1538276.43      6871617.52      1539005.59      6868657.48
      1539185.39       6867773.4      1540282.95      6863992.29
#Sta/Elev= 30
  1935.7 1723.02  3020.4 1720.15  3170.6 1720.75  3571.3 1721.66  3671.5 1721.32
  3871.8 1720.67  4472.8 1713.76  4597.6 1710.58    4653 1709.78  4959.4 1708.16
  4973.4 1698.61  5007.8 1709.46  5271.8 1710.53  5525.8 1714.37  5669.2 1712.85
  7697.6 1707.83  8410.4 1715.47  8560.2 1707.04  8599.4 1714.32  8660.9 1713.67
  8927.8 1714.41  8963.8 1706.44  9027.6 1714.28  9109.6 1711.62  9133.5 1718.59
    9231 1719.29  9400.7 1719.08  9667.5 1732.56  9721.8 1732.86  9823.6 1734.83
#Mann= 20 ,-1 , 0
  1935.7    .055       0  3020.4     .07       0  3170.6     .05       0
  3571.3     .07       0  3671.5     .05       0  3871.8    .045       0
  4472.8     .05       0  4597.6    .045       0    4653     .05       0
  4959.4    .035       0  5007.8     .05       0  5271.8     .07       0
  5525.8     .07       0  5669.2    .045       0  8660.9    .045       0
  8927.8     .07       0    9231     .05       0  9400.7     .07       0
  9667.5     .05       0  9721.8     .07       0
Bank Sta=4959.4,5007.8
XS Rating Curve= 0 ,0
Exp/Cntr=0.3,0.1

Type RM Length L Ch R = 1 ,103806  ,745,745,745
BEGIN DESCRIPTION:
Mapping XS 1d3eee4c
END DESCRIPTION:
XS GIS Cut Line= 4
      1538796.03      6871724.18      1539434.04      6869549.73
      1539905.04      6868688.08      1541825.26      6865162.95
#Sta/Elev= 30
  1751.9 1723.36  2994.4 1718.83  3220.8 1717.32  3415.4 1709.96  3702.9 1717.26
  4665.3 1712.69  4969.3 1706.39  5000.5 1697.84  5020.6 1707.47  5434.6 1708.91
  5760.2 1712.64  6682.8 1706.94  6724.9 1706.63  6741.1 1700.39  6762.9 1707.01
  6862.8 1706.01  6972.7 1705.81  7057.3 1703.04  7082.5 1707.76  7192.4 1709.26
  7302.3 1713.43  7402.8 1705.72  7631.8 1709.49  7741.7 1709.53  7956.5 1710.82
  8125.8 1718.53  8428.8 1721.42  8620.6 1724.98  9002.9 1742.39  9014.2 1742.78
#Mann= 20 ,-1 , 0
  1751.9    .055       0  2994.4     .07       0  3220.8     .05       0
  3702.9    .045       0  4665.3     .05       0  4969.3    .045       0
  5020.6     .16       0  5434.6    .045       0  6682.8     .16       0
  6862.8     .07       0  6972.7     .16       0  7082.5     .07       0
  7192.4     .16       0  7302.3     .07       0  7631.8     .16       0
  7741.7     .05       0  8125.8     .07       0  8428.8     .05       0
  8620.6     .07       0  9002.9     .05       0
Bank Sta=4969.3,5020.6
XS Rating Curve= 0 ,0
Exp/Cntr=0.3,0.1

Type RM Length L Ch R = 1 ,103061  ,2029,2029,2029
BEGIN DESCRIPTION:
Mapping XS 52a02301
END DESCRIPTION:
XS GIS Cut Line= 6
      1539097.56      6871374.47      1539507.27      6869638.39
      1539862.34      6869150.24      1540393.84      6868828.49
      1540577.87      6868818.53      1541925.99      6865175.04
#Sta/Elev= 30
  1991.3 1720.08  2852.7 1718.21  3088.3 1716.62  3333.7 1708.14  3397.8 1715.74
  3552.4 1716.68  4046.6 1716.47  4231.8 1711.78  4603.3 1706.65  4810.1 1706.34
    4877 1702.33  4892.5 1706.99  4972.1 1707.01  4987.6 1695.07  5003.1 1701.59
  5105.5 1709.37    5294  1713.8  5455.2 1713.19  6355.2 1706.64  6716.3 1707.01
  6762.9 1700.45  6794.9 1706.53  7004.6 1704.99  7261.8  1705.2  7457.6 1704.23
  7846.5 1713.89  8543.3 1723.54  8708.8 1727.37  8852.1 1730.39  9069.2 1743.08
#Mann= 20 ,-1 , 0
  1991.3    .055       0  2852.7     .07       0  3088.3     .05       0
  3552.4    .045       0  4231.8     .05       0  4603.3     .07       0
  4810.1     .16       0  4972.1    .045       0  5003.1     .16       0
  5105.5     .07       0    5294    .045       0  5455.2    .045       0
  6355.2     .07       0  7004.6     .05       0  7261.8     .16       0
  7457.6     .07       0  7846.5     .05       0  8543.3     .07       0
  8708.8     .05       0  8852.1     .05       0
Bank Sta=4972.1,5003.1
XS Rating Curve= 0 ,0
Exp/Cntr=0.3,0.1

Type RM Length L Ch R = 1 ,101032  ,1193,1193,1193
BEGIN DESCRIPTION:
Mapping XS e981e819
END DESCRIPTION:
XS GIS Cut Line= 4
      1539452.68      6871351.99      1539822.46      6870393.69
      1540884.96      6869440.56        1541985.      6865178.56
#Sta/Elev= 30
  3839.7 1719.16  4492.9 1717.14  4587.8 1716.82  4922.5 1714.32  4957.7 1707.81
  4971.9 1697.43  4986.1 1695.47  4992.8  1702.2  5000.3 1703.17  5193.5 1704.01
  5217.4 1703.42  5233.5 1699.94  5327.9 1703.24  5616.3 1708.32  5928.4 1705.86
    6243 1711.39  7845.1  1705.2    7970 1702.15  8067.5  1705.6  8620.6 1705.72
  8641.3 1698.72  8661.9 1705.18  8991.3 1704.31  9397.9 1710.15  9560.5 1718.91
  9875.5  1724.2 10073.7 1722.34 10200.8 1728.73 10475.1 1730.99 10695.9 1744.25
#Mann= 12 ,-1 , 0
  3839.7    .055       0  4492.9     .05       0  4587.8     .07       0
  4957.7    .045       0  5000.3     .07       0  5193.5     .07       0
  5217.4    .045       0  5327.9     .05       0  5928.4     .07       0
    6243    .045       0  7845.1     .07       0  8067.5     .05       0
Bank Sta=4957.7,5000.3
XS Rating Curve= 0 ,0
Exp/Cntr=0.3,0.1

Type RM Length L Ch R = 1 ,99839   ,171,171,171
BEGIN DESCRIPTION:
Mapping XS 22c1a7dd
END DESCRIPTION:
XS GIS Cut Line= 4
      1540473.49      6871346.85      1540775.59      6870346.81
      1540924.63      6869752.84      1542106.06      6865241.12
#Sta/Elev= 30
  3923.8 1714.77    4179 1713.44  4371.8 1710.99  4403.1 1707.43    4501 1705.73
  4539.2 1702.73    4821 1702.27  4873.2 1699.79  4884.4 1702.03  4945.1 1702.79
  4984.7 1699.15  5008.5 1691.84  5018.8  1691.8  5025.8 1695.31    5031 1701.76
  5580.8 1710.86  6510.5 1711.28  7002.1 1709.05  7459.8 1702.25  7697.1 1706.31
  8108.1 1707.21  8131.3 1706.04  8149.5 1700.49  8166.5 1699.62  8180.5  1706.6
  8190.8 1707.21  8918.8  1710.3  9312.6 1722.81  9782.1 1726.97 10244.7  1738.5
#Mann= 4 ,-1 , 0
  3923.8    .055       0    4179     .05       0  4984.7    .035       0
    5031     .05       0
Bank Sta=4984.7,5031
XS Rating Curve= 0 ,0
Exp/Cntr=0.3,0.1

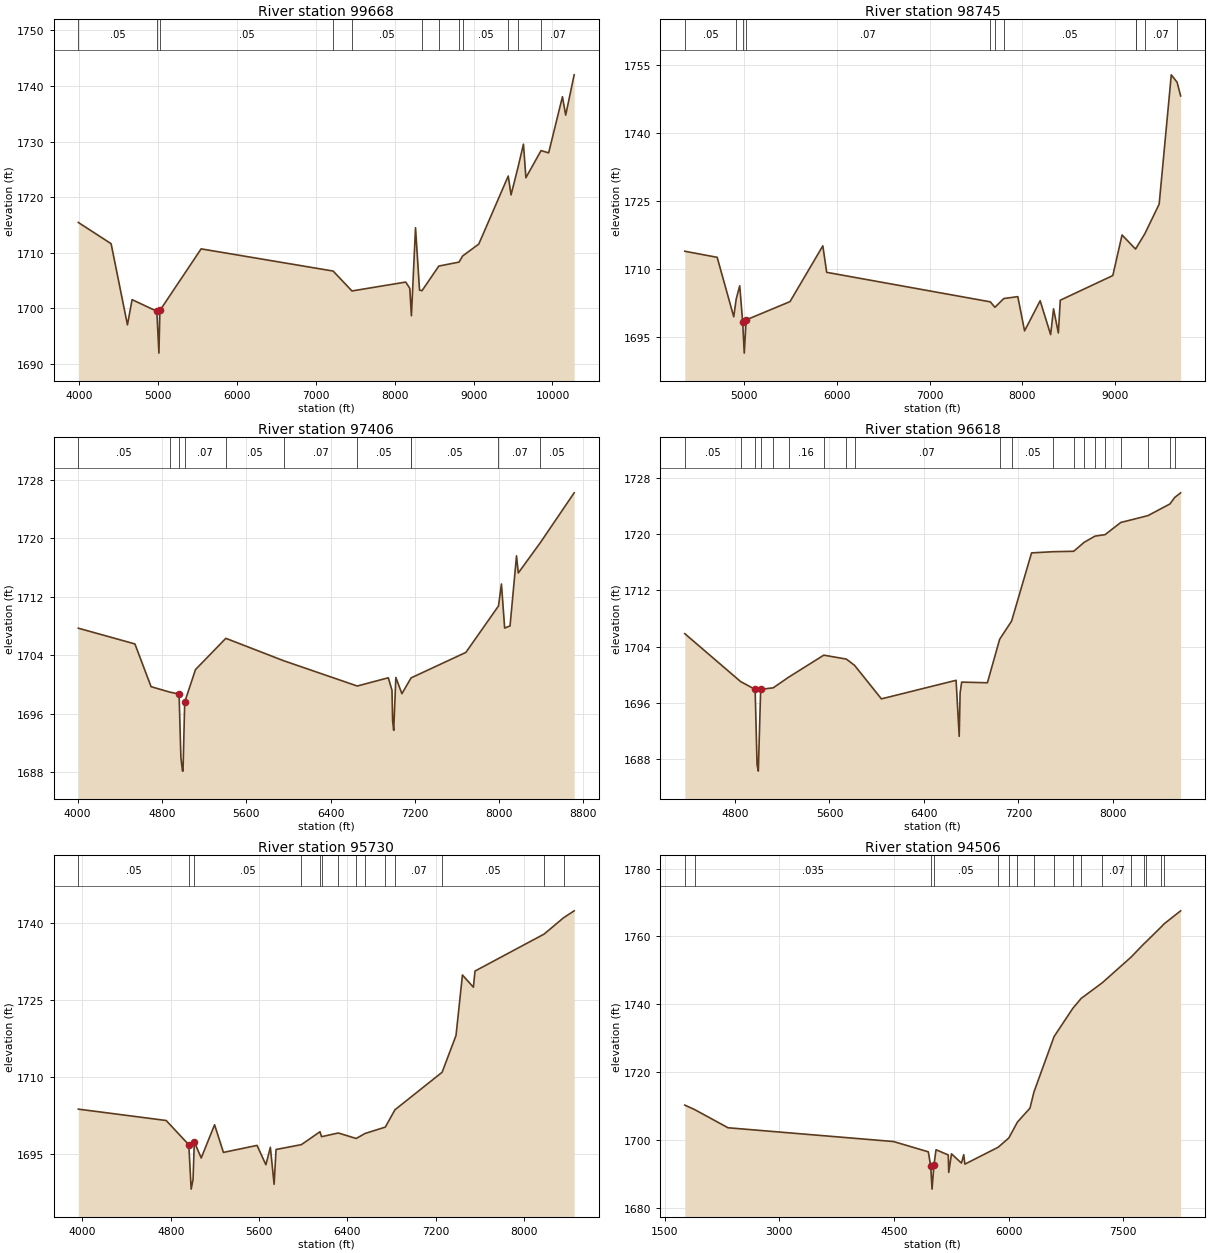
Type RM Length L Ch R = 1 ,99668   ,923,923,923
BEGIN DESCRIPTION:
Mapping XS 60f99294
END DESCRIPTION:
XS GIS Cut Line= 3
        1540661.      6871419.73      1540895.38      6870471.81
      1542160.15      6865313.67
#Sta/Elev= 30
  3987.3 1715.47    4403 1711.65  4610.2 1697.06    4669 1701.59  4982.6  1699.5
  5009.2 1691.97  5021.8 1699.64  5544.3 1710.72  7218.5 1706.73  7457.1 1703.15
  8138.9 1704.75  8190.4 1703.62    8211 1698.69  8263.1 1714.52    8314  1703.3
  8345.4  1703.2  8558.6 1707.63  8815.1 1708.34  8860.5 1709.44  9065.6 1711.59
  9438.9 1723.82  9474.3 1720.43  9560.1 1725.23  9631.9 1729.55  9662.8 1723.52
    9855  1728.4  9951.1 1727.98 10126.1 1738.08 10167.3 1734.78 10274.7 1742.02
#Mann= 12 ,-1 , 0
  3987.3     .05       0  4982.6    .035       0  5021.8     .05       0
  7218.5     .07       0  7457.1     .05       0  8345.4     .07       0
  8558.6     .05       0  8815.1     .07       0  8860.5     .05       0
  9438.9     .07       0  9560.1     .05       0    9855     .07       0
Bank Sta=4982.6,5021.8
XS Rating Curve= 0 ,0
Exp/Cntr=0.3,0.1

Type RM Length L Ch R = 1 ,98745   ,1339,1339,1339
BEGIN DESCRIPTION:
Mapping XS d9bb5ca2
END DESCRIPTION:
XS GIS Cut Line= 3
        1540830.        6871563.      1541218.04      6871052.04
      1542534.93      6866531.24
#Sta/Elev= 30
  4358.4 1713.89  4707.8 1712.55  4886.6 1699.44    4913 1703.35  4951.1 1706.28
  4982.9 1698.31  5000.1 1691.42  5020.4 1698.75  5493.7 1702.78  5847.9 1715.08
  5889.5 1709.24  7655.4 1702.73  7704.9 1701.53  7800.6 1703.46  7951.8 1703.88
  8024.7 1696.33    8193 1702.97    8306 1695.51  8337.4 1701.19  8389.3 1695.87
  8410.1 1703.09  8976.9 1708.53  9076.7 1717.48  9222.5 1714.37  9222.9 1714.39
  9323.7  1717.8  9477.1 1724.28  9607.9  1752.8  9670.9 1751.16  9708.7 1748.15
#Mann= 11 ,-1 , 0
  4358.4     .05       0    4913     .07       0  4982.9    .045       0
  5020.4     .07       0  7655.4     .05       0  7704.9     .07       0
  7800.6     .05       0  9222.5     .07       0  9222.9     .05       0
  9323.7     .07       0  9670.9     .05       0
Bank Sta=4982.9,5020.4
XS Rating Curve= 0 ,0
Exp/Cntr=0.3,0.1

Type RM Length L Ch R = 1 ,97406   ,788,788,788
BEGIN DESCRIPTION:
Mapping XS 7ffea320
END DESCRIPTION:
XS GIS Cut Line= 3
      1541822.45      6871409.35      1542207.45      6870493.48
      1542980.01      6866862.97
#Sta/Elev= 30
  4006.5  1707.7  4543.5 1705.54  4696.9 1699.68  4878.4 1698.92  4962.6 1698.67
  4979.8 1689.96  4994.8  1688.1    5000  1688.1    5016 1697.57  5118.1 1702.02
  5406.2 1706.31  5954.7 1703.24  6653.3 1699.77  6948.1  1700.9    6983 1699.19
    6989 1695.01  6999.3 1693.69  7019.7 1700.94  7077.1 1698.72  7162.9 1700.85
  7165.1 1700.89  7684.3 1704.38  7993.8 1710.75  8021.7 1713.76  8052.3 1707.72
  8103.4 1708.01  8164.8 1717.62  8181.7 1715.27  8390.9 1719.43  8711.8 1726.26
#Mann= 11 ,-1 , 0
  4006.5     .05       0  4878.4     .07       0  4962.6    .045       0
    5016     .07       0  5406.2     .05       0  5954.7     .07       0
  6653.3     .05       0  7162.9     .07       0  7165.1     .05       0
  7993.8     .07       0  8390.9     .05       0
Bank Sta=4962.6,5016
XS Rating Curve= 0 ,0
Exp/Cntr=0.3,0.1

Type RM Length L Ch R = 1 ,96618   ,888,888,888
BEGIN DESCRIPTION:
Mapping XS e218a0f8
END DESCRIPTION:
XS GIS Cut Line= 3
      1542619.33      6871325.99      1542864.13       6870773.9
      1543832.17      6867312.55
#Sta/Elev= 30
    4375 1705.85  4848.2 1699.04  4970.6 1697.94  4986.8 1687.26  4997.5 1686.33
  5017.4 1697.95  5123.8 1698.16  5253.2 1699.66  5551.9  1702.8  5743.1 1702.24
  5812.5 1701.35  6039.7 1696.59    6672 1699.23  6698.4 1691.27  6706.1 1697.44
  6719.1 1698.97  6937.2 1698.88  7040.8 1705.05  7141.7 1707.63    7311 1717.32
  7494.3 1717.49  7667.9 1717.55    7756 1718.82    7848  1719.7  7933.4 1719.91
  8066.4 1721.64  8296.1 1722.61  8482.6 1724.27    8523 1725.19  8573.1 1725.85
#Mann= 20 ,-1 , 0
    4375     .05       0  4848.2     .07       0  4970.6    .045       0
  5017.4     .07       0  5123.8     .05       0  5253.2     .16       0
  5551.9     .07       0  5743.1     .16       0  5812.5     .07       0
  7040.8     .07       0  7141.7     .05       0  7494.3     .07       0
  7667.9     .05       0    7756     .07       0    7848     .05       0
  7933.4     .07       0  8066.4     .16       0  8296.1     .07       0
  8482.6     .16       0    8523     .07       0
Bank Sta=4970.6,5017.4
XS Rating Curve= 0 ,0
Exp/Cntr=0.3,0.1

Type RM Length L Ch R = 1 ,95730   ,1224,1224,1224
BEGIN DESCRIPTION:
MULBERRY CREEK 24.0
END DESCRIPTION:
XS GIS Cut Line= 3
      1542879.79      6871617.62      1543698.95      6870929.85
       1545055.1      6867748.55
#Sta/Elev= 30
  3963.7 1703.72  4759.2  1701.5  4964.2 1696.76  4985.4  1688.1  5002.5 1689.98
  5013.8 1697.34  5076.5 1694.18  5197.5 1700.67  5277.7 1695.27  5582.1 1696.64
  5662.1 1692.86  5702.6 1696.27  5736.6 1689.04  5754.1 1695.84  5983.9 1696.79
  6152.2 1699.31  6165.7 1698.34  6317.9 1699.06  6479.8 1697.99  6560.5 1698.97
  6743.3 1700.21  6831.1  1703.6  7257.8 1710.92  7383.7  1718.1  7441.9 1729.91
    7541 1727.53  7555.7 1730.68  8181.5  1737.9  8357.3 1741.08  8453.5 1742.44
#Mann= 14 ,-1 , 0
  3963.7     .05       0  4964.2    .045       0  5013.8     .05       0
  5983.9     .05       0  6152.2     .07       0  6165.7     .05       0
  6317.9     .07       0  6479.8     .05       0  6560.5     .07       0
  6743.3     .05       0  6831.1     .07       0  7257.8     .05       0
  8181.5     .07       0  8357.3     .05       0
Bank Sta=4964.2,5013.8
XS Rating Curve= 0 ,0
Exp/Cntr=0.3,0.1

Type RM Length L Ch R = 1 ,94506   ,1628,1628,1628
BEGIN DESCRIPTION:
MULBERRY CREEK 23.0
END DESCRIPTION:
XS GIS Cut Line= 3
      1541318.75      6872190.74      1544484.88      6871518.05
      1547207.93      6869745.02
#Sta/Elev= 30
  1763.2 1710.34  1892.1 1709.02  2328.2 1703.67  4494.5 1699.61    4949 1696.58
  4980.5  1692.3  4997.5  1685.6  5022.8 1692.79  5049.9 1697.19  5209.9 1695.66
  5215.9 1690.52  5252.1 1695.99    5382 1693.27  5412.1 1695.75  5427.3 1692.96
  5862.3 1697.93    6002 1700.66  6115.1 1705.36  6278.4 1709.43  6331.1 1714.23
    6594 1730.52    6839 1738.83  6948.2 1741.75  7225.1 1746.37  7599.8 1753.88
  7771.9 1757.89  7792.9 1758.32  7992.9 1762.75  8031.6 1763.67  8249.4 1767.54
#Mann= 17 ,-1 , 0
  1763.2     .07       0  1892.1    .035       0  4980.5    .045       0
  5022.8     .05       0  5862.3     .05       0    6002     .07       0
  6115.1     .05       0  6331.1     .07       0    6594     .05       0
    6839     .07       0  6948.2     .05       0  7225.1     .07       0
  7599.8     .05       0  7771.9     .07       0  7792.9     .05       0
  7992.9     .07       0  8031.6     .05       0
Bank Sta=4980.5,5022.8
XS Rating Curve= 0 ,0
Exp/Cntr=0.3,0.1