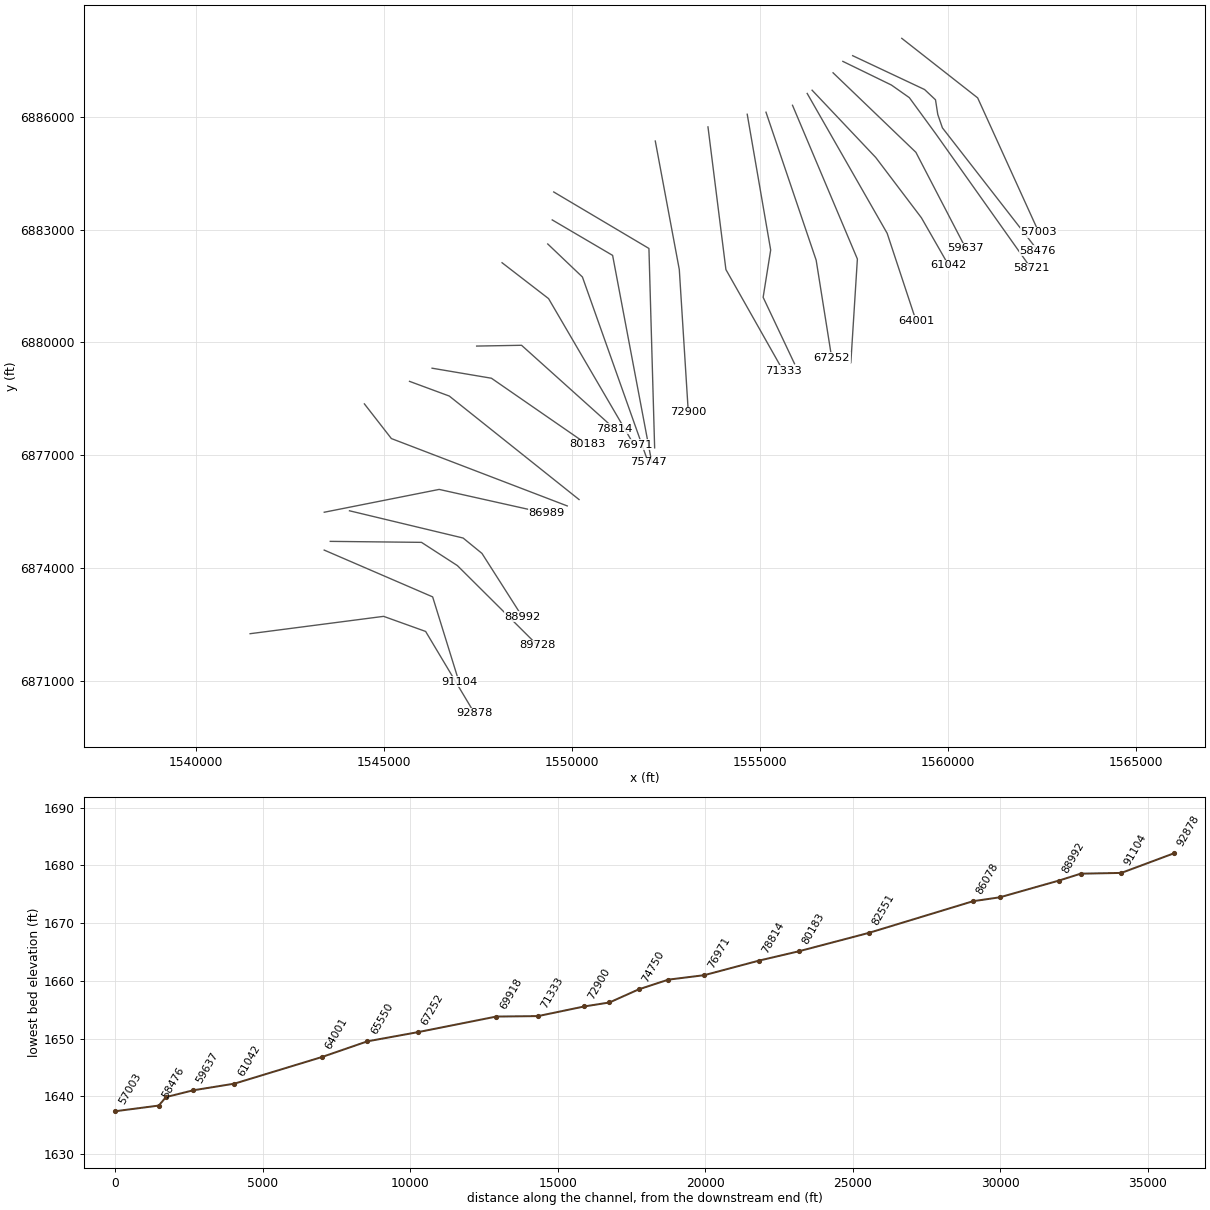
HEC-RAS study MULBERRY CREEK.prj: MULBERRY CREEK Base Level Engineering

--- MULBERRY CREEK.g01 (geometry) --- (continued)

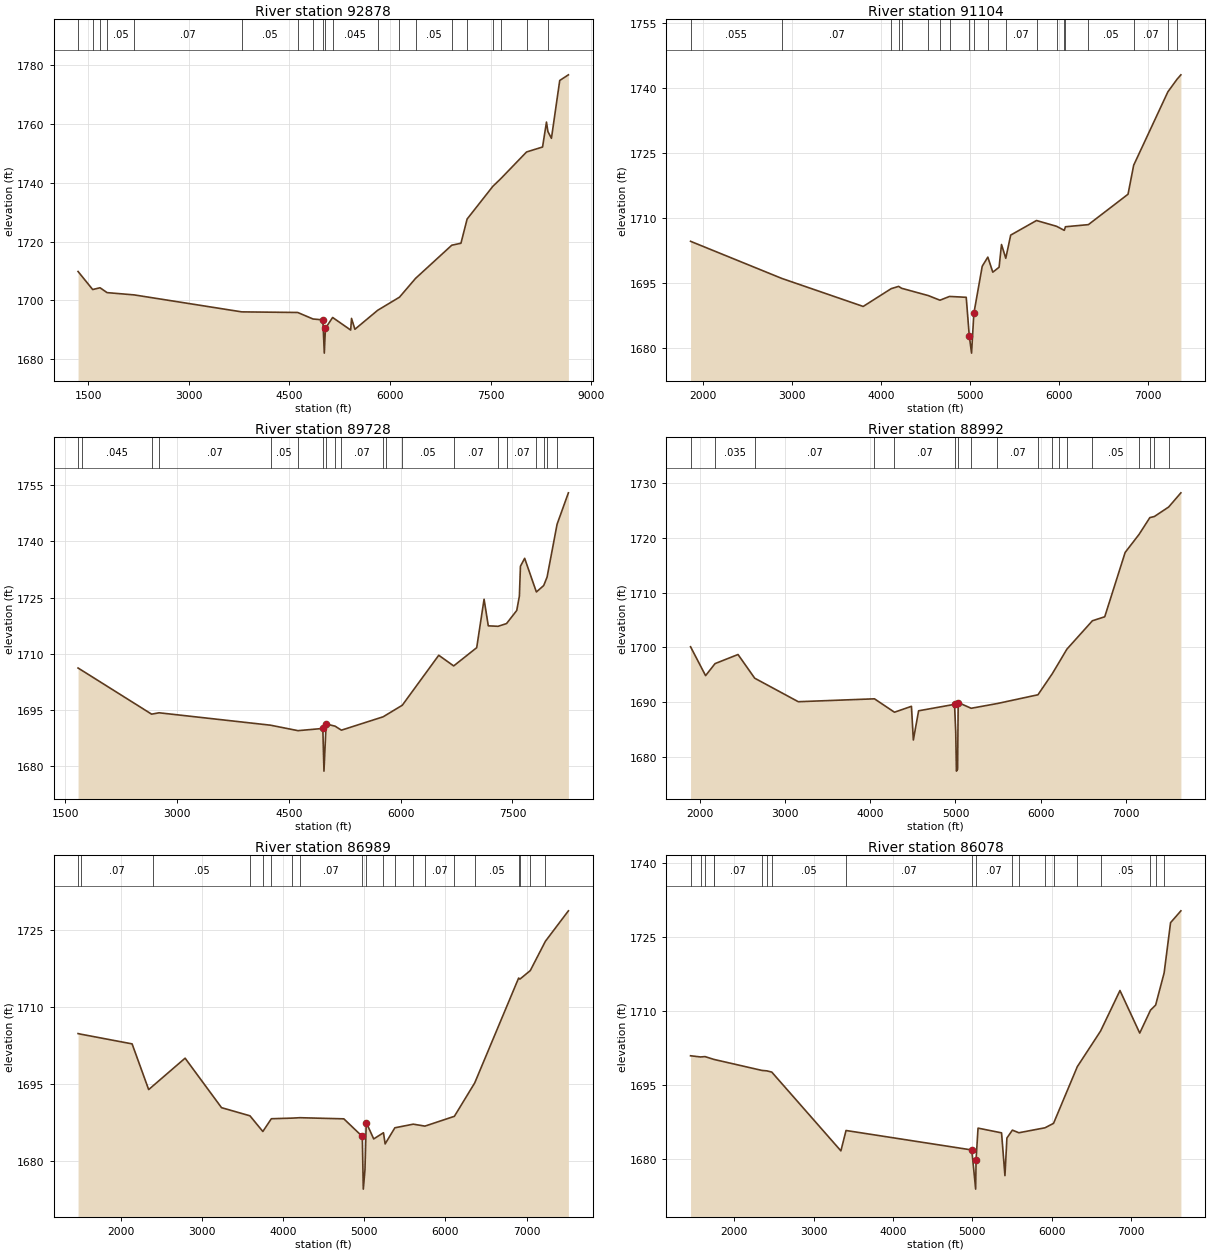
Type RM Length L Ch R = 1 ,92878   ,1774,1774,1774
BEGIN DESCRIPTION:
Mapping XS 49a216f2
END DESCRIPTION:
XS GIS Cut Line= 4
      1541440.27      6872247.34      1544990.88      6872709.02
       1546108.5      6872307.54      1547410.31      6870127.02
#Sta/Elev= 30
  1351.4 1709.87  1569.4 1703.73  1679.2 1704.33  1783.7 1702.68  2188.9  1701.9
    3790 1696.13  4624.8 1695.92  4852.5 1693.71  4999.9  1693.4  5021.3 1682.09
  5037.8 1690.54  5145.3 1694.22  5414.4 1689.94  5426.7 1693.91  5477.5 1690.21
  5816.4 1696.66  6141.6 1701.13  6381.3 1707.53  6920.8 1718.81  7057.6 1719.48
  7149.6 1727.72  7533.4 1738.86    7649  1741.4  8035.5 1750.54  8273.8 1752.23
  8332.2 1760.72  8353.6 1757.48  8406.1 1755.19  8529.8 1774.87    8659 1776.79
#Mann= 20 ,-1 , 0
  1351.4     .07       0  1569.4    .035       0  1679.2     .07       0
  1783.7     .05       0  2188.9     .07       0    3790     .05       0
  4624.8    .045       0  4852.5     .05       0  4999.9    .045       0
  5037.8     .12       0  5145.3    .045       0  5816.4     .05       0
  6141.6     .07       0  6381.3     .05       0  6920.8     .05       0
  7149.6     .07       0  7533.4     .05       0    7649     .07       0
  8035.5     .07       0  8353.6     .07       0
Bank Sta=4999.9,5037.8
XS Rating Curve= 0 ,0
Exp/Cntr=0.3,0.1

Type RM Length L Ch R = 1 ,91104   ,1376,1376,1376
BEGIN DESCRIPTION:
Mapping XS 3339e92a
END DESCRIPTION:
XS GIS Cut Line= 3
      1543411.31       6874472.4      1546295.36      6873227.14
      1546996.04      6870966.54
#Sta/Elev= 30
  1858.6 1704.53  2883.7 1695.96  3797.8 1689.49  4112.9  1693.6  4195.6 1694.12
  4230.2 1693.68  4530.1 1691.99  4660.3 1690.93  4767.9  1691.8  4955.3  1691.6
  4989.7 1682.65  5015.2 1678.71    5041 1687.88  5135.2 1698.78    5198 1700.88
  5253.9  1697.4  5324.3 1698.54  5351.6 1703.79  5399.6 1700.61  5454.7 1705.96
  5744.7 1709.33  5969.5    1708  6056.9 1707.06  6069.7 1707.89  6327.5 1708.38
  6772.9  1715.4  6836.2 1722.09  7220.4 1739.04  7323.4 1741.95  7366.7 1742.97
#Mann= 20 ,-1 , 0
  1858.6    .055       0  2883.7     .07       0  4112.9     .16       0
  4195.6    .045       0  4230.2     .16       0  4530.1    .045       0
  4660.3     .16       0  4767.9     .07       0  4989.7    .045       0
    5041     .07       0    5198     .05       0  5399.6     .07       0
  5744.7     .05       0  5969.5     .07       0  6056.9     .05       0
  6069.7     .07       0  6327.5     .05       0  6836.2     .07       0
  7220.4     .05       0  7323.4     .07       0
Bank Sta=4989.7,5041
XS Rating Curve= 0 ,0
Exp/Cntr=0.3,0.1

Type RM Length L Ch R = 1 ,89728   ,736,736,736
BEGIN DESCRIPTION:
Mapping XS 6c753149
END DESCRIPTION:
XS GIS Cut Line= 4
      1543572.18      6874704.44      1545998.55      6874678.06
      1546953.41      6874059.57      1549090.42      6871933.41
#Sta/Elev= 30
  1671.9 1706.15  1718.2 1705.58  2659.1 1693.81  2758.1 1694.18  4254.6 1690.86
  4622.5  1689.4  4955.9 1689.99  4971.1 1678.58  5000.1 1691.19  5120.4  1690.6
  5205.2 1689.53  5765.5 1693.11  5809.4 1693.64  6022.2  1696.2  6511.1 1709.56
  6711.5 1706.71  7020.2 1711.59  7119.2 1724.54  7175.8 1717.43  7306.5  1717.3
  7420.4 1718.03  7557.6 1721.54    7593 1725.39  7607.1 1733.36  7663.7 1735.48
    7821 1726.48  7919.1  1728.2  7964.6 1730.46  8098.9 1744.61  8250.6 1752.99
#Mann= 20 ,-1 , 0
  1671.9     .07       0  1718.2    .045       0  2659.1     .16       0
  2758.1     .07       0  4254.6     .05       0  4622.5     .07       0
  4955.9    .045       0  5000.1     .07       0  5120.4    .045       0
  5205.2     .07       0  5765.5     .05       0  5809.4     .07       0
  6022.2     .05       0  6711.5     .07       0  7306.5     .05       0
  7420.4     .07       0    7821     .16       0  7919.1     .07       0
  7964.6     .16       0  8098.9     .07       0
Bank Sta=4955.9,5000.1
XS Rating Curve= 0 ,0
Exp/Cntr=0.3,0.1

Type RM Length L Ch R = 1 ,88992   ,2003,2003,2003
BEGIN DESCRIPTION:
Mapping XS 4176b876
END DESCRIPTION:
XS GIS Cut Line= 4
       1544083.5      6875518.54      1547105.69      6874793.29
      1547607.12      6874383.82      1548680.35      6872699.69
#Sta/Elev= 30
    1892 1700.13  2068.4 1694.85  2179.7 1697.05  2448.9 1698.71  2644.6 1694.38
  3155.9 1690.08  4049.4 1690.61  4284.3 1688.16  4483.5 1689.24  4505.7 1683.08
  4567.4 1688.42    4989  1689.6    5003  1684.5  5010.9 1677.39  5024.9 1677.72
  5031.7 1689.93  5184.1 1688.88    5491 1689.75  5967.7 1691.35  6136.4 1695.22
  6216.5 1697.31  6306.1 1699.67  6606.2 1704.88  6750.9 1705.61  6990.4 1717.37
    7154 1720.68  7280.2 1723.74  7333.2 1723.94  7501.1 1725.68  7644.4 1728.27
#Mann= 18 ,-1 , 0
    1892     .07       0  2179.7    .035       0  2644.6     .07       0
  4049.4     .05       0  4284.3     .07       0    4989    .045       0
  5031.7     .07       0  5184.1     .05       0    5491     .07       0
  5967.7     .05       0  6136.4     .07       0  6216.5     .05       0
  6306.1     .07       0  6606.2     .05       0    7154     .07       0
  7280.2     .05       0  7333.2     .07       0  7501.1     .05       0
Bank Sta=4989,5031.7
XS Rating Curve= 0 ,0
Exp/Cntr=0.3,0.1

Type RM Length L Ch R = 1 ,86989   ,911,911,911
BEGIN DESCRIPTION:
Mapping XS 87789f03
END DESCRIPTION:
XS GIS Cut Line= 3
      1543412.35      6875479.87      1546468.93      6876087.24
      1549319.37       6875450.2
#Sta/Elev= 30
  1476.7 1704.85  1512.1 1704.73  2142.1 1702.84    2346 1693.92  2396.7 1694.61
  2794.6 1700.05  3243.2 1690.39  3593.1  1688.8  3751.8 1685.74  3856.4 1688.23
  4114.6 1688.35  4208.7 1688.43  4748.9 1688.21  4976.3 1684.77  4988.6 1674.49
  5009.1 1678.25  5024.8 1687.49  5116.8 1684.29    5237  1685.5  5257.3 1683.31
    5377 1686.46  5603.5 1687.17  5747.4 1686.79  6109.9  1688.7    6360 1695.21
    6901 1715.69  6916.9 1715.48  7044.6 1717.15  7230.3 1722.86  7513.8 1728.81
#Mann= 20 ,-1 , 0
  1476.7     .16       0  1512.1     .07       0  2396.7     .05       0
  3593.1     .07       0  3751.8     .05       0  3856.4     .07       0
  4114.6     .05       0  4208.7     .07       0  4976.3    .045       0
  5024.8     .07       0    5237     .05       0    5377     .07       0
  5603.5     .16       0  5747.4     .07       0  6109.9     .16       0
    6360     .05       0    6901     .07       0  6916.9     .05       0
  7044.6     .07       0  7230.3     .05       0
Bank Sta=4976.3,5024.8
XS Rating Curve= 0 ,0
Exp/Cntr=0.3,0.1

Type RM Length L Ch R = 1 ,86078   ,3527,3527,3527
BEGIN DESCRIPTION:
MULBERRY CREEK 20.0
END DESCRIPTION:
XS GIS Cut Line= 3
      1544480.01      6878362.99      1545197.46      6877440.56
      1549874.93      6875647.68
#Sta/Elev= 30
  1448.8 1700.85  1574.2 1700.61    1631 1700.68  1741.5 1700.12  1748.8 1700.09
    2348 1697.88  2410.7 1697.79  2472.2 1697.54    3343 1681.57  3407.7  1685.7
  4992.3 1681.75  5040.9 1673.81  5046.3 1679.81  5070.9 1686.18  5367.1 1685.22
  5409.9 1676.55  5434.6 1684.17  5503.6 1685.77  5585.1 1685.24    5915 1686.25
  6022.2 1687.15  6321.9 1698.65  6614.7 1705.86  6859.3 1714.08  7108.1 1705.45
  7243.7  1710.1  7308.4 1711.13  7415.6 1717.66  7496.5 1727.84  7626.7 1730.24
#Mann= 20 ,-1 , 0
  1448.8     .07       0  1574.2     .16       0    1631     .07       0
  1741.5     .05       0  1748.8     .07       0    2348     .05       0
  2410.7     .07       0  2472.2     .05       0  3407.7     .07       0
  4992.3    .045       0  5046.3     .07       0  5503.6     .05       0
  5585.1     .07       0    5915     .07       0  6022.2     .16       0
  6321.9     .07       0  6614.7     .05       0  7243.7     .07       0
  7308.4     .05       0  7415.6     .07       0
Bank Sta=4992.3,5046.3
XS Rating Curve= 0 ,0
Exp/Cntr=0.3,0.1

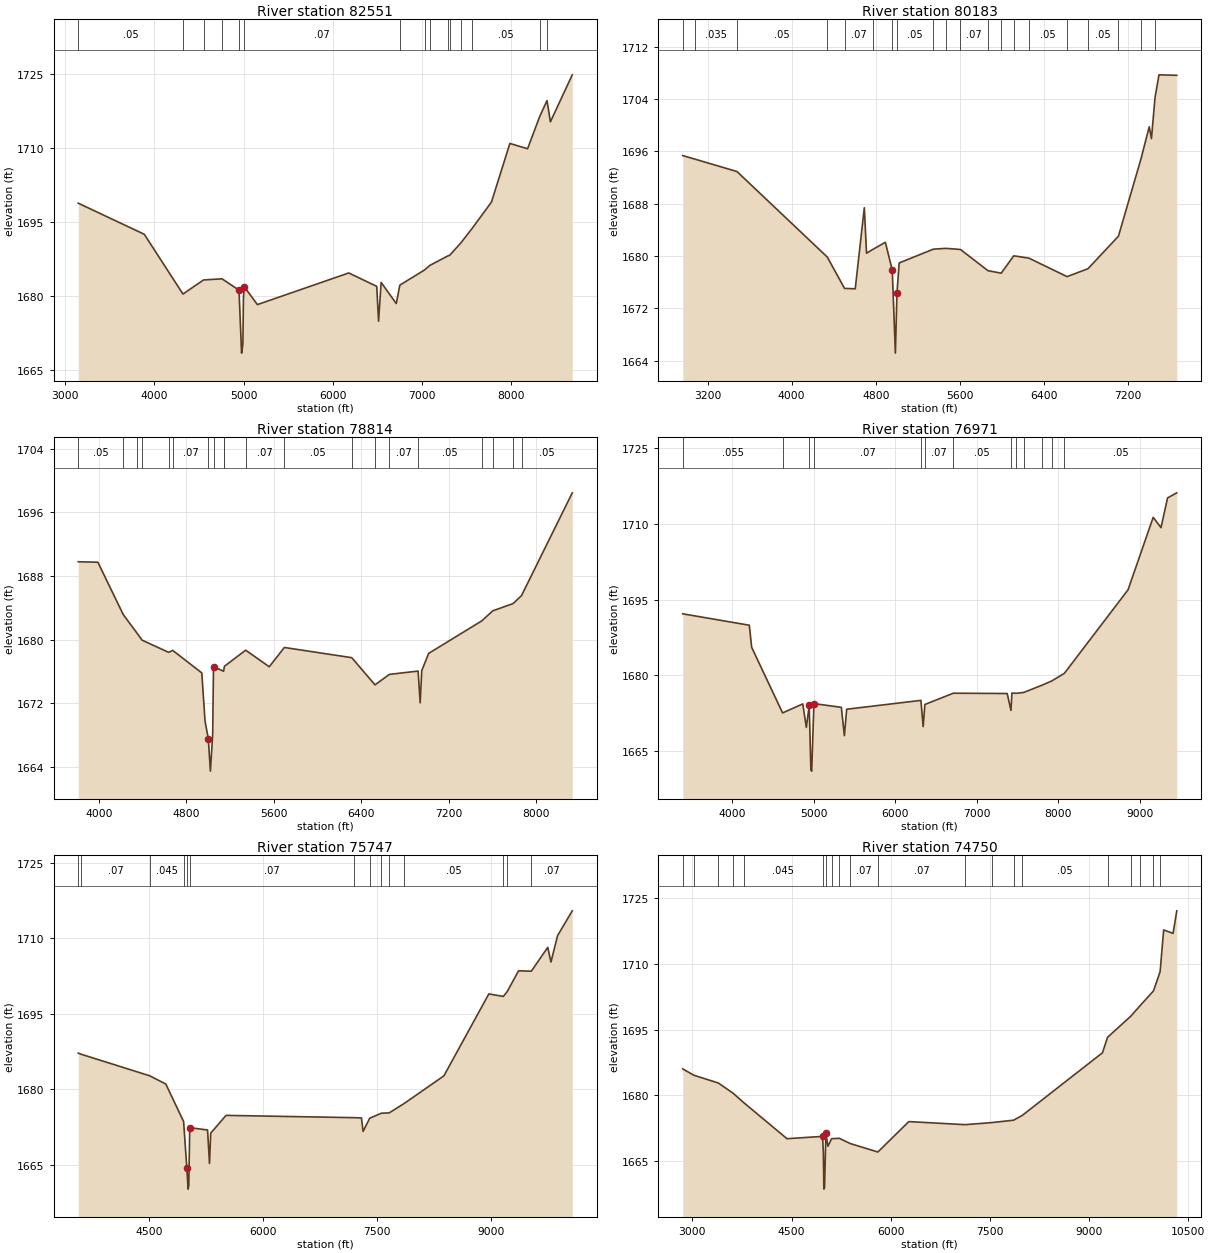
Type RM Length L Ch R = 1 ,82551   ,2368,2368,2368
BEGIN DESCRIPTION:
MULBERRY CREEK 18.0
END DESCRIPTION:
XS GIS Cut Line= 3
      1545680.02      6878962.99      1546737.88      6878571.52
      1550188.77      6875817.31
#Sta/Elev= 30
  3145.8 1698.76  3886.8 1692.45  4320.7 1680.32  4551.5 1683.18    4759 1683.41
  4949.6 1681.11  4978.5 1668.33  4992.9 1670.14  4999.4 1679.44  5007.3 1681.83
  5156.2 1678.18    6181  1684.6  6494.8 1681.88  6515.6 1674.81  6544.4 1682.68
  6714.2 1678.39  6754.3 1682.13  7031.6 1685.21  7089.6 1686.12  7291.7 1688.05
  7312.5 1688.17  7440.3 1690.73  7565.7 1693.65  7782.2 1698.99  7988.7 1710.88
  8187.3 1709.81    8325 1716.41  8405.5 1719.58  8443.4 1715.27    8689 1724.81
#Mann= 15 ,-1 , 0
  3145.8     .05       0  4320.7     .07       0  4551.5     .05       0
    4759     .07       0  4949.6    .045       0  5007.3     .07       0
  6754.3     .05       0  7031.6     .07       0  7089.6     .05       0
  7291.7     .07       0  7312.5     .05       0  7440.3     .07       0
  7565.7     .05       0    8325     .07       0  8405.5     .05       0
Bank Sta=4949.6,5007.3
XS Rating Curve= 0 ,0
Exp/Cntr=0.3,0.1

Type RM Length L Ch R = 1 ,80183   ,1369,1369,1369
BEGIN DESCRIPTION:
Mapping XS 1c101f01
END DESCRIPTION:
XS GIS Cut Line= 3
      1546280.02        6879313.      1547858.58       6879045.9
      1550405.78      6877284.32
#Sta/Elev= 30
  2964.4 1695.34  3081.9 1694.79  3480.3  1692.9  4338.5 1679.84  4503.2 1675.04
  4604.6 1674.98  4691.1 1687.37  4712.1 1680.42  4769.7 1680.98  4891.2 1682.09
  4956.7 1677.84  4986.5 1665.15  5001.4  1674.3  5022.3 1678.93  5348.2 1681.04
  5468.9 1681.16  5605.4 1680.99  5866.9 1677.75  5992.8 1677.37  6112.2 1680.02
    6256 1679.67  6619.2 1676.84  6817.7 1678.05  7107.6 1683.02  7321.4 1694.81
  7400.5 1699.74  7421.5 1697.94  7455.5 1704.21  7493.1 1707.68  7662.4 1707.61
#Mann= 20 ,-1 , 0
  2964.4     .07       0  3081.9    .035       0  3480.3     .05       0
  4338.5     .05       0  4503.2     .07       0  4769.7     .05       0
  4956.7    .045       0  5001.4     .05       0  5348.2     .07       0
  5468.9     .05       0  5605.4     .07       0  5866.9     .05       0
  5992.8     .05       0  6112.2     .07       0    6256     .05       0
  6619.2     .07       0  6817.7     .05       0  7107.6     .07       0
  7321.4     .07       0  7455.5     .05       0
Bank Sta=4956.7,5001.4
XS Rating Curve= 0 ,0
Exp/Cntr=0.3,0.1

Type RM Length L Ch R = 1 ,78814   ,1843,1843,1843
BEGIN DESCRIPTION:
Mapping XS 7b6d8823
END DESCRIPTION:
XS GIS Cut Line= 3
      1547465.29      6879901.94       1548659.7      6879922.77
      1551131.95      6877700.53
#Sta/Elev= 30
  3810.2 1689.79  3989.9 1689.73  4221.9 1683.16  4346.6 1680.85  4393.9 1679.95
  4636.8 1678.42  4674.7 1678.66  4940.1 1675.84  4970.1 1669.77  4999.9 1667.59
    5019 1663.51  5039.9 1668.13  5047.4 1676.62  5139.8 1676.05  5147.4 1676.67
  5341.7 1678.69  5557.2 1676.61  5695.4 1679.03    6312 1677.75  6524.5 1674.34
    6656 1675.65  6918.7 1676.07  6937.8 1672.09    6952 1676.12  7015.5 1678.29
  7500.4 1682.36  7601.7 1683.63  7787.4 1684.54  7864.7 1685.54    8329 1698.44
#Mann= 20 ,-1 , 0
  3810.2     .05       0  4221.9     .07       0  4346.6     .05       0
  4393.9     .07       0  4636.8     .05       0  4674.7     .07       0
  4999.9    .045       0  5047.4     .07       0  5139.8     .07       0
  5147.4     .05       0  5341.7     .07       0  5695.4     .05       0
    6312     .07       0  6524.5     .05       0    6656     .07       0
  6918.7     .05       0  7500.4     .07       0  7601.7     .05       0
  7787.4     .07       0  7864.7     .05       0
Bank Sta=4999.9,5047.4
XS Rating Curve= 0 ,0
Exp/Cntr=0.3,0.1

Type RM Length L Ch R = 1 ,76971   ,1224,1224,1224
BEGIN DESCRIPTION:
Mapping XS 6574220c
END DESCRIPTION:
XS GIS Cut Line= 3
      1548141.02      6882119.75        1549378.      6881164.89
      1551645.03      6877281.65
#Sta/Elev= 30
  3396.1 1692.19  4212.5 1689.93  4241.5 1685.55  4620.8 1672.54  4868.2 1674.33
  4911.7 1669.67  4947.1 1674.03  4967.6 1661.31  4977.5    1661  5004.8 1674.39
  5341.3 1673.65  5378.5 1668.04  5406.7 1673.27  6317.2 1675.03  6344.7 1669.83
    6366 1674.22  6715.1 1676.45  7375.2 1676.39  7421.8 1673.04  7433.1 1676.49
  7485.4 1676.43  7577.9  1676.6    7800 1678.02  7920.9 1678.87  8076.5 1680.39
  8857.4 1696.95  9165.9 1711.32  9261.9 1709.28    9342 1715.17  9455.3 1716.18
#Mann= 13 ,-1 , 0
  3396.1    .055       0  4620.8     .07       0  4947.1    .045       0
  5004.8     .07       0  6317.2     .05       0    6366     .07       0
  6715.1     .05       0  7421.8     .07       0  7485.4     .05       0
  7577.9     .07       0    7800     .05       0  7920.9     .07       0
  8076.5     .05       0
Bank Sta=4947.1,5004.8
XS Rating Curve= 0 ,0
Exp/Cntr=0.3,0.1

Type RM Length L Ch R = 1 ,75747   ,997,997,997
BEGIN DESCRIPTION:
Mapping XS e9919914
END DESCRIPTION:
XS GIS Cut Line= 3
      1549356.26      6882618.92      1550278.61      6881739.98
      1552025.58      6876813.74
#Sta/Elev= 30
  3564.6 1687.22  3605.1 1686.99    4505 1682.72  4717.3 1681.08    4951 1673.63
  4993.5 1664.44  5010.5 1660.22  5019.1 1660.93  5031.8 1672.43  5266.1 1671.96
  5291.7 1665.31  5307.6 1671.33  5509.2 1674.86  7188.6 1674.41  7291.3 1674.35
  7312.9 1671.68    7400  1674.3  7552.7 1675.29  7655.6 1675.35  7853.2 1677.22
  8376.3 1682.71  8967.3 1698.97  9158.1 1698.48  9208.6 1699.42    9358 1703.55
  9526.8 1703.49  9742.7 1708.22  9785.1 1705.31  9872.3 1710.56 10065.5 1715.47
#Mann= 14 ,-1 , 0
  3564.6     .05       0  3605.1     .07       0    4505    .045       0
    4951     .07       0  4993.5    .045       0  5031.8     .07       0
  7188.6     .05       0    7400     .07       0  7552.7     .05       0
  7655.6     .07       0  7853.2     .05       0  9158.1     .07       0
  9208.6     .05       0  9526.8     .07       0
Bank Sta=4993.5,5031.8
XS Rating Curve= 0 ,0
Exp/Cntr=0.3,0.1

Type RM Length L Ch R = 1 ,74750   ,996,996,996
BEGIN DESCRIPTION:
Mapping XS 03c410f4
END DESCRIPTION:
XS GIS Cut Line= 3
      1549475.67      6883259.07      1551081.56      6882315.06
      1552123.22      6876802.93
#Sta/Elev= 30
    2855 1686.04  3021.6  1684.6  3393.9 1682.81  3615.6 1680.49  3777.5 1678.33
  4431.8 1670.08  4969.2 1670.61  4981.6 1667.07  4989.6 1658.55  4999.8 1658.92
  5020.1 1671.31  5050.7 1668.34  5106.4 1670.08  5222.9 1670.17  5389.5 1668.96
  5806.7 1667.04  6274.1 1673.99  7124.8 1673.29    7534 1673.77  7859.1 1674.31
  7991.9 1675.42  9202.9 1689.72  9280.7 1693.27  9632.6  1698.1  9776.3 1700.56
  9974.6 1703.86 10075.2 1708.25   10129 1717.81 10271.5 1717.03 10327.5 1722.18
#Mann= 20 ,-1 , 0
    2855     .05       0  3021.6     .07       0  3393.9     .07       0
  3615.6     .05       0  3777.5    .045       0  4969.2    .035       0
  5020.1     .05       0  5106.4     .05       0  5222.9     .07       0
  5389.5     .07       0  5806.7     .07       0  7124.8     .05       0
    7534     .07       0  7859.1     .07       0  7991.9     .05       0
  9280.7     .07       0  9632.6     .05       0  9776.3     .07       0
  9974.6     .05       0 10075.2     .07       0
Bank Sta=4969.2,5020.1
XS Rating Curve= 0 ,0
Exp/Cntr=0.3,0.1

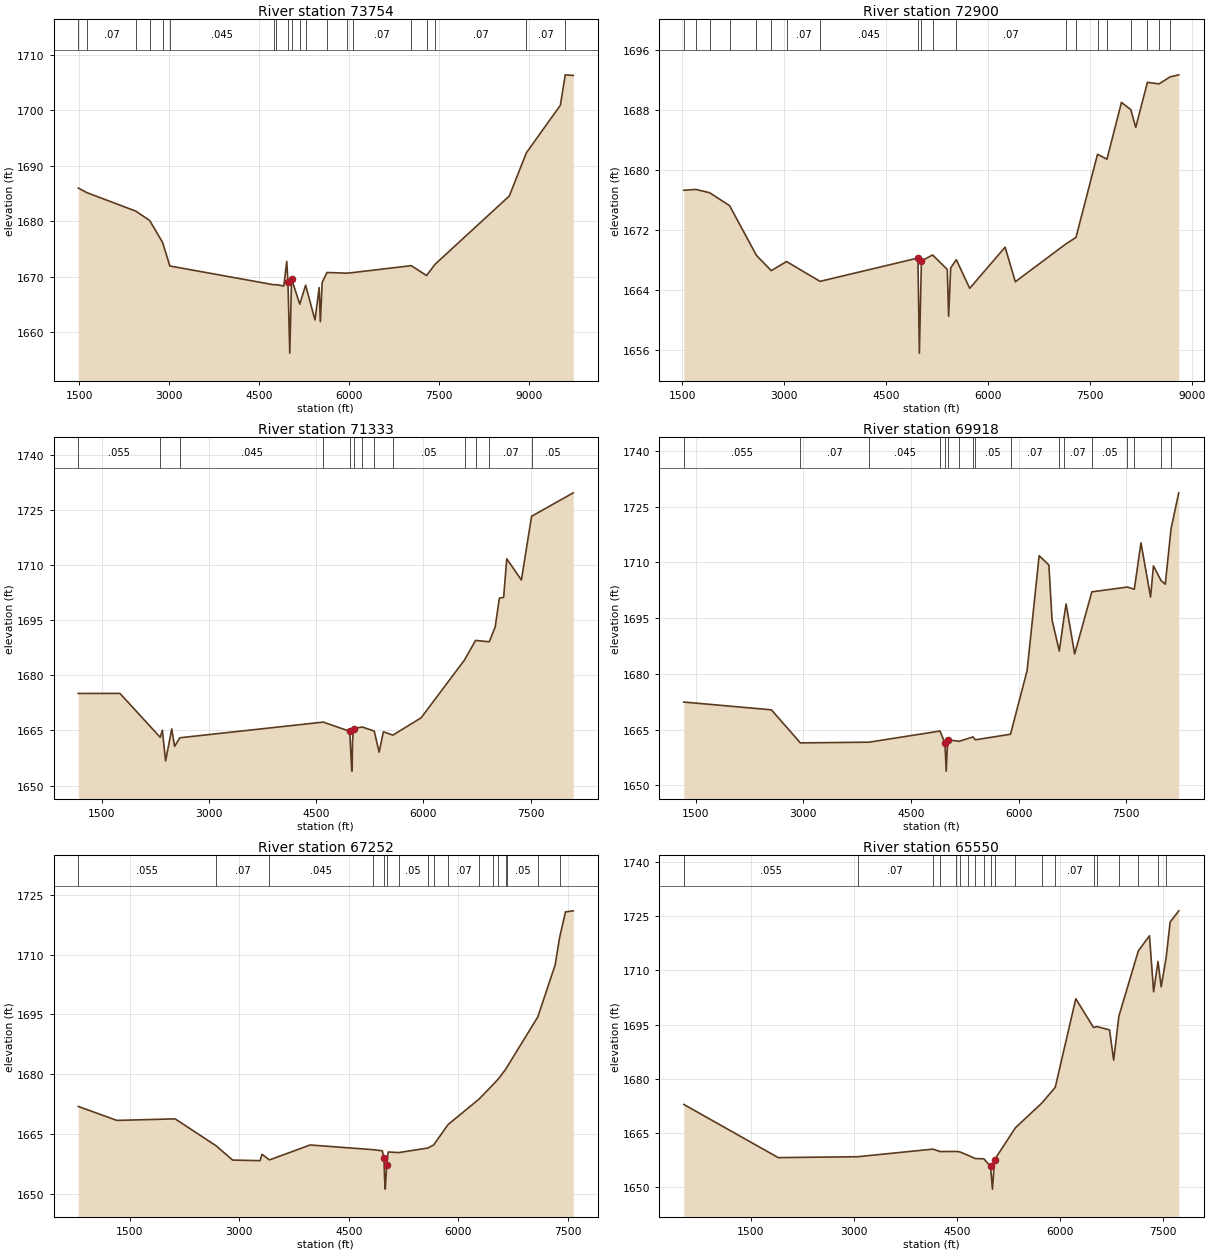
Type RM Length L Ch R = 1 ,73754   ,854,854,854
BEGIN DESCRIPTION:
Mapping XS 8a1bf8cb
END DESCRIPTION:
XS GIS Cut Line= 3
      1549515.48      6884002.69      1552047.27      6882499.53
      1552199.18      6877193.49
#Sta/Elev= 30
  1483.7 1685.98  1627.2 1685.15  2443.2 1681.82  2674.7 1680.13  2889.3 1676.19
  3010.2 1671.95  4749.7 1668.56  4784.9 1668.59  4909.8 1668.34  4959.8 1672.75
  4979.8 1668.99  5009.9 1656.27  5039.9 1669.63  5176.4 1665.08  5274.3 1668.49
    5430 1662.24  5500.1 1668.06  5520.1 1661.91  5550.1 1668.98    5630 1670.78
  5959.3 1670.66  6057.2 1670.76  7035.9 1672.01  7290.6 1670.23  7430.6 1672.24
  8671.4 1684.56  8953.6  1692.3  9521.7 1700.88  9603.1 1706.35  9736.3 1706.24
#Mann= 20 ,-1 , 0
  1483.7     .05       0  1627.2     .07       0  2443.2     .05       0
  2674.7     .07       0  2889.3     .05       0  3010.2    .045       0
  4749.7     .07       0  4784.9    .045       0  4979.8    .035       0
  5039.9    .045       0  5176.4     .16       0  5274.3     .07       0
    5630     .05       0  5959.3     .05       0  6057.2     .07       0
  7035.9     .07       0  7290.6     .05       0  7430.6     .07       0
  8953.6     .07       0  9603.1     .05       0
Bank Sta=4979.8,5039.9
XS Rating Curve= 0 ,0
Exp/Cntr=0.3,0.1

Type RM Length L Ch R = 1 ,72900   ,1567,1567,1567
BEGIN DESCRIPTION:
Mapping XS 7bf2354f
END DESCRIPTION:
XS GIS Cut Line= 3
      1552216.42      6885358.37      1552855.17       6881937.6
      1553094.77      6878135.74
#Sta/Elev= 30
  1520.1  1677.3  1698.5 1677.41  1900.5 1676.97  2193.9 1675.25  2590.3 1668.61
    2808 1666.58  3033.4 1667.79    3527 1665.15  4967.9 1668.26  4989.4 1655.58
  5019.6 1667.87    5184 1668.67  5400.4 1666.74  5420.4 1660.49  5450.5 1666.95
  5533.6 1668.04    5731 1664.22  6252.1 1669.71  6402.4  1665.1  7150.4 1670.16
  7295.7 1671.01    7613 1682.09  7751.7 1681.44  7965.5 1689.01  8102.6 1688.05
  8175.9 1685.68  8347.7 1691.69  8518.1 1691.48  8682.3 1692.42  8809.4 1692.69
#Mann= 20 ,-1 , 0
  1520.1     .07       0  1698.5     .07       0  1900.5     .05       0
  2193.9     .16       0  2590.3     .07       0    2808     .05       0
  3033.4     .07       0    3527    .045       0  4967.9    .045       0
  5019.6    .045       0    5184     .16       0  5533.6     .07       0
  7150.4     .05       0  7295.7     .07       0    7613     .05       0
  7751.7     .07       0  8102.6     .05       0  8347.7     .07       0
  8518.1     .05       0  8682.3     .07       0
Bank Sta=4967.9,5019.6
XS Rating Curve= 0 ,0
Exp/Cntr=0.3,0.1

Type RM Length L Ch R = 1 ,71333   ,1415,1415,1415
BEGIN DESCRIPTION:
Mapping XS 6e8f590f
END DESCRIPTION:
XS GIS Cut Line= 3
      1553617.73      6885734.44       1554094.8       6881937.5
       1555617.9      6879243.55
#Sta/Elev= 30
  1173.2 1675.03  1756.1 1675.04  2318.8  1663.1  2348.8 1665.03  2394.4 1656.69
  2479.9 1665.39  2520.2 1660.64  2592.8 1662.98  4599.5 1667.24  4969.3 1664.73
  4997.2 1653.91  5002.6 1653.91  5007.9 1661.92  5022.4 1665.47  5143.6 1665.91
  5312.1  1664.8  5380.3 1659.06  5439.5 1664.61  5571.6 1663.69  5967.8 1668.41
  6574.4 1684.14  6728.9 1689.45  6920.2 1689.08  7002.9 1693.09  7062.1 1700.95
  7121.3 1701.14  7164.6 1711.64  7369.6 1705.88  7512.2  1723.2  8094.7 1729.58
#Mann= 13 ,-1 , 0
  1173.2    .055       0  2318.8     .07       0  2592.8    .045       0
  4599.5     .07       0  4969.3    .045       0  5022.4     .07       0
  5143.6     .05       0  5312.1     .07       0  5571.6     .05       0
  6574.4     .07       0  6728.9     .05       0  6920.2     .07       0
  7512.2     .05       0
Bank Sta=4969.3,5022.4
XS Rating Curve= 0 ,0
Exp/Cntr=0.3,0.1

Type RM Length L Ch R = 1 ,69918   ,2666,2666,2666
BEGIN DESCRIPTION:
Mapping XS a56b7213
END DESCRIPTION:
XS GIS Cut Line= 4
      1554661.56      6886070.86      1555285.12      6882458.28
      1555084.74      6881198.89      1555919.47      6879431.86
#Sta/Elev= 30
    1334 1672.42  2554.5 1670.33    2958 1661.43  3915.2 1661.62  4903.8 1664.62
  4972.4 1661.36  4990.1 1653.83  5010.4  1662.3  5166.2 1661.84  5363.8 1663.04
  5395.4 1662.26  5885.5 1663.76  6116.8 1680.91  6284.6 1711.82    6420 1709.31
  6464.2 1694.55  6565.4 1686.14  6629.1 1694.96    6660 1698.81  6779.3 1685.37
  7018.9 1702.08    7512 1703.37  7610.7 1702.79  7702.9 1715.27  7836.9 1700.68
  7876.9 1709.07  7982.9 1705.12  8041.8 1704.14  8122.5 1719.13  8229.5 1728.73
#Mann= 17 ,-1 , 0
    1334    .055       0    2958     .07       0  3915.2    .045       0
  4903.8     .07       0  4972.4    .045       0  5010.4     .07       0
  5166.2     .05       0  5363.8     .07       0  5395.4     .05       0
  5885.5     .07       0  6565.4     .05       0  6629.1     .07       0
  7018.9     .05       0    7512     .07       0  7610.7     .05       0
  7982.9     .07       0  8122.5     .05       0
Bank Sta=4972.4,5010.4
XS Rating Curve= 0 ,0
Exp/Cntr=0.3,0.1

Type RM Length L Ch R = 1 ,67252   ,1702,1702,1702
BEGIN DESCRIPTION:
Mapping XS e15eb74a
END DESCRIPTION:
XS GIS Cut Line= 3
      1555160.69      6886125.13      1556495.33       6882186.3
      1556907.66      6879592.98
#Sta/Elev= 30
     792 1671.89  1320.9 1668.38  2119.3 1668.77  2679.3 1662.03  2907.4 1658.42
  3284.4 1658.27  3310.5 1659.88  3412.8 1658.46  3970.3 1662.21  4832.8 1661.03
  4959.2 1660.75  4982.5  1658.9  4989.6 1654.36  4999.7 1651.12    5020 1657.23
  5039.7 1660.45  5184.3  1660.3  5582.6 1661.44  5662.5  1662.2  5859.9 1667.32
  6284.4 1673.72  6477.5 1677.37  6550.9 1678.83  6649.6  1681.2  6666.1  1681.7
    7091 1694.38  7328.6 1707.43  7389.7 1714.31  7470.4 1720.75  7576.7 1721.02
#Mann= 17 ,-1 , 0
     792    .055       0  2679.3     .07       0  3412.8    .045       0
  4832.8     .07       0  4982.5    .045       0    5020     .07       0
  5184.3     .05       0  5582.6     .07       0  5662.5     .05       0
  5859.9     .07       0  6284.4     .05       0  6477.5     .07       0
  6550.9     .05       0  6649.6     .07       0  6666.1     .05       0
    7091     .07       0  7389.7     .05       0
Bank Sta=4982.5,5020
XS Rating Curve= 0 ,0
Exp/Cntr=0.3,0.1

Type RM Length L Ch R = 1 ,65550   ,1549,1549,1549
BEGIN DESCRIPTION:
Mapping XS 1381514a
END DESCRIPTION:
XS GIS Cut Line= 3
      1555866.01      6886309.53      1557591.25      6882218.86
      1557417.65      6879462.92
#Sta/Elev= 30
   529.6 1672.96    1904 1658.25  3057.4  1658.5  4153.9  1660.6  4258.9 1659.93
  4496.4 1659.96  4546.1 1659.83  4663.6  1658.9  4770.1 1657.99  4895.7 1657.93
  4992.1 1655.82  5020.2 1649.54  5050.2 1657.66  5353.8  1666.5  5737.7 1673.32
  5933.7 1677.68  6232.6 1702.18  6490.6 1694.23  6539.3 1694.49  6723.5 1693.56
  6783.6 1685.21  6859.7 1697.37  7141.9 1715.39  7304.7 1719.59  7364.8  1704.1
  7428.9  1712.5    7475 1705.46  7547.6 1713.61  7605.3 1723.38  7730.6 1726.49
#Mann= 20 ,-1 , 0
   529.6    .055       0  3057.4     .07       0  4153.9     .05       0
  4258.9     .07       0  4496.4     .05       0  4546.1     .07       0
  4663.6     .05       0  4770.1     .07       0  4895.7     .05       0
  4992.1    .045       0  5050.2     .05       0  5353.8     .05       0
  5737.7     .05       0  5933.7     .07       0  6490.6     .05       0
  6539.3     .07       0  6859.7     .07       0  7141.9     .05       0
  7428.9     .07       0  7547.6     .05       0
Bank Sta=4992.1,5050.2
XS Rating Curve= 0 ,0
Exp/Cntr=0.3,0.1

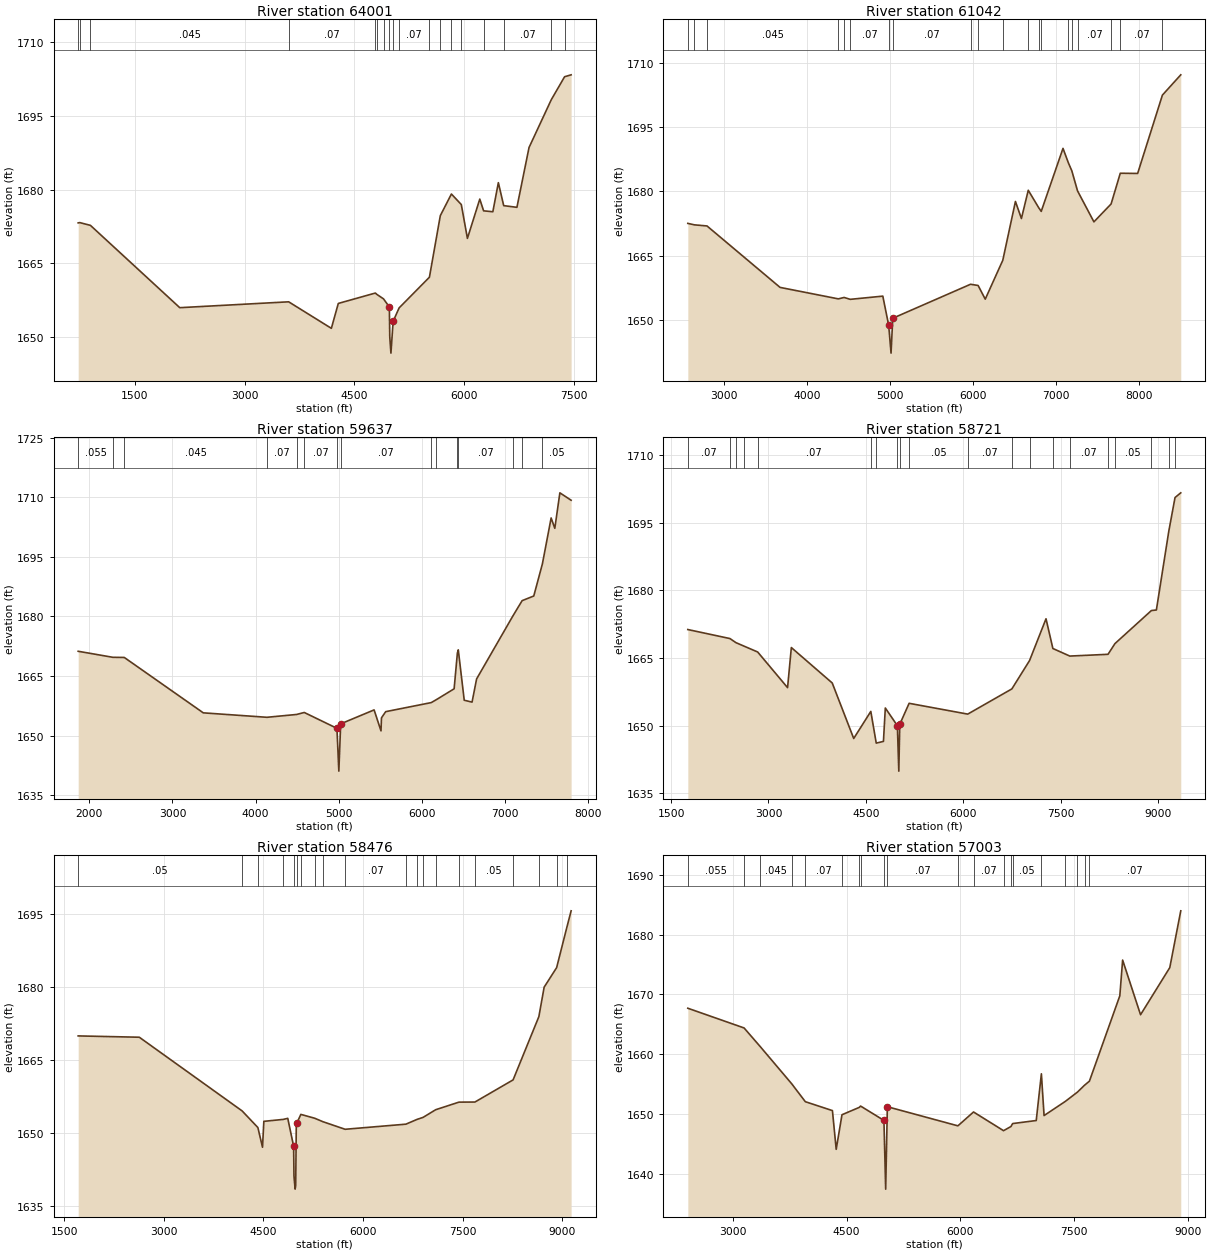
Type RM Length L Ch R = 1 ,64001   ,2959,2959,2959
BEGIN DESCRIPTION:
Mapping XS 6950f712
END DESCRIPTION:
XS GIS Cut Line= 3
       1556256.6      6886624.26      1558383.35      6882902.45
      1559153.18      6880571.27
#Sta/Elev= 30
   723.9 1673.23   745.5 1673.29   891.4 1672.73  2113.2 1656.03  3602.5 1657.22
  4186.4 1651.84  4281.2 1656.89  4788.5    1659  4807.4 1658.74  4899.5 1657.82
  4979.4 1656.18  4985.2 1650.09    5001 1646.81  5031.3 1653.25  5112.8 1655.98
  5527.5 1662.21  5676.4  1674.7  5828.1 1679.09  5963.6 1676.95  6047.1 1670.09
  6216.3 1678.06  6268.5 1675.68  6394.8 1675.49  6470.3 1681.39  6543.4 1676.73
  6724.2 1676.39  6889.7 1688.52    7194 1698.22    7376 1702.88  7465.5 1703.27
#Mann= 18 ,-1 , 0
   723.9    .055       0   745.5    .035       0   891.4    .045       0
  3602.5     .07       0  4788.5     .05       0  4807.4     .07       0
  4899.5     .16       0  4979.4    .045       0  5031.3     .07       0
  5112.8     .07       0  5527.5     .05       0  5676.4     .07       0
  5828.1     .05       0  5963.6     .07       0  6268.5     .05       0
  6543.4     .07       0    7194     .05       0    7376     .07       0
Bank Sta=4979.4,5031.3
XS Rating Curve= 0 ,0
Exp/Cntr=0.3,0.1

Type RM Length L Ch R = 1 ,61042   ,1405,1405,1405
BEGIN DESCRIPTION:
Mapping XS de7ccb3b
END DESCRIPTION:
XS GIS Cut Line= 4
      1556386.85      6886711.01      1558079.53      6884920.68
      1559294.81      6883314.78      1560020.92       6882046.8
#Sta/Elev= 30
  2563.6 1672.53  2643.2 1672.19  2794.8 1671.93    3675 1657.57  4376.8 1654.89
  4446.4 1655.22  4520.2 1654.78  4912.9 1655.53  4983.7  1648.7    5012 1642.21
  5032.6 1650.36  5969.4  1658.3    6061 1658.02  6146.9 1654.82  6358.3 1663.91
  6510.6 1677.65  6582.7 1673.67  6665.2 1680.27  6792.2 1676.16  6821.4 1675.34
  7083.7 1690.06  7147.9 1686.71  7189.9 1684.82    7259 1680.12  7456.2 1672.89
  7663.2 1677.07  7773.8 1684.25  7982.9  1684.2  8281.3 1702.51  8502.5 1707.25
#Mann= 20 ,-1 , 0
  2563.6    .055       0  2643.2     .05       0  2794.8    .045       0
  4376.8     .07       0  4446.4    .045       0  4520.2     .07       0
  4983.7    .045       0  5032.6     .07       0  5969.4     .07       0
    6061     .05       0  6358.3     .07       0  6665.2     .05       0
  6792.2     .07       0  6821.4     .05       0  7147.9     .07       0
  7189.9     .05       0    7259     .07       0  7663.2     .05       0
  7773.8     .07       0  8281.3     .05       0
Bank Sta=4983.7,5032.6
XS Rating Curve= 0 ,0
Exp/Cntr=0.3,0.1

Type RM Length L Ch R = 1 ,59637   ,916,916,916
BEGIN DESCRIPTION:
Mapping XS da0d831d
END DESCRIPTION:
XS GIS Cut Line= 3
      1556944.54      6887174.16      1559147.24      6885058.26
      1560470.53      6882509.31
#Sta/Elev= 30
  1866.6 1671.24  2283.4 1669.72  2420.9 1669.68  3370.6 1655.73  4136.4 1654.61
  4492.6 1655.32  4584.6 1655.82  4977.6 1651.83  5000.1 1641.05  5022.6 1652.96
  5424.3 1656.47  5507.1 1651.19  5512.8 1654.47  5563.5 1656.03  6110.9 1658.31
  6172.5 1659.05  6386.3 1661.79  6425.4  1670.8  6436.3  1671.6  6507.8  1658.9
  6601.9 1658.44  6656.4 1664.27  7094.5  1680.2  7203.8 1683.99  7343.7 1685.16
  7447.2 1693.23  7552.6 1704.82  7596.8 1702.21  7657.5 1711.15  7792.9 1709.28
#Mann= 15 ,-1 , 0
  1866.6    .055       0  2283.4     .05       0  2420.9    .045       0
  4136.4     .07       0  4492.6    .035       0  4584.6     .07       0
  4977.6    .045       0  5022.6     .07       0  6110.9     .05       0
  6172.5     .07       0  6425.4     .05       0  6436.3     .07       0
  7094.5     .05       0  7203.8     .07       0  7447.2     .05       0
Bank Sta=4977.6,5022.6
XS Rating Curve= 0 ,0
Exp/Cntr=0.3,0.1

Type RM Length L Ch R = 1 ,58721   ,245,245,245
BEGIN DESCRIPTION:
Mapping XS 746d8829
END DESCRIPTION:
XS GIS Cut Line= 5
      1557204.95      6887477.98       1558496.2      6886848.63
      1558973.63      6886512.26      1559678.92      6885546.55
      1562207.15      6881976.65
#Sta/Elev= 30
  1758.8 1671.32  2407.3 1669.32  2499.8 1668.41  2618.9 1667.67  2834.8 1666.33
  3294.8 1658.42  3352.8 1667.32  3982.7 1659.45  4313.3 1647.13  4576.7 1653.14
  4660.2  1646.1  4771.2 1646.48    4800  1653.9  4985.6 1649.97  5007.8 1639.88
  5022.4 1650.27  5166.5 1654.94  6068.9 1652.54  6748.9 1658.14    7021 1664.43
  7274.6 1673.71  7380.4 1667.11  7640.8 1665.43  8229.4 1665.82  8336.2  1668.2
  8897.5 1675.54    8974 1675.66  9165.5 1693.17  9261.2 1700.63  9349.6 1701.68
#Mann= 20 ,-1 , 0
  1758.8     .07       0  2407.3    .045       0  2499.8     .07       0
  2618.9     .05       0  2834.8     .07       0  4576.7    .035       0
  4660.2     .07       0  4985.6    .045       0  5022.4     .07       0
  5166.5     .05       0  6068.9     .07       0  6748.9     .05       0
    7021     .07       0  7380.4     .05       0  7640.8     .07       0
  8229.4     .07       0  8336.2     .05       0  8897.5     .07       0
  9165.5     .05       0  9261.2     .07       0
#XS Ineff= 1 ,-1
  4576.7    4800 1653.14
Permanent Ineff=
       T
Bank Sta=4985.6,5022.4
XS Rating Curve= 0 ,0
Exp/Cntr=0.3,0.1

Type RM Length L Ch R = 1 ,58476   ,1473,1473,1473
BEGIN DESCRIPTION:
Mapping XS 52650575
END DESCRIPTION:
XS GIS Cut Line= 6
       1557465.4      6887629.87      1559378.04       6886729.1
      1559668.84      6886455.66       1559729.6      6886065.04
      1559852.54      6885709.31      1562390.82      6882444.25
#Sta/Elev= 30
  1710.3  1669.9  2630.5 1669.63    4178 1654.49  4415.6 1651.07  4485.2 1647.02
  4505.5 1652.34    4797 1652.74  4865.6 1652.96  4953.9 1647.22  4959.1 1641.08
  4976.4 1638.41    4985 1639.13  4994.2 1651.91  5000.2 1651.91  5062.5 1653.77
  5270.9 1652.98  5392.4 1652.28  5729.1 1650.71    6644 1651.76    6814 1652.75
  6903.5 1653.16  7092.5 1654.73  7443.2 1656.29  7683.5 1656.31    8258 1660.86
  8646.3 1673.87  8725.6 1679.92  8913.5 1683.93  9063.9 1692.03  9131.8 1695.61
#Mann= 20 ,-1 , 0
  1710.3     .05       0    4178     .07       0  4415.6     .05       0
    4797     .07       0  4953.9    .045       0  5000.2     .07       0
  5062.5     .07       0  5270.9     .07       0  5392.4     .05       0
  5729.1     .07       0    6644     .05       0    6814     .07       0
  6903.5     .05       0  7092.5     .05       0  7443.2     .07       0
  7683.5     .05       0    8258     .07       0  8646.3     .05       0
  8913.5     .07       0  9063.9     .05       0
Bank Sta=4953.9,5000.2
XS Rating Curve= 0 ,0
Exp/Cntr=0.3,0.1

Type RM Length L Ch R = 1 ,57003   ,2111,2111,2111
BEGIN DESCRIPTION:
Mapping XS 5e205f38
END DESCRIPTION:
XS GIS Cut Line= 3
      1558771.83      6888091.38      1560790.04      6886507.19
      1562417.65      6882926.45
#Sta/Elev= 30
  2406.2  1667.7  3147.9  1664.4  3357.5 1661.33  3775.1 1655.07  3955.5 1652.06
  4312.7 1650.57  4362.4 1644.09  4438.7 1649.88  4666.9 1651.11    4684 1651.33
  4991.7 1648.93  5014.8 1637.43  5036.9 1651.22    5967 1648.02  6172.9 1650.34
  6568.6 1647.21  6666.9 1647.91  6688.4  1648.4  6999.7 1648.91  7067.6 1656.73
    7103 1649.74  7382.1  1652.1  7543.5 1653.67  7636.2 1654.81    7701  1655.5
  8101.6 1669.78  8138.8 1675.76    8375 1666.61  8760.5  1674.5  8905.2    1684
#Mann= 20 ,-1 , 0
  2406.2    .055       0  3147.9     .05       0  3357.5    .045       0
  3775.1    .045       0  3955.5     .07       0  4438.7     .07       0
  4666.9     .05       0    4684     .07       0  4991.7    .045       0
  5036.9     .07       0    5967     .05       0  6172.9     .07       0
  6568.6     .05       0  6666.9     .07       0  6688.4     .05       0
  7067.6     .07       0  7382.1     .05       0  7543.5     .07       0
  7636.2     .05       0    7701     .07       0
Bank Sta=4991.7,5036.9
XS Rating Curve= 0 ,0
Exp/Cntr=0.3,0.1