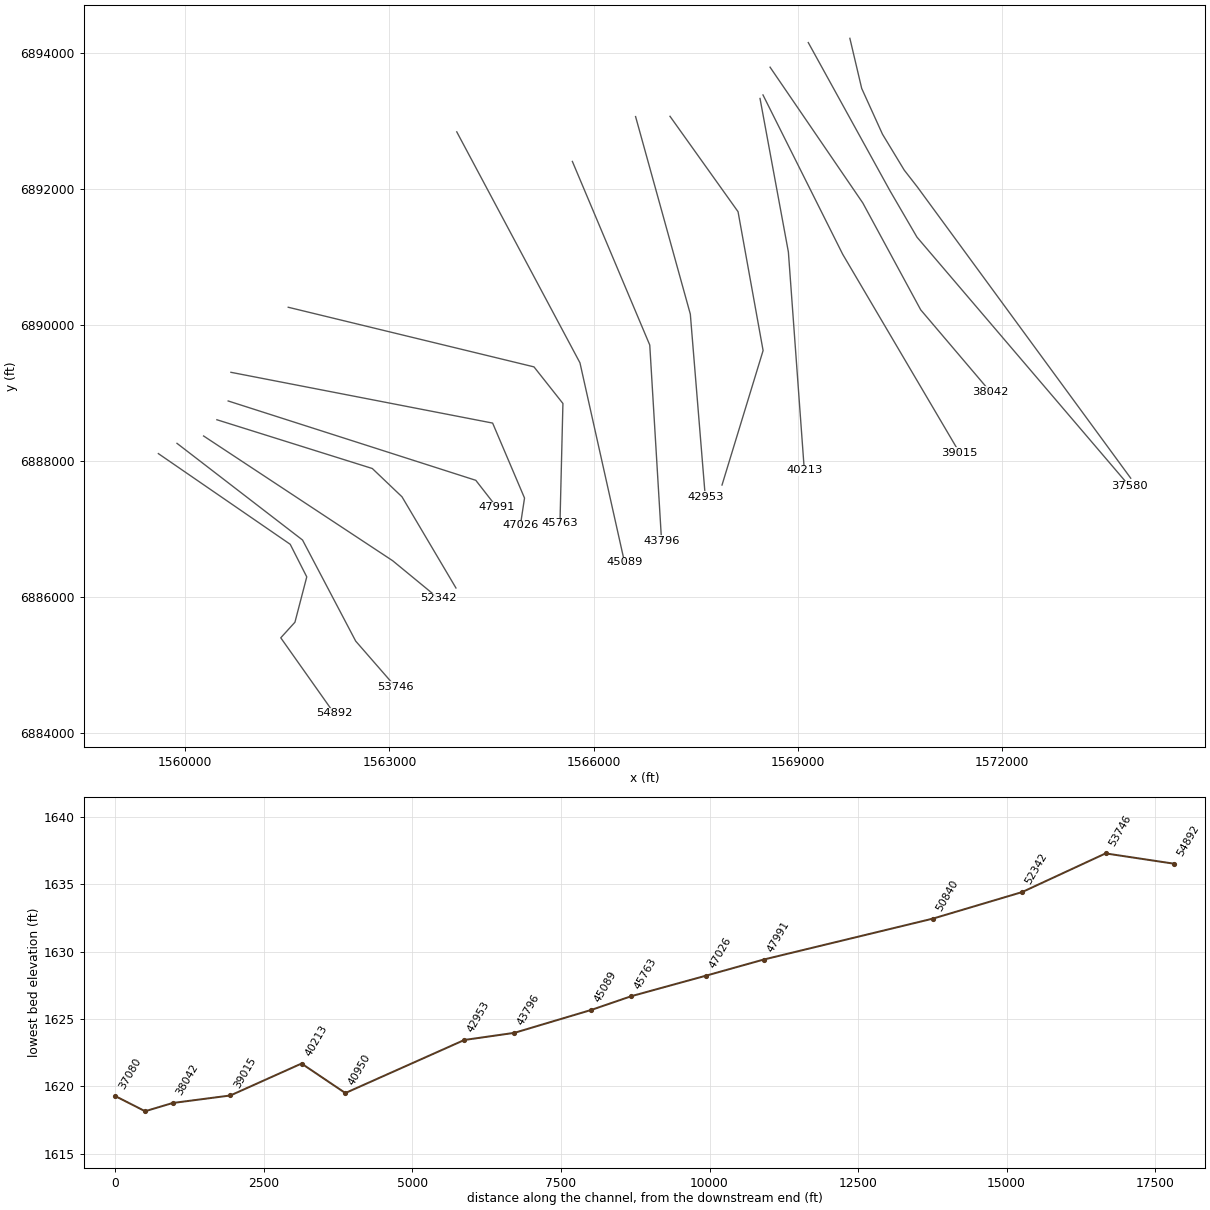
HEC-RAS study MULBERRY CREEK.prj: MULBERRY CREEK Base Level Engineering

--- MULBERRY CREEK.g01 (geometry) --- (continued)

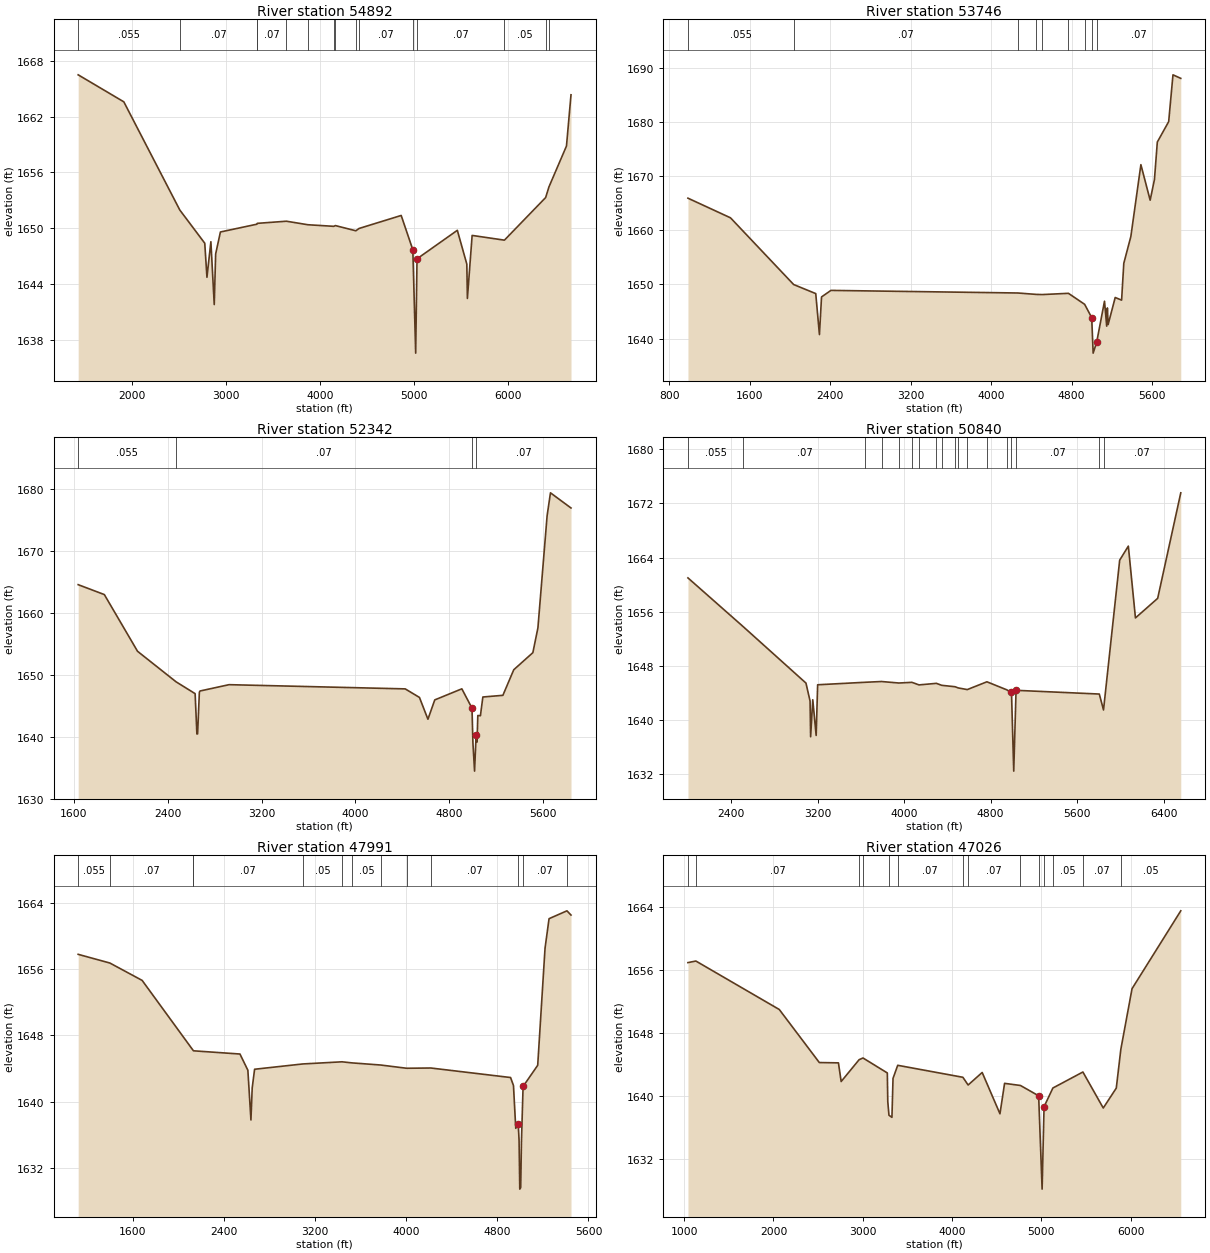
Type RM Length L Ch R = 1 ,54892   ,1146,1146,1146
BEGIN DESCRIPTION:
Mapping XS 1ac447a9
END DESCRIPTION:
XS GIS Cut Line= 6
      1559604.57      6888103.25       1561542.1       6886769.9
      1561785.15      6886290.73      1561611.54      6885624.07
      1561403.21       6885394.9      1562187.95      6884283.76
#Sta/Elev= 30
  1427.7 1666.52  1913.8 1663.61  2509.7 1651.96  2775.7 1648.38    2799 1644.71
  2840.9 1648.54  2876.7 1641.77  2891.6 1647.22  2942.4 1649.59  3331.2 1650.43
    3335 1650.52  3645.1 1650.75  3874.5 1650.37  4149.8  1650.2  4166.3 1650.28
  4384.7 1649.72  4419.1 1649.97  4867.5 1651.37  4991.5 1647.67  5021.9 1636.54
  5036.1  1646.7  5465.4 1649.77  5566.4 1646.13  5572.5 1642.43    5623 1649.22
  5966.9 1648.71  6405.9  1653.3  6441.1 1654.45  6627.7 1658.85  6675.9 1664.37
#Mann= 15 ,-1 , 0
  1427.7    .055       0  2509.7     .07       0  3331.2     .05       0
    3335     .07       0  3645.1     .05       0  3874.5     .07       0
  4149.8     .05       0  4166.3     .07       0  4384.7     .05       0
  4419.1     .07       0  4991.5    .045       0  5036.1     .07       0
  5966.9     .05       0  6405.9     .07       0  6441.1     .05       0
Bank Sta=4991.5,5036.1
XS Rating Curve= 0 ,0
Exp/Cntr=0.3,0.1

Type RM Length L Ch R = 1 ,53746   ,1404,1404,1404
BEGIN DESCRIPTION:
Mapping XS 6af474d2
END DESCRIPTION:
XS GIS Cut Line= 4
      1559878.57      6888254.16       1561723.2      6886832.72
      1562504.45      6885346.17      1563090.16      6884673.68
#Sta/Elev= 30
   985.2 1665.93  1408.3  1662.3  2036.3 1649.97  2255.8  1648.3  2292.5 1640.73
  2313.4 1647.68  2406.7 1648.89  4264.6 1648.41  4448.2 1648.15  4509.5 1648.12
  4768.2 1648.35  4929.2 1646.32  4999.6 1643.86  5013.9  1637.3    5049 1639.32
  5126.8 1646.89  5148.7 1642.28  5155.3 1645.65  5162.9 1642.58  5233.2 1647.58
  5296.8 1647.09  5318.6 1653.89  5388.9 1658.86  5488.6 1672.12  5580.7 1665.56
  5623.4 1669.38  5651.9  1676.3  5764.9 1680.07  5807.6 1688.72  5885.1 1688.07
#Mann= 9 ,-1 , 0
   985.2    .055       0  2036.3     .07       0  4264.6     .05       0
  4448.2     .07       0  4509.5     .05       0  4768.2     .07       0
  4929.2     .05       0  4999.6    .045       0    5049     .07       0
Bank Sta=4999.6,5049
XS Rating Curve= 0 ,0
Exp/Cntr=0.3,0.1

Type RM Length L Ch R = 1 ,52342   ,1502,1502,1502
BEGIN DESCRIPTION:
Mapping XS 6f721f29
END DESCRIPTION:
XS GIS Cut Line= 3
      1560269.24      6888362.64      1563046.98       6886528.9
       1563719.7      6885975.53
#Sta/Elev= 30
  1637.1 1664.54    1860 1662.94    2143 1653.78  2471.4 1648.85  2633.7 1646.94
  2648.7 1640.43  2654.7 1640.45  2669.8 1647.18  2675.8 1647.37  2922.6 1648.39
  4423.9 1647.71  4545.2 1646.33  4617.4 1642.81  4675.6 1645.93  4906.4 1647.72
  4992.9  1644.6  5000.8    1639  5014.8 1634.43  5028.1 1640.26    5036 1639.12
  5042.5 1643.41  5064.7 1643.38  5085.5  1646.4  5256.2 1646.67  5348.8  1650.8
  5511.6 1653.56  5554.7 1657.57  5632.9 1675.65  5661.6 1679.37  5836.6 1676.92
#Mann= 4 ,-1 , 0
  1637.1    .055       0  2471.4     .07       0  4992.9    .045       0
  5028.1     .07       0
Bank Sta=4992.9,5028.1
XS Rating Curve= 0 ,0
Exp/Cntr=0.3,0.1

Type RM Length L Ch R = 1 ,50840   ,2849,2849,2849
BEGIN DESCRIPTION:
Mapping XS 9c18ea20
END DESCRIPTION:
XS GIS Cut Line= 4
      1560464.48      6888601.39      1562748.37      6887884.36
      1563185.07      6887467.83      1563977.51      6886127.46
#Sta/Elev= 30
  2002.7 1660.99  2514.2 1653.78  3093.3 1645.46  3131.2 1642.81  3136.4 1637.53
  3156.2    1643  3187.6 1637.73  3201.3 1645.21  3642.6 1645.58  3791.4 1645.69
  3951.7 1645.47  4072.3 1645.57    4138 1645.19  4298.8 1645.42  4347.4 1645.13
  4471.2 1644.92  4501.1 1644.74  4584.3  1644.5  4765.5 1645.65  4948.1 1644.47
  4992.7 1644.07  5013.5 1632.46  5034.9 1644.39  5804.2 1643.84  5843.1 1641.49
  5992.6 1663.61  6072.6 1665.68  6138.3 1655.08  6343.7 1657.97  6557.1 1673.55
#Mann= 18 ,-1 , 0
  2002.7    .055       0  2514.2     .07       0  3642.6     .05       0
  3791.4     .07       0  3951.7     .05       0  4072.3     .07       0
    4138     .05       0  4298.8     .07       0  4347.4     .05       0
  4471.2     .07       0  4501.1    .035       0  4584.3     .07       0
  4765.5     .05       0  4948.1     .07       0  4992.7    .045       0
  5034.9     .07       0  5804.2     .05       0  5843.1     .07       0
Bank Sta=4992.7,5034.9
XS Rating Curve= 0 ,0
Exp/Cntr=0.3,0.1

Type RM Length L Ch R = 1 ,47991   ,965,965,965
BEGIN DESCRIPTION:
Mapping XS 347619e1
END DESCRIPTION:
XS GIS Cut Line= 3
      1560630.27      6888877.43       1564269.2      6887710.75
      1564579.38      6887312.21
#Sta/Elev= 30
  1120.1  1657.8  1398.4 1656.75  1681.6 1654.65  2129.3 1646.19  2131.4 1646.14
  2540.3 1645.75  2609.8 1643.79  2636.7 1637.78  2647.8 1641.65  2668.8 1643.91
  3091.7 1644.55  3436.7 1644.81  3523.2 1644.68    3777 1644.42    4003 1644.03
  4215.8 1644.06  4916.1 1642.91  4941.5 1641.94  4961.5 1636.77    4983 1637.29
  4990.5 1635.37  4996.8 1629.42    5005 1629.61  5011.3 1635.08  5025.8 1641.83
  5154.2 1644.39  5218.5 1658.53  5253.8 1662.11  5410.8 1663.06  5446.5 1662.55
#Mann= 13 ,-1 , 0
  1120.1    .055       0  1398.4     .07       0  2129.3     .05       0
  2131.4     .07       0  3091.7     .05       0  3436.7     .07       0
  3523.2     .05       0    3777     .07       0    4003     .05       0
  4215.8     .07       0    4983    .045       0  5025.8     .07       0
  5410.8     .05       0
Bank Sta=4983,5025.8
XS Rating Curve= 0 ,0
Exp/Cntr=0.3,0.1

Type RM Length L Ch R = 1 ,47026   ,1263,1263,1263
BEGIN DESCRIPTION:
Mapping XS 1c14e136
END DESCRIPTION:
XS GIS Cut Line= 4
      1560670.98      6889298.87      1564516.51      6888552.33
      1564985.26       6887449.9      1564924.67      6887051.75
#Sta/Elev= 30
  1042.6 1656.97  1131.4 1657.17  2065.3 1651.02  2513.6 1644.29  2727.5 1644.25
  2758.1 1641.88  2958.9 1644.65  3002.5 1644.87  3274.9 1642.97    3280 1639.36
  3293.3  1637.6  3326.6 1637.34  3338.7 1642.28  3391.4 1643.94    4121 1642.42
  4179.7 1641.44    4337 1643.03  4536.1 1637.79  4587.8 1641.65  4765.8 1641.38
  4969.4 1640.07  5008.1 1628.23  5029.8 1638.68  5128.8 1641.06  5464.7 1643.09
  5692.7 1638.52  5838.6 1641.05  5889.6 1645.97  6014.9 1653.66  6560.6 1663.54
#Mann= 14 ,-1 , 0
  1042.6    .055       0  1131.4     .07       0  2958.9     .05       0
  3002.5     .07       0  3293.3     .05       0  3391.4     .07       0
    4121     .05       0  4179.7     .07       0  4765.8     .05       0
  4969.4    .045       0  5029.8    .035       0  5128.8     .05       0
  5464.7     .07       0  5889.6     .05       0
Bank Sta=4969.4,5029.8
XS Rating Curve= 0 ,0
Exp/Cntr=0.3,0.1

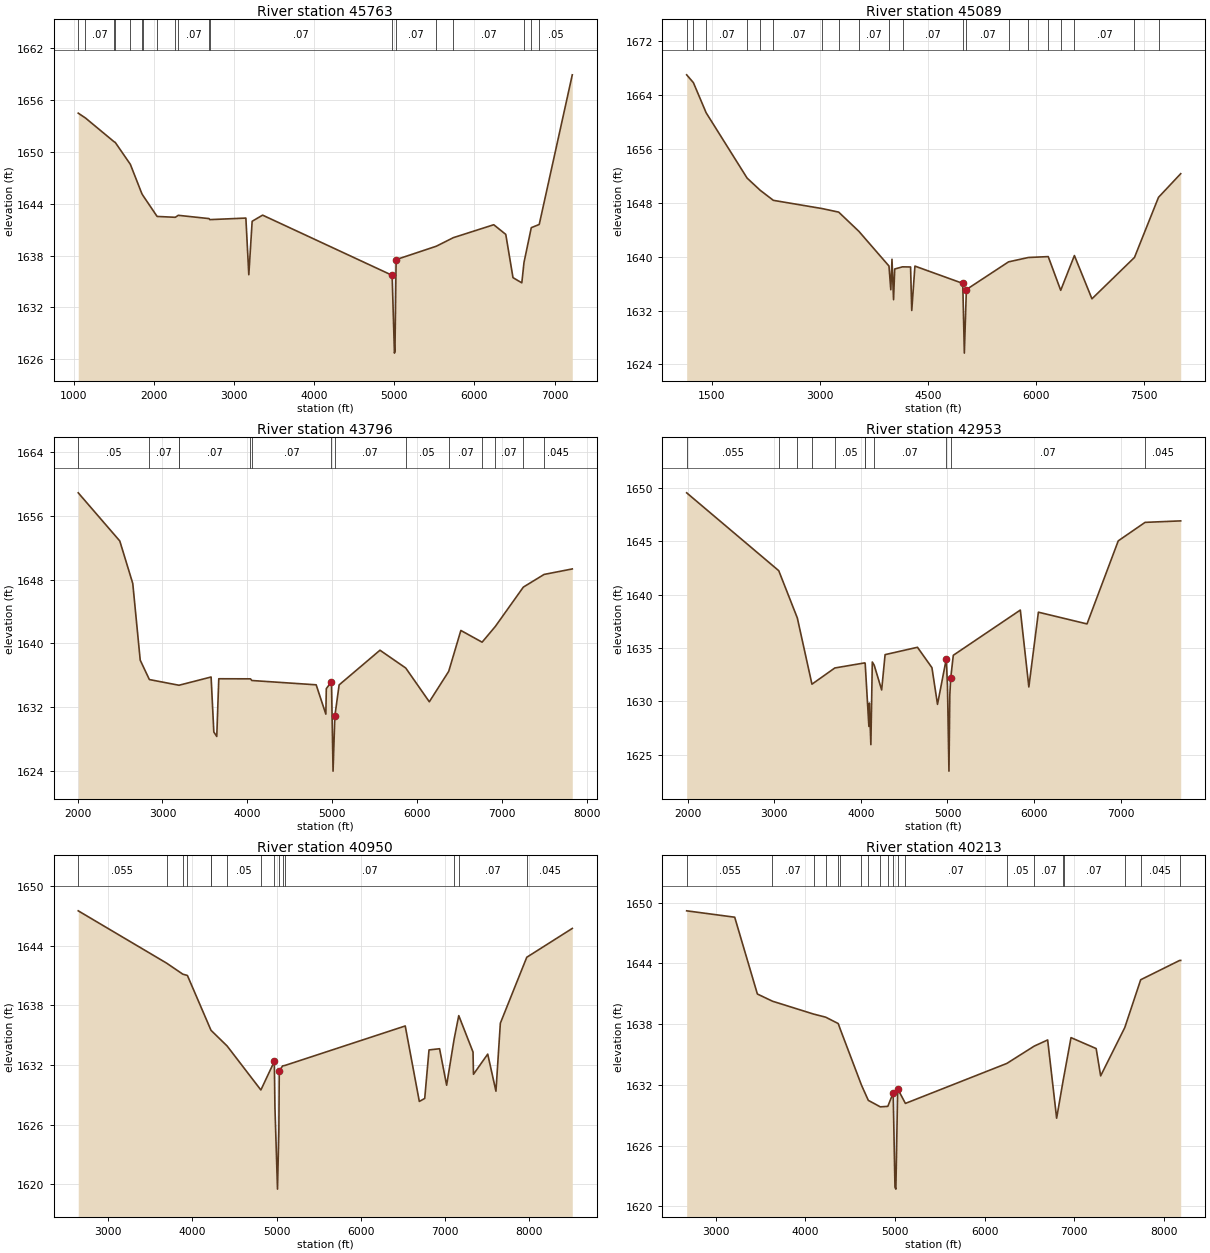
Type RM Length L Ch R = 1 ,45763   ,674,674,674
BEGIN DESCRIPTION:
Mapping XS adfcd3ce
END DESCRIPTION:
XS GIS Cut Line= 4
      1561513.01      6890255.46      1565124.15      6889378.72
       1565549.5      6888840.53      1565506.09      6887078.39
#Sta/Elev= 30
  1055.8 1654.49  1144.6 1653.94  1503.1 1651.18  1517.8  1651.1  1705.7 1648.57
  1849.6 1645.17  1863.8 1644.95  2039.9 1642.53  2266.8 1642.43  2304.2 1642.66
  2687.9 1642.28  2698.1 1642.16  3147.5 1642.34  3184.2 1635.78  3225.9 1641.97
  3356.4 1642.68  4972.6 1635.71  5001.4  1626.7  5007.8 1626.94  5022.3 1637.53
  5523.7 1639.08  5735.8 1640.07  6240.6 1641.57  6390.6 1640.45  6480.7 1635.44
  6590.7 1634.84    6618  1637.2  6708.9 1641.23    6808  1641.6  7220.5 1658.93
#Mann= 19 ,-1 , 0
  1055.8     .05       0  1144.6     .07       0  1503.1     .05       0
  1517.8     .07       0  1705.7     .05       0  1849.6     .07       0
  1863.8     .05       0  2039.9     .07       0  2266.8     .05       0
  2304.2     .07       0  2687.9    .035       0  2698.1     .07       0
  4972.6    .045       0  5022.3     .07       0  5523.7     .05       0
  5735.8     .07       0    6618     .05       0  6708.9     .07       0
    6808     .05       0
Bank Sta=4972.6,5022.3
XS Rating Curve= 0 ,0
Exp/Cntr=0.3,0.1

Type RM Length L Ch R = 1 ,45089   ,1293,1293,1293
BEGIN DESCRIPTION:
Mapping XS fee9e244
END DESCRIPTION:
XS GIS Cut Line= 3
      1563989.48      6892834.49      1565799.84      6889438.38
      1566454.76      6886506.33
#Sta/Elev= 30
  1151.5 1667.03  1244.8 1665.87  1421.8 1661.39  1989.6 1651.69  2171.8 1649.87
  2354.1 1648.38  3029.6 1647.16  3260.4 1646.63  3540.8 1643.77  3957.8 1638.62
  3983.1  1635.1  3999.4 1639.63  4021.3 1633.62  4037.2 1638.18  4145.3  1638.5
  4257.2 1638.48  4273.5 1632.02  4317.5 1638.61  4981.3 1636.04  5003.1 1625.68
  5031.1 1635.12    5616 1639.24  5891.6 1639.89  6166.7 1640.02  6339.8 1635.01
  6529.7 1640.18    6773 1633.75  7363.2  1639.9  7696.3 1648.83  8004.3 1652.34
#Mann= 20 ,-1 , 0
  1151.5     .07       0  1244.8     .05       0  1421.8     .07       0
  1989.6     .07       0  2171.8     .05       0  2354.1     .07       0
  3029.6     .05       0  3260.4     .07       0  3540.8     .07       0
  3957.8     .05       0  4145.3     .07       0  4981.3    .045       0
  5031.1     .07       0    5616     .07       0  5891.6     .07       0
  6166.7     .05       0  6339.8     .07       0  6529.7     .07       0
  7363.2     .07       0  7696.3    .045       0
Bank Sta=4981.3,5031.1
XS Rating Curve= 0 ,0
Exp/Cntr=0.3,0.1

Type RM Length L Ch R = 1 ,43796   ,843,843,843
BEGIN DESCRIPTION:
Mapping XS e77172e0
END DESCRIPTION:
XS GIS Cut Line= 3
      1565688.39      6892399.54      1566825.54       6889699.9
      1566999.15      6886817.99
#Sta/Elev= 30
  2008.6  1658.9  2497.7 1652.86  2650.5 1647.53  2738.4  1637.9  2846.1 1635.47
  3197.3 1634.75  3200.1 1634.77  3572.8 1635.79  3604.9 1628.89  3639.5 1628.33
  3663.2 1635.57  4035.6 1635.56    4053 1635.35  4809.8 1634.81  4923.7 1631.13
  4929.2 1634.33    4990  1635.2  5008.6 1623.98    5030 1630.91  5080.1  1634.8
    5561 1639.15  5864.1 1636.92    6142 1632.68  6370.3  1636.5  6513.3 1641.63
  6763.4 1640.16  6918.1 1642.12  7248.9 1647.07    7493 1648.66  7825.1 1649.35
#Mann= 14 ,-1 , 0
  2008.6     .05       0  2846.1     .07       0  3197.3     .05       0
  3200.1     .07       0  4035.6     .05       0    4053     .07       0
    4990    .045       0    5030     .07       0  5864.1     .05       0
  6370.3     .07       0  6763.4    .035       0  6918.1     .07       0
  7248.9     .05       0    7493    .045       0
Bank Sta=4990,5030
XS Rating Curve= 0 ,0
Exp/Cntr=0.3,0.1

Type RM Length L Ch R = 1 ,42953   ,2003,2003,2003
BEGIN DESCRIPTION:
Mapping XS 8fbb133a
END DESCRIPTION:
XS GIS Cut Line= 3
      1566617.22      6893059.23      1567421.55      6890154.95
      1567641.51      6887469.04
#Sta/Elev= 30
  1986.4 1649.54  3050.4 1642.24    3265 1637.81    3434  1631.6  3698.2 1633.12
  4045.7  1633.6  4049.2 1633.53  4091.9 1627.64  4097.1 1629.83  4114.8 1625.93
  4131.4 1633.68  4153.4 1633.38  4239.4 1631.06    4279 1634.37  4653.1 1635.06
  4820.4 1633.15  4884.8 1629.71  4986.5 1633.99    5000 1631.42    5017 1623.45
    5027 1630.57  5037.1 1632.16  5067.2 1634.31  5841.7 1638.55  5940.1 1631.34
  6050.5 1638.35  6612.3 1637.25  6973.5 1645.04    7283 1646.77  7694.9 1646.91
#Mann= 11 ,-1 , 0
  1986.4    .055       0  3050.4     .07       0    3265     .05       0
    3434     .07       0  3698.2     .05       0  4045.7     .07       0
  4049.2     .05       0  4153.4     .07       0  4986.5    .045       0
  5037.1     .07       0    7283    .045       0
Bank Sta=4986.5,5037.1
XS Rating Curve= 0 ,0
Exp/Cntr=0.3,0.1

Type RM Length L Ch R = 1 ,40950   ,737,737,737
BEGIN DESCRIPTION:
Mapping XS f78891c4
END DESCRIPTION:
XS GIS Cut Line= 4
      1567122.97      6893063.21      1568122.99      6891660.41
      1568491.05      6889618.74       1567887.4      6887641.26
#Sta/Elev= 30
  2644.5  1647.5  3693.4 1642.24  3885.8 1641.13  3940.5    1641  4220.3 1635.49
  4221.1 1635.48  4412.4  1633.9  4812.6 1629.48  4972.4 1632.36  4979.4 1627.79
  5009.9 1619.51  5025.9 1625.33    5031 1631.39  5070.1  1631.9  5098.9 1631.95
  6526.3 1635.92  6693.5 1628.33  6757.6 1628.63  6808.6 1633.51    6934 1633.63
  7017.7 1629.96  7106.7  1634.6  7161.7 1636.96    7331  1633.3  7336.3 1631.06
  7505.5 1633.09  7603.2 1629.36  7655.5  1636.2  7969.1 1642.83  8509.4 1645.73
#Mann= 15 ,-1 , 0
  2644.5    .055       0  3693.4     .07       0  3885.8     .16       0
  3940.5     .07       0  4220.3     .05       0  4221.1     .07       0
  4412.4     .05       0  4812.6     .07       0  4972.4    .045       0
    5031     .07       0  5070.1     .16       0  5098.9     .07       0
  7106.7     .05       0  7161.7     .07       0  7969.1    .045       0
Bank Sta=4972.4,5031
XS Rating Curve= 0 ,0
Exp/Cntr=0.3,0.1

Type RM Length L Ch R = 1 ,40213   ,1198,1198,1198
BEGIN DESCRIPTION:
Mapping XS 8f333c4e
END DESCRIPTION:
XS GIS Cut Line= 3
      1568445.92       6893325.3      1568862.58      6891068.39
      1569096.95      6887856.58
#Sta/Elev= 30
  2674.6  1649.2  3210.8 1648.57  3464.1 1640.98  3632.5 1640.27  4090.5    1639
  4226.9 1638.69  4366.7 1638.06  4389.4  1637.5    4626 1631.98  4702.4 1630.47
  4836.7 1629.83  4920.3 1629.88  4980.1 1631.21  5000.1 1621.89  5010.1  1621.7
  5030.2 1631.61  5116.7 1630.17  6248.8 1634.12  6554.2 1635.83  6704.6 1636.44
  6804.9 1628.71  6879.6 1632.54  6881.7 1632.63  6965.3 1636.67  7246.1 1635.59
  7296.2 1632.89  7565.9 1637.67  7743.2 1642.39  8178.5  1644.3    8190  1644.3
#Mann= 20 ,-1 , 0
  2674.6    .055       0  3632.5     .07       0  4090.5     .16       0
  4226.9     .05       0  4366.7     .07       0  4389.4     .05       0
    4626     .07       0  4702.4     .05       0  4836.7     .07       0
  4920.3     .05       0  4980.1    .035       0  5030.2     .05       0
  5116.7     .07       0  6248.8     .05       0  6554.2     .07       0
  6879.6     .05       0  6881.7     .07       0  7565.9     .05       0
  7743.2    .045       0  8178.5     .05       0
Bank Sta=4980.1,5030.2
XS Rating Curve= 0 ,0
Exp/Cntr=0.3,0.1

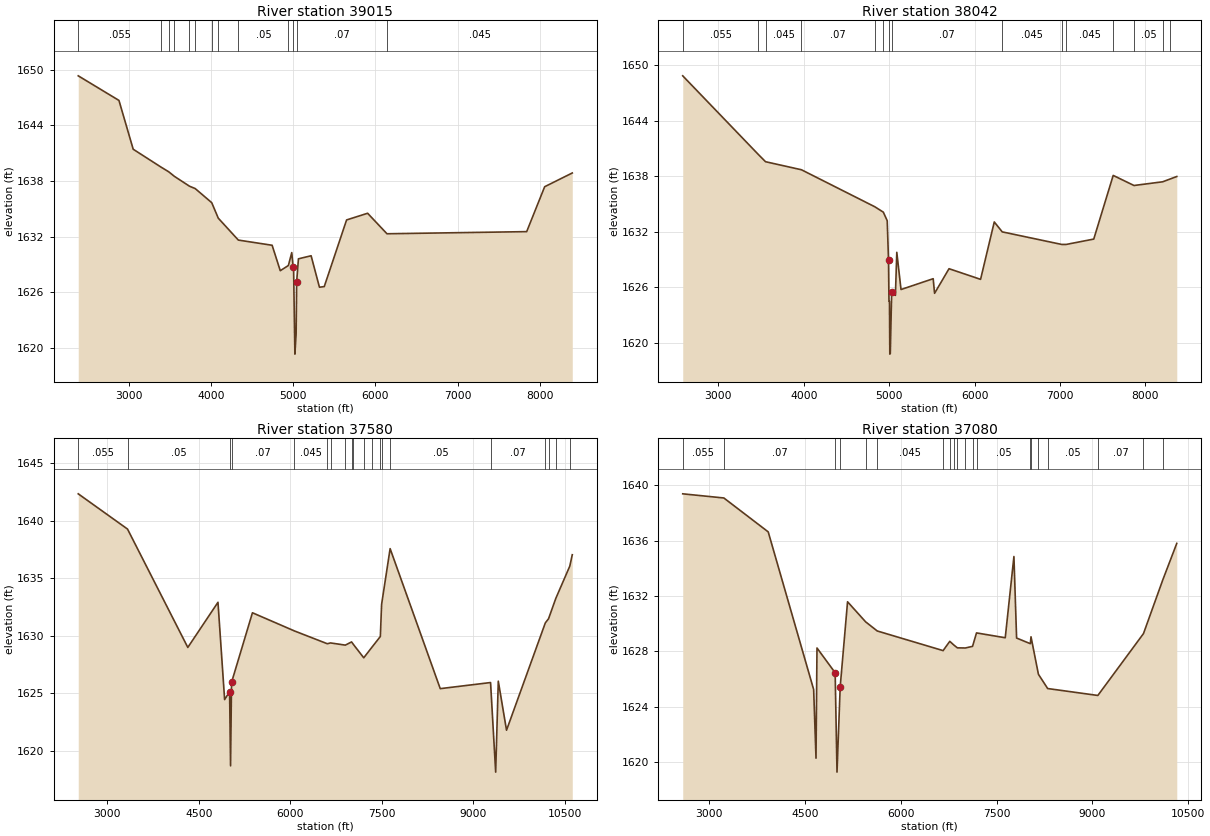
Type RM Length L Ch R = 1 ,39015   ,973,973,973
BEGIN DESCRIPTION:
Mapping XS 9cb95c3c
END DESCRIPTION:
XS GIS Cut Line= 3
      1568489.29      6893377.46      1569661.19      6891033.67
      1571379.98      6888113.03
#Sta/Elev= 30
  2384.3 1649.32  2879.5 1646.67  3052.8 1641.41    3392 1639.48  3484.8 1638.98
  3554.9 1638.48  3736.6 1637.43  3807.1 1637.17  4008.1 1635.65  4087.7 1633.98
  4331.7 1631.62  4742.7 1631.06  4841.7 1628.32  4940.4 1628.88  4981.4 1630.27
  4998.2 1628.71  5003.4 1628.75  5019.6 1619.33  5034.5 1621.49  5041.1 1627.13
  5062.5  1629.6  5216.8 1629.93  5318.3 1626.54  5376.9 1626.61  5648.4 1633.79
  5904.2 1634.51  6139.7  1632.3  7839.1 1632.53  8057.8 1637.37  8393.6 1638.85
#Mann= 13 ,-1 , 0
  2384.3    .055       0    3392     .07       0  3484.8     .16       0
  3554.9     .07       0  3736.6     .16       0  3807.1     .07       0
  4008.1     .05       0  4087.7     .07       0  4331.7     .05       0
  4940.4     .07       0  4998.2    .045       0  5041.1     .07       0
  6139.7    .045       0
Bank Sta=4998.2,5041.1
XS Rating Curve= 0 ,0
Exp/Cntr=0.3,0.1

Type RM Length L Ch R = 1 ,38042   ,462,462,462
BEGIN DESCRIPTION:
Mapping XS ccaa970d
END DESCRIPTION:
XS GIS Cut Line= 4
       1568593.5      6893785.38      1569956.33      6891788.88
      1570807.02       6890217.7      1571829.98      6889013.02
#Sta/Elev= 30
  2583.3 1648.84  3466.6 1640.36  3552.6 1639.56  3973.3 1638.69  4832.7 1634.69
  4931.8 1634.11  4977.6 1633.18  4992.5 1628.97  4998.1 1624.49  5003.9 1624.49
  5007.8 1618.77  5013.5 1618.83  5029.7 1625.48  5073.4 1625.12  5089.6 1629.77
    5139 1625.75  5515.7 1626.92  5531.9 1625.34  5701.2    1628  6070.5 1626.85
  6230.9 1633.05  6324.1 1631.98  7021.1 1630.62  7072.6 1630.62  7395.7  1631.2
  7623.4 1638.08  7866.8 1636.99  8202.4 1637.39  8286.6 1637.68  8367.7 1637.96
#Mann= 15 ,-1 , 0
  2583.3    .055       0  3466.6     .07       0  3552.6    .045       0
  3973.3     .07       0  4832.7     .05       0  4931.8     .07       0
  4992.5    .045       0  5029.7     .07       0  6324.1    .045       0
  7021.1     .05       0  7072.6    .045       0  7623.4     .07       0
  7866.8     .05       0  8202.4    .063       0  8286.6     .07       0
Bank Sta=4992.5,5029.7
XS Rating Curve= 0 ,0
Exp/Cntr=0.3,0.1

Type RM Length L Ch R = 1 ,37580   ,500,500,500
BEGIN DESCRIPTION:
Mapping XS 724eeed4
END DESCRIPTION:
XS GIS Cut Line= 4
      1569155.09      6894147.24       1570356.5      6891966.66
      1570752.33       6891286.1      1573877.51      6887622.11
#Sta/Elev= 30
  2525.8 1642.33  3332.9 1639.27  4320.6 1628.99  4814.8 1632.91  4923.7 1624.46
  5005.1 1625.15    5021 1618.71  5036.8 1625.95  5379.4    1632  6068.1 1630.42
  6605.9 1629.31  6658.1 1629.38  6901.2 1629.19  7003.1 1629.47    7033 1629.25
  7202.8 1628.09  7337.1 1629.01  7474.6 1629.94  7495.1 1632.73  7634.7 1637.57
  8455.7 1625.41    9280 1625.94  9363.7 1618.16  9406.6 1626.06  9541.6  1621.8
   10177 1631.12 10229.7 1631.48 10348.1 1633.24 10577.7 1636.05 10618.5 1637.04
#Mann= 20 ,-1 , 0
  2525.8    .055       0  3332.9     .05       0  5005.1    .035       0
  5036.8     .07       0  6068.1    .045       0  6605.9     .05       0
  6658.1    .045       0  6901.2     .05       0  7003.1    .045       0
    7033     .05       0  7202.8     .07       0  7337.1    .094       0
  7474.6     .05       0  7495.1    .094       0  7634.7     .05       0
    9280     .07       0   10177     .05       0 10229.7     .07       0
 10348.1     .07       0 10577.7     .05       0
Bank Sta=5005.1,5036.8
XS Rating Curve= 0 ,0
Exp/Cntr=0.3,0.1

Type RM Length L Ch R = 1 ,37080   ,719,719,719
BEGIN DESCRIPTION:
Mapping XS 1f9bf38c
END DESCRIPTION:
XS GIS Cut Line= 6
      1569766.22      6894209.71      1569939.83       6893473.6
      1570245.39      6892799.99      1570564.83      6892272.21
      1570759.28      6892022.21      1573893.19      6887741.98
#Sta/Elev= 30
  2586.7 1639.39  3230.4 1639.09    3925 1636.64  4636.3 1625.25  4673.1 1620.29
  4688.6 1628.25    4973 1626.46  5001.9 1619.28    5052 1625.45    5167 1631.59
  5449.9 1630.14  5631.8 1629.48    6663 1628.06  6767.3 1628.73  6837.3 1628.44
  6886.3 1628.26  7011.5 1628.25  7124.2 1628.37  7185.8 1629.34  7635.9 1628.99
  7771.7 1634.86  7813.5 1628.97  8028.7 1628.56  8039.1 1629.06  8155.3 1626.35
  8300.1 1625.32  9085.6 1624.82    9800 1629.29 10102.3 1633.17 10321.2 1635.81
#Mann= 20 ,-1 , 0
  2586.7    .055       0  3230.4     .07       0    4973    .045       0
    5052     .07       0  5449.9     .05       0  5631.8    .045       0
    6663     .05       0  6767.3    .045       0  6837.3     .05       0
  6886.3    .045       0  7011.5     .05       0  7124.2    .045       0
  7185.8     .05       0  8028.7     .07       0  8039.1     .05       0
  8155.3     .07       0  8300.1     .05       0  9085.6     .07       0
    9800     .05       0 10102.3     .07       0
Bank Sta=4973,5052
XS Rating Curve= 0 ,0
Exp/Cntr=0.3,0.1