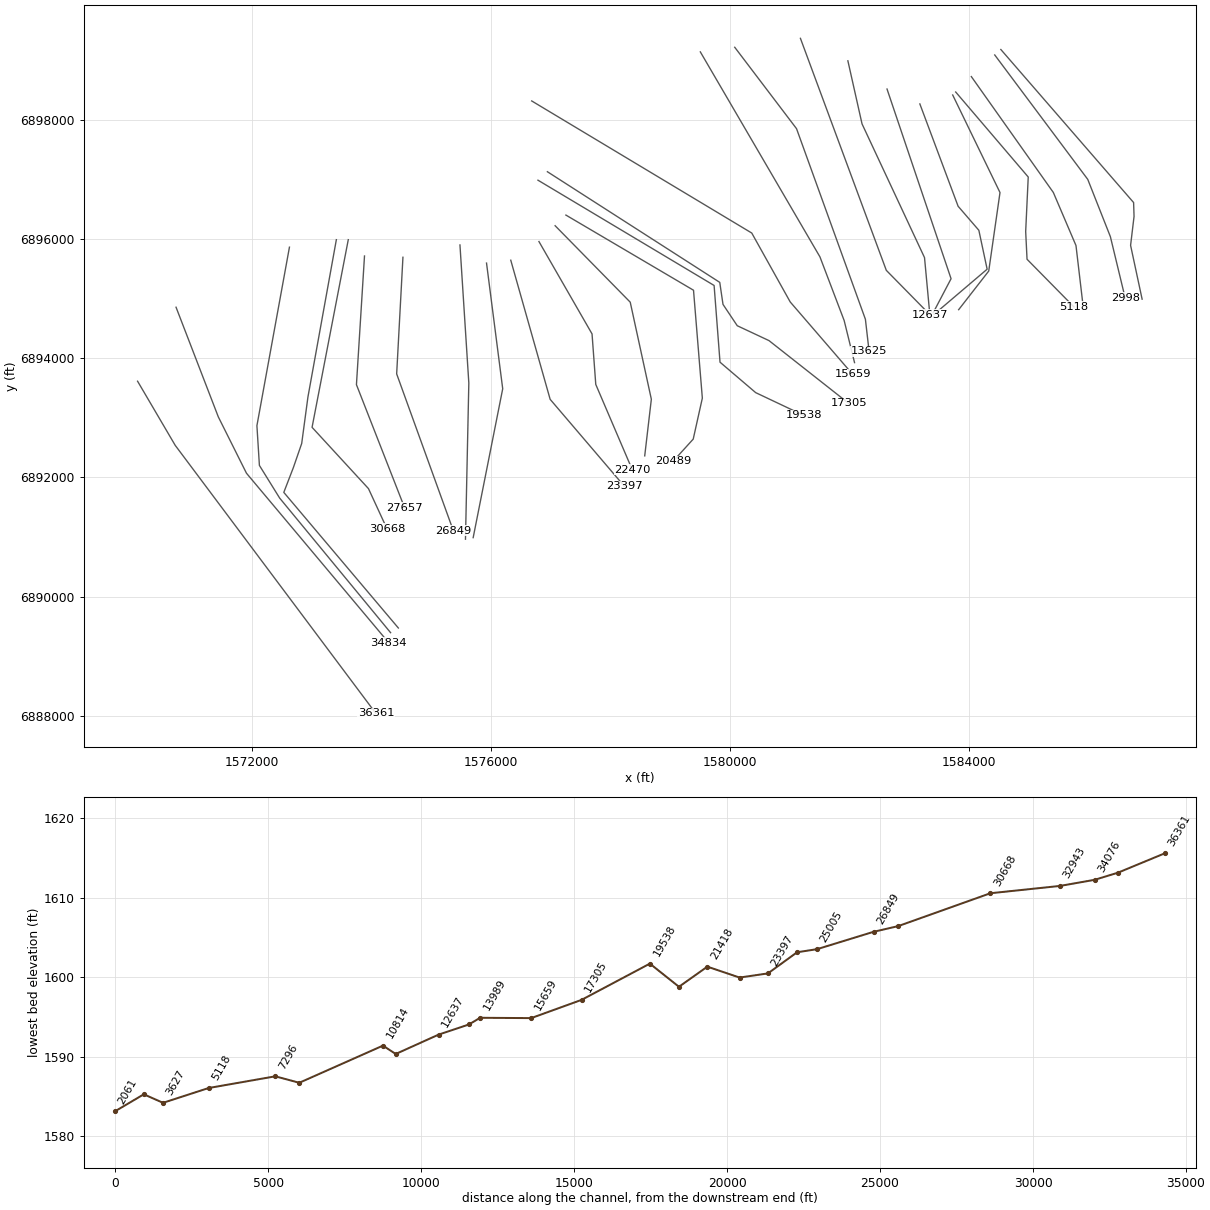
HEC-RAS study MULBERRY CREEK.prj: MULBERRY CREEK Base Level Engineering

--- MULBERRY CREEK.g01 (geometry) --- (continued)

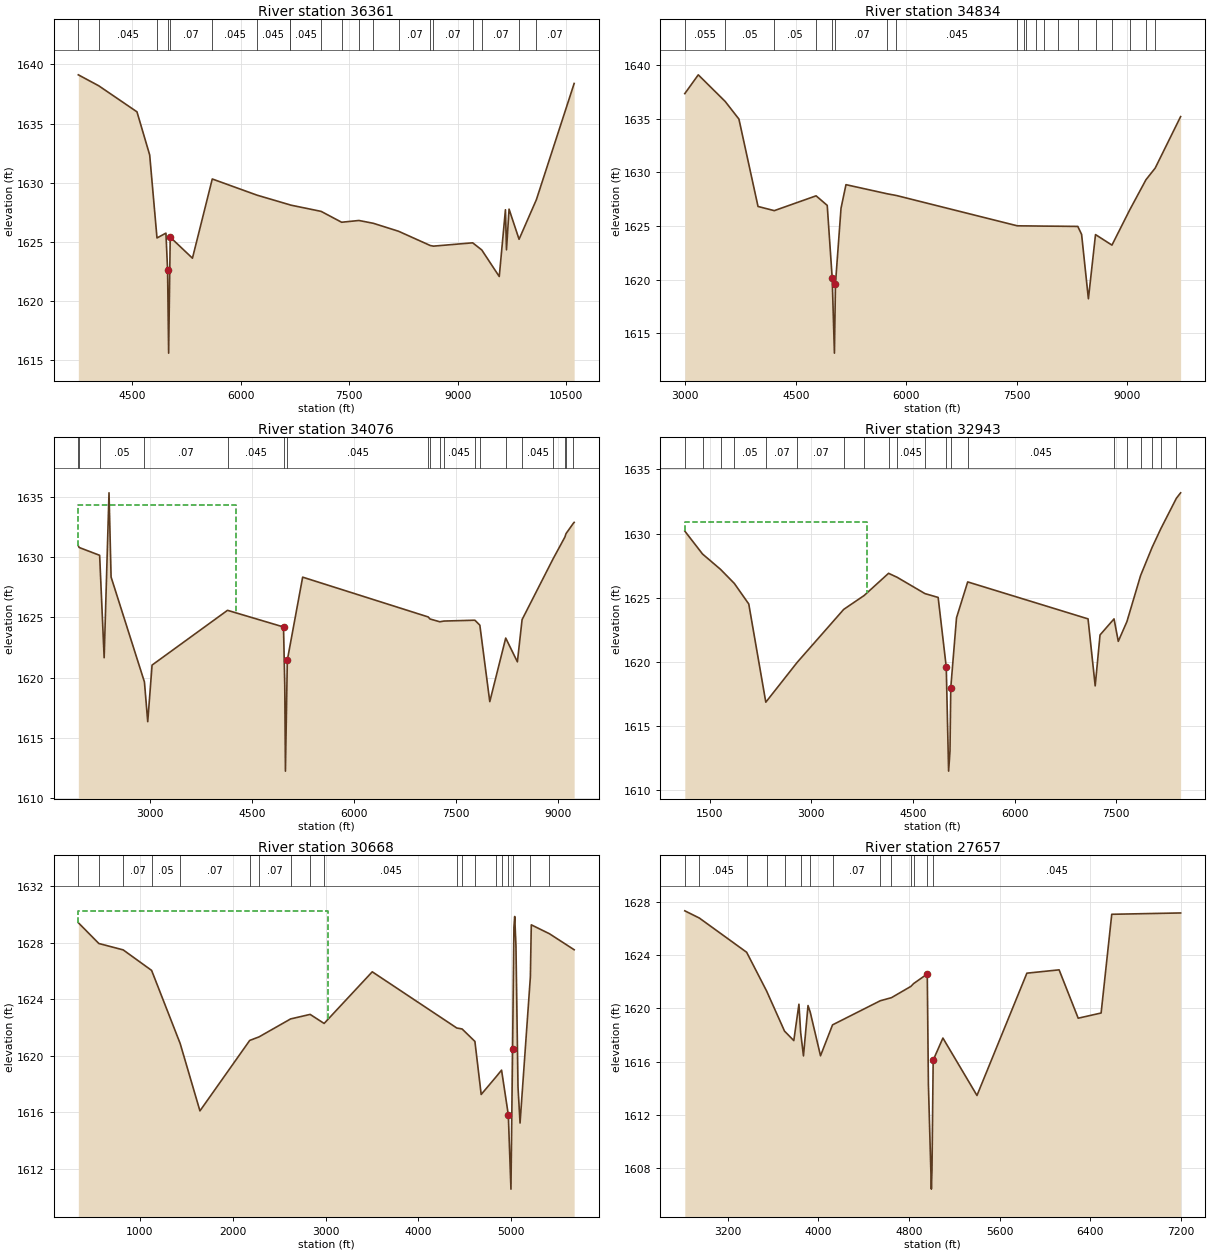
Type RM Length L Ch R = 1 ,36361   ,1527,1527,1527
BEGIN DESCRIPTION:
Mapping XS 8bf59e4a
END DESCRIPTION:
XS GIS Cut Line= 3
      1570080.02      6893612.97      1570709.97      6892538.06
      1574069.93      6888042.92
#Sta/Elev= 30
  3754.1 1639.12  4037.2 1638.19  4565.2 1635.99  4741.1 1632.34  4842.2 1625.32
  4965.8 1625.73  4988.5 1622.63  5003.2 1615.58  5025.1 1625.39  5332.5 1623.61
  5606.7 1630.31  6226.7 1628.94  6677.2 1628.13    6684 1628.11  7112.4 1627.57
    7396 1626.65  7635.6  1626.8  7835.2 1626.56  8182.5 1625.89    8623 1624.68
  8665.5 1624.63  9208.2 1624.91  9333.9 1624.31  9576.2 1622.06  9661.7 1627.71
  9676.2 1624.32  9711.7 1627.76  9850.2 1625.21 10089.6 1628.56 10612.1 1638.39
#Mann= 20 ,-1 , 0
  3754.1     .07       0  4037.2    .045       0  4842.2     .07       0
  4988.5    .045       0  5025.1     .07       0  5606.7    .045       0
  6226.7    .045       0  6677.2     .05       0    6684    .045       0
  7112.4     .07       0    7396     .05       0  7635.6     .07       0
  7835.2     .05       0  8182.5     .07       0    8623     .05       0
  8665.5     .07       0  9208.2     .05       0  9333.9     .07       0
  9850.2     .05       0 10089.6     .07       0
Bank Sta=4988.5,5025.1
XS Rating Curve= 0 ,0
Exp/Cntr=0.3,0.1

Type RM Length L Ch R = 1 ,34834   ,758,758,758
BEGIN DESCRIPTION:
Mapping XS a13414ec
END DESCRIPTION:
XS GIS Cut Line= 4
      1570724.22      6894853.83      1571432.56      6893013.53
      1571903.63      6892069.94      1574282.13      6889231.37
#Sta/Elev= 30
  2992.2 1637.32  3175.3 1639.07  3539.2  1636.6  3726.9 1634.95  3986.1 1626.81
  4206.5 1626.42  4774.3  1627.8  4925.5 1626.91  4992.7 1620.15  5023.1 1613.15
  5037.4 1619.63  5112.6 1626.64  5179.7 1628.84  5740.1 1627.99  5865.1 1627.83
  7503.4 1625.01  7594.2    1625  7628.3    1625    7754 1624.99  7862.8 1624.98
  8062.2 1624.97  8326.5 1624.95    8378 1624.21  8470.3 1618.21  8566.8 1624.19
  8790.1 1623.21  9029.7 1626.47  9251.7  1629.3  9376.6 1630.38  9722.1 1635.18
#Mann= 20 ,-1 , 0
  2992.2    .055       0  3539.2     .05       0  4206.5     .05       0
  4774.3    .045       0  4992.7    .045       0  5037.4     .07       0
  5740.1     .07       0  5865.1    .045       0  7503.4     .07       0
  7594.2    .045       0  7628.3     .07       0    7754     .07       0
  7862.8    .045       0  8062.2     .05       0  8326.5    .045       0
  8566.8     .05       0  8790.1     .07       0  9029.7    .045       0
  9251.7     .05       0  9376.6    .045       0
Bank Sta=4992.7,5037.4
XS Rating Curve= 0 ,0
Exp/Cntr=0.3,0.1

Type RM Length L Ch R = 1 ,34076   ,1133,1133,1133
BEGIN DESCRIPTION:
Mapping XS 92125bfe
END DESCRIPTION:
XS GIS Cut Line= 5
      1572623.25      6895860.99       1572078.4       6892867.7
      1572120.06      6892201.03      1572459.18      6891653.28
      1574316.82      6889396.33
#Sta/Elev= 30
  1954.2 1630.94  1966.3  1630.8    2267 1630.15  2333.3 1621.66  2404.5 1635.33
    2435 1628.35  2924.6 1619.65    2973 1616.36  3036.5 1621.05  4143.9 1625.59
  4965.9 1624.21  4984.4 1619.34    4994 1612.26  5021.9 1621.46  5246.9 1628.34
  7090.2 1625.04  7116.5 1624.87  7261.6 1624.64  7318.1  1624.7  7774.8 1624.77
  7847.7 1624.36  7993.4 1618.02  8227.6 1623.29  8398.7 1621.32  8467.7 1624.82
    8922 1629.85  9096.7 1631.67  9112.9 1631.95  9220.7 1632.81    9232 1632.88
#Mann= 19 ,-1 , 0
  1954.2    .055       0  1966.3     .07       0    2267     .05       0
  2924.6     .07       0  4143.9    .045       0  4965.9    .045       0
  5021.9    .045       0  7090.2     .07       0  7116.5    .045       0
  7261.6     .07       0  7318.1    .045       0  7774.8     .05       0
  7847.7    .045       0  8227.6     .05       0  8467.7    .045       0
    8922     .07       0  9096.7     .05       0  9112.9     .07       0
  9220.7     .05       0
#XS Ineff= 2 , 0
       0  4265.3 1634.29               0
Permanent Ineff=
       F       F
Bank Sta=4965.9,5021.9
XS Rating Curve= 0 ,0
Exp/Cntr=0.3,0.1

Type RM Length L Ch R = 1 ,32943   ,2275,2275,2275
BEGIN DESCRIPTION:
Mapping XS ed66d22b
END DESCRIPTION:
XS GIS Cut Line= 6
      1573408.84      6895986.88      1572932.56      6893346.86
       1572828.4      6892569.09      1572689.51      6892166.31
      1572528.63      6891748.76      1574447.01      6889474.48
#Sta/Elev= 30
  1133.5 1630.19  1395.9  1628.4  1660.3 1627.21  1864.8 1626.11  2077.4 1624.51
  2328.9 1616.86  2791.4 1619.96  3478.5 1624.09  3779.4 1625.17  4140.2  1626.9
  4266.7 1626.59  4677.2 1625.32  4871.9 1625.02  4991.4 1619.61  5026.2 1611.49
  5046.5 1613.05    5058 1617.98    5143 1623.44  5307.8 1626.23  7083.7 1623.35
  7189.2 1618.13  7260.6  1622.1  7467.2 1623.35  7529.8  1621.6  7657.3 1623.14
  7859.3 1626.73  8029.7 1628.93  8158.1 1630.38  8387.5 1632.75  8449.7 1633.17
#Mann= 20 ,-1 , 0
  1133.5    .055       0  1395.9     .05       0  1660.3     .07       0
  1864.8     .05       0  2328.9     .07       0  2791.4     .07       0
  3478.5    .045       0  3779.4    .045       0  4140.2     .05       0
  4266.7    .045       0  4677.2    .045       0  4991.4    .045       0
    5058     .07       0  5307.8    .045       0  7467.2    .035       0
  7657.3    .045       0  7859.3     .07       0  8029.7    .045       0
  8158.1    .035       0  8387.5    .035       0
#XS Ineff= 2 , 0
       0  3817.2  1630.9               0
Permanent Ineff=
       F       F
Bank Sta=4991.4,5058
XS Rating Curve= 0 ,0
Exp/Cntr=0.3,0.1

Type RM Length L Ch R = 1 ,30668   ,3011,3011,3011
BEGIN DESCRIPTION:
Mapping XS b14864b4
END DESCRIPTION:
XS GIS Cut Line= 4
      1573608.49      6895986.83      1573002.01      6892839.92
      1573946.45      6891812.14      1574256.67      6891138.47
#Sta/Elev= 30
   336.2  1629.4   557.2 1627.93   819.3 1627.48  1125.7 1626.03  1433.6 1620.86
  1646.5  1616.1  2182.8 1621.08  2283.1 1621.33  2623.6  1622.6  2833.8 1622.92
  2984.6 1622.28  3503.1 1625.93  4413.4 1621.96  4471.1 1621.89  4609.1 1621.01
  4676.8 1617.26  4833.9 1618.48  4896.4 1618.98  4969.1 1615.82  4997.5 1610.57
    5015 1620.44  5029.5 1629.09    5038 1629.84  5051.5 1627.74  5073.5 1617.79
  5095.5 1615.24  5206.8 1625.57  5216.6 1629.25  5412.3 1628.62  5678.5 1627.49
#Mann= 19 ,-1 , 0
   336.2    .055       0   557.2     .05       0   819.3     .07       0
  1125.7     .05       0  1433.6     .07       0  2182.8     .05       0
  2283.1     .07       0  2623.6    .045       0  2833.8     .07       0
  2984.6    .045       0  4413.4    .035       0  4471.1    .045       0
  4609.1     .05       0  4833.9     .07       0  4896.4     .05       0
  4969.1    .035       0    5015     .05       0  5206.8    .045       0
  5412.3     .05       0
#XS Ineff= 2 , 0
       0  3025.1 1630.24               0
Permanent Ineff=
       F       F
Bank Sta=4969.1,5015
XS Rating Curve= 0 ,0
Exp/Cntr=0.3,0.1

Type RM Length L Ch R = 1 ,27657   ,808,808,808
BEGIN DESCRIPTION:
Mapping XS a410c087
END DESCRIPTION:
XS GIS Cut Line= 3
        1573880.      6895712.95      1573745.06       6893555.2
      1574550.16      6891494.66
#Sta/Elev= 30
  2822.6 1627.33  2950.6 1626.79  3368.2 1624.22  3543.9 1621.32  3702.5  1618.3
  3784.2 1617.59  3829.5 1620.32  3844.7  1618.2  3869.6 1616.44  3909.7 1620.22
  3929.3 1619.72  4019.9 1616.45  4126.1 1618.77  4547.2 1620.58  4645.5 1620.81
  4817.6 1621.66  4841.3 1621.87  4961.7 1622.59  4971.7  1614.3  4997.9 1606.44
  5003.3 1607.84  5013.8 1616.12  5099.7 1617.78  5400.3 1613.47  5840.5 1622.65
  6124.8  1622.9  6293.2 1619.27  6495.4 1619.66  6589.2 1627.07  7196.8 1627.17
#Mann= 14 ,-1 , 0
  2822.6     .05       0  2950.6    .045       0  3368.2     .05       0
  3543.9     .07       0  3702.5     .05       0  3844.7     .07       0
  3929.3     .05       0  4126.1     .07       0  4547.2     .05       0
  4645.5    .045       0  4817.6     .07       0  4841.3    .045       0
  4961.7    .045       0  5013.8    .045       0
Bank Sta=4961.7,5013.8
XS Rating Curve= 0 ,0
Exp/Cntr=0.3,0.1

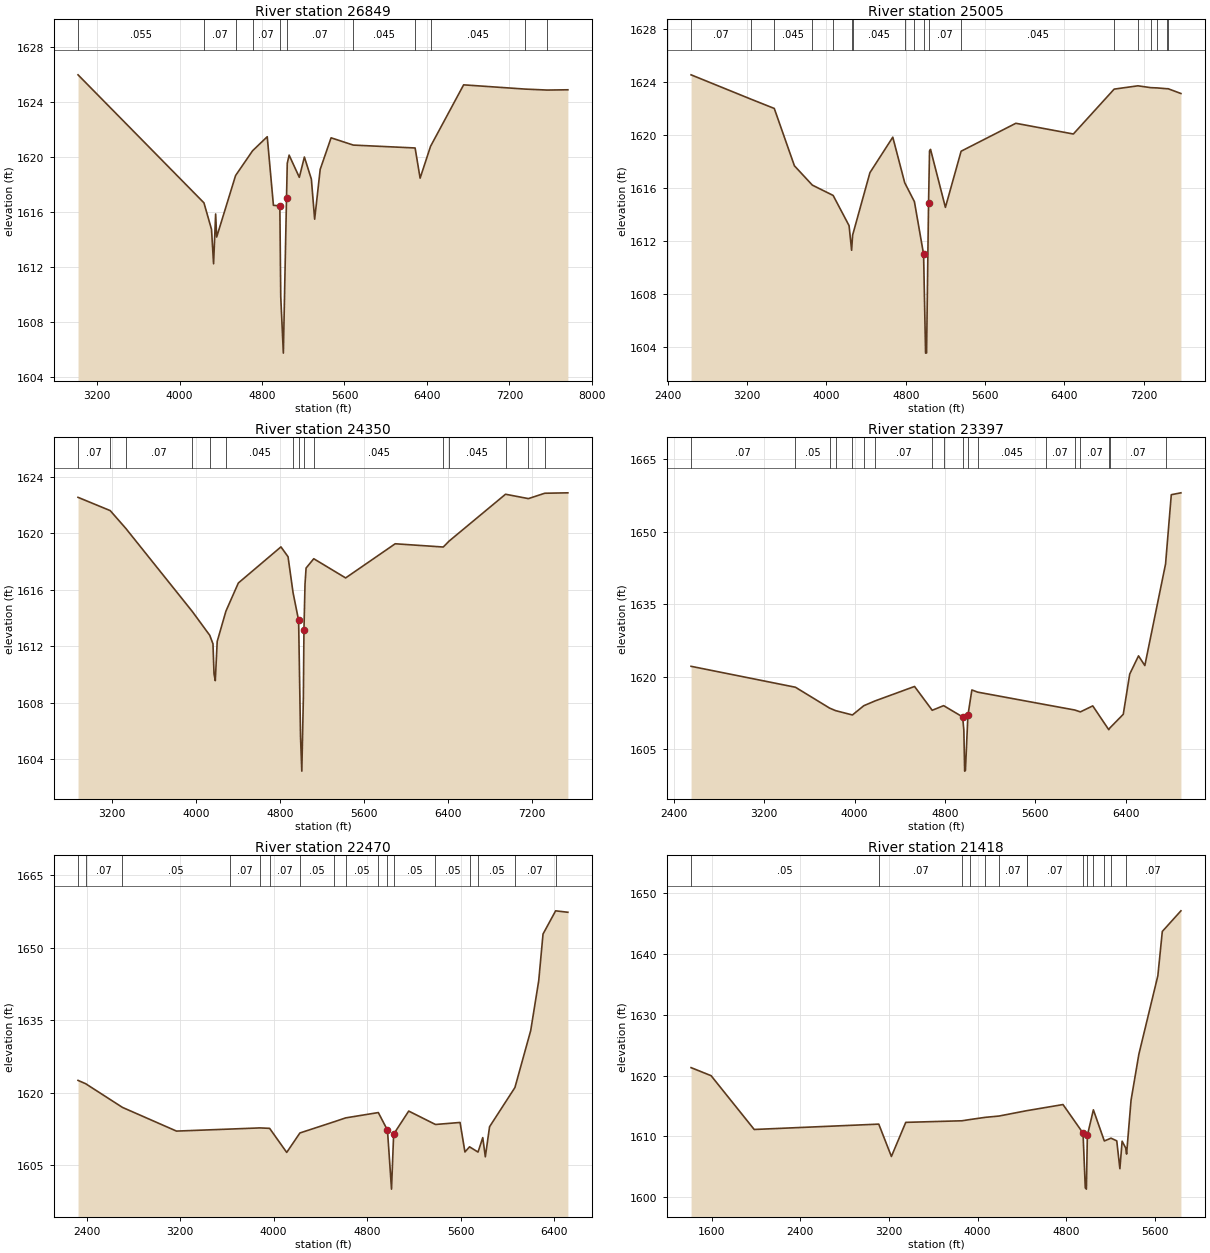
Type RM Length L Ch R = 1 ,26849   ,1844,1844,1844
BEGIN DESCRIPTION:
Mapping XS 21188de9
END DESCRIPTION:
XS GIS Cut Line= 3
      1574523.71      6895691.63      1574418.67      6893735.75
      1575367.58      6891106.23
#Sta/Elev= 30
  3013.9    1626  4236.1 1616.67  4309.4 1614.74  4329.4 1612.23  4349.5 1615.86
  4359.5 1614.18  4542.9 1618.66  4708.4 1620.47  4850.2 1621.49  4910.3 1616.49
  4972.6 1616.45  4981.3 1609.84  5006.7 1605.72  5037.4 1617.04  5044.6 1619.55
  5062.7 1620.15  5161.6 1618.53  5210.8 1620.01  5278.5  1618.4  5310.4 1615.48
  5364.2 1619.11  5469.9 1621.41  5685.7 1620.88  6285.4 1620.67    6334 1618.47
  6435.2 1620.79  6756.3 1625.27  7354.8 1624.96  7566.4 1624.89  7768.1 1624.91
#Mann= 11 ,-1 , 0
  3013.9    .055       0  4236.1     .07       0  4542.9    .045       0
  4708.4     .07       0  4972.6    .045       0  5037.4     .07       0
  5685.7    .045       0  6285.4     .07       0  6435.2    .045       0
  7354.8     .07       0  7566.4    .045       0
Bank Sta=4972.6,5037.4
XS Rating Curve= 0 ,0
Exp/Cntr=0.3,0.1

Type RM Length L Ch R = 1 ,25005   ,655,655,655
BEGIN DESCRIPTION:
Mapping XS f4618f58
END DESCRIPTION:
XS GIS Cut Line= 3
      1575478.57      6895897.82      1575627.01      6893582.98
      1575570.94      6890963.77
#Sta/Elev= 30
  2635.1 1624.56    3243 1622.71  3474.1 1622.02  3677.1 1617.69  3857.8 1616.23
  4067.7 1615.45  4228.2 1613.17  4253.9 1611.31  4263.9 1612.45  4438.6 1617.17
  4669.1 1619.85  4789.3 1616.41  4887.2 1614.98  4979.7 1611.01  4999.7 1603.54
  5009.7 1603.55  5029.7 1614.86  5039.7 1618.81  5049.7 1618.93  5199.7 1614.55
  5358.1 1618.79  5909.9  1620.9    6490 1620.09  6901.3 1623.48  7140.6 1623.73
  7271.7 1623.59  7337.9 1623.57  7431.5 1623.51  7445.2 1623.51  7574.5 1623.15
#Mann= 18 ,-1 , 0
  2635.1     .07       0    3243     .05       0  3474.1    .045       0
  3857.8     .07       0  4067.7    .045       0  4253.9     .05       0
  4263.9    .045       0  4789.3     .05       0  4887.2     .07       0
  4979.7    .035       0  5029.7     .07       0  5358.1    .045       0
  6901.3     .07       0  7140.6    .035       0  7271.7    .045       0
  7337.9    .035       0  7431.5    .045       0  7445.2     .05       0
Bank Sta=4979.7,5029.7
XS Rating Curve= 0 ,0
Exp/Cntr=0.3,0.1

Type RM Length L Ch R = 1 ,24350   ,953,953,953
BEGIN DESCRIPTION:
Mapping XS bb942bd8
END DESCRIPTION:
XS GIS Cut Line= 3
      1575923.44      6895594.04      1576194.52       6893486.5
      1575699.71      6890989.56
#Sta/Elev= 30
  2875.1 1622.55  3181.9 1621.61  3329.4 1620.36  3964.8 1614.46  4131.3 1612.77
  4161.7 1612.17  4171.7 1610.04  4183.8 1609.56    4202 1612.34  4285.4 1614.49
  4403.6 1616.48  4809.9 1619.04  4877.5 1618.34  4925.2  1615.8  4978.3 1613.83
  4996.7 1605.53  5008.7 1603.15  5023.6 1608.37  5029.1 1613.14  5039.3 1616.41
  5049.4 1617.54  5122.6  1618.2  5426.6 1616.84  5899.2 1619.26  6357.2 1619.03
    6413 1619.45    6951 1622.77  7169.2 1622.46  7324.7 1622.84  7545.5 1622.87
#Mann= 15 ,-1 , 0
  2875.1     .07       0  3181.9     .05       0  3329.4     .07       0
  3964.8     .05       0  4131.3     .07       0  4285.4    .045       0
  4925.2     .07       0  4978.3    .045       0  5029.1     .07       0
  5122.6    .045       0  6357.2     .05       0    6413    .045       0
    6951     .07       0  7169.2     .05       0  7324.7     .05       0
Bank Sta=4978.3,5029.1
XS Rating Curve= 0 ,0
Exp/Cntr=0.3,0.1

Type RM Length L Ch R = 1 ,23397   ,927,927,927
BEGIN DESCRIPTION:
Mapping XS c979a117
END DESCRIPTION:
XS GIS Cut Line= 3
      1576329.28      6895642.43      1576988.99      6893309.13
       1578230.1      6891853.08
#Sta/Elev= 30
  2552.4 1622.18  3476.5 1617.85  3779.4 1613.53  3831.8 1613.01  3981.3 1612.11
  4082.2 1614.03  4183.2 1615.03  4531.5 1618.01    4688 1613.08    4789 1614.04
  4957.6  1611.7    4968 1608.98  4975.2 1600.49    4982 1600.61    5004 1612.02
  5039.1 1617.29  5089.8 1616.84  5692.6 1614.24  5950.1 1613.14  6000.1 1612.75
  6109.7 1613.99  6251.5 1609.06  6261.1 1609.42  6379.8 1612.25  6436.9 1620.57
  6514.9 1624.34  6570.8 1622.34  6754.4 1643.36  6805.1 1657.69  6890.4 1658.08
#Mann= 18 ,-1 , 0
  2552.4     .07       0  3476.5     .05       0  3779.4     .07       0
  3831.8     .05       0  3981.3     .07       0  4082.2     .05       0
  4183.2     .07       0    4688    .035       0    4789     .07       0
  4957.6    .045       0    5004     .07       0  5089.8    .045       0
  5692.6     .07       0  5950.1     .05       0  6000.1     .07       0
  6251.5     .05       0  6261.1     .07       0  6754.4     .05       0
Bank Sta=4957.6,5004
XS Rating Curve= 0 ,0
Exp/Cntr=0.3,0.1

Type RM Length L Ch R = 1 ,22470   ,1052,1052,1052
BEGIN DESCRIPTION:
Mapping XS 1ba3bf09
END DESCRIPTION:
XS GIS Cut Line= 4
      1576801.46        6895955.      1577690.38      6894406.36
      1577752.88      6893559.13        1578364.      6892128.55
#Sta/Elev= 30
  2327.4 1622.51  2392.1 1621.83  2707.6 1616.91  3169.8    1612  3626.8 1612.42
    3883 1612.66  3966.5 1612.57  4112.7 1607.58  4225.6 1611.61  4519.5 1613.94
  4617.5 1614.74  4896.5 1615.84  4974.7  1612.2  5009.4 1599.97  5027.6 1611.36
  5156.5 1616.15  5385.6 1613.37  5595.8 1613.79  5637.5 1607.67  5676.9 1608.74
  5749.5 1607.65    5790 1610.65    5812 1606.67  5848.1  1612.9  6065.2 1621.03
  6200.3 1632.85  6268.7 1643.16  6305.6 1652.85  6413.5 1657.66  6518.2 1657.36
#Mann= 17 ,-1 , 0
  2327.4     .05       0  2392.1     .07       0  2707.6     .05       0
  3626.8     .07       0    3883     .05       0  3966.5     .07       0
  4225.6     .05       0  4519.5     .07       0  4617.5     .05       0
  4896.5     .07       0  4974.7    .045       0  5027.6     .05       0
  5385.6     .05       0  5676.9     .07       0  5749.5     .05       0
  6065.2     .07       0  6413.5     .05       0
Bank Sta=4974.7,5027.6
XS Rating Curve= 0 ,0
Exp/Cntr=0.3,0.1

Type RM Length L Ch R = 1 ,21418   ,929,929,929
BEGIN DESCRIPTION:
Mapping XS d8619799
END DESCRIPTION:
XS GIS Cut Line= 4
      1577072.35      6896220.56        1578330.      6894938.41
      1578683.43      6893310.87      1578572.53      6892361.28
#Sta/Elev= 30
  1415.5 1621.32    1596    1620  1984.9 1611.15  3108.2 1612.03  3222.1 1606.71
  3351.5 1612.32  3858.5 1612.58  3932.7 1612.79  4070.1 1613.15  4192.7 1613.36
  4444.7 1614.25  4445.8 1614.25  4769.5 1615.25  4950.3 1610.55  4970.5 1601.55
  4980.5 1601.34  4989.2 1610.16  5043.5 1614.38  5142.3 1609.26  5202.4 1609.72
  5254.4 1609.28  5282.6  1604.7  5302.7 1609.22  5334.9 1608.11    5343  1607.1
  5383.2 1615.96  5453.7 1623.52  5624.9 1636.43  5665.2 1643.72    5833 1647.11
#Mann= 14 ,-1 , 0
  1415.5     .05       0  3108.2     .07       0  3858.5     .16       0
  3932.7     .07       0  4070.1     .05       0  4192.7     .07       0
  4444.7     .05       0  4445.8     .07       0  4950.3    .045       0
  4989.2     .07       0  5043.5     .05       0  5142.3     .07       0
  5202.4     .05       0  5334.9     .07       0
Bank Sta=4950.3,4989.2
XS Rating Curve= 0 ,0
Exp/Cntr=0.3,0.1

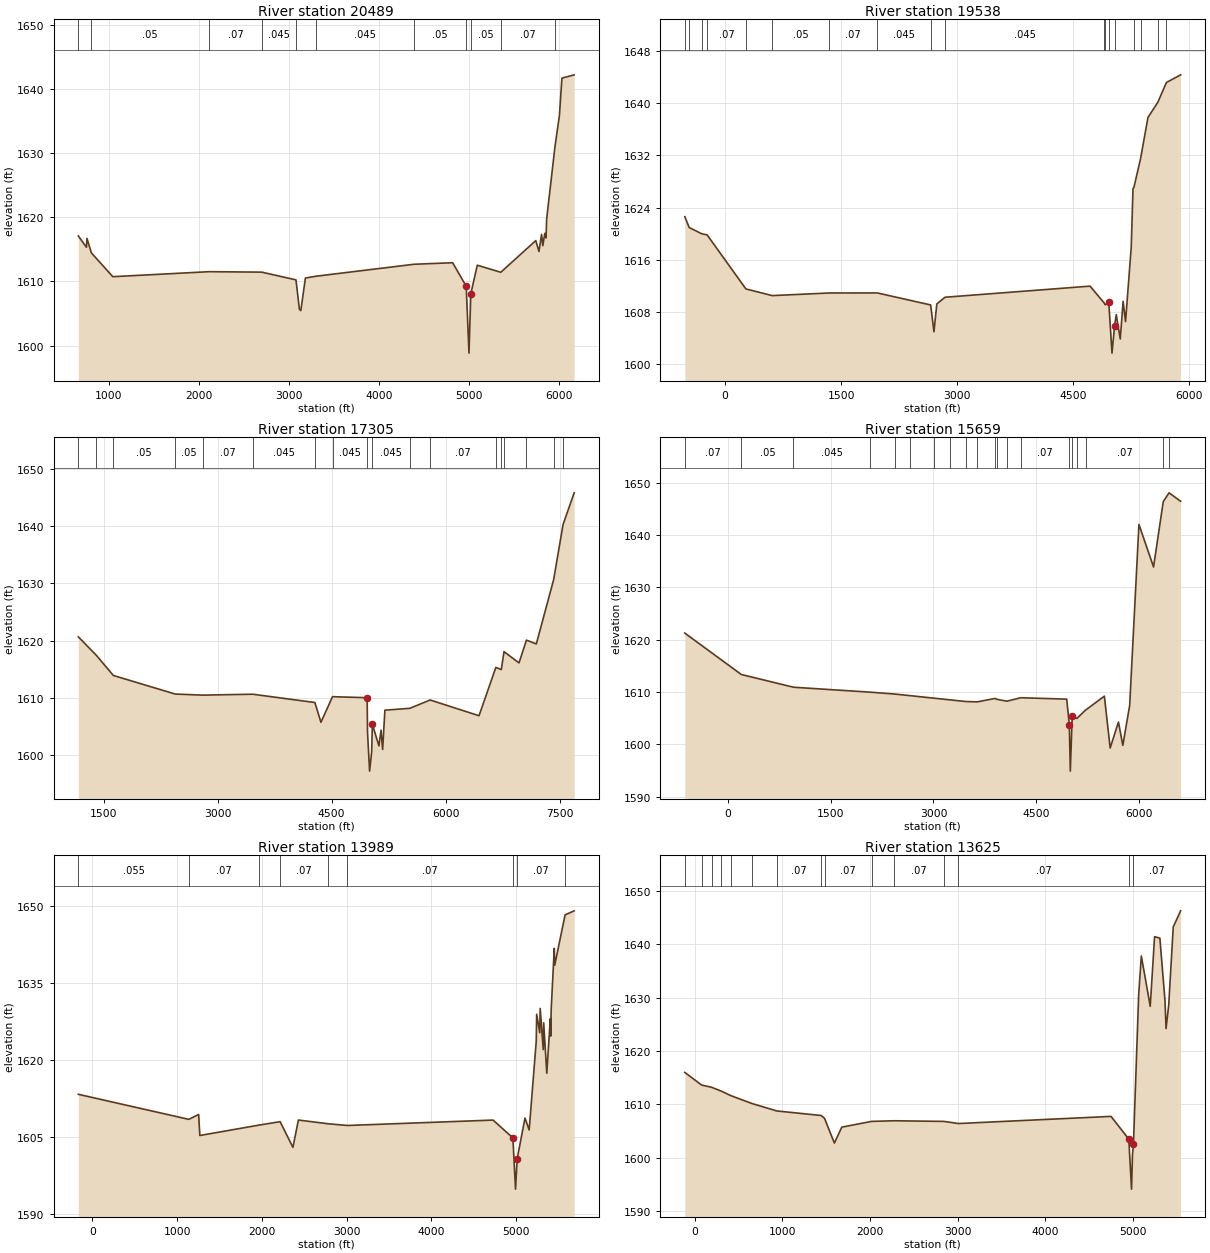
Type RM Length L Ch R = 1 ,20489   ,951,951,951
BEGIN DESCRIPTION:
Mapping XS 103903d3
END DESCRIPTION:
XS GIS Cut Line= 5
      1577252.79      6896399.04      1579389.66      6895138.81
      1579537.48      6893329.62       1579384.7      6892642.12
      1579044.41       6892267.1
#Sta/Elev= 30
   661.1 1617.11   751.2 1615.34     757 1616.73   806.1 1614.47    1044 1610.75
  2111.6 1611.53    2698 1611.46  3078.4 1610.25  3116.5 1605.64  3132.2 1605.45
  3182.9 1610.54  3299.5 1610.82  4389.5 1612.69  4818.3 1612.93    4969 1609.26
  4999.8 1598.81  5020.2 1608.07    5092 1612.54    5353 1611.44    5742 1616.39
  5777.2 1614.68  5805.5 1617.36  5819.7 1615.59  5841.4 1617.52  5855.6 1616.79
  5862.3 1619.75  5954.4 1631.02  6004.2 1635.94  6031.9 1641.76  6167.8 1642.28
#Mann= 11 ,-1 , 0
   661.1     .05       0   806.1     .05       0  2111.6     .07       0
    2698    .045       0  3078.4     .07       0  3299.5    .045       0
  4389.5     .05       0    4969    .035       0  5020.2     .05       0
    5353     .07       0  5954.4     .05       0
Bank Sta=4969,5020.2
XS Rating Curve= 0 ,0
Exp/Cntr=0.3,0.1

Type RM Length L Ch R = 1 ,19538   ,2233,2233,2233
BEGIN DESCRIPTION:
Mapping XS 928e359c
END DESCRIPTION:
XS GIS Cut Line= 5
      1576784.85      6896984.15      1579734.47      6895218.71
      1579833.49      6893932.05      1580430.71      6893421.63
      1581236.27      6893039.69
#Sta/Elev= 30
  -519.8 1622.59  -462.5 1620.93  -299.8 1619.98  -231.2 1619.81   269.5 1611.54
   610.4 1610.52  1346.4 1610.92  1966.7 1610.93  2656.2 1609.09    2699 1604.99
    2736 1609.25  2841.8 1610.27  4715.7 1611.97  4896.2 1609.42  4910.1 1609.12
  4957.2 1609.52    4999 1601.72  5031.8 1605.84    5054 1607.61  5105.6 1603.88
  5142.5 1609.64  5173.8 1606.54  5247.5 1617.94  5270.3 1626.91  5281.5 1627.05
  5368.4  1631.5  5463.4 1637.77  5590.5 1640.09  5701.5 1643.12  5885.4  1644.3
#Mann= 18 ,-1 , 0
  -519.8     .05       0  -462.5     .07       0  -299.8     .05       0
  -231.2     .07       0   269.5     .05       0   610.4     .05       0
  1346.4     .07       0  1966.7    .045       0  2656.2     .07       0
  2841.8    .045       0  4896.2     .05       0  4910.1     .07       0
  4957.2    .045       0  5031.8     .07       0  5281.5     .05       0
  5368.4     .07       0  5590.5     .05       0  5701.5     .07       0
Bank Sta=4957.2,5031.8
XS Rating Curve= 0 ,0
Exp/Cntr=0.3,0.1

Type RM Length L Ch R = 1 ,17305   ,1646,1646,1646
BEGIN DESCRIPTION:
Mapping XS da5d24cf
END DESCRIPTION:
XS GIS Cut Line= 6
      1576942.83      6897126.04      1579829.09      6895270.59
      1579883.34      6894901.67      1580122.06      6894543.59
      1580653.74      6894294.03      1581987.43      6893242.26
#Sta/Elev= 30
    1169 1620.64  1405.7 1617.42  1629.2 1613.89  2442.9 1610.64  2802.4 1610.45
  3462.4 1610.61  4279.8 1609.16  4359.4  1605.7    4512 1610.18  4966.7    1610
  4972.4 1603.87  4999.3 1597.16  5026.4 1600.52  5035.4 1605.37  5121.7 1601.58
  5149.6 1604.31  5170.6 1600.95  5200.6 1607.82  5527.8 1608.14  5795.3  1609.6
  6438.1 1606.85  6659.6  1615.3  6731.1 1614.92    6767 1618.05    6964 1616.09
    7062 1620.07  7191.7  1619.4  7419.4 1630.63  7543.6  1640.3  7689.3 1645.83
#Mann= 18 ,-1 , 0
    1169     .05       0  1405.7     .07       0  1629.2     .05       0
  2442.9     .05       0  2802.4     .07       0  3462.4    .045       0
  4279.8     .07       0    4512    .045       0  4966.7    .045       0
  5035.4    .045       0  5527.8     .05       0  5795.3     .07       0
  6659.6     .05       0  6731.1     .07       0    6767     .05       0
    7062     .07       0  7419.4     .05       0  7543.6     .07       0
Bank Sta=4966.7,5035.4
XS Rating Curve= 0 ,0
Exp/Cntr=0.3,0.1

Type RM Length L Ch R = 1 ,15659   ,1670,1670,1670
BEGIN DESCRIPTION:
Mapping XS 19543e3b
END DESCRIPTION:
XS GIS Cut Line= 4
      1576679.98      6898313.01      1580365.08      6896097.86
       1581009.1      6894942.12      1582053.51      6893729.76
#Sta/Elev= 30
  -622.7 1621.28     200 1613.36   960.7 1610.92  2071.9 1609.98  2432.2 1609.62
    2652 1609.32  3004.5 1608.83  3244.8  1608.5  3474.6 1608.18  3637.5 1608.12
  3899.4 1608.78  3919.4 1608.62    4070 1608.25    4270 1608.91    4941 1608.64
  4978.7 1603.76  4993.3 1594.87    5021 1605.39  5088.6 1604.95  5214.9 1606.54
  5489.4 1609.21  5573.9  1599.3  5694.6 1604.26  5758.3  1599.8  5858.1 1607.45
    5993 1642.06  6205.9 1633.93  6347.2 1646.43  6431.9 1648.11  6600.2  1646.5
#Mann= 20 ,-1 , 0
  -622.7     .07       0     200     .05       0   960.7    .045       0
  2071.9     .05       0  2432.2     .07       0    2652     .05       0
  3004.5     .07       0  3244.8    .045       0  3474.6     .05       0
  3637.5     .07       0  3899.4     .05       0  3919.4     .07       0
    4070     .05       0    4270     .07       0  4978.7    .045       0
    5021     .07       0  5088.6     .05       0  5214.9     .07       0
  6347.2     .05       0  6431.9     .07       0
Bank Sta=4978.7,5021
XS Rating Curve= 0 ,0
Exp/Cntr=0.3,0.1

Type RM Length L Ch R = 1 ,13989   ,364,364,364
BEGIN DESCRIPTION:
Mapping XS 7c0ab32e
END DESCRIPTION:
XS GIS Cut Line= 4
      1579503.73      6899135.87       1581506.9      6895698.01
      1581912.42       6894630.4      1582086.04      6893925.08
#Sta/Elev= 30
  -164.6 1613.34  1138.5 1608.47  1254.4 1609.42  1268.1 1605.33  1961.8 1607.34
  2215.3 1608.02  2366.1 1603.03  2430.6 1608.34  2783.8 1607.61  3009.4 1607.28
  4726.6 1608.33  4960.1 1604.87  4991.4 1594.91  5010.3 1600.76    5103 1608.73
  5152.3 1606.41  5235.4 1623.62  5240.5  1628.9  5276.9  1625.3    5282 1630.03
  5318.4 1622.03  5323.6 1627.24  5359.9 1617.44  5401.4 1628.04  5406.6 1624.66
  5411.9 1629.85  5448.1  1641.7  5453.3 1638.43  5575.8 1648.21  5682.7    1649
#Mann= 9 ,-1 , 0
  -164.6    .055       0  1138.5     .07       0  1961.8     .05       0
  2215.3     .07       0  2783.8    .045       0  3009.4     .07       0
  4960.1    .045       0  5010.3     .07       0  5575.8     .05       0
Bank Sta=4960.1,5010.3
XS Rating Curve= 0 ,0
Exp/Cntr=0.3,0.1

Type RM Length L Ch R = 1 ,13625   ,988,988,988
BEGIN DESCRIPTION:
Mapping XS b9bd7a71
END DESCRIPTION:
XS GIS Cut Line= 4
        1580080.        6899213.      1581114.86      6897848.08
      1582268.16      6894651.75        1582330.      6894112.99
#Sta/Elev= 30
  -110.9 1615.98      80 1613.61   195.3 1613.18   299.9  1612.5     414 1611.62
   655.9 1610.13   938.1 1608.74  1442.8 1607.89  1482.1 1607.36  1594.9 1602.71
  1678.9  1605.7  2017.8 1606.78  2271.2  1606.9  2843.1 1606.78  3009.4 1606.38
  4748.8 1607.72  4951.3 1603.46  4982.7 1594.07  4993.4 1600.48  5004.4 1602.52
  5064.2 1630.61  5094.4 1637.82  5195.8 1628.38  5245.4 1641.45  5305.7 1641.17
    5364 1629.48  5376.2 1624.21  5406.4 1628.59  5458.2 1643.27  5542.3  1646.3
#Mann= 15 ,-1 , 0
  -110.9     .07       0      80     .05       0   195.3     .07       0
   299.9     .05       0     414     .07       0   655.9     .05       0
   938.1     .07       0  1442.8     .05       0  1482.1     .07       0
  2017.8     .05       0  2271.2     .07       0  2843.1    .045       0
  3009.4     .07       0  4951.3    .045       0  5004.4     .07       0
Bank Sta=4951.3,5004.4
XS Rating Curve= 0 ,0
Exp/Cntr=0.3,0.1

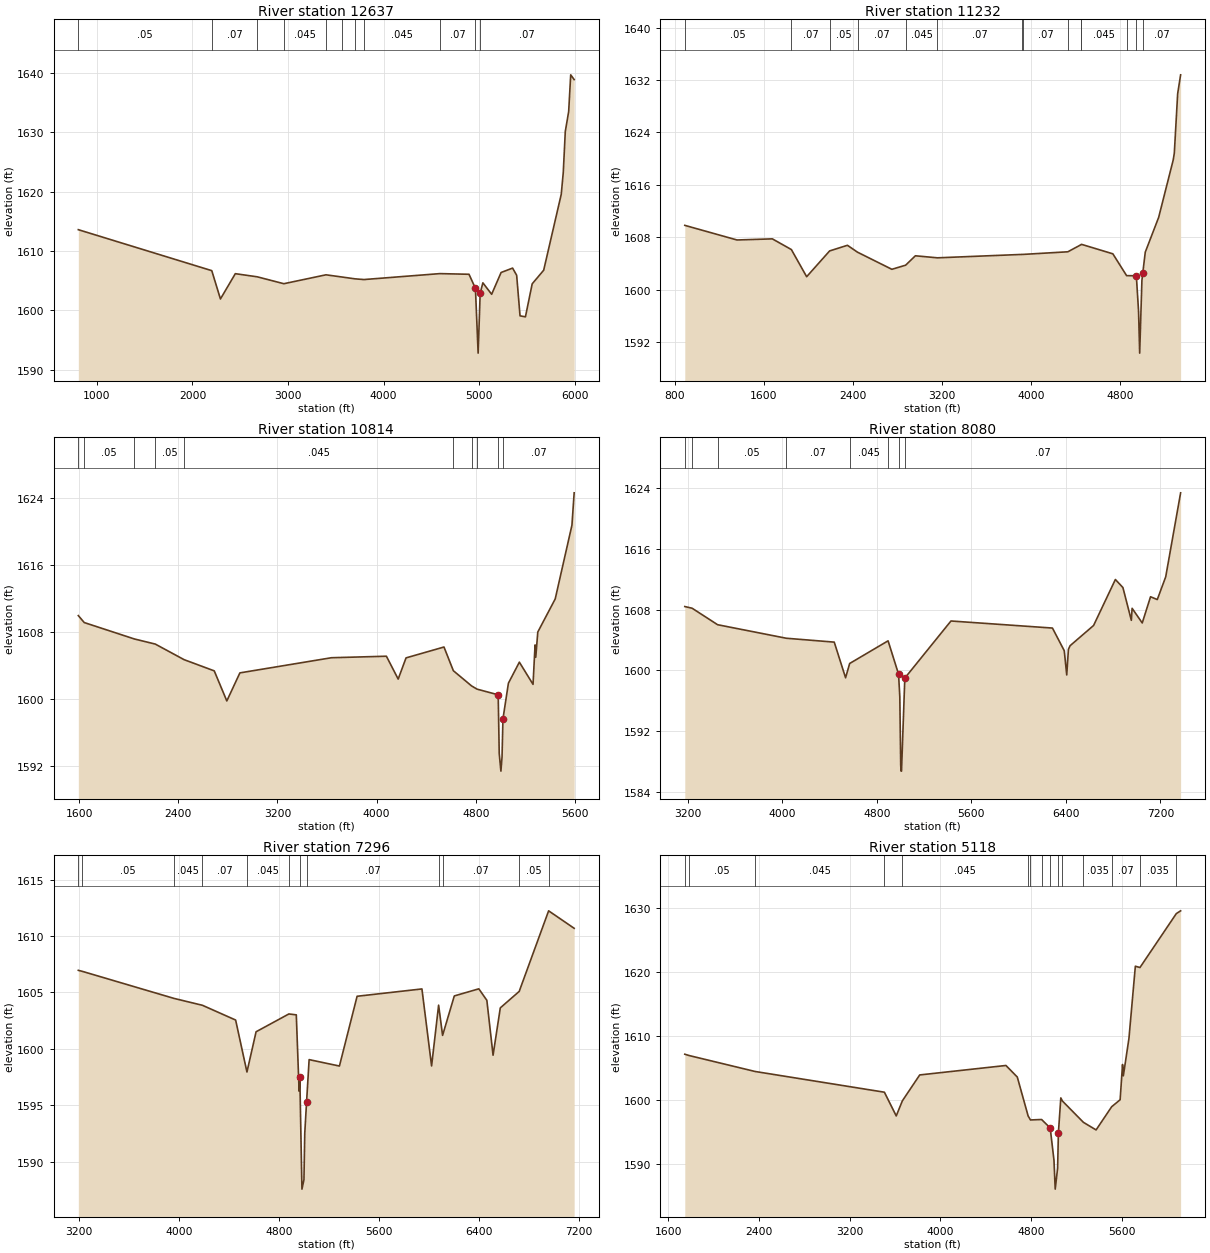
Type RM Length L Ch R = 1 ,12637   ,1405,1405,1405
BEGIN DESCRIPTION:
Mapping XS 9c2e858e
END DESCRIPTION:
XS GIS Cut Line= 3
        1581180.        6899363.      1582618.15      6895472.41
      1583347.35      6894729.32
#Sta/Elev= 30
   805.8 1613.59  2202.3 1606.69  2293.1 1601.92  2448.7 1606.18  2678.8 1605.65
  2956.5 1604.49  3397.9 1605.99    3564 1605.62  3701.7 1605.31  3794.7 1605.19
  4588.9 1606.19  4894.4 1606.08  4961.6 1603.71  4989.9  1592.8  5011.2 1602.89
  5039.5 1604.64  5131.3 1602.71  5230.3 1606.38  5350.6 1607.12  5393.1 1605.91
  5428.4 1599.08  5484.9 1598.91  5555.6 1604.47  5675.8 1606.76  5859.7 1619.55
    5881 1623.25  5902.1 1630.13  5937.5  1633.5  5958.7 1639.67  5994.8 1638.87
#Mann= 11 ,-1 , 0
   805.8     .05       0  2202.3     .07       0  2678.8     .05       0
  2956.5    .045       0  3397.9     .07       0    3564    .045       0
  3701.7     .07       0  3794.7    .045       0  4588.9     .07       0
  4961.6    .045       0  5011.2     .07       0
Bank Sta=4961.6,5011.2
XS Rating Curve= 0 ,0
Exp/Cntr=0.3,0.1

Type RM Length L Ch R = 1 ,11232   ,418,418,418
BEGIN DESCRIPTION:
Mapping XS f281deaf
END DESCRIPTION:
XS GIS Cut Line= 4
      1581974.63      6898986.02       1582211.6      6897928.54
      1583258.08      6895685.98      1583341.29      6894791.56
#Sta/Elev= 30
   890.4 1609.84  1359.8 1607.61  1677.5 1607.78  1848.4 1606.15  1985.7 1602.01
  2192.1 1605.94  2352.1  1606.8  2443.8 1605.74  2751.7 1603.14  2875.5 1603.77
  2962.9  1605.2  3161.5 1604.89  3924.5 1605.41  3930.3 1605.41  4333.4 1605.81
  4449.5 1606.87  4455.4 1606.95    4738  1605.5  4861.7 1602.17    4949 1602.16
    4969 1596.76  4979.1 1590.36  4999.2 1601.46  5006.8 1602.55  5029.3 1605.75
  5149.8 1611.06  5280.4  1619.8  5290.4 1620.85  5320.5 1629.91  5347.1 1632.79
#Mann= 14 ,-1 , 0
   890.4     .05       0  1848.4     .07       0  2192.1     .05       0
  2443.8     .07       0  2875.5    .045       0  3161.5     .07       0
  3924.5    .045       0  3930.3     .07       0  4333.4    .045       0
  4449.5     .07       0  4455.4    .045       0  4861.7     .07       0
    4949    .045       0  5006.8     .07       0
Bank Sta=4949,5006.8
XS Rating Curve= 0 ,0
Exp/Cntr=0.3,0.1

Type RM Length L Ch R = 1 ,10814   ,2734,2734,2734
BEGIN DESCRIPTION:
Mapping XS 7e79ff9c
END DESCRIPTION:
XS GIS Cut Line= 3
      1582630.01      6898512.98      1583702.53      6895331.82
       1583404.1      6894762.72
#Sta/Elev= 30
  1593.4 1609.98  1641.1 1609.15  2045.5 1607.19  2214.1 1606.58  2446.5 1604.72
  2689.9 1603.38  2791.2 1599.79  2896.7 1603.14  3635.4 1604.95  4078.6 1605.13
  4173.6  1602.4  4236.9 1604.93    4543 1606.23  4618.6  1603.4  4765.9 1601.58
  4809.8  1601.2  4980.3 1600.52  4988.7 1593.51  5002.3 1591.41  5011.3  1593.1
  5018.7 1597.64  5062.8 1601.91  5151.1 1604.42  5261.4 1601.77  5277.8 1606.48
  5283.4 1605.01  5299.8 1608.02  5440.3 1611.97  5575.3 1620.78  5593.1 1624.64
#Mann= 10 ,-1 , 0
  1593.4     .07       0  1641.1     .05       0  2045.5     .07       0
  2214.1     .05       0  2446.5    .045       0  4618.6     .07       0
  4765.9    .045       0  4809.8     .07       0  4980.3    .045       0
  5018.7     .07       0
Bank Sta=4980.3,5018.7
XS Rating Curve= 0 ,0
Exp/Cntr=0.3,0.1

Type RM Length L Ch R = 1 ,8080    ,784,784,784
BEGIN DESCRIPTION:
Mapping XS 76eb4e4d
END DESCRIPTION:
XS GIS Cut Line= 5
        1583180.        6898263.      1583820.58       6896547.1
      1584167.81      6896144.32      1584306.69      6895491.54
      1583418.92      6894735.54
#Sta/Elev= 30
    3174 1608.39  3235.8 1608.17  3451.8    1606  4033.4 1604.22  4438.9 1603.71
  4534.9 1599.02  4569.5  1600.9  4894.7 1603.88  4983.3  1599.5  4993.9 1596.54
  5001.6 1587.46  5004.7 1586.74  5008.3 1586.74  5036.3 1598.98  5426.9 1606.49
    6286 1605.56  6385.9 1602.58  6406.8 1599.39  6421.1 1602.76  6435.3 1603.24
  6634.1  1605.9  6818.6 1611.95  6882.3 1610.89  6953.7 1606.58  6960.2 1608.16
  7045.9 1606.23  7116.2 1609.68  7173.3 1609.31  7244.6  1612.3  7370.8 1623.35
#Mann= 8 ,-1 , 0
    3174     .07       0  3235.8     .05       0  3451.8     .05       0
  4033.4     .07       0  4569.5    .045       0  4894.7     .07       0
  4983.3    .045       0  5036.3     .07       0
Bank Sta=4983.3,5036.3
XS Rating Curve= 0 ,0
Exp/Cntr=0.3,0.1

Type RM Length L Ch R = 1 ,7296    ,2178,2178,2178
BEGIN DESCRIPTION:
Mapping XS 2fcd55cb
END DESCRIPTION:
XS GIS Cut Line= 4
      1583730.02      6898412.97      1584521.97      6896777.13
      1584333.39      6895460.51      1583829.99      6894812.99
#Sta/Elev= 30
    3195 1606.96  3226.9 1606.87  3960.6 1604.47    4188 1603.86  4453.8 1602.55
  4544.3 1597.94  4617.4 1601.51  4879.8 1603.09  4939.2 1603.01  4961.8 1596.24
  4967.3 1597.52  4984.4 1587.55  5000.4 1588.38  5006.9  1592.5  5021.5 1595.29
  5041.9 1599.04  5284.3 1598.47  5425.8 1604.66  5944.6 1605.31  6021.8 1598.48
  6078.1 1603.87  6109.9 1601.19  6203.6 1604.69  6399.8 1605.32  6464.1  1604.3
  6513.8 1599.43  6571.7 1603.63  6722.9 1605.09  6958.4 1612.24  7162.7 1610.69
#Mann= 12 ,-1 , 0
    3195     .05       0  3226.9     .05       0  3960.6    .045       0
    4188     .07       0  4544.3    .045       0  4879.8     .07       0
  4967.3    .045       0  5021.5     .07       0  6078.1     .05       0
  6109.9     .07       0  6722.9     .05       0  6958.4     .07       0
Bank Sta=4967.3,5021.5
XS Rating Curve= 0 ,0
Exp/Cntr=0.3,0.1

Type RM Length L Ch R = 1 ,5118    ,1491,1491,1491
BEGIN DESCRIPTION:
Mapping XS a7d147a3
END DESCRIPTION:
XS GIS Cut Line= 5
      1583780.01      6898462.99      1584994.81      6897037.55
      1584952.05      6896123.35      1584974.89      6895658.28
      1585760.69      6894858.95
#Sta/Elev= 30
  1746.3 1607.18  1785.7 1606.97  2366.9 1604.48  3507.3 1601.24  3611.9 1597.53
  3665.6 1599.88  3818.9 1603.94  4579.8 1605.42  4679.9 1603.61  4775.4 1597.53
  4796.3  1596.9  4894.2 1596.97  4970.2 1595.65  5003.6 1590.58  5014.4 1586.08
  5035.6 1589.35  5042.6 1594.93  5063.9 1600.35  5078.1 1599.86  5263.1 1596.53
  5375.1 1595.34  5512.6 1598.97  5587.2 1600.06  5608.4 1605.57  5615.5  1603.8
    5665 1609.66  5721.5 1620.95    5762 1620.74  6083.1 1629.18  6120.9 1629.61
#Mann= 15 ,-1 , 0
  1746.3    .035       0  1785.7     .05       0  2366.9    .045       0
  3507.3     .07       0  3665.6    .045       0  4775.4     .07       0
  4796.3    .045       0  4894.2    .035       0  4970.2    .045       0
  5042.6     .05       0  5078.1    .035       0  5263.1    .035       0
  5512.6     .07       0    5762    .035       0  6083.1     .07       0
Bank Sta=4970.2,5042.6
XS Rating Curve= 0 ,0
Exp/Cntr=0.3,0.1

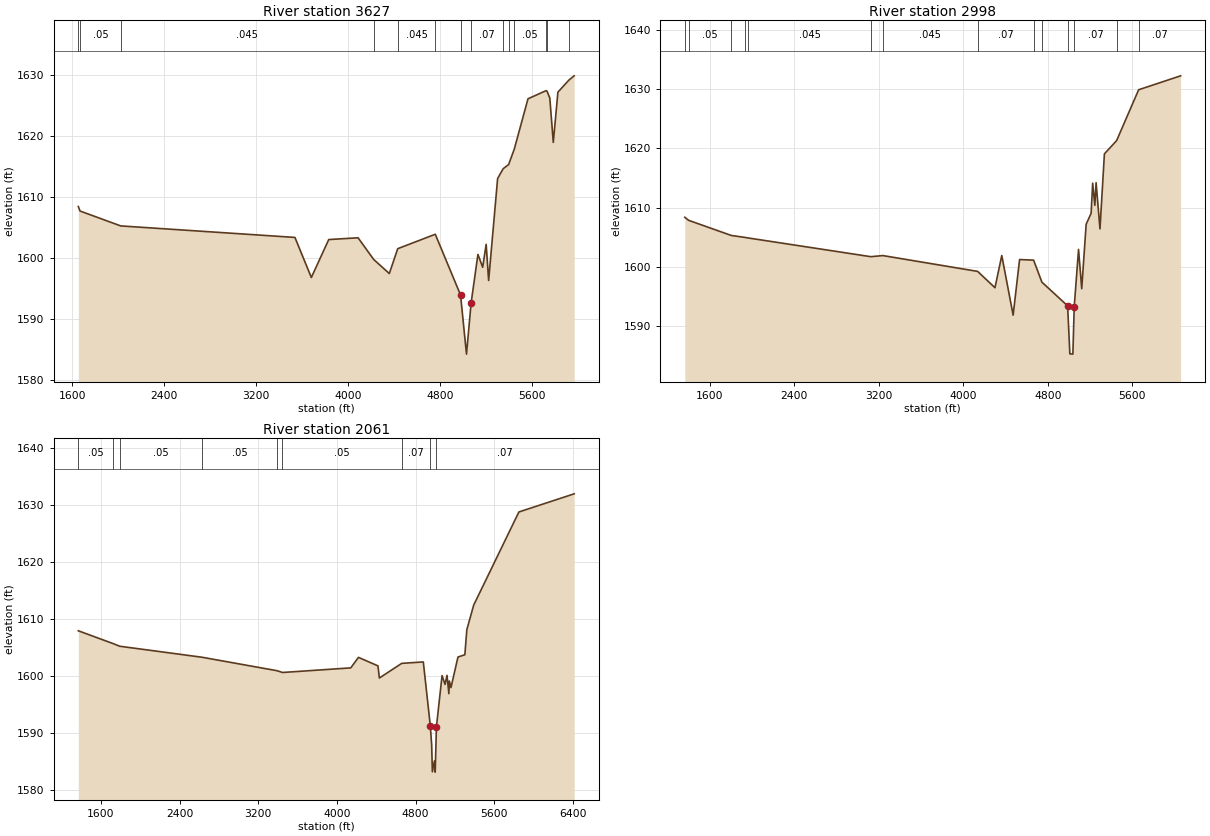
Type RM Length L Ch R = 1 ,3627    ,629,629,629
BEGIN DESCRIPTION:
Mapping XS aaf2c915
END DESCRIPTION:
XS GIS Cut Line= 4
      1584042.06      6898721.55      1585415.39      6896777.92
      1585794.36      6895888.55      1585907.27      6894927.67
#Sta/Elev= 30
  1653.4 1608.46  1667.7 1607.72  2021.9 1605.27    3538 1603.38  3680.8  1596.8
  3832.2 1603.03  4087.5 1603.32  4223.4 1599.76  4359.3 1597.45  4432.3 1601.53
  4759.3  1603.9  4978.9 1593.93  5030.8 1584.22    5071 1592.62  5130.2 1600.59
  5171.7 1598.48  5201.9 1602.25  5223.4 1596.31  5301.5 1613.04  5349.8 1614.66
  5397.3 1615.34  5446.8 1617.89  5565.9 1626.14  5723.8 1627.48  5732.1 1627.37
  5755.7 1626.26  5785.9 1618.98  5826.2 1627.23  5922.2 1629.22  5967.5 1629.91
#Mann= 14 ,-1 , 0
  1653.4     .05       0  1667.7     .05       0  2021.9    .045       0
  4223.4     .07       0  4432.3    .045       0  4759.3     .07       0
  4978.9    .045       0    5071     .07       0  5349.8     .05       0
  5397.3     .07       0  5446.8     .05       0  5723.8     .07       0
  5732.1     .05       0  5922.2     .07       0
Bank Sta=4978.9,5071
XS Rating Curve= 0 ,0
Exp/Cntr=0.3,0.1

Type RM Length L Ch R = 1 ,2998    ,937,937,937
BEGIN DESCRIPTION:
Mapping XS 5fb5b824
END DESCRIPTION:
XS GIS Cut Line= 4
      1584434.06       6899084.1      1585991.77      6896997.41
      1586370.48      6896036.96      1586618.32       6895008.5
#Sta/Elev= 30
  1363.6 1608.37  1400.4 1607.85  1803.8  1605.3  1937.5 1604.96  1962.9 1604.88
  3125.6 1601.72  3238.8 1601.91  4136.3 1599.24  4300.2 1596.49  4364.7 1601.92
  4472.2 1591.87  4533.3 1601.24    4666 1601.14  4744.5 1597.43  4988.1 1593.43
  5009.2 1585.35  5037.8 1585.29  5050.4 1593.24  5091.5 1602.95  5121.6 1596.33
  5163.5 1607.19  5210.6 1609.05  5225.2 1614.12  5245.8 1610.38  5257.6  1614.2
  5294.4 1606.41  5336.3 1619.06  5452.1  1621.3  5660.5 1629.87  6057.9 1632.22
#Mann= 14 ,-1 , 0
  1363.6     .05       0  1400.4     .05       0  1803.8    .045       0
  1937.5     .05       0  1962.9    .045       0  3125.6     .07       0
  3238.8    .045       0  4136.3     .07       0    4666    .045       0
  4744.5     .07       0  4988.1    .045       0  5050.4     .07       0
  5452.1     .05       0  5660.5     .07       0
Bank Sta=4988.1,5050.4
XS Rating Curve= 0 ,0
Exp/Cntr=0.3,0.1

Type RM Length L Ch R = 1 ,2061    ,0,0,0
BEGIN DESCRIPTION:
MULBERRY CREEK 1.0
END DESCRIPTION:
XS GIS Cut Line= 5
      1584536.33      6899175.59      1586759.42      6896609.13
      1586766.78      6896376.16      1586708.87      6895891.16
       1586901.9      6894988.72
#Sta/Elev= 30
  1371.5 1607.93  1721.1 1605.71  1792.6 1605.22  2629.6 1603.29  3392.3 1600.93
  3446.7 1600.62  4140.8 1601.43  4218.7 1603.27  4417.2 1601.78  4431.4 1599.65
  4658.6 1602.22  4878.1 1602.47  4949.1  1591.3    4963 1587.93  4970.2 1583.22
  4990.8  1585.1  4998.8 1583.16  5011.4 1591.11  5068.6 1600.07  5098.9 1598.53
    5119 1600.12  5137.8 1596.92  5142.8 1599.13  5159.3 1597.98  5230.3 1603.33
  5300.3 1603.73  5320.4 1608.12  5390.2 1612.43  5849.6 1628.75  6411.3 1631.93
#Mann= 9 ,-1 , 0
  1371.5     .05       0  1721.1     .05       0  1792.6     .05       0
  2629.6     .05       0  3392.3     .07       0  3446.7     .05       0
  4658.6     .07       0  4949.1    .045       0  5011.4     .07       0
Bank Sta=4949.1,5011.4
XS Rating Curve= 0 ,0
Exp/Cntr=0.3,0.1

Chan Stop Cuts=-1
Use User Specified Reach Order=0
Composite Channel Slope=5