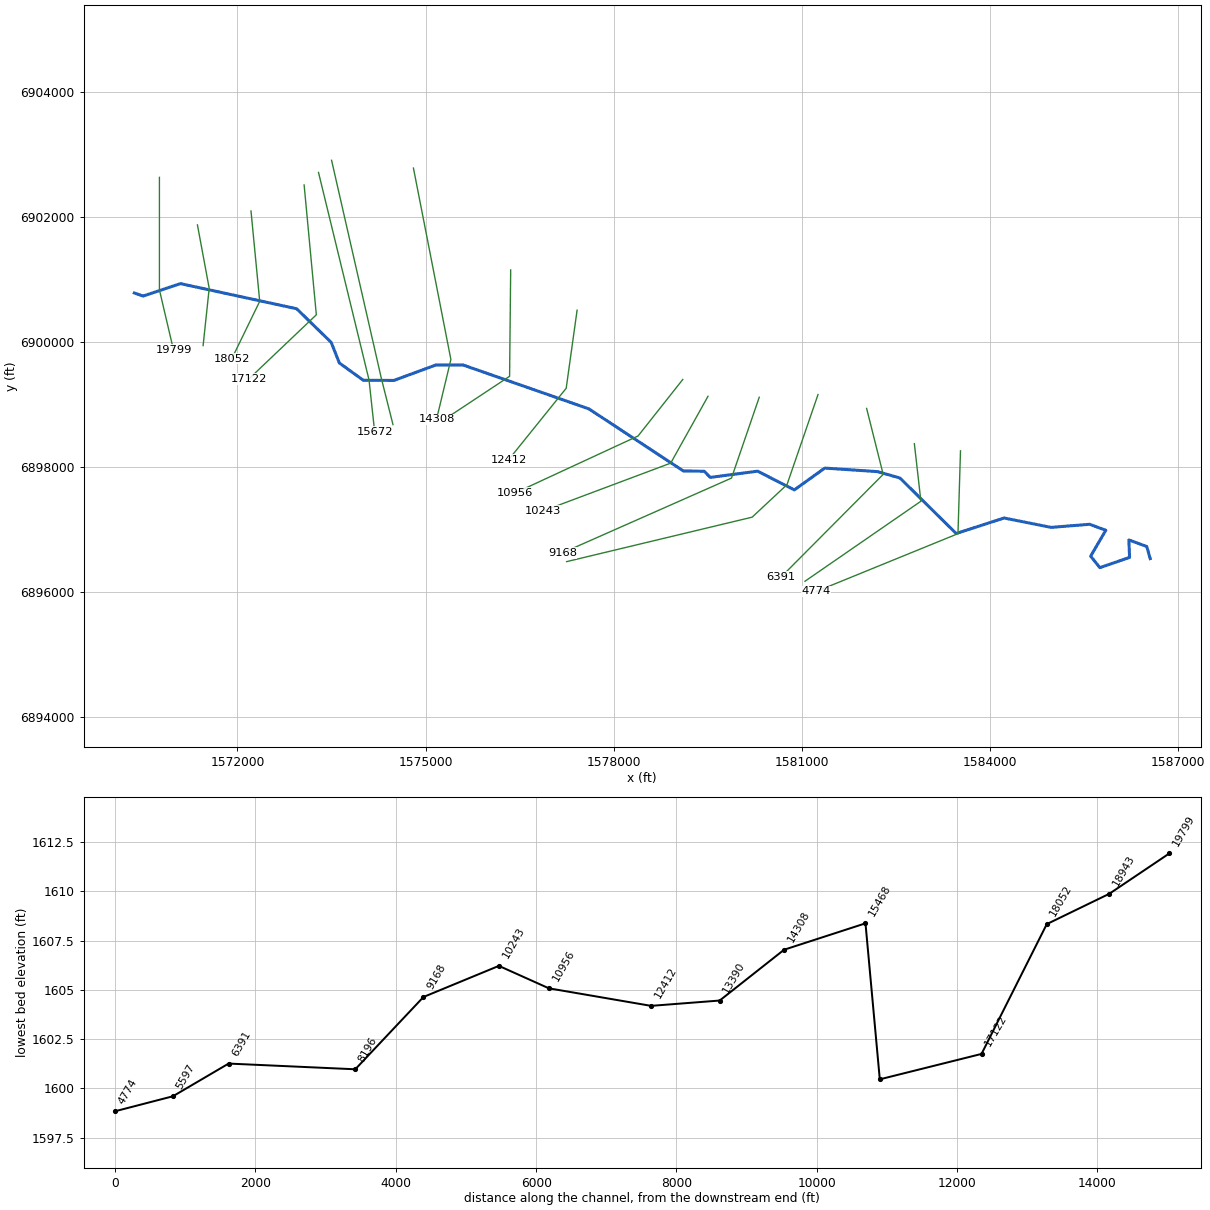
--- MULBERRY CREEK TRIBUTARY 1.prj (project) ---

Proj Title=MULBERRY CREEK TRIBUTARY 1 Base Level Engineering
Current Plan=p01
Default Exp/Contr=0.3,0.1
English Units
Geom File=g01
Flow File=f01
Plan File=p01
BEGIN DESCRIPTION:
MULBERRY CREEK TRIBUTARY 1
END DESCRIPTION:

--- MULBERRY CREEK TRIBUTARY 1.p01 (plan) ---

Plan Title=Multiple Run
Short Identifier=Multiple
Geom File=g01
Flow File=f01
Subcritical Flow
K Sum by GR= 0
Std Step Tol= 0.01
Critical Tol= 0.01
Num of Std Step Trials= 20
Max Error Tol= 0.3
Flow Tol Ratio= 0.001
Split Flow NTrial= 30
Split Flow Tol= 0.02
Split Flow Ratio= 0.02
Log Output Level= 0
Friction Slope Method= 1
Unsteady Friction Slope Method= 2
Unsteady Bridges Friction Slope Method= 1
Parabolic Critical Depth
Global Vel Dist=  1 , 1 , 1
Global Log Level= 0
CheckData=True
Encroach Param= -1, 0, 0, 0
BEGIN DESCRIPTION:
Multiple Run
END DESCRIPTION:

--- MULBERRY CREEK TRIBUTARY 1.f01 (steady flow) ---

Flow Title=Multiple
Number of Profiles=7
Profile Names=10-year,25-year,50-year,1pct_min,100-year,1pct_plu,500-year
River Rch & RM= MULBERRY CREEK T,Reach-1,19799
     268     368     450     273     545    1088     814
River Rch & RM= MULBERRY CREEK T,Reach-1,12412
     350     486     598     366     730    1456    1101
River Rch & RM= MULBERRY CREEK T,Reach-1,6391
     567     803    1002     620    1237    2468    1911
Boundary for River Rch & Prof#=MULBERRY CREEK T,Reach-1,1
Up Type=0
Dn Type=3
Dn Slope=0.005
Boundary for River Rch & Prof#=MULBERRY CREEK T,Reach-1,2
Up Type=0
Dn Type=3
Dn Slope=0.005
Boundary for River Rch & Prof#=MULBERRY CREEK T,Reach-1,3
Up Type=0
Dn Type=3
Dn Slope=0.005
Boundary for River Rch & Prof#=MULBERRY CREEK T,Reach-1,4
Up Type=0
Dn Type=3
Dn Slope=0.005
Boundary for River Rch & Prof#=MULBERRY CREEK T,Reach-1,5
Up Type=0
Dn Type=3
Dn Slope=0.005
Boundary for River Rch & Prof#=MULBERRY CREEK T,Reach-1,6
Up Type=0
Dn Type=3
Dn Slope=0.005
Boundary for River Rch & Prof#=MULBERRY CREEK T,Reach-1,7
Up Type=0
Dn Type=3
Dn Slope=0.005

--- MULBERRY CREEK TRIBUTARY 1.g01 (geometry) ---

Geom Title=Existing Conditions

River Reach=MULBERRY CREEK T,Reach-1
Reach XY= 30
      1570355.00      6900788.00      1570494.47      6900739.07
      1571089.60      6900937.91      1572943.05      6900536.07
      1573494.24      6899997.68      1573624.78      6899667.91
      1574006.55      6899391.75      1574494.50      6899389.22
      1575165.50      6899636.78      1575599.06      6899635.74
      1577603.42      6898934.17      1579110.93      6897940.24
      1579443.17      6897936.36      1579539.74      6897837.49
      1580294.31      6897937.23      1580880.00      6897637.53
      1581365.50      6897986.78      1582208.30      6897929.92
      1582564.79      6897827.48      1583460.86      6896940.05
      1584225.03      6897187.94      1584975.03      6897038.07
      1585589.78      6897087.48      1585847.32      6896991.71
      1585605.50      6896577.50      1585752.57      6896393.40
      1586226.10      6896557.59      1586215.24      6896837.01
      1586500.20      6896732.38      1586555.00      6896538.00

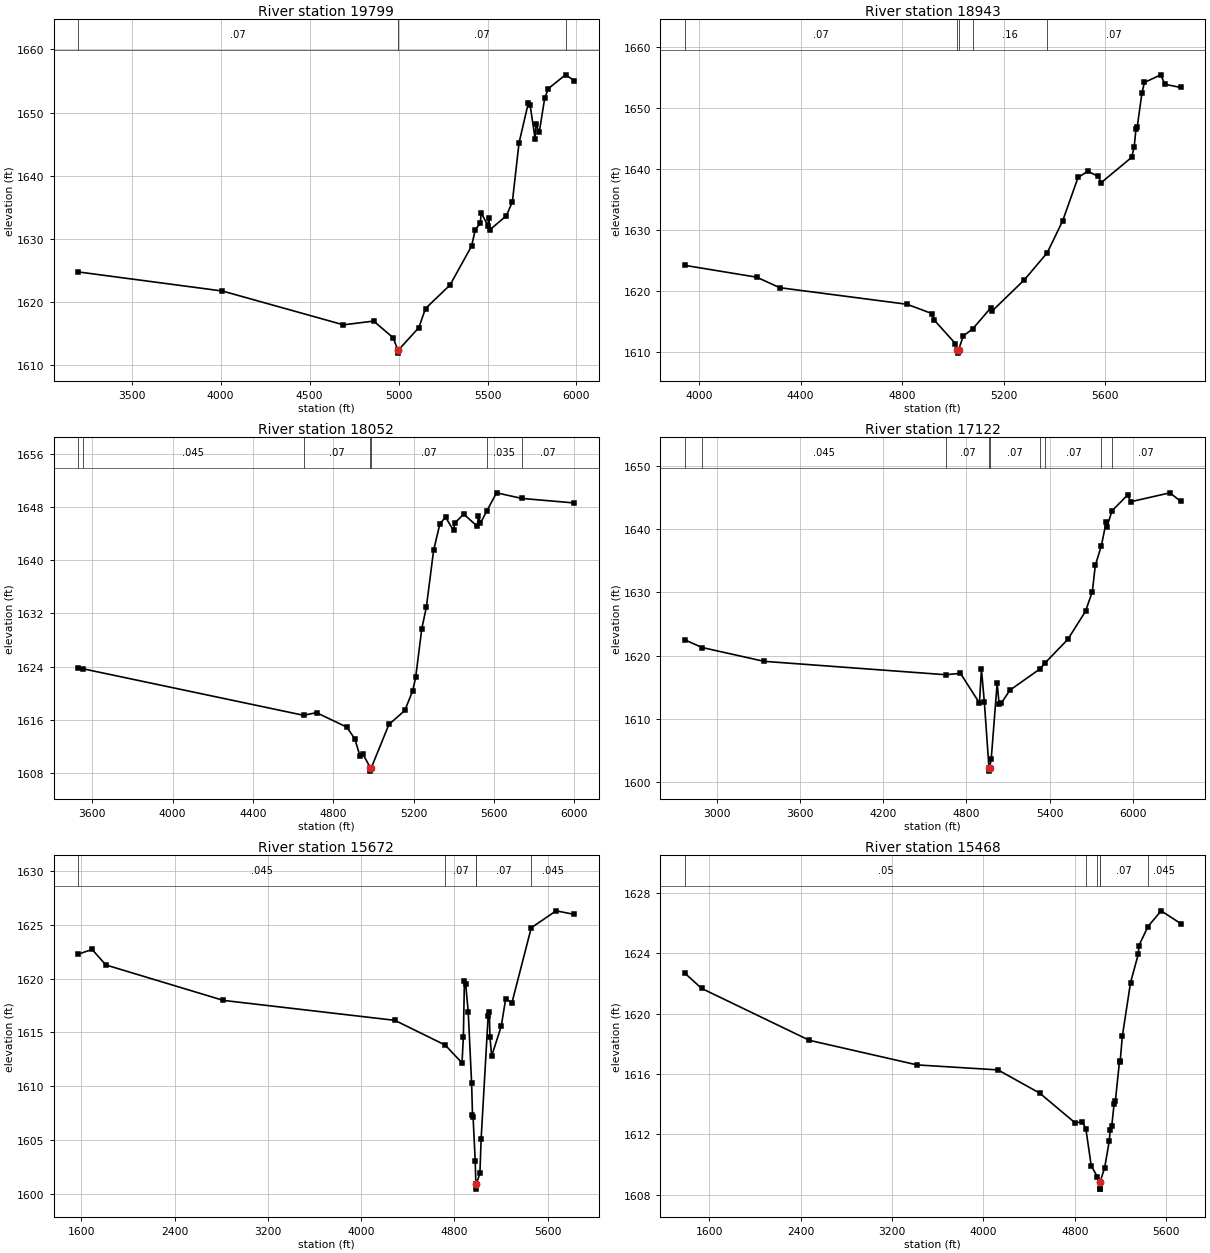
Type RM Length L Ch R = 1,19799,856,856,856
BEGIN DESCRIPTION:
MULBERRY CREEK TRIBUTARY 1 26.0
END DESCRIPTION:
XS GIS Cut Line= 3
      1570755.00      6902637.97      1570755.00      6900838.00
      1570979.42      6899876.82
#Sta/Elev= 30
  3200.1 1624.78  4010.1 1621.76  4690.1 1616.41  4860.1 1617.00  4970.1 1614.36
  4995.4 1612.43  4995.7 1611.93  4999.7 1612.43  5114.1 1615.97  5151.5 1618.99
  5289.3 1622.71  5410.8 1628.89  5431.4 1631.48  5459.5 1632.47  5464.6 1634.14
  5502.0 1632.13  5507.1 1633.32  5513.5 1631.46  5605.9 1633.67  5639.8 1635.88
  5677.2 1645.20  5730.0 1651.59  5739.4 1651.23  5767.4 1645.88  5772.6 1648.15
  5790.8 1646.86  5821.6 1652.30  5842.1 1653.80  5938.6 1655.98  5987.1 1655.08
#Mann=4,-1,0
  3200.1    0.07       0  4995.4    0.07       0  4999.7    0.07       0
  5938.6   0.035       0
Bank Sta=4995.4,4999.7
Exp/Cntr=0.3,0.1

Type RM Length L Ch R = 1,18943,891,891,891
BEGIN DESCRIPTION:
Mapping XS 530bb333
END DESCRIPTION:
XS GIS Cut Line= 3
      1571361.37      6901876.77      1571548.87      6900862.89
      1571451.65      6899946.21
#Sta/Elev= 30
  3943.9 1624.27  4227.4 1622.33  4317.6 1620.61  4819.3 1617.89  4918.9 1616.34
  4925.1 1615.36  5010.1 1611.42  5017.9 1610.38  5018.2 1609.88  5022.3 1610.38
  5040.2 1612.68  5077.9 1613.86  5149.9 1617.34  5154.9 1616.81  5281.6 1621.91
  5371.5 1626.34  5432.4 1631.59  5492.8 1638.68  5530.6 1639.69  5573.2 1638.85
  5583.3 1637.81  5703.9 1641.98  5714.0 1643.73  5720.9 1646.60  5725.9 1646.96
  5744.2 1652.46  5754.2 1654.26  5818.6 1655.51  5834.7 1653.96  5896.8 1653.44
#Mann=5,-1,0
  3943.9    0.07       0  5017.9    0.07       0  5022.3    0.07       0
  5077.9    0.16       0  5371.5    0.07       0
Bank Sta=5017.9,5022.3
Exp/Cntr=0.3,0.1

Type RM Length L Ch R = 1,18052,930,930,930
BEGIN DESCRIPTION:
Mapping XS 28e4b0c3
END DESCRIPTION:
XS GIS Cut Line= 3
      1572215.54      6902098.98      1572354.43      6900654.55
      1571909.99      6899737.91
#Sta/Elev= 30
  3530.1 1623.80  3554.3 1623.69  4651.7 1616.72  4716.5 1617.11  4867.2 1614.95
  4907.4 1613.18  4933.7 1610.54  4947.6 1610.90  4984.9 1608.84  4985.2 1608.34
  4989.4 1608.84  5077.4 1615.35  5156.3 1617.44  5195.9 1620.41  5210.7 1622.47
  5241.0 1629.72  5263.6 1632.93  5299.7 1641.45  5331.3 1645.49  5359.4 1646.44
  5399.0 1644.45  5404.6 1645.54  5449.7 1646.91  5517.5 1645.07  5523.0 1646.59
  5533.0 1645.55  5563.4 1647.30  5613.3 1650.10  5739.6 1649.26  5999.9 1648.58
#Mann=7,-1,0
  3530.1    0.07       0  3554.3   0.045       0  4651.7    0.07       0
  4984.9    0.07       0  4989.4    0.07       0  5563.4   0.035       0
  5739.6    0.07       0
Bank Sta=4984.9,4989.4
Exp/Cntr=0.3,0.1

Type RM Length L Ch R = 1,17122,1450,1450,1450
BEGIN DESCRIPTION:
Mapping XS 8ff14827
END DESCRIPTION:
XS GIS Cut Line= 3
      1573062.76      6902515.66      1573257.21      6900439.28
      1572181.57      6899412.22
#Sta/Elev= 30
  2770.4 1622.49  2895.1 1621.28  3340.5 1619.10  4650.4 1616.98  4756.7 1617.20
  4893.7 1612.50  4907.9 1617.85  4928.9 1612.63  4962.2 1602.25  4962.5 1601.75
  4966.8 1602.25  4978.6 1603.73  5021.1 1615.65  5035.2 1612.34  5049.4 1612.44
  5112.9 1614.54  5328.5 1617.88  5368.5 1618.89  5530.3 1622.57  5657.7 1627.00
  5707.0 1630.12  5728.4 1634.25  5772.2 1637.39  5806.1 1641.04  5813.0 1640.39
  5848.5 1642.87  5961.8 1645.40  5982.9 1644.31  6265.9 1645.72  6343.1 1644.38
#Mann=9,-1,0
  2770.4    0.07       0  2895.1   0.045       0  4650.4    0.07       0
  4962.2    0.07       0  4966.8    0.07       0  5328.5    0.16       0
  5368.5    0.07       0  5772.2   0.035       0  5848.5    0.07       0
Bank Sta=4962.2,4966.8
Exp/Cntr=0.3,0.1

Type RM Length L Ch R = 1,15672,204,204,204
BEGIN DESCRIPTION:
Mapping XS 447db906
END DESCRIPTION:
XS GIS Cut Line= 3
      1573291.92      6902717.08      1574097.49      6899397.61
      1574187.76      6898564.31
#Sta/Elev= 30
  1574.4 1622.26  1692.6 1622.70  1810.1 1621.26  2818.6 1617.97  4290.1 1616.12
  4722.6 1613.82  4866.3 1612.17  4877.7 1614.55  4886.9 1619.81  4897.2 1619.53
  4919.5 1616.91  4948.7 1610.27  4956.1 1607.35  4961.3 1607.14  4979.5 1603.07
  4985.0 1600.96  4985.3 1600.46  4989.9 1600.96  5020.0 1601.94  5030.1 1605.09
  5090.4 1616.50  5100.5 1616.89  5106.0 1614.58  5120.6 1612.81  5202.7 1615.57
  5241.3 1618.14  5294.4 1617.74  5460.3 1624.71  5673.8 1626.28  5828.4 1625.95
#Mann=5,-1,0
  1574.4   0.045       0  4722.6    0.07       0  4985.0    0.07       0
  4989.9    0.07       0  5460.3   0.045       0
Bank Sta=4985,4989.9
Exp/Cntr=0.3,0.1

Type RM Length L Ch R = 1,15468,1160,1160,1160
BEGIN DESCRIPTION:
Mapping XS 431ef90b
END DESCRIPTION:
XS GIS Cut Line= 3
      1573500.26      6902911.50      1574291.93      6899432.33
      1574479.34      6898682.71
#Sta/Elev= 30
  1386.2 1622.69  1533.4 1621.68  2476.9 1618.24  3420.4 1616.61  4128.0 1616.28
  4493.5 1614.74  4804.9 1612.76  4866.4 1612.85  4897.6 1612.37  4944.5 1609.92
  4997.5 1609.21  5018.1 1608.88  5018.5 1608.38  5022.7 1608.38  5023.1 1608.88
  5061.8 1609.79  5103.1 1611.60  5109.7 1612.29  5123.7 1612.53  5144.3 1614.01
  5156.1 1614.24  5192.2 1616.88  5197.4 1616.80  5216.5 1618.50  5288.6 1622.07
  5357.1 1623.97  5362.3 1624.52  5440.9 1625.78  5556.6 1626.82  5727.0 1625.98
#Mann=6,-1,0
  1386.2    0.05       0  4897.6   0.045       0  4997.5    0.07       0
  5018.1    0.07       0  5023.1    0.07       0  5440.9   0.045       0
Bank Sta=5018.1,5023.1
Exp/Cntr=0.3,0.1

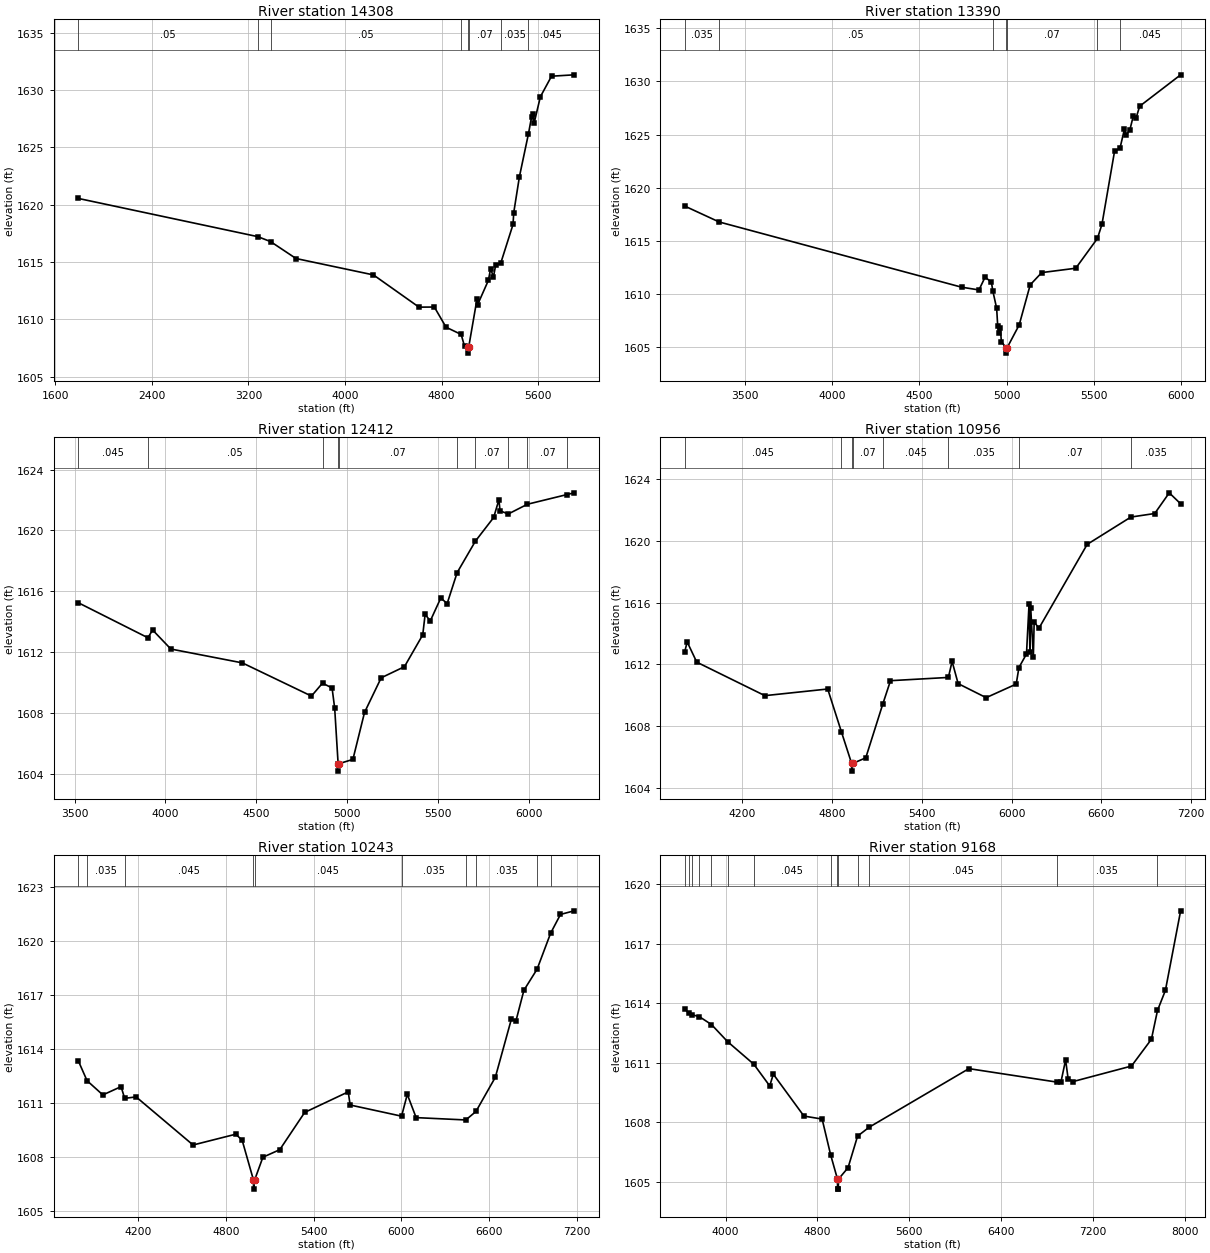
Type RM Length L Ch R = 1,14308,918,918,918
BEGIN DESCRIPTION:
Mapping XS de3dee74
END DESCRIPTION:
XS GIS Cut Line= 3
      1574805.82      6902786.49      1575403.04      6899724.00
      1575173.88      6898765.70
#Sta/Elev= 30
  1791.4 1620.53  3276.7 1617.20  3382.7 1616.77  3593.9 1615.29  4235.1 1613.86
  4612.0 1611.05  4739.2 1611.06  4836.2 1609.30  4961.2 1608.67  4989.7 1607.62
  5017.8 1607.54  5018.2 1607.04  5023.3 1607.54  5092.0 1611.73  5097.2 1611.26
  5186.4 1613.38  5205.6 1614.41  5228.5 1613.67  5246.8 1614.71  5288.2 1614.86
  5390.7 1618.26  5396.7 1619.30  5443.9 1622.44  5518.5 1626.17  5544.9 1627.67
  5555.2 1627.89  5565.0 1627.09  5617.3 1629.40  5709.5 1631.19  5896.9 1631.31
#Mann=8,-1,0
  1791.4    0.05       0  3276.7   0.035       0  3382.7    0.05       0
  4961.2    0.07       0  5017.8    0.07       0  5023.3    0.07       0
  5288.2   0.035       0  5518.5   0.045       0
Bank Sta=5017.8,5023.3
Exp/Cntr=0.3,0.1

Type RM Length L Ch R = 1,13390,978,978,978
BEGIN DESCRIPTION:
Mapping XS fac18032
END DESCRIPTION:
XS GIS Cut Line= 3
      1576356.60      6901156.28      1576339.24      6899454.90
      1575385.68      6898822.09
#Sta/Elev= 30
  3152.9 1618.28  3350.0 1616.79  4741.3 1610.66  4841.3 1610.40  4876.7 1611.61
  4912.8 1611.12  4920.8 1610.31  4942.9 1608.67  4948.9 1607.01  4955.5 1606.37
  4963.9 1606.85  4969.9 1605.55  4997.2 1604.96  4997.6 1604.46  5002.8 1604.96
  5072.2 1607.11  5135.5 1610.88  5201.5 1612.03  5396.9 1612.44  5521.3 1615.24
  5547.3 1616.57  5619.5 1623.43  5650.7 1623.72  5676.6 1625.53  5685.6 1624.99
  5706.7 1625.40  5727.7 1626.78  5742.8 1626.55  5763.8 1627.67  5998.8 1630.62
#Mann=7,-1,0
  3152.9   0.035       0  3350.0    0.05       0  4920.8    0.07       0
  4997.2    0.07       0  5002.8    0.07       0  5521.3   0.035       0
  5650.7   0.045       0
Bank Sta=4997.2,5002.8
Exp/Cntr=0.3,0.1

Type RM Length L Ch R = 1,12412,1456,1456,1456
BEGIN DESCRIPTION:
Mapping XS 5c440d8a
END DESCRIPTION:
XS GIS Cut Line= 3
      1577415.77      6900512.39      1577242.02      6899263.93
      1576321.91      6898118.13
#Sta/Elev= 30
  3520.4 1615.25  3903.5 1612.95  3929.4 1613.46  4029.7 1612.21  4423.4 1611.30
  4803.9 1609.12  4864.8 1609.97  4917.5 1609.65  4931.9 1608.32  4950.7 1604.69
  4951.2 1604.19  4957.9 1604.69  5032.2 1604.96  5096.3 1608.05  5187.9 1610.32
  5315.9 1611.05  5416.7 1613.14  5429.8 1614.48  5458.4 1614.06  5516.0 1615.56
  5551.2 1615.20  5606.1 1617.23  5706.9 1619.30  5807.2 1620.85  5836.0 1622.01
  5842.4 1621.29  5887.5 1621.08  5992.9 1621.72  6212.3 1622.36  6250.4 1622.47
#Mann=10,-1,0
  3520.4   0.045       0  3903.5    0.05       0  4864.8    0.07       0
  4950.7    0.07       0  4957.9    0.07       0  5606.1   0.035       0
  5706.9    0.07       0  5887.5   0.035       0  5992.9    0.07       0
  6212.3   0.035       0
Bank Sta=4950.7,4957.9
Exp/Cntr=0.3,0.1

Type RM Length L Ch R = 1,10956,713,713,713
BEGIN DESCRIPTION:
Mapping XS 551328fa
END DESCRIPTION:
XS GIS Cut Line= 3
      1579100.93      6899404.07      1578387.85      6898500.04
      1576426.05      6897588.59
#Sta/Elev= 30
  3815.0 1612.83  3830.9 1613.45  3895.0 1612.14  4350.3 1609.97  4770.4 1610.40
  4862.5 1607.61  4930.2 1605.58  4930.7 1605.08  4937.6 1605.58  5024.7 1605.94
  5137.7 1609.40  5190.1 1610.94  5577.0 1611.15  5601.9 1612.19  5642.2 1610.75
  5829.6 1609.84  6030.5 1610.72  6048.6 1611.79  6099.2 1612.67  6116.3 1615.90
  6122.1 1612.80  6127.6 1615.64  6145.0 1612.46  6150.5 1614.74  6182.5 1614.34
  6504.9 1619.77  6797.1 1621.54  6956.4 1621.77  7053.6 1623.11  7129.6 1622.40
#Mann=8,-1,0
  3815.0   0.045       0  4862.5    0.07       0  4930.2    0.07       0
  4937.6    0.07       0  5137.7   0.045       0  5577.0   0.035       0
  6048.6    0.07       0  6797.1   0.035       0
Bank Sta=4930.2,4937.6
Exp/Cntr=0.3,0.1

Type RM Length L Ch R = 1,10243,1075,1075,1075
BEGIN DESCRIPTION:
Mapping XS 516405bc
END DESCRIPTION:
XS GIS Cut Line= 3
      1579503.75      6899135.91      1578908.68      6898066.01
      1576877.42      6897302.12
#Sta/Elev= 30
  3788.4 1613.34  3848.1 1612.24  3956.3 1611.45  4081.0 1611.91  4105.5 1611.26
  4183.9 1611.34  4573.9 1608.67  4866.6 1609.27  4910.1 1608.93  4987.5 1606.72
  4988.0 1606.22  4995.0 1606.72  5051.8 1607.99  5167.4 1608.41  5338.1 1610.48
  5636.2 1611.62  5649.2 1610.89  6001.2 1610.27  6040.4 1611.48  6100.9 1610.19
  6440.8 1610.06  6510.4 1610.53  6643.2 1612.43  6753.4 1615.67  6783.7 1615.54
  6838.8 1617.26  6929.0 1618.43  7021.8 1620.43  7089.2 1621.47  7182.8 1621.67
#Mann=10,-1,0
  3788.4   0.045       0  3848.1   0.035       0  4105.5   0.045       0
  4987.5   0.045       0  4995.0   0.045       0  6001.2   0.035       0
  6440.8    0.07       0  6510.4   0.035       0  6929.0    0.07       0
  7021.8   0.035       0
Bank Sta=4987.5,4995
Exp/Cntr=0.3,0.1

Type RM Length L Ch R = 1,9168,972,972,972
BEGIN DESCRIPTION:
Mapping XS 2fdc5e07
END DESCRIPTION:
XS GIS Cut Line= 3
      1580320.57      6899119.95      1579877.87      6897826.57
      1577179.07      6896629.04
#Sta/Elev= 30
  3644.8 1613.71  3681.1 1613.49  3704.2 1613.43  3771.3 1613.33  3877.4 1612.93
  4017.6 1612.07  4246.3 1610.93  4384.6 1609.84  4415.9 1610.43  4682.7 1608.32
  4841.2 1608.17  4915.7 1606.36  4975.1 1605.14  4975.6 1604.64  4982.6 1604.64
  4983.1 1605.14  5067.1 1605.72  5150.0 1607.31  5251.3 1607.76  6119.9 1610.71
  6888.6 1610.03  6921.6 1610.03  6962.4 1611.15  6984.2 1610.20  7028.0 1610.06
  7536.1 1610.84  7709.9 1612.19  7762.9 1613.64  7831.7 1614.65  7964.4 1618.66
#Mann=14,-1,0
  3644.8   0.035       0  3681.1    0.07       0  3704.2   0.035       0
  3771.3    0.07       0  3877.4   0.035       0  4017.6    0.07       0
  4246.3   0.045       0  4915.7    0.07       0  4975.1    0.07       0
  4983.1    0.07       0  5150.0   0.035       0  5251.3   0.045       0
  6888.6   0.035       0  7762.9    0.07       0
Bank Sta=4975.1,4983.1
Exp/Cntr=0.3,0.1

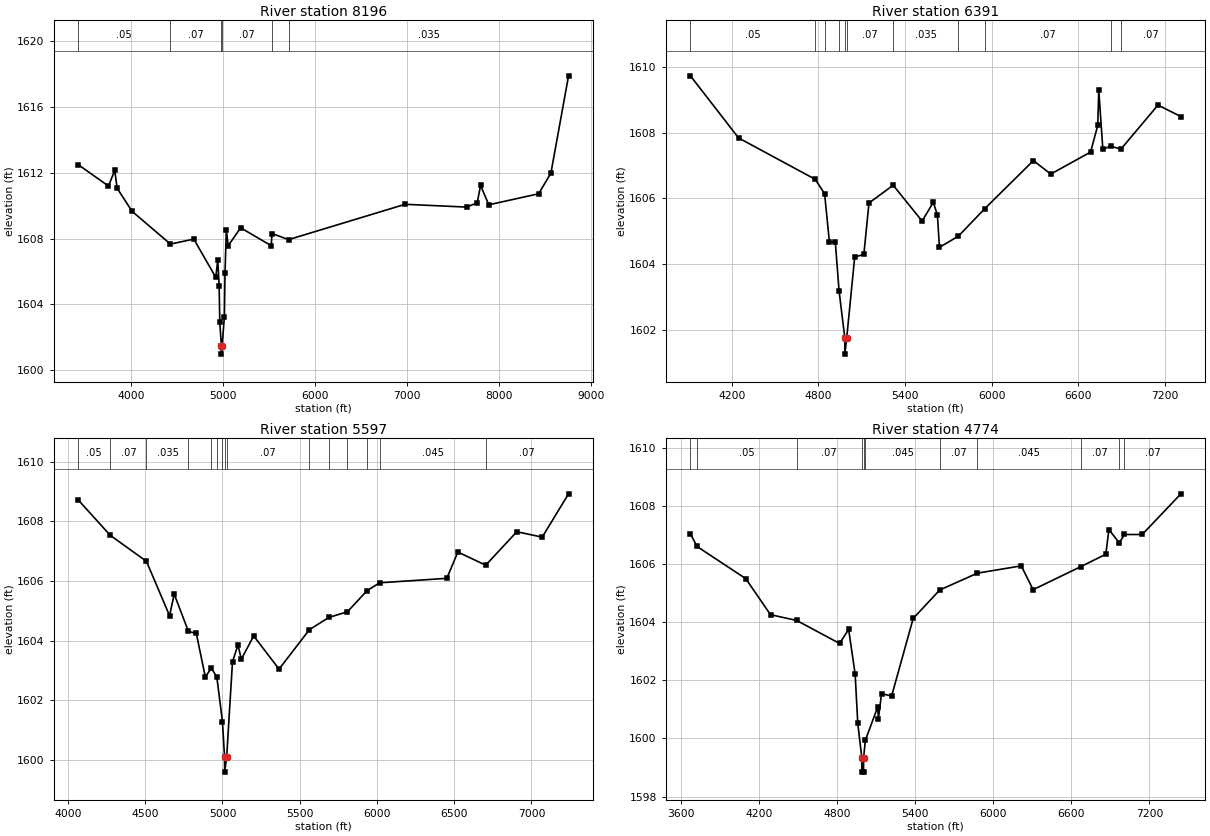
Type RM Length L Ch R = 1,8196,1805,1805,1805
BEGIN DESCRIPTION:
Mapping XS 383c06f7
END DESCRIPTION:
XS GIS Cut Line= 4
      1581258.08      6899163.39      1580763.28      6897722.41
      1580207.73      6897201.57      1577248.86      6896490.06
#Sta/Elev= 30
  3426.2 1612.51  3756.7 1611.20  3824.5 1612.16  3850.5 1611.07  4013.4 1609.66
  4429.6 1607.67  4683.8 1607.97  4922.7 1605.64  4943.9 1606.72  4958.9 1605.10
  4965.8 1602.91  4983.2 1601.47  4983.7 1600.97  4991.3 1601.47  5015.6 1603.25
  5022.4 1605.88  5036.6 1608.50  5057.6 1607.57  5192.4 1608.66  5524.6 1607.57
  5533.0 1608.31  5713.2 1607.94  6979.2 1610.09  7647.7 1609.92  7762.1 1610.18
  7798.9 1611.24  7887.9 1610.06  8429.4 1610.73  8563.1 1611.99  8754.5 1617.91
#Mann=6,-1,0
  3426.2    0.05       0  4429.6    0.07       0  4983.2    0.07       0
  4991.3    0.07       0  5533.0   0.045       0  5713.2   0.035       0
Bank Sta=4983.2,4991.3
Exp/Cntr=0.3,0.1

Type RM Length L Ch R = 1,6391,794,794,794
BEGIN DESCRIPTION:
Mapping XS a48f9127
END DESCRIPTION:
XS GIS Cut Line= 3
      1582033.00      6898941.42      1582296.90      6897885.84
      1580671.90      6896246.96
#Sta/Elev= 30
  3913.8 1609.73  4247.2 1607.84  4778.1 1606.58  4843.0 1606.14  4876.0 1604.68
  4917.2 1604.66  4943.2 1603.18  4982.6 1601.76  4983.1 1601.26  4996.1 1601.76
  5051.2 1604.21  5114.8 1604.30  5150.2 1605.86  5317.7 1606.40  5517.9 1605.31
  5595.7 1605.88  5623.9 1605.49  5638.1 1604.51  5769.0 1604.85  5952.6 1605.69
  6288.6 1607.15  6408.8 1606.74  6684.6 1607.41  6734.1 1608.22  6741.2 1609.29
  6769.5 1607.49  6822.6 1607.59  6894.7 1607.50  7151.3 1608.84  7309.8 1608.49
#Mann=11,-1,0
  3913.8    0.05       0  4778.1    0.07       0  4843.0    0.05       0
  4943.2    0.07       0  4982.6    0.07       0  4996.1    0.07       0
  5317.7   0.035       0  5769.0   0.045       0  5952.6    0.07       0
  6822.6   0.045       0  6894.7    0.07       0
Bank Sta=4982.6,4996.1
Exp/Cntr=0.3,0.1

Type RM Length L Ch R = 1,5597,823,823,823
BEGIN DESCRIPTION:
Mapping XS 5be17905
END DESCRIPTION:
XS GIS Cut Line= 3
      1582794.30      6898376.40      1582898.46      6897456.30
      1581049.74      6896176.08
#Sta/Elev= 30
  4065.4 1608.72  4273.9 1607.53  4507.9 1606.66  4657.6 1604.84  4687.8 1605.56
  4780.0 1604.31  4830.5 1604.25  4889.0 1602.79  4927.9 1603.08  4963.4 1602.79
  5000.0 1601.29  5013.6 1600.10  5014.1 1599.60  5027.2 1600.10  5065.0 1603.30
  5100.8 1603.86  5121.7 1603.38  5202.1 1604.16  5366.3 1603.05  5562.6 1604.37
  5688.6 1604.78  5808.8 1604.97  5934.6 1605.67  6016.9 1605.94  6452.1 1606.09
  6523.7 1606.97  6703.9 1606.53  6905.3 1607.65  7069.7 1607.47  7240.1 1608.92
#Mann=15,-1,0
  4065.4    0.05       0  4273.9    0.07       0  4507.9   0.035       0
  4780.0   0.045       0  4927.9    0.07       0  4963.4   0.045       0
  5000.0    0.07       0  5013.6   0.045       0  5027.2    0.07       0
  5562.6   0.045       0  5688.6    0.07       0  5808.8   0.045       0
  5934.6    0.07       0  6016.9   0.045       0  6703.9    0.07       0
Bank Sta=5013.6,5027.2
Exp/Cntr=0.3,0.1

Type RM Length L Ch R = 1,4774,0,0,0
BEGIN DESCRIPTION:
MULBERRY CREEK TRIBUTARY 1 2.0
END DESCRIPTION:
XS GIS Cut Line= 3
      1583530.00      6898262.96      1583489.81      6896937.47
      1581230.00      6896013.00
#Sta/Elev= 30
  3673.9 1607.05  3723.9 1606.61  4099.1 1605.50  4289.1 1604.26  4490.7 1604.06
  4819.4 1603.27  4889.4 1603.75  4939.4 1602.21  4959.5 1600.52  4990.2 1599.34
  4990.7 1598.84  5003.7 1598.84  5004.2 1599.34  5018.1 1599.94  5112.6 1601.08
  5118.0 1600.68  5142.1 1601.54  5219.5 1601.46  5385.2 1604.13  5589.3 1605.11
  5879.1 1605.69  6215.3 1605.94  6306.5 1605.12  6671.0 1605.91  6864.8 1606.34
  6888.8 1607.19  6968.1 1606.73  7008.2 1607.02  7144.5 1607.02  7441.6 1608.42
#Mann=11,-1,0
  3673.9   0.035       0  3723.9    0.05       0  4490.7    0.07       0
  4990.2    0.07       0  5004.2    0.07       0  5018.1   0.045       0
  5589.3    0.07       0  5879.1   0.045       0  6671.0    0.07       0
  6968.1    0.16       0  7008.2    0.07       0
Bank Sta=4990.2,5004.2
Exp/Cntr=0.3,0.1

Chan Stop Cuts=-1