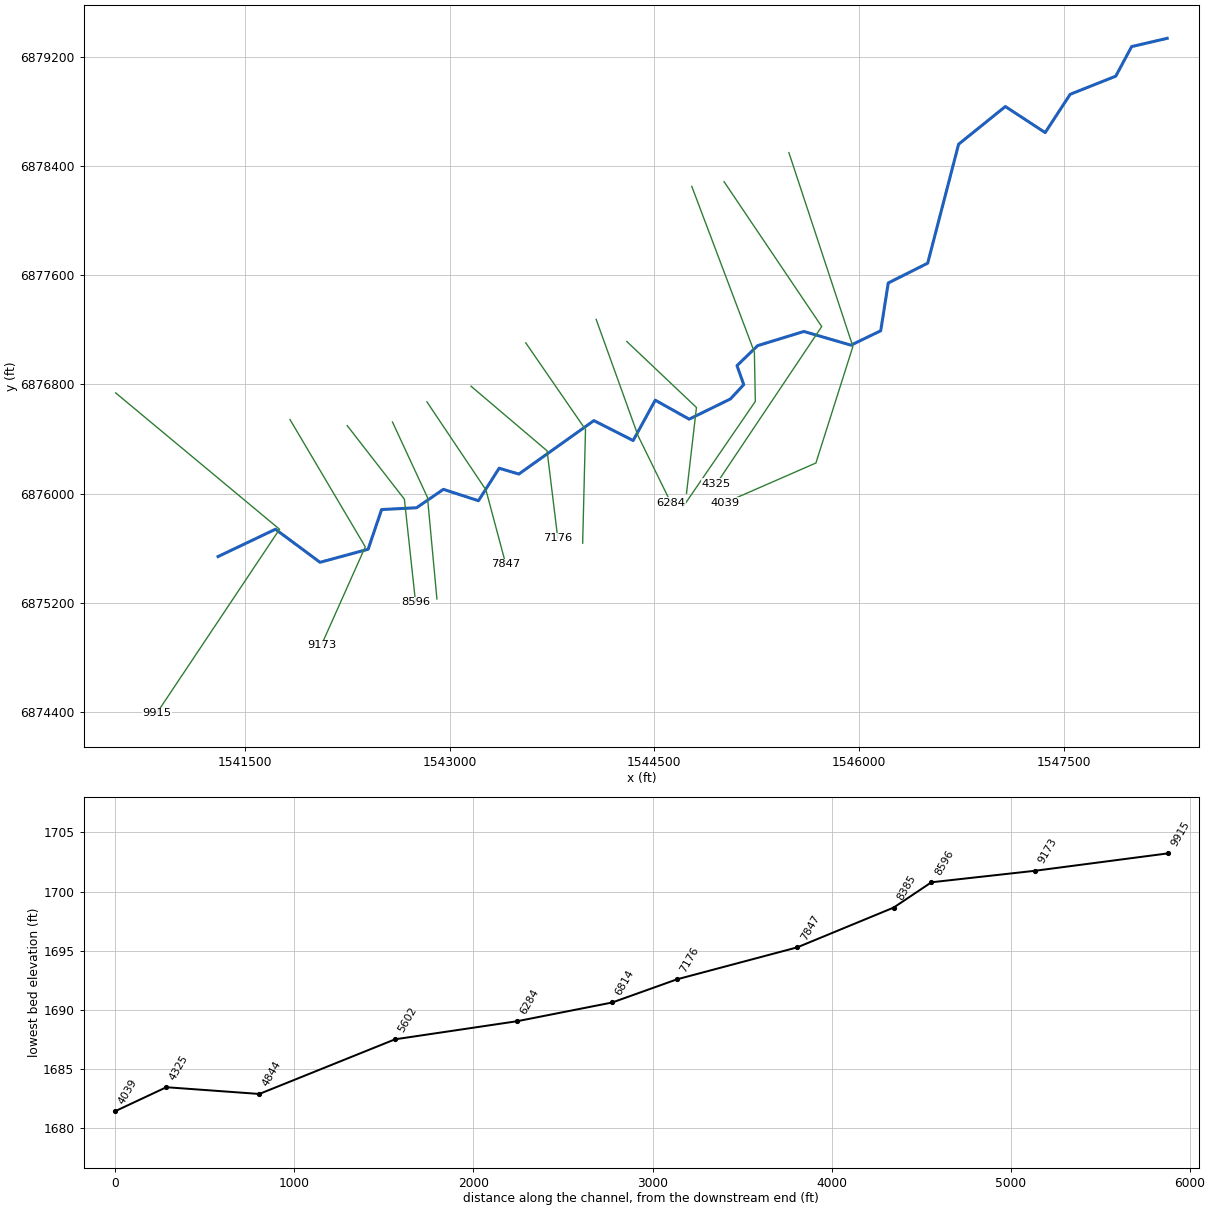
--- MULBERRY CREEK TRIBUTARY 10.prj (project) ---

Proj Title=MULBERRY CREEK TRIBUTARY 10 Base Level Engineering
Current Plan=p01
Default Exp/Contr=0.3,0.1
English Units
Geom File=g01
Flow File=f01
Plan File=p01
BEGIN DESCRIPTION:
MULBERRY CREEK TRIBUTARY 10
END DESCRIPTION:

--- MULBERRY CREEK TRIBUTARY 10.p01 (plan) ---

Plan Title=Multiple Run
Short Identifier=Multiple
Geom File=g01
Flow File=f01
Subcritical Flow
K Sum by GR= 0
Std Step Tol= 0.01
Critical Tol= 0.01
Num of Std Step Trials= 20
Max Error Tol= 0.3
Flow Tol Ratio= 0.001
Split Flow NTrial= 30
Split Flow Tol= 0.02
Split Flow Ratio= 0.02
Log Output Level= 0
Friction Slope Method= 1
Unsteady Friction Slope Method= 2
Unsteady Bridges Friction Slope Method= 1
Parabolic Critical Depth
Global Vel Dist=  1 , 1 , 1
Global Log Level= 0
CheckData=True
Encroach Param= -1, 0, 0, 0
BEGIN DESCRIPTION:
Multiple Run
END DESCRIPTION:

--- MULBERRY CREEK TRIBUTARY 10.f01 (steady flow) ---

Flow Title=Multiple
Number of Profiles=7
Profile Names=10-year,25-year,50-year,1pct_min,100-year,1pct_plu,500-year
River Rch & RM= MULBERRY CREEK T,Reach-1,9915
     133     175     208     123     245     489     346
River Rch & RM= MULBERRY CREEK T,Reach-1,8385
     207     280     339     204     407     812     595
River Rch & RM= MULBERRY CREEK T,Reach-1,4844
     458     649     809     502    1001    1997    1551
Boundary for River Rch & Prof#=MULBERRY CREEK T,Reach-1,1
Up Type=0
Dn Type=3
Dn Slope=0.005
Boundary for River Rch & Prof#=MULBERRY CREEK T,Reach-1,2
Up Type=0
Dn Type=3
Dn Slope=0.005
Boundary for River Rch & Prof#=MULBERRY CREEK T,Reach-1,3
Up Type=0
Dn Type=3
Dn Slope=0.005
Boundary for River Rch & Prof#=MULBERRY CREEK T,Reach-1,4
Up Type=0
Dn Type=3
Dn Slope=0.005
Boundary for River Rch & Prof#=MULBERRY CREEK T,Reach-1,5
Up Type=0
Dn Type=3
Dn Slope=0.005
Boundary for River Rch & Prof#=MULBERRY CREEK T,Reach-1,6
Up Type=0
Dn Type=3
Dn Slope=0.005
Boundary for River Rch & Prof#=MULBERRY CREEK T,Reach-1,7
Up Type=0
Dn Type=3
Dn Slope=0.005

--- MULBERRY CREEK TRIBUTARY 10.g01 (geometry) ---

Geom Title=Existing Conditions

River Reach=MULBERRY CREEK T,Reach-1
Reach XY= 30
      1541305.00      6875538.00      1541725.18      6875738.29
      1542051.58      6875495.79      1542403.81      6875591.45
      1542502.32      6875882.58      1542758.40      6875895.83
      1542955.08      6876030.70      1543211.67      6875947.30
      1543363.15      6876185.50      1543507.54      6876142.99
      1544057.10      6876534.84      1544344.53      6876388.57
      1544506.48      6876684.55      1544754.91      6876545.29
      1545057.31      6876693.83      1545154.44      6876798.60
      1545105.00      6876938.00      1545256.47      6877084.46
      1545594.81      6877188.46      1545939.59      6877088.02
      1546157.58      6877193.71      1546212.80      6877544.21
      1546501.57      6877689.22      1546727.88      6878561.52
      1547070.34      6878838.05      1547361.95      6878646.84
      1547544.90      6878927.61      1547878.71      6879060.36
      1547995.00      6879277.37      1548255.00      6879338.00

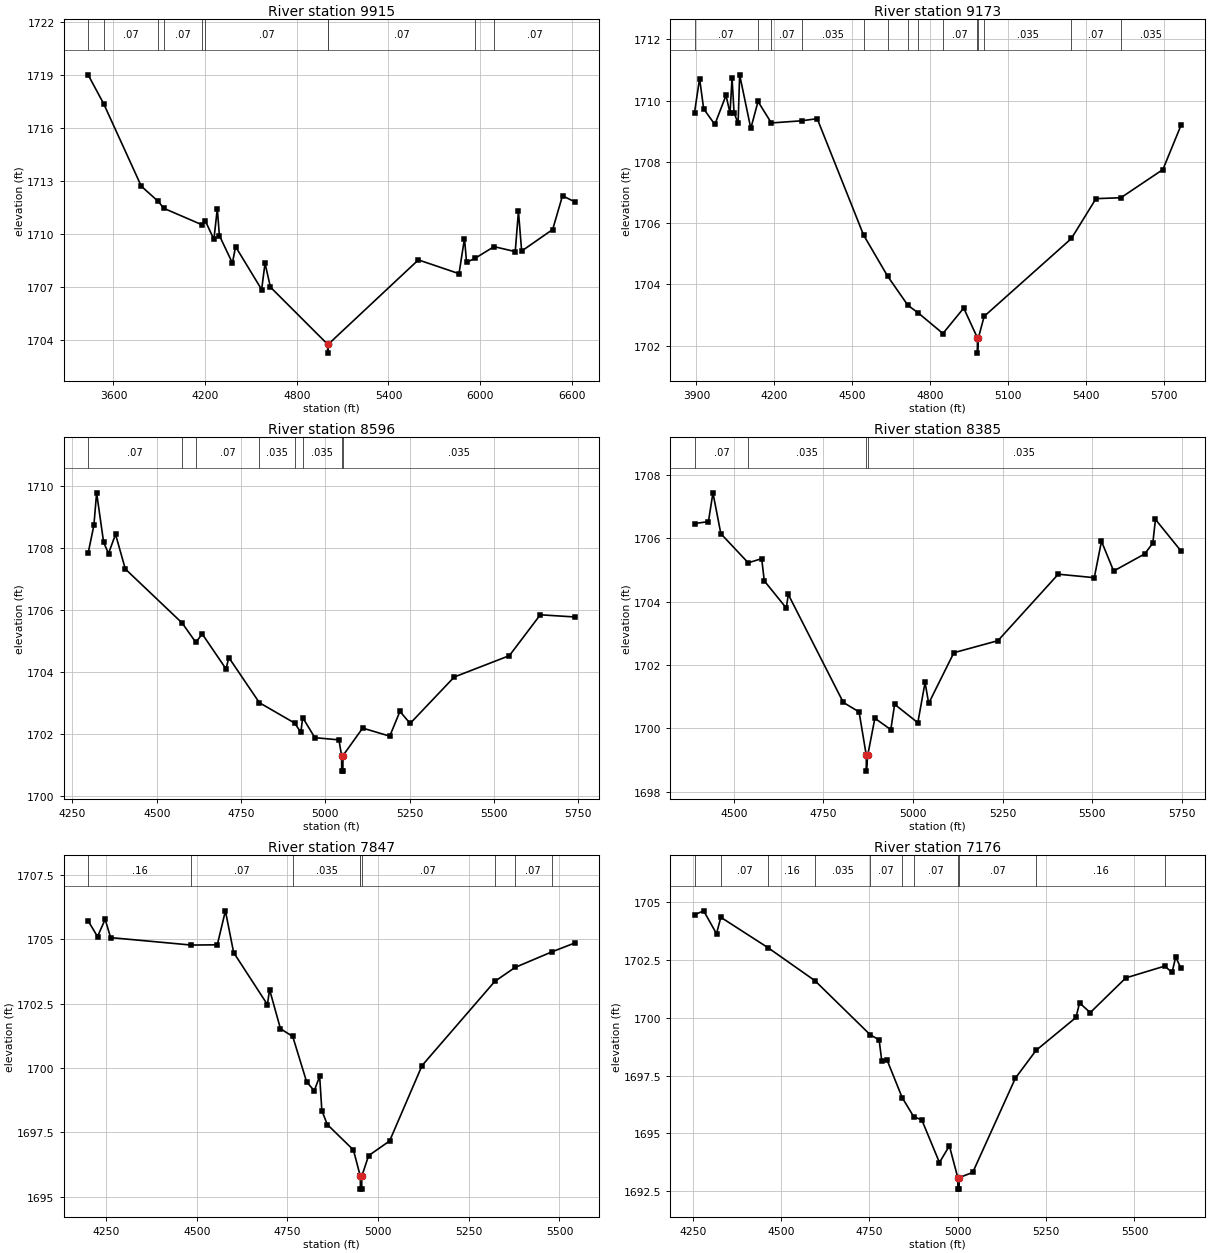
Type RM Length L Ch R = 1,9915,742,742,742
BEGIN DESCRIPTION:
MULBERRY CREEK TRIBUTARY 10_1 4.0
END DESCRIPTION:
XS GIS Cut Line= 3
      1540554.99      6876738.01      1541755.00      6875738.00
      1540854.98      6874387.96
#Sta/Elev= 30
  3434.1 1718.99  3536.6 1717.34  3782.3 1712.68  3893.2 1711.82  3929.8 1711.43
  4181.7 1710.49  4200.2 1710.74  4257.4 1709.67  4279.6 1711.41  4293.2 1709.89
  4378.5 1708.33  4399.3 1709.26  4569.8 1706.83  4592.0 1708.32  4627.1 1706.97
  5001.7 1703.73  5001.9 1703.23  5005.7 1703.73  5595.6 1708.51  5861.5 1707.73
  5897.5 1709.72  5911.1 1708.37  5966.6 1708.60  6091.0 1709.26  6229.6 1708.98
  6250.6 1711.26  6271.6 1709.01  6474.4 1710.23  6539.0 1712.14  6618.7 1711.80
#Mann=10,-1,0
  3434.1   0.035       0  3536.6    0.07       0  3893.2    0.16       0
  3929.8    0.07       0  4181.7    0.16       0  4200.2    0.07       0
  5001.7    0.07       0  5005.7    0.07       0  5966.6   0.035       0
  6091.0    0.07       0
Bank Sta=5001.7,5005.7
Exp/Cntr=0.3,0.1

Type RM Length L Ch R = 1,9173,577,577,577
BEGIN DESCRIPTION:
Mapping XS 1bd57bb5
END DESCRIPTION:
XS GIS Cut Line= 3
      1541831.57      6876542.37      1542382.79      6875609.20
      1542061.63      6874888.75
#Sta/Elev= 30
  3892.5 1709.61  3912.0 1710.72  3927.7 1709.73  3970.6 1709.22  4013.7 1710.17
  4029.1 1709.59  4036.9 1710.73  4044.7 1709.60  4060.2 1709.26  4066.2 1710.84
  4109.1 1709.09  4136.9 1709.97  4188.1 1709.27  4304.8 1709.34  4364.6 1709.41
  4543.3 1705.61  4635.7 1704.27  4713.7 1703.32  4753.8 1703.07  4848.5 1702.40
  4928.5 1703.23  4981.1 1702.26  4981.4 1701.76  4985.1 1702.26  5007.2 1702.96
  5343.0 1705.50  5437.5 1706.80  5533.4 1706.83  5695.1 1707.75  5765.1 1709.20
#Mann=14,-1,0
  3892.5    0.07       0  4136.9   0.035       0  4188.1    0.07       0
  4304.8   0.035       0  4543.3    0.07       0  4635.7   0.035       0
  4713.7    0.07       0  4753.8   0.035       0  4848.5    0.07       0
  4981.1    0.07       0  4985.1    0.07       0  5007.2   0.035       0
  5343.0    0.07       0  5533.4   0.035       0
Bank Sta=4981.1,4985.1
Exp/Cntr=0.3,0.1

Type RM Length L Ch R = 1,8596,211,211,211
BEGIN DESCRIPTION:
Mapping XS d828bfd6
END DESCRIPTION:
XS GIS Cut Line= 3
      1542250.68      6876497.96      1542669.35      6875958.27
      1542751.11      6875202.82
#Sta/Elev= 30
  4296.5 1707.83  4313.6 1708.73  4321.7 1709.78  4342.5 1708.18  4357.0 1707.82
  4377.8 1708.44  4406.8 1707.32  4575.7 1705.57  4615.8 1704.95  4634.9 1705.22
  4705.5 1704.09  4713.7 1704.46  4804.4 1703.00  4909.3 1702.34  4927.3 1702.04
  4932.8 1702.52  4968.9 1701.87  5040.2 1701.80  5048.2 1701.29  5048.5 1700.79
  5052.0 1700.79  5052.2 1701.29  5110.6 1702.18  5191.0 1701.92  5221.2 1702.72
  5251.4 1702.33  5382.2 1703.83  5545.7 1704.52  5637.4 1705.84  5739.4 1705.77
#Mann=8,-1,0
  4296.5    0.07       0  4575.7   0.035       0  4615.8    0.07       0
  4804.4   0.035       0  4909.3    0.07       0  4932.8   0.035       0
  5048.2   0.035       0  5052.2   0.035       0
Bank Sta=5048.2,5052.2
Exp/Cntr=0.3,0.1

Type RM Length L Ch R = 1,8385,538,538,538
BEGIN DESCRIPTION:
MULBERRY CREEK TRIBUTARY 10_1 2.0
END DESCRIPTION:
XS GIS Cut Line= 3
      1542581.99      6876524.60      1542838.33      6875971.30
      1542907.53      6875226.81
#Sta/Elev= 30
  4390.2 1706.47  4429.0 1706.53  4441.6 1707.44  4463.6 1706.15  4540.0 1705.23
  4577.6 1705.36  4584.8 1704.66  4646.3 1703.80  4651.8 1704.23  4805.3 1700.82
  4849.3 1700.52  4869.4 1699.15  4869.6 1698.65  4873.4 1699.15  4893.4 1700.32
  4937.8 1699.96  4948.5 1700.76  5013.2 1700.18  5033.4 1701.45  5043.5 1700.79
  5113.8 1702.39  5236.7 1702.77  5405.0 1704.87  5505.5 1704.76  5525.6 1705.91
  5559.5 1704.97  5646.1 1705.51  5668.8 1705.85  5676.2 1706.60  5747.7 1705.60
#Mann=4,-1,0
  4390.2    0.07       0  4540.0   0.035       0  4869.4   0.035       0
  4873.4   0.035       0
Bank Sta=4869.4,4873.4
Exp/Cntr=0.3,0.1

Type RM Length L Ch R = 1,7847,671,671,671
BEGIN DESCRIPTION:
Mapping XS 639f6f1e
END DESCRIPTION:
XS GIS Cut Line= 3
      1542834.21      6876672.53      1543266.47      6876026.73
      1543411.89      6875481.40
#Sta/Elev= 30
  4200.4 1705.71  4226.3 1705.10  4247.4 1705.77  4262.4 1705.06  4484.8 1704.77
  4556.6 1704.78  4578.9 1706.10  4601.6 1704.48  4694.7 1702.46  4700.7 1703.04
  4730.7 1701.52  4764.5 1701.22  4802.8 1699.46  4823.8 1699.11  4838.8 1699.67
  4844.8 1698.34  4859.8 1697.80  4931.9 1696.81  4950.5 1695.81  4950.9 1695.79
  4951.2 1695.29  4954.7 1695.29  4954.9 1695.79  4973.7 1696.59  5031.6 1697.16
  5121.1 1700.09  5321.7 1703.36  5377.4 1703.90  5478.0 1704.50  5541.9 1704.85
#Mann=9,-1,0
  4200.4    0.16       0  4484.8    0.07       0  4764.5   0.035       0
  4950.5    0.07       0  4950.9    0.07       0  4954.9    0.07       0
  5321.7    0.16       0  5377.4    0.07       0  5478.0    0.16       0
Bank Sta=4950.9,4954.9
Exp/Cntr=0.3,0.1

Type RM Length L Ch R = 1,7176,362,362,362
BEGIN DESCRIPTION:
Mapping XS 50e7481d
END DESCRIPTION:
XS GIS Cut Line= 3
      1543157.13      6876787.12      1543714.39      6876313.19
      1543792.49      6875672.78
#Sta/Elev= 30
  4255.2 1704.45  4281.1 1704.62  4317.4 1703.63  4329.6 1704.34  4462.8 1703.03
  4595.9 1701.60  4751.8 1699.27  4777.5 1699.04  4785.2 1698.11  4799.5 1698.19
  4842.6 1696.55  4875.4 1695.72  4898.3 1695.58  4948.2 1693.74  4976.3 1694.46
  5000.0 1693.09  5000.3 1692.59  5003.8 1692.59  5004.0 1693.09  5042.3 1693.31
  5163.2 1697.39  5221.7 1698.59  5334.5 1700.01  5344.6 1700.64  5374.8 1700.22
  5475.5 1701.72  5585.4 1702.23  5606.4 1701.96  5616.6 1702.62  5631.9 1702.13
#Mann=11,-1,0
  4255.2    0.16       0  4329.6    0.07       0  4462.8    0.16       0
  4595.9   0.035       0  4751.8    0.07       0  4842.6   0.035       0
  4875.4    0.07       0  5000.0    0.07       0  5004.0    0.07       0
  5221.7    0.16       0  5585.4    0.07       0
Bank Sta=5000,5004
Exp/Cntr=0.3,0.1

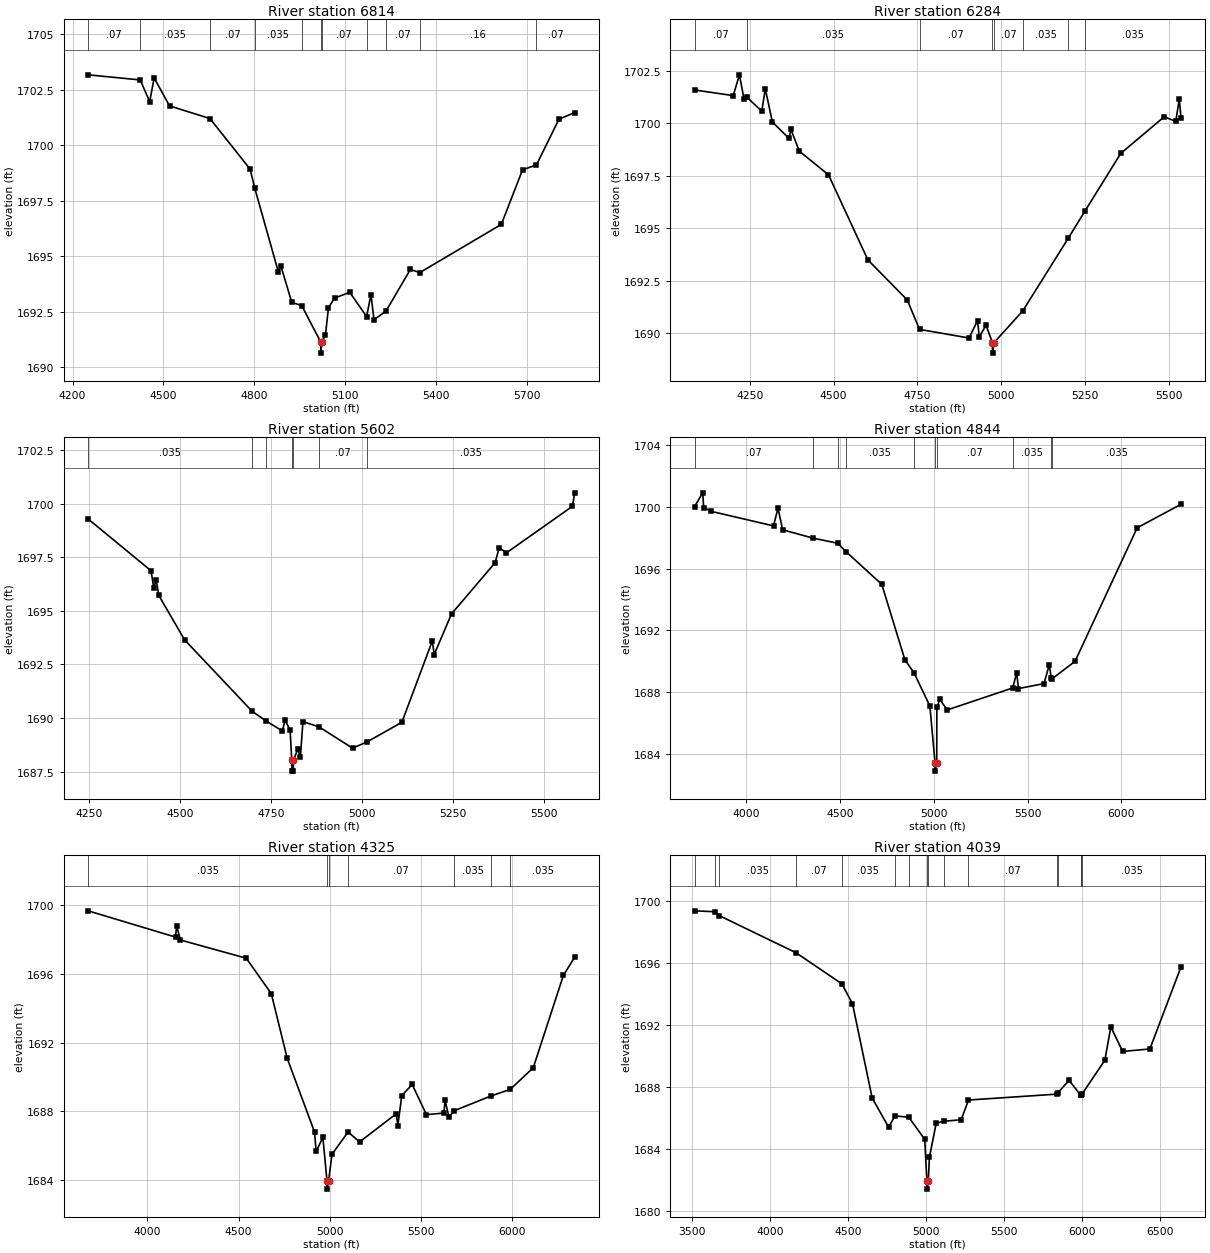
Type RM Length L Ch R = 1,6814,530,530,530
BEGIN DESCRIPTION:
Mapping XS 302bf4c6
END DESCRIPTION:
XS GIS Cut Line= 3
      1543558.13      6877104.87      1543995.64      6876469.44
      1543974.80      6875636.09
#Sta/Elev= 30
  4251.5 1703.17  4423.5 1702.94  4454.5 1701.96  4469.4 1703.03  4520.1 1701.77
  4653.4 1701.20  4785.9 1698.92  4801.5 1698.05  4879.0 1694.29  4887.4 1694.56
  4923.2 1692.92  4956.1 1692.77  5018.8 1691.13  5019.1 1690.63  5022.8 1691.13
  5034.4 1691.44  5044.4 1692.68  5064.4 1693.11  5114.5 1693.37  5170.2 1692.28
  5184.5 1693.27  5194.5 1692.14  5233.5 1692.51  5314.5 1694.40  5345.8 1694.26
  5614.6 1696.43  5684.6 1698.89  5730.5 1699.11  5804.7 1701.17  5856.6 1701.47
#Mann=11,-1,0
  4251.5    0.07       0  4423.5   0.035       0  4653.4    0.07       0
  4801.5   0.035       0  4956.1    0.07       0  5018.8    0.07       0
  5022.8    0.07       0  5170.2   0.035       0  5233.5    0.07       0
  5345.8    0.16       0  5730.5    0.07       0
Bank Sta=5018.8,5022.8
Exp/Cntr=0.3,0.1

Type RM Length L Ch R = 1,6284,682,682,682
BEGIN DESCRIPTION:
Mapping XS f53ceb8c
END DESCRIPTION:
XS GIS Cut Line= 3
      1544073.78      6877276.69      1544381.05      6876422.57
      1544620.29      6875933.68
#Sta/Elev= 30
  4084.9 1701.58  4200.4 1701.31  4218.9 1702.30  4232.3 1701.17  4241.3 1701.23
  4285.6 1700.57  4296.1 1701.63  4317.3 1700.05  4367.1 1699.27  4372.5 1699.70
  4397.9 1698.66  4484.7 1697.54  4602.2 1693.49  4719.7 1691.58  4756.4 1690.18
  4904.0 1689.77  4929.4 1690.59  4934.7 1689.82  4954.8 1690.38  4973.9 1689.55
  4974.2 1689.05  4978.6 1689.55  5064.4 1691.06  5200.2 1694.52  5251.1 1695.84
  5356.9 1698.56  5486.4 1700.30  5521.0 1700.09  5531.4 1701.13  5536.9 1700.24
#Mann=8,-1,0
  4084.9    0.07       0  4241.3   0.035       0  4756.4    0.07       0
  4973.9    0.07       0  4978.6    0.07       0  5064.4   0.035       0
  5200.2    0.07       0  5251.1   0.035       0
Bank Sta=4973.9,4978.6
Exp/Cntr=0.3,0.1

Type RM Length L Ch R = 1,5602,758,758,758
BEGIN DESCRIPTION:
Mapping XS ef85cc64
END DESCRIPTION:
XS GIS Cut Line= 3
      1544297.71      6877115.28      1544808.14      6876630.90
      1544735.36      6876001.88
#Sta/Elev= 30
  4246.5 1699.29  4419.6 1696.87  4426.5 1696.09  4433.8 1696.42  4440.7 1695.72
  4511.5 1693.65  4697.3 1690.31  4734.8 1689.87  4780.4 1689.39  4787.3 1689.90
  4801.5 1689.45  4806.0 1688.02  4806.4 1687.52  4810.4 1687.52  4810.7 1688.02
  4822.5 1688.55  4829.8 1688.17  4836.7 1689.83  4880.5 1689.59  4973.2 1688.59
  5013.5 1688.89  5108.6 1689.80  5192.3 1693.60  5197.4 1692.96  5245.0 1694.86
  5364.9 1697.25  5375.9 1697.95  5396.0 1697.71  5577.2 1699.88  5583.4 1700.51
#Mann=7,-1,0
  4246.5   0.035       0  4697.3    0.07       0  4734.8   0.035       0
  4806.0    0.07       0  4810.7   0.035       0  4880.5    0.07       0
  5013.5   0.035       0
Bank Sta=4806,4810.7
Exp/Cntr=0.3,0.1

Type RM Length L Ch R = 1,4844,519,519,519
BEGIN DESCRIPTION:
Mapping XS a4b714ea
END DESCRIPTION:
XS GIS Cut Line= 4
      1544774.04      6878252.19      1545232.39      6877036.86
      1545239.33      6876675.75      1544711.53      6875904.89
#Sta/Elev= 30
  3723.8 1700.01  3767.4 1700.90  3772.7 1699.95  3813.8 1699.70  4145.1 1698.76
  4168.8 1699.91  4193.6 1698.51  4355.5 1697.97  4487.0 1697.64  4532.0 1697.09
  4722.2 1694.98  4845.5 1690.10  4893.6 1689.27  4978.7 1687.11  5006.3 1683.40
  5006.8 1682.90  5015.1 1683.40  5016.0 1687.02  5031.5 1687.54  5071.6 1686.86
  5420.4 1688.28  5441.8 1689.26  5450.6 1688.24  5587.2 1688.56  5615.1 1689.78
  5626.3 1688.90  5632.3 1688.89  5752.6 1690.00  6084.1 1698.64  6318.1 1700.16
#Mann=10,-1,0
  3723.8    0.07       0  4355.5   0.035       0  4487.0    0.07       0
  4532.0   0.035       0  4893.6    0.07       0  5006.3    0.07       0
  5015.1    0.07       0  5420.4   0.035       0  5626.3    0.07       0
  5632.3   0.035       0
Bank Sta=5006.3,5015.1
Exp/Cntr=0.3,0.1

Type RM Length L Ch R = 1,4325,286,286,286
BEGIN DESCRIPTION:
Mapping XS 94f721a6
END DESCRIPTION:
XS GIS Cut Line= 3
      1545010.14      6878286.90      1545725.44      6877224.36
      1544955.07      6876072.28
#Sta/Elev= 30
  3675.5 1699.68  4154.5 1698.15  4160.6 1698.80  4181.6 1697.98  4542.1 1696.92
  4679.4 1694.86  4766.4 1691.10  4916.3 1686.80  4925.3 1685.67  4962.1 1686.48
  4984.6 1683.97  4985.1 1683.47  4993.6 1683.97  5012.2 1685.50  5100.4 1686.80
  5163.3 1686.22  5364.5 1687.86  5373.0 1687.17  5394.5 1688.91  5451.6 1689.57
  5529.7 1687.81  5625.7 1687.90  5631.7 1688.65  5652.8 1687.67  5682.7 1688.04
  5882.0 1688.89  5989.1 1689.28  6115.2 1690.54  6280.4 1695.92  6342.3 1696.98
#Mann=7,-1,0
  3675.5   0.035       0  4984.6   0.035       0  4993.6   0.035       0
  5100.4    0.07       0  5682.7   0.035       0  5882.0    0.07       0
  5989.1   0.035       0
Bank Sta=4984.6,4993.6
Exp/Cntr=0.3,0.1

Type RM Length L Ch R = 1,4039,0,0,0
BEGIN DESCRIPTION:
Mapping XS 99ecaba4
END DESCRIPTION:
XS GIS Cut Line= 4
      1545485.00      6878499.95      1545953.74      6877078.10
      1545682.91      6876223.93      1545017.04      6875932.61
#Sta/Elev= 30
  3515.5 1699.37  3647.9 1699.31  3674.6 1699.06  4166.3 1696.67  4459.7 1694.67
  4528.4 1693.39  4654.7 1687.31  4760.0 1685.43  4801.2 1686.16  4889.5 1686.07
  4991.7 1684.65  5005.5 1681.94  5006.0 1681.44  5014.5 1681.94  5021.5 1683.48
  5065.2 1685.69  5112.7 1685.81  5225.6 1685.91  5272.3 1687.18  5838.5 1687.56
  5846.2 1687.66  5917.3 1688.45  5991.2 1687.50  5993.2 1687.48  6002.0 1687.59
  6146.5 1689.74  6185.1 1691.89  6260.7 1690.31  6435.4 1690.47  6635.5 1695.77
#Mann=16,-1,0
  3515.5   0.035       0  3647.9    0.07       0  3674.6   0.035       0
  4166.3    0.07       0  4459.7   0.035       0  4801.2    0.07       0
  4889.5   0.035       0  5005.5   0.035       0  5014.5   0.035       0
  5112.7   0.035       0  5272.3    0.07       0  5838.5   0.035       0
  5846.2    0.07       0  5991.2   0.035       0  5993.2    0.07       0
  6002.0   0.035       0
Bank Sta=5005.5,5014.5
Exp/Cntr=0.3,0.1

Chan Stop Cuts=-1