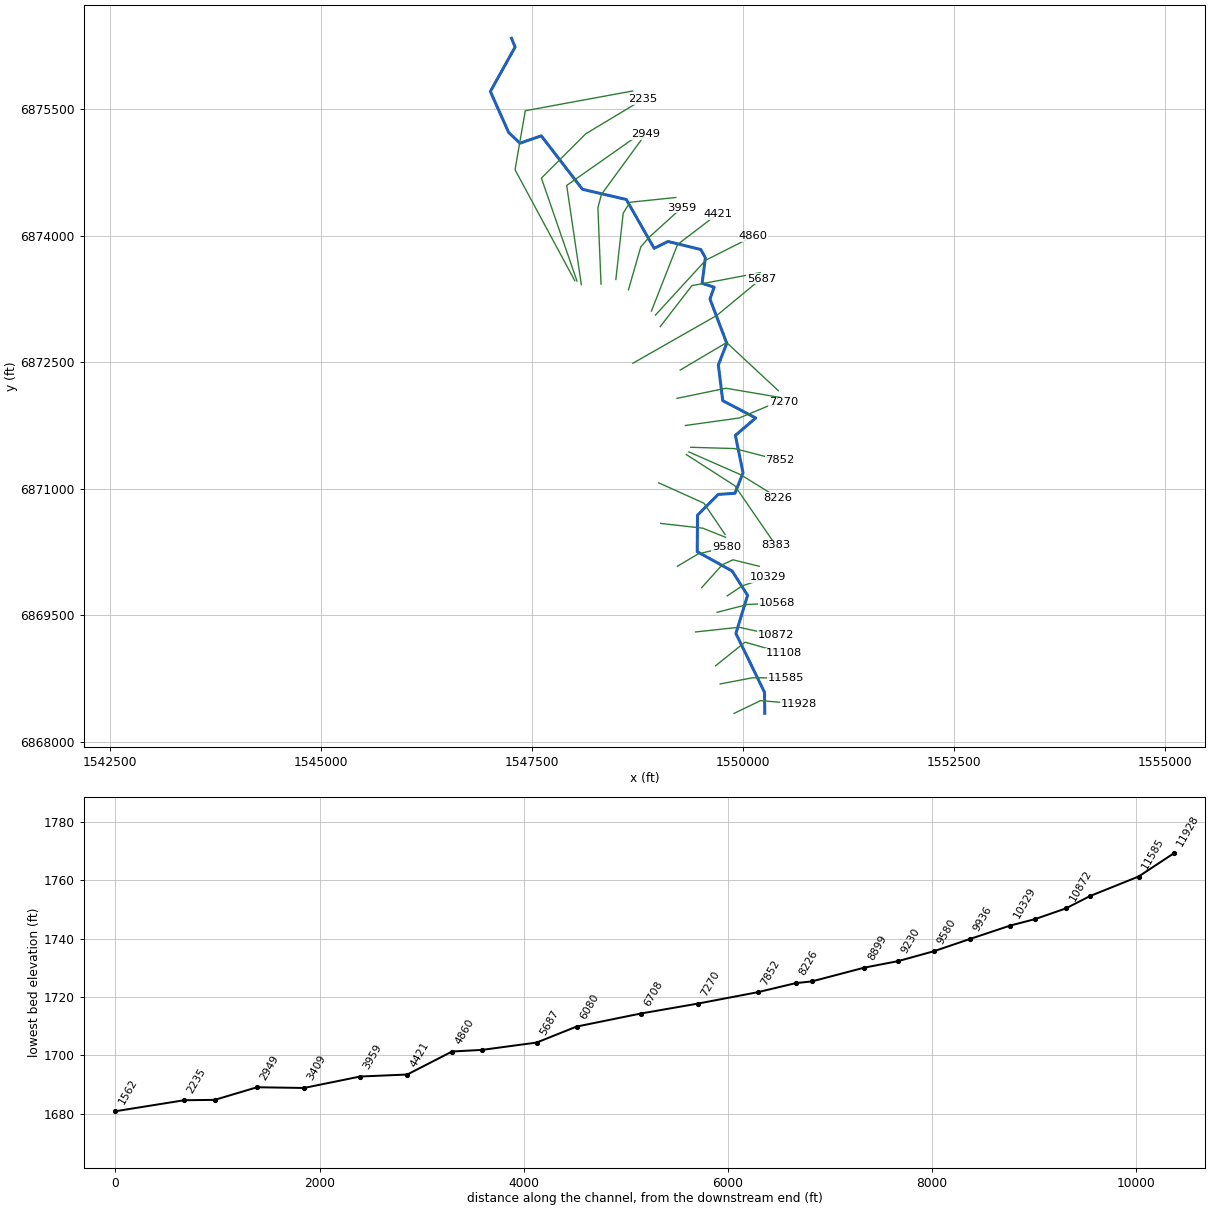
--- MULBERRY CREEK TRIBUTARY 11.prj (project) ---

Proj Title=MULBERRY CREEK TRIBUTARY 11 Base Level Engineering
Current Plan=p01
Default Exp/Contr=0.3,0.1
English Units
Geom File=g01
Flow File=f01
Plan File=p01
Y Axis Title=Elevation
X Axis Title(PF)=Main Channel Distance
X Axis Title(XS)=Station
BEGIN DESCRIPTION:
MULBERRY CREEK TRIBUTARY 11
END DESCRIPTION:
DSS Export Rating Curves= 0
DSS Export Rating Curve Sorted= 0
DSS Export Volume Flow Curves= 0
DXF OffsetX= 0
DXF OffsetY= 0
DXF ScaleX= 1
DXF ScaleY= 10

--- MULBERRY CREEK TRIBUTARY 11.p01 (plan) ---

Plan Title=Multiple Run
Short Identifier=Multiple
Geom File=g01
Flow File=f01
Subcritical Flow
K Sum by GR= 0
Std Step Tol= 0.01
Critical Tol= 0.01
Num of Std Step Trials= 20
Max Error Tol= 0.3
Flow Tol Ratio= 0.001
Split Flow NTrial= 30
Split Flow Tol= 0.02
Split Flow Ratio= 0.02
Log Output Level= 0
Friction Slope Method= 1
Unsteady Friction Slope Method= 2
Unsteady Bridges Friction Slope Method= 1
Parabolic Critical Depth
Global Vel Dist=  1 , 1 , 1
Global Log Level= 0
CheckData=True
Encroach Param= -1, 0, 0, 0
BEGIN DESCRIPTION:
Multiple Run
END DESCRIPTION:

--- MULBERRY CREEK TRIBUTARY 11.f01 (steady flow) ---

Flow Title=Multiple
Program Version=4.10
Number of Profiles= 7
Profile Names=10-year,25-year,50-year,1pct_min,100-year,1pct_plu,500-year
River Rch & RM=MULBERRY CREEK T,Reach-1         ,11928
     140     188     227     137     273     544     399
River Rch & RM=MULBERRY CREEK T,Reach-1         ,5687
     232     322     396     243     484     966     735
Boundary for River Rch & Prof#=MULBERRY CREEK T,Reach-1         , 1
Up Type= 0
Dn Type= 3
Dn Slope=0.005
Boundary for River Rch & Prof#=MULBERRY CREEK T,Reach-1         , 2
Up Type= 0
Dn Type= 3
Dn Slope=0.005
Boundary for River Rch & Prof#=MULBERRY CREEK T,Reach-1         , 3
Up Type= 0
Dn Type= 3
Dn Slope=0.005
Boundary for River Rch & Prof#=MULBERRY CREEK T,Reach-1         , 4
Up Type= 0
Dn Type= 3
Dn Slope=0.005
Boundary for River Rch & Prof#=MULBERRY CREEK T,Reach-1         , 5
Up Type= 0
Dn Type= 3
Dn Slope=0.005
Boundary for River Rch & Prof#=MULBERRY CREEK T,Reach-1         , 6
Up Type= 0
Dn Type= 3
Dn Slope=0.005
Boundary for River Rch & Prof#=MULBERRY CREEK T,Reach-1         , 7
Up Type= 0
Dn Type= 3
Dn Slope=0.005
DSS Import GetInterval= 0
DSS Import GetPeak= 0
DSS Import FillOption= 0

--- MULBERRY CREEK TRIBUTARY 11.g01 (geometry) ---

Geom Title=Existing Conditions
Program Version=4.10

River Reach=MULBERRY CREEK T,Reach-1
Reach XY= 30
        1550255.        6868338.      1550251.84      6868586.35
      1549912.79      6869284.58      1550051.46      6869736.53
       1549868.3      6870024.59      1549455.01      6870253.35
      1549458.34      6870686.28      1549702.72      6870932.18
      1549901.84       6870945.6      1549997.25      6871188.09
      1549907.05      6871632.16      1550148.02       6871838.2
      1549756.97       6872043.5      1549704.79      6872467.79
      1549804.92      6872722.61      1549605.73      6873248.68
        1549655.        6873388.      1549512.64      6873434.31
      1549551.26      6873736.48      1549496.72      6873834.94
      1549108.29      6873929.95      1548944.63      6873848.95
       1548614.7       6874427.8      1548095.32      6874548.75
      1547607.45      6875182.55      1547354.99      6875095.08
      1547221.65      6875221.32       1547004.6      6875708.14
      1547297.41      6876234.61        1547255.        6876338.

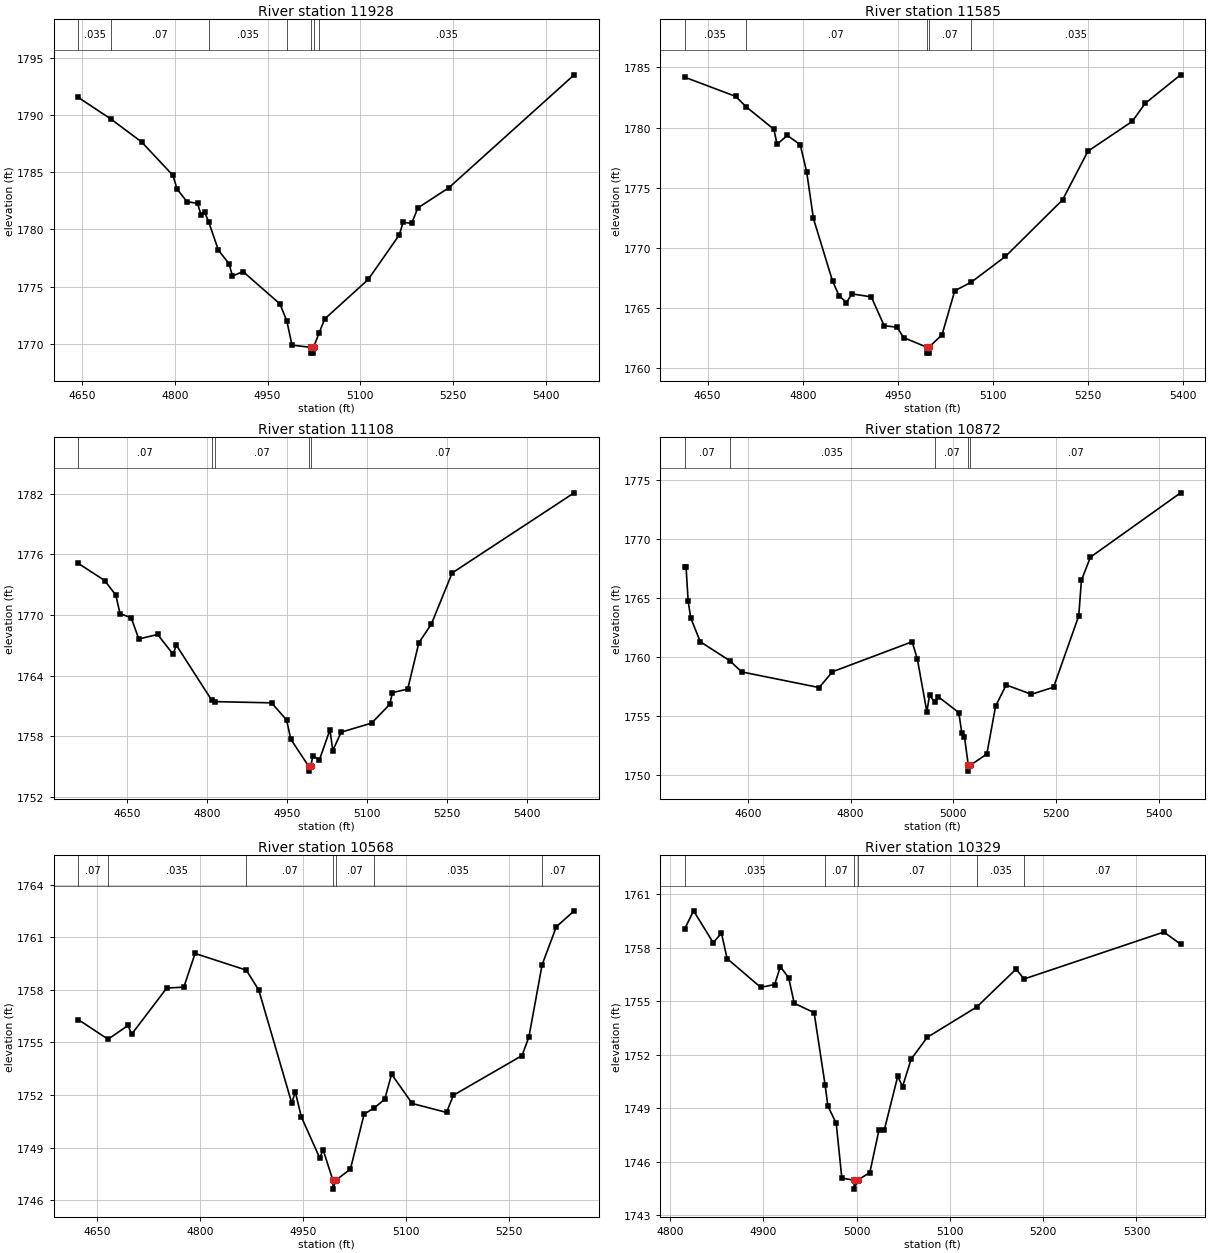
Type RM Length L Ch R = 1 ,11928   ,343,343,343
BEGIN DESCRIPTION:
MULBERRY CREEK TRIBUTARY 11 18.0
END DESCRIPTION:
XS GIS Cut Line= 3
      1549891.21      6868337.01        1550205.        6868488.
      1550656.87      6868449.85
#Sta/Elev= 30
  4644.1 1791.54  4696.4 1789.67  4746.4 1787.65  4797.2 1784.72  4803.7 1783.53
  4819.8 1782.43  4836.9 1782.28  4842.5 1781.27  4848.1 1781.55  4854.7 1780.68
  4870.6 1778.19  4887.7 1777.01  4893.3 1775.93  4910.4 1776.32  4970.1 1773.49
  4981.2    1772  4989.6 1769.89  5020.4 1769.69  5020.7 1769.19  5024.2 1769.19
  5024.4 1769.69  5033.2 1770.93  5042.5 1772.18  5112.8 1775.63  5162.9 1779.51
  5169.3 1780.63    5183 1780.53    5193 1781.88  5243.2 1783.65  5445.8 1793.52
#Mann= 7 ,-1 , 0
  4644.1    .035       0  4696.4     .07       0  4854.7    .035       0
  4981.2     .07       0  5020.4     .07       0  5024.4     .07       0
  5033.2    .035       0
Bank Sta=5020.4,5024.4
XS Rating Curve= 0 ,0
Exp/Cntr=0.3,0.1

Type RM Length L Ch R = 1 ,11585   ,477,477,477
BEGIN DESCRIPTION:
MULBERRY CREEK TRIBUTARY 11 17.0
END DESCRIPTION:
XS GIS Cut Line= 3
      1549726.22      6868685.96      1550105.31      6868758.13
      1550501.11      6868758.88
#Sta/Elev= 30
  4614.1 1784.18  4694.3 1782.59  4710.5 1781.74  4754.5 1779.86  4759.6 1778.61
  4775.7 1779.35  4796.1 1778.58  4806.3  1776.3  4816.9 1772.45    4847 1767.26
  4857.2 1766.05    4869 1765.47  4877.5 1766.19  4908.1 1765.94  4928.4 1763.55
  4948.8 1763.42    4959 1762.56  4995.3 1761.77  4995.5 1761.27    4999 1761.27
  4999.3 1761.77  5019.7  1762.8  5039.7 1766.45  5065.4 1767.15  5119.7  1769.3
  5209.7    1774  5249.7 1778.04  5319.7 1780.52  5339.7    1782  5395.8 1784.38
#Mann= 5 ,-1 , 0
  4614.1    .035       0  4710.5     .07       0  4995.3     .07       0
  4999.3     .07       0  5065.4    .035       0
Bank Sta=4995.3,4999.3
XS Rating Curve= 0 ,0
Exp/Cntr=0.3,0.1

Type RM Length L Ch R = 1 ,11108   ,236,236,236
BEGIN DESCRIPTION:
MULBERRY CREEK TRIBUTARY 11 16.0
END DESCRIPTION:
XS GIS Cut Line= 3
      1549672.48      6868901.27      1550021.25      6869181.13
      1550484.97       6869048.8
#Sta/Elev= 30
  4559.1 1775.09  4608.5  1773.4  4629.3 1771.96  4637.3 1770.12  4658.1 1769.73
  4672.5 1767.62  4707.7 1768.07  4736.5 1766.13  4742.9    1767    4809 1761.58
  4815.7 1761.43  4921.3 1761.31  4949.4 1759.62  4957.4 1757.71  4990.6 1755.06
  4990.8 1754.56  4994.6 1755.06    4999 1756.08  5010.8 1755.65  5030.8 1758.65
    5036 1756.59  5051.8 1758.41  5108.9 1759.31  5142.7 1761.15  5147.9 1762.32
  5176.5 1762.67  5197.4 1767.25  5220.7 1769.08  5259.8 1774.15  5488.5 1782.07
#Mann= 5 ,-1 , 0
  4559.1     .07       0    4809    .035       0  4815.7     .07       0
  4990.6     .07       0  4994.6     .07       0
Bank Sta=4990.6,4994.6
XS Rating Curve= 0 ,0
Exp/Cntr=0.3,0.1

Type RM Length L Ch R = 1 ,10872   ,304,304,304
BEGIN DESCRIPTION:
Mapping XS 96aebec1
END DESCRIPTION:
XS GIS Cut Line= 3
      1549435.01      6869302.14      1549950.66      6869357.69
      1550386.41      6869260.47
#Sta/Elev= 30
  4477.4 1767.59  4479.9 1767.59  4483.9 1764.75    4489  1763.3  4507.6 1761.29
  4564.8 1759.69    4588 1758.74  4738.9 1757.41  4764.8 1758.75  4919.9 1761.29
    4930 1759.84  4948.6 1755.35  4953.7 1756.75  4964.2 1756.17  4970.2 1756.65
  5010.7 1755.29  5016.7 1753.53  5021.8 1753.22  5029.2 1750.83  5029.5 1750.33
  5033.2 1750.83  5065.3 1751.78  5082.4 1755.84  5102.9 1757.63  5152.2 1756.84
  5195.2 1757.44  5244.2 1763.49  5249.4  1766.5  5266.9 1768.46  5442.5 1773.91
#Mann= 5 ,-1 , 0
  4477.4     .07       0  4564.8    .035       0  4964.2     .07       0
  5029.2     .07       0  5033.2     .07       0
Bank Sta=5029.2,5033.2
XS Rating Curve= 0 ,0
Exp/Cntr=0.3,0.1

Type RM Length L Ch R = 1 ,10568   ,239,239,239
BEGIN DESCRIPTION:
Mapping XS b86a0c0b
END DESCRIPTION:
XS GIS Cut Line= 3
      1549690.22      6869534.77      1550053.09      6869628.53
        1550401.      6869640.64
#Sta/Elev= 30
  4622.8  1756.3  4666.1 1755.18  4695.3 1755.97  4700.4 1755.46  4751.7  1758.1
  4776.6 1758.15    4793 1760.07  4867.7 1759.12  4885.9 1757.98    4934 1751.54
  4939.1 1752.19  4947.9 1750.76  4974.6 1748.43  4979.8 1748.87    4994 1747.14
  4994.2 1746.64    4998 1747.14  5019.5 1747.78  5039.5 1750.92  5053.6 1751.25
  5069.5 1751.76  5079.5 1753.19  5109.6 1751.52  5159.6 1751.01  5169.6 1751.99
  5269.7 1754.25  5279.7 1755.31    5299 1759.43  5319.7 1761.59  5345.7  1762.5
#Mann= 7 ,-1 , 0
  4622.8     .07       0  4666.1    .035       0  4867.7     .07       0
    4994     .07       0    4998     .07       0  5053.6    .035       0
    5299     .07       0
Bank Sta=4994,4998
XS Rating Curve= 0 ,0
Exp/Cntr=0.3,0.1

Type RM Length L Ch R = 1 ,10329   ,393,393,393
BEGIN DESCRIPTION:
Mapping XS 18021b66
END DESCRIPTION:
XS GIS Cut Line= 3
      1549810.04      6869729.23      1549985.38      6869847.28
      1550289.15      6869947.96
#Sta/Elev= 30
  4815.9 1759.07  4825.3 1760.07  4846.3 1758.29  4855.2 1758.81  4861.3 1757.39
  4897.3 1755.78  4912.2 1755.94  4918.3 1756.94  4927.2 1756.32  4933.2 1754.89
  4954.5 1754.36  4966.3  1750.3  4969.2 1749.14  4978.2 1748.15  4984.2 1745.09
  4997.2 1744.97  4997.4 1744.47  5001.2 1744.97  5014.2  1745.4    5024 1747.78
  5029.7 1747.78  5044.1 1750.79  5049.3 1750.22  5058.5 1751.76  5075.8 1752.98
  5128.8 1754.68  5170.9  1756.8  5179.6 1756.25  5329.3 1758.88  5347.3  1758.2
#Mann= 6 ,-1 , 0
  4815.9    .035       0  4966.3     .07       0  4997.2     .07       0
  5001.2     .07       0  5128.8    .035       0  5179.6     .07       0
Bank Sta=4997.2,5001.2
XS Rating Curve= 0 ,0
Exp/Cntr=0.3,0.1

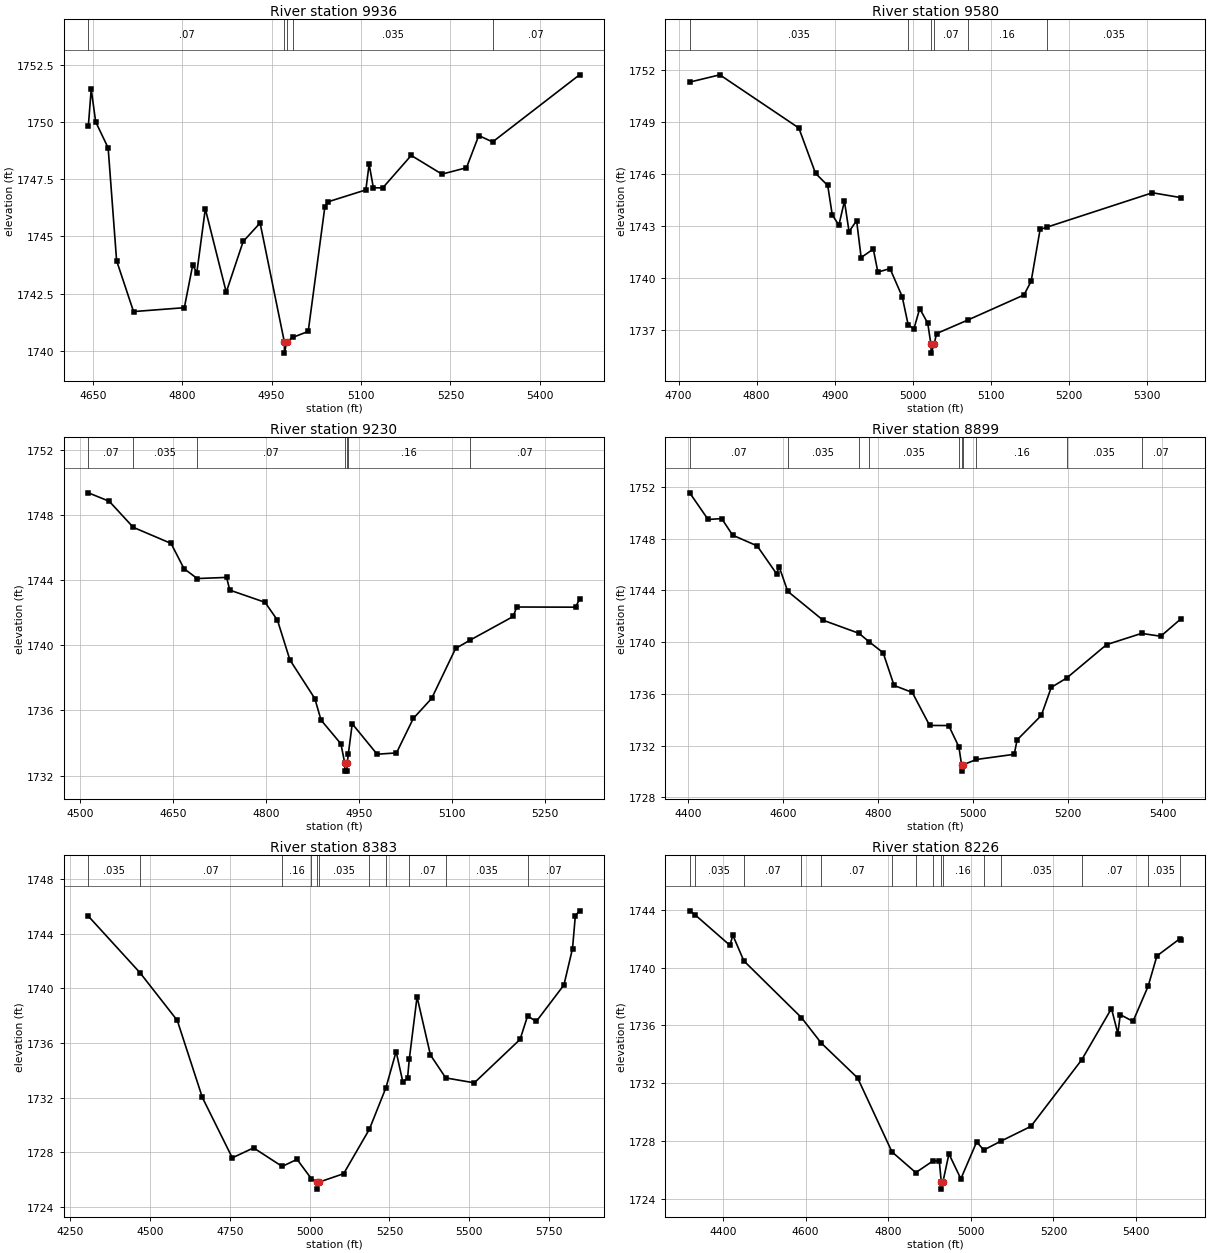
Type RM Length L Ch R = 1 ,9936    ,356,356,356
BEGIN DESCRIPTION:
Mapping XS d172af92
END DESCRIPTION:
XS GIS Cut Line= 4
      1549508.18      6869827.87      1549751.66      6870098.69
      1549877.96      6870157.28      1550189.11      6870080.47
#Sta/Elev= 30
  4642.7 1749.84  4647.5 1751.45    4655 1750.02  4675.9 1748.88  4690.1 1743.94
  4718.5 1741.71  4803.7 1741.88  4817.7 1743.74  4824.7 1743.42  4838.9 1746.21
    4874 1742.56  4902.4 1744.78  4930.8 1745.59  4971.4 1740.39  4971.7 1739.89
  4975.4 1740.39  4985.6 1740.58  5011.5 1740.84  5039.5 1746.31    5045 1746.52
  5108.2 1747.04  5113.7 1748.17  5120.8 1747.13  5136.6 1747.13  5184.3 1748.55
  5235.8 1747.73    5277 1748.01  5297.6 1749.42  5320.8 1749.14  5466.6 1752.08
#Mann= 5 ,-1 , 0
  4642.7     .07       0  4971.4    .035       0  4975.4     .07       0
  4985.6    .035       0  5320.8     .07       0
Bank Sta=4971.4,4975.4
XS Rating Curve= 0 ,0
Exp/Cntr=0.3,0.1

Type RM Length L Ch R = 1 ,9580    ,350,350,350
BEGIN DESCRIPTION:
Mapping XS e5116be5
END DESCRIPTION:
XS GIS Cut Line= 3
      1549220.82      6870080.88      1549465.63      6870226.73
      1549800.39      6870306.51
#Sta/Elev= 30
  4714.3 1751.31  4752.9 1751.73  4854.1 1748.66  4875.5 1746.04  4891.1 1745.34
  4896.9 1743.64  4905.4 1743.05  4912.5 1744.44  4918.4 1742.68  4928.1 1743.31
  4933.9 1741.18  4949.5 1741.67  4955.3 1740.34  4970.9 1740.54  4986.5 1738.92
  4994.1  1737.3  5001.5 1737.06  5008.9 1738.23  5019.2 1737.39  5023.3 1736.16
  5023.6 1735.66  5027.3 1736.16  5030.5 1736.79  5070.5 1737.57  5142.5 1739.02
  5151.7 1739.82  5163.1  1742.8  5171.6 1742.93    5307 1744.92  5343.4 1744.64
#Mann= 6 ,-1 , 0
  4714.3    .035       0  4994.1     .07       0  5023.3     .07       0
  5027.3     .07       0  5070.5     .16       0  5171.6    .035       0
Bank Sta=5023.3,5027.3
XS Rating Curve= 0 ,0
Exp/Cntr=0.3,0.1

Type RM Length L Ch R = 1 ,9230    ,331,331,331
BEGIN DESCRIPTION:
Mapping XS f49ddfa7
END DESCRIPTION:
XS GIS Cut Line= 3
      1549021.43      6870588.48      1549520.54      6870532.06
      1549790.93      6870423.91
#Sta/Elev= 30
  4512.9 1749.38  4546.7 1748.86  4585.4 1747.26  4646.5 1746.27  4667.4 1744.72
  4688.8 1744.11  4736.3 1744.18  4741.3  1743.4  4798.3 1742.65  4818.4 1741.55
  4838.5 1739.11  4878.8 1736.73  4888.8 1735.41  4920.9 1733.95  4927.1 1732.77
  4927.3 1732.27  4930.8 1732.27  4931.1 1732.77    4933 1733.34  4939.2 1735.18
  4979.4 1733.31  5010.7 1733.39  5037.9 1735.51  5067.5 1736.74  5106.2 1739.81
  5129.9 1740.33  5199.4 1741.78  5204.8 1742.36    5300 1742.35  5306.4 1742.84
#Mann= 7 ,-1 , 0
  4512.9     .07       0  4585.4    .035       0  4688.8     .07       0
  4927.1     .07       0  4931.1     .07       0    4933     .16       0
  5129.9     .07       0
Bank Sta=4927.1,4931.1
XS Rating Curve= 0 ,0
Exp/Cntr=0.3,0.1

Type RM Length L Ch R = 1 ,8899    ,516,516,516
BEGIN DESCRIPTION:
Mapping XS c56ce64f
END DESCRIPTION:
XS GIS Cut Line= 3
      1548997.54      6871070.26      1549533.99      6870828.07
      1549784.01      6870458.25
#Sta/Elev= 30
  4403.8 1751.53  4442.6 1749.47  4471.2 1749.54  4494.3 1748.26    4546 1747.43
  4586.8 1745.28  4592.3 1745.82  4610.4 1743.92  4684.8 1741.69  4760.3 1740.68
  4782.4 1740.01  4811.4 1739.18  4834.5 1736.65  4872.8 1736.11  4909.4 1733.56
  4949.6 1733.55    4971 1731.91  4976.7 1730.53    4977 1730.03  4980.7 1730.53
  5007.9 1730.93  5087.7 1731.33  5093.7 1732.44  5144.7 1734.33  5165.7  1736.5
  5198.5 1737.23  5282.2  1739.8    5356 1740.67  5396.4 1740.45  5438.8 1741.79
#Mann= 10 ,-1 , 0
  4403.8     .07       0  4610.4    .035       0  4760.3     .07       0
  4782.4    .035       0    4971     .07       0  4976.7     .07       0
  4980.7     .07       0  5007.9     .16       0  5198.5    .035       0
    5356     .07       0
Bank Sta=4976.7,4980.7
XS Rating Curve= 0 ,0
Exp/Cntr=0.3,0.1

Type RM Length L Ch R = 1 ,8383    ,157,157,157
BEGIN DESCRIPTION:
Mapping XS bba5fd00
END DESCRIPTION:
XS GIS Cut Line= 3
      1549326.36      6871403.93      1549899.27      6871035.88
      1550385.38      6870329.29
#Sta/Elev= 30
  4306.9 1745.28  4468.3 1741.15  4585.4 1737.65    4664 1732.01  4757.8 1727.59
  4824.5 1728.32  4914.1 1726.96  4960.6 1727.48  5005.9 1726.05  5024.1  1725.8
  5024.3  1725.3  5028.1  1725.8  5106.6 1726.43  5187.2 1729.68  5239.2 1732.73
    5271 1735.37  5291.9 1733.16  5306.8 1733.42  5312.3 1734.82  5336.6 1739.37
  5378.5 1735.12  5426.4 1733.44  5515.9 1733.08  5659.3 1736.26  5682.9 1737.98
    5710 1737.57  5796.6 1740.24  5823.6 1742.91  5832.4 1745.31  5845.5 1745.67
#Mann= 11 ,-1 , 0
  4306.9    .035       0  4468.3     .07       0  4914.1     .16       0
  5005.9    .035       0  5024.1     .07       0  5028.1    .035       0
  5187.2     .07       0  5239.2    .035       0  5312.3     .07       0
  5426.4    .035       0  5682.9     .07       0
Bank Sta=5024.1,5028.1
XS Rating Curve= 0 ,0
Exp/Cntr=0.3,0.1

Type RM Length L Ch R = 1 ,8226    ,374,374,374
BEGIN DESCRIPTION:
Mapping XS 93eed391
END DESCRIPTION:
XS GIS Cut Line= 3
      1549355.86      6871435.63      1549967.85      6871166.53
      1550410.32      6870893.24
#Sta/Elev= 30
  4319.7 1743.91  4332.5 1743.64  4417.1 1741.53  4424.1 1742.23  4450.7 1740.46
  4590.2 1736.54  4637.7  1734.8  4726.1 1732.38  4809.2 1727.28  4866.8 1725.85
  4908.7 1726.66  4923.8 1726.64  4928.5 1725.21  4928.8 1724.71  4932.5 1725.21
  4947.1 1727.14  4975.9 1725.42  5014.1 1727.96  5031.5 1727.41  5072.1 1728.01
  5145.4 1729.04  5268.3 1733.63  5340.4 1737.17  5355.8 1735.44  5361.7 1736.75
  5392.5 1736.28    5429  1738.7  5450.4  1740.8  5505.2 1741.97  5508.3 1741.93
#Mann= 15 ,-1 , 0
  4319.7     .07       0  4332.5    .035       0  4450.7     .07       0
  4590.2     .16       0  4637.7     .07       0  4809.2     .16       0
  4866.8     .07       0  4908.7     .16       0  4928.5     .07       0
  4932.5     .16       0  5031.5     .07       0  5072.1    .035       0
  5268.3     .07       0    5429    .035       0  5505.2     .07       0
Bank Sta=4928.5,4932.5
XS Rating Curve= 0 ,0
Exp/Cntr=0.3,0.1

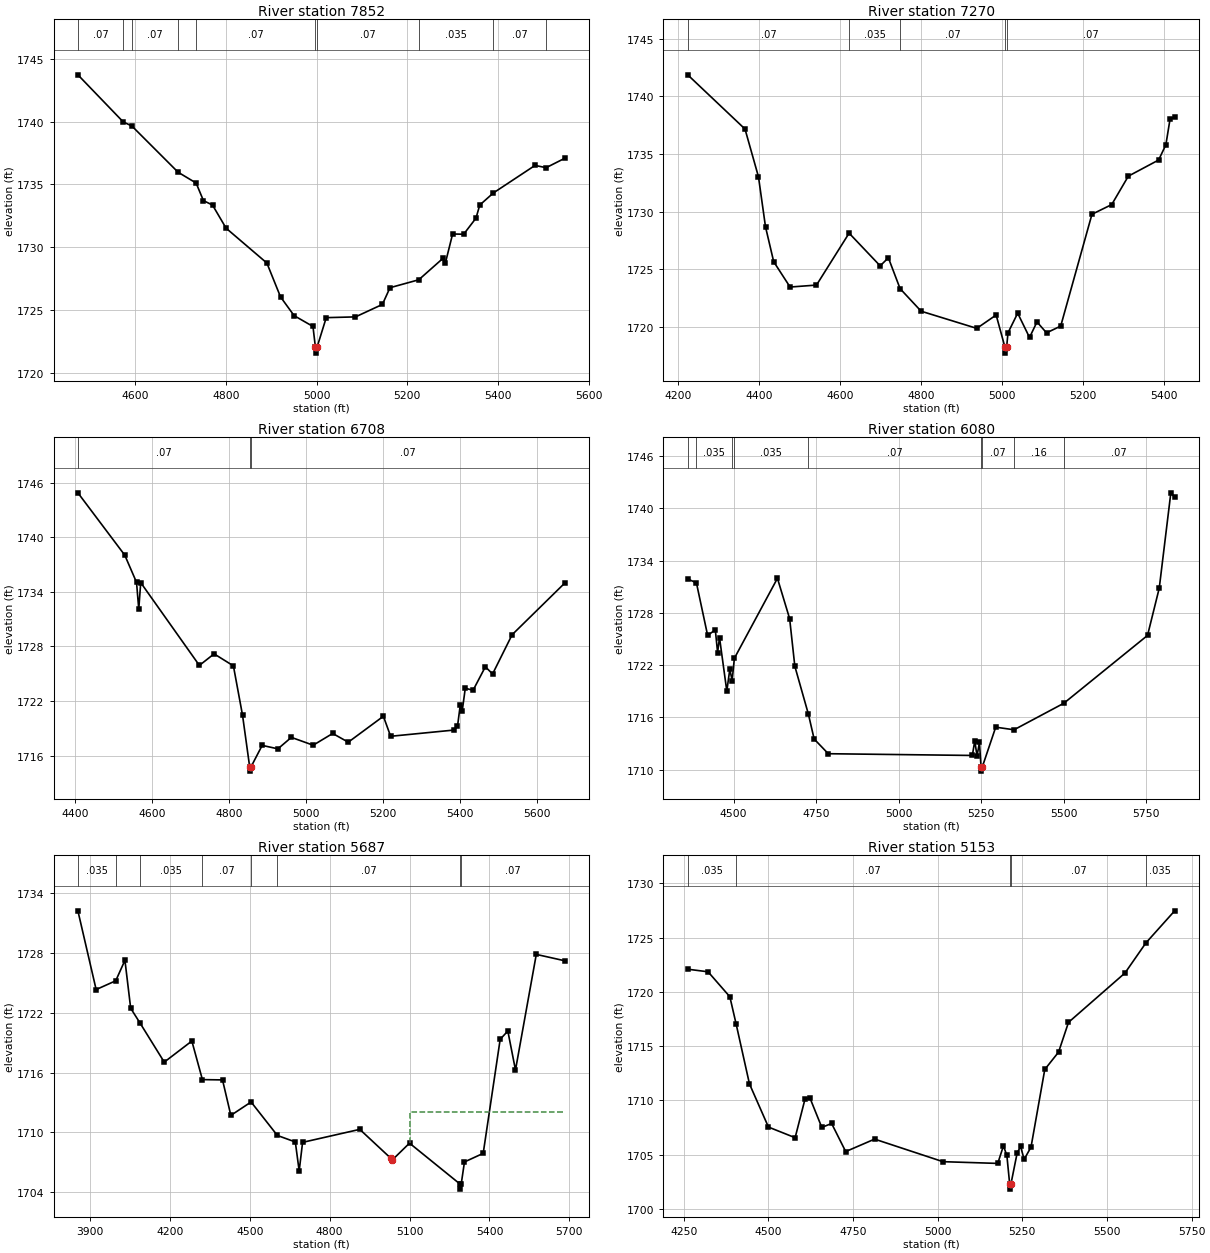
Type RM Length L Ch R = 1 ,7852    ,582,582,582
BEGIN DESCRIPTION:
Mapping XS f45aba95
END DESCRIPTION:
XS GIS Cut Line= 3
      1549378.04      6871490.96      1549896.67      6871475.77
      1550434.89      6871336.88
#Sta/Elev= 30
    4473 1743.71    4573 1739.97  4592.2 1739.64  4694.1 1735.97  4733.9 1735.11
  4750.1 1733.71  4770.1 1733.36  4800.1 1731.52  4890.1 1728.75  4920.2 1726.06
  4950.2 1724.57  4991.8 1723.71  4997.1 1722.09  4997.4 1721.59  5001.1 1722.09
  5021.1 1724.41  5085.6 1724.47    5145 1725.46  5161.8 1726.79  5225.3 1727.42
  5278.6 1729.12  5283.8 1728.72    5300 1731.06  5324.4 1731.04  5351.6 1732.32
  5359.9 1733.36  5389.9 1734.32  5481.9 1736.51  5506.4 1736.33  5547.7 1737.08
#Mann= 10 ,-1 , 0
    4473     .07       0    4573    .035       0  4592.2     .07       0
  4694.1     .16       0  4733.9     .07       0  4997.1     .07       0
  5001.1     .07       0  5225.3    .035       0  5389.9     .07       0
  5506.4     .16       0
Bank Sta=4997.1,5001.1
XS Rating Curve= 0 ,0
Exp/Cntr=0.3,0.1

Type RM Length L Ch R = 1 ,7270    ,562,562,562
BEGIN DESCRIPTION:
Mapping XS a1c760bb
END DESCRIPTION:
XS GIS Cut Line= 4
      1549315.05      6871749.21      1549953.09      6871838.18
      1550291.63      6871979.24      1550476.12      6872022.65
#Sta/Elev= 30
  4224.8 1741.88  4366.1 1737.17  4399.3 1733.02  4416.6 1728.68  4436.8 1725.65
  4477.2 1723.45  4542.3 1723.62  4622.7 1728.13  4699.3 1725.29  4719.5 1725.99
  4748.4 1723.31  4800.3 1721.35  4937.5 1719.86  4985.2 1721.02    5007 1718.21
  5007.3 1717.71    5011 1718.21  5014.4 1719.47  5038.3 1721.18  5067.5 1719.07
  5085.9 1720.42  5109.4 1719.47  5144.4 1720.06  5221.4 1729.77  5270.1 1730.61
  5311.1 1733.08  5385.7 1734.48  5403.6  1735.8  5413.9 1738.03  5425.3 1738.21
#Mann= 5 ,-1 , 0
  4224.8     .07       0  4622.7    .035       0  4748.4     .07       0
    5007     .07       0    5011     .07       0
Bank Sta=5007,5011
XS Rating Curve= 0 ,0
Exp/Cntr=0.3,0.1

Type RM Length L Ch R = 1 ,6708    ,628,628,628
BEGIN DESCRIPTION:
Mapping XS 72fd994b
END DESCRIPTION:
XS GIS Cut Line= 3
      1549215.67      6872070.82      1549795.54      6872190.61
      1550460.22      6872077.81
#Sta/Elev= 30
  4406.3 1744.88  4528.2 1738.03  4558.8 1735.04  4564.6 1732.09  4569.7 1735.01
  4722.2 1725.91  4760.5 1727.18  4810.7 1725.86  4834.5 1720.42  4852.9 1714.79
  4853.2 1714.29  4856.9 1714.79  4885.5 1717.12  4926.4 1716.74  4961.4    1718
  5018.2 1717.14  5068.9 1718.43  5109.4 1717.47  5200.7 1720.32  5219.6 1718.12
  5383.3  1718.8  5393.4  1719.2  5400.5 1721.51  5405.6 1720.87  5413.7  1723.4
    5434 1723.18  5465.9 1725.76  5484.7 1724.97  5535.4 1729.28  5672.6 1734.97
#Mann= 3 ,-1 , 0
  4406.3     .07       0  4852.9     .07       0  4856.9     .07       0
Bank Sta=4852.9,4856.9
XS Rating Curve= 0 ,0
Exp/Cntr=0.3,0.1

Type RM Length L Ch R = 1 ,6080    ,393,393,393
BEGIN DESCRIPTION:
MULBERRY CREEK TRIBUTARY 11 7.0
END DESCRIPTION:
XS GIS Cut Line= 3
      1549253.01      6872406.33       1549803.2      6872731.89
      1550415.18      6872162.05
#Sta/Elev= 30
  4360.7 1731.89  4387.1 1731.45  4421.1 1725.41  4444.4 1726.05  4451.3 1723.44
  4457.1 1725.16  4479.2 1719.01  4488.3 1721.52  4495.4 1720.23  4502.1 1722.78
  4632.6 1731.97  4669.6 1727.33  4685.3 1721.87  4726.5 1716.35  4743.8 1713.51
  4786.6 1711.82  5223.2 1711.62  5230.5  1713.3  5237.4 1711.56  5244.7 1713.12
  5249.5 1710.32  5249.8 1709.82  5253.5 1710.32    5294 1714.87  5349.5 1714.57
  5500.5 1717.62    5754 1725.41  5789.5 1730.84  5824.6 1741.79  5836.2 1741.28
#Mann= 9 ,-1 , 0
  4360.7     .07       0  4387.1    .035       0  4495.4     .07       0
  4502.1    .035       0  4726.5     .07       0  5249.5     .07       0
  5253.5     .07       0  5349.5     .16       0  5500.5     .07       0
Bank Sta=5249.5,5253.5
XS Rating Curve= 0 ,0
Exp/Cntr=0.3,0.1

Type RM Length L Ch R = 1 ,5687    ,534,534,534
BEGIN DESCRIPTION:
MULBERRY CREEK TRIBUTARY 11 6.0
END DESCRIPTION:
XS GIS Cut Line= 3
      1548693.36       6872487.4      1549688.07      6873054.48
      1550214.19      6873490.01
#Sta/Elev= 30
    3855 1732.18  3923.5  1724.3  3997.1 1725.18  4031.6 1727.23  4053.2 1722.43
  4088.5 1720.94  4179.2 1717.04  4282.8 1719.15  4322.4 1715.29  4397.9 1715.26
  4429.2 1711.71  4505.2 1713.05  4603.9  1709.7  4671.2 1709.05  4685.7 1706.15
  4698.5 1709.01  4913.2 1710.31  5028.8 1707.44  5035.2 1707.25  5099.9 1708.93
  5289.9 1704.83  5290.1 1704.33  5293.9 1704.83  5306.2 1707.05  5376.5 1707.91
  5440.3 1719.33    5469 1720.15  5497.7 1716.25  5575.8 1727.82    5683 1727.18
#Mann= 8 ,-1 , 0
    3855    .035       0  3997.1     .07       0  4088.5    .035       0
  4322.4     .07       0  4505.2    .035       0  4603.9     .07       0
  5289.9     .07       0  5293.9     .07       0
#XS Ineff= 2 , 0
       0                 5099.91       0    1712
Permanent Ineff=
       F       F
Bank Sta=5028.8,5035.2
XS Rating Curve= 0 ,0
Exp/Cntr=0.3,0.1

Type RM Length L Ch R = 1 ,5153    ,293,293,293
BEGIN DESCRIPTION:
MULBERRY CREEK TRIBUTARY 11 5.0
END DESCRIPTION:
XS GIS Cut Line= 3
      1549016.28      6872921.41      1549391.96      6873406.92
      1550201.89      6873560.81
#Sta/Elev= 30
  4261.5 1722.09  4321.7 1721.85    4386 1719.55  4404.6 1717.03  4443.9 1711.52
    4500 1707.54  4578.8 1706.56  4607.8  1710.1  4622.3 1710.24  4657.6 1707.51
  4686.6 1707.87  4728.2 1705.28  4813.5 1706.43  5015.5 1704.35  5177.3 1704.19
    5194  1705.8  5204.2 1704.93  5212.4 1702.32  5212.6 1701.82  5216.4 1702.32
  5234.7 1705.17  5244.9 1705.75  5255.1 1704.56  5275.5 1705.69  5316.2 1712.85
  5356.9 1714.45  5386.2 1717.19  5553.1 1721.74  5614.8 1724.51  5699.8 1727.47
#Mann= 5 ,-1 , 0
  4261.5    .035       0  4404.6     .07       0  5212.4     .07       0
  5216.4     .07       0  5614.8    .035       0
Bank Sta=5212.4,5216.4
XS Rating Curve= 0 ,0
Exp/Cntr=0.3,0.1

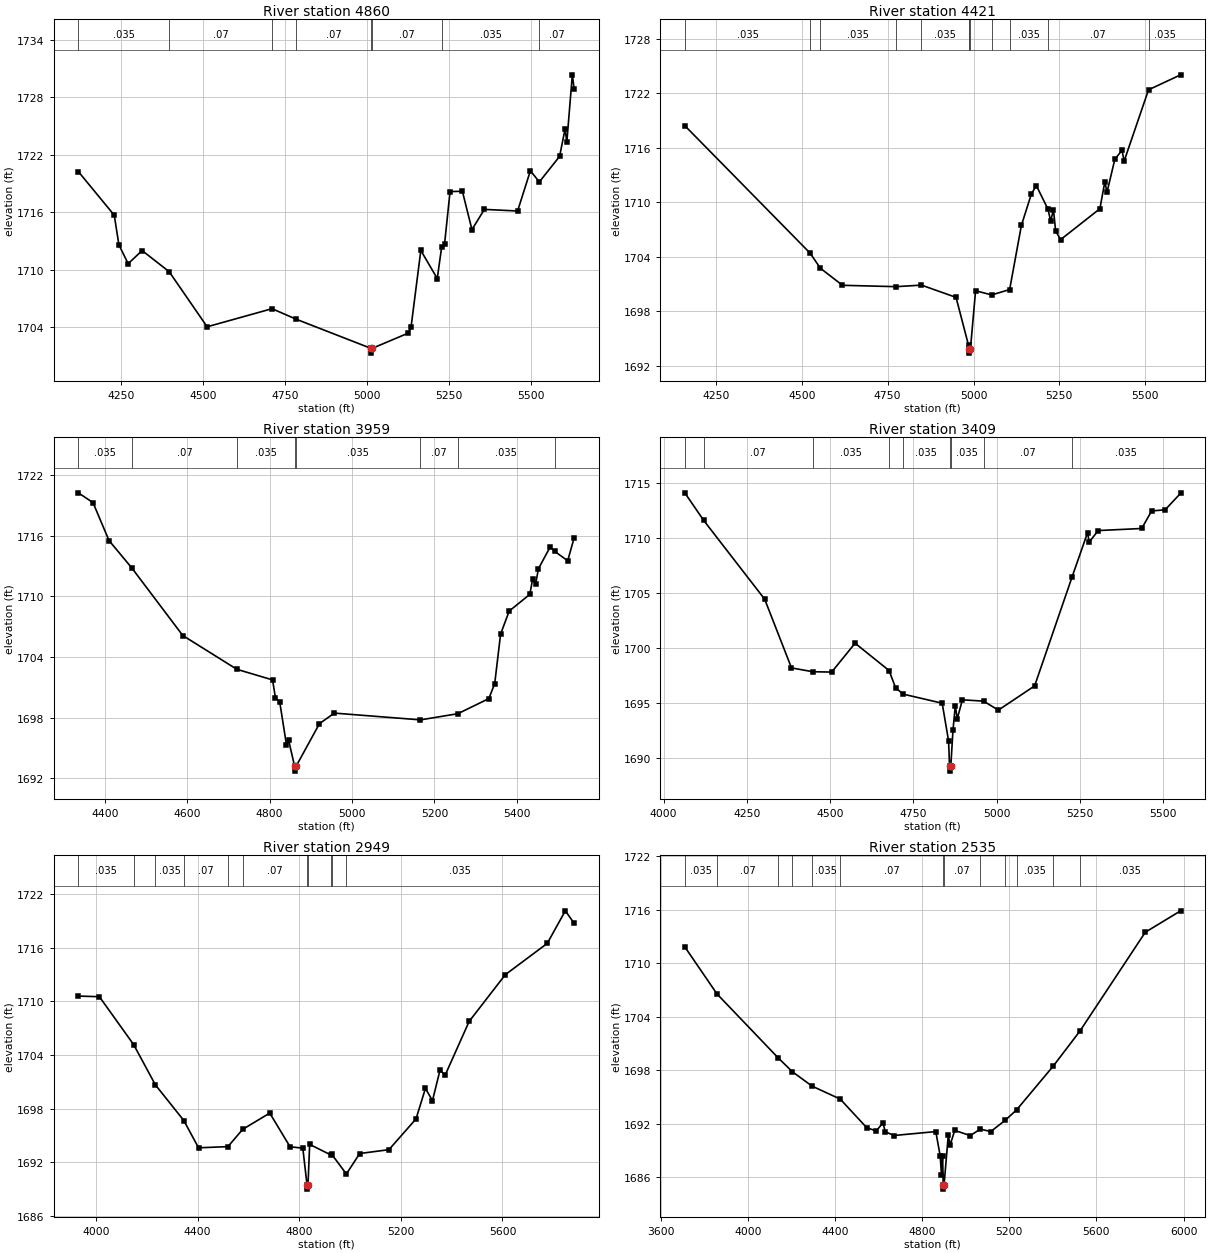
Type RM Length L Ch R = 1 ,4860    ,439,439,439
BEGIN DESCRIPTION:
MULBERRY CREEK TRIBUTARY 11 4.0
END DESCRIPTION:
XS GIS Cut Line= 3
      1548959.69      6873057.98      1549555.37      6873708.16
      1550119.71      6873993.11
#Sta/Elev= 30
  4118.2 1720.23  4227.9 1715.67  4242.1 1712.57  4270.4 1710.61    4313 1711.98
  4395.7 1709.77  4511.5 1704.02  4709.7 1705.91  4783.5 1704.81  5011.6 1701.77
  5011.8 1701.27  5015.6 1701.77    5125 1703.35    5134 1703.95    5164 1711.99
  5214.2 1709.06  5227.6 1712.35  5236.5 1712.68  5253.2 1718.14  5290.9 1718.17
  5320.1 1714.17  5358.1 1716.28  5459.5 1716.11  5498.5 1720.31  5525.9 1719.15
  5587.7 1721.81  5604.3 1724.65  5609.9 1723.34  5626.6 1730.33  5632.2 1728.84
#Mann= 8 ,-1 , 0
  4118.2    .035       0  4395.7     .07       0  4709.7    .035       0
  4783.5     .07       0  5011.6     .07       0  5015.6     .07       0
  5227.6    .035       0  5525.9     .07       0
Bank Sta=5011.6,5015.6
XS Rating Curve= 0 ,0
Exp/Cntr=0.3,0.1

Type RM Length L Ch R = 1 ,4421    ,462,462,462
BEGIN DESCRIPTION:
Mapping XS 8597a87c
END DESCRIPTION:
XS GIS Cut Line= 3
      1548912.08      6873105.46      1549221.97       6873894.5
      1549695.94      6874256.49
#Sta/Elev= 30
  4159.1 1718.43  4524.1 1704.39    4554 1702.73  4618.4 1700.85  4774.2  1700.7
  4848.4 1700.87  4949.1 1699.52  4985.5 1694.24  4987.1 1693.88  4987.3 1693.38
  4991.1 1693.88    5006 1700.25  5052.8 1699.79  5105.2 1700.38  5139.4 1707.44
  5168.5 1710.91    5183 1711.83  5216.8 1709.24  5224.7 1707.94  5232.9 1709.16
  5239.2 1706.83  5253.7 1705.88    5368 1709.28  5382.5 1712.25  5388.8  1711.1
  5411.6 1714.73  5432.4 1715.72  5438.7 1714.53  5509.7 1722.38  5603.2 1724.03
#Mann= 12 ,-1 , 0
  4159.1    .035       0  4524.1     .07       0    4554    .035       0
  4774.2     .07       0  4848.4    .035       0  4985.5     .07       0
  4987.1    .035       0  4991.1     .07       0  5052.8     .07       0
  5105.2    .035       0  5216.8     .07       0  5509.7    .035       0
Bank Sta=4987.1,4991.1
XS Rating Curve= 0 ,0
Exp/Cntr=0.3,0.1

Type RM Length L Ch R = 1 ,3959    ,550,550,550
BEGIN DESCRIPTION:
Mapping XS 76af4b6d
END DESCRIPTION:
XS GIS Cut Line= 4
      1548640.37      6873358.17       1548786.2        6873866.
      1548879.95      6873975.37      1549273.21      6874332.16
#Sta/Elev= 30
  4335.8 1720.27  4371.4  1719.3  4410.3 1715.54  4465.5 1712.83  4589.3 1706.13
  4720.6 1702.78  4807.2 1701.73  4814.2 1699.96  4824.6 1699.55    4841 1695.28
  4846.2 1695.75  4860.6 1693.19  4860.8 1692.69  4864.6 1693.19  4921.1  1697.4
  4957.3 1698.44  5166.2 1697.77  5256.9 1698.38  5332.2 1699.88  5346.4 1701.37
  5360.6 1706.26  5381.5 1708.55  5431.6 1710.21  5438.3 1711.69  5445.8 1711.26
  5452.5 1712.75  5480.9  1714.9  5492.2 1714.46  5523.5 1713.54  5539.2 1715.82
#Mann= 8 ,-1 , 0
  4335.8    .035       0  4465.5     .07       0  4720.6    .035       0
  4860.6    .035       0  4864.6    .035       0  5166.2     .07       0
  5256.9    .035       0  5492.2     .07       0
Bank Sta=4860.6,4864.6
XS Rating Curve= 0 ,0
Exp/Cntr=0.3,0.1

Type RM Length L Ch R = 1 ,3409    ,460,460,460
BEGIN DESCRIPTION:
Mapping XS 4cf90e37
END DESCRIPTION:
XS GIS Cut Line= 4
      1548490.92      6873479.45      1548577.72      6874264.99
      1548658.02       6874395.2      1549201.31      6874451.48
#Sta/Elev= 30
  4063.6 1714.14  4120.5 1711.62  4303.6 1704.44  4384.1 1698.18  4448.3 1697.83
  4504.8  1697.8  4575.2 1700.43  4677.2 1697.94  4696.8 1696.37  4719.6 1695.79
  4836.8 1694.96  4856.1 1691.51  4858.8 1689.27    4859 1688.77  4862.8 1689.27
  4869.2 1692.49  4876.2 1694.72  4882.1 1693.54  4897.5 1695.27  4961.3 1695.15
  5005.6 1694.33  5114.5 1696.54  5226.8 1706.45  5273.5 1710.51  5278.5 1709.65
  5305.5  1710.7  5436.2 1710.89  5466.1 1712.49  5506.5 1712.59  5553.1  1714.1
#Mann= 9 ,-1 , 0
  4063.6    .035       0  4120.5     .07       0  4448.3    .035       0
  4677.2     .07       0  4719.6    .035       0  4858.8     .07       0
  4862.8    .035       0  4961.3     .07       0  5226.8    .035       0
Bank Sta=4858.8,4862.8
XS Rating Curve= 0 ,0
Exp/Cntr=0.3,0.1

Type RM Length L Ch R = 1 ,2949    ,414,414,414
BEGIN DESCRIPTION:
Mapping XS 1c49e994
END DESCRIPTION:
XS GIS Cut Line= 4
      1548315.14      6873425.15      1548278.24      6874330.09
      1548320.36      6874488.28      1548840.86       6875200.7
#Sta/Elev= 30
  3930.6 1710.59  4013.5 1710.52  4148.5 1705.16  4233.8 1700.67  4345.8 1696.68
  4403.8 1693.63  4519.5 1693.76  4577.4 1695.69  4684.1 1697.51  4764.1 1693.74
  4814.2 1693.59  4830.7 1689.51    4831 1689.01  4834.7 1689.51  4841.2 1694.01
  4923.3 1692.85  4927.9 1692.91  4985.7  1690.7  5038.1 1692.99  5153.2 1693.42
  5259.8 1696.86  5296.9 1700.27  5324.6  1698.9    5354 1702.29  5374.8 1701.77
    5469 1707.76  5611.2 1712.98  5776.4 1716.48  5847.5 1720.12  5882.3 1718.73
#Mann= 11 ,-1 , 0
  3930.6    .035       0  4148.5     .07       0  4233.8    .035       0
  4345.8     .07       0  4519.5    .035       0  4577.4     .07       0
  4830.7    .035       0  4834.7     .07       0  4923.3    .035       0
  4927.9     .07       0  4985.7    .035       0
Bank Sta=4830.7,4834.7
XS Rating Curve= 0 ,0
Exp/Cntr=0.3,0.1

Type RM Length L Ch R = 1 ,2535    ,300,300,300
BEGIN DESCRIPTION:
Mapping XS 8039d7e8
END DESCRIPTION:
XS GIS Cut Line= 3
      1548082.21      6873418.09       1547908.6       6874594.3
      1548798.37      6875219.31
#Sta/Elev= 30
  3710.5 1711.84  3858.5 1706.56    4138 1699.43  4204.2 1697.85    4295 1696.23
  4424.2 1694.78  4545.9 1691.57  4589.8 1691.21  4620.6 1692.14  4630.3 1691.13
  4670.7  1690.7  4862.8 1691.14    4883 1688.41  4888.9 1686.26    4894 1688.44
  4896.8 1685.19    4897 1684.69  4900.8 1685.19  4920.1 1690.72  4928.8 1689.64
  4949.7 1691.27  5021.2 1690.69  5067.3 1691.42    5115 1691.14  5180.6 1692.39
  5233.4 1693.56    5403 1698.51  5525.5 1702.44  5824.6 1713.48  5986.8 1715.88
#Mann= 13 ,-1 , 0
  3710.5    .035       0  3858.5     .07       0    4138    .035       0
  4204.2     .07       0    4295    .035       0  4424.2     .07       0
  4896.8     .07       0  4900.8     .07       0  5067.3    .035       0
  5180.6     .07       0  5233.4    .035       0    5403     .07       0
  5525.5    .035       0
Bank Sta=4896.8,4900.8
XS Rating Curve= 0 ,0
Exp/Cntr=0.3,0.1

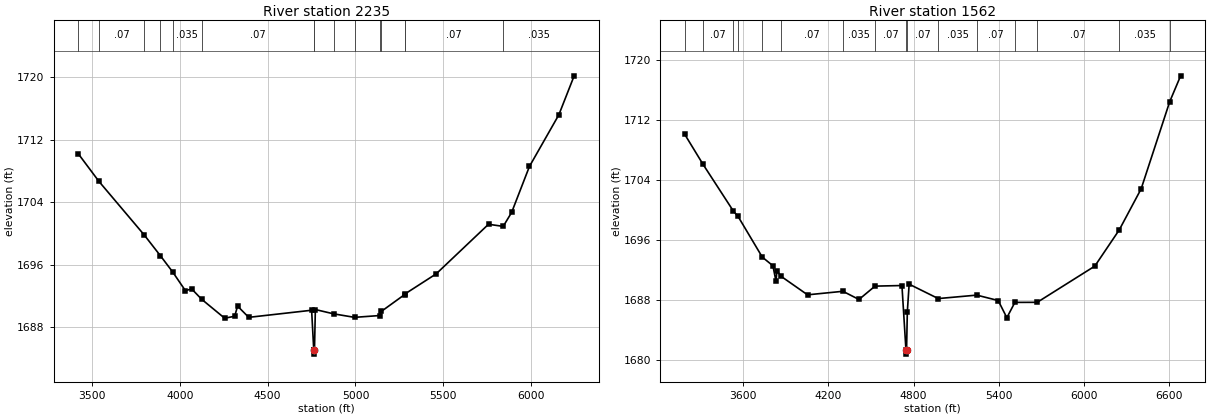
Type RM Length L Ch R = 1 ,2235    ,673,673,673
BEGIN DESCRIPTION:
Mapping XS 9aae9190
END DESCRIPTION:
XS GIS Cut Line= 4
      1548030.12      6873461.51      1547609.12       6874681.1
       1548134.3      6875206.28      1548809.64      6875613.22
#Sta/Elev= 30
    3423 1710.21  3540.6 1706.67  3798.7  1699.8    3890 1697.16  3959.3  1695.1
  4031.9  1692.7  4068.4  1692.9  4125.1 1691.58  4255.6 1689.16  4312.7 1689.41
  4329.1 1690.71  4392.6 1689.27  4750.5 1690.18  4762.7 1685.06  4762.9 1684.56
  4766.7 1685.06  4771.7 1690.27  4875.4 1689.72  4994.6 1689.27    5137  1689.5
  5147.7 1690.04  5279.3 1692.18  5282.7 1692.28  5459.3 1694.84    5757 1701.19
  5840.7 1700.92  5888.7 1702.71    5990  1708.6  6157.3 1715.21  6244.4  1720.2
#Mann= 15 ,-1 , 0
    3423    .035       0  3540.6     .07       0  3798.7    .035       0
    3890     .07       0  3959.3    .035       0  4125.1     .07       0
  4762.7     .07       0  4766.7     .07       0  4875.4    .035       0
  4994.6     .16       0    5137     .07       0  5147.7     .16       0
  5279.3    .035       0  5282.7     .07       0  5840.7    .035       0
Bank Sta=4762.7,4766.7
XS Rating Curve= 0 ,0
Exp/Cntr=0.3,0.1

Type RM Length L Ch R = 1 ,1562    ,0,0,0
BEGIN DESCRIPTION:
Mapping XS 4e114901
END DESCRIPTION:
XS GIS Cut Line= 4
      1548004.07      6873465.85      1547296.62      6874780.93
      1547418.15      6875479.71      1548689.87      6875714.09
#Sta/Elev= 30
  3187.2 1710.09  3314.9 1706.13  3530.4 1699.85  3562.9 1699.15  3733.5 1693.73
  3808.2 1692.58  3830.1 1690.53  3836.9  1691.9  3865.1 1691.18  4052.6  1688.7
  4301.9 1689.17  4415.2 1688.08  4528.3 1689.86  4718.1 1689.94  4746.6 1681.29
  4746.8 1680.79  4750.6 1681.29  4756.1 1686.44  4768.9 1690.12  4974.1  1688.2
  5245.7 1688.66  5396.7 1687.94  5457.7 1685.65  5514.4 1687.69  5671.9  1687.7
    6078 1692.53  6250.5 1697.37  6404.7 1702.84  6605.9 1714.46  6682.9 1717.91
#Mann= 16 ,-1 , 0
  3187.2    .035       0  3314.9     .07       0  3530.4    .035       0
  3562.9     .07       0  3733.5    .035       0  3865.1     .07       0
  4301.9    .035       0  4528.3     .07       0  4746.6    .035       0
  4750.6     .07       0  4974.1    .035       0  5245.7     .07       0
  5514.4     .16       0  5671.9     .07       0  6250.5    .035       0
  6605.9     .07       0
Bank Sta=4746.6,4750.6
XS Rating Curve= 0 ,0
Exp/Cntr=0.3,0.1

Chan Stop Cuts=-1
Use User Specified Reach Order=0
Composite Channel Slope=5