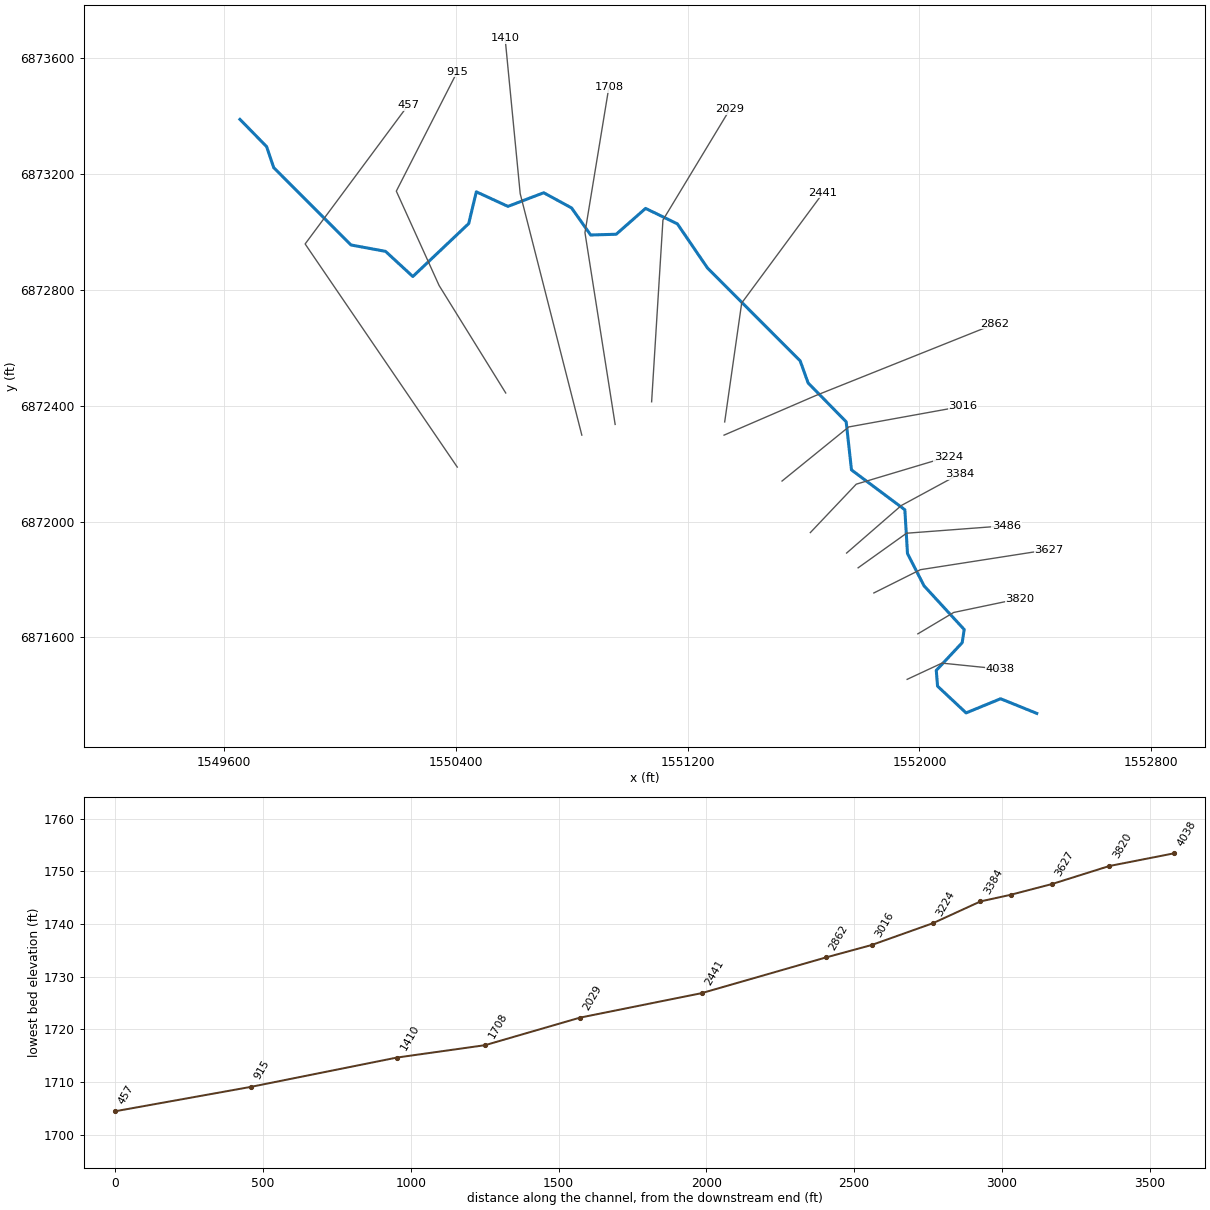
--- MULBERRY CREEK TRIBUTARY 11_1.prj (project) ---

Proj Title=MULBERRY CREEK TRIBUTARY 11_1 Base Level Engineering
Current Plan=p01
Default Exp/Contr=0.3,0.1
English Units
Geom File=g01
Flow File=f01
Plan File=p01
Y Axis Title=Elevation
X Axis Title(PF)=Main Channel Distance
X Axis Title(XS)=Station
BEGIN DESCRIPTION:
MULBERRY CREEK TRIBUTARY 11_1
END DESCRIPTION:
DSS Export Rating Curves= 0
DSS Export Rating Curve Sorted= 0
DSS Export Volume Flow Curves= 0
DXF OffsetX= 0
DXF OffsetY= 0
DXF ScaleX= 1
DXF ScaleY= 10

--- MULBERRY CREEK TRIBUTARY 11_1.p01 (plan) ---

Plan Title=Multiple Run
Short Identifier=Multiple
Geom File=g01
Flow File=f01
Subcritical Flow
K Sum by GR= 0
Std Step Tol= 0.01
Critical Tol= 0.01
Num of Std Step Trials= 20
Max Error Tol= 0.3
Flow Tol Ratio= 0.001
Split Flow NTrial= 30
Split Flow Tol= 0.02
Split Flow Ratio= 0.02
Log Output Level= 0
Friction Slope Method= 1
Unsteady Friction Slope Method= 2
Unsteady Bridges Friction Slope Method= 1
Parabolic Critical Depth
Global Vel Dist=  1 , 1 , 1
Global Log Level= 0
CheckData=True
Encroach Param= -1, 0, 0, 0
BEGIN DESCRIPTION:
Multiple Run
END DESCRIPTION:

--- MULBERRY CREEK TRIBUTARY 11_1.f01 (steady flow) ---

Flow Title=Multiple
Number of Profiles=7
Profile Names=10-year,25-year,50-year,1pct_min,100-year,1pct_plu,500-year
River Rch & RM= MULBERRY CREEK T,Reach-1,4038
      98     130     155      92     184     367     263
Boundary for River Rch & Prof#=MULBERRY CREEK T,Reach-1,1
Up Type=0
Dn Type=3
Dn Slope=0.005
Boundary for River Rch & Prof#=MULBERRY CREEK T,Reach-1,2
Up Type=0
Dn Type=3
Dn Slope=0.005
Boundary for River Rch & Prof#=MULBERRY CREEK T,Reach-1,3
Up Type=0
Dn Type=3
Dn Slope=0.005
Boundary for River Rch & Prof#=MULBERRY CREEK T,Reach-1,4
Up Type=0
Dn Type=3
Dn Slope=0.005
Boundary for River Rch & Prof#=MULBERRY CREEK T,Reach-1,5
Up Type=0
Dn Type=3
Dn Slope=0.005
Boundary for River Rch & Prof#=MULBERRY CREEK T,Reach-1,6
Up Type=0
Dn Type=3
Dn Slope=0.005
Boundary for River Rch & Prof#=MULBERRY CREEK T,Reach-1,7
Up Type=0
Dn Type=3
Dn Slope=0.005

--- MULBERRY CREEK TRIBUTARY 11_1.g01 (geometry) ---

Geom Title=Existing Conditions
Program Version=4.10

River Reach=MULBERRY CREEK T,Reach-1
Reach XY= 30
        1552405.        6871338.      1552279.99      6871388.46
      1552161.02      6871339.62      1552062.45      6871431.93
      1552058.11      6871486.35      1552147.52      6871581.96
      1552154.45      6871627.36      1552015.76      6871778.32
      1551958.76      6871889.56      1551949.64       6872040.7
      1551765.47      6872178.18      1551747.18      6872344.19
      1551615.78      6872478.32      1551588.35      6872554.67
      1551268.63      6872874.79       1551164.7      6873027.26
      1551054.92       6873080.7       1550953.5      6872991.48
      1550865.34      6872988.88      1550799.38      6873082.38
      1550703.31      6873134.67      1550579.99      6873087.62
      1550470.76      6873137.87      1550444.47      6873028.26
      1550251.67       6872845.6      1550157.43      6872932.45
      1550038.25      6872954.46      1549771.65      6873221.33
      1549746.89      6873294.07        1549655.        6873388.

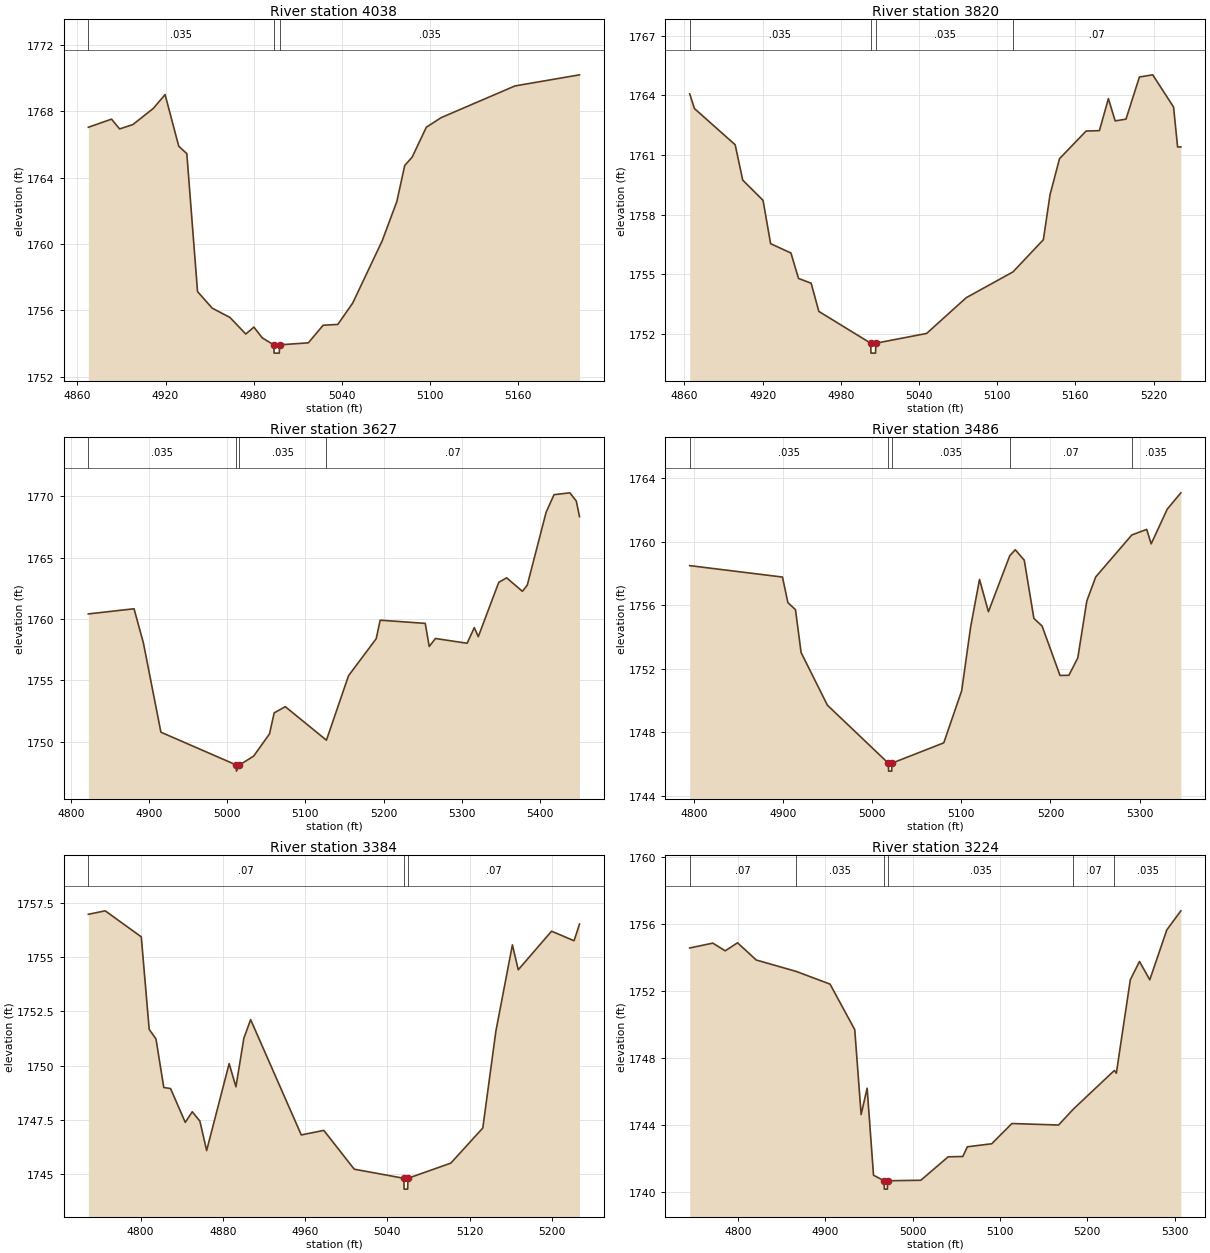
Type RM Length L Ch R = 1 ,4038    ,218,218,218
BEGIN DESCRIPTION:
MULBERRY CREEK TRIBUTARY 11_1 9.0
END DESCRIPTION:
XS GIS Cut Line= 3
      1551957.58      6871455.41      1552077.76      6871511.44
      1552278.82      6871490.96
#Sta/Elev= 30
  4867.4 1767.04  4883.2 1767.53  4888.7 1766.94  4897.7  1767.2  4911.6 1768.17
  4919.7 1769.01    4929  1765.9  4934.5 1765.45  4941.8 1757.14  4951.8 1756.14
  4963.9 1755.58  4974.7 1754.58  4980.2    1755  4985.9 1754.35  4993.7 1753.93
    4994 1753.43  4997.5 1753.43  4997.7 1753.93  5017.3 1754.05  5027.4 1755.11
  5037.4 1755.16  5047.5 1756.44  5067.6 1760.19  5077.6 1762.56    5083 1764.74
    5088 1765.23  5097.7 1767.04  5107.8 1767.62  5158.1 1769.53  5202.1  1770.2
#Mann= 3 ,-1 , 0
  4867.4    .035       0  4993.7    .035       0  4997.7    .035       0
Bank Sta=4993.7,4997.7
XS Rating Curve= 0 ,0
Exp/Cntr=0.3,0.1

Type RM Length L Ch R = 1 ,3820    ,193,193,193
BEGIN DESCRIPTION:
Mapping XS f09c643c
END DESCRIPTION:
XS GIS Cut Line= 3
      1551994.55      6871612.47      1552118.28      6871686.27
      1552346.16      6871734.02
#Sta/Elev= 30
    4864 1764.08  4867.7 1763.34  4898.9 1761.52  4904.7 1759.74  4920.3 1758.72
  4926.1 1756.54  4941.7 1756.07  4947.5 1754.79  4957.2 1754.55  4963.1 1753.13
  5002.9 1751.53  5003.1 1751.03  5006.6 1751.03  5006.9 1751.53  5045.8 1752.02
  5076.2 1753.82  5112.1 1755.12  5135.4 1756.74  5140.5    1759  5147.8 1760.82
  5168.2 1762.21  5178.4 1762.23  5185.3 1763.84  5190.5 1762.72  5198.8 1762.81
  5209.1 1764.93  5219.3 1765.04  5235.3 1763.42  5238.4 1761.41  5240.9 1761.41
#Mann= 4 ,-1 , 0
    4864    .035       0  5002.9    .035       0  5006.9    .035       0
  5112.1     .07       0
Bank Sta=5002.9,5006.9
XS Rating Curve= 0 ,0
Exp/Cntr=0.3,0.1

Type RM Length L Ch R = 1 ,3627    ,141,141,141
BEGIN DESCRIPTION:
Mapping XS 97f58da9
END DESCRIPTION:
XS GIS Cut Line= 3
      1551842.72      6871753.57      1552003.26      6871833.84
      1552447.19      6871903.14
#Sta/Elev= 30
  4822.1 1760.42  4880.6 1760.84  4892.6 1758.05    4915 1750.79  5011.5 1748.12
  5011.7 1747.62  5015.5 1748.12  5033.7 1748.84    5054 1750.65    5060 1752.36
  5074.2 1752.87  5126.9 1750.14  5155.2 1755.39  5190.6  1758.4  5195.7 1759.91
  5253.4 1759.65  5258.5 1757.77  5266.5 1758.42    5307 1758.03  5316.2  1759.3
  5321.3 1758.57  5347.5 1762.99  5357.6 1763.36  5377.8 1762.26    5384 1762.76
  5408.2 1768.71  5418.3 1770.13  5438.6 1770.28  5446.8 1769.61  5450.9 1768.34
#Mann= 4 ,-1 , 0
  4822.1    .035       0  5011.5    .035       0  5015.5    .035       0
  5126.9     .07       0
Bank Sta=5011.5,5015.5
XS Rating Curve= 0 ,0
Exp/Cntr=0.3,0.1

Type RM Length L Ch R = 1 ,3486    ,102,102,102
BEGIN DESCRIPTION:
Mapping XS a95c1d43
END DESCRIPTION:
XS GIS Cut Line= 3
      1551788.38      6871840.32      1551955.52      6871959.71
      1552300.24      6871985.73
#Sta/Elev= 30
  4795.3 1758.49  4899.4 1757.77  4905.5 1756.16    4914 1755.72  4920.3 1753.02
  4949.8 1749.71  5018.2 1746.06  5018.5 1745.56    5022 1745.56  5022.2 1746.06
  5080.4 1747.34  5100.5 1750.62  5110.5 1754.62  5120.5 1757.62  5130.5 1755.59
  5154.4 1759.11  5160.6 1759.49  5170.7 1758.83  5181.5 1755.17  5190.7 1754.69
  5210.8 1751.58  5220.8 1751.59  5230.8 1752.69  5240.9 1756.27  5250.9 1757.78
  5291.4 1760.42  5308.1 1760.77  5313.1 1759.86  5331.1 1762.04  5346.4 1763.07
#Mann= 5 ,-1 , 0
  4795.3    .035       0  5018.2    .035       0  5022.2    .035       0
  5154.4     .07       0  5291.4    .035       0
Bank Sta=5018.2,5022.2
XS Rating Curve= 0 ,0
Exp/Cntr=0.3,0.1

Type RM Length L Ch R = 1 ,3384    ,160,160,160
BEGIN DESCRIPTION:
Mapping XS eeff5452
END DESCRIPTION:
XS GIS Cut Line= 3
      1551748.69      6871891.29      1551937.53      6872055.38
      1552137.75      6872163.89
#Sta/Elev= 30
  4749.1 1756.98  4765.5 1757.14  4800.6 1755.94  4808.3 1751.67  4814.9 1751.23
  4822.5 1748.99  4829.1 1748.94  4843.4 1747.38  4850.2 1747.87  4857.6 1747.44
  4864.2 1746.08  4886.1 1750.09  4892.7 1749.02  4900.4 1751.26    4907 1752.12
  4956.3  1746.8  4978.2 1747.01  5007.8 1745.22  5056.1  1744.8  5056.3  1744.3
  5059.8  1744.3  5060.1  1744.8  5101.8  1745.5  5132.9 1747.12  5145.6 1751.58
  5161.7 1755.57  5167.4 1754.42  5199.8  1756.2  5221.7 1755.76    5227 1756.53
#Mann= 3 ,-1 , 0
  4749.1     .07       0  5056.1    .035       0  5060.1     .07       0
Bank Sta=5056.1,5060.1
XS Rating Curve= 0 ,0
Exp/Cntr=0.3,0.1

Type RM Length L Ch R = 1 ,3224    ,208,208,208
BEGIN DESCRIPTION:
Mapping XS c559e98a
END DESCRIPTION:
XS GIS Cut Line= 3
      1551623.51      6871961.91      1551781.91      6872128.98
      1552100.42      6872224.32
#Sta/Elev= 30
  4744.5 1754.59    4771 1754.88  4785.2 1754.42  4799.3  1754.9  4820.8 1753.87
  4866.5 1753.19  4905.3 1752.43  4933.6 1749.71  4940.9 1744.64  4947.8 1746.21
  4955.1 1741.01  4967.2 1740.68  4967.5 1740.18    4971 1740.18  4971.2 1740.68
  5009.3 1740.71  5040.6 1742.11  5057.4 1742.13  5062.6 1742.71  5090.5 1742.89
  5113.6  1744.1  5167.1 1744.01    5184 1744.96    5231 1747.27  5233.3 1747.11
  5249.3 1752.69  5259.8 1753.78  5271.6 1752.69  5291.1 1755.67  5307.2 1756.81
#Mann= 6 ,-1 , 0
  4744.5     .07       0  4866.5    .035       0  4967.2    .035       0
  4971.2    .035       0    5184     .07       0    5231    .035       0
Bank Sta=4967.2,4971.2
XS Rating Curve= 0 ,0
Exp/Cntr=0.3,0.1

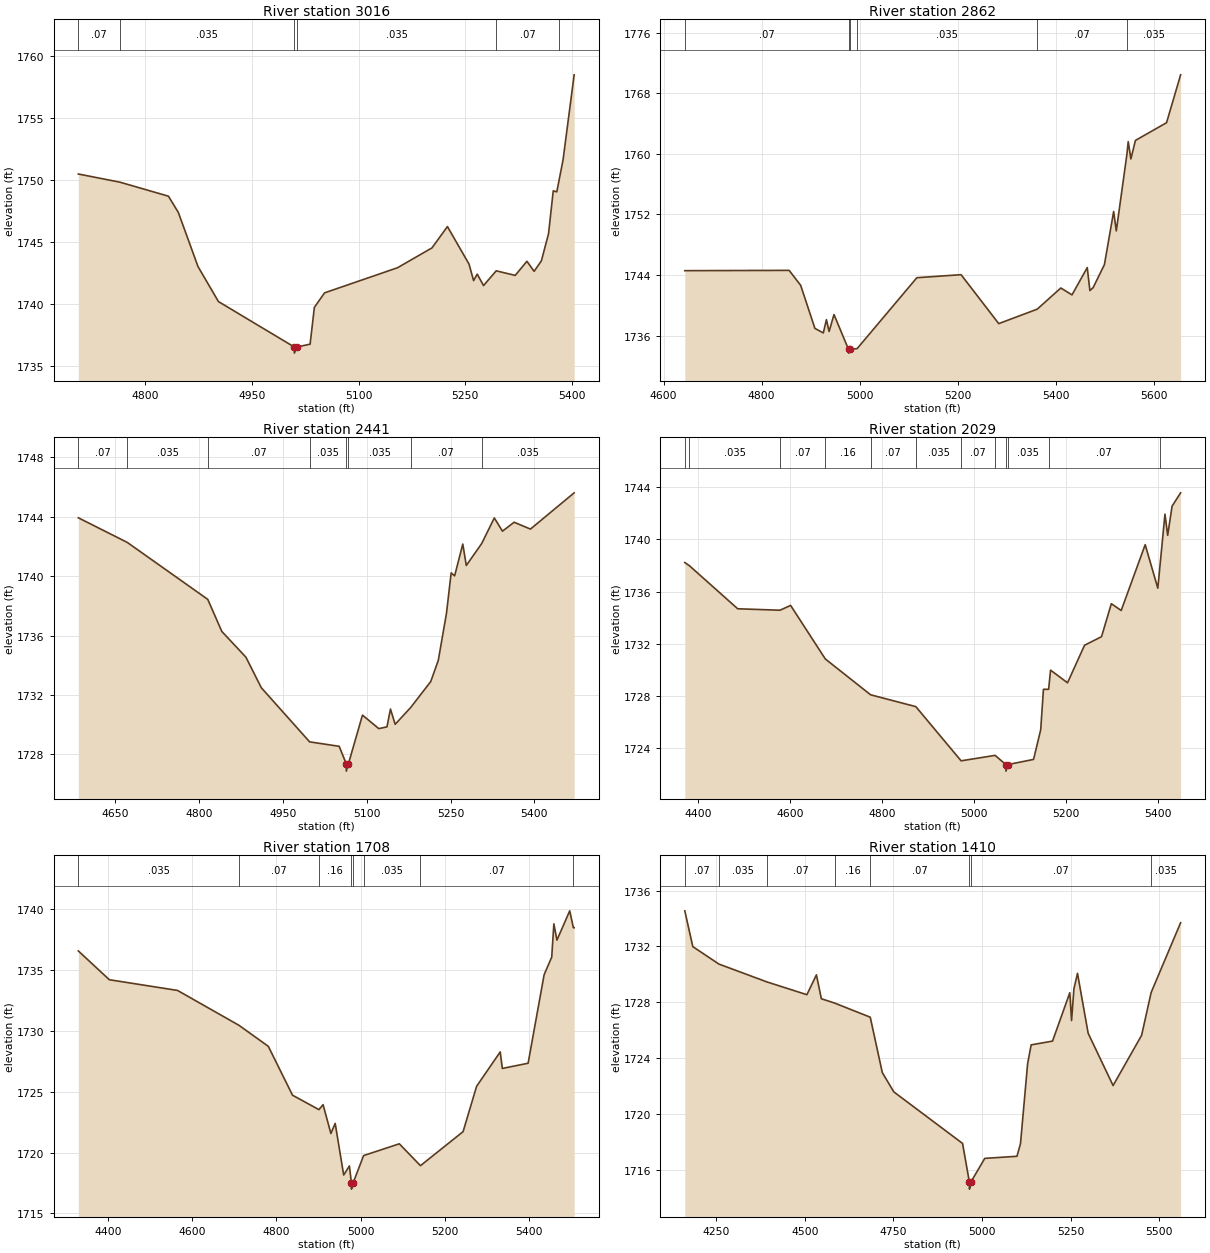
Type RM Length L Ch R = 1 ,3016    ,154,154,154
BEGIN DESCRIPTION:
Mapping XS c162bae7
END DESCRIPTION:
XS GIS Cut Line= 3
      1551525.81      6872139.81      1551755.87      6872326.46
      1552150.38        6872398.
#Sta/Elev= 30
  4705.8 1750.47  4764.3 1749.81  4832.5 1748.68  4846.4 1747.37  4874.1    1743
  4902.8 1740.18  5009.3 1736.52  5009.6 1736.02  5013.3 1736.52  5031.7 1736.74
  5037.7 1739.71    5052 1740.88  5154.7 1742.91  5203.1 1744.51  5224.8 1746.23
  5255.2  1743.2  5261.6 1741.87  5266.7 1742.39  5275.6 1741.47  5293.4 1742.66
  5320.1 1742.29  5336.6 1743.43  5346.7 1742.62  5356.9 1743.46    5367 1745.66
  5373.6 1749.11  5378.6 1749.03  5382.2 1750.09  5387.4 1751.61    5403 1758.47
#Mann= 6 ,-1 , 0
  4705.8     .07       0  4764.3    .035       0  5009.3    .035       0
  5013.3    .035       0  5293.4     .07       0  5382.2    .035       0
Bank Sta=5009.3,5013.3
XS Rating Curve= 0 ,0
Exp/Cntr=0.3,0.1

Type RM Length L Ch R = 1 ,2862    ,421,421,421
BEGIN DESCRIPTION:
Mapping XS a409b7cb
END DESCRIPTION:
XS GIS Cut Line= 3
      1551325.76      6872298.26      1551642.58      6872434.97
      1552260.52      6872682.14
#Sta/Elev= 30
  4643.3 1744.57    4856 1744.61  4879.5 1742.63  4908.5 1736.94  4925.6 1736.34
    4932 1738.09  4937.4 1736.53  4947.4 1738.77    4977 1734.17  4977.3 1733.67
    4981 1734.17  4994.6 1734.27  5116.3 1743.64  5206.4 1744.04  5283.2 1737.57
  5361.6 1739.48  5409.7 1742.28  5432.5 1741.37  5463.6 1744.98    5469 1741.94
  5475.6 1742.33  5498.6 1745.38  5517.4 1752.39  5522.8 1749.83  5544.4 1759.94
  5547.1 1761.63  5552.5 1759.34  5561.8 1761.79  5625.2 1764.13  5653.9 1770.46
#Mann= 6 ,-1 , 0
  4643.3     .07       0    4977    .035       0    4981     .07       0
  4994.6    .035       0  5361.6     .07       0  5544.4    .035       0
Bank Sta=4977,4981
XS Rating Curve= 0 ,0
Exp/Cntr=0.3,0.1

Type RM Length L Ch R = 1 ,2441    ,412,412,412
BEGIN DESCRIPTION:
Mapping XS c3e0fbf4
END DESCRIPTION:
XS GIS Cut Line= 3
      1551327.92      6872343.83      1551386.51      6872753.98
      1551667.53      6873134.43
#Sta/Elev= 30
  4583.9 1743.93  4671.6 1742.27  4815.5 1738.44  4840.7 1736.28  4883.8 1734.55
  4911.4 1732.49  4997.8 1728.85  5050.7 1728.55  5063.3 1727.38  5063.5 1726.88
  5067.3 1727.38  5092.4 1730.65  5121.6 1729.74  5136.2 1729.86  5142.5 1731.06
  5150.9 1730.03  5178.6 1731.16  5214.6 1732.91  5228.1 1734.34  5242.7  1737.5
  5251.1 1740.22  5257.3 1740.02  5271.9 1742.16  5278.2 1740.72  5305.8  1742.2
  5328.3 1743.92  5342.9 1743.03  5363.8 1743.63    5393 1743.17  5471.2 1745.61
#Mann= 8 ,-1 , 0
  4583.9     .07       0  4671.6    .035       0  4815.5     .07       0
  4997.8    .035       0  5063.3    .035       0  5067.3    .035       0
  5178.6     .07       0  5305.8    .035       0
Bank Sta=5063.3,5067.3
XS Rating Curve= 0 ,0
Exp/Cntr=0.3,0.1

Type RM Length L Ch R = 1 ,2029    ,321,321,321
BEGIN DESCRIPTION:
Mapping XS 933593be
END DESCRIPTION:
XS GIS Cut Line= 3
      1551075.75       6872413.3      1551114.81      6873040.44
      1551346.55      6873423.78
#Sta/Elev= 30
    4372 1738.23  4382.2 1737.98  4486.9 1734.68  4578.8 1734.57  4601.7 1734.94
    4677 1730.83  4775.3 1728.08  4873.5 1727.17  4971.8 1723.01  5045.6 1723.43
  5068.9 1722.72  5069.2 1722.22  5072.9 1722.72  5129.1 1723.12  5144.6  1725.4
  5150.5  1728.5  5161.8  1728.5    5166 1729.97  5202.8    1729  5239.7 1731.88
  5276.6 1732.54  5297.9 1735.07  5319.3 1734.55  5371.4  1739.6  5398.8 1736.26
  5403.3 1737.91  5414.3 1741.94  5420.2 1740.32  5429.8 1742.56  5448.3 1743.58
#Mann= 12 ,-1 , 0
    4372     .16       0  4382.2    .035       0  4578.8     .07       0
    4677     .16       0  4775.3     .07       0  4873.5    .035       0
  4971.8     .07       0  5045.6    .035       0  5068.9     .07       0
  5072.9    .035       0  5161.8     .07       0  5403.3    .035       0
Bank Sta=5068.9,5072.9
XS Rating Curve= 0 ,0
Exp/Cntr=0.3,0.1

Type RM Length L Ch R = 1 ,1708    ,298,298,298
BEGIN DESCRIPTION:
Mapping XS 757ca4ad
END DESCRIPTION:
XS GIS Cut Line= 3
      1550949.88      6872335.15      1550845.71      6872997.03
      1550928.18      6873498.37
#Sta/Elev= 30
  4329.3 1736.59    4403 1734.22    4565 1733.34    4711 1730.47  4780.7 1728.74
  4838.2 1724.72    4901 1723.53  4910.8 1723.94  4929.4 1721.57  4939.6  1722.4
  4959.8 1718.15  4973.4  1718.9  4978.1 1717.49  4978.3 1716.99  4982.1 1717.49
  5007.1 1719.75    5092 1720.72  5142.2 1718.92  5243.5 1721.72  5275.6 1725.45
  5331.7 1728.28  5336.8 1726.92    5398 1727.35  5436.1 1734.64  5454.1 1736.08
  5459.2 1738.82  5466.5 1737.48  5496.9 1739.89  5505.5  1738.5  5507.4  1738.5
#Mann= 8 ,-1 , 0
  4329.3    .035       0    4711     .07       0    4901     .16       0
  4978.1     .07       0  4982.1     .16       0  5007.1    .035       0
  5142.2     .07       0  5505.5    .035       0
Bank Sta=4978.1,4982.1
XS Rating Curve= 0 ,0
Exp/Cntr=0.3,0.1

Type RM Length L Ch R = 1 ,1410    ,495,495,495
BEGIN DESCRIPTION:
Mapping XS b7d9d005
END DESCRIPTION:
XS GIS Cut Line= 3
      1550834.87      6872298.21      1550622.19      6873131.58
      1550570.11      6873667.58
#Sta/Elev= 30
  4161.6 1734.55  4184.2 1731.99  4257.9 1730.74  4393.7 1729.46    4506 1728.55
  4532.9 1729.97  4546.8 1728.26  4584.3 1727.95  4684.7 1726.94  4718.7 1722.98
  4751.1  1721.6  4945.1 1717.91  4964.4 1715.14  4964.6 1714.64  4968.4 1715.14
  5007.7 1716.84  5098.5 1716.99  5108.5 1717.89  5128.6 1723.61  5138.6 1724.96
  5198.9 1725.23  5247.6 1728.69  5252.6  1726.7  5259.2 1728.97  5269.3 1730.08
  5299.4 1725.79  5369.7 1722.05  5450.1 1725.64  5477.1 1728.71  5560.2  1733.7
#Mann= 8 ,-1 , 0
  4161.6     .07       0  4257.9    .035       0  4393.7     .07       0
  4584.3     .16       0  4684.7     .07       0  4964.4     .07       0
  4968.4     .07       0  5477.1    .035       0
Bank Sta=4964.4,4968.4
XS Rating Curve= 0 ,0
Exp/Cntr=0.3,0.1

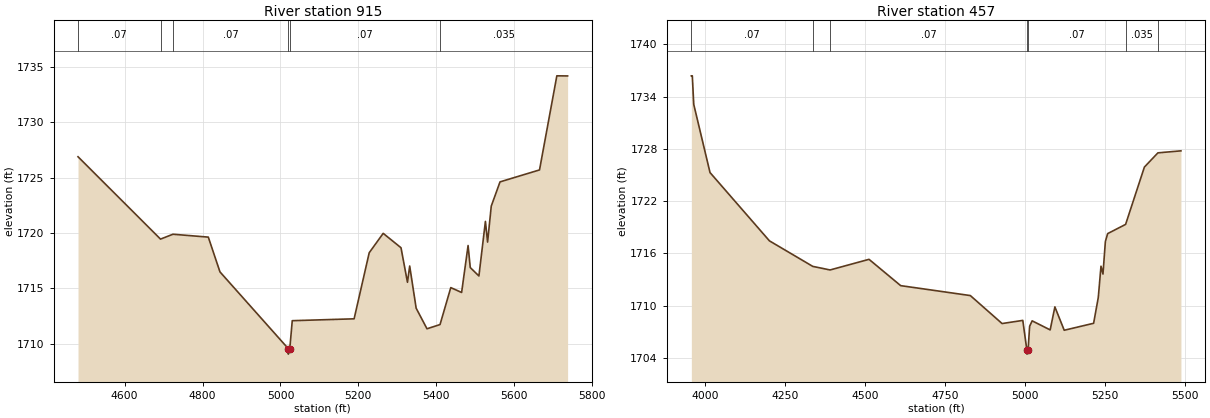
Type RM Length L Ch R = 1 ,915     ,458,458,458
BEGIN DESCRIPTION:
Mapping XS 3bbf1547
END DESCRIPTION:
XS GIS Cut Line= 4
      1550572.26      6872443.67      1550342.24      6872814.74
      1550194.67      6873140.26      1550405.15      6873552.55
#Sta/Elev= 30
  4480.3 1726.89  4692.1 1719.45    4724 1719.89  4814.8 1719.63  4844.7 1716.49
    5020 1709.56  5020.2 1709.06    5024 1709.56  5030.3 1712.08  5189.1 1712.25
  5227.9 1718.22  5263.8 1719.97  5309.5 1718.67  5326.1 1715.55  5331.8 1717.02
  5348.4 1713.21  5376.2 1711.35  5409.7 1711.73  5437.3 1715.07  5465.1 1714.63
  5481.7 1718.87  5487.3 1716.88  5509.5 1716.12  5526.2 1721.05  5531.8 1719.18
  5541.2 1722.43  5563.7 1724.62  5665.1  1725.7  5709.6  1734.2  5737.2 1734.19
#Mann= 6 ,-1 , 0
  4480.3     .07       0  4692.1     .16       0    4724     .07       0
    5020     .07       0    5024     .07       0  5409.7    .035       0
Bank Sta=5020,5024
XS Rating Curve= 0 ,0
Exp/Cntr=0.3,0.1

Type RM Length L Ch R = 1 ,457     ,0,0,0
BEGIN DESCRIPTION:
MULBERRY CREEK TRIBUTARY 11_1 1.0
END DESCRIPTION:
XS GIS Cut Line= 3
        1550405.        6872188.        1549880.      6872957.97
      1550235.87      6873437.53
#Sta/Elev= 30
  3957.3 1736.38  3960.3 1736.38  3964.8  1733.1  4015.6 1725.28  4201.2 1717.44
  4336.5 1714.51  4390.6  1714.1  4512.2 1715.32  4611.1  1712.3  4828.7 1711.16
  4927.8 1707.95  4992.5 1708.31  5005.1 1704.94  5005.4 1704.44  5009.1 1704.94
  5013.8 1707.63  5021.7 1708.26    5078 1707.22  5092.7 1709.86  5121.9 1707.18
  5213.7 1707.98  5228.3 1710.95  5236.7 1714.53  5242.9 1713.63  5250.4 1717.36
  5257.5 1718.27  5313.6 1719.33  5372.3 1725.91  5414.5 1727.54  5486.4 1727.77
#Mann= 7 ,-1 , 0
  3957.3     .07       0  4336.5     .16       0  4390.6     .07       0
  5005.1     .07       0  5009.1     .07       0  5313.6    .035       0
  5414.5     .07       0
#XS Ineff= 2 , 0
       0                  5092.7       0 1709.86
Permanent Ineff=
       F       F
Bank Sta=5005.1,5009.1
XS Rating Curve= 0 ,0
Exp/Cntr=0.3,0.1

Chan Stop Cuts=-1
Use User Specified Reach Order=0
Composite Channel Slope=5