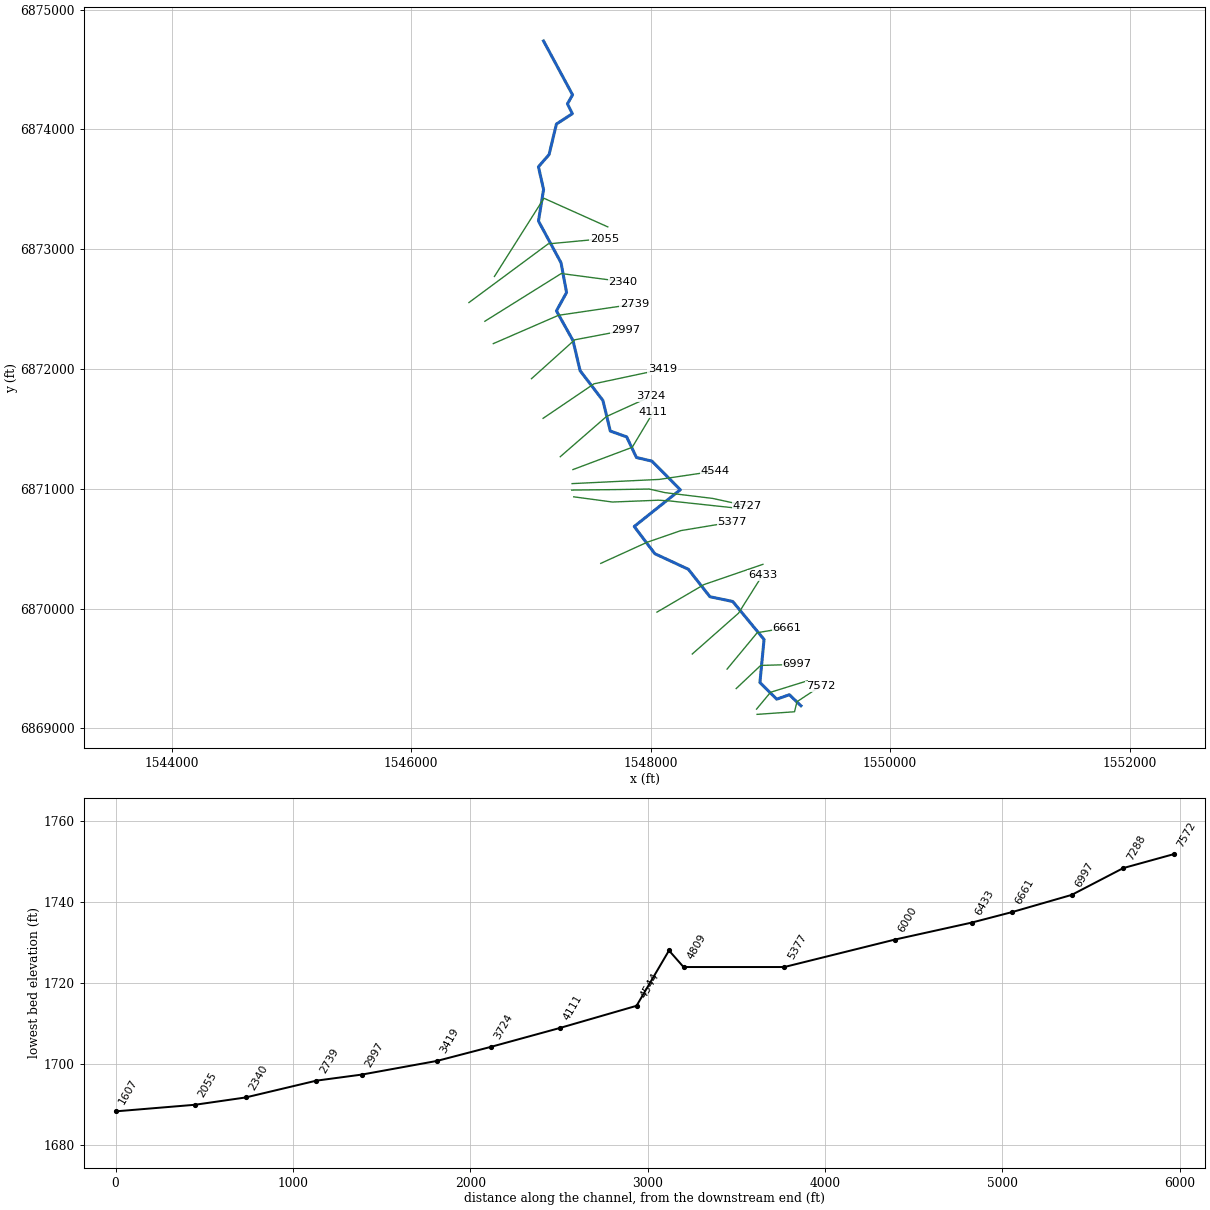
--- MULBERRY CREEK TRIBUTARY 12.prj (project) ---

Proj Title=MULBERRY CREEK TRIBUTARY 12 Base Level Engineering
Current Plan=p01
Default Exp/Contr=0.3,0.1
English Units
Geom File=g01
Flow File=f01
Plan File=p01
BEGIN DESCRIPTION:
MULBERRY CREEK TRIBUTARY 12
END DESCRIPTION:

--- MULBERRY CREEK TRIBUTARY 12.p01 (plan) ---

Plan Title=Multiple Run
Short Identifier=Multiple
Geom File=g01
Flow File=f01
Subcritical Flow
K Sum by GR= 0
Std Step Tol= 0.01
Critical Tol= 0.01
Num of Std Step Trials= 20
Max Error Tol= 0.3
Flow Tol Ratio= 0.001
Split Flow NTrial= 30
Split Flow Tol= 0.02
Split Flow Ratio= 0.02
Log Output Level= 0
Friction Slope Method= 1
Unsteady Friction Slope Method= 2
Unsteady Bridges Friction Slope Method= 1
Parabolic Critical Depth
Global Vel Dist=  1 , 1 , 1
Global Log Level= 0
CheckData=True
Encroach Param= -1, 0, 0, 0
BEGIN DESCRIPTION:
Multiple Run
END DESCRIPTION:

--- MULBERRY CREEK TRIBUTARY 12.f01 (steady flow) ---

Flow Title=Multiple
Number of Profiles=7
Profile Names=10-year,25-year,50-year,1pct_min,100-year,1pct_plu,500-year
River Rch & RM= MULBERRY CREEK T,Reach-1,7572
      88     115     136      81     161     321     228
River Rch & RM= MULBERRY CREEK T,Reach-1,4809
     138     187     226     136     272     543     400
Boundary for River Rch & Prof#=MULBERRY CREEK T,Reach-1,1
Up Type=0
Dn Type=3
Dn Slope=0.005
Boundary for River Rch & Prof#=MULBERRY CREEK T,Reach-1,2
Up Type=0
Dn Type=3
Dn Slope=0.005
Boundary for River Rch & Prof#=MULBERRY CREEK T,Reach-1,3
Up Type=0
Dn Type=3
Dn Slope=0.005
Boundary for River Rch & Prof#=MULBERRY CREEK T,Reach-1,4
Up Type=0
Dn Type=3
Dn Slope=0.005
Boundary for River Rch & Prof#=MULBERRY CREEK T,Reach-1,5
Up Type=0
Dn Type=3
Dn Slope=0.005
Boundary for River Rch & Prof#=MULBERRY CREEK T,Reach-1,6
Up Type=0
Dn Type=3
Dn Slope=0.005
Boundary for River Rch & Prof#=MULBERRY CREEK T,Reach-1,7
Up Type=0
Dn Type=3
Dn Slope=0.005

--- MULBERRY CREEK TRIBUTARY 12.g01 (geometry) ---

Geom Title=Existing Conditions

River Reach=MULBERRY CREEK T,Reach-1
Reach XY= 30
      1549255.00      6869188.00      1549158.41      6869280.30
      1549052.71      6869243.11      1548912.50      6869381.95
      1548947.02      6869741.33      1548685.41      6870058.58
      1548494.88      6870098.35      1548314.79      6870327.48
      1548034.53      6870457.63      1547862.59      6870684.67
      1548247.42      6870991.32      1548011.17      6871230.14
      1547881.10      6871260.72      1547799.55      6871432.75
      1547662.73      6871481.50      1547601.18      6871736.42
      1547410.52      6871985.57      1547351.38      6872236.50
      1547213.05      6872484.71      1547297.47      6872637.99
      1547251.25      6872886.45      1547062.82      6873234.58
      1547105.40      6873498.21      1547062.55      6873688.00
      1547151.36      6873789.50      1547212.75      6874044.45
      1547345.97      6874130.99      1547304.79      6874213.00
      1547347.64      6874288.08      1547105.00      6874738.00

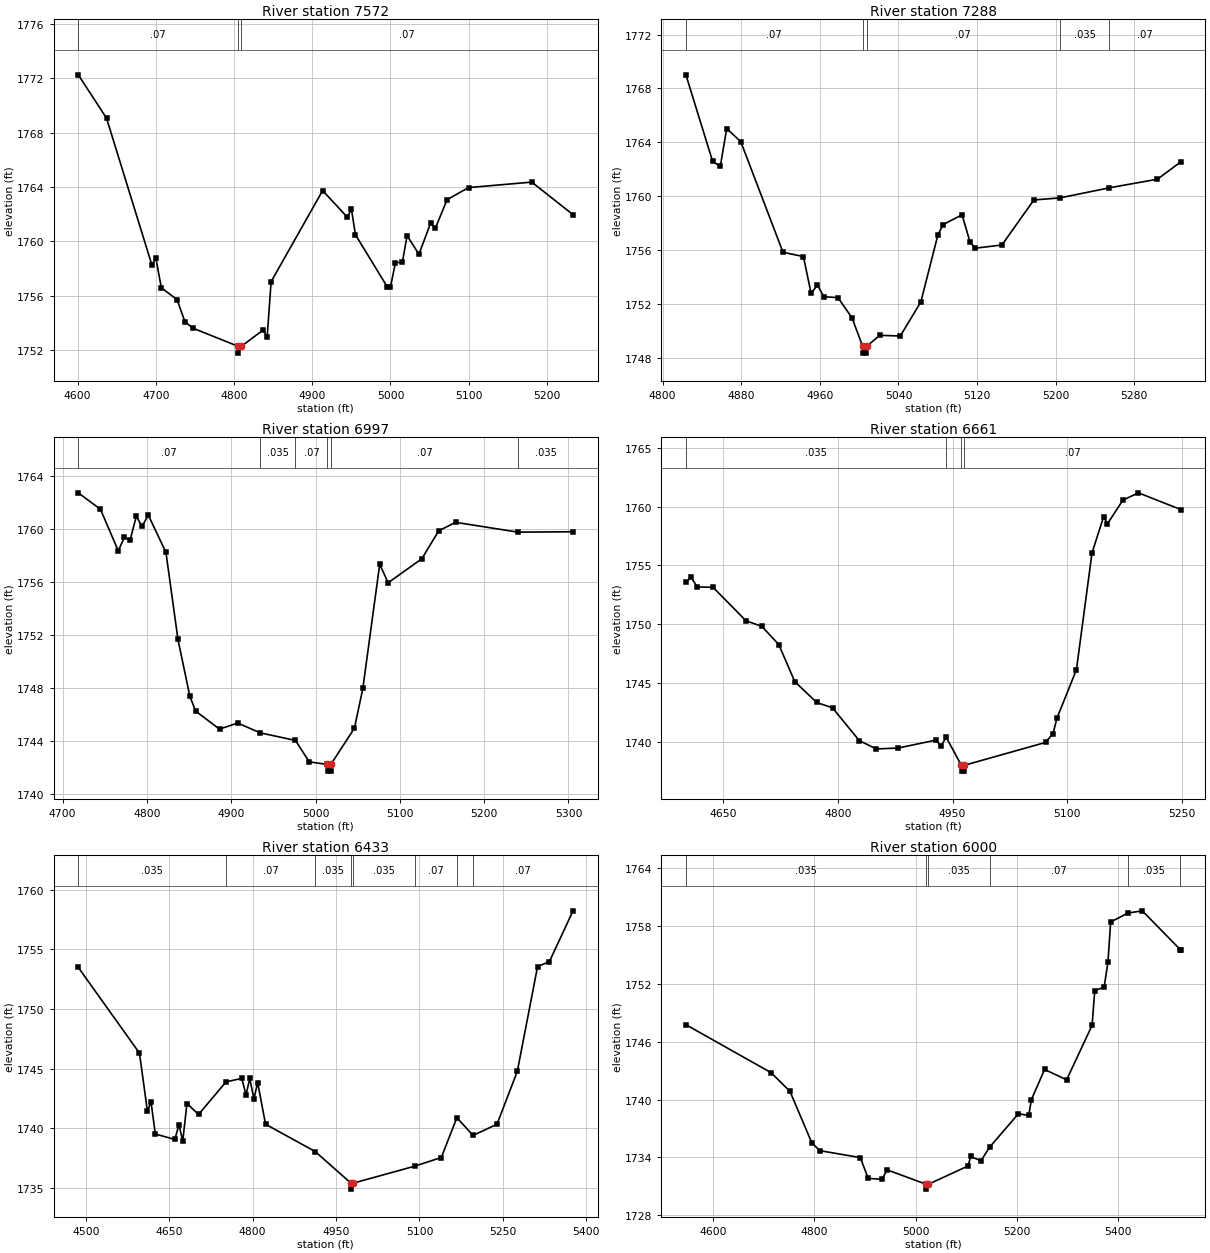
Type RM Length L Ch R = 1,7572,284,284,284
BEGIN DESCRIPTION:
MULBERRY CREEK TRIBUTARY 12 14.0
END DESCRIPTION:
XS GIS Cut Line= 4
      1548889.04      6869116.27      1549201.51      6869137.97
      1549221.78      6869221.52      1549416.34      6869350.63
#Sta/Elev= 30
  4600.8 1772.24  4636.9 1769.06  4695.0 1758.26  4700.0 1758.79  4707.0 1756.60
  4727.1 1755.73  4737.1 1754.12  4747.1 1753.64  4805.3 1752.30  4805.5 1751.80
  4809.3 1752.30  4837.3 1753.50  4842.3 1752.95  4847.4 1757.05  4913.3 1763.74
  4944.9 1761.78  4950.1 1762.38  4955.2 1760.50  4996.2 1756.64  5000.0 1756.64
  5006.3 1758.43  5015.3 1758.49  5021.3 1760.43  5036.4 1759.06  5051.4 1761.35
  5057.4 1760.97  5072.4 1763.07  5099.9 1763.96  5180.7 1764.36  5233.5 1761.97
#Mann=3,-1,0
  4600.8    0.07       0  4805.3    0.07       0  4809.3    0.07       0
Bank Sta=4805.3,4809.3
Exp/Cntr=0.3,0.1

Type RM Length L Ch R = 1,7288,291,291,291
BEGIN DESCRIPTION:
Mapping XS 7fbd3b11
END DESCRIPTION:
XS GIS Cut Line= 3
      1548884.29      6869160.12      1549001.49      6869300.75
      1549307.50      6869395.81
#Sta/Elev= 30
  4823.7 1769.01  4850.9 1762.59  4858.7 1762.22  4865.2 1765.02  4879.5 1764.06
  4922.5 1755.85  4943.3 1755.53  4951.1 1752.80  4957.6 1753.42  4964.1 1752.55
  4978.4 1752.49  4992.7 1750.99  5003.6 1748.87  5003.9 1748.37  5007.4 1748.37
  5007.6 1748.87  5020.9 1749.69  5041.9 1749.64  5062.8 1752.17  5080.1 1757.13
  5085.4 1757.90  5104.7 1758.63  5112.7 1756.64  5117.9 1756.15  5145.3 1756.39
  5177.8 1759.73  5204.2 1759.88  5254.6 1760.63  5303.6 1761.27  5327.2 1762.55
#Mann=5,-1,0
  4823.7    0.07       0  5003.6    0.07       0  5007.6    0.07       0
  5204.2   0.035       0  5254.6    0.07       0
Bank Sta=5003.6,5007.6
Exp/Cntr=0.3,0.1

Type RM Length L Ch R = 1,6997,336,336,336
BEGIN DESCRIPTION:
MULBERRY CREEK TRIBUTARY 12 13.0
END DESCRIPTION:
XS GIS Cut Line= 3
      1548714.30      6869331.66      1548918.95      6869524.80
      1549224.23      6869533.45
#Sta/Elev= 30
  4718.6 1762.70  4744.9 1761.46  4766.0 1758.34  4773.3 1759.35  4780.1 1759.15
  4787.4 1760.93  4794.3 1760.17  4801.6 1761.03  4822.6 1758.21  4836.8 1751.67
  4850.9 1747.39  4857.8 1746.27  4886.1 1744.91  4907.6 1745.37  4934.5 1744.63
  4976.2 1744.06  4992.5 1742.45  5014.1 1742.25  5014.3 1741.75  5017.8 1741.75
  5018.1 1742.25  5046.1 1744.98  5056.1 1747.98  5076.1 1757.32  5086.1 1755.93
  5126.1 1757.74  5146.1 1759.84  5166.1 1760.48  5240.2 1759.74  5305.4 1759.77
#Mann=6,-1,0
  4718.6    0.07       0  4934.5   0.035       0  4976.2    0.07       0
  5014.1    0.07       0  5018.1    0.07       0  5240.2   0.035       0
Bank Sta=5014.1,5018.1
Exp/Cntr=0.3,0.1

Type RM Length L Ch R = 1,6661,228,228,228
BEGIN DESCRIPTION:
Mapping XS cb74e32e
END DESCRIPTION:
XS GIS Cut Line= 3
      1548638.30      6869494.37      1548890.05      6869798.21
      1549139.58      6869839.44
#Sta/Elev= 30
  4601.0 1753.57  4607.9 1753.98  4615.8 1753.18  4636.6 1753.14  4679.6 1750.30
  4700.4 1749.82  4722.6 1748.27  4743.4 1745.13  4772.1 1743.35  4792.9 1742.89
  4828.0 1740.10  4850.2 1739.40  4878.4 1739.47  4928.4 1740.15  4934.8 1739.63
  4941.6 1740.39  4961.5 1738.01  4961.8 1737.51  4965.3 1737.51  4965.5 1738.01
  5071.6 1739.95  5081.5 1740.71  5086.5 1742.00  5112.1 1746.14  5132.4 1756.05
  5147.6 1759.14  5152.7 1758.55  5172.9 1760.56  5193.2 1761.18  5248.5 1759.76
#Mann=4,-1,0
  4601.0   0.035       0  4941.6    0.07       0  4961.5    0.07       0
  4965.5    0.07       0
Bank Sta=4961.5,4965.5
Exp/Cntr=0.3,0.1

Type RM Length L Ch R = 1,6433,433,433,433
BEGIN DESCRIPTION:
Mapping XS 816f0f62
END DESCRIPTION:
XS GIS Cut Line= 3
      1548347.48      6869620.23      1548733.80      6869960.97
      1548933.44      6870277.80
#Sta/Elev= 30
  4486.5 1753.49  4596.5 1746.31  4610.7 1741.48  4617.4 1742.18  4625.0 1739.53
  4660.1 1739.07  4667.6 1740.32  4674.3 1738.92  4681.9 1742.08  4702.8 1741.17
  4752.2 1743.90  4780.6 1744.19  4788.1 1742.79  4794.8 1744.18  4802.3 1742.47
  4809.0 1743.84  4823.2 1740.35  4912.5 1738.06  4976.8 1735.41  4977.1 1734.91
  4980.8 1735.41  5091.2 1736.83  5139.3 1737.56  5167.2 1740.90  5196.3 1739.41
  5239.4 1740.35  5275.9 1744.78  5312.3 1753.56  5333.5 1753.97  5376.1 1758.23
#Mann=8,-1,0
  4486.5   0.035       0  4752.2    0.07       0  4912.5   0.035       0
  4976.8   0.035       0  4980.8   0.035       0  5091.2    0.07       0
  5167.2   0.035       0  5196.3    0.07       0
Bank Sta=4976.8,4980.8
Exp/Cntr=0.3,0.1

Type RM Length L Ch R = 1,6000,623,623,623
BEGIN DESCRIPTION:
Mapping XS 505c4098
END DESCRIPTION:
XS GIS Cut Line= 3
      1548052.34      6869969.63      1548445.17      6870199.69
      1548937.76      6870368.95
#Sta/Elev= 30
  4546.8 1747.76  4714.8 1742.79  4752.0 1740.86  4795.0 1735.54  4810.7 1734.71
  4890.8 1733.99  4906.5 1731.83  4933.8 1731.74  4943.7 1732.72  5021.0 1731.22
  5021.3 1730.72  5025.0 1731.22  5103.4 1733.12  5108.7 1734.11  5128.7 1733.65
  5146.6 1735.11  5202.8 1738.53  5223.1 1738.36  5228.4 1739.99  5254.4 1743.12
  5297.9 1742.05  5348.1 1747.69  5353.4 1751.30  5371.9 1751.65  5379.4 1754.23
  5384.7 1758.40  5418.8 1759.33  5447.2 1759.56  5522.5 1755.52  5522.9 1755.52
#Mann=6,-1,0
  4546.8   0.035       0  5021.0   0.035       0  5025.0   0.035       0
  5146.6    0.07       0  5418.8   0.035       0  5522.5    0.07       0
Bank Sta=5021,5025
Exp/Cntr=0.3,0.1

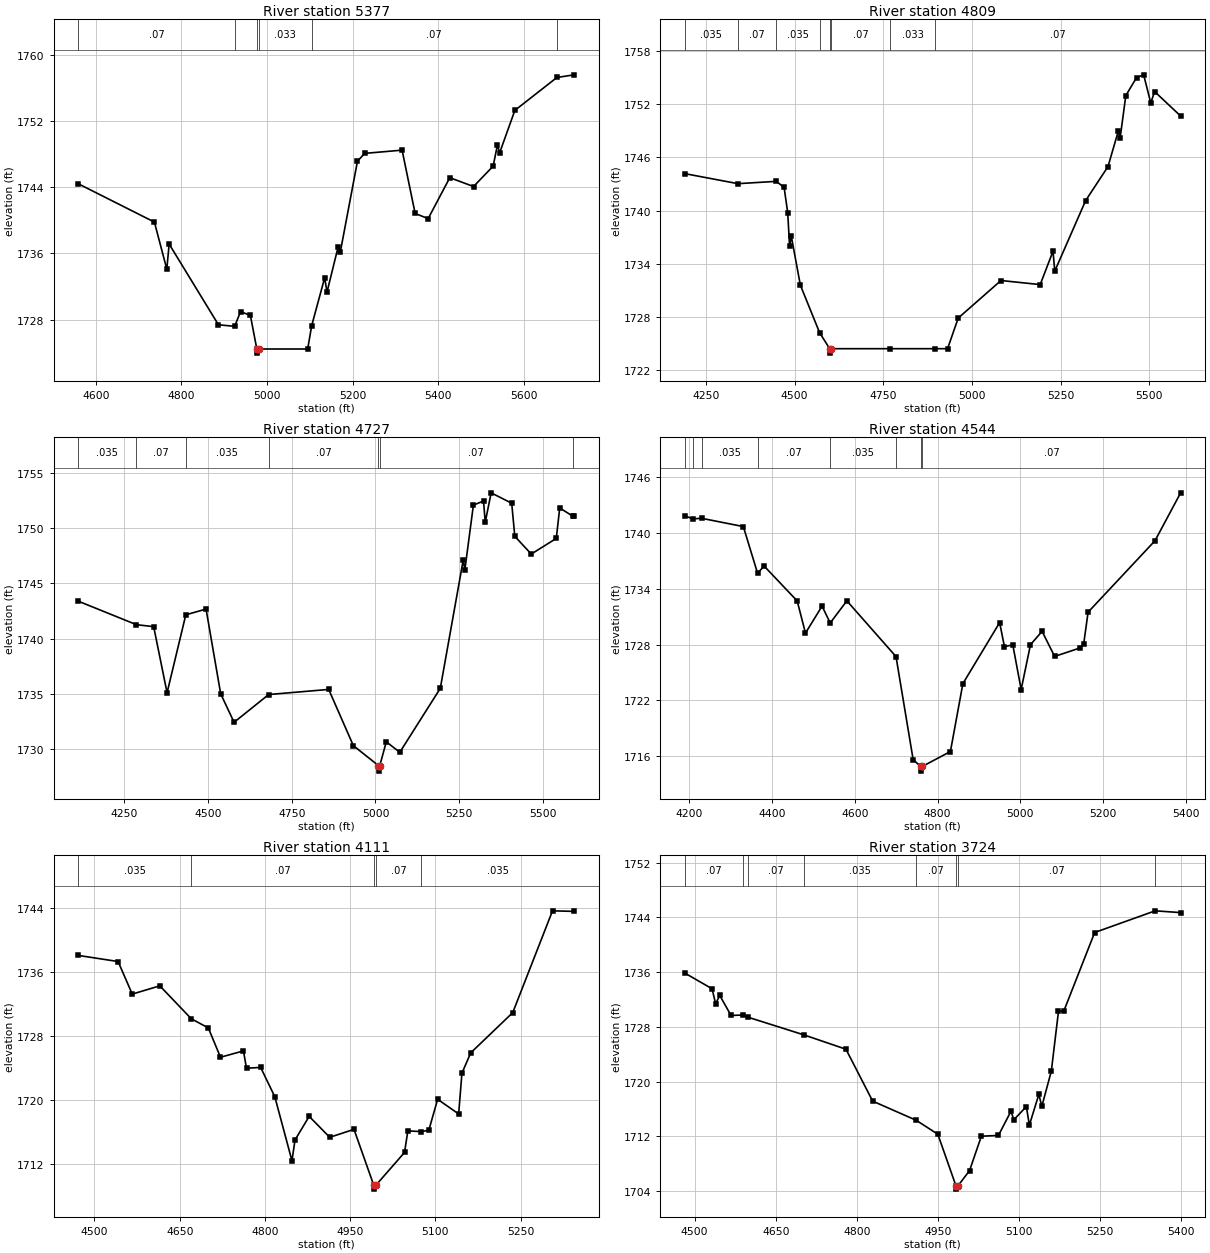
Type RM Length L Ch R = 1,5377,568,568,568
BEGIN DESCRIPTION:
Mapping XS 0f6f6050
END DESCRIPTION:
XS GIS Cut Line= 4
      1547583.15      6870376.75      1547969.47      6870552.55
      1548251.59      6870650.21      1548681.74      6870721.54
#Sta/Elev= 30
  4558.9 1744.43  4736.7 1739.80  4765.7 1734.10  4771.2 1737.14  4886.4 1727.38
  4924.3 1727.19  4938.1 1728.97  4961.1 1728.51  4976.1 1724.45  4976.4 1723.95
  4980.1 1724.45  5095.0 1724.45  5104.4 1727.28  5134.8 1733.08  5140.1 1731.31
  5166.0 1736.76  5171.3 1736.19  5211.4 1747.17  5228.3 1748.11  5315.7 1748.50
  5346.2 1740.84  5376.6 1740.22  5427.2 1745.17  5482.7 1744.10  5528.6 1746.57
  5538.6 1749.15  5543.6 1748.16  5579.3 1753.31  5677.6 1757.29  5717.9 1757.61
#Mann=6,-1,0
  4558.9    0.07       0  4924.3   0.033       0  4976.1   0.033       0
  4980.1   0.033       0  5104.4    0.07       0  5677.6   0.035       0
Bank Sta=4976.1,4980.1
Exp/Cntr=0.3,0.1

Type RM Length L Ch R = 1,4809,82,82,82
BEGIN DESCRIPTION:
Mapping XS 65985955
END DESCRIPTION:
XS GIS Cut Line= 5
      1547357.48      6870932.33      1547680.85      6870888.92
      1548064.96      6870904.11      1548162.62      6870897.60
      1548748.59      6870834.66
#Sta/Elev= 30
  4190.6 1744.17  4340.3 1743.04  4448.8 1743.30  4470.6 1742.61  4480.7 1739.79
  4486.0 1736.03  4491.0 1737.09  4516.4 1731.61  4570.7 1726.25  4599.1 1724.45
  4599.3 1723.95  4603.1 1724.45  4768.7 1724.45  4896.7 1724.45  4931.4 1724.45
  4961.5 1727.90  5082.0 1732.13  5192.6 1731.67  5228.7 1735.43  5233.7 1733.19
  5320.8 1741.14  5383.7 1744.96  5412.8 1748.96  5417.9 1748.17  5434.0 1752.97
  5464.2 1754.98  5484.3 1755.30  5504.4 1752.12  5515.0 1753.42  5588.5 1750.66
#Mann=8,-1,0
  4190.6   0.035       0  4340.3    0.07       0  4448.8   0.035       0
  4570.7    0.07       0  4599.1    0.07       0  4603.1    0.07       0
  4768.7   0.033       0  4896.7    0.07       0
Bank Sta=4599.1,4603.1
Exp/Cntr=0.3,0.1

Type RM Length L Ch R = 1,4727,183,183,183
BEGIN DESCRIPTION:
Mapping XS b9fe3270
END DESCRIPTION:
XS GIS Cut Line= 6
      1547340.13      6870988.75      1547730.76      6870993.09
      1547986.84      6870997.43      1548121.38      6870967.05
      1548516.35      6870919.30      1548807.17      6870856.36
#Sta/Elev= 30
  4113.1 1743.38  4286.5 1741.26  4338.0 1741.08  4378.0 1735.11  4433.9 1742.15
  4494.4 1742.67  4538.0 1735.02  4578.0 1732.44  4681.3 1734.95  4860.5 1735.41
  4934.1 1730.33  5009.0 1728.53  5009.3 1728.03  5013.0 1728.53  5032.4 1730.68
  5072.7 1729.73  5193.6 1735.51  5261.9 1747.08  5267.0 1746.23  5292.4 1752.06
  5322.6 1752.43  5327.8 1750.52  5345.4 1753.17  5406.8 1752.23  5416.0 1749.24
  5465.2 1747.64  5539.8 1749.05  5550.1 1751.80  5588.3 1751.08  5593.2 1751.05
#Mann=7,-1,0
  4113.1   0.035       0  4286.5    0.07       0  4433.9   0.035       0
  4681.3    0.07       0  5009.0    0.07       0  5013.0    0.07       0
  5588.3   0.035       0
Bank Sta=5009,5013
Exp/Cntr=0.3,0.1

Type RM Length L Ch R = 1,4544,433,433,433
BEGIN DESCRIPTION:
Mapping XS f94884b6
END DESCRIPTION:
XS GIS Cut Line= 3
      1547343.62      6871042.57      1548071.47      6871077.72
      1548536.27      6871146.73
#Sta/Elev= 30
  4188.7 1741.83  4209.0 1741.52  4229.3 1741.58  4330.2 1740.69  4364.7 1735.66
  4380.3 1736.45  4460.4 1732.69  4480.4 1729.23  4520.5 1732.13  4540.2 1730.32
  4580.5 1732.70  4699.3 1726.70  4740.7 1715.62  4758.7 1714.88  4759.0 1714.38
  4762.7 1714.88  4830.8 1716.49  4860.9 1723.79  4949.8 1730.36  4961.4 1727.77
  4981.6 1727.97  5001.8 1723.16  5024.3 1727.98  5052.4 1729.42  5082.7 1726.72
  5143.4 1727.62  5153.0 1728.07  5163.6 1731.48  5325.4 1739.17  5387.3 1744.32
#Mann=8,-1,0
  4188.7   0.035       0  4209.0    0.07       0  4229.3   0.035       0
  4364.7    0.07       0  4540.2   0.035       0  4699.3    0.07       0
  4758.7    0.07       0  4762.7    0.07       0
Bank Sta=4758.7,4762.7
Exp/Cntr=0.3,0.1

Type RM Length L Ch R = 1,4111,387,387,387
BEGIN DESCRIPTION:
Mapping XS e384b415
END DESCRIPTION:
XS GIS Cut Line= 3
      1547350.76      6871159.77      1547845.52      6871345.52
      1548022.62      6871640.69
#Sta/Elev= 30
  4471.6 1738.03  4541.6 1737.27  4566.5 1733.21  4615.0 1734.24  4670.4 1730.14
  4700.4 1728.99  4721.8 1725.34  4762.2 1726.13  4767.6 1723.97  4792.5 1724.07
  4817.4 1720.42  4847.6 1712.44  4853.0 1715.03  4877.9 1717.97  4914.1 1715.36
  4956.8 1716.35  4991.5 1709.40  4991.8 1708.90  4995.5 1709.40  5045.7 1713.47
  5051.6 1716.16  5075.2 1716.07  5088.5 1716.24  5104.0 1720.10  5141.0 1718.27
  5146.8 1723.36  5162.3 1725.89  5236.2 1730.90  5306.2 1743.59  5344.3 1743.52
#Mann=5,-1,0
  4471.6   0.035       0  4670.4    0.07       0  4991.5    0.07       0
  4995.5    0.07       0  5075.2   0.035       0
Bank Sta=4991.5,4995.5
Exp/Cntr=0.3,0.1

Type RM Length L Ch R = 1,3724,305,305,305
BEGIN DESCRIPTION:
Mapping XS 7c8443ff
END DESCRIPTION:
XS GIS Cut Line= 3
      1547244.78      6871267.36      1547630.24      6871602.46
      1548000.89      6871770.47
#Sta/Elev= 30
  4481.7 1735.86  4532.2 1733.56  4538.8 1731.37  4546.4 1732.58  4567.3 1729.66
  4589.4 1729.72  4599.6 1729.38  4701.7 1726.83  4780.0 1724.72  4829.4 1717.13
  4910.2 1714.32  4950.0 1712.29  4983.5 1704.76  4983.8 1704.26  4987.5 1704.76
  5008.7 1706.96  5030.6 1712.00  5062.2 1712.11  5085.3 1715.64  5090.8 1714.41
  5113.9 1716.34  5119.4 1713.61  5137.0 1718.12  5142.5 1716.36  5160.1 1721.52
  5173.3 1730.24  5183.2 1730.30  5240.3 1741.79  5352.3 1744.96  5399.4 1744.70
#Mann=8,-1,0
  4481.7    0.07       0  4589.4   0.035       0  4599.6    0.07       0
  4701.7   0.035       0  4910.2    0.07       0  4983.5    0.07       0
  4987.5    0.07       0  5352.3   0.035       0
Bank Sta=4983.5,4987.5
Exp/Cntr=0.3,0.1

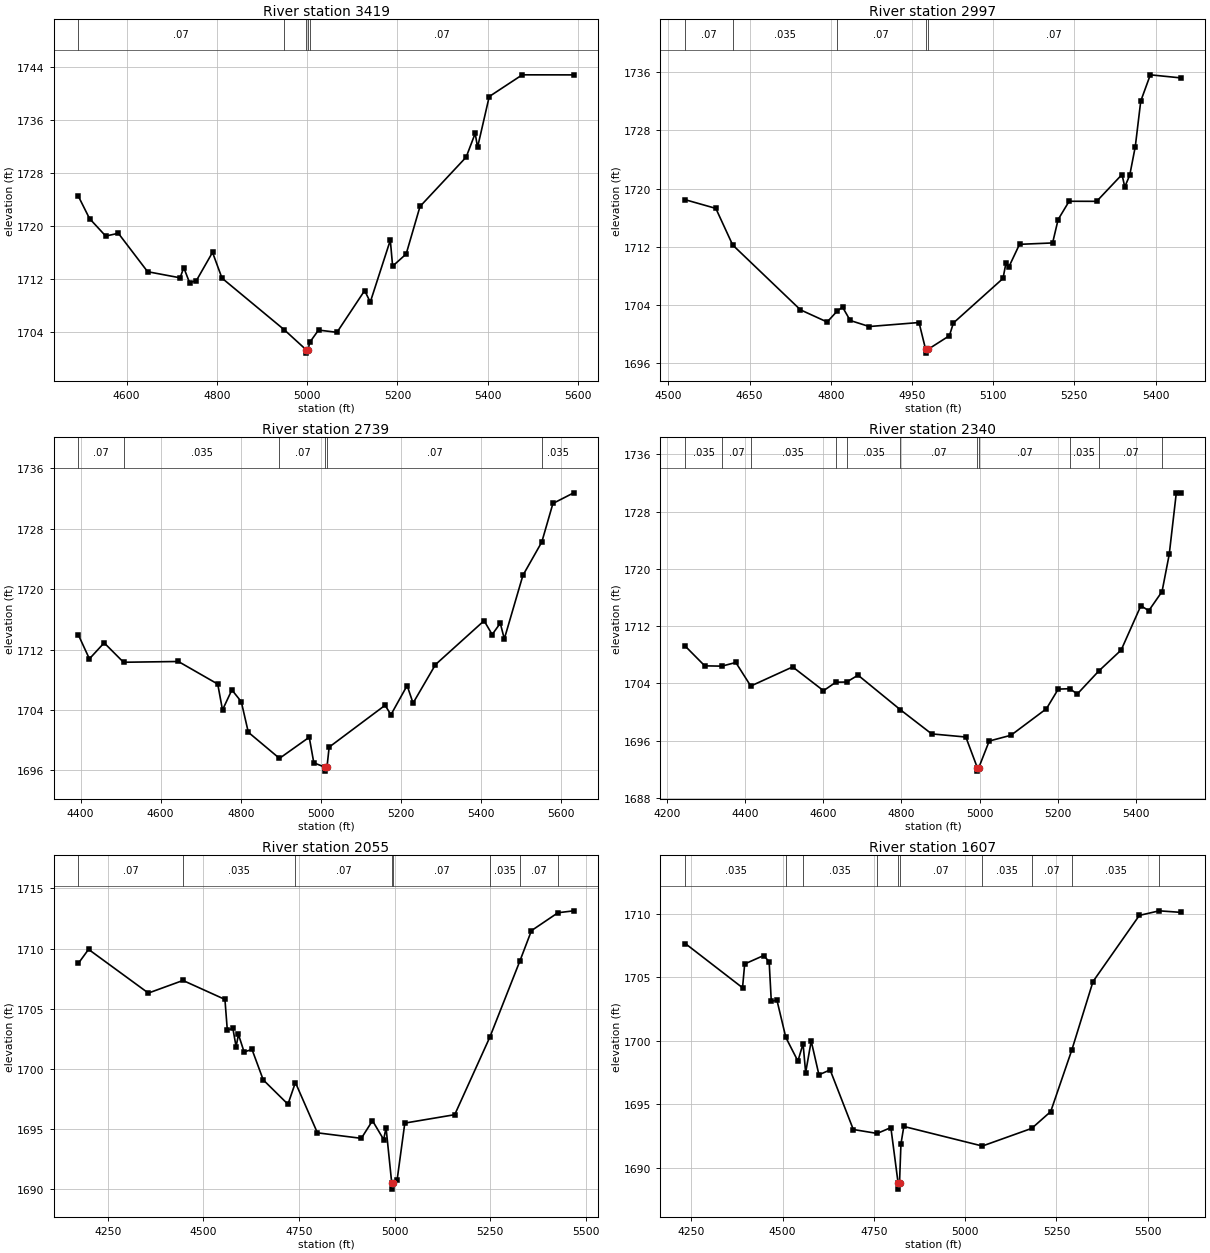
Type RM Length L Ch R = 1,3419,422,422,422
BEGIN DESCRIPTION:
Mapping XS ba196dde
END DESCRIPTION:
XS GIS Cut Line= 3
      1547101.56      6871587.68      1547526.94      6871875.90
      1548098.13      6871997.43
#Sta/Elev= 30
  4492.9 1724.48  4517.7 1721.10  4553.6 1718.45  4581.6 1718.87  4646.5 1713.07
  4718.4 1712.15  4726.6 1713.68  4739.4 1711.42  4754.4 1711.71  4790.3 1715.99
  4811.3 1712.10  4948.7 1704.34  4997.9 1701.28  4998.2 1700.78  5001.9 1701.28
  5005.8 1702.41  5025.2 1704.26  5066.1 1703.92  5127.4 1710.22  5139.9 1708.48
  5184.3 1717.83  5189.4 1713.91  5219.4 1715.74  5250.1 1722.92  5352.4 1730.37
  5372.4 1733.96  5377.6 1731.84  5403.5 1739.51  5476.7 1742.79  5590.7 1742.78
#Mann=5,-1,0
  4492.9    0.07       0  4948.7   0.035       0  4997.9   0.035       0
  5001.9   0.035       0  5005.8    0.07       0
Bank Sta=4997.9,5001.9
Exp/Cntr=0.3,0.1

Type RM Length L Ch R = 1,2997,258,258,258
BEGIN DESCRIPTION:
Mapping XS 3be736c2
END DESCRIPTION:
XS GIS Cut Line= 3
      1547004.36      6871918.43      1547365.48      6872243.09
      1547787.38      6872322.96
#Sta/Elev= 30
  4531.3 1718.47  4587.8 1717.28  4618.9 1712.26  4744.1 1703.36  4793.4 1701.69
  4811.3 1703.14  4821.8 1703.74  4836.0 1701.90  4871.1 1701.07  4963.1 1701.62
  4975.3 1697.92  4975.5 1697.42  4979.3 1697.92  5019.2 1699.81  5026.6 1701.56
  5118.2 1707.67  5123.6 1709.76  5128.7 1709.20  5148.7 1712.35  5209.8 1712.54
  5220.0 1715.75  5240.3 1718.26  5291.2 1718.25  5338.0 1721.93  5343.1 1720.22
  5352.3 1721.85  5362.5 1725.75  5372.6 1732.00  5390.3 1735.61  5446.3 1735.19
#Mann=5,-1,0
  4531.3    0.07       0  4618.9   0.035       0  4811.3    0.07       0
  4975.3    0.07       0  4979.3    0.07       0
Bank Sta=4975.3,4979.3
Exp/Cntr=0.3,0.1

Type RM Length L Ch R = 1,2739,399,399,399
BEGIN DESCRIPTION:
Mapping XS 2b0b1006
END DESCRIPTION:
XS GIS Cut Line= 3
      1546685.82      6872211.42      1547230.50      6872447.95
      1547866.37      6872541.27
#Sta/Elev= 30
  4394.4 1713.97  4422.1 1710.78  4458.9 1712.90  4507.2 1710.33  4644.1 1710.43
  4742.4 1707.44  4754.3 1704.01  4777.7 1706.67  4801.2 1705.10  4818.7 1701.06
  4896.5 1697.60  4970.8 1700.40  4982.2 1697.01  5011.0 1696.41  5011.2 1695.91
  5015.0 1696.41  5020.5 1699.09  5160.1 1704.63  5174.7 1703.38  5215.1 1707.24
  5229.9 1704.92  5285.9 1710.02  5407.2 1715.83  5427.4 1714.00  5447.6 1715.50
  5457.7 1713.42  5504.1 1721.84  5551.2 1726.25  5579.0 1731.36  5630.9 1732.77
#Mann=6,-1,0
  4394.4    0.07       0  4507.2   0.035       0  4896.5    0.07       0
  5011.0    0.07       0  5015.0    0.07       0  5551.2   0.035       0
Bank Sta=5011,5015
Exp/Cntr=0.3,0.1

Type RM Length L Ch R = 1,2340,285,285,285
BEGIN DESCRIPTION:
Mapping XS cf3ec2dd
END DESCRIPTION:
XS GIS Cut Line= 3
      1546615.08      6872398.06      1547253.07      6872796.47
      1547766.05      6872728.77
#Sta/Elev= 30
  4245.8 1709.21  4295.8 1706.46  4339.8 1706.42  4375.4 1706.93  4413.7 1703.64
  4521.1 1706.31  4600.1 1702.99  4631.9 1704.18  4659.5 1704.20  4688.6 1705.16
  4797.4 1700.32  4877.3 1696.96  4964.9 1696.52  4994.2 1692.26  4994.4 1691.76
  4998.2 1692.26  5024.8 1695.96  5080.6 1696.77  5171.4 1700.47  5201.7 1703.21
  5231.6 1703.27  5250.4 1702.52  5305.6 1705.74  5363.0 1708.67  5413.5 1714.86
  5433.7 1714.16  5467.7 1716.83  5486.1 1722.01  5504.3 1730.62  5515.4 1730.60
#Mann=11,-1,0
  4245.8   0.035       0  4339.8    0.07       0  4413.7   0.035       0
  4631.9    0.07       0  4659.5   0.035       0  4797.4    0.07       0
  4994.2    0.07       0  4998.2    0.07       0  5231.6   0.035       0
  5305.6    0.07       0  5467.7   0.035       0
Bank Sta=4994.2,4998.2
Exp/Cntr=0.3,0.1

Type RM Length L Ch R = 1,2055,448,448,448
BEGIN DESCRIPTION:
Mapping XS 93c817f1
END DESCRIPTION:
XS GIS Cut Line= 3
      1546482.23      6872554.29      1547143.69      6873043.87
      1547615.08      6873088.14
#Sta/Elev= 30
  4172.4 1708.76  4199.2 1709.93  4355.7 1706.29  4446.3 1707.34  4556.1 1705.76
  4562.3 1703.21  4576.9 1703.34  4585.3 1701.83  4591.5 1702.84  4606.2 1701.39
  4627.0 1701.59  4656.3 1699.06  4721.0 1697.03  4740.5 1698.84  4798.1 1694.65
  4913.0 1694.19  4942.2 1695.66  4971.5 1694.09  4977.7 1695.08  4992.6 1690.46
  4992.9 1689.96  4996.6 1690.46  5006.7 1690.73  5026.8 1695.46  5157.4 1696.16
  5249.2 1702.61  5328.3 1708.99  5358.2 1711.49  5427.5 1712.98  5468.8 1713.14
#Mann=8,-1,0
  4172.4    0.07       0  4446.3   0.035       0  4740.5    0.07       0
  4992.6    0.07       0  4996.6    0.07       0  5249.2   0.035       0
  5328.3    0.07       0  5427.5   0.035       0
Bank Sta=4992.6,4996.6
Exp/Cntr=0.3,0.1

Type RM Length L Ch R = 1,1607,0,0,0
BEGIN DESCRIPTION:
MULBERRY CREEK TRIBUTARY 12 1.0
END DESCRIPTION:
XS GIS Cut Line= 3
      1546695.05      6872772.09      1547108.26      6873424.89
      1547641.50      6873185.97
#Sta/Elev= 30
  4233.4 1707.65  4390.3 1704.17  4396.2 1706.04  4447.9 1706.70  4463.2 1706.23
  4469.1 1703.09  4484.4 1703.21  4508.9 1700.26  4542.0 1698.40  4556.1 1699.77
  4563.2 1697.50  4578.4 1699.98  4599.6 1697.32  4630.2 1697.71  4693.7 1693.02
  4759.0 1692.71  4796.6 1693.17  4816.3 1688.83  4816.6 1688.33  4820.3 1688.83
  4824.2 1691.88  4832.1 1693.26  5047.2 1691.72  5182.5 1693.11  5234.4 1694.43
  5292.4 1699.29  5350.3 1704.66  5477.2 1709.86  5531.6 1710.22  5590.3 1710.10
#Mann=10,-1,0
  4233.4   0.035       0  4508.9    0.07       0  4556.1   0.035       0
  4759.0    0.07       0  4816.3    0.07       0  4820.3    0.07       0
  5047.2   0.035       0  5182.5    0.07       0  5292.4   0.035       0
  5531.6    0.07       0
Bank Sta=4816.3,4820.3
Exp/Cntr=0.3,0.1

Chan Stop Cuts=-1