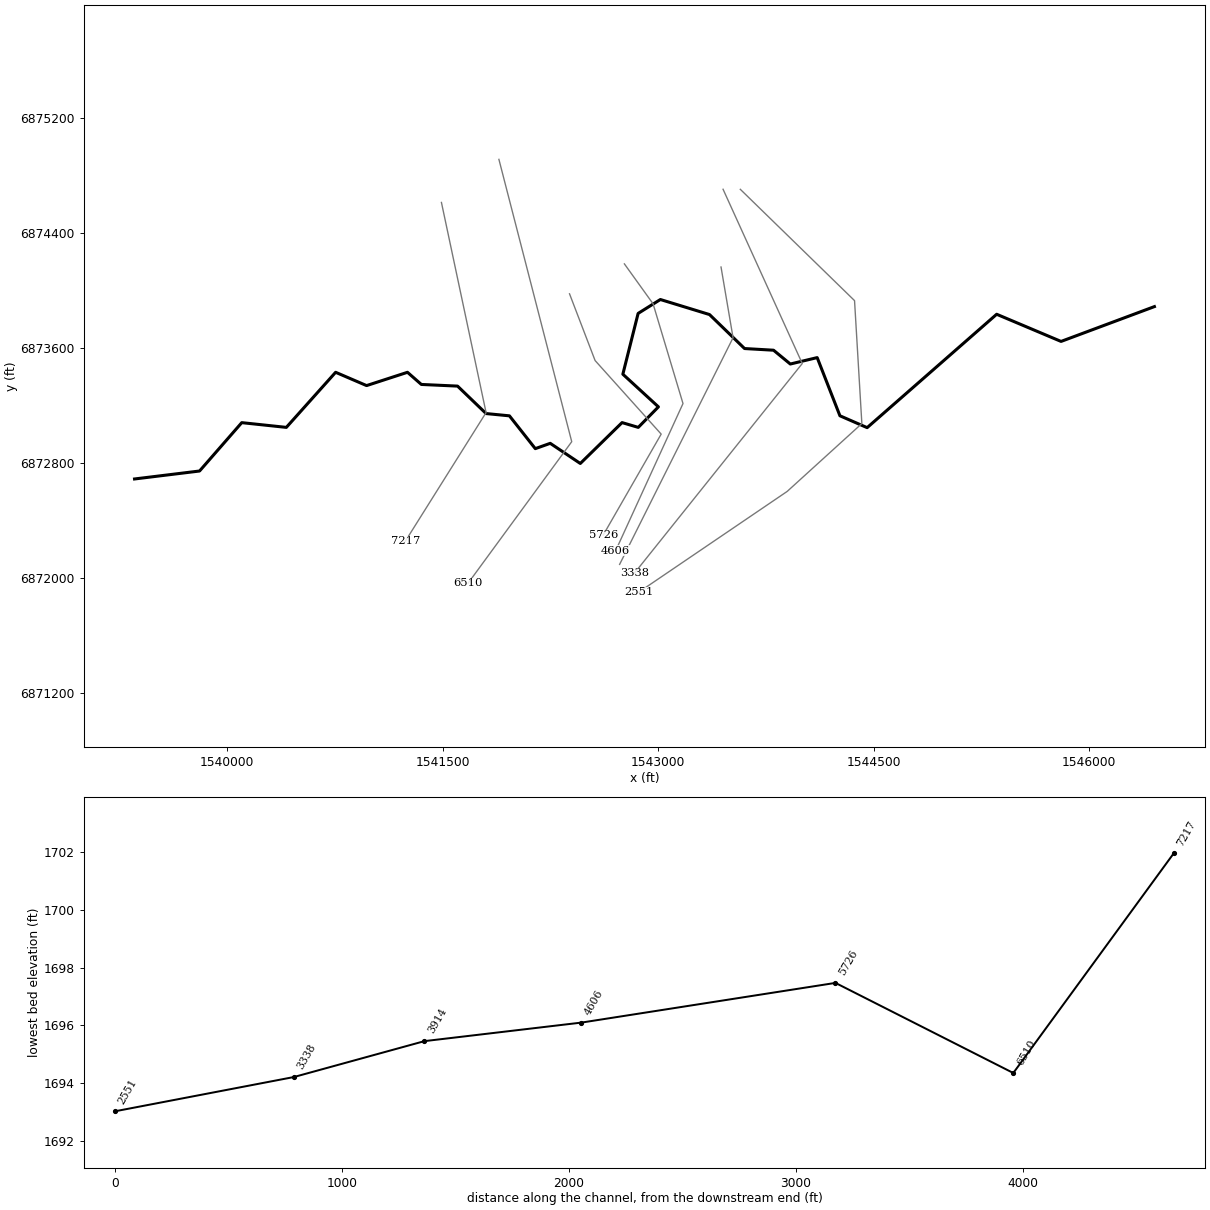
--- MULBERRY CREEK TRIBUTARY 13.prj (project) ---

Proj Title=MULBERRY CREEK TRIBUTARY 13 Base Level Engineering
Current Plan=p01
Default Exp/Contr=0.3,0.1
English Units
Geom File=g01
Flow File=f01
Plan File=p01
Y Axis Title=Elevation
X Axis Title(PF)=Main Channel Distance
X Axis Title(XS)=Station
BEGIN DESCRIPTION:
MULBERRY CREEK TRIBUTARY 13
END DESCRIPTION:
DSS Export Rating Curves= 0
DSS Export Rating Curve Sorted= 0
DSS Export Volume Flow Curves= 0
DXF OffsetX= 0
DXF OffsetY= 0
DXF ScaleX= 1
DXF ScaleY= 10

--- MULBERRY CREEK TRIBUTARY 13.p01 (plan) ---

Plan Title=Multiple Run
Short Identifier=Multiple
Geom File=g01
Flow File=f01
Subcritical Flow
K Sum by GR= 0
Std Step Tol= 0.01
Critical Tol= 0.01
Num of Std Step Trials= 20
Max Error Tol= 0.3
Flow Tol Ratio= 0.001
Split Flow NTrial= 30
Split Flow Tol= 0.02
Split Flow Ratio= 0.02
Log Output Level= 0
Friction Slope Method= 1
Unsteady Friction Slope Method= 2
Unsteady Bridges Friction Slope Method= 1
Parabolic Critical Depth
Global Vel Dist=  1 , 1 , 1
Global Log Level= 0
CheckData=True
Encroach Param= -1, 0, 0, 0
BEGIN DESCRIPTION:
Multiple Run
END DESCRIPTION:

--- MULBERRY CREEK TRIBUTARY 13.f01 (steady flow) ---

Flow Title=Multiple
Number of Profiles=7
Profile Names=10-year,25-year,50-year,1pct_min,100-year,1pct_plu,500-year
River Rch & RM= MULBERRY CREEK T,Reach-1,7217
     258     355     434     264     527    1052     788
River Rch & RM= MULBERRY CREEK T,Reach-1,6510
     305     424     521     319     636    1269     960
Boundary for River Rch & Prof#=MULBERRY CREEK T,Reach-1,1
Up Type=0
Dn Type=3
Dn Slope=0.005
Boundary for River Rch & Prof#=MULBERRY CREEK T,Reach-1,2
Up Type=0
Dn Type=3
Dn Slope=0.005
Boundary for River Rch & Prof#=MULBERRY CREEK T,Reach-1,3
Up Type=0
Dn Type=3
Dn Slope=0.005
Boundary for River Rch & Prof#=MULBERRY CREEK T,Reach-1,4
Up Type=0
Dn Type=3
Dn Slope=0.005
Boundary for River Rch & Prof#=MULBERRY CREEK T,Reach-1,5
Up Type=0
Dn Type=3
Dn Slope=0.005
Boundary for River Rch & Prof#=MULBERRY CREEK T,Reach-1,6
Up Type=0
Dn Type=3
Dn Slope=0.005
Boundary for River Rch & Prof#=MULBERRY CREEK T,Reach-1,7
Up Type=0
Dn Type=3
Dn Slope=0.005

--- MULBERRY CREEK TRIBUTARY 13.g01 (geometry) ---

Geom Title=Existing Conditions
Program Version=4.10

River Reach=MULBERRY CREEK T,Reach-1
Reach XY= 30
        1539355.        6872688.      1539807.67      6872743.42
      1540101.42      6873080.11      1540411.74      6873047.13
      1540754.89      6873430.69      1540970.39      6873338.09
       1541255.1      6873430.66      1541351.66      6873346.02
      1541603.73      6873334.51      1541802.32       6873143.4
      1541964.82      6873127.53      1542144.92       6872899.1
      1542248.88      6872936.16      1542458.24      6872795.84
      1542748.95       6873080.5      1542861.73      6873047.15
      1543002.05      6873190.01      1542754.46      6873417.38
      1542860.73      6873840.55       1543015.7       6873937.3
       1543357.7      6873832.64      1543601.67      6873596.01
       1543803.5      6873584.38      1543920.22      6873488.25
      1544107.31      6873532.92      1544265.62      6873127.95
       1544455.1      6873045.31      1545356.72      6873834.66
      1545804.99      6873645.53        1546455.        6873888.

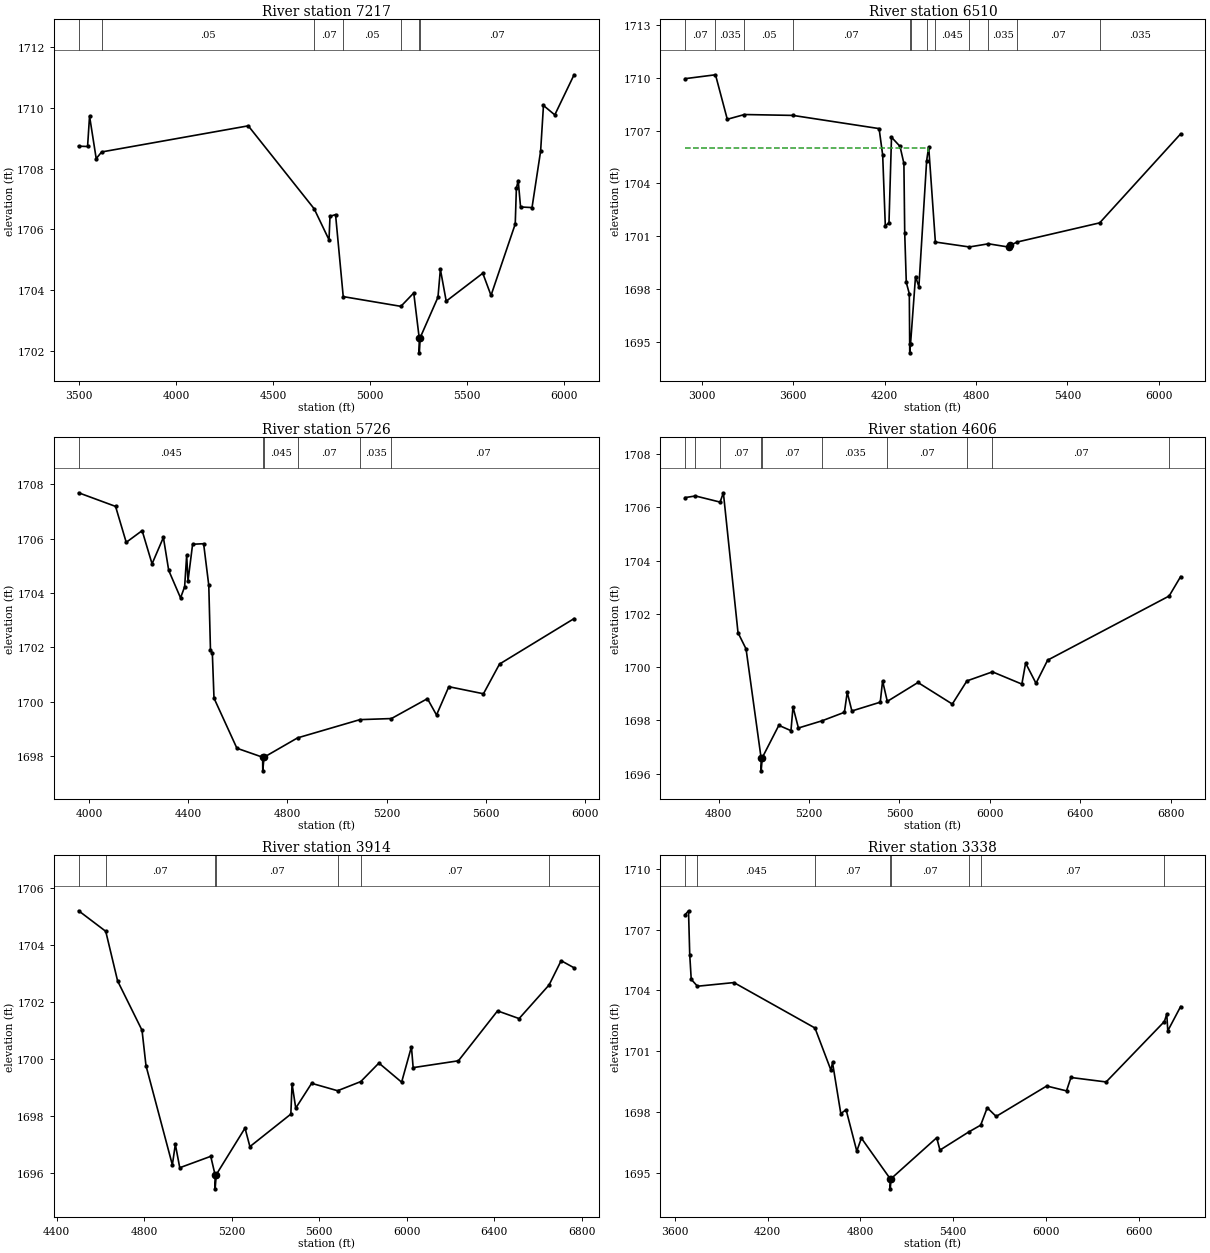
Type RM Length L Ch R = 1 ,7217    ,707,707,707
BEGIN DESCRIPTION:
Mapping XS 18146e2d
END DESCRIPTION:
XS GIS Cut Line= 3
      1541491.49       6874613.1      1541802.26      6873150.06
       1541239.9      6872254.45
#Sta/Elev= 30
  3498.7 1708.74  3544.8 1708.73    3555 1709.73  3589.3 1708.33  3617.1 1708.55
  4372.9 1709.41  4712.5 1706.68    4789 1705.66  4794.1 1706.43  4822.7 1706.49
  4862.3 1703.79  5159.4 1703.47  5225.7 1703.91  5253.6 1702.44  5254.1 1701.94
  5258.9 1702.44  5350.5 1703.77  5362.9 1704.69    5393 1703.64  5581.4 1704.56
  5623.9 1703.83  5748.7 1706.18  5754.6 1707.36    5764 1707.61  5776.1 1706.74
  5835.2 1706.72  5879.5 1708.58  5894.2 1710.08  5952.5 1709.77  6051.9 1711.09
#Mann= 7 ,-1 , 0
  3498.7     .07       0  3617.1     .05       0  4712.5     .07       0
  4862.3     .05       0  5159.4     .07       0  5253.6     .05       0
  5258.9     .07       0
Bank Sta=5253.6,5258.9
XS Rating Curve= 0 ,0
Exp/Cntr=0.3,0.1

Type RM Length L Ch R = 1 ,6510    ,784,784,784
BEGIN DESCRIPTION:
Mapping XS 68a0d559
END DESCRIPTION:
XS GIS Cut Line= 3
      1541891.61      6874912.83      1542398.56       6872947.5
      1541676.91      6871962.16
#Sta/Elev= 30
  2892.1 1709.95  3090.9 1710.17  3168.3 1707.64  3281.1 1707.91  3598.9 1707.86
  4164.5 1707.11    4188  1705.6  4205.2 1701.59  4229.3 1701.75  4245.8 1706.62
  4301.6  1706.1  4327.2 1705.13  4332.6 1701.16  4342.9 1698.36  4362.7 1697.72
  4365.1 1694.86  4365.5 1694.36  4370.7 1694.86  4403.4  1698.7  4425.5 1698.12
  4476.5 1705.29  4489.9 1706.07  4533.7 1700.66  4756.6 1700.38    4882 1700.56
  5017.5 1700.37  5023.7 1700.47  5070.1 1700.66  5611.8 1701.75  6143.1 1706.81
#Mann= 12 ,-1 , 0
  2892.1     .07       0  3090.9    .035       0  3281.1     .05       0
  3598.9     .07       0  4365.1    .035       0  4370.7     .07       0
  4476.5     .05       0  4533.7    .045       0  4756.6     .07       0
    4882    .035       0  5070.1     .07       0  5611.8    .035       0
#XS Ineff= 2 , 0
       0  4484.7 1705.98               0
Permanent Ineff=
       F       F
Bank Sta=5017.5,5023.7
XS Rating Curve= 0 ,0
Exp/Cntr=0.3,0.1

Type RM Length L Ch R = 1 ,5726    ,1120,1120,1120
BEGIN DESCRIPTION:
Mapping XS c493af73
END DESCRIPTION:
XS GIS Cut Line= 4
      1542383.22      6873976.94      1542561.18      6873512.52
      1543021.25      6873000.37      1542617.62      6872297.28
#Sta/Elev= 30
  3958.4 1707.68  4107.2 1707.18  4150.2 1705.86  4214.3 1706.29  4254.3 1705.07
    4300 1706.04  4321.4 1704.83  4369.1 1703.82  4385.6 1704.23  4393.8 1705.39
  4399.1 1704.44  4417.7 1705.79  4462.1 1705.81  4482.9 1704.28  4489.7  1701.9
  4497.2  1701.8  4503.9 1700.14  4596.2  1698.3  4699.9 1697.97  4700.4 1697.47
  4705.5 1697.97  4840.6 1698.68    5092 1699.35  5218.9 1699.39  5363.9 1700.12
  5400.6 1699.52  5450.2 1700.56  5589.7  1700.3  5654.4 1701.39  5954.9 1703.06
#Mann= 6 ,-1 , 0
  3958.4    .045       0  4699.9     .07       0  4705.5    .045       0
  4840.6     .07       0    5092    .035       0  5218.9     .07       0
Bank Sta=4699.9,4705.5
XS Rating Curve= 0 ,0
Exp/Cntr=0.3,0.1

Type RM Length L Ch R = 1 ,4606    ,692,692,692
BEGIN DESCRIPTION:
Mapping XS ae28eb84
END DESCRIPTION:
XS GIS Cut Line= 4
      1542765.17      6874185.27      1542964.82      6873907.48
      1543173.15      6873213.04       1542704.4      6872188.71
#Sta/Elev= 30
  4651.2 1706.37  4696.7 1706.43  4805.7  1706.2  4820.2 1706.55  4885.1 1701.29
  4920.7 1700.68    4987  1696.6  4987.5  1696.1  4992.7  1696.6  5065.8 1697.81
  5119.5 1697.61  5128.5  1698.5  5152.5 1697.71  5256.9 1697.98  5356.1  1698.3
  5368.6 1699.05  5389.2 1698.35  5514.8 1698.68  5525.2 1699.48    5546 1698.71
  5681.8 1699.42  5833.8 1698.61  5898.5 1699.48  6011.6 1699.82  6141.8 1699.36
  6158.4 1700.15  6204.4 1699.39  6255.9 1700.26  6793.8 1702.67  6844.8  1703.4
#Mann= 10 ,-1 , 0
  4651.2    .045       0  4696.7     .05       0  4805.7     .07       0
    4987     .07       0  4992.7     .07       0  5256.9    .035       0
    5546     .07       0  5898.5    .035       0  6011.6     .07       0
  6793.8    .035       0
Bank Sta=4987,4992.7
XS Rating Curve= 0 ,0
Exp/Cntr=0.3,0.1

Type RM Length L Ch R = 1 ,3914    ,576,576,576
BEGIN DESCRIPTION:
Mapping XS 6702faa8
END DESCRIPTION:
XS GIS Cut Line= 3
       1543437.9       6874163.6      1543521.66      6873671.27
      1542731.92      6872093.38
#Sta/Elev= 30
  4500.6 1705.21  4624.5 1704.49  4678.7 1702.75  4790.3 1701.02  4808.4 1699.78
  4928.9  1696.3  4942.5 1697.02  4962.7  1696.2  5104.3  1696.6  5123.8 1695.96
  5124.3 1695.46  5129.6 1695.96  5260.9 1697.59  5283.2 1696.94  5470.3 1698.08
  5475.9 1699.14  5492.7 1698.29  5565.3 1699.16    5684  1698.9  5789.7 1699.22
  5872.7 1699.87  5976.5  1699.2  6021.3 1700.44  6029.2 1699.71    6236 1699.95
  6414.8  1701.7  6513.3 1701.43  6650.4 1702.61  6705.4 1703.46  6764.5 1703.21
#Mann= 7 ,-1 , 0
  4500.6    .045       0  4624.5     .07       0  5123.8     .07       0
  5129.6     .07       0    5684    .035       0  5789.7     .07       0
  6650.4    .035       0
Bank Sta=5123.8,5129.6
XS Rating Curve= 0 ,0
Exp/Cntr=0.3,0.1

Type RM Length L Ch R = 1 ,3338    ,787,787,787
BEGIN DESCRIPTION:
Mapping XS a45017d8
END DESCRIPTION:
XS GIS Cut Line= 3
      1543452.14      6874704.74      1544003.41      6873491.73
      1542834.84      6872032.08
#Sta/Elev= 30
  3667.6 1707.74    3689 1707.93    3697 1705.75  3706.6 1704.55  3746.8 1704.21
  3982.6 1704.39  4506.4 1702.15  4609.6 1700.07  4619.7 1700.45  4673.3 1697.93
  4707.5 1698.12  4776.6 1696.08  4806.4 1696.72  4992.3 1694.72  4992.7 1694.22
  4998.1 1694.72  5293.2 1696.74  5314.1 1696.13  5499.2 1697.02  5577.4 1697.36
  5619.8 1698.22  5677.4 1697.79    6004 1699.29  6132.1 1699.05  6160.8 1699.71
  6388.2 1699.49  6764.7 1702.47  6780.2 1702.84  6786.7 1702.01  6869.8 1703.21
#Mann= 8 ,-1 , 0
  3667.6     .07       0  3746.8    .045       0  4506.4     .07       0
  4992.3     .07       0  4998.1     .07       0  5499.2    .035       0
  5577.4     .07       0  6764.7    .035       0
Bank Sta=4992.3,4998.1
XS Rating Curve= 0 ,0
Exp/Cntr=0.3,0.1

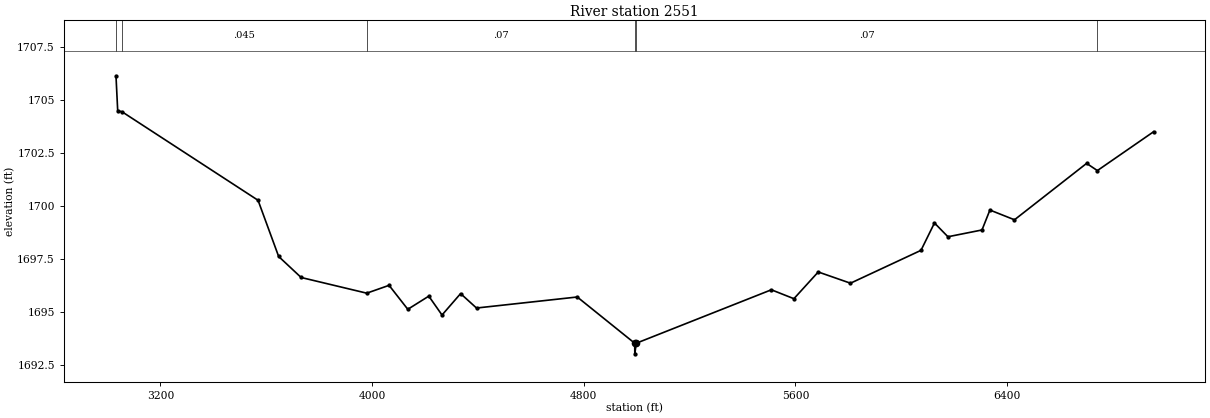
Type RM Length L Ch R = 1 ,2551    ,0,0,0
BEGIN DESCRIPTION:
MULBERRY CREEK TRIBUTARY 13 1.0
END DESCRIPTION:
XS GIS Cut Line= 5
       1543572.2      6874704.42      1544367.36      6873929.57
       1544418.3      6873073.75      1543898.61      6872601.45
      1542863.82      6871898.88
#Sta/Elev= 30
  3032.4 1706.15  3038.9  1704.5  3055.7 1704.45  3569.2 1700.28  3647.1 1697.63
    3732 1696.64    3980  1695.9  4064.3 1696.27  4135.1 1695.14  4214.4 1695.76
  4264.4 1694.87  4334.6 1695.88  4394.7  1695.2  4775.4 1695.72  4992.5 1693.54
  4992.9 1693.04  4998.3 1693.54  5508.9 1696.06  5594.1 1695.64    5686  1696.9
  5807.8 1696.37  6074.3 1697.92  6125.2 1699.21  6176.1 1698.56  6304.8 1698.88
  6334.7 1699.82  6427.6 1699.36  6700.1 1702.02  6740.8 1701.68    6953 1703.51
#Mann= 6 ,-1 , 0
  3032.4     .07       0  3055.7    .045       0    3980     .07       0
  4992.5     .07       0  4998.3     .07       0  6740.8    .035       0
Bank Sta=4992.5,4998.3
XS Rating Curve= 0 ,0
Exp/Cntr=0.3,0.1

Chan Stop Cuts=-1
Use User Specified Reach Order=0
Composite Channel Slope=5