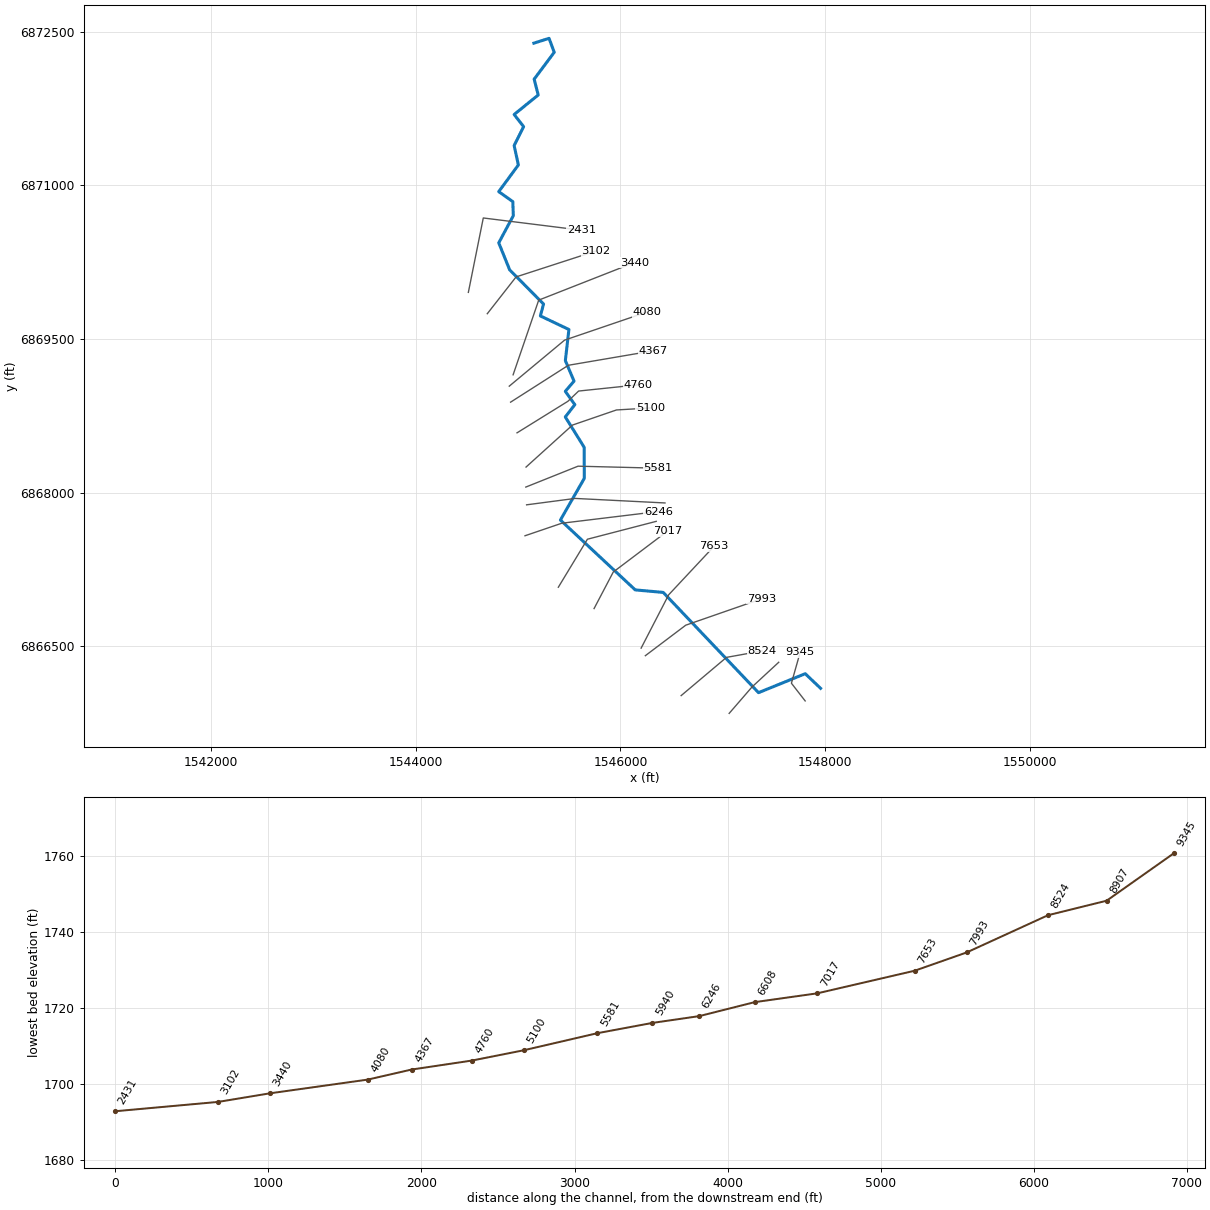
--- MULBERRY CREEK TRIBUTARY 14.prj (project) ---

Proj Title=MULBERRY CREEK TRIBUTARY 14 Base Level Engineering
Current Plan=p01
Default Exp/Contr=0.3,0.1
English Units
Geom File=g01
Flow File=f01
Plan File=p01
Y Axis Title=Elevation
X Axis Title(PF)=Main Channel Distance
X Axis Title(XS)=Station
BEGIN DESCRIPTION:
MULBERRY CREEK TRIBUTARY 14
END DESCRIPTION:
DSS Export Rating Curves= 0
DSS Export Rating Curve Sorted= 0
DSS Export Volume Flow Curves= 0
DXF OffsetX= 0
DXF OffsetY= 0
DXF ScaleX= 1
DXF ScaleY= 10

--- MULBERRY CREEK TRIBUTARY 14.p01 (plan) ---

Plan Title=Multiple Run
Short Identifier=Multiple
Geom File=g01
Flow File=f01
Subcritical Flow
K Sum by GR= 0
Std Step Tol= 0.01
Critical Tol= 0.01
Num of Std Step Trials= 20
Max Error Tol= 0.3
Flow Tol Ratio= 0.001
Split Flow NTrial= 30
Split Flow Tol= 0.02
Split Flow Ratio= 0.02
Log Output Level= 0
Friction Slope Method= 1
Unsteady Friction Slope Method= 2
Unsteady Bridges Friction Slope Method= 1
Parabolic Critical Depth
Global Vel Dist=  1 , 1 , 1
Global Log Level= 0
CheckData=True
Encroach Param= -1, 0, 0, 0
BEGIN DESCRIPTION:
Multiple Run
END DESCRIPTION:

--- MULBERRY CREEK TRIBUTARY 14.f01 (steady flow) ---

Flow Title=Multiple
Number of Profiles=7
Profile Names=10-year,25-year,50-year,1pct_min,100-year,1pct_plu,500-year
River Rch & RM= MULBERRY CREEK T,Reach-1,9345
     144     195     236     143     286     571     424
River Rch & RM= MULBERRY CREEK T,Reach-1,4760
     201     276     339     207     414     826     625
Boundary for River Rch & Prof#=MULBERRY CREEK T,Reach-1,1
Up Type=0
Dn Type=3
Dn Slope=0.005
Boundary for River Rch & Prof#=MULBERRY CREEK T,Reach-1,2
Up Type=0
Dn Type=3
Dn Slope=0.005
Boundary for River Rch & Prof#=MULBERRY CREEK T,Reach-1,3
Up Type=0
Dn Type=3
Dn Slope=0.005
Boundary for River Rch & Prof#=MULBERRY CREEK T,Reach-1,4
Up Type=0
Dn Type=3
Dn Slope=0.005
Boundary for River Rch & Prof#=MULBERRY CREEK T,Reach-1,5
Up Type=0
Dn Type=3
Dn Slope=0.005
Boundary for River Rch & Prof#=MULBERRY CREEK T,Reach-1,6
Up Type=0
Dn Type=3
Dn Slope=0.005
Boundary for River Rch & Prof#=MULBERRY CREEK T,Reach-1,7
Up Type=0
Dn Type=3
Dn Slope=0.005

--- MULBERRY CREEK TRIBUTARY 14.g01 (geometry) ---

Geom Title=Existing Conditions
Program Version=4.10

River Reach=MULBERRY CREEK T,Reach-1
Reach XY= 30
        1547955.        6866088.      1547805.01      6866230.92
      1547348.83      6866045.76      1546418.34      6867024.64
        1546145.      6867049.24      1545414.24      6867731.45
      1545647.47      6868137.99      1545646.73      6868441.22
      1545462.08        6868738.      1545555.46      6868858.16
      1545462.11        6868988.      1545547.66       6869087.9
      1545462.59      6869288.01      1545497.32       6869591.7
      1545218.53      6869724.59      1545249.87      6869840.28
      1544918.65      6870174.67       1544812.3      6870438.08
       1544954.5      6870703.22      1544949.65       6870840.7
      1544811.98      6870937.79      1545003.81       6871198.5
      1544962.53      6871388.01      1545055.04      6871572.66
       1544962.6      6871691.34      1545197.63      6871881.66
      1545158.13      6872036.36      1545353.92      6872298.55
      1545303.63      6872434.99        1545155.        6872388.

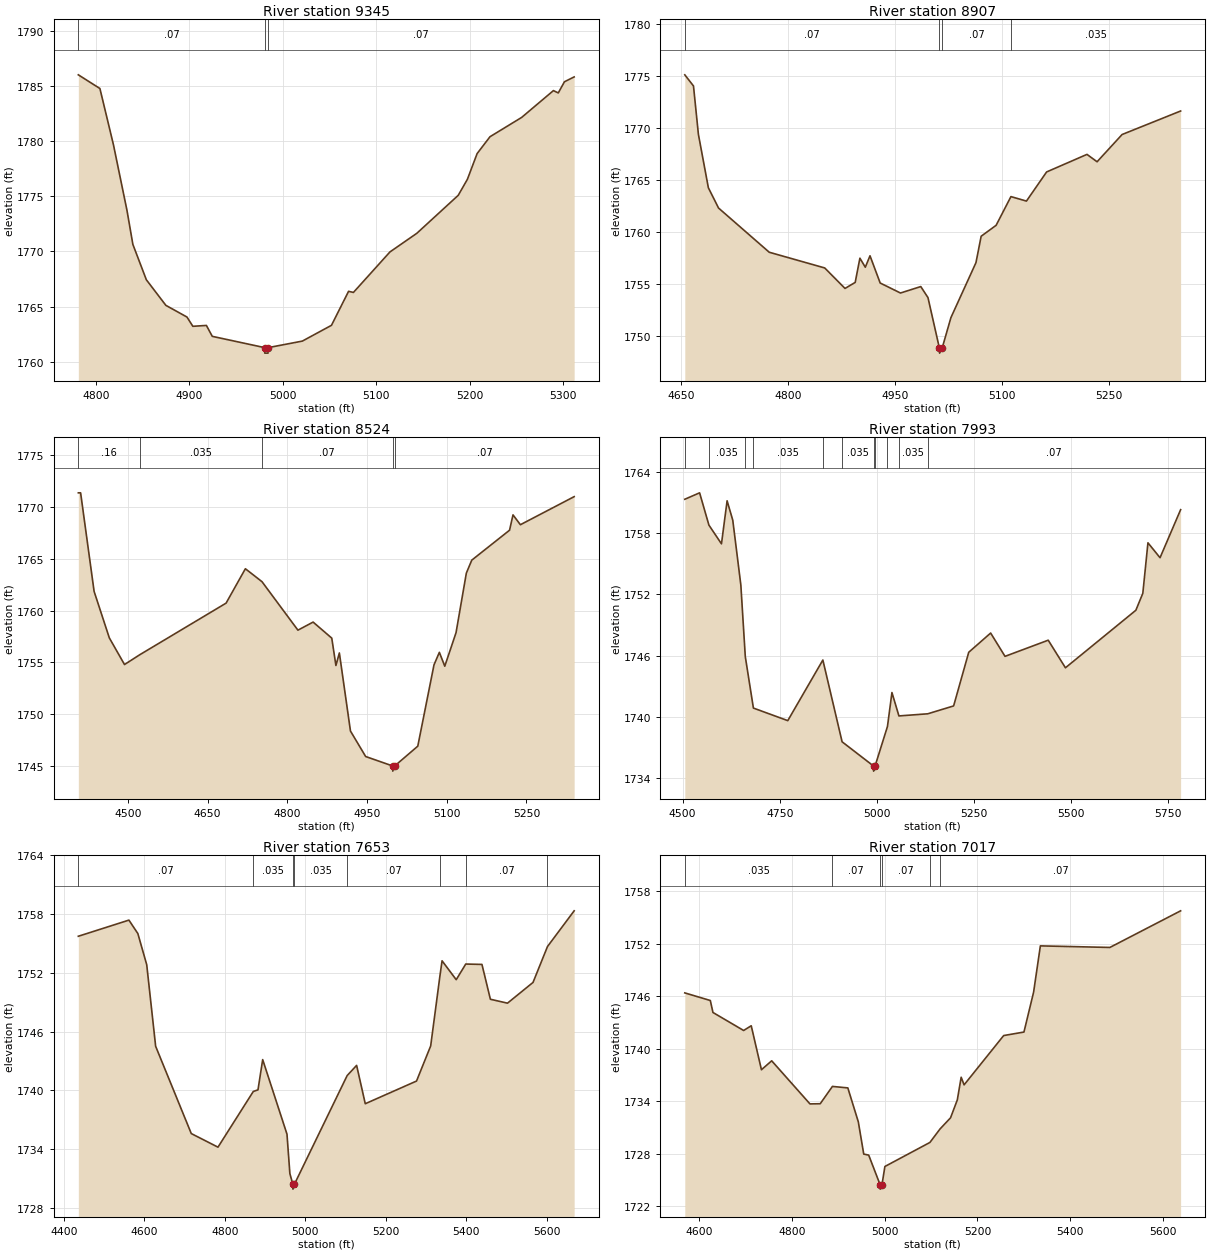
Type RM Length L Ch R = 1 ,9345    ,438,438,438
BEGIN DESCRIPTION:
MULBERRY CREEK TRIBUTARY 14 14.0
END DESCRIPTION:
XS GIS Cut Line= 3
      1547804.35      6865965.03      1547670.09      6866137.79
        1547755.      6866438.02
#Sta/Elev= 30
  4781.2 1786.01  4804.3 1784.77  4818.8 1779.67  4833.2 1773.76  4839.6 1770.64
    4854 1767.44  4874.9 1765.12  4897.5 1764.06  4903.8 1763.22  4918.3  1763.3
  4924.6 1762.31  4980.6 1761.29  4980.8 1760.79  4984.3 1760.79  4984.6 1761.29
    5021 1761.88  5052.2 1763.31  5070.5 1766.39  5075.7 1766.29  5114.8 1769.96
  5143.6 1771.65  5187.9 1775.09  5197.7 1776.54  5208.1 1778.87  5221.9  1780.4
  5255.8 1782.15  5289.8 1784.58    5295 1784.37  5301.6 1785.38    5312 1785.82
#Mann= 3 ,-1 , 0
  4781.2     .07       0  4980.6     .07       0  4984.6     .07       0
Bank Sta=4980.6,4984.6
XS Rating Curve= 0 ,0
Exp/Cntr=0.3,0.1

Type RM Length L Ch R = 1 ,8907    ,383,383,383
BEGIN DESCRIPTION:
Mapping XS efe170e5
END DESCRIPTION:
XS GIS Cut Line= 3
      1547062.19      6865843.52      1547285.69      6866101.74
      1547546.14      6866342.66
#Sta/Elev= 30
  4654.7 1775.09  4666.9 1774.02  4673.8 1769.37  4687.8 1764.23  4702.1 1762.28
  4773.3 1758.03  4851.2 1756.52  4879.7 1754.55    4894 1755.13  4900.6 1757.46
  4908.2 1756.59  4914.8 1757.69  4929.1 1755.07  4957.6 1754.11  4986.1 1754.73
  4996.2 1753.67  5012.2 1748.83  5012.5 1748.33  5016.2 1748.83  5028.4 1751.74
  5063.6 1757.03  5070.9 1759.57  5091.9 1760.62  5112.7 1763.38  5134.5 1762.95
  5162.8 1765.75  5219.5 1767.44  5233.7 1766.73  5268.8 1769.35    5351 1771.61
#Mann= 4 ,-1 , 0
  4654.7     .07       0  5012.2     .07       0  5016.2     .07       0
  5112.7    .035       0
Bank Sta=5012.2,5016.2
XS Rating Curve= 0 ,0
Exp/Cntr=0.3,0.1

Type RM Length L Ch R = 1 ,8524    ,531,531,531
BEGIN DESCRIPTION:
Mapping XS 545c87e1
END DESCRIPTION:
XS GIS Cut Line= 3
      1546593.41       6866017.1      1547036.12      6866390.37
      1547384.64      6866453.15
#Sta/Elev= 30
  4406.7 1771.38    4411 1771.38  4436.4 1761.86    4465 1757.38  4493.6  1754.8
  4522.1 1755.74  4684.8 1760.73  4721.1 1764.05  4752.4  1762.8    4820 1758.12
  4848.6  1758.9  4883.7 1757.35  4891.5 1754.71    4898 1755.92  4918.9 1748.38
  4947.5 1745.92  4998.2 1745.01  4998.5 1744.51  5002.2 1745.01  5045.6 1746.92
  5076.1 1754.77  5086.2 1755.98  5096.4 1754.64  5117.6 1757.88    5137 1763.63
  5147.2 1764.88  5218.3 1767.77  5224.8 1769.25  5238.7  1768.3  5339.9 1771.01
#Mann= 5 ,-1 , 0
  4406.7     .16       0  4522.1    .035       0  4752.4     .07       0
  4998.2     .07       0  5002.2     .07       0
Bank Sta=4998.2,5002.2
XS Rating Curve= 0 ,0
Exp/Cntr=0.3,0.1

Type RM Length L Ch R = 1 ,7993    ,340,340,340
BEGIN DESCRIPTION:
Mapping XS 534985e9
END DESCRIPTION:
XS GIS Cut Line= 3
      1546243.75      6866406.85      1546638.29      6866704.63
      1547376.89      6866961.54
#Sta/Elev= 30
  4505.7 1761.31  4543.8 1761.94  4567.8 1758.78  4600.1 1756.95  4614.6 1761.16
  4629.2 1759.26    4650 1752.91  4661.4 1745.92  4682.3 1740.88  4770.8 1739.65
  4861.1 1745.58  4910.6 1737.58  4991.5 1735.21  4991.7 1734.71  4995.5 1735.21
  5027.4 1739.08  5038.9  1742.4  5056.9 1740.11  5131.2 1740.32  5197.7 1741.09
  5236.6 1746.34    5293 1748.22    5330 1745.94  5441.2 1747.52  5485.5 1744.82
  5666.8 1750.45  5684.7 1752.11  5697.9 1757.05    5729 1755.59    5782 1760.29
#Mann= 11 ,-1 , 0
  4505.7     .07       0  4567.8    .035       0  4661.4     .07       0
  4682.3    .035       0  4861.1     .07       0  4910.6    .035       0
  4991.5    .035       0  4995.5    .035       0  5027.4     .07       0
  5056.9    .035       0  5131.2     .07       0
Bank Sta=4991.5,4995.5
XS Rating Curve= 0 ,0
Exp/Cntr=0.3,0.1

Type RM Length L Ch R = 1 ,7653    ,636,636,636
BEGIN DESCRIPTION:
Mapping XS 4ced16ba
END DESCRIPTION:
XS GIS Cut Line= 3
      1546202.53      6866480.63      1546471.63      6867001.48
       1546913.6      6867473.78
#Sta/Elev= 30
  4435.6 1755.74  4561.4 1757.39  4583.6 1756.02  4605.7 1752.83  4627.9 1744.49
  4716.5 1735.57  4782.9 1734.18  4870.7 1739.87  4882.4 1740.04  4894.1 1743.13
  4954.5 1735.51  4961.7 1731.48    4969 1730.39  4969.3 1729.89    4973 1730.39
  5104.2  1741.5  5127.7 1742.54  5149.2 1738.62  5276.7 1740.94  5311.9 1744.53
  5335.1 1751.75  5340.2 1753.23  5375.4  1751.3  5399.1  1752.9  5439.4 1752.86
  5460.4  1749.3  5502.9  1748.9  5566.4 1751.02  5602.4 1754.69  5668.7 1758.34
#Mann= 8 ,-1 , 0
  4435.6     .07       0  4870.7    .035       0    4969    .035       0
    4973    .035       0  5104.2     .07       0  5335.1    .035       0
  5399.1     .07       0  5602.4    .035       0
Bank Sta=4969,4973
XS Rating Curve= 0 ,0
Exp/Cntr=0.3,0.1

Type RM Length L Ch R = 1 ,7017    ,409,409,409
BEGIN DESCRIPTION:
Mapping XS af9b9e67
END DESCRIPTION:
XS GIS Cut Line= 3
      1545743.03      6866866.93      1545930.53       6867223.7
       1546461.8      6867624.76
#Sta/Elev= 30
  4569.3 1746.39  4624.3 1745.52    4630 1744.15  4696.1 1742.09  4712.5 1742.63
  4734.5  1737.6  4756.6 1738.62  4839.1 1733.69  4861.2 1733.71  4887.5 1735.69
  4920.7 1735.52  4943.3 1731.64    4955 1727.95  4965.7 1727.83  4990.3 1724.44
  4990.5 1723.94  4994.3 1724.44  5000.6 1726.53  5097.6 1729.28  5119.4 1730.82
  5142.1  1732.1  5156.7 1734.15    5165 1736.74  5171.3 1735.87  5256.6 1741.51
  5300.3 1741.91  5321.1 1746.47  5335.7 1751.77  5485.5 1751.59    5638 1755.78
#Mann= 6 ,-1 , 0
  4569.3    .035       0  4887.5     .07       0  4990.3     .07       0
  4994.3     .07       0  5097.6    .035       0  5119.4     .07       0
Bank Sta=4990.3,4994.3
XS Rating Curve= 0 ,0
Exp/Cntr=0.3,0.1

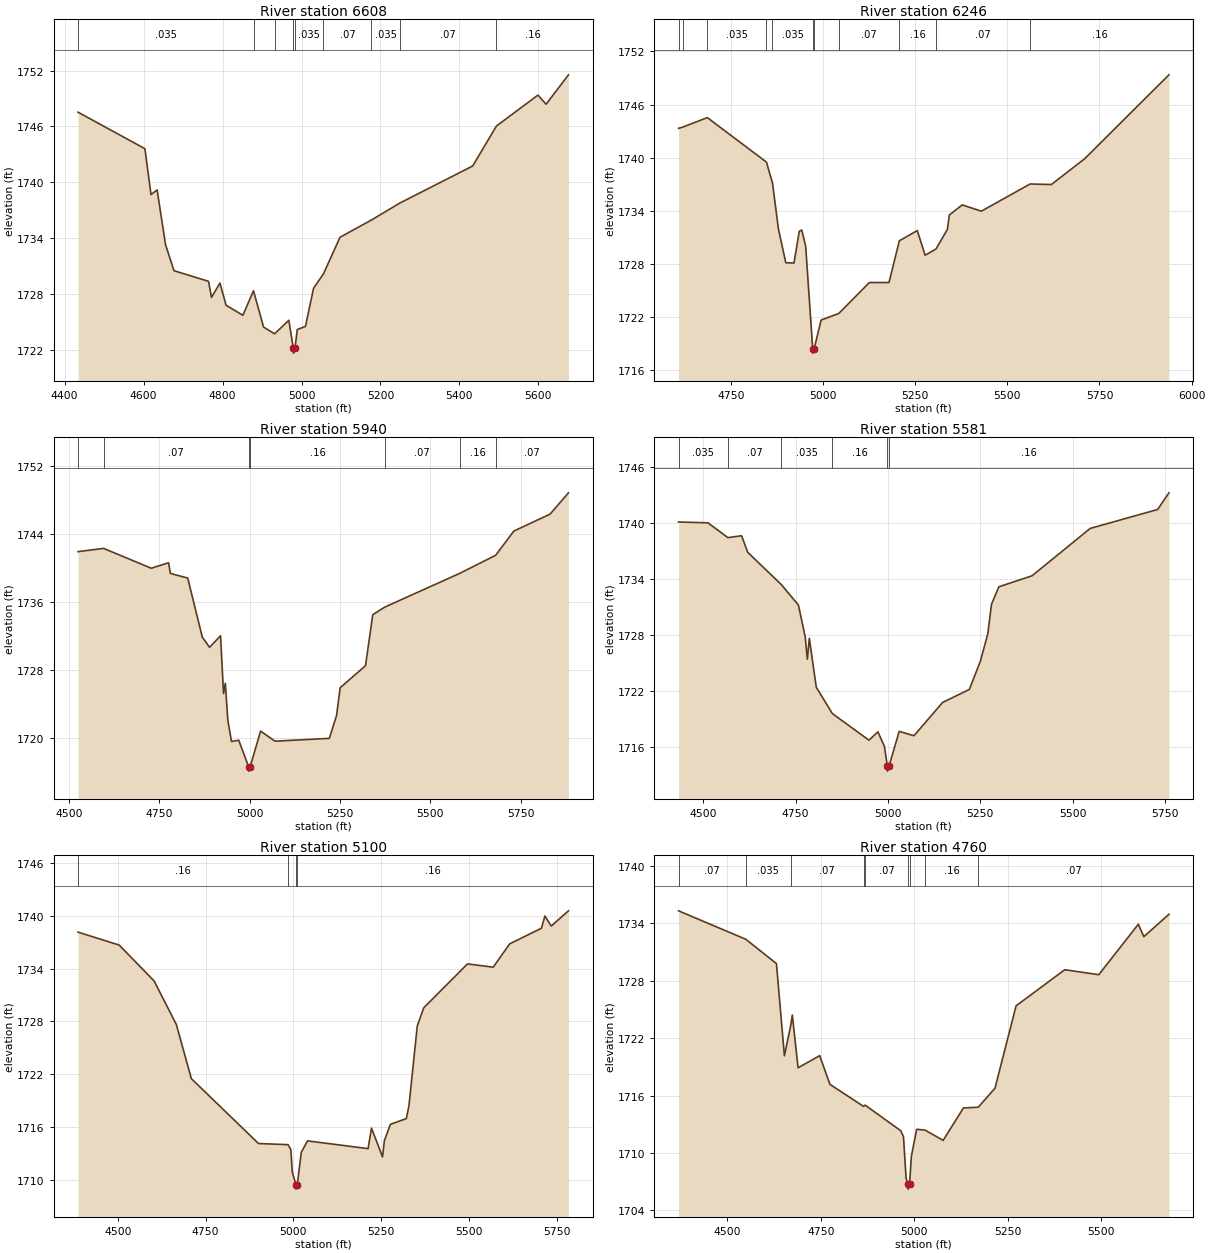
Type RM Length L Ch R = 1 ,6608    ,362,362,362
BEGIN DESCRIPTION:
Mapping XS 1a9133de
END DESCRIPTION:
XS GIS Cut Line= 3
      1545394.07      6867075.26      1545677.93      6867544.02
      1546349.84       6867718.5
#Sta/Elev= 30
    4434 1747.52  4603.3  1743.6  4618.8 1738.67  4634.3 1739.16  4655.6 1733.28
    4677 1730.48  4764.5 1729.34    4772 1727.61  4793.4 1729.15  4808.9 1726.77
  4851.5 1725.69  4878.4 1728.32  4903.9 1724.42  4931.9  1723.7  4967.9 1725.15
  4979.4 1722.12  4979.7 1721.62  4983.4 1722.12  4989.3 1724.16    5010 1724.49
  5030.6  1728.6  5055.7 1730.15  5097.6 1734.08  5177.1 1735.93  5249.4 1737.76
  5433.6 1741.74  5493.9 1746.04  5598.9 1749.36  5619.6 1748.38  5676.2 1751.54
#Mann= 9 ,-1 , 0
    4434    .035       0  4878.4     .07       0  4931.9    .035       0
  4979.4    .035       0  4983.4    .035       0  5055.7     .07       0
  5177.1    .035       0  5249.4     .07       0  5493.9     .16       0
Bank Sta=4979.4,4983.4
XS Rating Curve= 0 ,0
Exp/Cntr=0.3,0.1

Type RM Length L Ch R = 1 ,6246    ,306,306,306
BEGIN DESCRIPTION:
Mapping XS 9120a4f6
END DESCRIPTION:
XS GIS Cut Line= 3
      1545068.59      6867577.88      1545427.93      6867700.27
      1546371.62      6867814.65
#Sta/Elev= 30
  4608.2 1743.31  4619.5 1743.45  4686.3 1744.52  4846.6  1739.5    4863 1737.14
  4879.1 1731.96  4899.1 1728.14  4921.3 1728.11  4935.7  1731.7  4942.5 1731.83
    4953 1730.01  4972.1 1718.44  4972.4 1717.94  4976.1 1718.44  4994.9 1721.67
  5042.9 1722.42  5125.9 1725.91    5179 1725.91  5207.1 1730.62  5255.8 1731.77
    5277 1728.99  5306.5 1729.69  5337.4 1731.91  5342.7 1733.53  5377.7 1734.67
  5429.6 1733.96  5561.7 1737.03  5619.5 1736.97  5710.1 1739.89  5938.4 1749.35
#Mann= 11 ,-1 , 0
  4608.2    .035       0  4619.5     .07       0  4686.3    .035       0
  4846.6     .07       0    4863    .035       0  4972.1    .035       0
  4976.1    .035       0  5042.9     .07       0  5207.1     .16       0
  5306.5     .07       0  5561.7     .16       0
Bank Sta=4972.1,4976.1
XS Rating Curve= 0 ,0
Exp/Cntr=0.3,0.1

Type RM Length L Ch R = 1 ,5940    ,359,359,359
BEGIN DESCRIPTION:
Mapping XS eeab7406
END DESCRIPTION:
XS GIS Cut Line= 3
      1545084.17      6867879.95      1545558.14      6867942.45
      1546435.76      6867898.18
#Sta/Elev= 30
  4525.1 1741.94  4595.7 1742.32  4727.7 1739.99  4775.5 1740.63  4780.5 1739.38
  4828.5 1738.83  4868.9 1731.89    4889  1730.7  4919.3 1732.06  4927.6 1725.27
  4932.6 1726.47  4939.5  1722.1  4949.6 1719.64  4969.7 1719.78  4997.1 1716.65
  4997.3 1716.15  5001.1 1716.65  5030.1 1720.85  5070.1 1719.67  5220.3    1720
  5240.3 1722.69  5250.3 1725.95  5320.4 1728.54  5340.5 1734.53  5373.6 1735.42
  5581.2 1739.39  5680.4 1741.51    5731 1744.36  5831.1 1746.35  5881.9 1748.85
#Mann= 7 ,-1 , 0
  4525.1    .035       0  4595.7     .07       0  4997.1     .07       0
  5001.1     .16       0  5373.6     .07       0  5581.2     .16       0
  5680.4     .07       0
Bank Sta=4997.1,5001.1
XS Rating Curve= 0 ,0
Exp/Cntr=0.3,0.1

Type RM Length L Ch R = 1 ,5581    ,481,481,481
BEGIN DESCRIPTION:
Mapping XS 9b132a49
END DESCRIPTION:
XS GIS Cut Line= 3
      1545076.48      6868053.24      1545586.46      6868257.23
      1546365.55       6868237.7
#Sta/Elev= 30
  4432.7  1740.1  4512.4 1740.01  4566.3 1738.43  4603.4 1738.63  4620.1 1736.86
  4711.4 1733.39  4757.4 1731.22  4775.8 1727.82  4781.6 1725.42    4787 1727.66
  4805.8 1722.43  4849.3 1719.61  4948.6 1716.76  4972.8 1717.65  4990.5 1716.09
  4998.5 1713.95  4998.8 1713.45  5002.5 1713.95  5030.5  1717.7  5070.5 1717.24
  5148.2  1720.8  5220.6 1722.19  5250.6 1725.23  5270.6 1728.15  5280.6 1731.31
  5300.6 1733.17  5390.6 1734.35  5547.8 1739.41  5730.7 1741.44  5761.3 1743.22
#Mann= 6 ,-1 , 0
  4432.7    .035       0  4566.3     .07       0  4711.4    .035       0
  4849.3     .16       0  4998.5     .07       0  5002.5     .16       0
Bank Sta=4998.5,5002.5
XS Rating Curve= 0 ,0
Exp/Cntr=0.3,0.1

Type RM Length L Ch R = 1 ,5100    ,340,340,340
BEGIN DESCRIPTION:
Mapping XS 6b682cd6
END DESCRIPTION:
XS GIS Cut Line= 4
      1545078.63      6868248.54       1545532.2      6868658.71
      1545961.89      6868806.28      1546291.98      6868825.69
#Sta/Elev= 30
  4386.8 1738.14  4503.9 1736.67  4603.3  1732.6  4666.8 1727.64  4709.4  1721.5
  4900.7 1714.13  4984.8    1714  4992.6 1713.46  4996.8 1710.91  5007.1 1709.45
  5007.3 1708.95  5011.1 1709.45  5022.4 1713.13  5040.3 1714.43  5212.7 1713.55
  5222.5 1715.88  5253.8 1712.61  5259.1 1714.45  5276.2 1716.31  5321.6 1716.96
  5329.1 1718.42  5352.8  1727.5  5371.3 1729.55  5495.8 1734.53    5569 1734.16
    5616 1736.81  5706.2 1738.58  5716.2 1739.97  5734.3 1738.83  5783.3 1740.56
#Mann= 4 ,-1 , 0
  4386.8     .16       0  4984.8     .16       0  5007.1     .07       0
  5011.1     .16       0
#XS Ineff= 2 , 0
       0                  5222.5       0 1715.88
Permanent Ineff=
       F       F
Bank Sta=5007.1,5011.1
XS Rating Curve= 0 ,0
Exp/Cntr=0.3,0.1

Type RM Length L Ch R = 1 ,4760    ,393,393,393
BEGIN DESCRIPTION:
Mapping XS 0c2714eb
END DESCRIPTION:
XS GIS Cut Line= 4
      1544990.79      6868582.87      1545487.79      6868891.06
      1545591.95      6868990.88      1546171.82      6869051.47
#Sta/Elev= 30
  4369.5 1735.29  4549.5 1732.32  4631.4 1729.78  4652.7 1720.15  4670.2 1723.44
  4673.9 1724.41  4689.3  1718.9  4747.2 1720.17  4774.5 1717.17  4864.5 1714.87
  4868.8    1715  4964.3 1712.32  4971.4 1711.68  4978.3 1707.37  4983.5 1706.73
  4983.8 1706.23  4987.5 1706.73  4992.5 1709.67  5006.6 1712.48  5029.2 1712.39
  5077.4 1711.32  5131.8 1714.71  5171.3 1714.78  5216.2 1716.77  5272.6 1725.37
  5402.9 1729.14  5493.8 1728.62  5599.7 1733.89  5614.4 1732.59  5681.6 1734.93
#Mann= 9 ,-1 , 0
  4369.5     .07       0  4549.5    .035       0  4670.2     .07       0
  4864.5    .035       0  4868.8     .07       0  4983.5     .07       0
  4987.5     .07       0  5029.2     .16       0  5171.3     .07       0
Bank Sta=4983.5,4987.5
XS Rating Curve= 0 ,0
Exp/Cntr=0.3,0.1

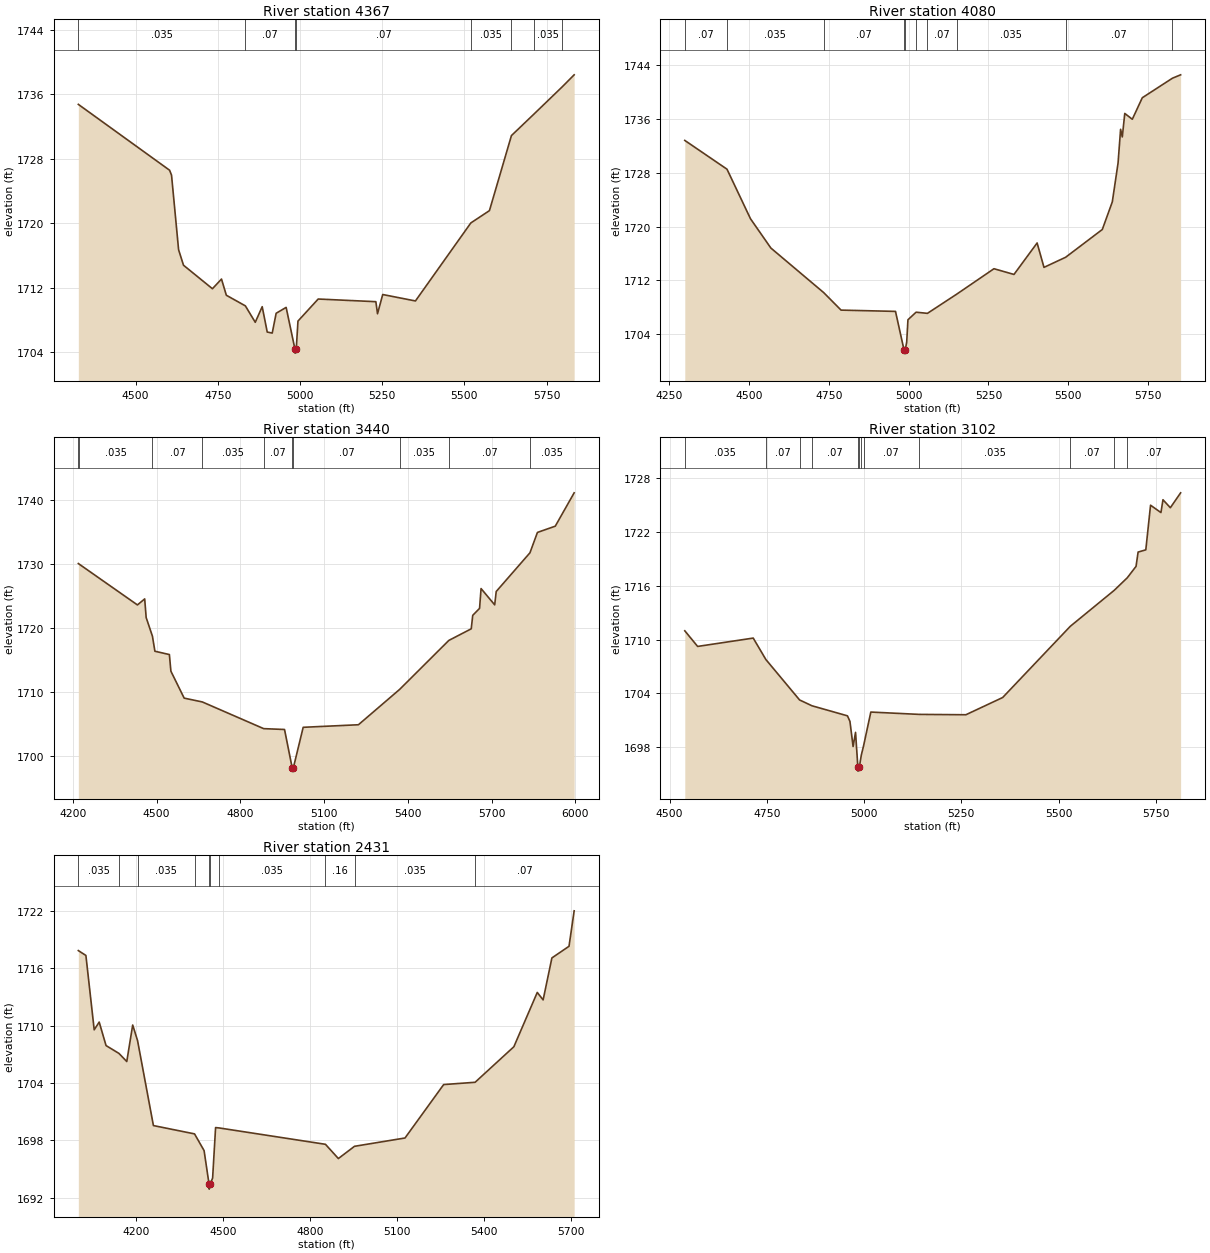
Type RM Length L Ch R = 1 ,4367    ,287,287,287
BEGIN DESCRIPTION:
Mapping XS 14d34456
END DESCRIPTION:
XS GIS Cut Line= 3
      1544927.92       6868882.4      1545492.13      6869242.62
      1546318.99      6869383.68
#Sta/Elev= 30
  4325.7 1734.77  4603.3 1726.59  4609.2 1725.98  4630.7 1716.71  4645.6 1714.79
  4733.6 1711.87  4761.2 1713.07  4775.9 1711.06  4833.8 1709.74  4863.9  1707.7
    4885 1709.64  4900.3 1706.49  4915.5 1706.36  4927.4 1708.82  4957.8 1709.55
  4984.6 1704.37  4984.9 1703.87  4988.6 1704.37  4993.8 1707.85  5055.3 1710.59
  5230.7 1710.26  5235.8 1708.76  5251.6 1711.15  5351.1 1710.35  5519.6 1720.04
  5576.2 1721.57  5643.1 1730.89  5710.5 1733.52  5797.9 1736.96  5833.9 1738.44
#Mann= 8 ,-1 , 0
  4325.7    .035       0  4833.8     .07       0  4984.6     .07       0
  4988.6     .07       0  5519.6    .035       0  5643.1     .07       0
  5710.5    .035       0  5797.9     .07       0
Bank Sta=4984.6,4988.6
XS Rating Curve= 0 ,0
Exp/Cntr=0.3,0.1

Type RM Length L Ch R = 1 ,4080    ,640,640,640
BEGIN DESCRIPTION:
MULBERRY CREEK TRIBUTARY 14 2.0
END DESCRIPTION:
XS GIS Cut Line= 3
       1544914.9      6869038.65        1545455.        6869488.
      1546260.63      6869762.81
#Sta/Elev= 30
  4298.4 1732.77  4430.7  1728.5  4504.3 1721.15  4568.1 1716.81  4733.6  1710.2
  4788.1  1707.6  4958.7 1707.41  4985.3 1701.72  4985.6 1701.22  4989.3 1701.72
  4993.8 1702.86  4997.7 1706.17  5023.2 1707.29  5058.8 1707.12  5151.3 1709.99
  5267.3 1713.74    5330 1712.89  5402.5 1717.56    5424 1713.94  5491.9 1715.44
  5606.8 1719.56  5638.1 1723.65  5656.1  1729.4  5664.1 1734.42  5669.4 1733.29
  5677.2 1736.77  5700.8 1735.91  5732.1  1739.1  5826.6    1742  5852.2  1742.5
#Mann= 10 ,-1 , 0
  4298.4     .07       0  4430.7    .035       0  4733.6     .07       0
  4985.3     .07       0  4989.3     .07       0  5023.2    .035       0
  5058.8     .07       0  5151.3    .035       0  5491.9     .07       0
  5826.6    .035       0
Bank Sta=4985.3,4989.3
XS Rating Curve= 0 ,0
Exp/Cntr=0.3,0.1

Type RM Length L Ch R = 1 ,3440    ,338,338,338
BEGIN DESCRIPTION:
Mapping XS 77a614c7
END DESCRIPTION:
XS GIS Cut Line= 3
      1544952.48      6869149.58      1545202.49      6869878.77
       1546137.4      6870245.97
#Sta/Elev= 30
  4219.9  1730.1  4223.2    1730  4431.5 1723.62  4457.5 1724.56  4462.8 1721.64
  4485.2 1718.73  4494.1 1716.37  4545.9 1715.85  4551.3 1713.25  4598.8 1709.03
  4663.9 1708.43  4883.6 1704.25  4958.2 1704.12  4985.7  1698.1    4986  1697.6
  4989.7  1698.1    5025 1704.46  5222.8 1704.86  5370.5  1710.4  5546.4 1718.06
  5626.7 1719.88  5632.1 1721.99  5656.5 1723.08  5661.9 1726.18  5710.7 1723.63
  5716.1 1725.72  5836.9 1731.78  5863.7 1734.97  5927.6 1735.95  5995.2 1741.17
#Mann= 10 ,-1 , 0
  4219.9     .07       0  4223.2    .035       0  4485.2     .07       0
  4663.9    .035       0  4883.6     .07       0  4985.7     .07       0
  4989.7     .07       0  5370.5    .035       0  5546.4     .07       0
  5836.9    .035       0
Bank Sta=4985.7,4989.7
XS Rating Curve= 0 ,0
Exp/Cntr=0.3,0.1

Type RM Length L Ch R = 1 ,3102    ,671,671,671
BEGIN DESCRIPTION:
Mapping XS c2bc53be
END DESCRIPTION:
XS GIS Cut Line= 3
      1544700.39      6869746.04      1544981.63       6870105.4
      1545760.16      6870357.96
#Sta/Elev= 30
  4539.1 1710.97  4572.1 1709.23    4715 1710.16  4747.6 1707.77  4834.2 1703.27
    4866 1702.62  4957.3  1701.5  4963.7 1700.88  4971.8 1698.08  4978.1 1699.66
    4984 1695.84  4984.3 1695.34    4988 1695.84    4993 1697.14  4998.6 1698.13
  5017.4 1701.92  5141.5 1701.66  5261.8 1701.62  5356.4 1703.54  5530.2 1711.47
  5643.2 1715.48  5676.8 1716.88  5699.3 1718.15  5704.6 1719.74  5724.4 1719.99
  5736.6 1724.96  5763.3 1724.14  5768.5 1725.57  5787.5 1724.68  5813.9 1726.34
#Mann= 12 ,-1 , 0
  4539.1    .035       0  4747.6     .07       0  4834.2    .035       0
    4866     .07       0    4984     .07       0    4988     .07       0
    4993     .16       0  4998.6     .07       0  5141.5    .035       0
  5530.2     .07       0  5643.2    .035       0  5676.8     .07       0
Bank Sta=4984,4988
XS Rating Curve= 0 ,0
Exp/Cntr=0.3,0.1

Type RM Length L Ch R = 1 ,2431    ,0,0,0
BEGIN DESCRIPTION:
MULBERRY CREEK TRIBUTARY 14 1.0
END DESCRIPTION:
XS GIS Cut Line= 3
      1544515.48      6869954.35      1544661.31      6870680.92
      1545621.12      6870561.27
#Sta/Elev= 30
  4001.2 1717.85  4027.3 1717.34  4055.9 1709.56  4073.1 1710.37  4096.7 1707.91
  4141.2 1707.09  4168.1 1706.24  4188.5 1710.06  4205.2 1708.44  4259.9 1699.54
  4401.6 1698.67  4434.5 1696.92  4451.7 1693.39    4452 1692.89  4455.7 1693.39
  4463.9 1694.06  4474.1 1699.33  4486.8 1699.29  4852.6 1697.58  4897.1 1696.09
  4952.7 1697.37  5126.7 1698.24  5259.9 1703.83  5368.2 1704.07  5501.8 1707.79
  5582.4 1713.47  5602.6 1712.69  5632.8 1717.08  5691.8  1718.3  5709.5 1722.01
#Mann= 10 ,-1 , 0
  4001.2    .035       0  4141.2     .07       0  4205.2    .035       0
  4401.6     .07       0  4451.7    .035       0  4455.7     .07       0
  4486.8    .035       0  4852.6     .16       0  4952.7    .035       0
  5368.2     .07       0
Bank Sta=4451.7,4455.7
XS Rating Curve= 0 ,0
Exp/Cntr=0.3,0.1

Chan Stop Cuts=-1
Use User Specified Reach Order=0
Composite Channel Slope=5