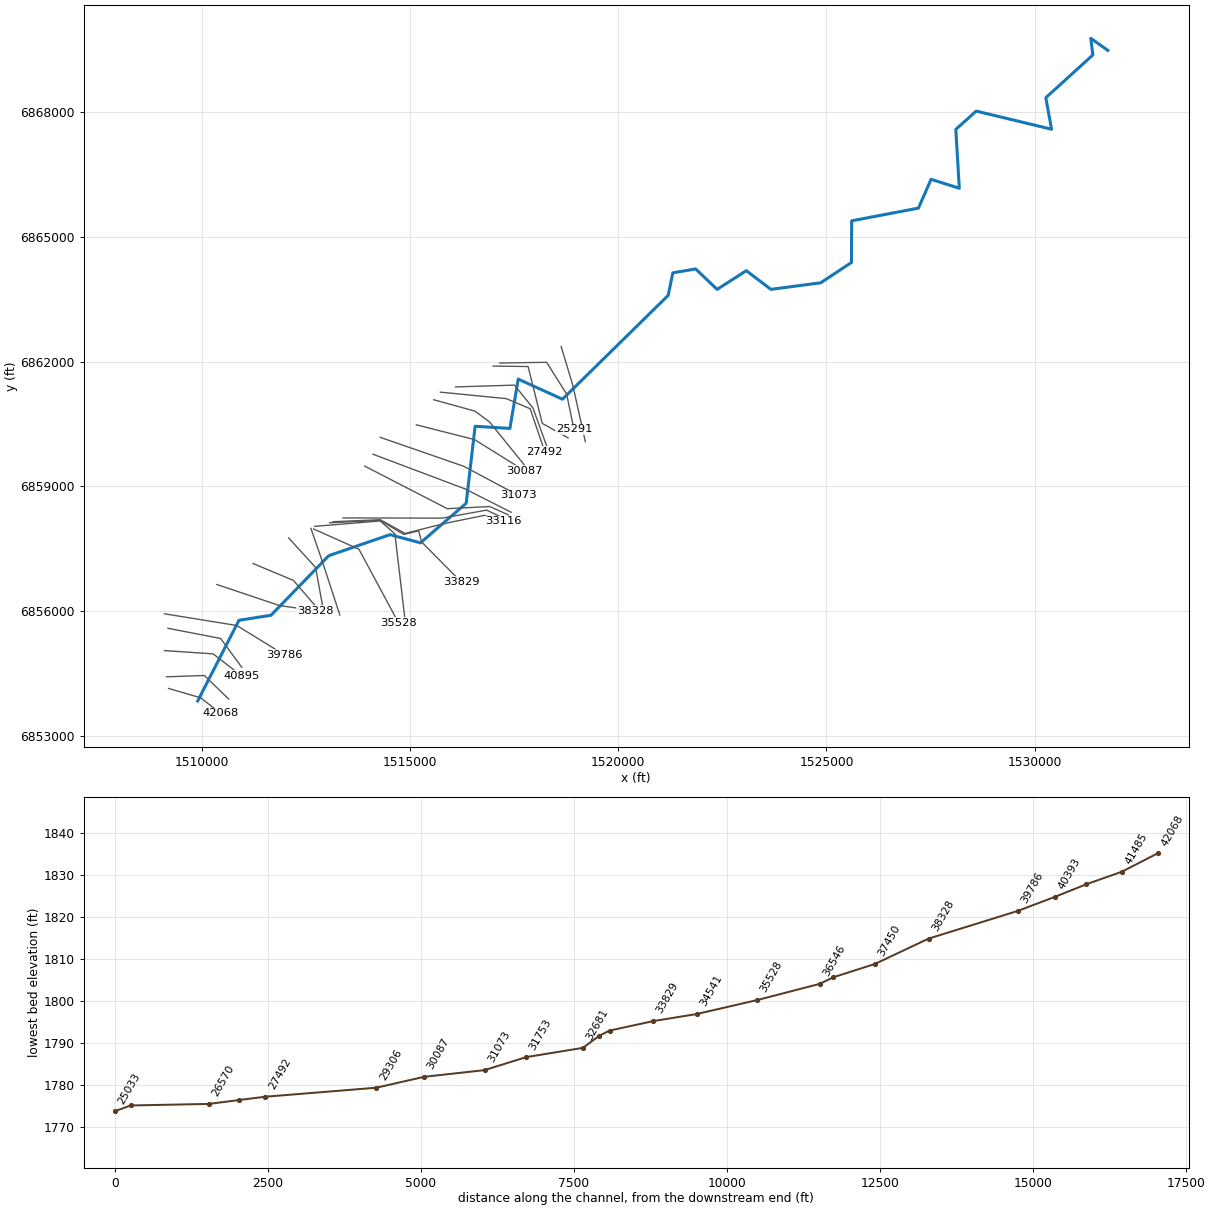
--- MULBERRY CREEK TRIBUTARY 15.prj (project) ---

Proj Title=MULBERRY CREEK TRIBUTARY 15 Base Level Engineering
Current Plan=p01
Default Exp/Contr=0.3,0.1
English Units
Geom File=g01
Flow File=f01
Plan File=p01
Y Axis Title=Elevation
X Axis Title(PF)=Main Channel Distance
X Axis Title(XS)=Station
BEGIN DESCRIPTION:
MULBERRY CREEK TRIBUTARY 15
END DESCRIPTION:
DSS Export Rating Curves= 0
DSS Export Rating Curve Sorted= 0
DSS Export Volume Flow Curves= 0
DXF OffsetX= 0
DXF OffsetY= 0
DXF ScaleX= 1
DXF ScaleY= 10

--- MULBERRY CREEK TRIBUTARY 15.p01 (plan) ---

Plan Title=Multiple Run
Short Identifier=Multiple
Geom File=g01
Flow File=f01
Subcritical Flow
K Sum by GR= 0
Std Step Tol= 0.01
Critical Tol= 0.01
Num of Std Step Trials= 20
Max Error Tol= 0.3
Flow Tol Ratio= 0.001
Split Flow NTrial= 30
Split Flow Tol= 0.02
Split Flow Ratio= 0.02
Log Output Level= 0
Friction Slope Method= 1
Unsteady Friction Slope Method= 2
Unsteady Bridges Friction Slope Method= 1
Parabolic Critical Depth
Global Vel Dist=  1 , 1 , 1
Global Log Level= 0
CheckData=True
Encroach Param= -1, 0, 0, 0
BEGIN DESCRIPTION:
Multiple Run
END DESCRIPTION:

--- MULBERRY CREEK TRIBUTARY 15.f01 (steady flow) ---

Flow Title=Multiple
Program Version=4.10
Number of Profiles= 7
Profile Names=10-year,25-year,50-year,1pct_min,100-year,1pct_plu,500-year
River Rch & RM=MULBERRY CREEK T,Reach-1         ,42068
     166     224     271     163     326     650     477
River Rch & RM=MULBERRY CREEK T,Reach-1         ,34541
     262     364     447     274     547    1091     827
River Rch & RM=MULBERRY CREEK T,Reach-1         ,32681
     424     600     747     462     923    1841    1427
River Rch & RM=MULBERRY CREEK T,Reach-1         ,23123
     630     909    1147     719    1434    2861    2273
River Rch & RM=MULBERRY CREEK T,Reach-1         ,22747
     673     970    1224     766    1528    3049    2417
River Rch & RM=MULBERRY CREEK T,Reach-1         ,16709
     706    1019    1286     805    1607    3206    2544
River Rch & RM=MULBERRY CREEK T,Reach-1         ,14707
     763    1103    1394     874    1743    3478    2764
River Rch & RM=MULBERRY CREEK T,Reach-1         ,7261
     930    1353    1717    1080    2154    4299    3441
Boundary for River Rch & Prof#=MULBERRY CREEK T,Reach-1         , 1
Up Type= 0
Dn Type= 3
Dn Slope=0.00185
Boundary for River Rch & Prof#=MULBERRY CREEK T,Reach-1         , 2
Up Type= 0
Dn Type= 3
Dn Slope=0.00185
Boundary for River Rch & Prof#=MULBERRY CREEK T,Reach-1         , 3
Up Type= 0
Dn Type= 3
Dn Slope=0.00185
Boundary for River Rch & Prof#=MULBERRY CREEK T,Reach-1         , 4
Up Type= 0
Dn Type= 3
Dn Slope=0.00185
Boundary for River Rch & Prof#=MULBERRY CREEK T,Reach-1         , 5
Up Type= 0
Dn Type= 3
Dn Slope=0.00185
Boundary for River Rch & Prof#=MULBERRY CREEK T,Reach-1         , 6
Up Type= 0
Dn Type= 3
Dn Slope=0.00185
Boundary for River Rch & Prof#=MULBERRY CREEK T,Reach-1         , 7
Up Type= 0
Dn Type= 3
Dn Slope=0.00185
DSS Import GetInterval= 0
DSS Import GetPeak= 0
DSS Import FillOption= 0

--- MULBERRY CREEK TRIBUTARY 15.g01 (geometry) ---

Geom Title=Existing Conditions
Program Version=4.10

River Reach=MULBERRY CREEK T,Reach-1
Reach XY= 30
        1509905.        6853838.      1510894.49      6855777.53
      1511664.72      6855898.78      1513052.55      6857332.54
      1514520.22      6857837.48      1515253.37      6857641.13
      1516349.83      6858592.59      1516564.12      6860444.76
      1517399.56      6860393.17      1517598.79       6861580.2
      1518661.17      6861095.76      1521199.41      6863593.61
      1521311.05      6864136.42      1521858.41      6864230.62
      1522374.76      6863737.96      1523075.03      6864188.44
      1523665.45      6863738.53      1524861.66      6863896.98
      1525599.61      6864385.56        1525605.        6865388.
      1527207.55      6865692.98       1527510.9      6866386.03
       1528188.6      6866171.18        1528105.        6867588.
       1528594.9       6868027.7      1530403.35       6867591.1
      1530265.79      6868348.37      1531394.57      6869378.17
       1531345.3      6869777.84        1531755.        6869488.

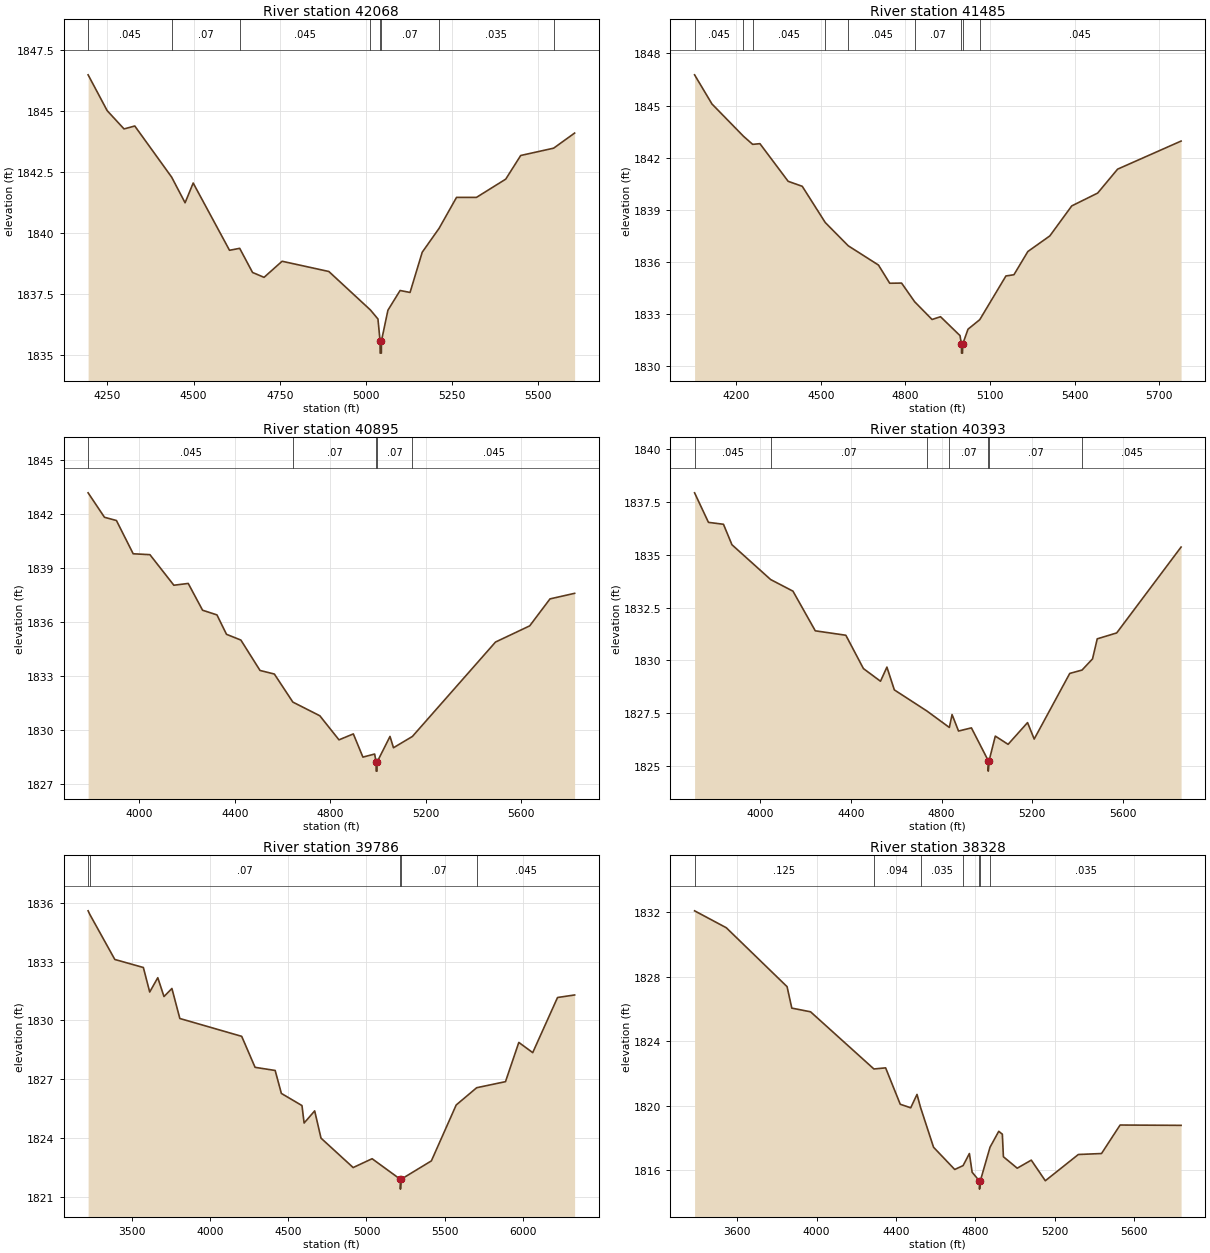
Type RM Length L Ch R = 1 ,42068   ,583,583,583
BEGIN DESCRIPTION:
MULBERRY CREEK TRIBUTARY 15 44.0
END DESCRIPTION:
XS GIS Cut Line= 3
      1509205.04      6854137.99       1509978.4      6853911.31
        1510455.        6853538.
#Sta/Elev= 30
  4194.1  1846.5  4249.4 1845.03  4298.3 1844.28  4329.5  1844.4  4436.5  1842.3
  4475.4 1841.25  4498.9 1842.06  4604.3  1839.3  4633.8 1839.38  4671.1 1838.39
  4704.5 1838.19  4756.8 1838.85  4892.4 1838.43  5013.1 1836.85  5034.9 1836.48
    5041 1835.58  5041.3 1835.08  5044.8 1835.08    5045 1835.58  5063.8 1836.84
  5099.1 1837.65    5128 1837.57  5163.3 1839.22  5212.2  1840.2  5262.8 1841.47
  5320.6 1841.47  5405.6 1842.22    5449 1843.19  5544.5 1843.49  5605.4 1844.11
#Mann= 8 ,-1 , 0
  4194.1    .045       0  4436.5     .07       0  4633.8    .045       0
  5013.1     .07       0    5041    .045       0    5045     .07       0
  5212.2    .035       0  5544.5     .07       0
Bank Sta=5041,5045
XS Rating Curve= 0 ,0
Exp/Cntr=0.3,0.1

Type RM Length L Ch R = 1 ,41485   ,590,590,590
BEGIN DESCRIPTION:
Mapping XS ac8a84b5
END DESCRIPTION:
XS GIS Cut Line= 3
      1509153.47      6854417.95      1510064.97      6854449.21
       1510647.5      6853882.27
#Sta/Elev= 30
  4052.4 1846.77    4114 1845.09  4225.6 1843.23  4258.3 1842.76  4284.1  1842.8
  4384.1 1840.63  4434.2 1840.34  4515.8 1838.25  4597.2 1836.91  4704.3  1835.8
  4744.3 1834.75  4786.3 1834.76  4832.8 1833.68  4894.4 1832.66  4924.4 1832.82
  4993.5 1831.73  4998.7 1831.22  4998.9 1830.72  5002.4 1830.72  5002.7 1831.22
  5021.8  1832.1  5063.5 1832.65  5156.3 1835.17  5184.6 1835.24    5234 1836.58
  5311.9 1837.48  5389.6 1839.21  5481.5 1839.95  5552.2 1841.33  5777.3 1842.95
#Mann= 9 ,-1 , 0
  4052.4    .045       0  4225.6     .07       0  4258.3    .045       0
  4515.8     .07       0  4597.2    .045       0  4832.8     .07       0
  4998.7     .07       0  5002.7     .07       0  5063.5    .045       0
Bank Sta=4998.7,5002.7
XS Rating Curve= 0 ,0
Exp/Cntr=0.3,0.1

Type RM Length L Ch R = 1 ,40895   ,502,502,502
BEGIN DESCRIPTION:
Mapping XS ced9f61c
END DESCRIPTION:
XS GIS Cut Line= 3
      1509106.65      6855048.16       1510273.3      6854970.04
      1510960.41       6854439.1
#Sta/Elev= 30
  3785.3 1843.17  3853.8 1841.81  3903.9 1841.63  3974.1 1839.78  4044.2 1839.73
  4144.4 1838.03  4204.6 1838.13  4264.7 1836.64  4324.9 1836.38  4364.9  1835.3
  4425.1 1834.98  4505.3 1833.29  4565.4 1833.09  4642.8 1831.53  4755.7 1830.77
    4836 1829.43  4896.1 1829.76  4936.2 1828.47  4985.4 1828.64  4991.5 1828.19
  4991.8 1827.69  4995.3 1827.69  4995.5 1828.19  5049.7 1829.62  5064.2 1828.99
  5143.6 1829.62  5491.6 1834.87  5634.7 1835.77  5719.8 1837.27  5822.9 1837.58
#Mann= 5 ,-1 , 0
  3785.3    .045       0  4642.8     .07       0  4991.5     .07       0
  4995.5     .07       0  5143.6    .045       0
Bank Sta=4991.5,4995.5
XS Rating Curve= 0 ,0
Exp/Cntr=0.3,0.1

Type RM Length L Ch R = 1 ,40393   ,607,607,607
BEGIN DESCRIPTION:
Mapping XS abe4a2aa
END DESCRIPTION:
XS GIS Cut Line= 3
      1509189.93      6855584.63      1510455.59      6855339.83
       1510960.4      6854647.68
#Sta/Elev= 30
  3710.6 1837.94  3771.8 1836.54    3838 1836.45  3875.4 1835.48  4046.1 1833.83
  4144.5 1833.28    4243  1831.4  4377.8 1831.19  4455.3 1829.61  4530.6 1829.01
  4558.9 1829.68  4591.7  1828.6  4735.2  1827.6  4834.3 1826.82  4846.3 1827.43
  4874.8 1826.65  4931.6  1826.8  5005.7 1825.25  5005.9 1824.75  5009.7 1825.25
    5037 1826.41  5093.4 1826.02  5179.2 1827.05  5208.5 1826.27  5365.3 1829.38
  5419.6 1829.54  5465.8 1830.07  5486.6 1831.02  5572.4  1831.3  5856.4 1835.37
#Mann= 7 ,-1 , 0
  3710.6    .045       0  4046.1     .07       0  4735.2     .16       0
  4834.3     .07       0  5005.7     .07       0  5009.7     .07       0
  5419.6    .045       0
Bank Sta=5005.7,5009.7
XS Rating Curve= 0 ,0
Exp/Cntr=0.3,0.1

Type RM Length L Ch R = 1 ,39786   ,1458,1458,1458
BEGIN DESCRIPTION:
Mapping XS 0c576f68
END DESCRIPTION:
XS GIS Cut Line= 3
      1509106.66      6855933.58      1510841.01      6855652.33
        1511991.      6854944.65
#Sta/Elev= 30
    3222 1835.59    3232 1835.42  3392.5 1833.11  3574.9  1832.7  3615.4 1831.45
    3667 1832.18  3706.6 1831.22  3757.2 1831.63  3807.9  1830.1    4203 1829.19
  4288.4 1827.61  4416.7 1827.45  4456.3 1826.28    4588 1825.66  4601.6 1824.77
    4669 1825.39  4709.5    1824  4914.8  1822.5  5035.8 1822.95  5216.5  1821.9
  5216.8  1821.4  5220.5  1821.9  5414.4 1822.84  5572.9 1825.69  5703.7 1826.57
  5887.8 1826.88  5972.9 1828.88  6061.7 1828.36  6220.2 1831.17  6329.3  1831.3
#Mann= 5 ,-1 , 0
    3222    .045       0    3232     .07       0  5216.5     .07       0
  5220.5     .07       0  5703.7    .045       0
Bank Sta=5216.5,5220.5
XS Rating Curve= 0 ,0
Exp/Cntr=0.3,0.1

Type RM Length L Ch R = 1 ,38328   ,878,878,878
BEGIN DESCRIPTION:
Mapping XS 4abe1742
END DESCRIPTION:
XS GIS Cut Line= 3
      1510363.61      6856638.43      1511863.58      6856133.23
      1512721.49      6856008.45
#Sta/Elev= 30
  3385.7 1832.09  3545.4 1831.04  3851.5 1827.38  3875.2 1826.05  3969.7 1825.82
  4288.7 1822.27  4347.6 1822.34  4421.3 1820.08    4474 1819.86  4505.7 1820.69
  4523.3 1819.89    4589 1817.41  4695.6 1816.03  4737.7 1816.27  4769.5 1817.02
  4783.3 1815.86  4820.2 1815.31  4820.5 1814.81  4824.2 1815.31  4873.3 1817.41
  4917.2  1818.4  4935.4 1818.22  4940.7 1816.82  5010.3 1816.11  5081.1 1816.61
  5151.8 1815.33    5318 1816.96  5434.7 1817.02  5528.3 1818.79  5835.4 1818.77
#Mann= 7 ,-1 , 0
  3385.7    .125       0  4288.7    .094       0  4523.3    .035       0
  4737.7    .094       0  4820.2    .035       0  4824.2    .094       0
  4873.3    .035       0
Bank Sta=4820.2,4824.2
XS Rating Curve= 0 ,0
Exp/Cntr=0.3,0.1

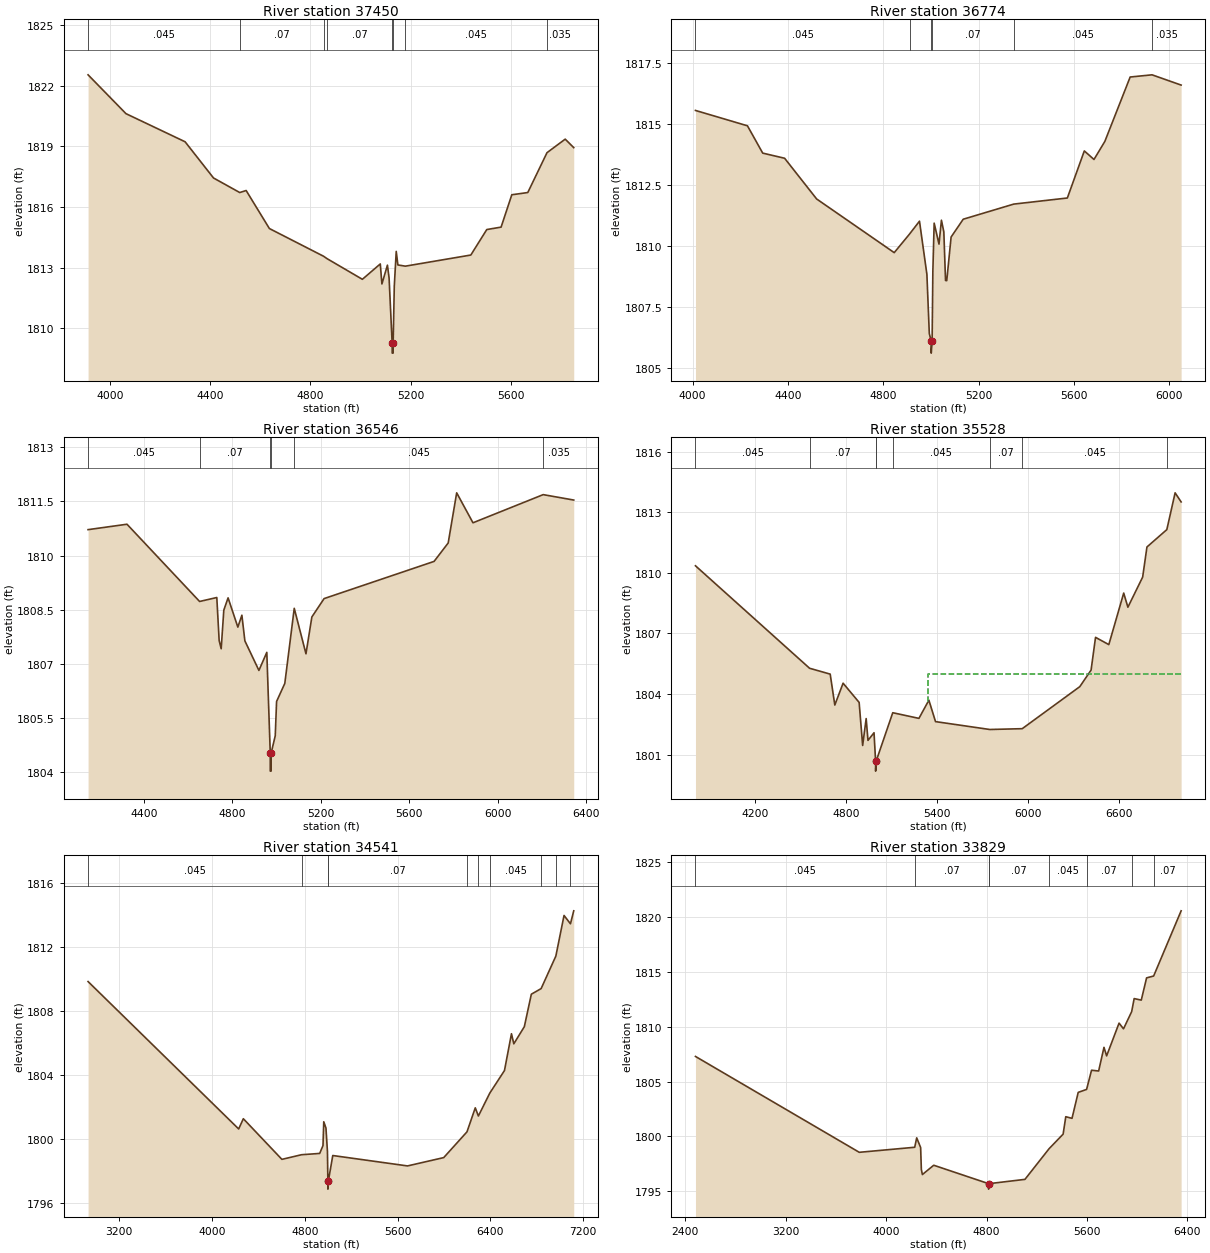
Type RM Length L Ch R = 1 ,37450   ,676,676,676
BEGIN DESCRIPTION:
Mapping XS aa453712
END DESCRIPTION:
XS GIS Cut Line= 3
      1511233.81      6857142.78      1512202.56      6856736.53
      1512780.32      6856065.07
#Sta/Elev= 30
  3913.6 1822.53  4064.7 1820.61  4300.4 1819.22  4413.7 1817.43  4518.3 1816.71
  4543.8 1816.81  4636.5 1814.93  4852.5 1813.56  4866.5 1813.44  5007.2 1812.42
  5078.6 1813.18  5085.1 1812.19  5107.1 1813.12  5113.7 1812.49  5125.9 1809.27
  5126.2 1808.77  5129.7 1808.77  5129.9 1809.27  5134.5 1812.09  5142.2  1813.8
  5148.8 1813.13  5178.6 1813.07  5439.6 1813.62  5503.2 1814.88  5560.3    1815
    5603  1816.6  5666.7 1816.71  5743.3 1818.68  5815.9 1819.35  5849.9 1818.93
#Mann= 8 ,-1 , 0
  3913.6    .045       0  4518.3     .07       0  4852.5    .045       0
  4866.5     .07       0  5125.9     .07       0  5129.9     .07       0
  5178.6    .045       0  5743.3    .035       0
Bank Sta=5125.9,5129.9
XS Rating Curve= 0 ,0
Exp/Cntr=0.3,0.1

Type RM Length L Ch R = 1 ,36774   ,228,228,228
BEGIN DESCRIPTION:
Mapping XS 0a3dd68f
END DESCRIPTION:
XS GIS Cut Line= 3
      1512087.42      6857759.05      1512733.25      6857050.71
      1512927.69      6855988.22
#Sta/Elev= 30
  4011.8 1815.57    4230 1814.94  4294.1 1813.82    4386 1813.61  4520.5 1811.94
  4846.1 1809.74  4910.3  1810.5  4952.2 1811.03  4983.3 1808.85  4993.4 1806.42
  5001.2 1806.12  5001.4 1805.62  5005.2 1806.12  5008.3 1808.98  5013.8 1810.95
  5034.1 1810.09  5044.3 1811.07  5054.4 1810.59  5061.5  1808.6  5066.6 1808.59
  5084.9 1810.38  5135.8 1811.11  5347.9 1811.73  5572.9 1811.98  5644.1 1813.91
  5684.7 1813.56  5730.3  1814.3  5836.6 1816.94  5928.4 1817.03  6050.5 1816.61
#Mann= 6 ,-1 , 0
  4011.8    .045       0  4910.3     .07       0  5001.2     .07       0
  5005.2     .07       0  5347.9    .045       0  5928.4    .035       0
Bank Sta=5001.2,5005.2
XS Rating Curve= 0 ,0
Exp/Cntr=0.3,0.1

Type RM Length L Ch R = 1 ,36546   ,1018,1018,1018
BEGIN DESCRIPTION:
Mapping XS c909c914
END DESCRIPTION:
XS GIS Cut Line= 3
      1512622.15      6857988.18      1512886.03      6857224.33
      1513316.59      6855904.85
#Sta/Elev= 30
    4148 1810.72    4324 1810.87  4652.3 1808.73  4730.1 1808.84  4740.7 1807.65
  4749.9 1807.42  4761.8 1808.49  4781.1 1808.83  4825.3 1808.02  4843.5 1808.35
    4857 1807.64  4920.5 1806.82  4956.2 1807.32  4971.8 1804.53    4972 1804.03
  4975.5 1804.03  4975.8 1804.53  4994.4 1805.01  5000.4 1805.96  5037.6 1806.46
  5080.3 1808.54  5133.3 1807.28  5159.9  1808.3  5215.3 1808.81  5712.6 1809.84
  5776.4 1810.35  5814.8 1811.74  5888.5 1810.91    6206 1811.69  6344.1 1811.54
#Mann= 6 ,-1 , 0
    4148    .045       0  4652.3     .07       0  4971.8     .07       0
  4975.8     .07       0  5080.3    .045       0    6206    .035       0
Bank Sta=4971.8,4975.8
XS Rating Curve= 0 ,0
Exp/Cntr=0.3,0.1

Type RM Length L Ch R = 1 ,35528   ,987,987,987
BEGIN DESCRIPTION:
Mapping XS e8e2f806
END DESCRIPTION:
XS GIS Cut Line= 3
      1512685.05      6857974.54       1513775.2      6857487.51
      1514726.69      6855714.14
#Sta/Elev= 30
    3806 1810.35  4559.3 1805.28  4695.5 1804.99    4726 1803.46  4780.7 1804.54
  4886.6 1803.59  4909.8 1801.46    4933 1802.79    4945 1801.71  4984.9 1802.09
  4995.2 1800.69  4995.4 1800.19  4999.2 1800.69  5108.6 1803.08  5281.3  1802.8
  5347.1  1803.7  5390.9 1802.64  5749.2 1802.25  5963.4 1802.29  6343.5 1804.37
    6418 1805.19  6447.4 1806.81  6535.1 1806.45  6633.4    1809    6661  1808.3
  6758.5 1809.79  6786.8 1811.28  6918.1 1812.14  6972.8 1813.96  7012.5 1813.51
#Mann= 8 ,-1 , 0
    3806    .045       0  4559.3     .07       0  4995.2     .07       0
  4999.2     .07       0  5108.6    .045       0  5749.2     .07       0
  5963.4    .045       0  6918.1    .035       0
#XS Ineff= 2 , 0
       0                  5339.9       0    1805
Permanent Ineff=
       F       F
Bank Sta=4995.2,4999.2
XS Rating Curve= 0 ,0
Exp/Cntr=0.3,0.1

Type RM Length L Ch R = 1 ,34541   ,712,712,712
BEGIN DESCRIPTION:
Mapping XS 081eda1f
END DESCRIPTION:
XS GIS Cut Line= 4
       1512711.1      6858037.06      1514283.98      6858167.26
      1514638.15      6857859.97      1514888.14      6855734.98
#Sta/Elev= 30
  2930.8 1809.84  4229.1 1800.63  4269.3 1801.27  4601.8 1798.73  4771.4 1799.02
  4927.5  1799.1    4956 1799.59  4962.6 1801.08  4981.5 1800.69  4994.4 1799.22
  4998.1 1797.37  4998.3 1796.87  5002.1 1797.37  5040.3 1798.97  5684.8 1798.32
  5996.9 1798.84  6197.4 1800.45  6268.8 1801.95  6295.7 1801.44    6394 1802.87
  6520.5 1804.28  6580.9 1806.58    6601 1805.95  6691.7 1807.02  6752.1 1809.05
  6836.5  1809.4  6963.4 1811.43    7034 1813.97  7089.4 1813.45  7117.6 1814.26
#Mann= 10 ,-1 , 0
  2930.8    .045       0  4771.4     .07       0  4998.1     .07       0
  5002.1     .07       0  6197.4    .045       0  6295.7     .07       0
    6394    .045       0  6836.5     .07       0  6963.4    .045       0
  7089.4    .035       0
#XS Ineff= 2 , 0
       0  4962.6 1801.08               0
Permanent Ineff=
       F       F
Bank Sta=4998.1,5002.1
XS Rating Curve= 0 ,0
Exp/Cntr=0.3,0.1

Type RM Length L Ch R = 1 ,33829   ,713,713,713
BEGIN DESCRIPTION:
Mapping XS f76536da
END DESCRIPTION:
XS GIS Cut Line= 6
      1513072.74      6858123.53      1514286.28      6858180.82
      1514853.99      6857842.28      1515208.55      6857929.99
      1515281.07      6857659.98      1516228.32      6856702.33
#Sta/Elev= 30
    2482 1807.29  3786.5 1798.54    4228    1799  4243.9 1799.86  4275.1 1798.98
  4280.9 1796.98  4289.2 1796.51  4379.5 1797.36  4816.2 1795.68  4816.5 1795.18
  4820.6 1795.68  5105.9 1796.07  5298.2 1798.87    5410  1800.2  5431.1 1801.79
  5480.7 1801.64  5530.1 1804.01  5596.8 1804.28  5636.3 1806.03  5692.8 1805.96
  5735.3 1808.12  5756.4 1807.34  5855.4 1810.33  5890.8 1809.81  5955.8 1811.38
  5975.7 1812.57  6032.3 1812.43  6074.6 1814.46  6130.9 1814.63  6349.7 1820.58
#Mann= 8 ,-1 , 0
    2482    .045       0    4228     .07       0  4816.2     .07       0
  4820.6     .07       0  5298.2    .045       0  5596.8     .07       0
  5955.8    .045       0  6130.9     .07       0
Bank Sta=4816.2,4820.6
XS Rating Curve= 0 ,0
Exp/Cntr=0.3,0.1

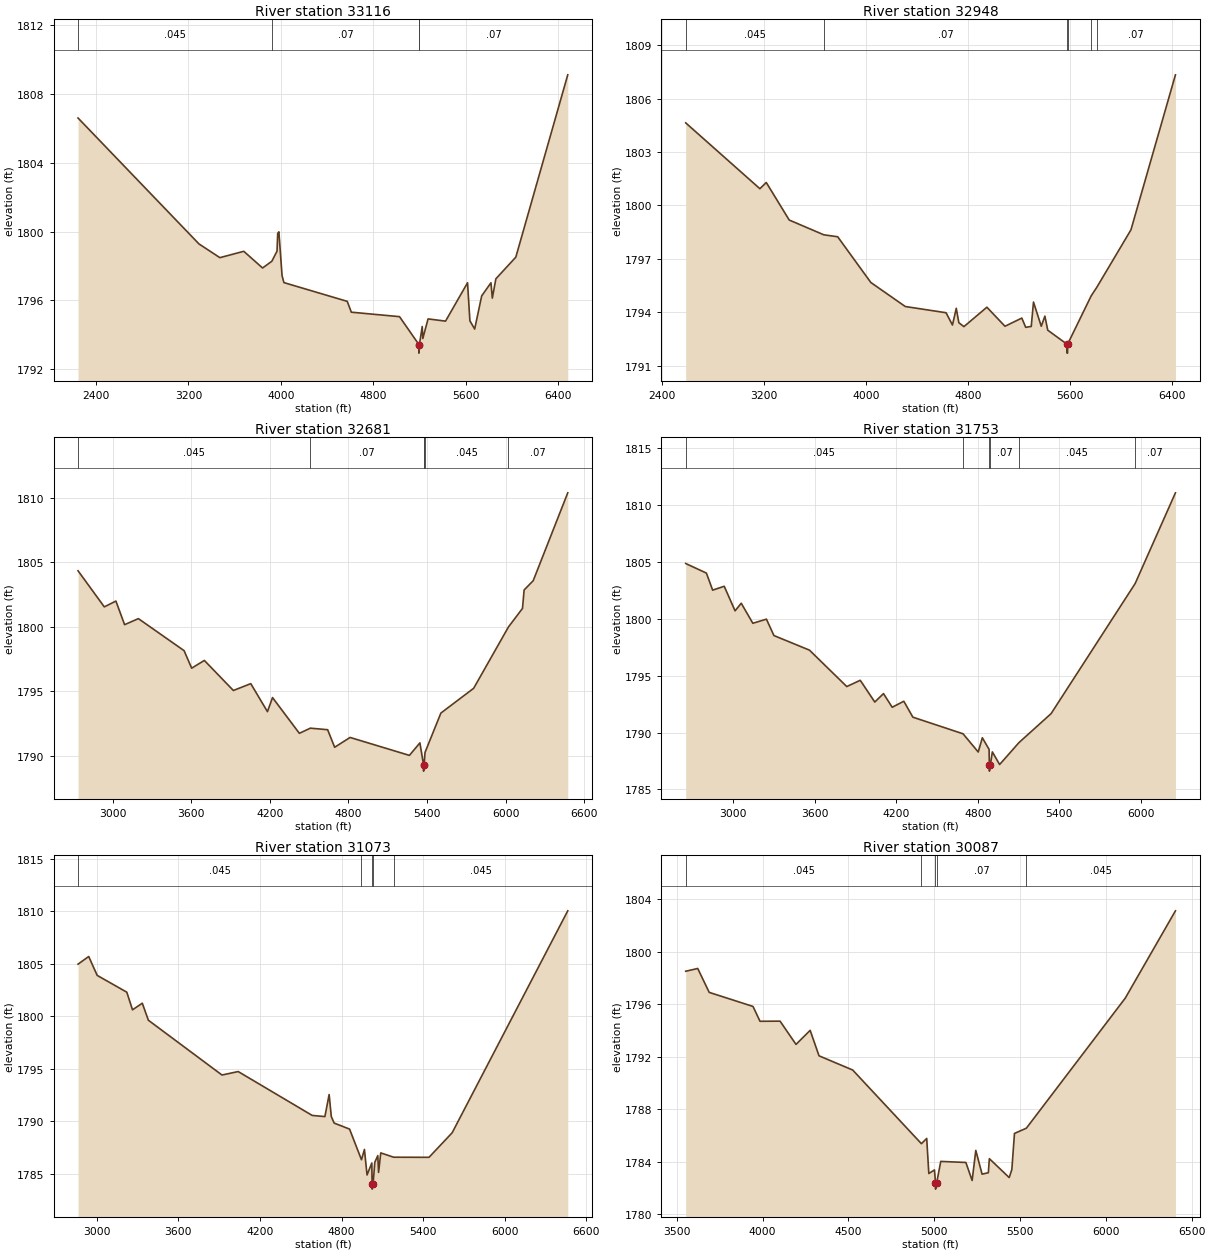
Type RM Length L Ch R = 1 ,33116   ,168,168,168
BEGIN DESCRIPTION:
Mapping XS 8c20e4bb
END DESCRIPTION:
XS GIS Cut Line= 6
      1513153.32      6858149.03      1514286.15      6858196.78
      1514885.11      6857866.91      1515787.88      6858096.95
      1516781.81      6858300.94      1517231.62      6858158.21
#Sta/Elev= 30
  2245.3  1806.6  3291.2 1799.28  3472.4 1798.48  3678.8 1798.85  3841.6 1797.88
  3921.5 1798.27  3966.6 1798.86  3972.3 1799.89  3982.6 1799.98  4010.1 1797.43
  4026.2 1797.03  4573.6 1795.94  4609.3 1795.31    5026 1795.05  5193.5 1793.43
  5193.8 1792.93    5198 1793.43  5222.4 1794.48  5227.5 1793.78  5272.8 1794.92
    5424 1794.79  5614.3 1797.02  5634.7 1794.81    5676 1794.33  5736.8 1796.26
  5816.9 1797.02  5828.7 1796.13  5859.3 1797.25  6031.9 1798.51  6481.1 1809.11
#Mann= 4 ,-1 , 0
  2245.3    .045       0  3921.5     .07       0  5193.5     .07       0
    5198     .07       0
#XS Ineff= 2 , 0
       0                  5614.3       0 1797.02
Permanent Ineff=
       F       F
Bank Sta=5193.5,5198
XS Rating Curve= 0 ,0
Exp/Cntr=0.3,0.1

Type RM Length L Ch R = 1 ,32948   ,267,267,267
BEGIN DESCRIPTION:
Mapping XS b9f4343b
END DESCRIPTION:
XS GIS Cut Line= 4
      1513393.33      6858240.18      1515773.56      6858234.97
      1516841.27      6858427.68      1517179.84      6858266.21
#Sta/Elev= 30
  2587.9 1804.64  3169.6 1800.94  3219.6 1801.29  3399.6 1799.18  3670.6 1798.35
  3779.6 1798.24  4039.6 1795.67  4309.6 1794.32  4629.6 1793.97  4679.6 1793.28
  4709.6 1794.22  4729.6 1793.41  4769.6 1793.19  4949.6 1794.28  5091.5 1793.21
  5223.6 1793.67  5254.1 1793.15  5297.4  1793.2  5315.1 1794.57  5376.1 1793.21
  5404.5 1793.78  5426.9 1792.99  5578.1  1792.2  5578.4  1791.7  5582.3  1791.7
  5582.6  1792.2  5767.6 1794.92  5810.8 1795.39  6079.4 1798.63  6428.2 1807.34
#Mann= 6 ,-1 , 0
  2587.9    .045       0  3670.6     .07       0  5578.1     .07       0
  5582.6     .07       0  5767.6    .045       0  5810.8     .07       0
Bank Sta=5578.1,5582.6
XS Rating Curve= 0 ,0
Exp/Cntr=0.3,0.1

Type RM Length L Ch R = 1 ,32681   ,928,928,928
BEGIN DESCRIPTION:
Mapping XS 0e4bf138
END DESCRIPTION:
XS GIS Cut Line= 4
      1513914.06      6859486.21       1515897.6      6858461.88
      1516917.56      6858513.97      1517360.14      6858314.38
#Sta/Elev= 30
    2735 1804.35  2935.6 1801.55  3024.2    1802  3090.6 1800.17  3195.8 1800.64
  3544.6 1798.16  3602.7  1796.8  3699.6  1797.4  3921.1 1795.07  4054.1  1795.6
  4181.3 1793.43    4220 1794.52    4425 1791.75  4509.2 1792.15  4640.9 1792.03
  4694.4 1790.67  4812.5 1791.43  5265.2 1790.04  5345.3 1791.01  5373.1 1789.32
  5373.4 1788.82  5377.6 1789.32  5384.4 1790.27  5505.5 1793.32  5755.8 1795.24
  6021.2 1799.99  6128.5 1801.43    6141 1802.86  6210.4 1803.58  6474.2 1810.39
#Mann= 6 ,-1 , 0
    2735    .045       0  4509.2     .07       0  5373.1     .07       0
  5377.6     .07       0  5384.4    .045       0  6021.2     .07       0
Bank Sta=5373.1,5377.6
XS Rating Curve= 0 ,0
Exp/Cntr=0.3,0.1

Type RM Length L Ch R = 1 ,31753   ,680,680,680
BEGIN DESCRIPTION:
Mapping XS 34cb75ae
END DESCRIPTION:
XS GIS Cut Line= 3
      1514112.51      6859772.31      1516321.74      6858938.96
      1517431.38      6858375.47
#Sta/Elev= 30
  2649.7 1804.85    2802 1804.01  2848.1 1802.51  2933.3 1802.85  3013.2 1800.69
  3058.5 1801.36    3144  1799.6  3244.1 1799.96  3299.2 1798.52  3560.8 1797.24
  3835.6 1794.04  3934.9 1794.59  4041.8 1792.68  4105.9 1793.42    4170 1792.22
  4255.5 1792.75  4322.2 1791.35  4691.6 1789.89  4803.5 1788.29  4833.7 1789.54
  4883.4 1788.52  4885.3 1787.11  4885.8 1786.61  4892.3 1787.11  4907.5  1788.3
  4960.9 1787.19  5103.7 1789.12  5339.8 1791.66  5958.8 1803.09  6255.4 1811.06
#Mann= 6 ,-1 , 0
  2649.7    .045       0  4691.6     .07       0  4885.3     .07       0
  4892.3     .07       0  5103.7    .045       0  5958.8     .07       0
Bank Sta=4885.3,4892.3
XS Rating Curve= 0 ,0
Exp/Cntr=0.3,0.1

Type RM Length L Ch R = 1 ,31073   ,986,986,986
BEGIN DESCRIPTION:
Mapping XS 1502291e
END DESCRIPTION:
XS GIS Cut Line= 3
      1514286.71      6860179.13      1516296.28      6859480.34
      1517594.05      6858785.88
#Sta/Elev= 30
  2863.5 1804.95  2942.1 1805.68  3004.3 1803.88    3222 1802.28    3264  1800.6
  3335.8 1801.23  3380.5 1799.61  3921.5 1794.39  4040.7 1794.72  4584.7 1790.54
    4678 1790.43  4709.1 1792.53  4725.1 1790.43  4746.2 1789.81  4859.3 1789.24
  4946.8 1786.32  4968.6  1787.3  4987.8 1784.87  5022.9 1786.01  5024.9 1784.02
  5025.4 1783.52  5032.2 1784.02  5044.9 1786.08  5066.8 1786.71  5072.5 1785.11
  5088.7 1786.97  5183.4 1786.56  5443.3 1786.55  5613.4 1788.89    6463 1810.03
#Mann= 5 ,-1 , 0
  2863.5    .045       0  4946.8     .07       0  5024.9     .07       0
  5032.2     .07       0  5183.4    .045       0
Bank Sta=5024.9,5032.2
XS Rating Curve= 0 ,0
Exp/Cntr=0.3,0.1

Type RM Length L Ch R = 1 ,30087   ,781,781,781
BEGIN DESCRIPTION:
Mapping XS c38dce46
END DESCRIPTION:
XS GIS Cut Line= 3
       1515152.2      6860480.34      1516549.75      6860124.44
      1517747.62      6859377.93
#Sta/Elev= 30
    3552 1798.52  3622.1 1798.73    3689 1796.91  3944.1 1795.84    3985 1794.71
  4101.8 1794.72  4194.7 1792.95  4277.2 1794.02  4328.8 1792.08  4524.9    1791
  4925.4 1785.39  4956.3 1785.79  4968.6 1783.12  5001.6 1783.39  5007.3 1782.43
  5007.8 1781.93  5014.7 1782.43  5038.1 1784.04  5184.5 1783.96    5221 1782.59
  5242.3 1784.88  5278.9 1783.07  5315.4 1783.18  5321.3 1784.25    5437 1782.81
  5452.3 1783.42  5467.7 1786.17    5537 1786.57  6113.1 1796.47  6405.6 1803.12
#Mann= 5 ,-1 , 0
    3552    .045       0  4925.4     .07       0  5007.3     .07       0
  5014.7     .07       0    5537    .045       0
Bank Sta=5007.3,5014.7
XS Rating Curve= 0 ,0
Exp/Cntr=0.3,0.1

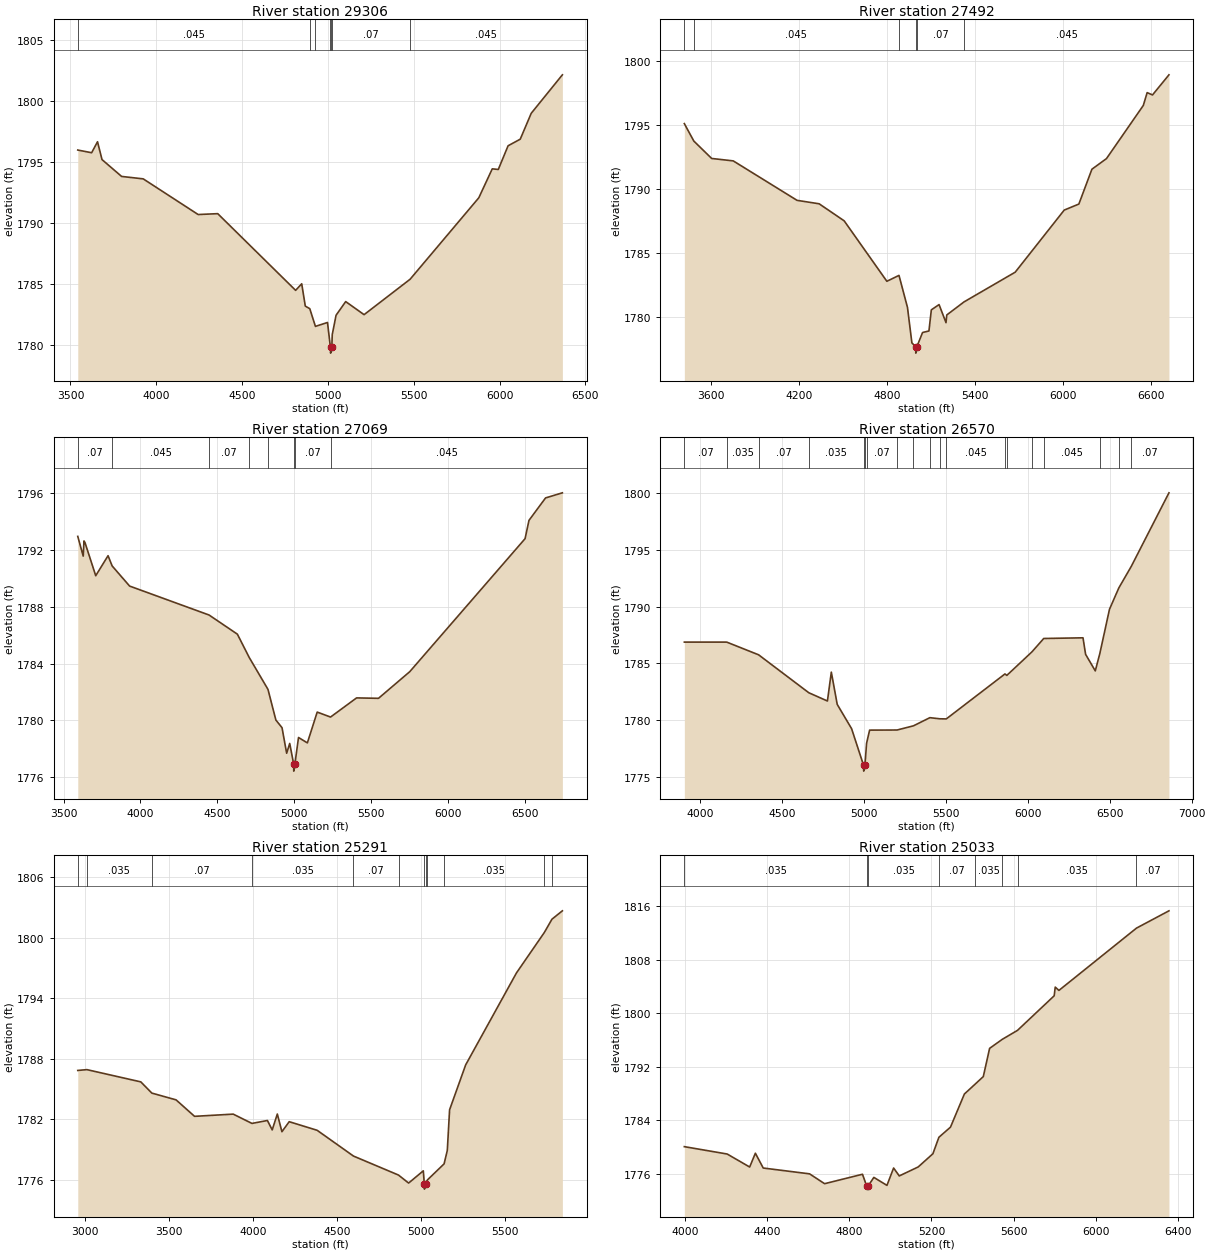
Type RM Length L Ch R = 1 ,29306   ,1814,1814,1814
BEGIN DESCRIPTION:
Mapping XS 39e47b5d
END DESCRIPTION:
XS GIS Cut Line= 4
      1515568.89      6861083.63      1516558.43       6860810.2
      1516909.99      6860549.78      1517764.12      6859491.88
#Sta/Elev= 30
  3542.6 1795.97  3623.4 1795.75  3657.7 1796.65  3683.8 1795.19  3797.9 1793.81
    3924 1793.61    4244 1790.69  4358.2 1790.76  4812.1 1784.48  4847.5 1785.02
  4868.4 1783.19  4894.5 1782.98  4927.4 1781.53  4997.8 1781.85  5014.2 1779.89
  5015.4 1779.84  5015.9 1779.34  5022.8 1779.84  5025.5 1780.86  5047.6 1782.44
  5103.8 1783.56    5211 1782.49  5479.1 1785.39  5879.4 1792.06  5957.8 1794.43
    5993 1794.38  6050.1 1796.32  6120.9 1796.86  6184.9 1798.98  6366.4 1802.13
#Mann= 7 ,-1 , 0
  3542.6    .045       0  4894.5     .07       0  4927.4    .045       0
  5014.2     .07       0  5015.4    .045       0  5022.8     .07       0
  5479.1    .045       0
Bank Sta=5015.4,5022.8
XS Rating Curve= 0 ,0
Exp/Cntr=0.3,0.1

Type RM Length L Ch R = 1 ,27492   ,423,423,423
BEGIN DESCRIPTION:
Mapping XS 6af4666c
END DESCRIPTION:
XS GIS Cut Line= 4
      1515729.48      6861265.93      1517313.64      6861109.68
      1517886.55      6860866.62      1518237.48      6859831.16
#Sta/Elev= 30
  3416.8 1795.11  3481.4 1793.75  3603.2 1792.39  3750.6  1792.2    4186 1789.12
  4336.8 1788.85  4507.6 1787.52    4799  1782.8  4881.8 1783.26  4939.7 1780.76
  4969.8 1777.99    4996 1777.69  4996.5 1777.19  5003.9 1777.69  5042.7  1778.8
  5086.2 1778.92  5102.5 1780.57  5155.3 1780.98  5202.6 1779.57    5208 1780.17
  5325.7 1781.19    5675 1783.51  6009.6 1788.36  6109.5 1788.83  6198.5 1791.55
    6298 1792.38  6549.3 1796.53  6575.5 1797.53  6612.1 1797.35  6724.3 1798.92
#Mann= 6 ,-1 , 0
  3416.8     .07       0  3481.4    .045       0  4881.8     .07       0
    4996     .07       0  5003.9     .07       0  5325.7    .045       0
Bank Sta=4996,5003.9
XS Rating Curve= 0 ,0
Exp/Cntr=0.3,0.1

Type RM Length L Ch R = 1 ,27069   ,499,499,499
BEGIN DESCRIPTION:
Mapping XS 2404acff
END DESCRIPTION:
XS GIS Cut Line= 4
      1516098.33       6861391.8      1517508.95       6861435.2
      1517953.28      6860883.93      1518302.23       6859915.2
#Sta/Elev= 30
  3592.5 1792.96  3627.9 1791.57  3632.9 1792.64  3639.2 1792.53  3709.2 1790.19
  3789.3  1791.6  3815.8 1790.88  3929.3 1789.46  4445.7 1787.42  4629.7 1786.07
  4706.5 1784.43  4828.5 1782.18  4879.8 1780.02  4919.8 1779.48  4949.8 1777.68
  4969.8 1778.37  4995.4 1776.92  4995.9 1776.42  5003.3 1776.92  5026.9 1778.79
  5084.4 1778.41  5148.4 1780.58    5235 1780.23  5404.3 1781.58  5546.7 1781.55
    5750 1783.43  6499.1  1792.8  6524.5 1794.09  6632.2 1795.67  6741.5 1796.03
#Mann= 8 ,-1 , 0
  3592.5     .07       0  3815.8    .045       0  4445.7     .07       0
  4706.5    .035       0  4828.5     .07       0  4995.4     .07       0
  5003.3     .07       0    5235    .045       0
Bank Sta=4995.4,5003.3
XS Rating Curve= 0 ,0
Exp/Cntr=0.3,0.1

Type RM Length L Ch R = 1 ,26570   ,1279,1279,1279
BEGIN DESCRIPTION:
Mapping XS befd9a34
END DESCRIPTION:
XS GIS Cut Line= 4
      1516997.65      6861892.67      1517836.21      6861882.25
      1518177.24      6860514.14      1518797.05      6860165.17
#Sta/Elev= 30
  3901.4 1786.87  4160.3 1786.87  4354.9 1785.75  4661.6  1782.4  4775.3 1781.67
  4799.1 1784.22  4835.2 1781.37  4922.9 1779.23  4996.4 1775.98  4996.9 1775.48
  5004.3 1775.98  5014.5 1777.94    5033  1779.1  5200.7 1779.11  5300.9 1779.48
  5401.2  1780.2  5461.4  1780.1  5501.4 1780.09  5859.7 1784.06    5871 1783.93
  6024.5 1786.01  6096.5 1787.19  6336.3 1787.25  6352.2 1785.79  6411.4 1784.33
  6439.4 1785.88  6498.1 1789.77    6555 1791.65  6631.3 1793.56  6861.3 1800.05
#Mann= 19 ,-1 , 0
  3901.4     .07       0  4160.3    .035       0  4354.9     .07       0
  4661.6    .035       0  4996.4    .035       0  5004.3    .035       0
  5014.5     .07       0  5200.7    .035       0  5300.9     .07       0
  5401.2    .045       0  5461.4     .07       0  5501.4    .045       0
  5859.7    .035       0    5871    .045       0  6024.5    .035       0
  6096.5    .045       0  6439.4    .035       0    6555    .045       0
  6631.3     .07       0
Bank Sta=4996.4,5004.3
XS Rating Curve= 0 ,0
Exp/Cntr=0.3,0.1

Type RM Length L Ch R = 1 ,25291   ,258,258,258
BEGIN DESCRIPTION:
Mapping XS 09552609
END DESCRIPTION:
XS GIS Cut Line= 4
      1517159.86      6861966.74      1518281.41       6861984.1
      1518763.29      6861215.58      1518935.17        6860377.
#Sta/Elev= 30
  2954.5 1786.85  3008.9 1786.93  3329.7 1785.72  3395.4 1784.61  3539.7 1783.94
  3649.7 1782.31  3879.8 1782.53  3991.4 1781.61  4083.4  1781.9    4112 1780.97
  4142.4 1782.54  4169.8 1780.79  4213.2 1781.78  4379.5 1780.93  4595.8 1778.38
  4863.9  1776.5    4924 1775.71  5011.4 1776.92  5017.6 1775.61  5018.1 1775.11
  5025.8 1775.61  5035.9 1776.02  5135.2 1777.61  5154.3 1778.94  5167.9 1782.96
  5263.6  1787.4  5566.1  1796.5  5731.6 1800.49  5777.2 1801.81  5839.3 1802.64
#Mann= 12 ,-1 , 0
  2954.5     .07       0  3008.9    .035       0  3395.4     .07       0
  3991.4    .035       0  4595.8     .07       0  4863.9    .035       0
  5017.6    .035       0  5025.8    .035       0  5035.9     .07       0
  5135.2    .035       0  5731.6     .07       0  5777.2    .035       0
Bank Sta=5017.6,5025.8
XS Rating Curve= 0 ,0
Exp/Cntr=0.3,0.1

Type RM Length L Ch R = 1 ,25033   ,849,849,849
BEGIN DESCRIPTION:
Mapping XS 1ab05a0e
END DESCRIPTION:
XS GIS Cut Line= 3
      1518630.01      6862362.97       1518912.6      6861420.44
      1519210.28      6860074.24
#Sta/Elev= 30
  3995.2 1780.08    4204 1778.98  4313.7 1777.04  4341.5  1779.1  4379.8 1776.89
  4605.9 1776.02    4679 1774.55  4863.7 1775.96  4883.7 1774.24  4884.2 1773.74
  4891.9 1774.24  4919.1 1775.49    4983  1774.3  5015.5 1776.89  5043.1 1775.71
  5135.3 1777.05    5207 1779.02  5236.3 1781.48  5292.7 1782.99  5360.6 1787.94
  5411.2 1789.36  5452.8 1790.54  5483.5 1794.75  5545.3  1796.1  5619.6 1797.44
  5798.4  1802.6  5803.5 1803.89  5821.5  1803.4  6199.6  1812.7  6357.9 1815.28
#Mann= 8 ,-1 , 0
  3995.2    .035       0  4883.7    .035       0  4891.9    .035       0
  5236.3     .07       0  5411.2    .035       0  5545.3     .07       0
  5619.6    .035       0  6199.6     .07       0
Bank Sta=4883.7,4891.9
XS Rating Curve= 0 ,0
Exp/Cntr=0.3,0.1