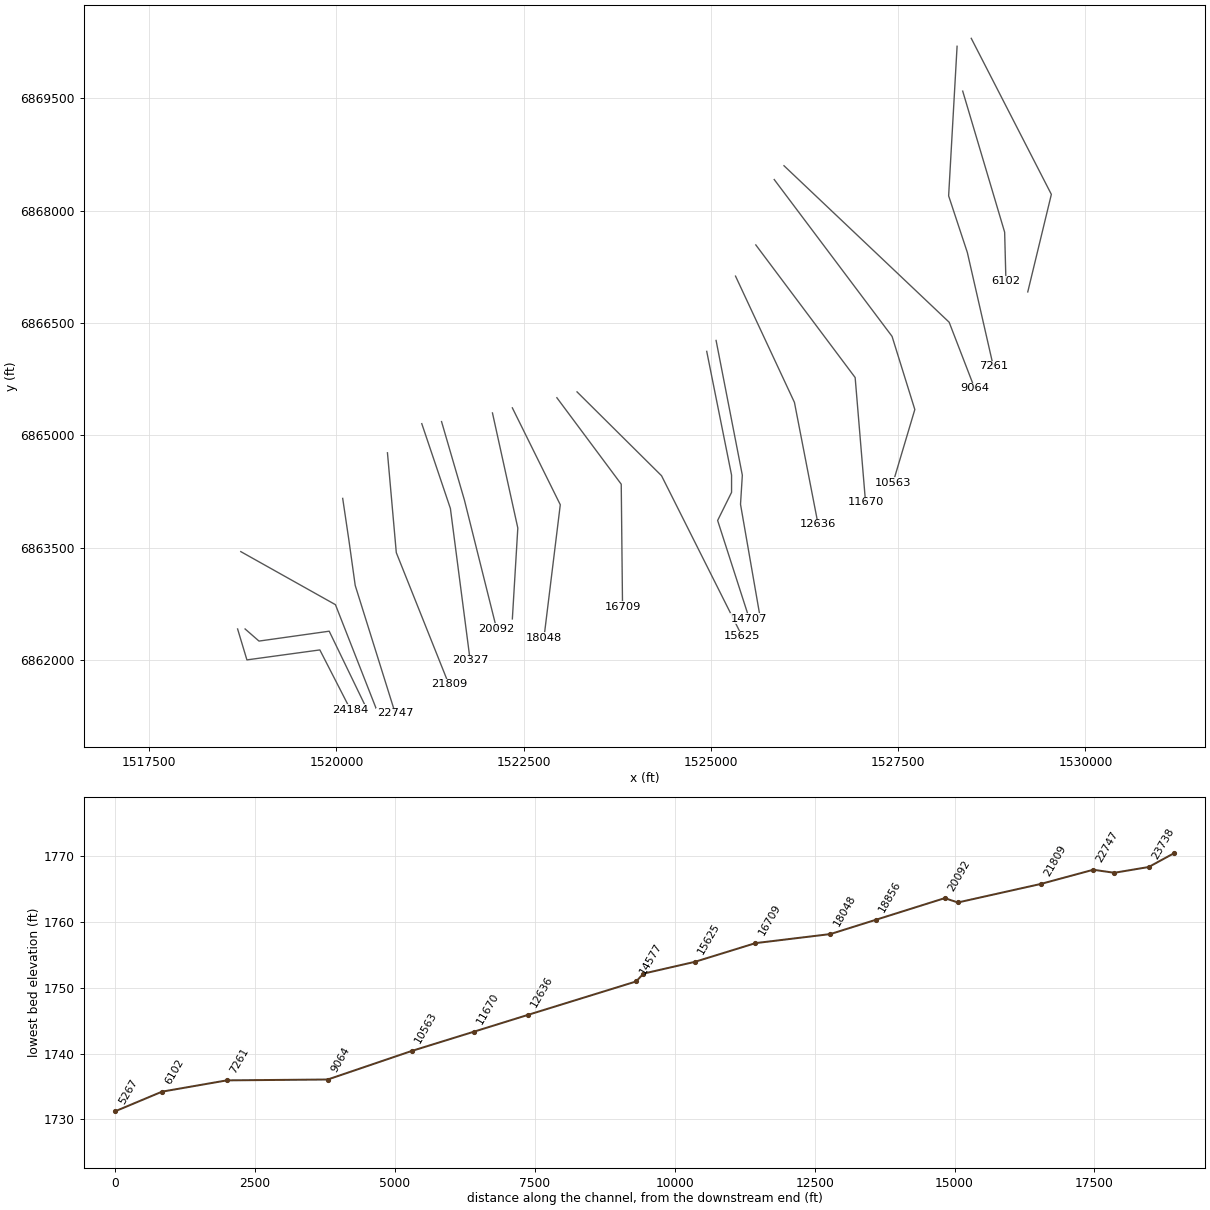
HEC-RAS study MULBERRY CREEK TRIBUTARY 15.prj: MULBERRY CREEK TRIBUTARY 15 Base Level Engineering

--- MULBERRY CREEK TRIBUTARY 15.g01 (geometry) --- (continued)

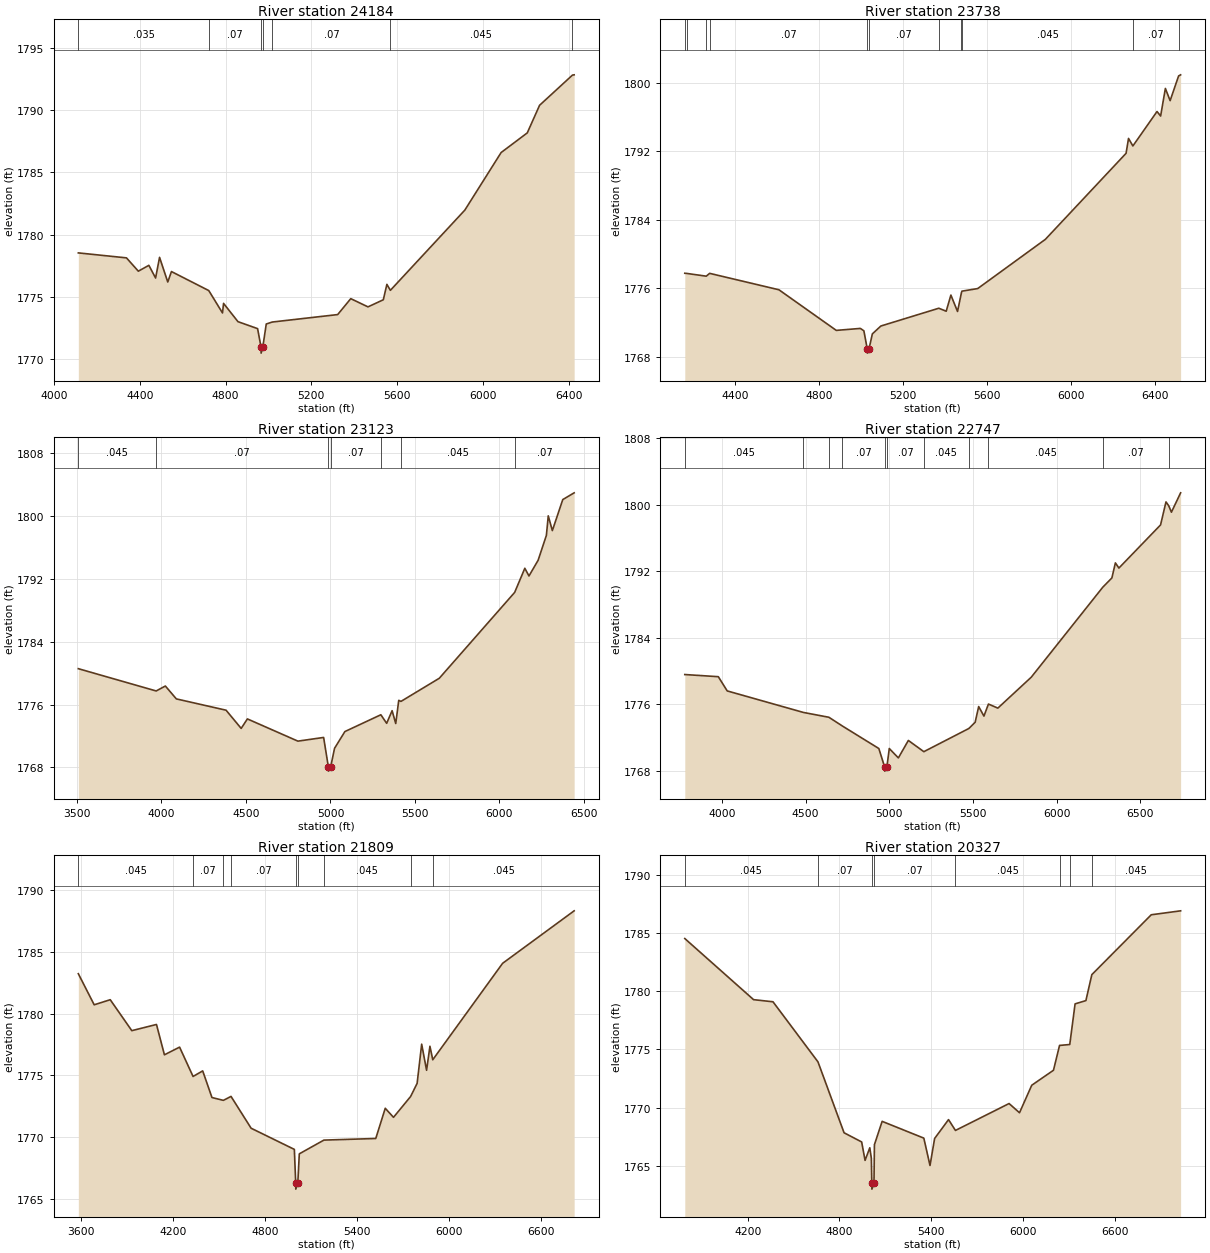
Type RM Length L Ch R = 1 ,24184   ,446,446,446
BEGIN DESCRIPTION:
Mapping XS 0a7dc2b2
END DESCRIPTION:
XS GIS Cut Line= 4
      1518680.01      6862412.96      1518804.33      6861999.98
      1519778.05      6862133.12      1520187.75      6861334.54
#Sta/Elev= 30
  4113.8 1778.53  4338.3 1778.13  4393.5 1777.06  4442.7 1777.53    4474 1776.51
  4492.5 1778.17  4530.8 1776.19  4547.9 1777.03    4722  1775.5  4785.9  1773.7
  4790.9 1774.47  4858.1    1773  4949.5 1772.44  4965.5 1770.97    4966 1770.47
  4973.9 1770.97  4989.9 1772.81  5017.9 1772.97  5322.9 1773.57  5383.9 1774.85
  5464.2 1774.19  5535.7 1774.76  5552.3    1776  5568.6 1775.52  5915.7 1781.97
  6084.9  1786.6  6206.8 1788.18  6264.2  1790.4  6417.6 1792.83  6425.4 1792.85
#Mann= 7 ,-1 , 0
  4113.8    .035       0    4722     .07       0  4965.5    .035       0
  4973.9     .07       0  5017.9     .07       0  5568.6    .045       0
  6417.6     .07       0
Bank Sta=4965.5,4973.9
XS Rating Curve= 0 ,0
Exp/Cntr=0.3,0.1

Type RM Length L Ch R = 1 ,23738   ,615,615,615
BEGIN DESCRIPTION:
Mapping XS 9742615b
END DESCRIPTION:
XS GIS Cut Line= 4
      1518780.01      6862412.99      1518965.55      6862251.17
      1519903.05      6862383.12      1520410.01      6861334.46
#Sta/Elev= 30
  4162.6 1777.74  4172.4 1777.72  4264.7  1777.4  4280.8 1777.73  4610.2 1775.81
  4882.9 1771.06  4997.5 1771.29  5014.2 1771.01  5030.1  1768.9  5030.6  1768.4
  5038.6  1768.9  5054.5 1770.65  5094.9 1771.57  5370.3 1773.65  5405.6  1773.3
  5427.9 1775.19  5459.5 1773.27  5478.3  1775.5  5480.7 1775.65  5555.4 1775.95
  5877.3 1781.71  6260.9 1791.77  6272.6 1793.51  6293.3 1792.63  6408.1 1796.66
  6425.2 1796.13  6447.8 1799.36  6470.4 1797.93  6510.7 1800.82  6520.3 1800.95
#Mann= 11 ,-1 , 0
  4162.6    .035       0  4172.4     .07       0  4264.7    .035       0
  4280.8     .07       0  5030.1     .07       0  5038.6     .07       0
  5370.3    .035       0  5478.3     .07       0  5480.7    .045       0
  6293.3     .07       0  6510.7    .035       0
Bank Sta=5030.1,5038.6
XS Rating Curve= 0 ,0
Exp/Cntr=0.3,0.1

Type RM Length L Ch R = 1 ,23123   ,376,376,376
BEGIN DESCRIPTION:
Mapping XS 4f95987e
END DESCRIPTION:
XS GIS Cut Line= 3
      1518722.53       6863445.6      1519986.38      6862737.28
      1520528.04      6861355.35
#Sta/Elev= 30
  3508.6 1780.57  3969.1 1777.73  4023.4 1778.36  4088.5 1776.72  4382.6 1775.28
  4471.9 1772.96  4508.7 1774.17  4807.5 1771.34  4959.7 1771.81    4988 1768.02
  4988.5 1767.52  5000.9 1768.02  5024.3 1770.43  5085.5 1772.56  5298.1  1774.7
  5332.6 1773.61  5364.8 1775.22  5386.3 1773.58  5404.1 1776.54  5417.1  1776.4
    5644 1779.35  6089.9 1790.29  6149.9 1793.36  6174.4 1792.38  6228.6 1794.38
  6277.5 1797.56  6288.5 1800.04  6312.7 1798.16  6374.4 1802.11  6441.7 1802.97
#Mann= 7 ,-1 , 0
  3508.6    .045       0  3969.1     .07       0    4988     .07       0
  5000.9     .07       0  5298.1    .035       0  5417.1    .045       0
  6089.9     .07       0
Bank Sta=4988,5000.9
XS Rating Curve= 0 ,0
Exp/Cntr=0.3,0.1

Type RM Length L Ch R = 1 ,22747   ,938,938,938
BEGIN DESCRIPTION:
Mapping XS 1d2ef92a
END DESCRIPTION:
XS GIS Cut Line= 4
      1520083.15       6864156.2      1520166.94      6863591.45
      1520250.27      6862994.23      1520784.99       6861285.9
#Sta/Elev= 30
    3778  1779.6  3978.4 1779.34  4031.5 1777.63  4487.1 1775.04  4639.3 1774.46
  4720.7  1773.4    4938  1770.7  4972.6 1768.48  4973.1 1767.98  4986.1 1768.48
  5000.4  1770.7  5054.7 1769.57  5114.4 1771.67    5207 1770.32  5476.2 1773.11
  5513.8 1773.86  5534.8 1775.75  5566.2  1774.6  5593.3 1776.05  5649.4 1775.56
  5849.1 1779.28  6276.9 1790.11  6331.1 1791.22    6352 1793.03  6373.1 1792.41
  6622.1  1797.6  6654.5 1800.37  6671.2 1799.89    6687 1799.13    6742 1801.46
#Mann= 11 ,-1 , 0
    3778    .045       0  4487.1     .07       0  4639.3     .16       0
  4720.7     .07       0  4972.6     .07       0  4986.1     .07       0
    5207    .045       0  5476.2    .035       0  5593.3    .045       0
  6276.9     .07       0  6671.2    .045       0
Bank Sta=4972.6,4986.1
XS Rating Curve= 0 ,0
Exp/Cntr=0.3,0.1

Type RM Length L Ch R = 1 ,21809   ,1482,1482,1482
BEGIN DESCRIPTION:
Mapping XS 7a74f305
END DESCRIPTION:
XS GIS Cut Line= 3
      1520680.82      6864765.08      1520798.88      6863431.73
      1521500.14       6861675.1
#Sta/Elev= 30
  3584.8 1783.22  3688.1 1780.71  3792.7 1781.12  3933.2 1778.62  4093.9 1779.12
  4145.7 1776.67  4244.4 1777.29  4332.2 1774.92    4395 1775.37  4455.3 1773.22
  4529.7 1772.99  4579.5 1773.31  4710.3 1770.74    4992 1769.03  5000.9 1766.32
  5001.4 1765.82  5014.5 1766.32  5024.3 1768.67  5184.5 1769.78  5522.4 1769.91
  5584.2 1772.35    5638 1771.62  5749.3  1773.3  5791.8 1774.36  5821.5 1777.53
  5853.4 1775.42  5875.3 1777.36  5893.7 1776.27  6348.7 1784.06  6814.8  1788.3
#Mann= 9 ,-1 , 0
  3584.8    .045       0  4332.2     .07       0  4529.7    .045       0
  4579.5     .07       0  5000.9     .07       0  5014.5     .07       0
  5184.5    .045       0  5749.3    .035       0  5893.7    .045       0
Bank Sta=5000.9,5014.5
XS Rating Curve= 0 ,0
Exp/Cntr=0.3,0.1

Type RM Length L Ch R = 1 ,20327   ,235,235,235
BEGIN DESCRIPTION:
Mapping XS 912f74fd
END DESCRIPTION:
XS GIS Cut Line= 3
      1521139.16      6865153.95       1521521.1      6864022.01
      1521784.99      6861994.25
#Sta/Elev= 30
  3789.3 1784.52  4238.8 1779.27  4365.5 1779.09  4659.4 1773.93  4829.9 1767.84
  4944.9 1767.05  4967.1 1765.47  4998.1 1766.55  5008.2 1765.64  5011.2  1763.5
  5011.7    1763  5025.3  1763.5  5028.3 1766.82  5078.7 1768.82    5351 1767.38
  5391.4 1765.03  5421.6 1767.35  5512.4 1768.97  5557.6 1768.04    5908 1770.35
  5976.2 1769.56  6056.1 1771.92  6198.1 1773.21  6237.7 1775.34  6304.5 1775.42
  6339.3 1778.91  6409.9 1779.19  6448.7 1781.42  6836.8 1786.56  7028.8  1786.9
#Mann= 8 ,-1 , 0
  3789.3    .045       0  4659.4     .07       0  5011.2     .07       0
  5025.3     .07       0  5557.6    .045       0  6237.7    .035       0
  6304.5     .07       0  6448.7    .045       0
Bank Sta=5011.2,5025.3
XS Rating Curve= 0 ,0
Exp/Cntr=0.3,0.1

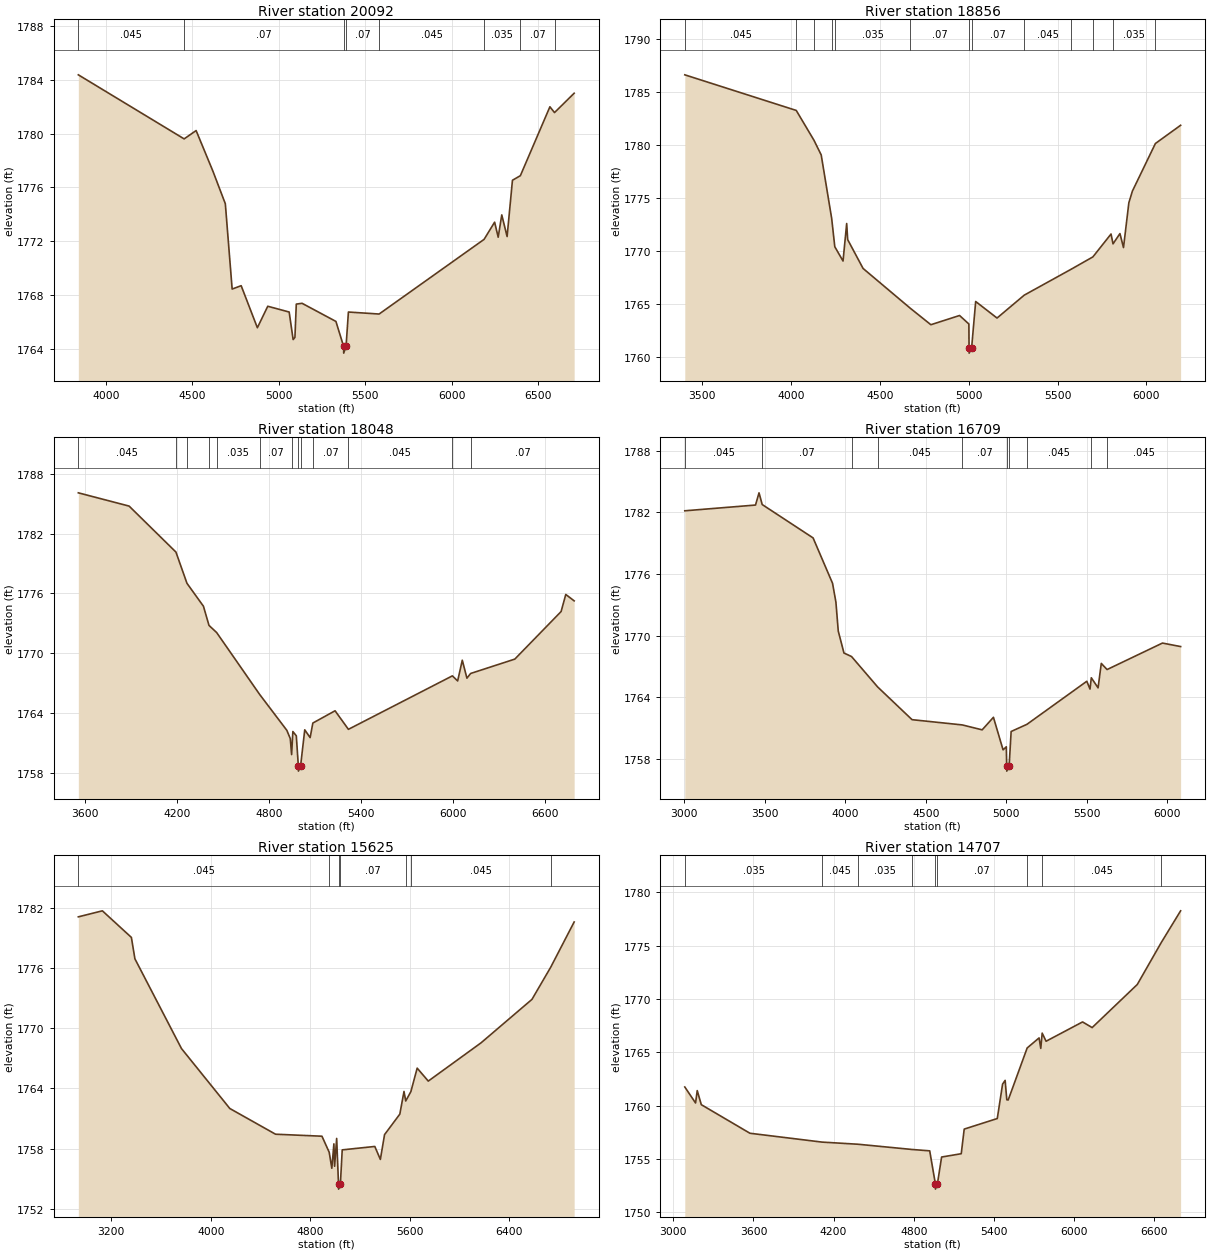
Type RM Length L Ch R = 1 ,20092   ,1236,1236,1236
BEGIN DESCRIPTION:
Mapping XS 07915123
END DESCRIPTION:
XS GIS Cut Line= 3
      1521403.06      6865181.69       1521708.6      6864133.12
      1522138.89      6862411.97
#Sta/Elev= 30
  3840.4 1784.38  4452.1 1779.61  4521.3 1780.23    4618 1777.22  4690.2 1774.78
  4729.6 1768.43  4781.7 1768.68  4875.4 1765.55  4935.5 1767.15  5059.2 1766.72
  5082.2 1764.67  5092.5 1764.83  5100.4 1767.31  5133.7 1767.37  5329.5 1766.02
    5374 1764.16  5374.5 1763.66  5388.1 1764.16  5401.7 1766.72  5579.1 1766.57
  6186.1 1772.13  6246.9 1773.41  6267.6 1772.29  6288.2 1773.95  6319.1 1772.34
    6350 1776.53  6395.7 1776.87  6566.5    1782  6593.2 1781.57  6706.7 1783.01
#Mann= 8 ,-1 , 0
  3840.4    .045       0  4452.1     .07       0    5374     .07       0
  5388.1     .07       0  5579.1    .045       0  6186.1    .035       0
  6395.7     .07       0  6593.2    .045       0
Bank Sta=5374,5388.1
XS Rating Curve= 0 ,0
Exp/Cntr=0.3,0.1

Type RM Length L Ch R = 1 ,18856   ,808,808,808
BEGIN DESCRIPTION:
Mapping XS e74e4b56
END DESCRIPTION:
XS GIS Cut Line= 3
      1522082.74      6865297.28      1522421.28      6863760.83
      1522348.36      6862547.32
#Sta/Elev= 30
  3403.5 1786.61  4030.4 1783.25    4130 1780.44  4170.8 1779.05  4229.7 1773.06
  4247.2 1770.39  4293.6 1769.04  4314.1 1772.58  4319.7 1771.06  4406.3 1768.34
  4672.3 1764.58  4787.6 1763.03    4949  1763.9  5001.4  1763.1  5002.5 1760.85
    5003 1760.35  5016.9 1760.85  5039.7 1765.22  5159.9 1763.66  5312.8 1765.82
  5576.2 1768.26    5699 1769.43  5801.1 1771.59  5812.3 1770.66  5851.2 1771.63
  5871.2 1770.31  5901.3 1774.54  5921.3 1775.64  6050.6 1780.13  6192.5 1781.85
#Mann= 13 ,-1 , 0
  3403.5    .045       0  4030.4     .07       0    4130    .035       0
  4229.7     .07       0  4247.2    .035       0  4672.3     .07       0
  5002.5     .07       0  5016.9     .07       0  5312.8    .045       0
  5576.2     .07       0    5699    .045       0  5812.3    .035       0
  6050.6     .07       0
Bank Sta=5002.5,5016.9
XS Rating Curve= 0 ,0
Exp/Cntr=0.3,0.1

Type RM Length L Ch R = 1 ,18048   ,1339,1339,1339
BEGIN DESCRIPTION:
Mapping XS 9e2bfa7d
END DESCRIPTION:
XS GIS Cut Line= 3
      1522348.36      6865364.99      1522988.34      6864071.34
      1522770.23      6862293.77
#Sta/Elev= 30
  3556.7 1786.09    3888 1784.76  4193.4 1780.15  4265.3 1777.02  4372.8 1774.72
    4409  1772.8  4459.1 1772.08  4738.9 1765.89  4916.8 1762.28  4939.2 1761.45
  4947.9 1759.85  4956.1 1762.16  4978.5 1761.73  4991.9 1758.69  4992.4 1758.19
  5006.3 1758.69  5033.6 1762.33  5068.7 1761.55  5086.4 1763.01  5231.4 1764.24
  5318.4 1762.38  5996.5 1767.74    6031 1767.23  6061.2 1769.31  6091.5 1767.51
  6115.6 1767.98  6403.8 1769.42  6705.8 1774.19  6736.3  1775.9  6790.9 1775.26
#Mann= 13 ,-1 , 0
  3556.7    .045       0  4193.4     .07       0  4265.3    .035       0
    4409     .07       0  4459.1    .035       0  4738.9     .07       0
  4947.9    .035       0  4991.9    .035       0  5006.3    .035       0
  5086.4     .07       0  5318.4    .045       0  5996.5    .035       0
  6115.6     .07       0
Bank Sta=4991.9,5006.3
XS Rating Curve= 0 ,0
Exp/Cntr=0.3,0.1

Type RM Length L Ch R = 1 ,16709   ,1084,1084,1084
BEGIN DESCRIPTION:
Mapping XS 79cefe73
END DESCRIPTION:
XS GIS Cut Line= 3
      1522942.81       6865500.4      1523802.18       6864345.9
      1523819.54      6862705.23
#Sta/Elev= 30
  3003.6 1782.16  3442.9 1782.72  3464.7 1783.91  3484.4 1782.77  3800.5 1779.52
  3921.4  1775.1  3942.3 1773.27  3956.9 1770.45  3992.3 1768.31  4039.3 1767.97
  4201.3 1765.01  4415.3 1761.82  4726.9 1761.31  4850.8 1760.83  4920.8 1762.05
  4980.8 1758.88  5000.8 1759.18  5003.2 1757.31  5003.7 1756.81  5018.3 1757.31
  5030.8 1760.67  5129.2 1761.37  5500.8 1765.56  5520.8  1764.8  5528.8  1765.9
  5570.8 1764.92  5590.8  1767.3  5626.7  1766.7  5970.8 1769.28  6083.6 1768.94
#Mann= 10 ,-1 , 0
  3003.6    .045       0  3484.4     .07       0  4039.3    .035       0
  4201.3    .045       0  4726.9     .07       0  5003.2     .07       0
  5018.3     .07       0  5129.2    .045       0  5528.8    .035       0
  5626.7    .045       0
Bank Sta=5003.2,5018.3
XS Rating Curve= 0 ,0
Exp/Cntr=0.3,0.1

Type RM Length L Ch R = 1 ,15625   ,918,918,918
BEGIN DESCRIPTION:
Mapping XS f5fc9dce
END DESCRIPTION:
XS GIS Cut Line= 3
      1523211.89      6865578.55      1524340.37      6864458.75
      1525416.76      6862314.65
#Sta/Elev= 30
  2934.6 1781.08  3128.1 1781.68  3361.5 1779.03  3389.8  1776.9  3764.5 1767.96
  4153.4 1761.99  4521.1 1759.43  4894.5 1759.23  4952.9 1757.63  4973.9 1756.04
  4990.6 1758.47  4996.2 1756.24  5012.9 1759.01  5027.7 1754.46  5028.2 1753.96
  5042.8 1754.46  5057.6 1757.87  5319.7 1758.21  5364.4 1756.92  5398.2 1759.39
    5521 1761.43  5554.6 1763.69  5568.5 1762.74  5609.9 1763.67  5660.6 1766.01
  5749.9 1764.72  6174.3 1768.53  6584.1 1772.86  6735.2 1776.07  6923.5 1780.57
#Mann= 7 ,-1 , 0
  2934.6    .045       0  4952.9     .07       0  5027.7     .07       0
  5042.8     .07       0  5568.5    .035       0  5609.9    .045       0
  6735.2     .07       0
Bank Sta=5027.7,5042.8
XS Rating Curve= 0 ,0
Exp/Cntr=0.3,0.1

Type RM Length L Ch R = 1 ,14707   ,130,130,130
BEGIN DESCRIPTION:
Mapping XS 79d956a1
END DESCRIPTION:
XS GIS Cut Line= 5
      1524943.61      6866119.29       1525275.2      6864466.71
      1525275.14      6864236.79      1525089.14      6863861.35
      1525512.26        6862549.
#Sta/Elev= 30
  3085.8 1761.75  3166.4 1760.25  3178.9 1761.41  3209.5 1760.09  3573.7 1757.41
    4114 1756.58  4382.6 1756.38  4786.7 1755.89    4920 1755.76  4962.4 1752.67
  4962.9 1752.17  4977.7 1752.67  5009.1 1755.18  5156.1 1755.49  5178.4  1757.8
    5426 1758.79  5465.8 1762.02  5484.9 1762.37  5497.3 1760.55  5507.8 1760.53
    5650 1765.41    5739 1766.35  5751.8 1765.37  5762.3  1766.8  5791.5 1766.04
  6064.7 1767.85  6136.5 1767.32  6474.4 1771.36  6654.3  1775.3  6799.1 1778.27
#Mann= 9 ,-1 , 0
  3085.8    .035       0    4114    .045       0  4382.6    .035       0
  4786.7     .07       0  4962.4     .07       0  4977.7     .07       0
    5650    .035       0  5762.3    .045       0  6654.3     .07       0
Bank Sta=4962.4,4977.7
XS Rating Curve= 0 ,0
Exp/Cntr=0.3,0.1

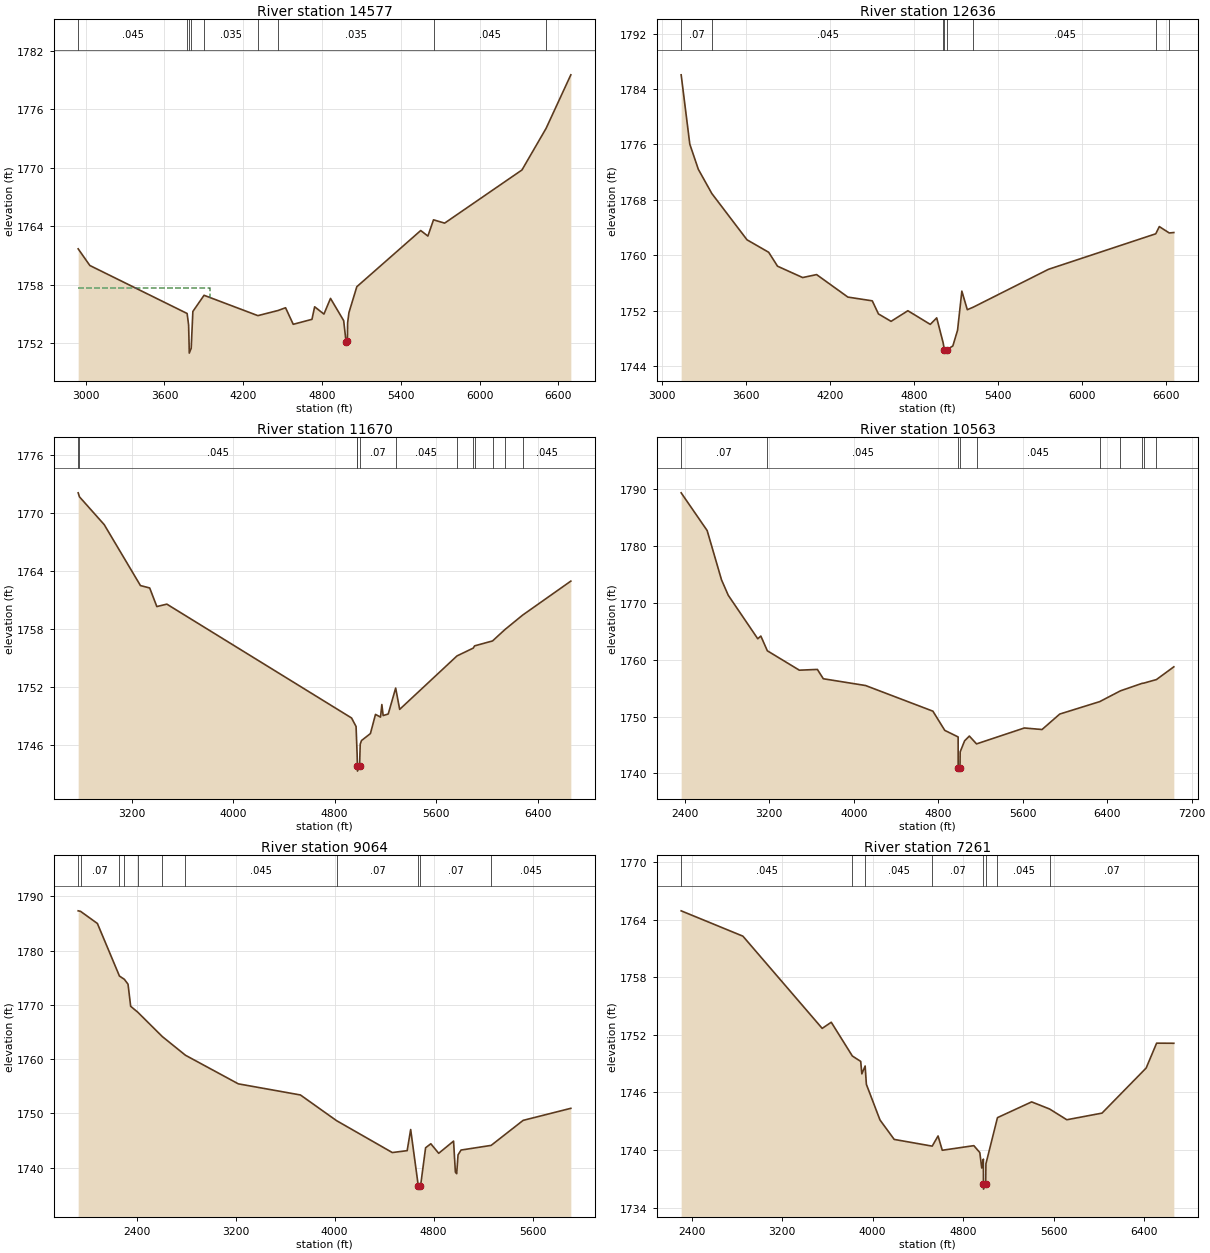
Type RM Length L Ch R = 1 ,14577   ,1941,1941,1941
BEGIN DESCRIPTION:
Mapping XS 938b5054
END DESCRIPTION:
XS GIS Cut Line= 4
      1525068.61      6866265.11      1525419.02      6864466.19
      1525394.72       6864077.3      1525656.61      6862571.49
#Sta/Elev= 30
  2943.2 1761.69    3032 1759.98  3772.7 1755.05    3784 1753.87  3788.4 1751.48
  3788.9 1750.98  3803.7 1751.48  3816.4 1755.26  3901.6 1756.92  4311.3 1754.83
  4465.5 1755.36    4522 1755.64  4580.5 1753.94  4723.1 1754.45  4743.5 1755.74
  4814.2 1754.99  4864.3  1756.6  4964.5 1754.32 4983.261752.085 4992.851752.257
  4994.5 1754.08  5004.6 1755.14  5064.7  1757.8  5551.1 1763.57  5605.7    1763
  5648.5 1764.67  5733.3 1764.33    6322 1769.79  6505.5 1774.06    6694 1779.56
#Mann= 9 ,-1 , 0
  2943.2    .045       0  3772.7     .07       0  3788.4    .035       0
  3803.7     .07       0  3901.6    .035       0  4311.3     .16       0
  4465.5    .035       0  5648.5    .045       0  6505.5     .07       0
#XS Ineff= 2 , 0
       0  3949.1 1757.62               0
Permanent Ineff=
       F       F
Bank Sta=4983.26,4992.85
XS Rating Curve= 0 ,0
Exp/Cntr=0.3,0.1

Type RM Length L Ch R = 1 ,12636   ,966,966,966
BEGIN DESCRIPTION:
Mapping XS 355ee160
END DESCRIPTION:
XS GIS Cut Line= 3
      1525328.14      6867123.87      1526114.77      6865437.96
      1526430.01      6863812.95
#Sta/Elev= 30
  3139.6 1786.05  3201.3 1776.04  3262.1 1772.41  3358.3 1768.92  3609.5 1762.23
  3764.2 1760.43  3827.3 1758.42  4006.8 1756.78  4106.1 1757.21  4329.4 1753.96
  4503.4 1753.42  4547.5 1751.53  4637.6 1750.46  4757.5 1751.99  4917.5 1750.02
  4963.2 1750.96  5009.1 1747.37  5018.1 1746.37  5018.6 1745.87  5034.7 1746.37
  5078.2  1746.9    5112 1749.17  5142.6 1754.82  5181.6 1752.14  5224.5 1752.51
  5760.7 1757.97  6526.4  1763.1  6551.8 1764.14  6622.4 1763.22  6655.3 1763.28
#Mann= 8 ,-1 , 0
  3139.6     .07       0  3358.3    .045       0  5009.1     .07       0
  5018.1    .045       0  5034.7     .07       0  5224.5    .045       0
  6526.4    .035       0  6622.4    .045       0
Bank Sta=5018.1,5034.7
XS Rating Curve= 0 ,0
Exp/Cntr=0.3,0.1

Type RM Length L Ch R = 1 ,11670   ,1107,1107,1107
BEGIN DESCRIPTION:
Mapping XS ca9d1357
END DESCRIPTION:
XS GIS Cut Line= 3
      1525598.97      6867540.52      1526925.38      6865769.67
      1527064.27      6864102.97
#Sta/Elev= 30
  2777.4 1772.06  2787.5 1771.65    2983 1768.77  3268.5 1762.48  3341.4 1762.23
  3397.7 1760.31  3476.8 1760.56  4933.3  1748.8  4968.8 1747.92  4977.2 1745.02
  4979.4 1743.81  4979.9 1743.31  4996.3 1743.81  5001.6  1746.1  5011.7 1746.47
  5081.9 1747.19    5122 1749.17  5161.6 1748.89  5172.2 1750.19  5182.3 1749.05
  5222.4 1749.21  5281.1 1751.89  5312.7 1749.69  5764.5 1755.21  5892.9 1756.02
  5903.5 1756.25  6045.1 1756.76  6143.2 1757.94  6282.5 1759.43  6662.4 1762.94
#Mann= 12 ,-1 , 0
  2777.4     .07       0  2787.5    .045       0  4977.2     .07       0
  4979.4     .07       0  4996.3     .07       0  5281.1    .045       0
  5764.5     .07       0  5892.9    .045       0  5903.5     .07       0
  6045.1    .045       0  6143.2     .07       0  6282.5    .045       0
Bank Sta=4979.4,4996.3
XS Rating Curve= 0 ,0
Exp/Cntr=0.3,0.1

Type RM Length L Ch R = 1 ,10563   ,1499,1499,1499
BEGIN DESCRIPTION:
Mapping XS ef6ac62e
END DESCRIPTION:
XS GIS Cut Line= 4
      1525844.86      6868413.46      1527418.21      6866319.28
      1527722.03      6865342.72        1527430.      6864363.01
#Sta/Elev= 30
  2366.2 1789.35  2612.4 1782.71  2748.3 1774.04  2812.3 1771.32  3091.4 1763.68
  3120.6 1764.15  3182.1 1761.56  3485.1 1758.15  3655.9 1758.28  3712.1 1756.64
    4112 1755.45  4749.4 1750.94  4862.1 1747.56  4988.6  1746.4  4988.8 1740.89
  4989.3 1740.39  5005.9 1740.89  5007.8 1743.78  5049.7 1745.72  5094.7 1746.56
  5162.8 1745.18  5615.3 1747.98  5782.8 1747.71  5950.4 1750.43  6329.3 1752.62
  6525.7 1754.52    6730 1755.83  6748.1 1755.88  6866.1  1756.5  7030.6 1758.74
#Mann= 10 ,-1 , 0
  2366.2     .07       0  3182.1    .045       0  4988.8     .07       0
  5005.9    .045       0  5162.8    .045       0  6329.3     .07       0
  6525.7    .045       0    6730     .07       0  6748.1    .045       0
  6866.1     .07       0
Bank Sta=4988.8,5005.9
XS Rating Curve= 0 ,0
Exp/Cntr=0.3,0.1

Type RM Length L Ch R = 1 ,9064    ,1803,1803,1803
BEGIN DESCRIPTION:
Mapping XS 34bc8ad6
END DESCRIPTION:
XS GIS Cut Line= 3
      1525975.08      6868597.92      1528180.39      6866508.35
      1528520.33       6865627.3
#Sta/Elev= 30
  1927.5 1787.33  1947.1 1787.23  2082.9    1785  2261.2 1775.31  2300.9 1774.71
  2330.5 1773.81  2351.9 1769.74  2409.3 1768.65  2607.7 1764.16  2794.7 1760.72
    3222 1755.45  3724.1  1753.4  4015.9 1748.67  4466.8 1742.79  4586.9 1743.14
  4615.2 1747.03  4677.4 1736.55  4677.9 1736.05  4694.6 1736.55  4735.8 1743.67
  4778.2 1744.41  4841.7 1742.65  4961.9  1744.9  4976.6 1739.19  4987.1  1738.9
  4998.1 1742.36  5022.4 1743.25  5265.8 1744.11  5524.4 1748.72  5909.9 1750.94
#Mann= 11 ,-1 , 0
  1927.5    .045       0  1947.1     .07       0  2261.2    .035       0
  2300.9     .07       0  2409.3    .035       0  2607.7     .07       0
  2794.7    .045       0  4015.9     .07       0  4677.4     .07       0
  4694.6     .07       0  5265.8    .045       0
Bank Sta=4677.4,4694.6
XS Rating Curve= 0 ,0
Exp/Cntr=0.3,0.1

Type RM Length L Ch R = 1 ,7261    ,1159,1159,1159
BEGIN DESCRIPTION:
Mapping XS 04c5efec
END DESCRIPTION:
XS GIS Cut Line= 4
      1528286.26      6870192.98      1528173.45      6868195.85
      1528423.45       6867438.9      1528770.33      6865919.58
#Sta/Elev= 30
  2307.6 1764.92  2853.5 1762.28  3554.6 1752.67  3634.7 1753.31  3821.3 1749.79
  3895.1 1749.23  3905.1 1747.93  3934.3 1748.75  3945.2 1746.84  4065.4 1743.13
  4191.2  1741.1  4527.2  1740.4  4579.1 1741.46  4616.1 1739.97  4895.4 1740.45
  4948.1 1739.73  4965.2 1738.12  4979.7 1739.05  4980.4 1736.42  4980.9 1735.92
  4999.9 1736.42  5002.2 1738.56  5104.3 1743.37  5406.3 1745.01  5565.1 1744.27
  5717.4 1743.15  6028.5 1743.84  6418.9 1748.54  6511.3 1751.13  6663.5 1751.12
#Mann= 8 ,-1 , 0
  2307.6    .045       0  3821.3    .035       0  3934.3    .045       0
  4527.2     .07       0  4980.4     .07       0  4999.9     .07       0
  5104.3    .045       0  5565.1     .07       0
Bank Sta=4980.4,4999.9
XS Rating Curve= 0 ,0
Exp/Cntr=0.3,0.1

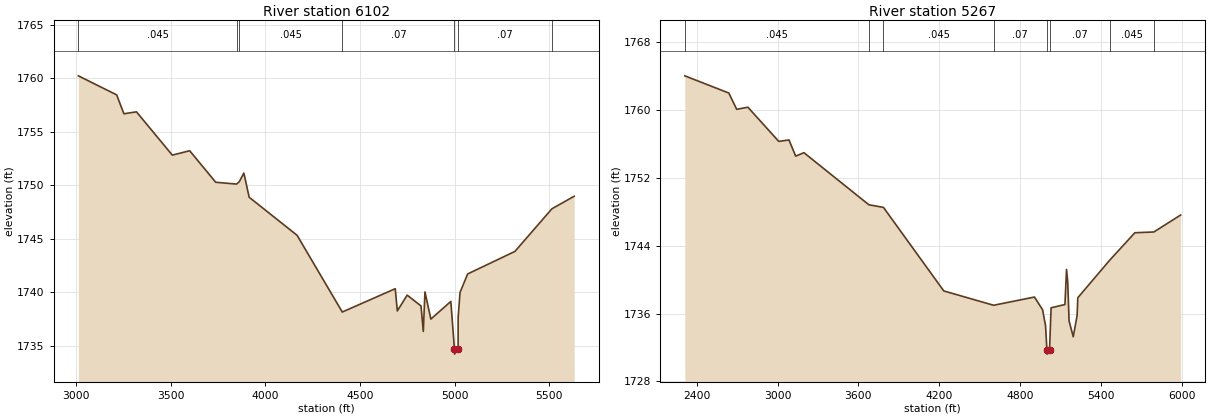
Type RM Length L Ch R = 1 ,6102    ,835,835,835
BEGIN DESCRIPTION:
Mapping XS f0dc67e0
END DESCRIPTION:
XS GIS Cut Line= 3
      1528361.42      6869594.17      1528921.32      6867710.46
      1528938.69      6867055.05
#Sta/Elev= 30
  3011.6 1760.24  3214.1 1758.46  3252.5 1756.69  3318.9 1756.87  3508.4 1752.82
  3600.2 1753.23  3737.9 1750.28  3848.4 1750.11  3862.5 1750.34  3886.6 1751.14
  3914.6 1748.88  4167.8 1745.32  4406.7 1738.14  4686.7 1740.32  4697.7 1738.24
  4749.8 1739.72  4822.8 1738.71  4835.1 1736.32  4843.7 1740.02    4875 1737.48
  4980.5 1739.13  4999.5  1734.7    5000  1734.2    5019  1734.7  5019.2 1737.65
  5029.2 1739.97  5069.3  1741.7  5319.3 1743.81  5514.9  1747.8  5632.4 1748.97
#Mann= 7 ,-1 , 0
  3011.6    .045       0  3848.4    .035       0  3862.5    .045       0
  4406.7     .07       0  4999.5     .07       0    5019     .07       0
  5514.9    .045       0
Bank Sta=4999.5,5019
XS Rating Curve= 0 ,0
Exp/Cntr=0.3,0.1

Type RM Length L Ch R = 1 ,5267    ,682,682,682
BEGIN DESCRIPTION:
Mapping XS 52b3c4c1
END DESCRIPTION:
XS GIS Cut Line= 3
      1528475.53      6870298.82      1529544.97      6868215.49
      1529230.01      6866913.02
#Sta/Elev= 30
  2311.1 1764.03    2638    1762  2696.5 1760.08  2779.6 1760.33  3008.9  1756.3
  3084.7 1756.47  3134.6 1754.56  3195.6 1754.97  3677.7 1748.83  3786.2 1748.52
  4234.2 1738.67  4604.3 1736.98  4907.5 1737.95    4968 1736.45  4989.8 1734.57
  5000.1 1731.72  5000.6 1731.22  5019.6 1731.72    5031 1736.68  5133.9 1737.07
  5145.7 1741.21  5154.4 1739.76  5164.7 1735.12  5195.6 1733.27  5224.2 1735.77
  5229.4 1737.87  5465.6 1742.28    5653 1745.53  5794.1 1745.62  5992.9 1747.62
#Mann= 8 ,-1 , 0
  2311.1    .045       0  3677.7    .035       0  3786.2    .045       0
  4604.3     .07       0  5000.1     .07       0  5019.6     .07       0
  5465.6    .045       0  5794.1     .07       0
#XS Ineff= 2 , 0
       0                  5145.7       0 1741.21
Permanent Ineff=
       F       F
Bank Sta=5000.1,5019.6
XS Rating Curve= 0 ,0
Exp/Cntr=0.3,0.1