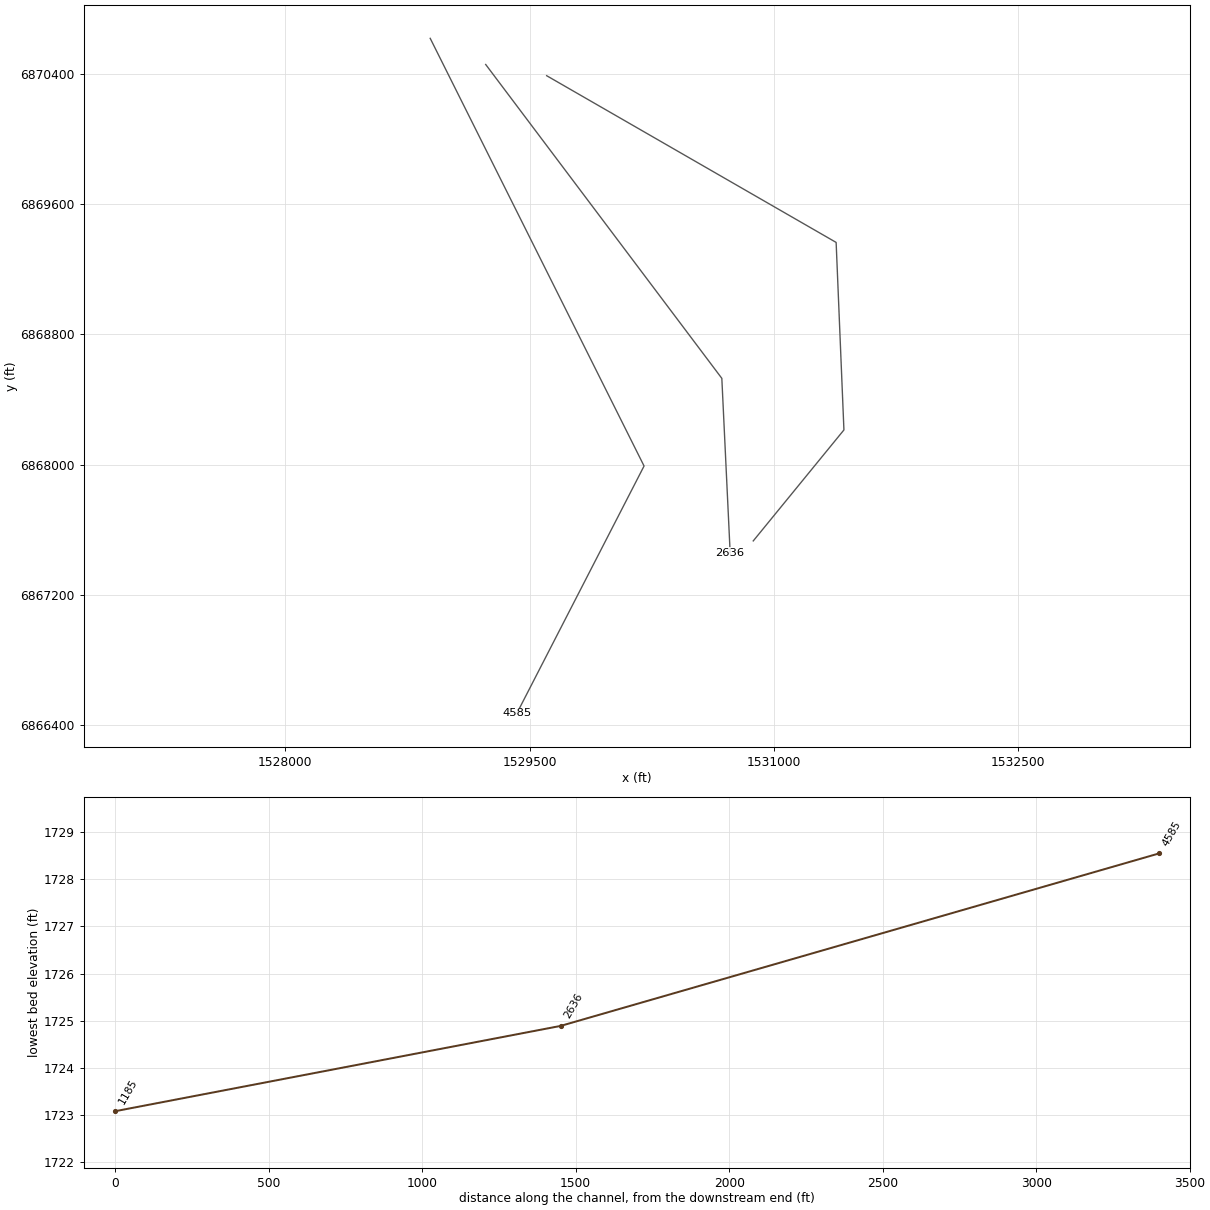
HEC-RAS study MULBERRY CREEK TRIBUTARY 15.prj: MULBERRY CREEK TRIBUTARY 15 Base Level Engineering

--- MULBERRY CREEK TRIBUTARY 15.g01 (geometry) --- (continued)

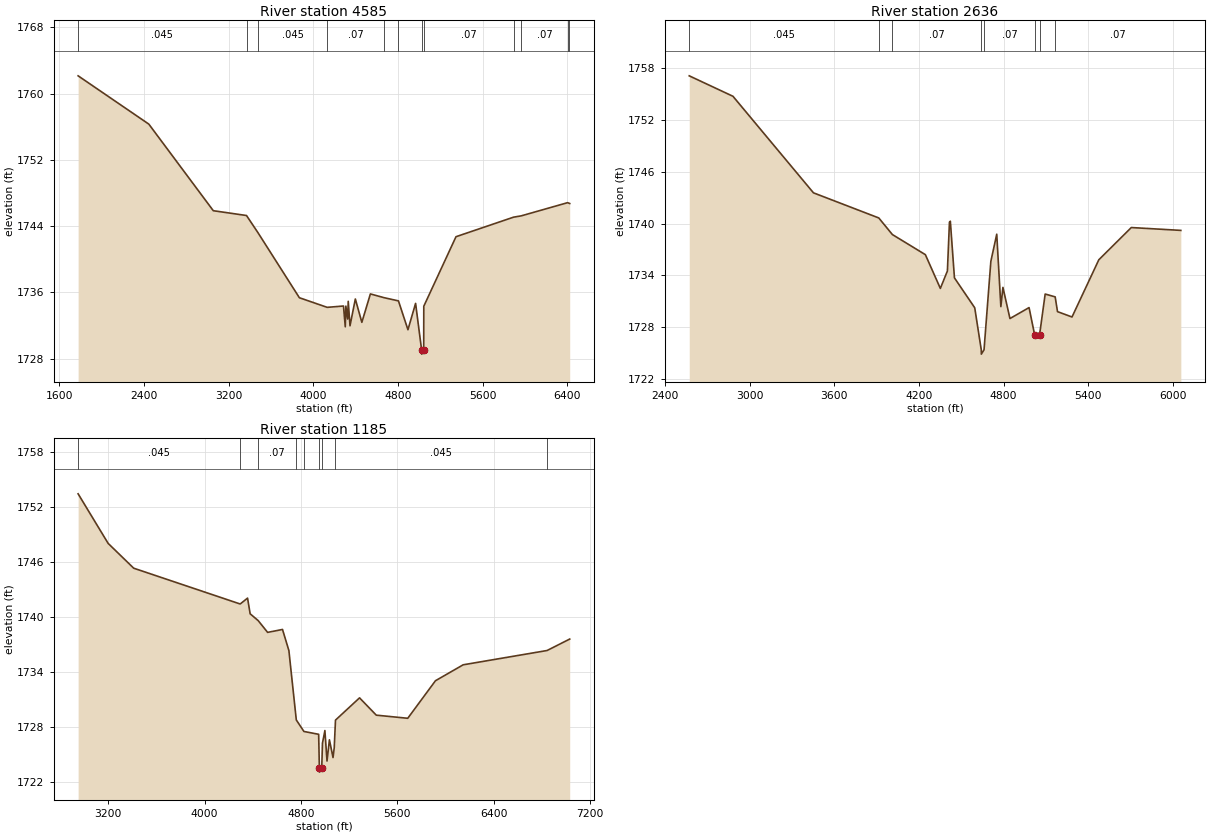
Type RM Length L Ch R = 1 ,4585    ,1949,1949,1949
BEGIN DESCRIPTION:
Mapping XS b6a2b235
END DESCRIPTION:
XS GIS Cut Line= 3
      1528890.02      6870617.42      1530202.96      6867991.53
      1529421.87      6866472.74
#Sta/Elev= 30
  1779.4 1762.16  2447.1 1756.33  3056.4 1745.87  3370.1 1745.29  3478.1 1743.22
  3869.5 1735.36  4132.1  1734.2  4286.2 1734.36    4303 1731.85  4308.6 1734.35
  4325.4 1732.79    4331 1734.93  4347.7 1731.97  4398.1 1735.21  4459.5 1732.39
  4540.3 1735.82  4671.5 1735.36  4805.3 1734.98  4895.1  1731.5  4967.2 1734.68
  5024.3 1729.05  5024.8 1728.55  5043.9 1729.05  5044.7 1734.33  5348.9 1742.73
  5892.6 1745.09  5965.7 1745.25  6402.7 1746.84  6413.8 1746.79  6423.1 1746.74
#Mann= 12 ,-1 , 0
  1779.4    .045       0  3370.1    .035       0  3478.1    .045       0
  4132.1     .07       0  4671.5     .16       0  4805.3     .07       0
  5024.3     .07       0  5043.9     .07       0  5892.6    .045       0
  5965.7     .07       0  6402.7    .045       0  6413.8     .07       0
Bank Sta=5024.3,5043.9
XS Rating Curve= 0 ,0
Exp/Cntr=0.3,0.1

Type RM Length L Ch R = 1 ,2636    ,1451,1451,1451
BEGIN DESCRIPTION:
Mapping XS b3dab427
END DESCRIPTION:
XS GIS Cut Line= 3
      1529230.72      6870456.83      1530680.39      6868529.73
      1530731.57      6867457.33
#Sta/Elev= 30
  2571.8 1757.12  2881.8 1754.75  3452.4 1743.57  3915.6 1740.66  4011.8 1738.74
  4245.8 1736.41    4352  1732.5    4402 1734.52  4416.6 1740.18  4422.8 1740.28
    4452 1733.72  4595.7 1730.26  4642.1 1725.39  4642.6 1724.89  4661.7 1725.39
  4710.1 1735.64  4751.8 1738.78    4781 1730.39  4795.6 1732.62  4845.5 1729.01
  4980.9 1730.28 5021.031727.077  5055.1 1727.08  5095.1 1731.85    5166 1731.52
  5182.6 1729.81  5285.4 1729.19  5475.6 1735.82  5705.8 1739.55  6056.9 1739.22
#Mann= 8 ,-1 , 0
  2571.8    .045       0  3915.6    .035       0  4011.8     .07       0
  4642.1     .07       0  4661.7     .07       0 5021.03    .045       0
  5055.1    .045       0    5166     .07       0
#XS Ineff= 2 , 0
       0  4751.8 1738.78               0
Permanent Ineff=
       F       F
Bank Sta=5021.03,5055.1
XS Rating Curve= 0 ,0
Exp/Cntr=0.3,0.1

Type RM Length L Ch R = 1 ,1185    ,0,0,0
BEGIN DESCRIPTION:
MULBERRY CREEK TRIBUTARY 15 1.0
END DESCRIPTION:
XS GIS Cut Line= 4
      1529604.98      6870388.01      1531382.16      6869364.37
        1531430.        6868213.      1530873.33      6867531.65
#Sta/Elev= 30
  2949.1 1753.47  3198.4 1748.06  3410.7 1745.35  4295.2 1741.44  4356.4 1742.08
    4378 1740.37  4444.4 1739.63  4523.1 1738.34  4646.7 1738.66  4699.8 1736.35
  4761.3 1728.78  4824.6 1727.52    4947 1727.21  4952.9 1723.58  4953.4 1723.08
  4972.7 1723.58  4978.6 1726.24  4998.8 1727.62  5016.4 1724.29  5036.4 1726.61
  5066.4 1724.67  5076.4 1725.75  5086.8 1728.76  5286.6 1731.19  5425.7  1729.3
    5687 1728.96  5917.2 1733.06  6147.4  1734.8  6844.2 1736.36  7032.2 1737.61
#Mann= 9 ,-1 , 0
  2949.1    .045       0  4295.2    .035       0  4444.4     .07       0
  4761.3    .045       0  4824.6     .07       0  4952.9     .07       0
  4972.7     .07       0  5086.8    .045       0  6844.2    .035       0
Bank Sta=4952.9,4972.7
XS Rating Curve= 0 ,0
Exp/Cntr=0.3,0.1

Chan Stop Cuts=-1
Use User Specified Reach Order=0
Composite Channel Slope=5