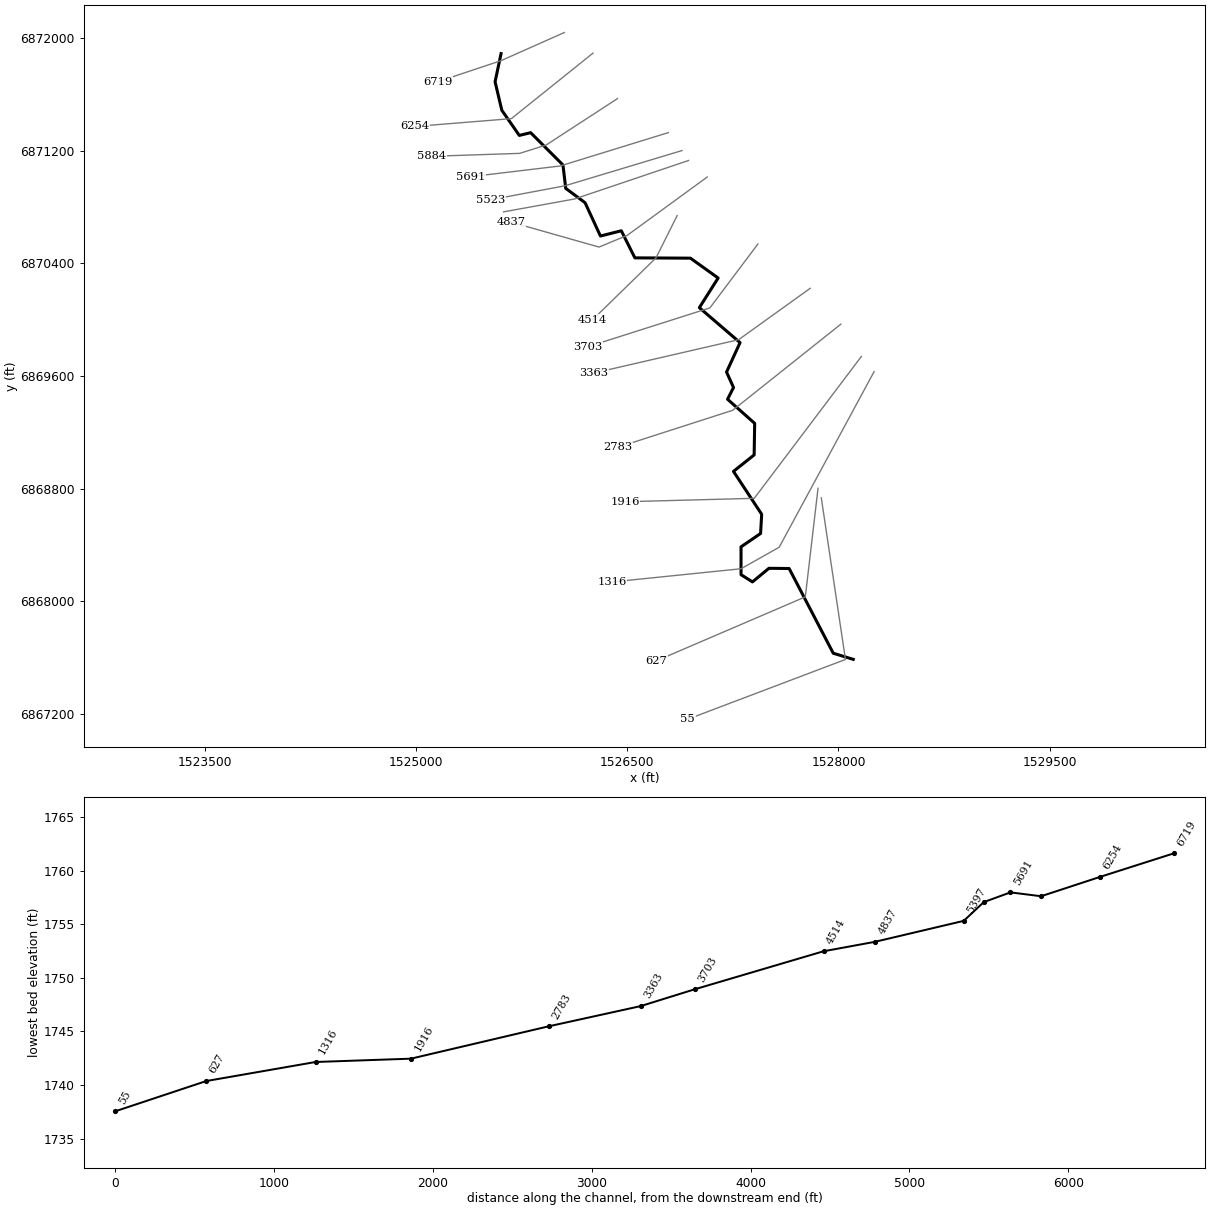
--- MULBERRY CREEK TRIBUTARY 15_1.prj (project) ---

Proj Title=MULBERRY CREEK TRIBUTARY 15_1 Base Level Engineering
Current Plan=p01
Default Exp/Contr=0.3,0.1
English Units
Geom File=g01
Flow File=f01
Plan File=p01
BEGIN DESCRIPTION:
MULBERRY CREEK TRIBUTARY 15_1
END DESCRIPTION:

--- MULBERRY CREEK TRIBUTARY 15_1.p01 (plan) ---

Plan Title=Multiple Run
Short Identifier=Multiple
Geom File=g01
Flow File=f01
Subcritical Flow
K Sum by GR= 0
Std Step Tol= 0.01
Critical Tol= 0.01
Num of Std Step Trials= 20
Max Error Tol= 0.3
Flow Tol Ratio= 0.001
Split Flow NTrial= 30
Split Flow Tol= 0.02
Split Flow Ratio= 0.02
Log Output Level= 0
Friction Slope Method= 1
Unsteady Friction Slope Method= 2
Unsteady Bridges Friction Slope Method= 1
Parabolic Critical Depth
Global Vel Dist=  1 , 1 , 1
Global Log Level= 0
CheckData=True
Encroach Param= -1, 0, 0, 0
BEGIN DESCRIPTION:
Multiple Run
END DESCRIPTION:

--- MULBERRY CREEK TRIBUTARY 15_1.f01 (steady flow) ---

Flow Title=Multiple
Number of Profiles=7
Profile Names=10-year,25-year,50-year,1pct_min,100-year,1pct_plu,500-year
River Rch & RM= MULBERRY CREEK T,Reach-1,6719
     169     228     275     165     330     658     480
River Rch & RM= MULBERRY CREEK T,Reach-1,4514
     302     420     518     318     634    1264     961
Boundary for River Rch & Prof#=MULBERRY CREEK T,Reach-1,1
Up Type=0
Dn Type=3
Dn Slope=0.005
Boundary for River Rch & Prof#=MULBERRY CREEK T,Reach-1,2
Up Type=0
Dn Type=3
Dn Slope=0.005
Boundary for River Rch & Prof#=MULBERRY CREEK T,Reach-1,3
Up Type=0
Dn Type=3
Dn Slope=0.005
Boundary for River Rch & Prof#=MULBERRY CREEK T,Reach-1,4
Up Type=0
Dn Type=3
Dn Slope=0.005
Boundary for River Rch & Prof#=MULBERRY CREEK T,Reach-1,5
Up Type=0
Dn Type=3
Dn Slope=0.005
Boundary for River Rch & Prof#=MULBERRY CREEK T,Reach-1,6
Up Type=0
Dn Type=3
Dn Slope=0.005
Boundary for River Rch & Prof#=MULBERRY CREEK T,Reach-1,7
Up Type=0
Dn Type=3
Dn Slope=0.005

--- MULBERRY CREEK TRIBUTARY 15_1.g01 (geometry) ---

Geom Title=Existing Conditions

River Reach=MULBERRY CREEK T,Reach-1
Reach XY= 30
      1525605.00      6871888.00      1525562.55      6871688.00
      1525610.48      6871485.56      1525734.62      6871307.21
      1525814.99      6871326.75      1526044.25      6871097.68
      1526064.29      6870931.31      1526201.49      6870829.52
      1526310.44      6870593.10      1526458.66      6870630.31
      1526555.00      6870438.00      1526949.14      6870435.94
      1527146.01      6870295.01      1527012.59      6870084.65
      1527301.54      6869836.50      1527205.61      6869627.37
      1527255.19      6869517.80      1527212.82      6869434.59
      1527405.33      6869263.21      1527401.55      6869039.25
      1527254.82      6868922.47      1527454.96      6868617.97
      1527447.31      6868481.53      1527308.45      6868386.75
      1527308.45      6868189.19      1527389.57      6868137.87
      1527506.48      6868234.46      1527649.92      6868232.98
      1527963.01      6867631.63      1528105.00      6867588.00

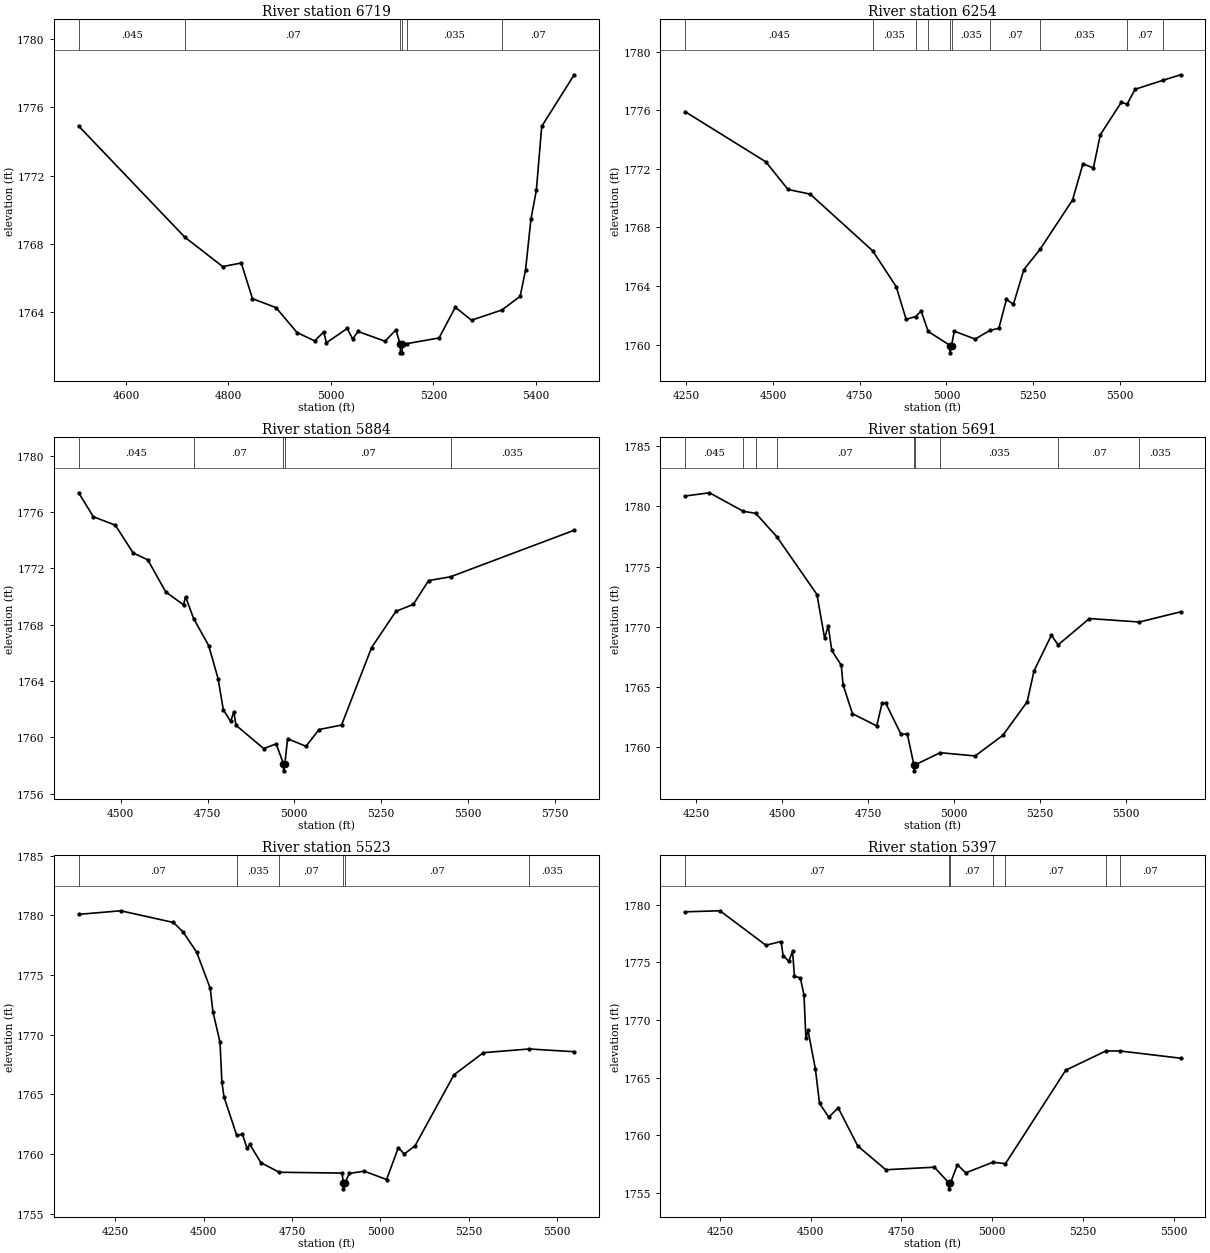
Type RM Length L Ch R = 1,6719,465,465,465
BEGIN DESCRIPTION:
MULBERRY CREEK TRIBUTARY 15_1 12.0
END DESCRIPTION:
XS GIS Cut Line= 3
      1526054.98      6872037.99      1525605.00      6871838.00
      1525154.96      6871687.99
#Sta/Elev= 30
  4507.7 1774.91  4714.6 1768.41  4788.8 1766.68  4825.0 1766.89  4846.9 1764.80
  4892.7 1764.28  4933.8 1762.82  4968.0 1762.33  4985.8 1762.85  4991.2 1762.22
  5031.7 1763.06  5042.3 1762.44  5052.8 1762.88  5105.5 1762.31  5126.6 1762.97
  5135.2 1762.13  5135.4 1761.63  5138.9 1761.63  5139.2 1762.13  5148.3 1762.17
  5210.9 1762.50  5242.6 1764.30  5274.2 1763.54  5333.6 1764.14  5369.1 1764.94
  5379.6 1766.47  5390.1 1769.44  5400.7 1771.15  5411.2 1774.89  5474.5 1777.91
#Mann=6,-1,0
  4507.7   0.045       0  4714.6    0.07       0  5135.2    0.07       0
  5139.2    0.07       0  5148.3   0.035       0  5333.6    0.07       0
Bank Sta=5135.2,5139.2
Exp/Cntr=0.3,0.1

Type RM Length L Ch R = 1,6254,370,370,370
BEGIN DESCRIPTION:
Mapping XS e76501e3
END DESCRIPTION:
XS GIS Cut Line= 3
      1526258.02      6871891.66      1525678.13      6871426.36
      1524994.07      6871370.80
#Sta/Elev= 30
  4246.1 1775.92  4479.0 1772.49  4543.0 1770.60  4607.0 1770.28  4787.1 1766.41
  4855.1 1763.96  4883.9 1761.72  4911.2 1761.91  4927.1 1762.29  4947.6 1760.89
  5010.8 1759.93  5011.0 1759.43  5014.8 1759.93  5022.8 1760.91  5083.0 1760.37
  5125.2 1760.96  5151.4 1761.11  5173.3 1763.08  5193.4 1762.75  5223.5 1765.12
  5270.1 1766.50  5364.0 1769.88  5394.0 1772.35  5424.1 1772.07  5444.2 1774.34
  5504.4 1776.55  5521.6 1776.44  5544.5 1777.45  5624.6 1778.06  5675.9 1778.44
#Mann=10,-1,0
  4246.1   0.045       0  4787.1   0.035       0  4911.2    0.07       0
  4947.6   0.035       0  5010.8   0.035       0  5014.8   0.035       0
  5125.2    0.07       0  5270.1   0.035       0  5521.6    0.07       0
  5624.6   0.045       0
Bank Sta=5010.8,5014.8
Exp/Cntr=0.3,0.1

Type RM Length L Ch R = 1,5884,193,193,193
BEGIN DESCRIPTION:
Mapping XS 37237447
END DESCRIPTION:
XS GIS Cut Line= 4
      1526431.56      6871568.69      1525924.66      6871238.86
      1525737.16      6871179.83      1525112.15      6871158.99
#Sta/Elev= 30
  4378.9 1777.36  4421.3 1775.66  4484.6 1775.06  4535.9 1773.09  4578.1 1772.60
  4629.5 1770.33  4680.9 1769.41  4686.8 1769.98  4710.1 1768.43  4753.3 1766.52
  4780.4 1764.17  4795.5 1761.96  4816.6 1761.14  4825.8 1761.81  4831.8 1760.87
  4911.7 1759.21  4947.5 1759.54  4968.7 1758.13  4969.0 1757.63  4972.7 1758.13
  4980.5 1759.91  5033.5 1759.37  5071.1 1760.56  5135.9 1760.88  5222.4 1766.38
  5292.5 1768.95  5342.5 1769.44  5386.4 1771.13  5449.6 1771.40  5805.6 1774.70
#Mann=5,-1,0
  4378.9   0.045       0  4710.1    0.07       0  4968.7    0.07       0
  4972.7    0.07       0  5449.6   0.035       0
Bank Sta=4968.7,4972.7
Exp/Cntr=0.3,0.1

Type RM Length L Ch R = 1,5691,168,168,168
BEGIN DESCRIPTION:
Mapping XS 6156f0d3
END DESCRIPTION:
XS GIS Cut Line= 3
      1526792.68      6871327.21      1526024.48      6871090.24
      1525391.69      6871014.73
#Sta/Elev= 30
  4217.6 1780.87  4288.4 1781.14  4387.4 1779.59  4423.0 1779.43  4484.4 1777.48
  4601.1 1772.67  4623.3 1769.04  4633.8 1770.05  4644.2 1768.01  4671.7 1766.79
  4676.9 1765.17  4704.3 1762.75  4774.9 1761.73  4790.7 1763.65  4801.2 1763.62
  4845.4 1761.04  4864.0 1761.05  4882.9 1758.49  4883.2 1757.99  4886.9 1758.49
  4959.2 1759.50  5061.3 1759.23  5141.8 1760.95  5212.3 1763.73  5232.5 1766.32
  5282.8 1769.28  5302.5 1768.48  5393.6 1770.67  5538.8 1770.38  5658.8 1771.23
#Mann=9,-1,0
  4217.6   0.045       0  4387.4    0.07       0  4423.0   0.035       0
  4484.4    0.07       0  4882.9   0.035       0  4886.9    0.07       0
  4959.2   0.035       0  5302.5    0.07       0  5538.8   0.035       0
Bank Sta=4882.9,4886.9
Exp/Cntr=0.3,0.1

Type RM Length L Ch R = 1,5523,126,126,126
BEGIN DESCRIPTION:
Mapping XS 50f86a25
END DESCRIPTION:
XS GIS Cut Line= 3
      1526889.11      6871199.63      1526058.34      6870949.62
      1525532.34      6870850.67
#Sta/Elev= 30
  4145.7 1780.08  4264.9 1780.38  4414.0 1779.40  4441.8 1778.59  4480.0 1776.90
  4518.2 1773.88  4525.9 1771.92  4546.0 1769.35  4551.2 1766.03  4557.3 1764.77
  4593.3 1761.56  4609.5 1761.65  4622.5 1760.47  4630.4 1760.80  4661.7 1759.27
  4713.7 1758.47  4891.4 1758.40  4895.1 1757.58  4895.3 1757.08  4899.1 1757.58
  4912.3 1758.37  4954.1 1758.56  5017.5 1757.86  5050.7 1760.53  5067.6 1760.00
  5098.1 1760.69  5208.1 1766.63  5291.4 1768.49  5421.4 1768.80  5548.5 1768.57
#Mann=6,-1,0
  4145.7    0.07       0  4593.3   0.035       0  4713.7    0.07       0
  4895.1    0.07       0  4899.1    0.07       0  5421.4   0.035       0
Bank Sta=4895.1,4899.1
Exp/Cntr=0.3,0.1

Type RM Length L Ch R = 1,5397,560,560,560
BEGIN DESCRIPTION:
Mapping XS 63761c91
END DESCRIPTION:
XS GIS Cut Line= 3
      1526935.93      6871129.30      1526126.05      6870855.87
      1525623.44      6870764.72
#Sta/Elev= 30
  4153.8 1779.40  4249.8 1779.49  4376.4 1776.50  4418.5 1776.82  4423.8 1775.60
  4439.8 1775.10  4449.9 1775.99  4455.2 1773.79  4471.4 1773.66  4481.4 1772.19
  4486.7 1768.40  4492.5 1769.09  4512.9 1765.74  4524.2 1762.76  4549.6 1761.56
  4575.8 1762.36  4629.7 1759.05  4706.9 1756.99  4840.8 1757.21  4881.0 1755.83
  4881.3 1755.33  4885.0 1755.83  4904.2 1757.43  4927.2 1756.72  5001.9 1757.64
  5036.7 1757.52  5202.8 1765.64  5313.4 1767.31  5351.8 1767.31  5519.4 1766.68
#Mann=7,-1,0
  4153.8    0.07       0  4881.0    0.07       0  4885.0    0.07       0
  5001.9   0.035       0  5036.7    0.07       0  5313.4   0.035       0
  5351.8    0.07       0
Bank Sta=4881,4885
Exp/Cntr=0.3,0.1

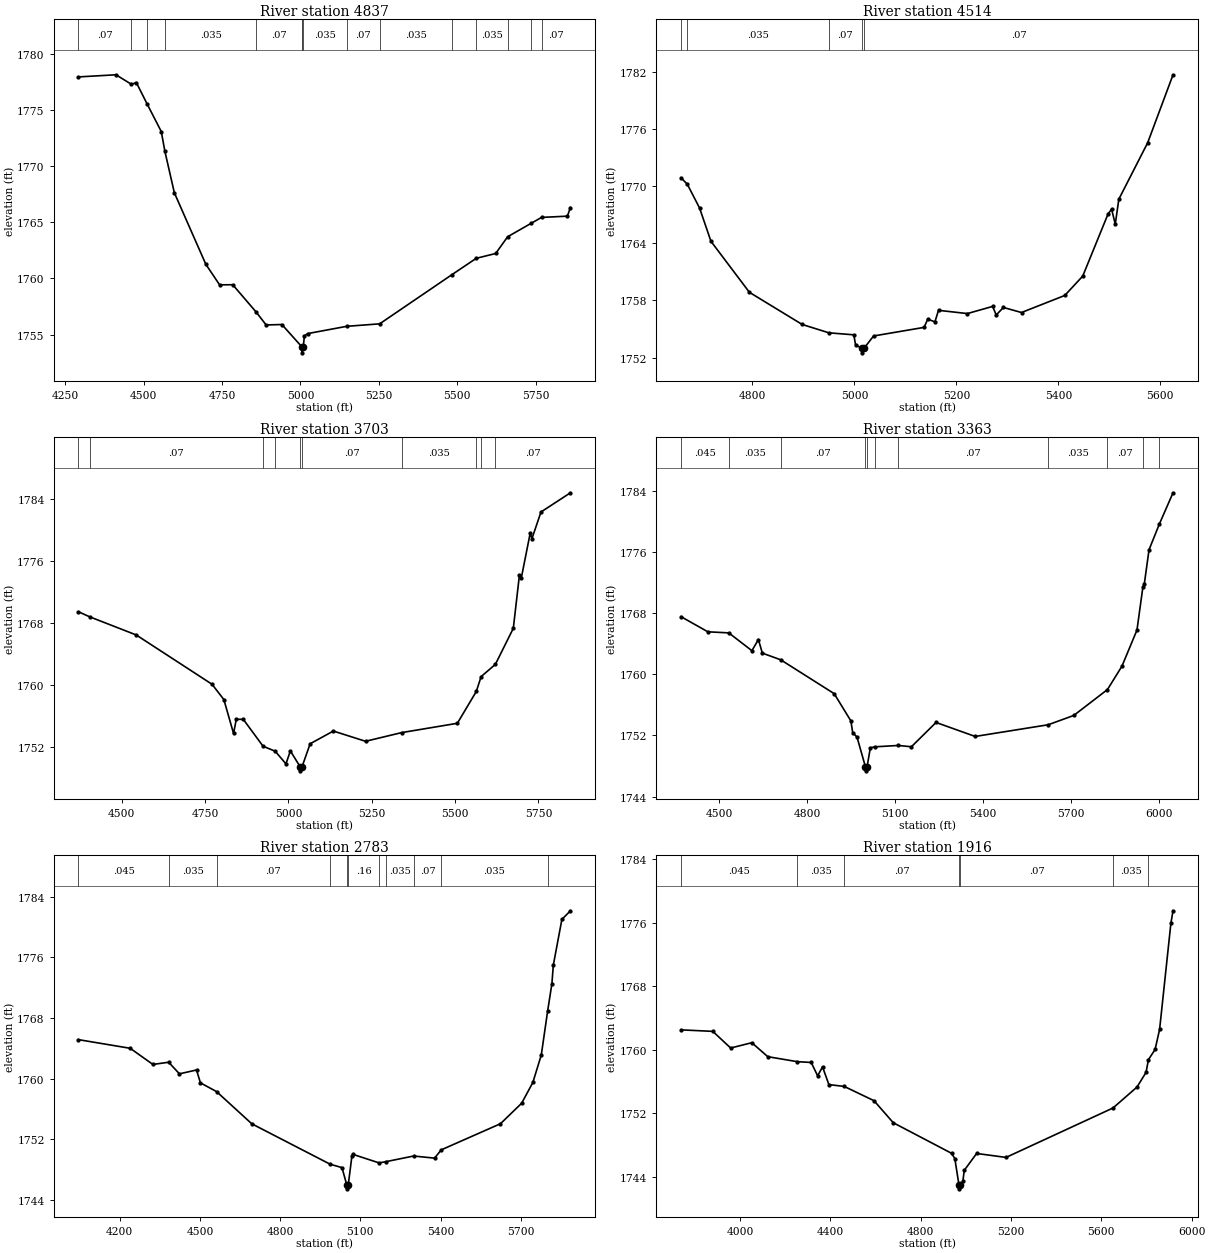
Type RM Length L Ch R = 1,4837,323,323,323
BEGIN DESCRIPTION:
Mapping XS 3b888a96
END DESCRIPTION:
XS GIS Cut Line= 4
      1527068.73      6871012.10      1526501.05      6870598.06
      1526300.53      6870514.72      1525675.51      6870691.81
#Sta/Elev= 30
  4291.9 1777.92  4411.6 1778.11  4461.0 1777.26  4476.5 1777.42  4510.8 1775.52
  4556.1 1773.06  4567.6 1771.30  4597.8 1767.61  4698.2 1761.25  4742.1 1759.42
  4784.0 1759.43  4859.0 1756.99  4890.6 1755.85  4940.8 1755.89  5005.0 1753.89
  5005.1 1753.87  5005.4 1753.37  5009.1 1753.87  5012.5 1754.87  5022.7 1755.08
  5147.6 1755.73  5252.7 1755.95  5482.4 1760.31  5560.8 1761.78  5622.8 1762.21
  5661.0 1763.70  5735.1 1764.88  5769.0 1765.42  5851.4 1765.53  5861.3 1766.30
#Mann=15,-1,0
  4291.9    0.07       0  4461.0   0.035       0  4510.8    0.07       0
  4567.6   0.035       0  4859.0    0.07       0  5005.0   0.035       0
  5005.1    0.07       0  5009.1   0.035       0  5147.6    0.07       0
  5252.7   0.035       0  5482.4    0.07       0  5560.8   0.035       0
  5661.0    0.07       0  5735.1   0.035       0  5769.0    0.07       0
Bank Sta=5005.1,5009.1
Exp/Cntr=0.3,0.1

Type RM Length L Ch R = 1,4514,811,811,811
BEGIN DESCRIPTION:
MULBERRY CREEK TRIBUTARY 15_1 7.0
END DESCRIPTION:
XS GIS Cut Line= 3
      1526854.98      6870737.97      1526705.00      6870438.00
      1526254.28      6869998.36
#Sta/Elev= 30
  4659.9 1770.86  4672.3 1770.17  4696.2 1767.69  4718.6 1764.19  4794.0 1758.84
  4897.4 1755.47  4949.9 1754.59  4998.8 1754.38  5002.3 1753.31  5013.9 1752.99
  5014.3 1752.49  5019.1 1752.99  5037.6 1754.26  5136.6 1755.16  5143.8 1756.02
  5157.9 1755.74  5164.9 1756.95  5221.5 1756.61  5271.1 1757.36  5278.1 1756.46
  5292.2 1757.25  5327.7 1756.72  5412.6 1758.51  5447.8 1760.54  5497.4 1767.05
  5504.4 1767.56  5511.6 1765.99  5518.6 1768.61  5575.1 1774.52  5624.9 1781.66
#Mann=5,-1,0
  4659.9    0.07       0  4672.3   0.035       0  4949.9    0.07       0
  5013.9    0.07       0  5019.1    0.07       0
Bank Sta=5013.9,5019.1
Exp/Cntr=0.3,0.1

Type RM Length L Ch R = 1,3703,340,340,340
BEGIN DESCRIPTION:
Mapping XS a8ead599
END DESCRIPTION:
XS GIS Cut Line= 3
      1527428.35      6870536.57      1527087.63      6870083.01
      1526221.71      6869807.39
#Sta/Elev= 30
  4370.1 1769.45  4403.7 1768.80  4543.4 1766.46  4770.9 1760.10  4806.3 1758.13
  4835.4 1753.76  4843.6 1755.59  4864.6 1755.58  4924.0 1752.11  4960.3 1751.47
  4992.6 1749.84  5005.9 1751.51  5035.5 1749.44  5035.9 1748.94  5040.7 1749.44
  5065.1 1752.43  5134.8 1754.07  5231.4 1752.75  5339.7 1753.87  5506.8 1755.07
  5563.6 1759.17  5578.1 1761.09  5620.9 1762.67  5674.7 1767.32  5693.1 1774.21
  5698.4 1773.75  5725.3 1779.58  5730.6 1778.88  5757.6 1782.31  5846.1 1784.79
#Mann=10,-1,0
  4370.1   0.035       0  4403.7    0.07       0  4924.0    0.16       0
  4960.3    0.07       0  5035.5    0.07       0  5040.7    0.07       0
  5339.7   0.035       0  5563.6    0.07       0  5578.1   0.035       0
  5620.9    0.07       0
Bank Sta=5035.5,5040.7
Exp/Cntr=0.3,0.1

Type RM Length L Ch R = 1,3363,580,580,580
BEGIN DESCRIPTION:
Mapping XS db786391
END DESCRIPTION:
XS GIS Cut Line= 3
      1527799.43      6870221.89      1527291.63      6869857.32
      1526265.15      6869620.77
#Sta/Elev= 30
  4370.3 1767.54  4461.9 1765.56  4533.2 1765.42  4612.1 1763.09  4634.3 1764.55
  4647.7 1762.77  4710.3 1761.90  4892.8 1757.47  4949.8 1753.90  4955.9 1752.38
  4970.7 1751.78  4999.6 1747.87  5000.0 1747.37  5004.9 1747.87  5016.1 1750.38
  5030.9 1750.51  5111.4 1750.69  5156.2 1750.52  5240.3 1753.70  5373.8 1751.87
  5623.1 1753.40  5710.3 1754.62  5825.0 1758.00  5874.5 1761.06  5925.8 1765.79
  5945.8 1771.37  5950.6 1771.76  5966.9 1776.29  6002.4 1779.68  6048.8 1783.75
#Mann=11,-1,0
  4370.3   0.045       0  4533.2   0.035       0  4710.3    0.07       0
  4999.6    0.07       0  5004.9    0.07       0  5030.9    0.16       0
  5111.4    0.07       0  5623.1   0.035       0  5825.0    0.07       0
  5945.8   0.035       0  6002.4    0.07       0
Bank Sta=4999.6,5004.9
Exp/Cntr=0.3,0.1

Type RM Length L Ch R = 1,2783,867,867,867
BEGIN DESCRIPTION:
Mapping XS dc6fc3ce
END DESCRIPTION:
XS GIS Cut Line= 3
      1528016.86      6869967.28      1527249.53      6869356.19
      1526431.15      6869092.64
#Sta/Elev= 30
  4045.4 1765.16  4239.0 1764.02  4323.9 1761.89  4382.9 1762.18  4423.2 1760.65
  4487.2 1761.16  4501.7 1759.46  4562.0 1758.31  4693.9 1754.06  4986.9 1748.73
  5031.3 1748.28  5049.4 1745.98  5049.8 1745.48  5054.8 1745.98  5068.6 1749.85
  5073.9 1750.01  5170.2 1748.90  5196.5 1749.07  5299.5 1749.81  5377.8 1749.53
  5402.6 1750.62  5624.3 1754.07  5703.5 1756.77  5745.5 1759.52  5777.0 1763.14
  5800.9 1768.98  5816.7 1772.54  5822.0 1774.99  5854.1 1781.03  5886.1 1782.16
#Mann=11,-1,0
  4045.4   0.045       0  4382.9   0.035       0  4562.0    0.07       0
  4986.9    0.16       0  5049.4    0.07       0  5054.8    0.16       0
  5170.2    0.07       0  5196.5   0.035       0  5299.5    0.07       0
  5402.6   0.035       0  5800.9    0.07       0
Bank Sta=5049.4,5054.8
Exp/Cntr=0.3,0.1

Type RM Length L Ch R = 1,1916,600,600,600
BEGIN DESCRIPTION:
Mapping XS 0751d8c1
END DESCRIPTION:
XS GIS Cut Line= 3
      1528162.69      6869738.09      1527402.30      6868731.19
      1526485.59      6868706.88
#Sta/Elev= 30
  3738.7 1762.50  3879.4 1762.31  3958.5 1760.21  4052.1 1760.88  4122.9 1759.12
  4253.5 1758.49  4315.2 1758.39  4343.6 1756.71  4365.4 1757.83  4393.5 1755.60
  4461.3 1755.37  4593.3 1753.57  4678.7 1750.79  4936.7 1746.94  4951.3 1746.27
  4969.4 1742.96  4969.8 1742.46  4974.9 1742.96  4986.7 1743.39  4992.9 1744.79
  5047.8 1746.92  5177.8 1746.42  5651.6 1752.65  5758.0 1755.29  5798.0 1757.14
  5808.6 1758.74  5838.1 1760.03  5858.1 1762.57  5908.1 1775.95  5917.5 1777.51
#Mann=7,-1,0
  3738.7   0.045       0  4253.5   0.035       0  4461.3    0.07       0
  4969.4    0.07       0  4974.9    0.07       0  5651.6   0.035       0
  5808.6    0.07       0
Bank Sta=4969.4,4974.9
Exp/Cntr=0.3,0.1

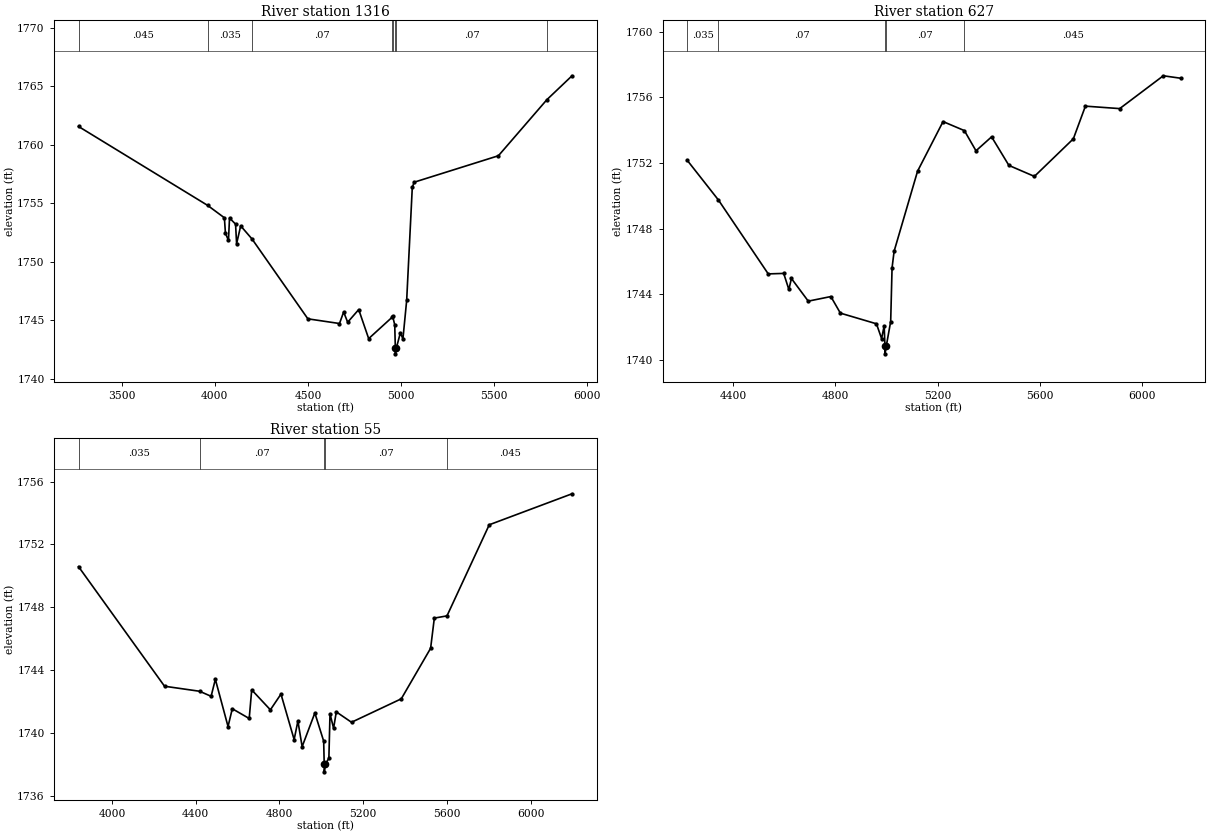
Type RM Length L Ch R = 1,1316,689,689,689
BEGIN DESCRIPTION:
Mapping XS f88eea44
END DESCRIPTION:
XS GIS Cut Line= 4
      1528252.99      6869630.48      1527579.39      6868383.97
      1527308.55      6868231.19      1526391.86      6868137.44
#Sta/Elev= 30
  3268.1 1761.57  3961.1 1754.83  4051.1 1753.77  4056.8 1752.44  4073.0 1751.84
  4078.7 1753.75  4111.1 1753.23  4116.7 1751.56  4138.6 1753.08  4199.5 1751.96
  4499.3 1745.14  4669.0 1744.74  4691.3 1745.72  4713.0 1744.85  4772.2 1745.93
  4825.7 1743.45  4951.2 1745.27  4954.0 1745.39  4965.6 1744.63  4968.8 1742.65
  4969.2 1742.15  4974.4 1742.65  4995.9 1743.95  5009.6 1743.43  5029.7 1746.72
  5059.8 1756.36  5069.9 1756.81  5522.2 1759.07  5782.5 1763.86  5917.4 1765.90
#Mann=8,-1,0
  3268.1   0.045       0  3961.1   0.035       0  4199.5    0.07       0
  4951.2   0.035       0  4954.0    0.07       0  4968.8    0.07       0
  4974.4    0.07       0  5782.5   0.035       0
Bank Sta=4968.8,4974.4
Exp/Cntr=0.3,0.1

Type RM Length L Ch R = 1,627,572,572,572
BEGIN DESCRIPTION:
Mapping XS 2610fa03
END DESCRIPTION:
XS GIS Cut Line= 3
      1527855.06      6868802.48      1527764.78      6868031.60
      1526705.77      6867576.75
#Sta/Elev= 30
  4221.6 1752.16  4343.6 1749.74  4538.2 1745.24  4598.6 1745.27  4618.8 1744.29
  4628.8 1744.96  4694.6 1743.58  4782.9 1743.86  4820.1 1742.85  4961.1 1742.20
  4981.2 1741.30  4991.3 1742.08  4994.2 1740.87  4994.7 1740.37  4999.8 1740.87
  5016.7 1742.34  5022.1 1745.61  5030.1 1746.62  5121.8 1751.50  5221.4 1754.52
  5304.7 1753.97  5350.1 1752.74  5411.1 1753.59  5478.7 1751.85  5578.4 1751.18
  5730.6 1753.47  5777.7 1755.46  5911.8 1755.31  6082.1 1757.31  6150.3 1757.16
#Mann=5,-1,0
  4221.6   0.035       0  4343.6    0.07       0  4994.2    0.07       0
  4999.8    0.07       0  5304.7   0.045       0
Bank Sta=4994.2,4999.8
Exp/Cntr=0.3,0.1

Type RM Length L Ch R = 1,55,0,0,0
BEGIN DESCRIPTION:
MULBERRY CREEK TRIBUTARY 15_1 1.0
END DESCRIPTION:
XS GIS Cut Line= 3
      1527878.28      6868734.29      1528049.63      6867587.22
      1526930.01      6867163.00
#Sta/Elev= 30
  3840.2 1750.59  4251.0 1742.99  4418.7 1742.67  4473.4 1742.35  4493.7 1743.43
  4554.3 1740.43  4574.6 1741.56  4655.4 1740.94  4667.3 1742.76  4756.5 1741.49
  4807.1 1742.49  4870.0 1739.60  4888.0 1740.78  4908.2 1739.15  4968.9 1741.29
  5011.1 1739.50  5013.6 1738.05  5014.1 1737.55  5019.3 1738.05  5035.9 1738.41
  5041.3 1741.24  5058.4 1740.32  5071.4 1741.36  5144.0 1740.70  5381.7 1742.19
  5521.8 1745.40  5539.6 1747.32  5600.0 1747.46  5801.9 1753.25  6197.3 1755.22
#Mann=5,-1,0
  3840.2   0.035       0  4418.7    0.07       0  5013.6    0.07       0
  5019.3    0.07       0  5600.0   0.045       0
Bank Sta=5013.6,5019.3
Exp/Cntr=0.3,0.1

Chan Stop Cuts=-1