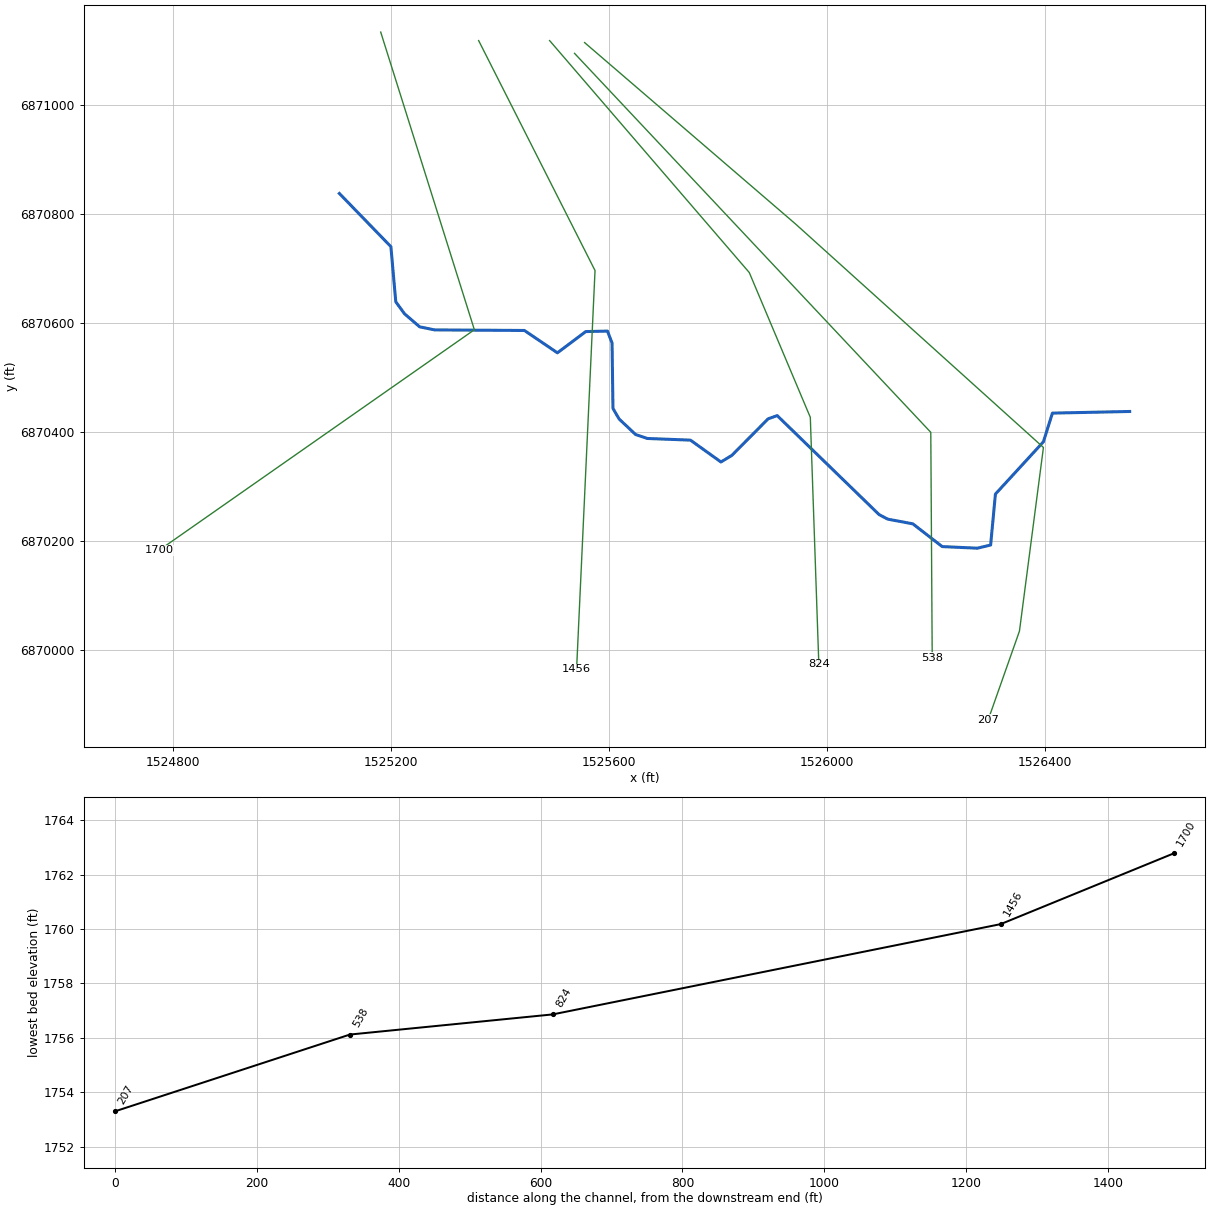
--- MULBERRY CREEK TRIBUTARY 15_1_1.prj (project) ---

Proj Title=MULBERRY CREEK TRIBUTARY 15_1_1 Base Level Engineering
Current Plan=p01
Default Exp/Contr=0.3,0.1
English Units
Geom File=g01
Flow File=f01
Plan File=p01
Y Axis Title=Elevation
X Axis Title(PF)=Main Channel Distance
X Axis Title(XS)=Station
BEGIN DESCRIPTION:
MULBERRY CREEK TRIBUTARY 15_1_1
END DESCRIPTION:
DSS Export Rating Curves= 0
DSS Export Rating Curve Sorted= 0
DSS Export Volume Flow Curves= 0
DXF OffsetX= 0
DXF OffsetY= 0
DXF ScaleX= 1
DXF ScaleY= 10

--- MULBERRY CREEK TRIBUTARY 15_1_1.p01 (plan) ---

Plan Title=Multiple Run
Short Identifier=Multiple
Geom File=g01
Flow File=f01
Subcritical Flow
K Sum by GR= 0
Std Step Tol= 0.01
Critical Tol= 0.01
Num of Std Step Trials= 20
Max Error Tol= 0.3
Flow Tol Ratio= 0.001
Split Flow NTrial= 30
Split Flow Tol= 0.02
Split Flow Ratio= 0.02
Log Output Level= 0
Friction Slope Method= 1
Unsteady Friction Slope Method= 2
Unsteady Bridges Friction Slope Method= 1
Parabolic Critical Depth
Global Vel Dist=  1 , 1 , 1
Global Log Level= 0
CheckData=True
Encroach Param= -1, 0, 0, 0
BEGIN DESCRIPTION:
Multiple Run
END DESCRIPTION:

--- MULBERRY CREEK TRIBUTARY 15_1_1.f01 (steady flow) ---

Flow Title=Multiple
Program Version=4.10
Number of Profiles= 7
Profile Names=10-year,25-year,50-year,1pct_min,100-year,1pct_plu,500-year
River Rch & RM=MULBERRY CREEK T,Reach-1         ,1700
     168     228     276     166     332     663     488
Boundary for River Rch & Prof#=MULBERRY CREEK T,Reach-1         , 1
Up Type= 0
Dn Type= 3
Dn Slope=0.00858
Boundary for River Rch & Prof#=MULBERRY CREEK T,Reach-1         , 2
Up Type= 0
Dn Type= 3
Dn Slope=0.00858
Boundary for River Rch & Prof#=MULBERRY CREEK T,Reach-1         , 3
Up Type= 0
Dn Type= 3
Dn Slope=0.00858
Boundary for River Rch & Prof#=MULBERRY CREEK T,Reach-1         , 4
Up Type= 0
Dn Type= 3
Dn Slope=0.00858
Boundary for River Rch & Prof#=MULBERRY CREEK T,Reach-1         , 5
Up Type= 0
Dn Type= 3
Dn Slope=0.00858
Boundary for River Rch & Prof#=MULBERRY CREEK T,Reach-1         , 6
Up Type= 0
Dn Type= 3
Dn Slope=0.00858
Boundary for River Rch & Prof#=MULBERRY CREEK T,Reach-1         , 7
Up Type= 0
Dn Type= 3
Dn Slope=0.00858
DSS Import GetInterval= 0
DSS Import GetPeak= 0
DSS Import FillOption= 0

--- MULBERRY CREEK TRIBUTARY 15_1_1.g01 (geometry) ---

Geom Title=Existing Conditions

River Reach=MULBERRY CREEK T,Reach-1
Reach XY= 30
      1525105.00      6870838.00      1525199.54      6870740.45
      1525208.51      6870639.25      1525224.42      6870617.35
      1525252.26      6870593.34      1525279.78      6870587.67
      1525444.56      6870586.62      1525505.04      6870545.61
      1525557.09      6870584.61      1525596.89      6870585.49
      1525605.30      6870563.60      1525606.99      6870443.66
      1525618.20      6870424.27      1525648.50      6870395.72
      1525670.08      6870388.46      1525749.10      6870385.43
      1525805.10      6870345.34      1525825.03      6870357.38
      1525891.67      6870424.54      1525908.33      6870430.39
      1526095.32      6870248.76      1526111.03      6870240.49
      1526157.17      6870231.85      1526211.06      6870190.10
      1526275.49      6870187.16      1526299.89      6870192.96
      1526308.66      6870286.42      1526396.68      6870382.30
      1526413.25      6870434.99      1526555.00      6870438.00

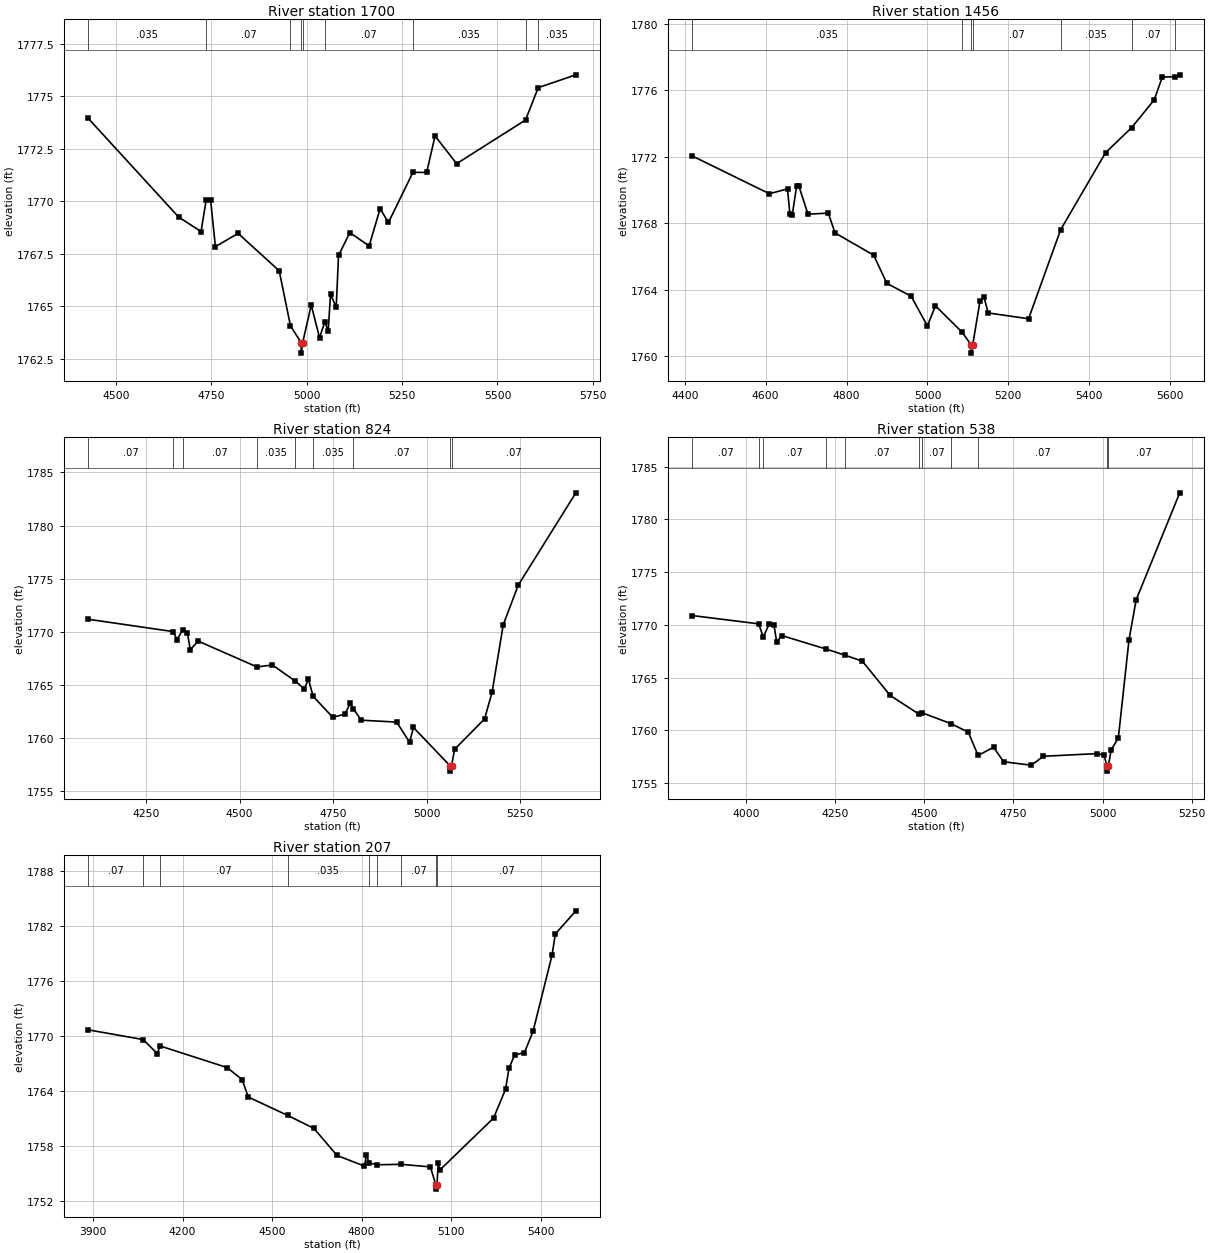
Type RM Length L Ch R = 1,1700,244,244,244
BEGIN DESCRIPTION:
MULBERRY CREEK TRIBUTARY 15_1_1 1.0
END DESCRIPTION:
XS GIS Cut Line= 3
      1525180.87      6871134.05      1525352.70      6870587.95
      1524774.60      6870183.57
#Sta/Elev= 30
  4427.5 1773.96  4664.5 1769.26  4723.3 1768.57  4736.9 1770.09  4748.3 1770.07
  4760.9 1767.85  4820.4 1768.48  4928.1 1766.70  4957.6 1764.08  4985.6 1763.28
  4985.9 1762.78  4989.6 1763.28  5012.1 1765.07  5033.8 1763.51  5047.8 1764.28
  5056.5 1763.83  5062.6 1765.59  5077.5 1764.96  5083.6 1767.43  5113.2 1768.52
  5163.8 1767.88  5192.5 1769.66  5214.4 1769.00  5278.6 1771.39  5314.5 1771.38
  5336.5 1773.12  5393.1 1771.80  5573.7 1773.88  5606.9 1775.42  5705.5 1776.03
#Mann=9,-1,0
  4427.5   0.035       0  4736.9    0.07       0  4957.6   0.035       0
  4985.6   0.035       0  4989.6   0.035       0  5047.8    0.07       0
  5278.6   0.035       0  5573.7    0.07       0  5606.9   0.035       0
Bank Sta=4985.6,4989.6
Exp/Cntr=0.3,0.1

Type RM Length L Ch R = 1,1456,632,632,632
BEGIN DESCRIPTION:
MULBERRY CREEK TRIBUTARY 15_1_1 0.6
END DESCRIPTION:
XS GIS Cut Line= 3
      1525360.54      6871118.48      1525574.08      6870696.59
      1525540.23      6869964.83
#Sta/Elev= 30
  4418.2 1772.06  4609.3 1769.78  4654.1 1770.07  4660.1 1768.54  4665.8 1768.49
  4676.5 1770.22  4682.4 1770.23  4704.7 1768.55  4755.0 1768.61  4771.5 1767.42
  4867.1 1766.08  4899.7 1764.38  4959.7 1763.61  4999.8 1761.82  5019.8 1763.03
  5086.1 1761.43  5107.9 1760.68  5108.1 1760.18  5111.9 1760.68  5129.9 1763.32
  5139.9 1763.56  5149.9 1762.60  5250.0 1762.25  5329.0 1767.60  5440.2 1772.25
  5504.7 1773.76  5560.4 1775.43  5580.4 1776.80  5611.5 1776.83  5623.6 1776.94
#Mann=7,-1,0
  4418.2   0.035       0  5086.1    0.07       0  5107.9   0.035       0
  5111.9    0.07       0  5329.0   0.035       0  5504.7    0.07       0
  5611.5   0.035       0
Bank Sta=5107.9,5111.9
Exp/Cntr=0.3,0.1

Type RM Length L Ch R = 1,824,286,286,286
BEGIN DESCRIPTION:
MULBERRY CREEK TRIBUTARY 15_1_1 0.7
END DESCRIPTION:
XS GIS Cut Line= 4
      1525490.76      6871118.46      1525857.07      6870692.91
      1525969.05      6870427.28      1525984.68      6869974.11
#Sta/Elev= 30
  4095.2 1771.17  4321.7 1770.01  4333.0 1769.25  4348.1 1770.20  4360.5 1769.85
  4368.1 1768.29  4389.0 1769.11  4546.2 1766.68  4587.6 1766.86  4647.9 1765.36
  4672.9 1764.60  4683.7 1765.53  4696.3 1763.91  4748.8 1761.93  4781.4 1762.23
  4795.3 1763.25  4803.9 1762.74  4824.8 1761.66  4919.4 1761.48  4954.3 1759.58
  4964.3 1760.98  5062.3 1757.36  5062.6 1756.86  5066.3 1757.36  5074.3 1758.91
  5154.4 1761.78  5174.4 1764.27  5204.4 1770.65  5244.4 1774.38  5398.4 1783.08
#Mann=9,-1,0
  4095.2    0.07       0  4321.7   0.035       0  4348.1    0.07       0
  4546.2   0.035       0  4647.9    0.07       0  4696.3   0.035       0
  4803.9    0.07       0  5062.3    0.07       0  5066.3    0.07       0
Bank Sta=5062.3,5066.3
Exp/Cntr=0.3,0.1

Type RM Length L Ch R = 1,538,331,331,331
BEGIN DESCRIPTION:
Mapping XS c6b61ded
END DESCRIPTION:
XS GIS Cut Line= 3
      1525536.47      6871095.05      1526190.10      6870399.75
      1526192.71      6869985.65
#Sta/Elev= 30
  3848.1 1770.88  4035.2 1770.09  4047.8 1768.84  4064.1 1770.05  4078.2 1769.94
  4085.5 1768.37  4099.7 1768.98  4223.3 1767.71  4278.1 1767.11  4325.9 1766.55
  4404.0 1763.30  4484.1 1761.54  4493.8 1761.65  4575.7 1760.61  4623.3 1759.81
  4650.6 1757.61  4694.1 1758.38  4722.4 1757.01  4800.1 1756.68  4834.1 1757.53
  4984.1 1757.78  5004.1 1757.64  5012.1 1756.62  5012.4 1756.12  5016.1 1756.62
  5024.2 1758.14  5044.2 1759.26  5074.2 1768.60  5094.2 1772.37  5216.5 1782.52
#Mann=11,-1,0
  3848.1    0.07       0  4035.2   0.035       0  4047.8    0.07       0
  4223.3   0.035       0  4278.1    0.07       0  4484.1   0.035       0
  4493.8    0.07       0  4575.7   0.035       0  4650.6    0.07       0
  5012.1    0.07       0  5016.1    0.07       0
Bank Sta=5012.1,5016.1
Exp/Cntr=0.3,0.1

Type RM Length L Ch R = 1,207,0,0,0
BEGIN DESCRIPTION:
MULBERRY CREEK TRIBUTARY 15_1_1 0.8
END DESCRIPTION:
XS GIS Cut Line= 5
      1525554.96      6871114.80      1525942.07      6870781.90
      1526396.74      6870371.96      1526352.78      6870035.05
      1526295.54      6869872.66
#Sta/Elev= 30
  3883.5 1770.70  4067.4 1769.64  4115.3 1768.11  4124.2 1768.94  4349.1 1766.58
  4399.4 1765.27  4420.2 1763.36  4552.2 1761.35  4640.0 1759.94  4717.7 1756.98
  4809.6 1755.81  4816.3 1757.07  4824.8 1756.17  4852.6 1755.96  4931.8 1756.01
  5030.4 1755.73  5048.6 1753.80  5048.8 1753.30  5052.6 1753.80  5057.0 1756.10
  5062.0 1755.38  5242.2 1761.06  5282.5 1764.20  5293.9 1766.48  5312.8 1767.94
  5346.0 1768.22  5374.7 1770.54  5438.3 1778.85  5449.4 1781.17  5518.2 1783.70
#Mann=9,-1,0
  3883.5    0.07       0  4067.4   0.035       0  4124.2    0.07       0
  4552.2   0.035       0  4824.8    0.07       0  4852.6   0.035       0
  4931.8    0.07       0  5048.6    0.07       0  5052.6    0.07       0
Bank Sta=5048.6,5052.6
Exp/Cntr=0.3,0.1

Chan Stop Cuts=-1