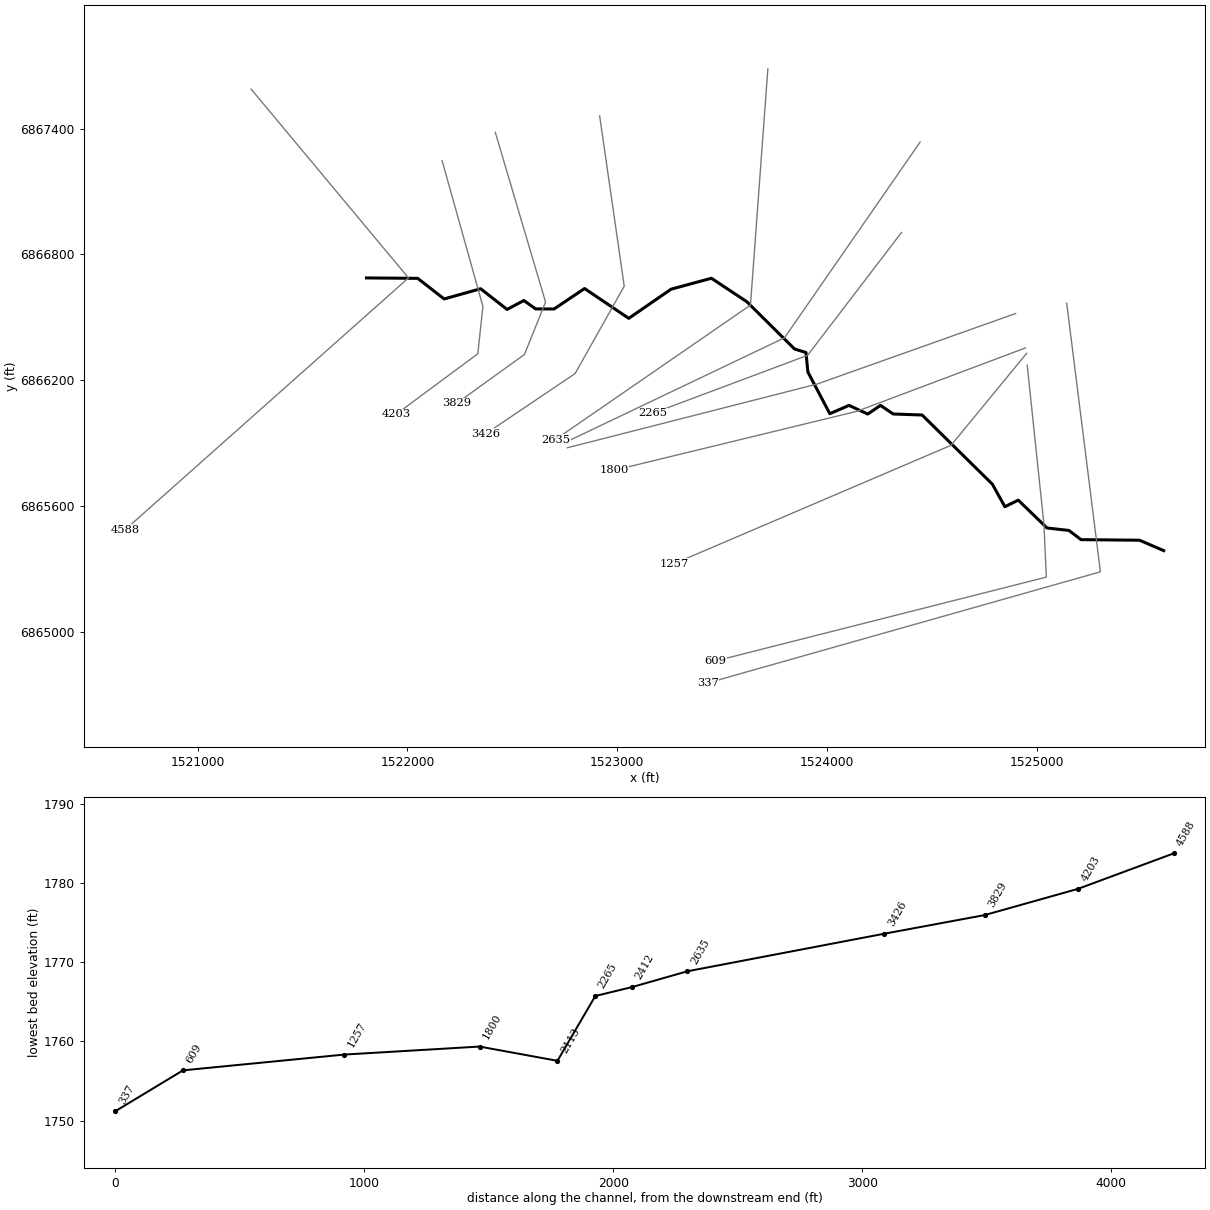
--- MULBERRY CREEK TRIBUTARY 15_2.prj (project) ---

Proj Title=MULBERRY CREEK TRIBUTARY 15_2 Base Level Engineering
Current Plan=p01
Default Exp/Contr=0.3,0.1
English Units
Geom File=g01
Flow File=f01
Plan File=p01
BEGIN DESCRIPTION:
MULBERRY CREEK TRIBUTARY 15_2
END DESCRIPTION:

--- MULBERRY CREEK TRIBUTARY 15_2.p01 (plan) ---

Plan Title=Multiple Run
Short Identifier=Multiple
Geom File=g01
Flow File=f01
Subcritical Flow
K Sum by GR= 0
Std Step Tol= 0.01
Critical Tol= 0.01
Num of Std Step Trials= 20
Max Error Tol= 0.3
Flow Tol Ratio= 0.001
Split Flow NTrial= 30
Split Flow Tol= 0.02
Split Flow Ratio= 0.02
Log Output Level= 0
Friction Slope Method= 1
Unsteady Friction Slope Method= 2
Unsteady Bridges Friction Slope Method= 1
Parabolic Critical Depth
Global Vel Dist=  1 , 1 , 1
Global Log Level= 0
CheckData=True
Encroach Param= -1, 0, 0, 0
BEGIN DESCRIPTION:
Multiple Run
END DESCRIPTION:

--- MULBERRY CREEK TRIBUTARY 15_2.f01 (steady flow) ---

Flow Title=Multiple
Number of Profiles=7
Profile Names=10-year,25-year,50-year,1pct_min,100-year,1pct_plu,500-year
River Rch & RM= MULBERRY CREEK T,Reach-1,4588
     174     237     289     176     351     700     523
Boundary for River Rch & Prof#=MULBERRY CREEK T,Reach-1,1
Up Type=0
Dn Type=3
Dn Slope=0.005
Boundary for River Rch & Prof#=MULBERRY CREEK T,Reach-1,2
Up Type=0
Dn Type=3
Dn Slope=0.005
Boundary for River Rch & Prof#=MULBERRY CREEK T,Reach-1,3
Up Type=0
Dn Type=3
Dn Slope=0.005
Boundary for River Rch & Prof#=MULBERRY CREEK T,Reach-1,4
Up Type=0
Dn Type=3
Dn Slope=0.005
Boundary for River Rch & Prof#=MULBERRY CREEK T,Reach-1,5
Up Type=0
Dn Type=3
Dn Slope=0.005
Boundary for River Rch & Prof#=MULBERRY CREEK T,Reach-1,6
Up Type=0
Dn Type=3
Dn Slope=0.005
Boundary for River Rch & Prof#=MULBERRY CREEK T,Reach-1,7
Up Type=0
Dn Type=3
Dn Slope=0.005

--- MULBERRY CREEK TRIBUTARY 15_2.g01 (geometry) ---

Geom Title=Existing Conditions

River Reach=MULBERRY CREEK T,Reach-1
Reach XY= 30
      1521805.00      6866688.00      1522049.14      6866685.94
      1522175.05      6866587.79      1522348.96      6866636.37
      1522475.16      6866537.68      1522554.99      6866580.40
      1522610.90      6866540.36      1522699.10      6866539.98
      1522844.36      6866637.44      1523055.08      6866495.30
      1523256.58      6866634.18      1523448.96      6866686.37
      1523618.21      6866574.37      1523845.62      6866348.90
      1523899.74      6866332.53      1523908.86      6866239.66
      1524013.48      6866040.66      1524104.97      6866080.36
      1524194.36      6866038.98      1524254.99      6866080.41
      1524315.44      6866039.39      1524453.53      6866034.46
      1524788.35      6865704.65      1524848.05      6865597.19
      1524911.66      6865628.69      1525048.83      6865495.86
      1525153.40      6865484.14      1525210.94      6865440.26
      1525489.81      6865437.55      1525605.00      6865388.00

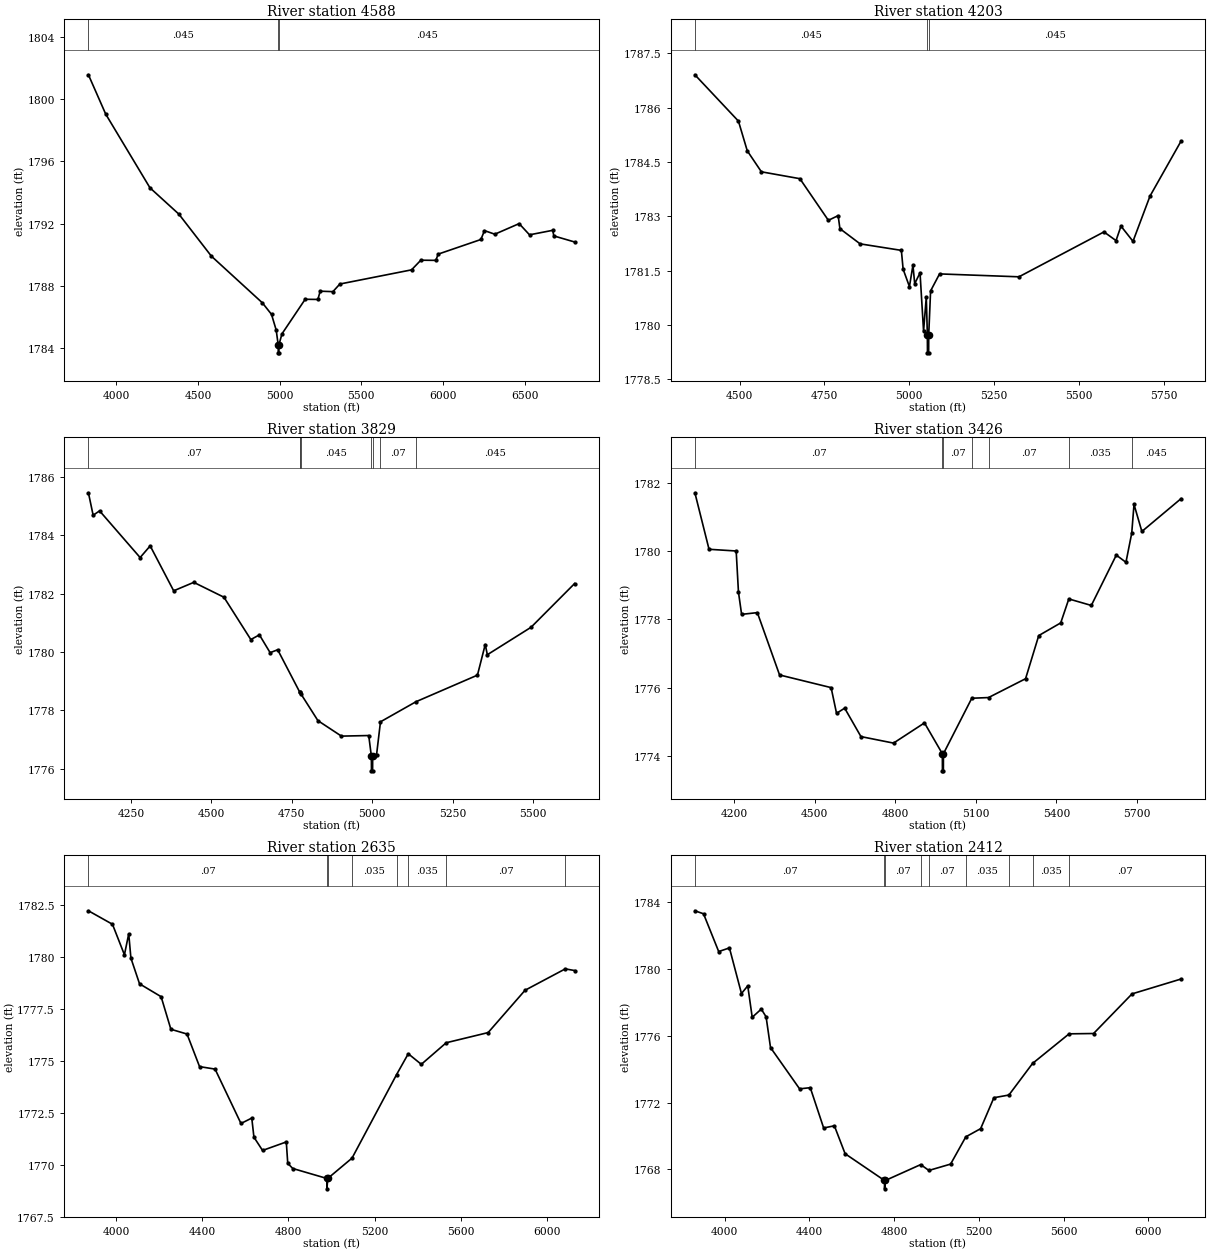
Type RM Length L Ch R = 1,4588,385,385,385
BEGIN DESCRIPTION:
MULBERRY CREEK TRIBUTARY 15_2 8.0
END DESCRIPTION:
XS GIS Cut Line= 3
      1521254.98      6867588.02      1522005.00      6866688.00
      1520655.00      6865488.00
#Sta/Elev= 30
  3829.0 1801.57  3935.1 1799.04  4205.9 1794.31  4382.9 1792.62  4582.1 1789.92
  4894.5 1786.92  4950.4 1786.18  4979.1 1785.17  4991.4 1784.21  4991.7 1783.71
  4995.2 1783.71  4995.4 1784.21  5014.4 1784.93  5156.5 1787.15  5234.3 1787.14
  5248.5 1787.67  5326.3 1787.64  5368.9 1788.13  5807.9 1789.04  5864.8 1789.66
  5956.8 1789.65  5971.0 1790.05  6232.7 1790.99  6254.5 1791.56  6318.0 1791.33
  6466.9 1792.01  6530.4 1791.29  6672.6 1791.58  6679.3 1791.22  6806.8 1790.83
#Mann=3,-1,0
  3829.0   0.045       0  4991.4   0.045       0  4995.4   0.045       0
Bank Sta=4991.4,4995.4
Exp/Cntr=0.3,0.1

Type RM Length L Ch R = 1,4203,374,374,374
BEGIN DESCRIPTION:
Mapping XS 120e5194
END DESCRIPTION:
XS GIS Cut Line= 4
      1522165.44      6867246.63      1522359.88      6866552.20
      1522335.58      6866326.50      1521946.67      6866038.29
#Sta/Elev= 30
  4368.3 1786.91  4496.6 1785.63  4522.6 1784.81  4564.2 1784.23  4677.6 1784.04
  4761.5 1782.89  4790.3 1783.02  4795.5 1782.66  4855.0 1782.24  4976.5 1782.06
  4981.7 1781.54  5000.3 1781.06  5010.6 1781.65  5015.8 1781.14  5031.5 1781.44
  5041.9 1779.83  5049.9 1780.77  5053.1 1779.73  5053.4 1779.23  5056.9 1779.23
  5057.1 1779.73  5062.6 1780.94  5089.0 1781.41  5322.9 1781.33  5573.3 1782.57
  5608.8 1782.33  5623.4 1782.73  5658.8 1782.31  5708.9 1783.56  5800.5 1785.08
#Mann=3,-1,0
  4368.3   0.045       0  5053.1   0.045       0  5057.1   0.045       0
Bank Sta=5053.1,5057.1
Exp/Cntr=0.3,0.1

Type RM Length L Ch R = 1,3829,403,403,403
BEGIN DESCRIPTION:
Mapping XS c688e3a3
END DESCRIPTION:
XS GIS Cut Line= 4
      1522418.91      6867382.05      1522658.49      6866573.03
      1522557.80      6866323.03      1522234.85      6866090.37
#Sta/Elev= 30
  4117.7 1785.46  4132.4 1784.69  4152.4 1784.84  4278.4 1783.24  4309.7 1783.64
  4382.7 1782.10  4445.2 1782.39  4539.0 1781.88  4622.5 1780.43  4649.2 1780.59
  4682.5 1779.98  4706.0 1780.08  4774.9 1778.62  4775.0 1778.62  4778.6 1778.56
  4831.1 1777.65  4904.1 1777.12  4989.0 1777.14  4997.2 1776.43  4997.5 1775.93
  5001.0 1775.93  5001.2 1776.43  5013.2 1776.47  5025.5 1777.61  5136.1 1778.30
  5326.9 1779.21  5351.1 1780.26  5357.7 1779.91  5493.5 1780.85  5629.0 1782.35
#Mann=8,-1,0
  4117.7    0.07       0  4774.9   0.045       0  4775.0    0.07       0
  4778.6   0.045       0  4997.2   0.045       0  5001.2   0.045       0
  5025.5    0.07       0  5136.1   0.045       0
Bank Sta=4997.2,5001.2
Exp/Cntr=0.3,0.1

Type RM Length L Ch R = 1,3426,791,791,791
BEGIN DESCRIPTION:
Mapping XS e34376b0
END DESCRIPTION:
XS GIS Cut Line= 4
      1522916.30      6867460.20      1523033.49      6866648.55
      1522799.12      6866231.88      1522373.81      6865945.45
#Sta/Elev= 30
  4053.8 1781.70  4106.5 1780.05  4207.6 1780.00  4216.1 1778.80  4227.8 1778.15
  4286.5 1778.20  4369.2 1776.38  4561.2 1776.01  4581.4 1775.26  4611.7 1775.41
  4672.3 1774.58  4793.6 1774.39  4908.9 1774.98  4975.5 1774.08  4975.8 1773.58
  4979.3 1773.58  4979.5 1774.08  5085.1 1775.70  5147.5 1775.72  5285.4 1776.27
  5334.5 1777.53  5416.3 1777.90  5446.5 1778.60  5530.3 1778.41  5623.3 1779.88
  5659.3 1779.67  5680.8 1780.52  5689.3 1781.36  5718.6 1780.57  5864.7 1781.53
#Mann=7,-1,0
  4053.8    0.07       0  4975.5    0.07       0  4979.5    0.07       0
  5085.1   0.045       0  5147.5    0.07       0  5446.5   0.035       0
  5680.8   0.045       0
Bank Sta=4975.5,4979.5
Exp/Cntr=0.3,0.1

Type RM Length L Ch R = 1,2635,223,223,223
BEGIN DESCRIPTION:
MULBERRY CREEK TRIBUTARY 15_2 4.0
END DESCRIPTION:
XS GIS Cut Line= 3
      1523718.18      6867684.83      1523635.16      6866558.38
      1522705.37      6865917.43
#Sta/Elev= 30
  3870.5 1782.24  3982.2 1781.59  4037.8 1780.12  4057.8 1781.13  4067.9 1779.96
  4108.0 1778.72  4208.2 1778.10  4253.6 1776.53  4328.6 1776.30  4386.8 1774.73
  4458.9 1774.61  4579.2 1771.99  4629.4 1772.25  4639.4 1771.33  4679.5 1770.69
  4789.8 1771.10  4796.5 1770.07  4819.9 1769.82  4978.3 1769.34  4978.6 1768.84
  4982.3 1769.34  5095.1 1770.32  5302.3 1774.35  5356.4 1775.35  5417.0 1774.84
  5532.7 1775.88  5727.4 1776.37  5899.0 1778.41  6085.8 1779.44  6129.3 1779.36
#Mann=8,-1,0
  3870.5    0.07       0  4978.3    0.07       0  4982.3    0.07       0
  5095.1   0.035       0  5302.3    0.07       0  5356.4   0.035       0
  5532.7    0.07       0  6085.8   0.035       0
Bank Sta=4978.3,4982.3
Exp/Cntr=0.3,0.1

Type RM Length L Ch R = 1,2412,147,147,147
BEGIN DESCRIPTION:
Mapping XS 09e5f552
END DESCRIPTION:
XS GIS Cut Line= 3
      1524443.90      6867335.52      1523797.22      6866402.40
      1522751.21      6865903.27
#Sta/Elev= 30
  3859.6 1783.47  3900.4 1783.29  3972.0 1781.03  4022.6 1781.25  4079.4 1778.52
  4109.1 1778.98  4130.1 1777.10  4172.9 1777.59  4195.6 1777.13  4216.5 1775.29
  4353.7 1772.82  4404.1 1772.89  4467.2 1770.48  4517.8 1770.61  4568.5 1768.94
  4754.3 1767.34  4754.6 1766.84  4758.3 1767.34  4925.1 1768.29  4963.8 1767.94
  5066.3 1768.32  5138.0 1769.95  5208.0 1770.44  5270.5 1772.29  5341.3 1772.45
  5453.0 1774.34  5625.4 1776.11  5740.9 1776.13  5922.4 1778.50  6153.9 1779.39
#Mann=9,-1,0
  3859.6    0.07       0  4754.3    0.07       0  4758.3    0.07       0
  4925.1   0.035       0  4963.8    0.07       0  5138.0   0.035       0
  5341.3    0.07       0  5453.0   0.035       0  5625.4    0.07       0
Bank Sta=4754.3,4758.3
Exp/Cntr=0.3,0.1

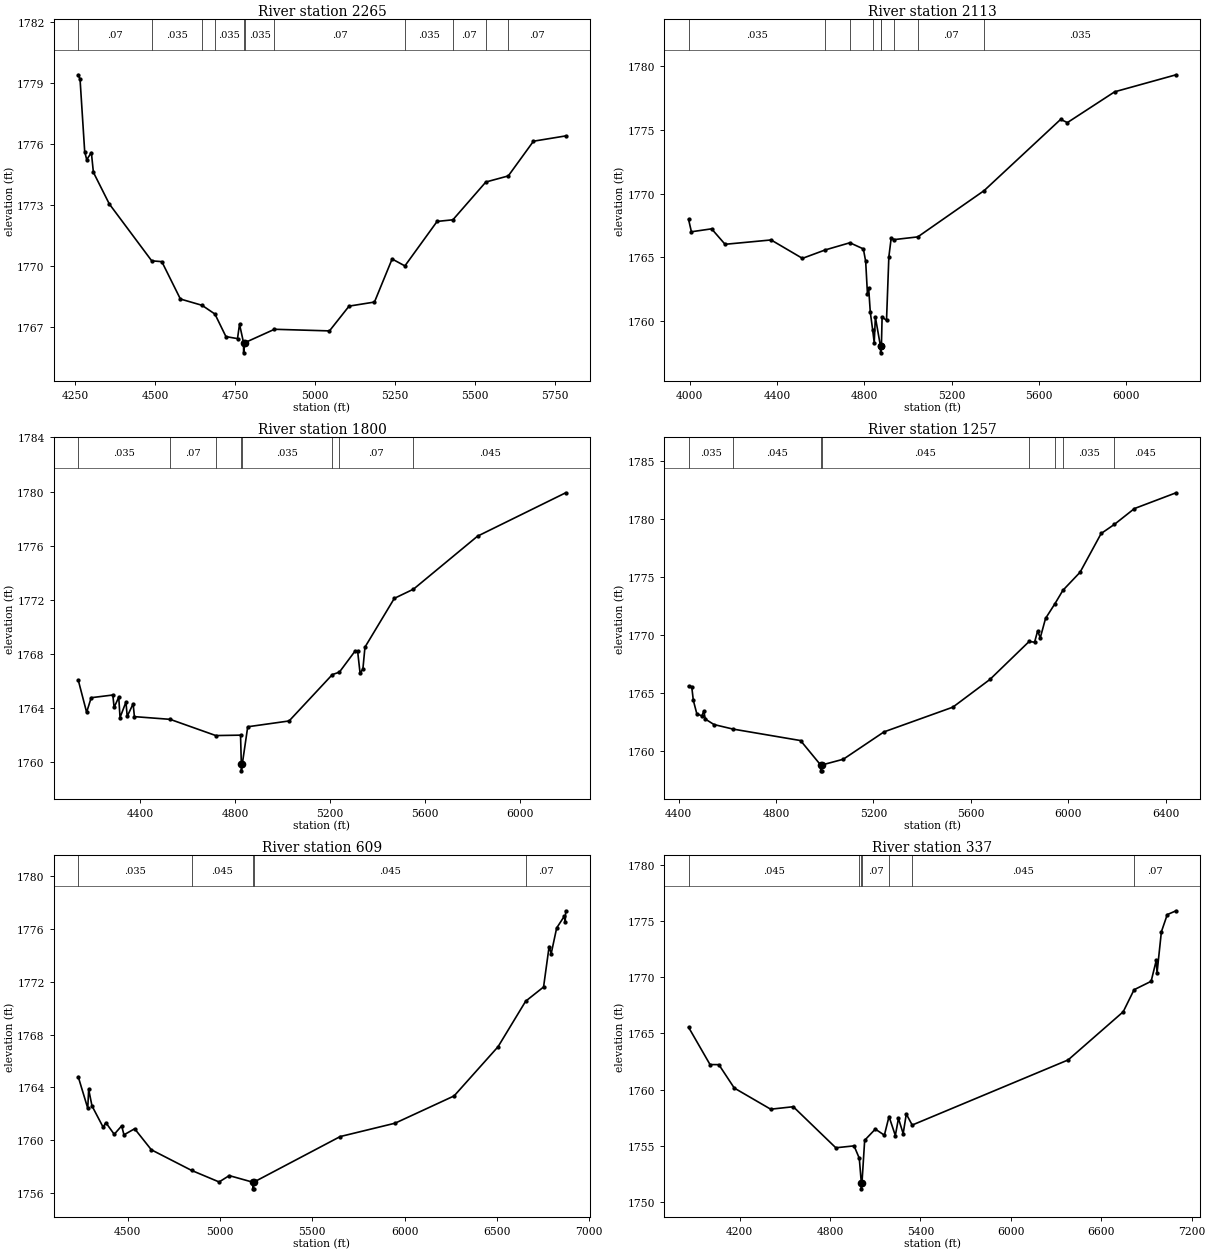
Type RM Length L Ch R = 1,2265,152,152,152
BEGIN DESCRIPTION:
Mapping XS 8d592815
END DESCRIPTION:
XS GIS Cut Line= 3
      1524355.44      6866904.96      1523907.49      6866318.98
      1523170.57      6866042.96
#Sta/Elev= 30
  4259.5 1779.41  4265.2 1779.19  4279.7 1775.63  4286.0 1775.23  4300.6 1775.58
  4306.9 1774.61  4356.7 1773.05  4489.3 1770.25  4520.9 1770.21  4579.0 1768.37
  4646.7 1768.06  4687.0 1767.63  4721.4 1766.52  4757.6 1766.42  4763.9 1767.13
  4776.5 1766.22  4776.7 1765.72  4780.5 1766.22  4873.2 1766.88  5045.2 1766.80
  5106.5 1768.02  5185.9 1768.22  5241.1 1770.34  5281.1 1770.00  5381.8 1772.19
  5431.2 1772.27  5534.2 1774.13  5604.4 1774.43  5683.2 1776.14  5784.0 1776.40
#Mann=11,-1,0
  4259.5    0.07       0  4489.3   0.035       0  4646.7    0.07       0
  4687.0   0.035       0  4776.5    0.07       0  4780.5   0.035       0
  4873.2    0.07       0  5281.1   0.035       0  5431.2    0.07       0
  5534.2   0.035       0  5604.4    0.07       0
Bank Sta=4776.5,4780.5
Exp/Cntr=0.3,0.1

Type RM Length L Ch R = 1,2113,313,313,313
BEGIN DESCRIPTION:
MULBERRY CREEK TRIBUTARY 15_2 3.0
END DESCRIPTION:
XS GIS Cut Line= 3
      1524899.19      6866518.35      1523952.30      6866181.88
      1522762.70      6865878.38
#Sta/Elev= 30
  3995.1 1767.97  4008.0 1767.01  4100.5 1767.24  4162.2 1766.03  4372.9 1766.37
  4516.5 1764.93  4621.0 1765.59  4733.8 1766.15  4795.5 1765.67  4806.1 1764.70
  4814.4 1762.11  4819.7 1762.63  4827.3 1760.72  4837.9 1759.36  4845.3 1758.34
  4850.6 1760.33  4874.1 1758.04  4874.4 1757.54  4878.1 1758.04  4881.4 1760.34
  4901.6 1760.08  4912.3 1765.05  4922.8 1766.49  4937.8 1766.40  5044.8 1766.61
  5348.7 1770.23  5699.0 1775.80  5730.0 1775.55  5946.7 1777.96  6227.7 1779.29
#Mann=9,-1,0
  3995.1   0.035       0  4621.0    0.07       0  4733.8   0.035       0
  4837.9    0.07       0  4874.1   0.035       0  4878.1    0.07       0
  4937.8   0.035       0  5044.8    0.07       0  5348.7   0.035       0
Bank Sta=4874.1,4878.1
Exp/Cntr=0.3,0.1

Type RM Length L Ch R = 1,1800,543,543,543
BEGIN DESCRIPTION:
MULBERRY CREEK TRIBUTARY 15_2 2.0
END DESCRIPTION:
XS GIS Cut Line= 3
      1524946.05      6866354.28      1524141.80      6866051.95
      1522984.66      6865770.81
#Sta/Elev= 30
  4140.8 1766.06  4176.1 1763.67  4195.3 1764.75  4286.3 1764.95  4291.7 1764.03
  4311.2 1764.79  4316.6 1763.28  4341.5 1764.43  4346.8 1763.37  4371.7 1764.30
  4377.0 1763.35  4527.1 1763.15  4719.3 1761.95  4823.4 1761.98  4826.7 1759.84
  4827.0 1759.34  4830.7 1759.84  4853.6 1762.60  5027.6 1763.03  5209.4 1766.46
  5239.0 1766.64  5305.4 1768.21  5315.7 1768.20  5326.0 1766.57  5337.9 1766.87
  5346.6 1768.49  5470.1 1772.10  5550.7 1772.78  5820.0 1776.70  6190.8 1779.91
#Mann=8,-1,0
  4140.8   0.035       0  4527.1    0.07       0  4719.3   0.035       0
  4826.7    0.07       0  4830.7   0.035       0  5209.4   0.045       0
  5239.0    0.07       0  5550.7   0.045       0
Bank Sta=4826.7,4830.7
Exp/Cntr=0.3,0.1

Type RM Length L Ch R = 1,1257,648,648,648
BEGIN DESCRIPTION:
Mapping XS 1c1889f4
END DESCRIPTION:
XS GIS Cut Line= 3
      1524951.74      6866328.62      1524591.50      6865890.25
      1523272.08      6865326.02
#Sta/Elev= 30
  4440.6 1765.61  4453.5 1765.59  4460.0 1764.41  4474.3 1763.26  4495.1 1763.06
  4503.0 1763.48  4509.5 1762.79  4545.0 1762.32  4622.9 1761.93  4900.5 1760.94
  4983.2 1758.83  4983.4 1758.33  4986.9 1758.33  4987.2 1758.83  5076.1 1759.33
  5243.5 1761.69  5526.2 1763.82  5678.5 1766.21  5839.4 1769.48  5861.8 1769.42
  5874.3 1770.38  5885.2 1769.80  5906.9 1771.47  5945.8 1772.75  5978.1 1773.89
  6048.7 1775.45  6135.3 1778.79  6190.0 1779.58  6272.0 1780.94  6443.0 1782.30
#Mann=8,-1,0
  4440.6   0.035       0  4622.9   0.045       0  4983.2   0.045       0
  4987.2   0.045       0  5839.4   0.035       0  5945.8    0.07       0
  5978.1   0.035       0  6190.0   0.045       0
Bank Sta=4983.2,4987.2
Exp/Cntr=0.3,0.1

Type RM Length L Ch R = 1,609,272,272,272
BEGIN DESCRIPTION:
Mapping XS bdcd7293
END DESCRIPTION:
XS GIS Cut Line= 4
      1524954.37      6866272.06      1525034.20      6865512.64
      1525045.51      6865261.69      1523468.71      6864861.94
#Sta/Elev= 30
  4231.8 1764.81  4283.4 1762.43  4288.4 1763.86  4306.3 1762.61  4366.6 1761.00
  4381.5 1761.34  4426.9 1760.46  4467.2 1761.10  4479.6 1760.42  4537.5 1760.88
  4628.0 1759.29  4846.4 1757.73  4995.2 1756.86  5050.1 1757.34  5178.2 1756.84
  5178.5 1756.34  5182.0 1756.34  5182.2 1756.84  5651.4 1760.29  5948.7 1761.30
  6268.5 1763.36  6506.8 1767.08  6656.4 1770.52  6753.3 1771.59  6783.4 1774.65
  6794.6 1774.11  6824.3 1776.05  6865.3 1776.93  6870.5 1776.48  6873.3 1777.35
#Mann=5,-1,0
  4231.8   0.035       0  4846.4   0.045       0  5178.2   0.045       0
  5182.2   0.045       0  6656.4    0.07       0
Bank Sta=5178.2,5182.2
Exp/Cntr=0.3,0.1

Type RM Length L Ch R = 1,337,0,0,0
BEGIN DESCRIPTION:
MULBERRY CREEK TRIBUTARY 15_2 1.0
END DESCRIPTION:
XS GIS Cut Line= 3
      1525142.71      6866567.34      1525303.30      6865286.95
      1523432.62      6864757.43
#Sta/Elev= 30
  3861.6 1765.54  4003.8 1762.23  4062.5 1762.22  4164.8 1760.14  4406.3 1758.26
  4556.3 1758.48  4838.5 1754.83  4959.5 1755.00  4994.3 1753.90  5007.9 1751.68
  5008.1 1751.18  5011.9 1751.68  5030.0 1755.50  5100.6 1756.49  5160.7 1755.95
  5191.5 1757.61  5233.4 1755.92  5254.2 1757.44  5285.4 1756.09  5306.2 1757.83
  5345.3 1756.85  6380.0 1762.64  6745.4 1766.92  6817.5 1768.88  6930.8 1769.63
  6964.7 1771.49  6969.9 1770.37  6998.7 1774.03  7037.8 1775.56  7096.2 1775.90
#Mann=7,-1,0
  3861.6   0.045       0  4994.3    0.07       0  5007.9    0.07       0
  5011.9    0.07       0  5191.5   0.035       0  5345.3   0.045       0
  6817.5    0.07       0
Bank Sta=5007.9,5011.9
Exp/Cntr=0.3,0.1

Chan Stop Cuts=-1