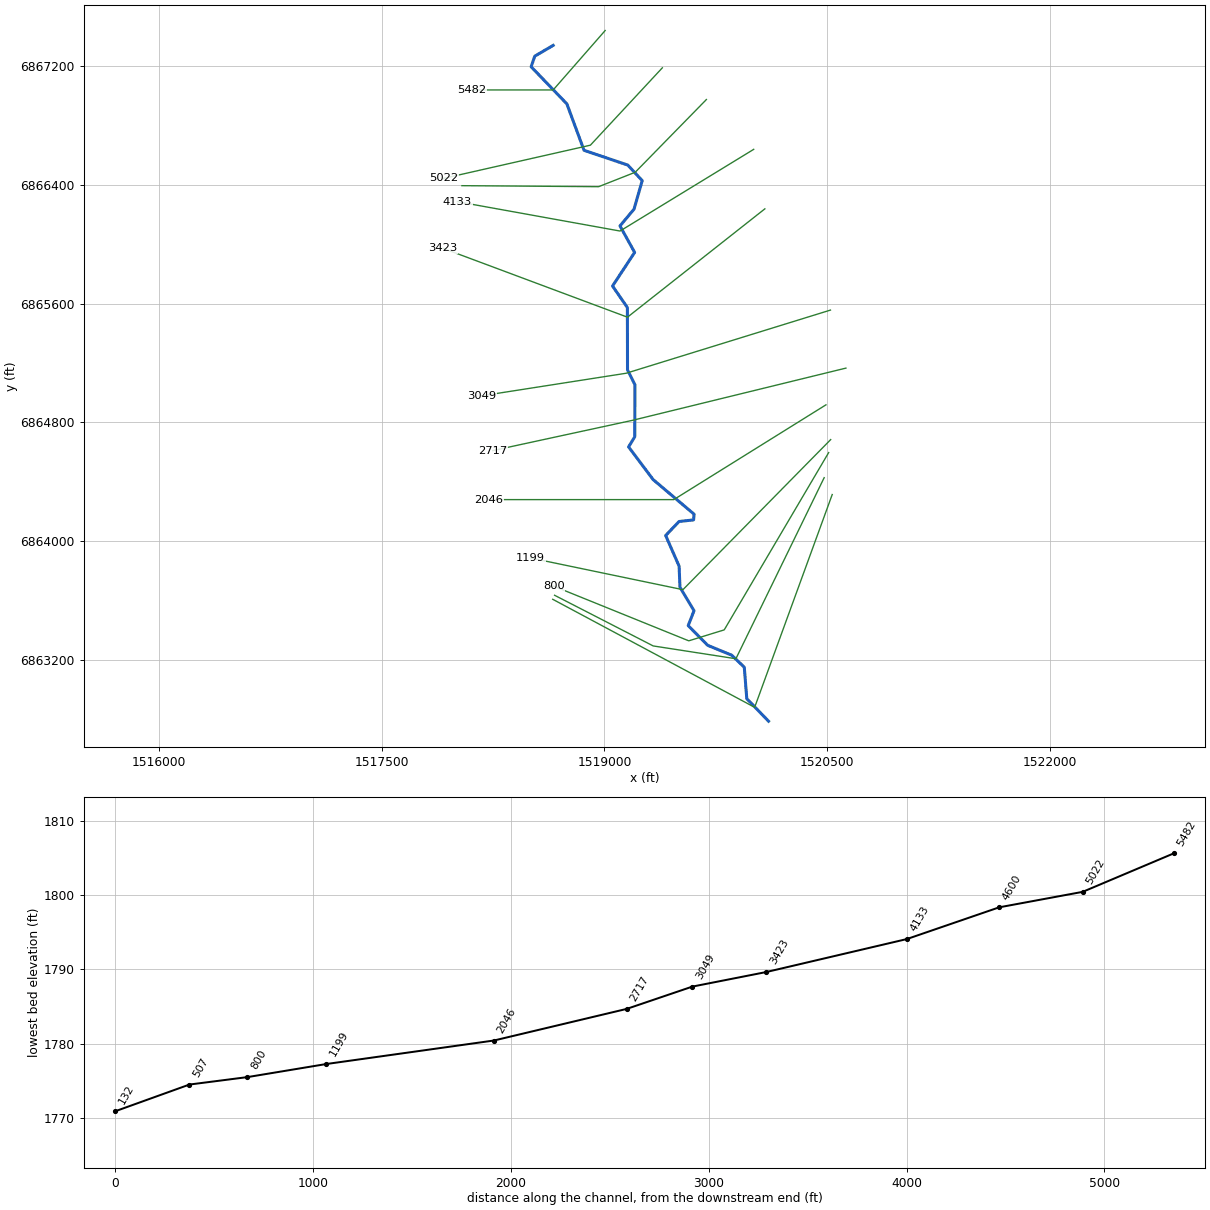
--- MULBERRY CREEK TRIBUTARY 15_3.prj (project) ---

Proj Title=MULBERRY CREEK TRIBUTARY 15_3 Base Level Engineering
Current Plan=p01
Default Exp/Contr=0.3,0.1
English Units
Geom File=g01
Flow File=f01
Plan File=p01
Y Axis Title=Elevation
X Axis Title(PF)=Main Channel Distance
X Axis Title(XS)=Station
BEGIN DESCRIPTION:
MULBERRY CREEK TRIBUTARY 15_3
END DESCRIPTION:
DSS Export Rating Curves= 0
DSS Export Rating Curve Sorted= 0
DSS Export Volume Flow Curves= 0
DXF OffsetX= 0
DXF OffsetY= 0
DXF ScaleX= 1
DXF ScaleY= 10

--- MULBERRY CREEK TRIBUTARY 15_3.p01 (plan) ---

Plan Title=Multiple Run
Short Identifier=Multiple
Geom File=g01
Flow File=f01
Subcritical Flow
K Sum by GR= 0
Std Step Tol= 0.01
Critical Tol= 0.01
Num of Std Step Trials= 20
Max Error Tol= 0.3
Flow Tol Ratio= 0.001
Split Flow NTrial= 30
Split Flow Tol= 0.02
Split Flow Ratio= 0.02
Log Output Level= 0
Friction Slope Method= 1
Unsteady Friction Slope Method= 2
Unsteady Bridges Friction Slope Method= 1
Parabolic Critical Depth
Global Vel Dist=  1 , 1 , 1
Global Log Level= 0
CheckData=True
Encroach Param= -1, 0, 0, 0
BEGIN DESCRIPTION:
Multiple Run
END DESCRIPTION:

--- MULBERRY CREEK TRIBUTARY 15_3.f01 (steady flow) ---

Flow Title=Multiple
Number of Profiles=7
Profile Names=10-year,25-year,50-year,1pct_min,100-year,1pct_plu,500-year
River Rch & RM= MULBERRY CREEK T,Reach-1,5482
      93     121     143      84     168     335     236
Boundary for River Rch & Prof#=MULBERRY CREEK T,Reach-1,1
Up Type=0
Dn Type=3
Dn Slope=0.005
Boundary for River Rch & Prof#=MULBERRY CREEK T,Reach-1,2
Up Type=0
Dn Type=3
Dn Slope=0.005
Boundary for River Rch & Prof#=MULBERRY CREEK T,Reach-1,3
Up Type=0
Dn Type=3
Dn Slope=0.005
Boundary for River Rch & Prof#=MULBERRY CREEK T,Reach-1,4
Up Type=0
Dn Type=3
Dn Slope=0.005
Boundary for River Rch & Prof#=MULBERRY CREEK T,Reach-1,5
Up Type=0
Dn Type=3
Dn Slope=0.005
Boundary for River Rch & Prof#=MULBERRY CREEK T,Reach-1,6
Up Type=0
Dn Type=3
Dn Slope=0.005
Boundary for River Rch & Prof#=MULBERRY CREEK T,Reach-1,7
Up Type=0
Dn Type=3
Dn Slope=0.005

--- MULBERRY CREEK TRIBUTARY 15_3.g01 (geometry) ---

Geom Title=Existing Conditions
Program Version=4.10

River Reach=MULBERRY CREEK T,Reach-1
Reach XY= 30
        1518655.        6867338.      1518530.87      6867265.17
      1518506.56      6867194.09      1518747.14      6866944.17
      1518862.73       6866631.5      1519157.32      6866532.18
      1519254.41      6866427.39      1519199.46      6866235.58
       1519104.9      6866122.64      1519203.41      6865944.05
      1519054.63       6865717.8      1519154.61      6865572.84
      1519155.52      6865153.22      1519205.43      6865053.18
      1519204.34      6864703.16      1519162.79      6864634.58
      1519328.02      6864414.53      1519603.69      6864181.66
      1519600.42      6864143.29      1519502.62      6864132.45
      1519412.31      6864038.11      1519502.73      6863832.06
      1519508.76      6863689.56      1519603.16      6863531.87
      1519564.15      6863431.27      1519695.32      6863298.76
      1519857.31      6863232.17      1519941.64      6863151.34
      1519958.53      6862939.46        1520105.        6862788.

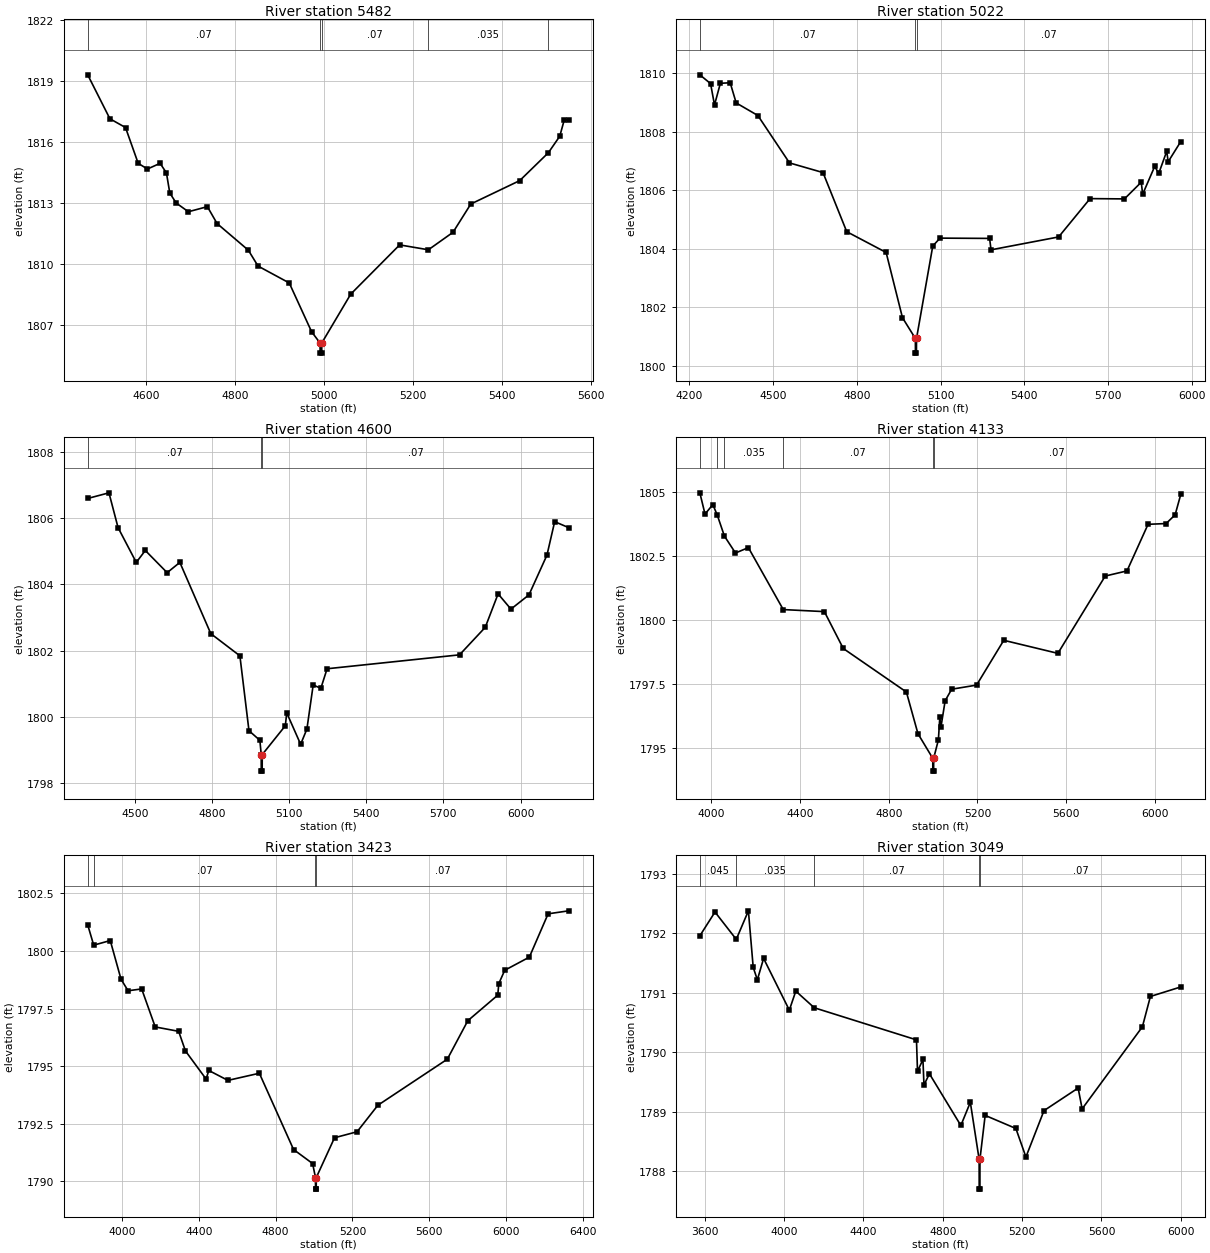
Type RM Length L Ch R = 1 ,5482    ,460,460,460
BEGIN DESCRIPTION:
MULBERRY CREEK TRIBUTARY 15_3 4.0
END DESCRIPTION:
XS GIS Cut Line= 3
      1519005.02      6867438.03        1518655.        6867038.
      1518105.04        6867038.
#Sta/Elev= 30
  4468.5 1819.29  4518.4 1817.13  4553.5  1816.7    4582 1814.94  4602.8 1814.66
  4631.3 1814.94  4645.5 1814.47  4653.1 1813.48  4667.4 1812.99  4694.9 1812.56
  4737.6 1812.81  4759.4 1811.98  4829.7 1810.67  4851.5 1809.89  4921.7 1809.06
    4972 1806.66  4990.9 1806.11  4991.2 1805.61  4994.7 1805.61  4994.9 1806.11
    5060 1808.51    5170 1810.93  5234.6 1810.69    5290 1811.55    5330 1812.94
    5440 1814.09  5504.4 1815.46    5530 1816.27    5540 1817.06    5550 1817.09
#Mann= 5 ,-1 , 0
  4468.5     .07       0  4990.9     .07       0  4994.9     .07       0
  5234.6    .035       0  5504.4     .07       0
Bank Sta=4990.9,4994.9
XS Rating Curve= 0 ,0
Exp/Cntr=0.3,0.1

Type RM Length L Ch R = 1 ,5022    ,422,422,422
BEGIN DESCRIPTION:
Mapping XS 151ff243
END DESCRIPTION:
XS GIS Cut Line= 3
      1519389.97      6867186.96      1518905.56      6866666.09
      1517917.94      6866442.58
#Sta/Elev= 30
  4237.2 1809.95  4275.6 1809.65  4289.7 1808.92  4310.7 1809.66  4345.9 1809.68
  4367.4 1808.99  4445.1 1808.56  4558.5 1806.94  4678.6 1806.61  4763.7 1804.59
  4904.9 1803.88  4963.5 1801.65  5009.8 1800.94    5010 1800.44  5013.5 1800.44
  5013.8 1800.94  5072.1  1804.1  5098.1 1804.37  5275.8 1804.36    5281 1803.97
  5523.2 1804.41    5636 1805.72  5759.1 1805.71  5819.4 1806.28  5824.5 1805.87
  5867.6 1806.82  5882.1 1806.58  5910.8 1807.34  5915.9 1806.98  5961.1 1807.67
#Mann= 3 ,-1 , 0
  4237.2     .07       0  5009.8     .07       0  5013.8     .07       0
Bank Sta=5009.8,5013.8
XS Rating Curve= 0 ,0
Exp/Cntr=0.3,0.1

Type RM Length L Ch R = 1 ,4600    ,467,467,467
BEGIN DESCRIPTION:
Mapping XS b7a36959
END DESCRIPTION:
XS GIS Cut Line= 4
      1519686.49      6866973.34      1519207.35      6866483.78
      1518960.83      6866386.56      1518040.67       6866393.5
#Sta/Elev= 30
  4316.8 1806.59  4399.4 1806.76  4434.8 1805.71  4505.6 1804.66  4540.8 1805.02
  4625.7 1804.35  4675.1 1804.66  4795.4 1802.51  4908.6 1801.84  4943.9 1799.58
  4986.3 1799.29  4991.5 1798.86  4991.7 1798.36  4995.2 1798.36  4995.5 1798.86
  5085.3 1799.73  5090.7 1800.12  5144.8 1799.17  5169.2 1799.63  5193.6 1800.96
  5223.4 1800.86  5247.7 1801.45  5762.7 1801.87  5862.7  1802.7  5912.7 1803.71
  5962.7 1803.25  6032.7 1803.68  6102.7 1804.88  6132.7 1805.89    6187 1805.71
#Mann= 3 ,-1 , 0
  4316.8     .07       0  4991.5     .07       0  4995.5     .07       0
Bank Sta=4991.5,4995.5
XS Rating Curve= 0 ,0
Exp/Cntr=0.3,0.1

Type RM Length L Ch R = 1 ,4133    ,710,710,710
BEGIN DESCRIPTION:
MULBERRY CREEK TRIBUTARY 15_3 3.0
END DESCRIPTION:
XS GIS Cut Line= 3
      1520005.01      6866638.01        1519105.        6866088.
      1518009.89      6866285.85
#Sta/Elev= 30
  3948.8 1804.96    3972 1804.13  4007.4  1804.5  4027.7 1804.08  4059.5 1803.27
  4109.4 1802.61  4167.5 1802.82  4324.7  1800.4    4510 1800.32  4595.2 1798.88
  4879.7 1797.18  4931.9 1795.55  4998.6 1794.59  4998.9 1794.09  5002.4 1794.09
  5002.6 1794.59  5023.9 1795.31  5030.3 1796.19  5035.4 1795.81  5054.4 1796.84
  5083.9 1797.29    5196 1797.45  5318.6  1799.2  5562.5 1798.69  5775.9 1801.71
  5873.9 1801.91  5968.9 1803.73  6050.2 1803.76  6090.9  1804.1  6116.4  1804.9
#Mann= 6 ,-1 , 0
  3948.8    .035       0  4027.7     .07       0  4059.5    .035       0
  4324.7     .07       0  4998.6     .07       0  5002.6     .07       0
Bank Sta=4998.6,5002.6
XS Rating Curve= 0 ,0
Exp/Cntr=0.3,0.1

Type RM Length L Ch R = 1 ,3423    ,374,374,374
BEGIN DESCRIPTION:
MULBERRY CREEK TRIBUTARY 15_3 2.0
END DESCRIPTION:
XS GIS Cut Line= 3
      1520080.08       6866237.3      1519155.18      6865508.07
      1517913.38      6865971.64
#Sta/Elev= 30
  3822.2 1801.13  3853.4 1800.25  3939.6 1800.45  3995.6 1798.77  4032.4 1798.27
  4103.1 1798.35  4173.6  1796.7  4295.5 1796.51  4330.8 1795.66  4438.2 1794.44
  4452.6 1794.81  4552.1 1794.38  4715.6 1794.69  4893.6 1791.38  4992.9 1790.77
  5007.8 1790.16  5008.1 1789.66  5011.6 1789.66  5011.8 1790.16  5106.9 1791.89
  5224.3 1792.15  5332.5  1793.3    5694  1795.3  5800.7 1796.97  5956.6 1798.08
  5961.9 1798.58  5992.9 1799.16    6121 1799.73  6218.7 1801.61  6325.5 1801.74
#Mann= 4 ,-1 , 0
  3822.2    .035       0  3853.4     .07       0  5007.8     .07       0
  5011.8     .07       0
Bank Sta=5007.8,5011.8
XS Rating Curve= 0 ,0
Exp/Cntr=0.3,0.1

Type RM Length L Ch R = 1 ,3049    ,332,332,332
BEGIN DESCRIPTION:
Mapping XS 90342682
END DESCRIPTION:
XS GIS Cut Line= 3
      1520521.93      6865555.86      1519146.01       6865130.5
      1518173.77      6864978.59
#Sta/Elev= 30
  3575.6 1791.96  3651.9 1792.36  3759.2  1791.9  3820.3 1792.38  3844.5 1791.43
  3865.5 1791.22  3896.9 1791.58  4026.6 1790.71  4059.2 1791.03  4152.3 1790.75
  4667.5 1790.21  4672.7 1789.68  4700.1 1789.88  4705.3 1789.45  4732.7 1789.64
  4891.2 1788.77    4939 1789.16  4983.4  1788.2  4983.7  1787.7  4987.2  1787.7
  4987.4  1788.2  5013.7 1788.94  5168.6 1788.72  5219.2 1788.24  5310.3 1789.02
  5482.4  1789.4  5502.6 1789.05  5806.3 1790.43  5846.7 1790.94  5999.8  1791.1
#Mann= 5 ,-1 , 0
  3575.6    .045       0  3759.2    .035       0  4152.3     .07       0
  4983.4     .07       0  4987.4     .07       0
Bank Sta=4983.4,4987.4
XS Rating Curve= 0 ,0
Exp/Cntr=0.3,0.1

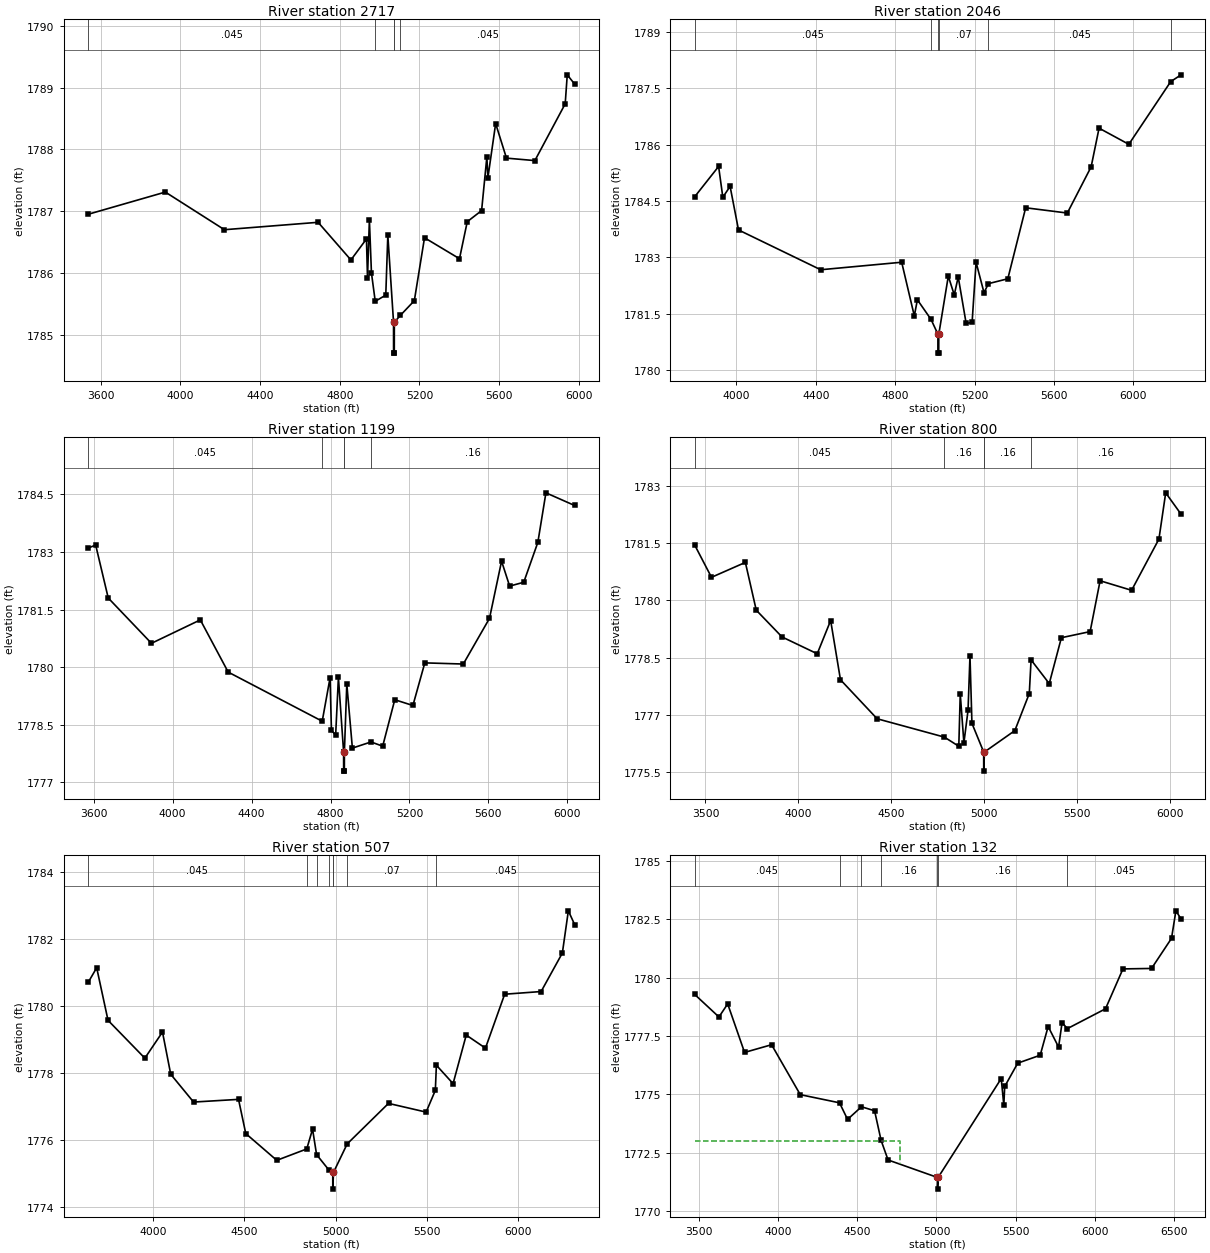
Type RM Length L Ch R = 1 ,2717    ,671,671,671
BEGIN DESCRIPTION:
Mapping XS 66ce3032
END DESCRIPTION:
XS GIS Cut Line= 3
      1520626.01      6865165.21      1519189.42      6864813.66
      1518248.81      6864609.93
#Sta/Elev= 30
  3537.1 1786.95  3924.6 1787.31  4221.1  1786.7  4691.2 1786.82  4855.9 1786.21
  4933.9 1786.55  4939.1 1785.92  4948.6 1786.86  4958.9    1786  4977.9 1785.54
  5030.8 1785.64  5041.1 1786.61  5069.8  1785.2    5070  1784.7  5073.5  1784.7
  5073.8  1785.2  5103.5 1785.31  5174.1 1785.55  5225.2 1786.57  5400.7 1786.23
  5439.7 1786.83  5511.7 1787.01  5538.1 1787.88  5543.2 1787.54  5582.2 1788.42
  5636.5 1787.86    5779 1787.82  5931.2 1788.74  5941.5 1789.21  5978.5 1789.06
#Mann= 5 ,-1 , 0
  3537.1    .045       0  4977.9     .07       0  5069.8     .07       0
  5073.8     .07       0  5103.5    .045       0
Bank Sta=5069.8,5073.8
XS Rating Curve= 0 ,0
Exp/Cntr=0.3,0.1

Type RM Length L Ch R = 1 ,2046    ,847,847,847
BEGIN DESCRIPTION:
Mapping XS f29cd4b0
END DESCRIPTION:
XS GIS Cut Line= 3
      1520491.53      6864917.85      1519467.19      6864279.81
      1518221.49      6864279.81
#Sta/Elev= 30
  3788.8 1784.61  3909.9 1785.42  3931.2  1784.6  3967.8 1784.89  4010.2 1783.73
  4424.5 1782.67  4832.8 1782.87  4896.5 1781.44  4911.9 1781.87  4980.5 1781.35
  5015.8 1780.95    5016 1780.45  5019.5 1780.45  5019.8 1780.95  5067.8  1782.5
  5097.8    1782  5117.8 1782.48  5157.8 1781.24  5187.8 1781.27  5207.8 1782.87
  5247.8 1782.06  5270.1  1782.3  5367.8 1782.43  5457.8 1784.32  5667.8 1784.18
  5787.8 1785.41  5827.8 1786.44  5977.8 1786.01  6189.1 1787.68  6241.3 1787.86
#Mann= 6 ,-1 , 0
  3788.8    .045       0  4980.5     .07       0  5015.8     .07       0
  5019.8     .07       0  5270.1    .045       0  6189.1    .035       0
Bank Sta=5015.8,5019.8
XS Rating Curve= 0 ,0
Exp/Cntr=0.3,0.1

Type RM Length L Ch R = 1 ,1199    ,399,399,399
BEGIN DESCRIPTION:
Mapping XS f75d96e8
END DESCRIPTION:
XS GIS Cut Line= 3
      1520523.36      6864683.82      1519528.53      6863673.36
      1518502.51       6863886.9
#Sta/Elev= 30
  3571.4  1783.1  3609.7 1783.18  3673.4  1781.8  3892.5 1780.62  4140.1 1781.23
  4281.4 1779.87    4758 1778.59  4797.7 1779.72  4804.7 1778.36    4826 1778.22
  4840.1 1779.73  4866.4 1777.79  4866.7 1777.29  4870.2 1777.29  4870.4 1777.79
  4882.6 1779.56  4910.9 1777.89  5005.3 1778.05  5064.5 1777.94  5125.8 1779.15
  5217.7    1779    5278 1780.11  5473.1 1780.08  5605.9 1781.27  5667.1 1782.76
    5708 1782.11  5779.5 1782.21    5851 1783.25  5891.9 1784.54  6037.4 1784.21
#Mann= 5 ,-1 , 0
  3571.4    .045       0    4758     .16       0  4866.4     .07       0
  4870.4     .16       0  5005.3     .16       0
#XS Ineff= 2 , 0
       0  4840.1 1779.73               0
Permanent Ineff=
       F       F
Bank Sta=4866.4,4870.4
XS Rating Curve= 0 ,0
Exp/Cntr=0.3,0.1

Type RM Length L Ch R = 1 ,800     ,293,293,293
BEGIN DESCRIPTION:
Mapping XS 662d7d90
END DESCRIPTION:
XS GIS Cut Line= 4
      1520509.76      6864596.36      1519806.65       6863402.8
      1519567.93      6863329.02      1518658.24      6863697.23
#Sta/Elev= 30
  3441.5 1781.45  3532.4  1780.6  3714.6 1780.99  3773.2 1779.74  3911.8 1779.04
  4101.1  1778.6  4173.3 1779.47  4226.1 1777.92  4423.2  1776.9  4784.8 1776.42
  4862.5 1776.18  4870.3 1777.55  4889.9 1776.27  4912.2 1777.12  4922.6 1778.54
  4933.2 1776.78  4996.3 1776.03  4996.5 1775.53  5000.3 1776.03  5163.9 1776.59
  5241.6 1777.56  5251.2 1778.44  5348.9 1777.82  5414.2 1779.02  5568.8 1779.18
  5622.4 1780.51  5791.8 1780.26  5938.8  1781.6  5975.2 1782.81    6058 1782.25
#Mann= 5 ,-1 , 0
  3441.5    .045       0  4784.8     .16       0  4996.3     .07       0
  5000.3     .16       0  5251.2     .16       0
#XS Ineff= 2 , 0
       0  4922.6 1778.54               0
Permanent Ineff=
       F       F
Bank Sta=4996.3,5000.3
XS Rating Curve= 0 ,0
Exp/Cntr=0.3,0.1

Type RM Length L Ch R = 1 ,507     ,375,375,375
BEGIN DESCRIPTION:
Mapping XS d4a57920
END DESCRIPTION:
XS GIS Cut Line= 4
      1520479.52      6864427.49      1519885.24      6863208.42
      1519328.46      6863294.65      1518664.38       6863635.8
#Sta/Elev= 30
  3643.8  1780.7  3690.8 1781.14  3752.9 1779.57  3954.7 1778.44  4051.4 1779.22
  4096.5 1777.96  4221.7 1777.13  4468.1 1777.21  4507.7 1776.19  4677.8 1775.39
    4842 1775.73  4873.8 1776.32  4895.9 1775.56    4962 1775.11  4984.5 1775.03
  4984.7 1774.53  4988.5 1775.03  5063.5 1775.88    5290 1777.09  5496.1 1776.83
  5546.7 1777.48  5552.4 1778.23  5643.9 1777.68    5716 1779.13  5821.3 1778.74
  5926.6 1780.35  6126.3 1780.43  6242.8 1781.58  6275.6 1782.84    6310 1782.43
#Mann= 8 ,-1 , 0
  3643.8    .045       0    4842     .16       0  4895.9     .07       0
    4962     .16       0  4984.5     .07       0  4988.5     .16       0
  5063.5     .07       0  5552.4    .045       0
Bank Sta=4984.5,4988.5
XS Rating Curve= 0 ,0
Exp/Cntr=0.3,0.1

Type RM Length L Ch R = 1 ,132     ,0,0,0
BEGIN DESCRIPTION:
MULBERRY CREEK TRIBUTARY 15_3 1.0
END DESCRIPTION:
XS GIS Cut Line= 3
      1520533.76      6864314.03      1520011.48      6862881.26
      1518651.79      6863608.79
#Sta/Elev= 30
    3475 1779.29  3628.5 1778.32  3683.7 1778.88  3790.1  1776.8  3960.4 1777.13
  4141.3 1774.99  4388.7 1774.64  4439.4 1773.93  4527.2 1774.47  4609.7  1774.3
  4650.8 1773.03  4694.8 1772.19  5006.4 1771.44  5006.6 1770.94  5010.4 1771.44
  5408.2 1775.68  5424.5 1774.54  5430.1 1775.34  5512.2 1776.34  5653.8 1776.68
    5704 1777.91  5769.8 1777.03  5791.8 1778.08    5825 1777.82  6065.6 1778.67
  6175.5 1780.38  6355.8  1780.4  6481.7 1781.69  6509.4 1782.87  6542.1 1782.52
#Mann= 7 ,-1 , 0
    3475    .045       0  4388.7     .07       0  4527.2     .16       0
  4650.8     .16       0  5006.4     .07       0  5010.4     .16       0
    5825    .045       0
#XS Ineff= 2 , 0
       0  4772.7 1773.02               0
Permanent Ineff=
       F       F
Bank Sta=5006.4,5010.4
XS Rating Curve= 0 ,0
Exp/Cntr=0.3,0.1

Chan Stop Cuts=-1
Use User Specified Reach Order=0
Composite Channel Slope=5