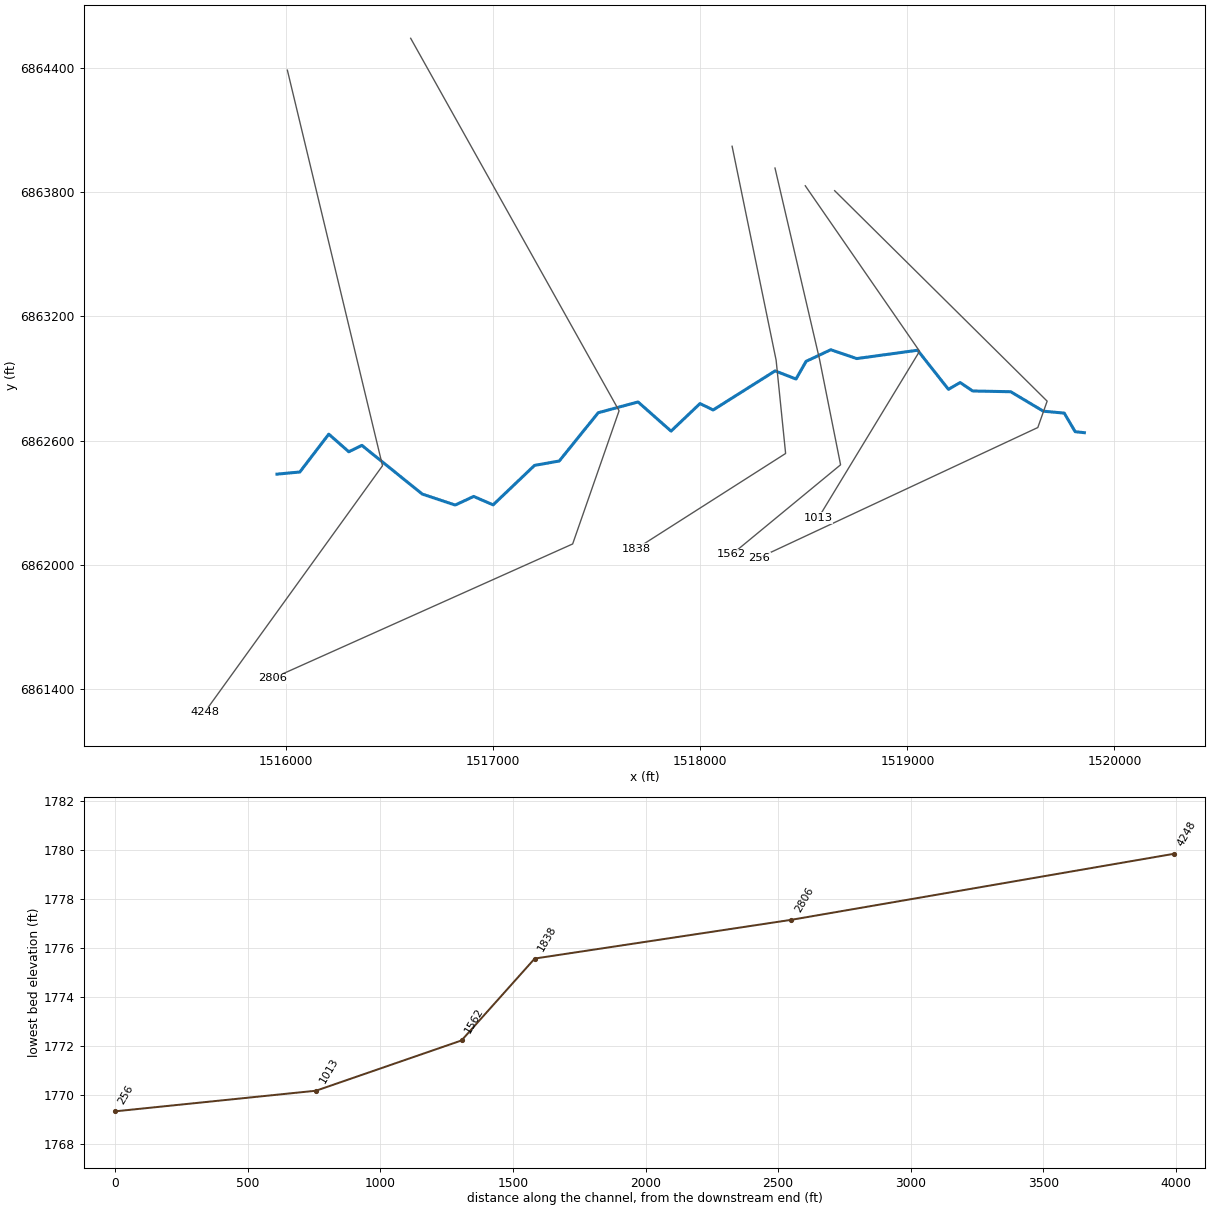
--- MULBERRY CREEK TRIBUTARY 15_4.prj (project) ---

Proj Title=MULBERRY CREEK TRIBUTARY 15_4 Base Level Engineering
Current Plan=p01
Default Exp/Contr=0.3,0.1
English Units
Geom File=g01
Flow File=f01
Plan File=p01
BEGIN DESCRIPTION:
MULBERRY CREEK TRIBUTARY 15_4
END DESCRIPTION:

--- MULBERRY CREEK TRIBUTARY 15_4.p01 (plan) ---

Plan Title=Multiple Run
Short Identifier=Multiple
Geom File=g01
Flow File=f01
Subcritical Flow
K Sum by GR= 0
Std Step Tol= 0.01
Critical Tol= 0.01
Num of Std Step Trials= 20
Max Error Tol= 0.3
Flow Tol Ratio= 0.001
Split Flow NTrial= 30
Split Flow Tol= 0.02
Split Flow Ratio= 0.02
Log Output Level= 0
Friction Slope Method= 1
Unsteady Friction Slope Method= 2
Unsteady Bridges Friction Slope Method= 1
Parabolic Critical Depth
Global Vel Dist=  1 , 1 , 1
Global Log Level= 0
CheckData=True
Encroach Param= -1, 0, 0, 0
BEGIN DESCRIPTION:
Multiple Run
END DESCRIPTION:

--- MULBERRY CREEK TRIBUTARY 15_4.f01 (steady flow) ---

Flow Title=Multiple
Number of Profiles=7
Profile Names=10-year,25-year,50-year,1pct_min,100-year,1pct_plu,500-year
River Rch & RM= MULBERRY CREEK T,Reach-1,4248
     374     530     661     411     820    1636    1277
Boundary for River Rch & Prof#=MULBERRY CREEK T,Reach-1,1
Up Type=0
Dn Type=3
Dn Slope=0.005
Boundary for River Rch & Prof#=MULBERRY CREEK T,Reach-1,2
Up Type=0
Dn Type=3
Dn Slope=0.005
Boundary for River Rch & Prof#=MULBERRY CREEK T,Reach-1,3
Up Type=0
Dn Type=3
Dn Slope=0.005
Boundary for River Rch & Prof#=MULBERRY CREEK T,Reach-1,4
Up Type=0
Dn Type=3
Dn Slope=0.005
Boundary for River Rch & Prof#=MULBERRY CREEK T,Reach-1,5
Up Type=0
Dn Type=3
Dn Slope=0.005
Boundary for River Rch & Prof#=MULBERRY CREEK T,Reach-1,6
Up Type=0
Dn Type=3
Dn Slope=0.005
Boundary for River Rch & Prof#=MULBERRY CREEK T,Reach-1,7
Up Type=0
Dn Type=3
Dn Slope=0.005

--- MULBERRY CREEK TRIBUTARY 15_4.g01 (geometry) ---

Geom Title=Existing Conditions

River Reach=MULBERRY CREEK T,Reach-1
Reach XY= 30
      1515955.00      6862438.00      1516065.18      6862448.29
      1516204.99      6862630.91      1516301.67      6862546.03
      1516365.00      6862576.76      1516656.58      6862341.82
      1516815.71      6862288.81      1516905.00      6862330.38
      1516998.95      6862289.66      1517198.83      6862480.14
      1517318.33      6862501.39      1517506.48      6862734.39
      1517698.97      6862786.38      1517858.33      6862645.59
      1517998.33      6862778.70      1518061.55      6862747.59
      1518361.05      6862936.33      1518462.00      6862897.08
      1518510.61      6862982.35      1518629.99      6863038.41
      1518755.10      6862995.79      1519049.32      6863036.03
      1519198.31      6862847.29      1519254.90      6862880.19
      1519315.43      6862839.38      1519499.07      6862835.76
      1519656.59      6862741.83      1519757.67      6862732.58
      1519810.35      6862642.96      1519855.00      6862638.00

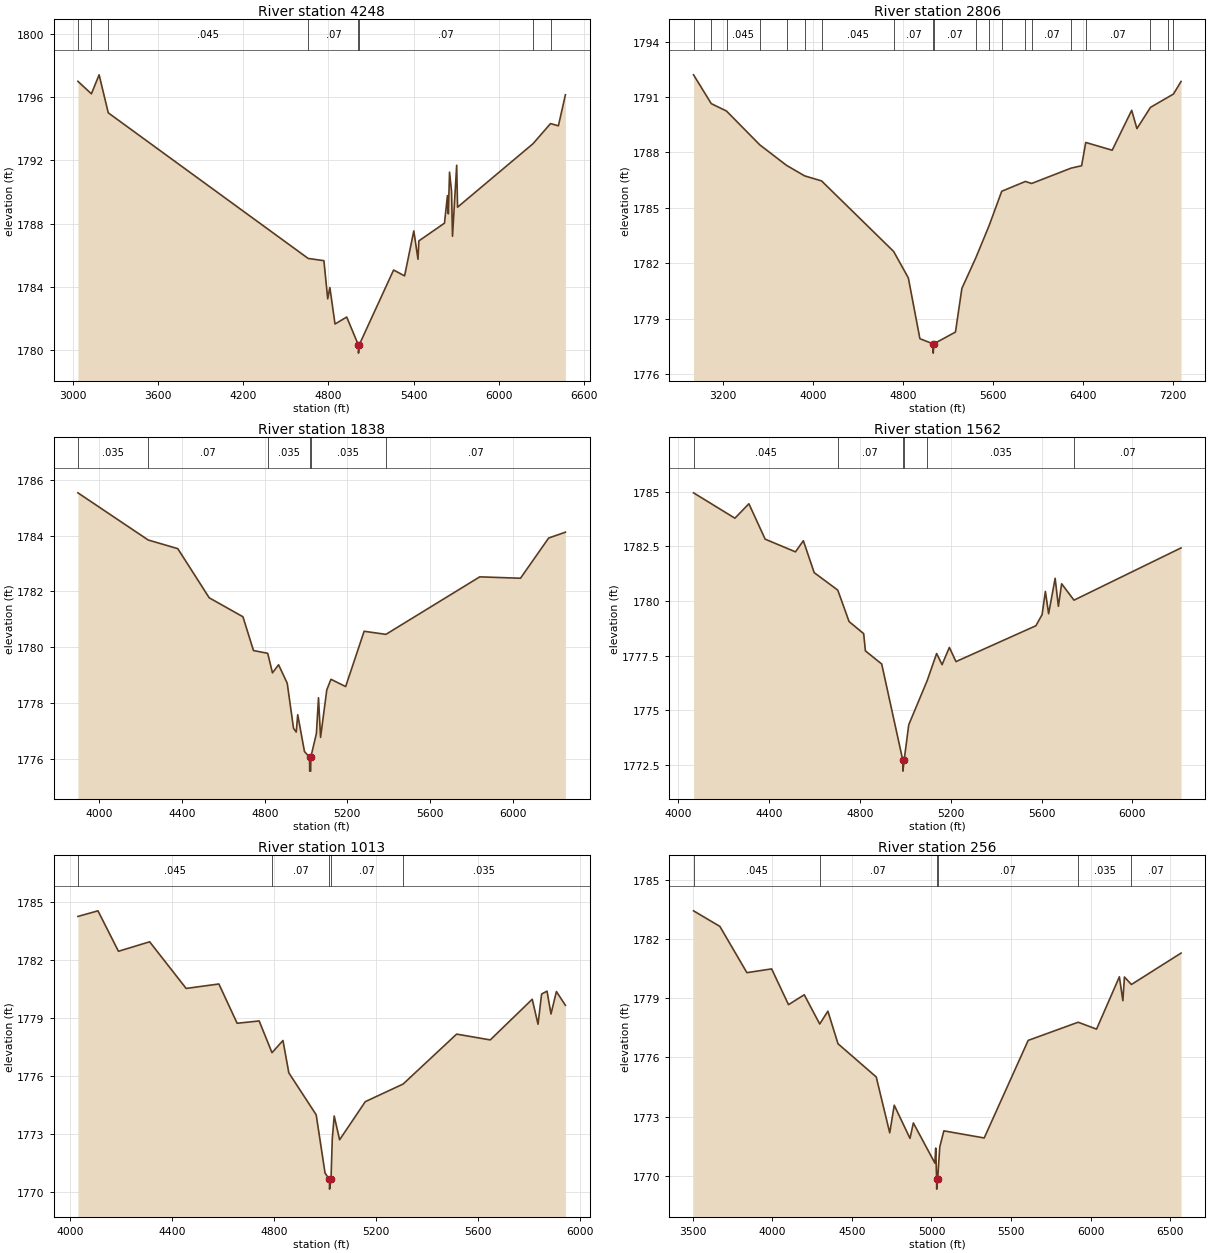
Type RM Length L Ch R = 1,4248,1442,1442,1442
BEGIN DESCRIPTION:
MULBERRY CREEK TRIBUTARY 15_4 1.0
END DESCRIPTION:
XS GIS Cut Line= 3
      1516005.01      6864387.95      1516464.52      6862478.46
      1515605.01      6861288.02
#Sta/Elev= 30
  3036.0 1797.00  3130.9 1796.21  3185.3 1797.41  3249.7 1795.01  4657.5 1785.81
  4768.0 1785.67  4794.8 1783.26  4810.0 1783.97  4846.2 1781.67  4928.5 1782.11
  5011.3 1780.33  5011.6 1779.83  5015.4 1780.33  5258.7 1785.08  5336.0 1784.71
  5401.0 1787.55  5430.4 1785.76  5436.6 1786.92  5616.9 1788.04  5637.8 1789.78
  5644.0 1788.63  5652.5 1791.26  5666.6 1790.05  5673.4 1787.21  5702.8 1791.70
  5709.0 1789.05  6240.4 1793.06  6363.6 1794.33  6419.0 1794.19  6468.3 1796.15
#Mann=8,-1,0
  3036.0   0.045       0  3130.9    0.07       0  3249.7   0.045       0
  4657.5    0.07       0  5011.3    0.07       0  5015.4    0.07       0
  6240.4   0.035       0  6363.6    0.07       0
Bank Sta=5011.3,5015.4
Exp/Cntr=0.3,0.1

Type RM Length L Ch R = 1,2806,968,968,968
BEGIN DESCRIPTION:
MULBERRY CREEK TRIBUTARY 15_4 0.0
END DESCRIPTION:
XS GIS Cut Line= 4
      1516600.62      6864541.80      1517607.32      6862743.85
      1517383.08      6862101.00      1515933.90      6861452.27
#Sta/Elev= 30
  2939.4 1792.20  3097.1 1790.64  3232.2 1790.24  3527.9 1788.41  3765.4 1787.30
  3926.5 1786.73  4076.2 1786.46  4716.6 1782.64  4846.9 1781.21  4949.6 1777.92
  5067.5 1777.64  5067.8 1777.14  5072.0 1777.64  5265.4 1778.28  5322.2 1780.64
  5447.0 1782.31  5565.4 1784.06  5676.3 1785.90  5886.8 1786.43  5941.5 1786.32
  6291.8 1787.15  6385.6 1787.28  6422.4 1788.54  6657.1 1788.12  6830.4 1790.28
  6876.8 1789.29  6997.3 1790.44  7155.7 1791.00  7201.2 1791.16  7268.6 1791.84
#Mann=20,-1,0
  2939.4   0.045       0  3097.1    0.07       0  3232.2   0.045       0
  3527.9    0.07       0  3765.4   0.045       0  3926.5    0.07       0
  4076.2   0.045       0  4716.6    0.07       0  5067.5    0.07       0
  5072.0    0.07       0  5447.0   0.035       0  5565.4    0.07       0
  5676.3    0.07       0  5886.8   0.035       0  5941.5    0.07       0
  6291.8   0.035       0  6422.4    0.07       0  6997.3   0.035       0
  7155.7    0.07       0  7201.2   0.035       0
Bank Sta=5067.5,5072
Exp/Cntr=0.3,0.1

Type RM Length L Ch R = 1,1838,276,276,276
BEGIN DESCRIPTION:
Mapping XS 39e31eaa
END DESCRIPTION:
XS GIS Cut Line= 4
      1518153.28      6864020.60      1518365.96      6862987.59
      1518411.76      6862537.73      1517692.12      6862078.95
#Sta/Elev= 30
  3895.5 1785.53  4235.8 1783.84  4379.1 1783.53  4531.2 1781.77  4694.5 1781.09
  4745.6 1779.88  4814.5 1779.78  4837.5 1779.08  4867.0 1779.37  4908.9 1778.71
  4939.6 1777.09  4952.5 1776.96  4959.8 1777.58  4992.5 1776.26  5017.1 1776.06
  5017.6 1775.56  5022.6 1775.56  5023.1 1776.06  5050.3 1776.91  5060.3 1778.19
  5070.4 1776.77  5100.5 1778.47  5120.6 1778.85  5191.8 1778.59  5281.3 1780.57
  5386.9 1780.46  5841.1 1782.52  6038.3 1782.47  6174.6 1783.91  6255.8 1784.12
#Mann=6,-1,0
  3895.5   0.035       0  4235.8    0.07       0  4814.5   0.035       0
  5017.1   0.035       0  5023.1   0.035       0  5386.9    0.07       0
Bank Sta=5017.1,5023.1
Exp/Cntr=0.3,0.1

Type RM Length L Ch R = 1,1562,549,549,549
BEGIN DESCRIPTION:
Mapping XS 9bcde03b
END DESCRIPTION:
XS GIS Cut Line= 4
      1518360.50      6863915.41      1518575.83      6862991.15
      1518677.24      6862483.04      1518151.82      6862050.35
#Sta/Elev= 30
  4066.4 1784.95  4248.6 1783.79  4310.2 1784.45  4382.0 1782.83  4515.5 1782.25
  4550.2 1782.76  4597.9 1781.30  4701.8 1780.50  4751.7 1779.06  4815.9 1778.51
  4823.6 1777.72  4895.4 1777.12  4988.3 1772.72  4988.8 1772.22  4994.3 1772.72
  5014.5 1774.34  5095.7 1776.36  5137.4 1777.60  5161.4 1777.09  5193.5 1777.88
  5222.6 1777.23  5574.8 1778.87  5602.1 1779.38  5616.5 1780.44  5630.8 1779.42
  5659.5 1781.04  5673.8 1779.76  5688.2 1780.79  5742.5 1780.04  6214.2 1782.43
#Mann=6,-1,0
  4066.4   0.045       0  4701.8    0.07       0  4988.3    0.07       0
  4994.3    0.07       0  5095.7   0.035       0  5742.5    0.07       0
Bank Sta=4988.3,4994.3
Exp/Cntr=0.3,0.1

Type RM Length L Ch R = 1,1013,757,757,757
BEGIN DESCRIPTION:
Mapping XS b57ce45d
END DESCRIPTION:
XS GIS Cut Line= 3
      1518506.74      6863829.88      1519058.84      6863031.23
      1518569.60      6862226.25
#Sta/Elev= 30
  4030.6 1784.26  4109.3 1784.55  4189.7 1782.46  4312.1 1782.95  4455.3 1780.54
  4583.8 1780.77  4655.4 1778.74  4741.9 1778.86  4792.2 1777.22  4835.2 1777.85
  4858.2 1776.18  4965.6 1774.01  5000.4 1771.00  5017.6 1770.67  5018.1 1770.17
  5023.7 1770.67  5028.7 1772.76  5036.2 1773.95  5057.5 1772.72  5158.3 1774.69
  5306.7 1775.60  5516.7 1778.18  5648.5 1777.88  5813.3 1779.98  5836.1 1778.69
  5850.1 1780.25  5871.4 1780.40  5886.9 1779.22  5908.2 1780.38  5943.5 1779.67
#Mann=5,-1,0
  4030.6   0.045       0  4792.2    0.07       0  5017.6    0.07       0
  5023.7    0.07       0  5306.7   0.035       0
Bank Sta=5017.6,5023.7
Exp/Cntr=0.3,0.1

Type RM Length L Ch R = 1,256,0,0,0
BEGIN DESCRIPTION:
MULBERRY CREEK TRIBUTARY 15_4 2.0
END DESCRIPTION:
XS GIS Cut Line= 4
      1518648.69      6863806.11      1519675.07      6862790.27
      1519630.00      6862663.00      1518283.68      6862034.24
#Sta/Elev= 30
  3504.1 1783.42  3669.8 1782.63  3839.5 1780.29  3995.1 1780.48  4101.2 1778.67
  4200.2 1779.17  4297.4 1777.69  4348.7 1778.34  4412.4 1776.69  4652.7 1775.01
  4737.6 1772.18  4765.9 1773.58  4864.9 1771.90  4886.1 1772.68  5021.4 1770.65
  5026.7 1771.41  5032.4 1769.83  5032.9 1769.33  5038.6 1769.83  5052.3 1771.47
  5077.9 1772.28  5331.5 1771.92  5608.0 1776.86  5922.1 1777.78  6037.9 1777.43
  6181.4 1780.08  6203.4 1778.87  6213.2 1780.07  6257.2 1779.69  6569.1 1781.28
#Mann=6,-1,0
  3504.1   0.045       0  4297.4    0.07       0  5032.4    0.07       0
  5038.6    0.07       0  5922.1   0.035       0  6257.2    0.07       0
Bank Sta=5032.4,5038.6
Exp/Cntr=0.3,0.1

Chan Stop Cuts=-1