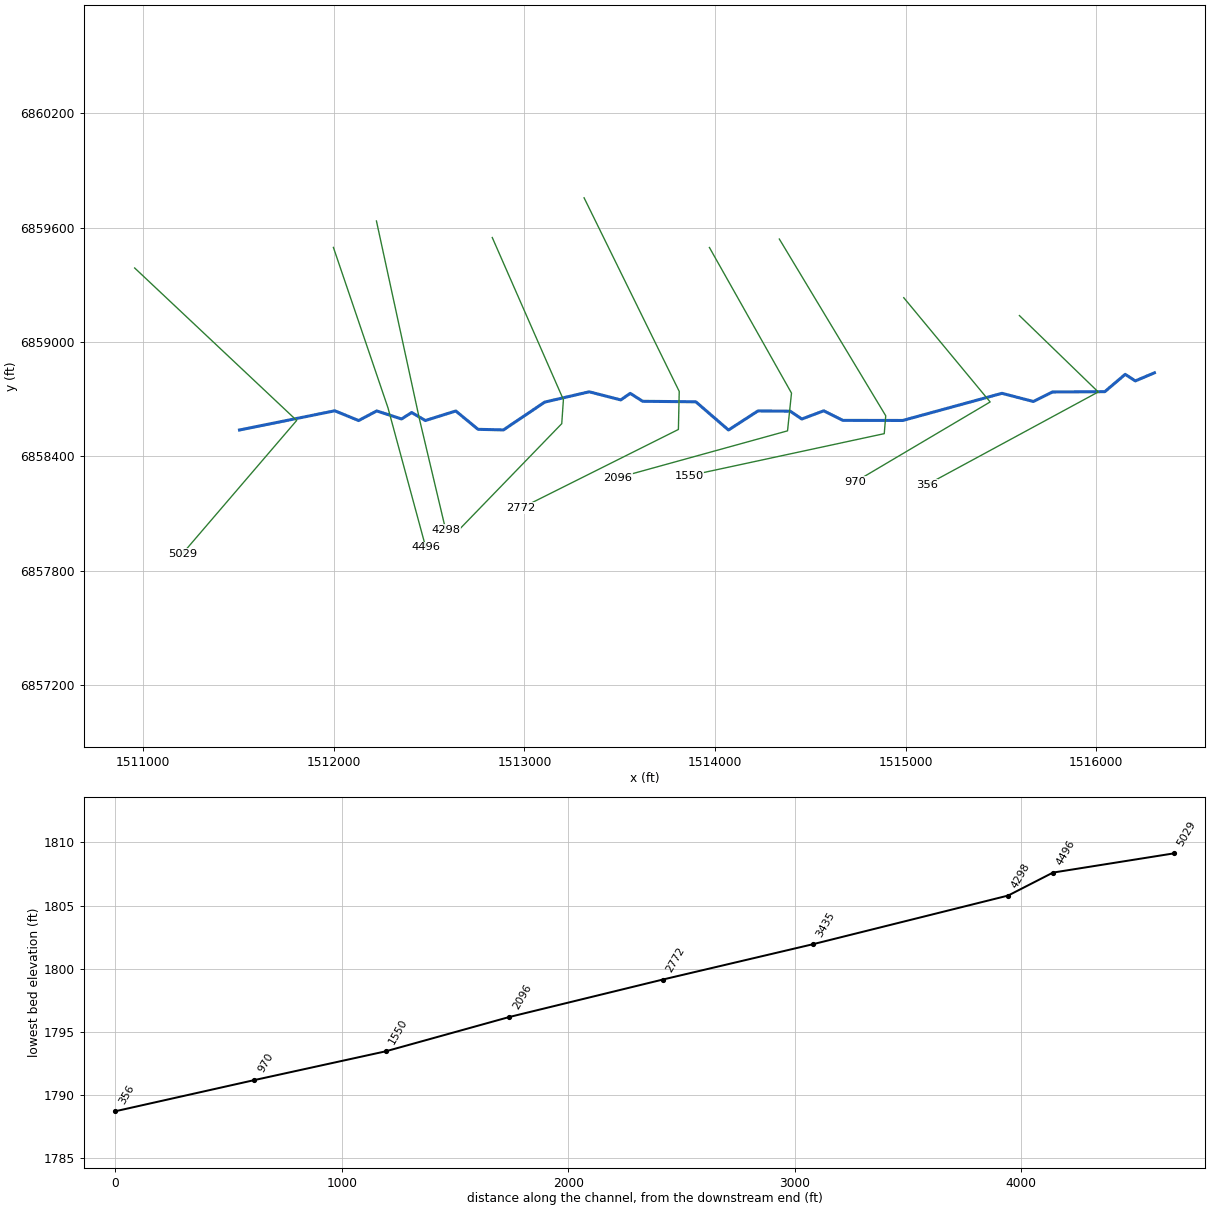
--- MULBERRY CREEK TRIBUTARY 15_5.prj (project) ---

Proj Title=MULBERRY CREEK TRIBUTARY 15_5 Base Level Engineering
Current Plan=p01
Default Exp/Contr=0.3,0.1
English Units
Geom File=g01
Flow File=f01
Plan File=p01
Y Axis Title=Elevation
X Axis Title(PF)=Main Channel Distance
X Axis Title(XS)=Station
BEGIN DESCRIPTION:
MULBERRY CREEK TRIBUTARY 15_5
END DESCRIPTION:
DSS Export Rating Curves= 0
DSS Export Rating Curve Sorted= 0
DSS Export Volume Flow Curves= 0
DXF OffsetX= 0
DXF OffsetY= 0
DXF ScaleX= 1
DXF ScaleY= 10

--- MULBERRY CREEK TRIBUTARY 15_5.p01 (plan) ---

Plan Title=Multiple Run
Short Identifier=Multiple
Geom File=g01
Flow File=f01
Subcritical Flow
K Sum by GR= 0
Std Step Tol= 0.01
Critical Tol= 0.01
Num of Std Step Trials= 20
Max Error Tol= 0.3
Flow Tol Ratio= 0.001
Split Flow NTrial= 30
Split Flow Tol= 0.02
Split Flow Ratio= 0.02
Log Output Level= 0
Friction Slope Method= 1
Unsteady Friction Slope Method= 2
Unsteady Bridges Friction Slope Method= 1
Parabolic Critical Depth
Global Vel Dist=  1 , 1 , 1
Global Log Level= 0
CheckData=True
Encroach Param= -1, 0, 0, 0
BEGIN DESCRIPTION:
Multiple Run
END DESCRIPTION:

--- MULBERRY CREEK TRIBUTARY 15_5.f01 (steady flow) ---

Flow Title=Multiple
Number of Profiles=7
Profile Names=10-year,25-year,50-year,1pct_min,100-year,1pct_plu,500-year
River Rch & RM= MULBERRY CREEK T,Reach-1,5029
     178     243     295     178     356     710     526
River Rch & RM= MULBERRY CREEK T,Reach-1,2772
     199     271     330     200     398     795     589
Boundary for River Rch & Prof#=MULBERRY CREEK T,Reach-1,1
Up Type=0
Dn Type=3
Dn Slope=0.005
Boundary for River Rch & Prof#=MULBERRY CREEK T,Reach-1,2
Up Type=0
Dn Type=3
Dn Slope=0.005
Boundary for River Rch & Prof#=MULBERRY CREEK T,Reach-1,3
Up Type=0
Dn Type=3
Dn Slope=0.005
Boundary for River Rch & Prof#=MULBERRY CREEK T,Reach-1,4
Up Type=0
Dn Type=3
Dn Slope=0.005
Boundary for River Rch & Prof#=MULBERRY CREEK T,Reach-1,5
Up Type=0
Dn Type=3
Dn Slope=0.005
Boundary for River Rch & Prof#=MULBERRY CREEK T,Reach-1,6
Up Type=0
Dn Type=3
Dn Slope=0.005
Boundary for River Rch & Prof#=MULBERRY CREEK T,Reach-1,7
Up Type=0
Dn Type=3
Dn Slope=0.005

--- MULBERRY CREEK TRIBUTARY 15_5.g01 (geometry) ---

Geom Title=Existing Conditions
Program Version=4.10

River Reach=MULBERRY CREEK T,Reach-1
Reach XY= 30
        1511505.        6858538.        1512005.      6858638.81
        1512130.       6858587.6       1512225.1      6858638.08
       1512355.1       6858595.8      1512408.23      6858629.68
      1512479.96      6858587.69      1512639.78      6858637.75
      1512756.47      6858541.54      1512889.78      6858538.49
      1513106.47      6858684.45      1513339.84      6858738.47
       1513505.1       6858695.8       1513554.9      6858730.21
      1513620.16      6858688.65      1513899.15      6858685.94
      1514070.36      6858537.89      1514224.98      6858638.04
      1514394.56      6858636.62        1514455.      6858595.56
      1514570.06      6858638.69      1514670.22      6858588.52
      1514984.97      6858588.07        1515505.      6858730.44
      1515670.16      6858687.53      1515770.22      6858737.48
      1516044.57      6858739.06      1516151.67      6858830.01
      1516204.93      6858795.58        1516305.        6858838.

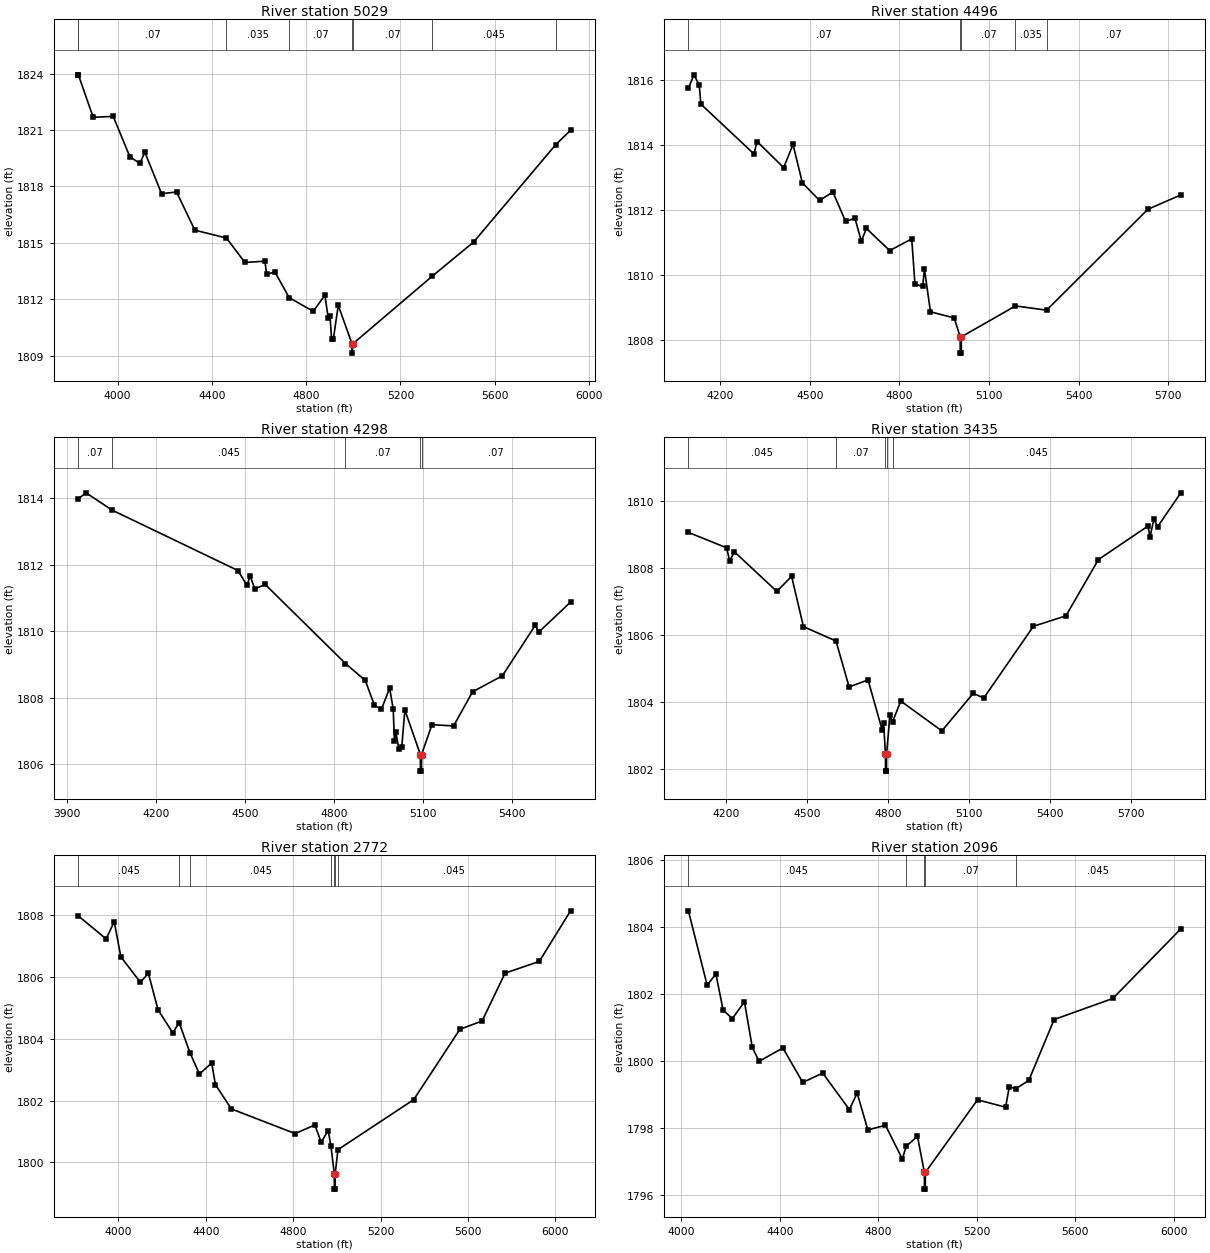
Type RM Length L Ch R = 1 ,5029    ,533,533,533
BEGIN DESCRIPTION:
MULBERRY CREEK TRIBUTARY 15_5 2.0
END DESCRIPTION:
XS GIS Cut Line= 3
      1510954.97      6859388.03        1511805.        6858588.
      1511204.97      6857887.97
#Sta/Elev= 30
  3832.6 1823.93  3833.5 1823.93  3896.4 1821.67  3981.3 1821.72  4052.1 1819.57
  4094.2 1819.22  4115.7 1819.81  4186.5 1817.61    4250  1817.7  4327.7 1815.67
  4461.8 1815.25  4540.1 1813.95  4625.1 1814.02  4631.9 1813.33  4667.5 1813.44
  4728.1 1812.08  4830.2 1811.35  4879.5 1812.21  4893.7 1810.99    4901 1811.13
  4907.9 1809.88  4915.2 1809.86  4936.2 1811.67  4994.5 1809.63  4994.7 1809.13
  4998.5 1809.63  5333.9 1813.21  5510.8 1815.04  5858.4 1820.21  5921.9 1820.98
#Mann= 8 ,-1 , 0
  3832.6    .035       0  3833.5     .07       0  4461.8    .035       0
  4728.1     .07       0  4994.5     .07       0  4998.5     .07       0
  5333.9    .045       0  5858.4     .07       0
Bank Sta=4994.5,4998.5
XS Rating Curve= 0 ,0
Exp/Cntr=0.3,0.1

Type RM Length L Ch R = 1 ,4496    ,198,198,198
BEGIN DESCRIPTION:
Mapping XS a3b70c67
END DESCRIPTION:
XS GIS Cut Line= 3
       1511997.7      6859495.74      1512284.18      6858653.69
      1512482.27      6857921.88
#Sta/Elev= 30
  4093.9 1815.75  4112.6 1816.16  4130.3 1815.84  4135.6 1815.26  4313.2 1813.73
  4323.9 1814.11  4412.6 1813.31    4444 1814.02  4475.3 1812.84  4532.8  1812.3
  4577.4 1812.56  4619.7 1811.66  4651.3 1811.75  4672.5 1811.05  4689.6 1811.44
  4767.5 1810.76  4841.2 1811.12    4852 1809.73  4877.8 1809.66  4883.7 1810.19
  4903.9 1808.88  4983.3 1808.69  5003.2 1808.11  5003.5 1807.61    5007 1807.61
  5007.2 1808.11  5188.3 1809.06  5292.5 1808.93  5631.6 1812.03  5741.5 1812.47
#Mann= 5 ,-1 , 0
  4093.9     .07       0  5003.2     .07       0  5007.2     .07       0
  5188.3    .035       0  5292.5     .07       0
Bank Sta=5003.2,5007.2
XS Rating Curve= 0 ,0
Exp/Cntr=0.3,0.1

Type RM Length L Ch R = 1 ,4298    ,863,863,863
BEGIN DESCRIPTION:
Mapping XS b92c2969
END DESCRIPTION:
XS GIS Cut Line= 3
      1512223.41       6859634.6      1512448.94      6858596.11
      1512586.74       6858014.1
#Sta/Elev= 30
  3937.3 1813.99  3963.9 1814.17  4051.6 1813.65  4476.2 1811.83  4506.9 1811.38
  4517.1 1811.67  4533.1 1811.28  4568.3 1811.41  4838.9 1809.03  4905.8 1808.52
  4936.7 1807.77  4960.1 1807.65  4987.8 1808.29    5000 1807.66  5003.9 1806.69
    5009 1806.96  5018.6 1806.47  5028.9 1806.53  5039.2 1807.63  5091.5 1806.29
  5091.8 1805.79  5095.3 1805.79  5095.5 1806.29  5130.7 1807.19  5203.6 1807.15
  5267.7 1808.18    5368 1808.66    5479 1810.18  5491.3 1809.98  5598.1 1810.88
#Mann= 5 ,-1 , 0
  3937.3     .07       0  4051.6    .045       0  4838.9     .07       0
  5091.5     .07       0  5095.5     .07       0
Bank Sta=5091.5,5095.5
XS Rating Curve= 0 ,0
Exp/Cntr=0.3,0.1

Type RM Length L Ch R = 1 ,3435    ,663,663,663
BEGIN DESCRIPTION:
Mapping XS 5a695acd
END DESCRIPTION:
XS GIS Cut Line= 4
      1512831.05      6859547.78      1513204.32      6858697.09
      1513195.63      6858571.22      1512661.78      6858020.01
#Sta/Elev= 30
  4061.6 1809.05  4203.1 1808.59  4214.2  1808.2  4231.9 1808.47    4389 1807.29
  4443.6 1807.74  4487.4 1806.24  4607.9 1805.81  4656.4 1804.44  4726.5 1804.65
  4778.7 1803.16  4784.1 1803.37    4791 1802.43  4791.3 1801.93  4794.8 1801.93
    4795 1802.43  4807.5  1803.6  4817.2  1803.4  4847.6 1804.02  4999.7 1803.13
  5115.9 1804.25  5154.8 1804.11  5338.7 1806.25  5458.9 1806.56  5579.2 1808.24
  5762.9 1809.24  5770.1 1808.91  5784.3 1809.44  5798.4 1809.22  5884.1 1810.23
#Mann= 5 ,-1 , 0
  4061.6    .045       0  4607.9     .07       0    4791    .045       0
    4795     .07       0  4817.2    .045       0
Bank Sta=4791,4795
XS Rating Curve= 0 ,0
Exp/Cntr=0.3,0.1

Type RM Length L Ch R = 1 ,2772    ,676,676,676
BEGIN DESCRIPTION:
Mapping XS 2e26d7e1
END DESCRIPTION:
XS GIS Cut Line= 4
       1513312.8      6859756.16      1513811.95      6858740.49
      1513807.61      6858540.84      1512982.95      6858128.51
#Sta/Elev= 30
  3815.9 1807.99  3943.8 1807.24    3981  1807.8  4011.2 1806.66  4101.1 1805.83
    4137 1806.13  4181.6 1804.94  4248.4  1804.2  4278.4 1804.52  4327.6 1803.55
  4370.9 1802.86    4427 1803.22  4443.9 1802.52  4516.9 1801.73  4809.1 1800.93
    4899 1801.21  4928.1 1800.65  4960.1 1801.03  4972.7 1800.52  4988.1 1799.63
  4988.4 1799.13  4991.9 1799.13  4992.1 1799.63  5004.9 1800.41  5351.5 1802.03
  5562.8 1804.31  5664.5 1804.58  5769.6 1806.13  5926.2 1806.51  6069.3 1808.15
#Mann= 7 ,-1 , 0
  3815.9    .045       0  4278.4     .07       0  4327.6    .045       0
  4972.7     .07       0  4988.1     .07       0  4992.1     .07       0
  5004.9    .045       0
Bank Sta=4988.1,4992.1
XS Rating Curve= 0 ,0
Exp/Cntr=0.3,0.1

Type RM Length L Ch R = 1 ,2096    ,546,546,546
BEGIN DESCRIPTION:
Mapping XS d9178e06
END DESCRIPTION:
XS GIS Cut Line= 4
      1513970.45      6859495.36      1514400.98       6858731.5
      1514380.15      6858533.59      1513488.88      6858287.36
#Sta/Elev= 30
  4028.3 1804.49  4104.4 1802.27  4140.1  1802.6  4169.4 1801.52  4206.9 1801.27
    4256 1801.77  4287.8 1800.41  4315.3 1799.99  4412.1 1800.39    4493 1799.36
  4573.9 1799.64  4682.2 1798.55    4714 1799.04  4757.4 1797.94  4828.8 1798.08
  4897.5 1797.07  4913.1 1797.45  4958.9 1797.75  4987.1 1796.67  4987.3 1796.17
  4990.8 1796.17  4991.1 1796.67  5202.9 1798.84    5317 1798.62  5332.1 1799.23
  5358.2 1799.17  5411.2 1799.42  5514.1 1801.24  5752.7 1801.87  6028.8 1803.95
#Mann= 5 ,-1 , 0
  4028.3    .045       0  4913.1     .07       0  4987.1     .07       0
  4991.1     .07       0  5358.2    .045       0
Bank Sta=4987.1,4991.1
XS Rating Curve= 0 ,0
Exp/Cntr=0.3,0.1

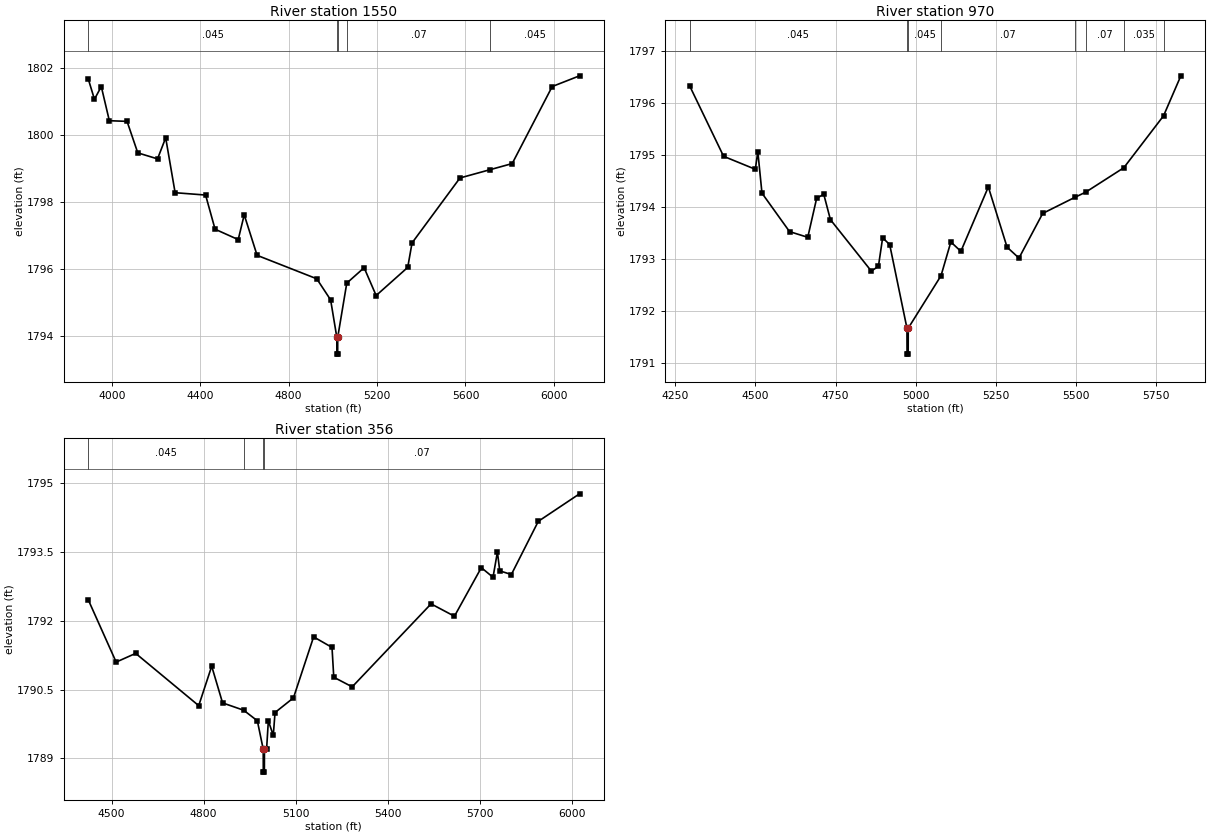
Type RM Length L Ch R = 1 ,1550    ,580,580,580
BEGIN DESCRIPTION:
Mapping XS d1151985
END DESCRIPTION:
XS GIS Cut Line= 4
      1514337.16      6859539.81      1514895.34      6858612.58
      1514887.53      6858518.83      1513864.12      6858298.49
#Sta/Elev= 30
    3893 1801.67  3921.1 1801.06  3952.1 1801.44  3988.5 1800.42  4068.7  1800.4
  4117.2 1799.46  4206.6 1799.28  4243.5 1799.91  4286.2 1798.27  4424.1  1798.2
    4467 1797.18  4571.7 1796.87  4598.9 1797.61  4657.2  1796.4  4927.1  1795.7
  4989.9 1795.07    5018 1793.95  5018.3 1793.45  5021.8 1793.45    5022 1793.95
    5063 1795.57  5141.5 1796.03  5195.9  1795.2  5338.8 1796.04  5358.3 1796.77
  5575.2 1798.71  5712.7 1798.96  5811.6 1799.14  5992.6 1801.44  6116.2 1801.76
#Mann= 5 ,-1 , 0
    3893    .045       0    5018    .045       0    5022    .045       0
    5063     .07       0  5712.7    .045       0
Bank Sta=5018,5022
XS Rating Curve= 0 ,0
Exp/Cntr=0.3,0.1

Type RM Length L Ch R = 1 ,970     ,614,614,614
BEGIN DESCRIPTION:
Mapping XS 9f86a316
END DESCRIPTION:
XS GIS Cut Line= 3
      1514989.94      6859232.03       1515443.1      6858685.12
      1514734.74      6858265.84
#Sta/Elev= 30
  4294.4 1796.34  4400.6 1794.98  4499.6 1794.73  4507.4 1795.07  4520.4 1794.27
  4606.4 1793.53  4663.3 1793.42    4691 1794.17  4713.2 1794.25    4734 1793.76
  4861.6 1792.77  4883.8 1792.86    4897 1793.41    4919 1793.28  4972.9 1791.67
  4973.2 1791.17  4976.7 1791.17  4976.9 1791.67  5079.2 1792.68  5109.9 1793.33
  5141.2 1793.15  5226.9 1794.39  5285.4 1793.23  5322.5 1793.02  5396.6 1793.88
  5497.1 1794.19    5531 1794.29  5649.8 1794.76  5773.8 1795.76  5827.8 1796.53
#Mann= 8 ,-1 , 0
  4294.4    .045       0  4972.9    .045       0  4976.9    .045       0
  5079.2     .07       0  5497.1    .035       0    5531     .07       0
  5649.8    .035       0  5773.8     .07       0
Bank Sta=4972.9,4976.9
XS Rating Curve= 0 ,0
Exp/Cntr=0.3,0.1

Type RM Length L Ch R = 1 ,356     ,0,0,0
BEGIN DESCRIPTION:
MULBERRY CREEK TRIBUTARY 15_5 1.0
END DESCRIPTION:
XS GIS Cut Line= 3
      1515596.73      6859138.26       1516010.2      6858737.52
      1515109.88      6858250.29
#Sta/Elev= 30
  4424.2 1792.46  4515.1  1791.1  4578.7 1791.29  4783.9 1790.15  4826.2 1791.01
  4861.6 1790.21  4930.3 1790.05  4974.8 1789.82  4993.9  1789.2  4994.2  1788.7
  4997.7  1788.7  4997.9  1789.2  5004.9  1789.2  5010.6 1789.82  5026.7  1789.5
  5032.4    1790  5092.4 1790.32    5158 1791.65  5217.9 1791.42  5223.6 1790.77
  5283.6 1790.56  5540.4 1792.37  5616.5  1792.1    5704 1793.16  5742.1 1792.95
  5756.4  1793.5    5764 1793.09  5801.8 1793.01  5889.5 1794.17  6023.7 1794.77
#Mann= 4 ,-1 , 0
  4424.2    .045       0  4930.3     .07       0  4993.9    .045       0
  4997.9     .07       0
Bank Sta=4993.9,4997.9
XS Rating Curve= 0 ,0
Exp/Cntr=0.3,0.1

Chan Stop Cuts=-1
Use User Specified Reach Order=0
Composite Channel Slope=5