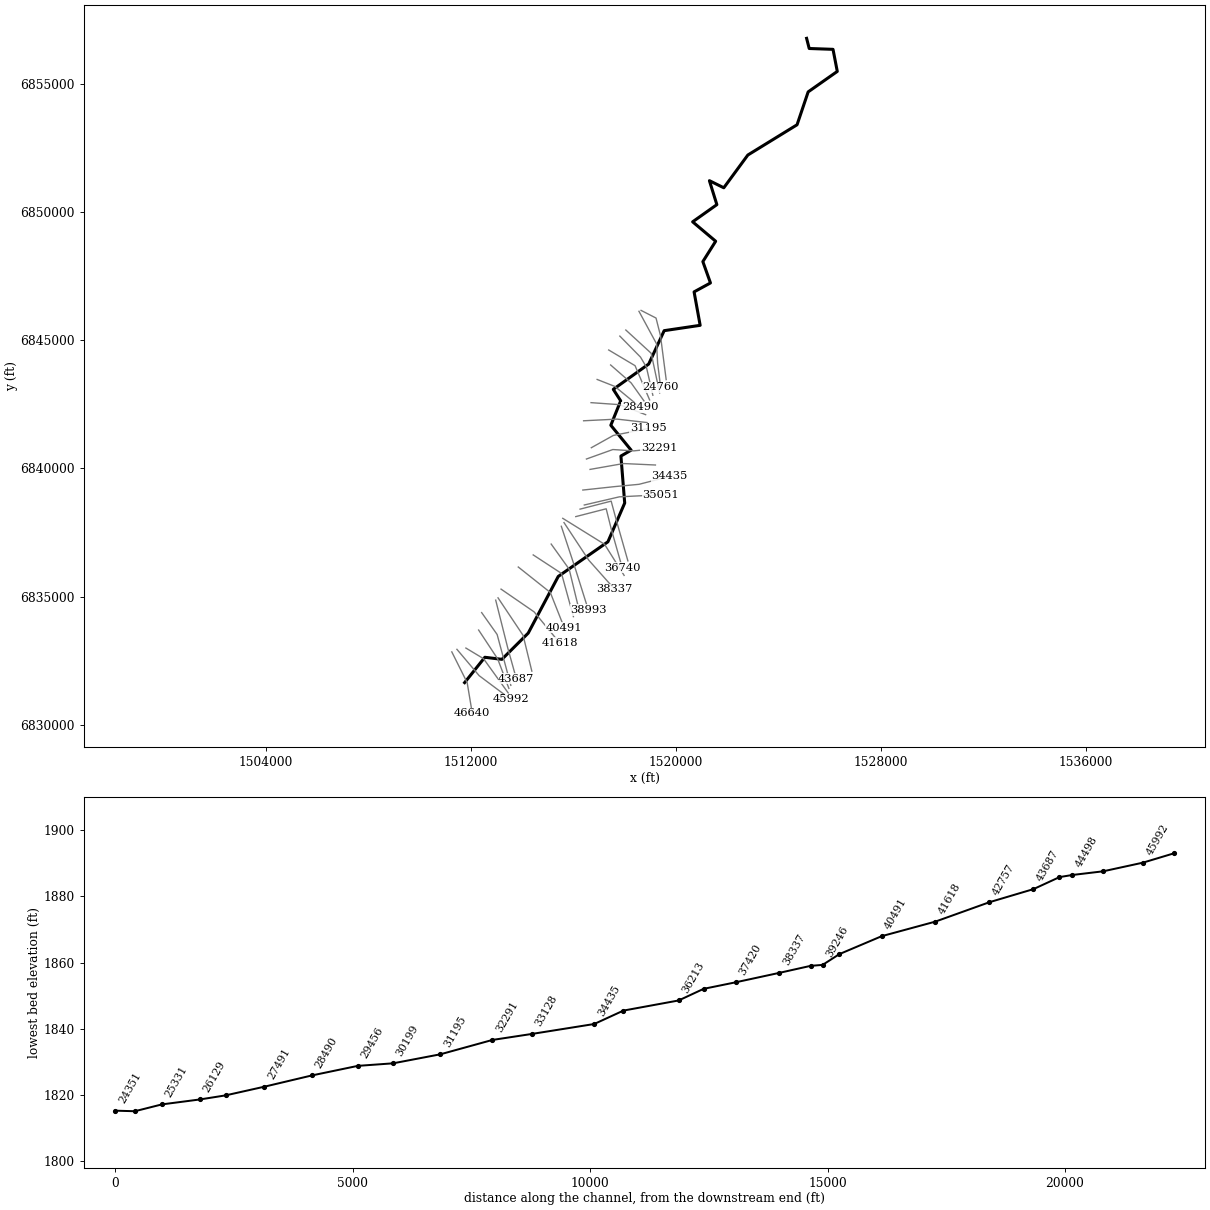
--- MULBERRY CREEK TRIBUTARY 16.prj (project) ---

Proj Title=MULBERRY CREEK TRIBUTARY 16 Base Level Engineering
Current Plan=p01
Default Exp/Contr=0.3,0.1
English Units
Geom File=g01
Flow File=f01
Plan File=p01
BEGIN DESCRIPTION:
MULBERRY CREEK TRIBUTARY 16
END DESCRIPTION:

--- MULBERRY CREEK TRIBUTARY 16.p01 (plan) ---

Plan Title=Multiple Run
Short Identifier=Multiple
Geom File=g01
Flow File=f01
Subcritical Flow
K Sum by GR= 0
Std Step Tol= 0.01
Critical Tol= 0.01
Num of Std Step Trials= 20
Max Error Tol= 0.3
Flow Tol Ratio= 0.001
Split Flow NTrial= 30
Split Flow Tol= 0.02
Split Flow Ratio= 0.02
Log Output Level= 0
Friction Slope Method= 1
Unsteady Friction Slope Method= 2
Unsteady Bridges Friction Slope Method= 1
Parabolic Critical Depth
Global Vel Dist=  1 , 1 , 1
Global Log Level= 0
CheckData=True
Encroach Param= -1, 0, 0, 0
BEGIN DESCRIPTION:
Multiple Run
END DESCRIPTION:

--- MULBERRY CREEK TRIBUTARY 16.f01 (steady flow) ---

Flow Title=Multiple
Number of Profiles=7
Profile Names=10-year,25-year,50-year,1pct_min,100-year,1pct_plu,500-year
River Rch & RM= MULBERRY CREEK T,Reach-1,46640
     180     244     295     178     354     707     519
River Rch & RM= MULBERRY CREEK T,Reach-1,40491
     274     380     467     286     570    1137     860
River Rch & RM= MULBERRY CREEK T,Reach-1,36213
     326     455     562     345     689    1375    1050
River Rch & RM= MULBERRY CREEK T,Reach-1,31195
     409     577     717     443     884    1764    1362
River Rch & RM= MULBERRY CREEK T,Reach-1,24760
     444     627     780     482     962    1919    1483
River Rch & RM= MULBERRY CREEK T,Reach-1,17519
     469     664     827     511    1020    2035    1574
River Rch & RM= MULBERRY CREEK T,Reach-1,12475
     493     698     870     538    1074    2142    1658
River Rch & RM= MULBERRY CREEK T,Reach-1,6908
     530     752     938     581    1160    2314    1797
Boundary for River Rch & Prof#=MULBERRY CREEK T,Reach-1,1
Up Type=0
Dn Type=3
Dn Slope=0.005
Boundary for River Rch & Prof#=MULBERRY CREEK T,Reach-1,2
Up Type=0
Dn Type=3
Dn Slope=0.005
Boundary for River Rch & Prof#=MULBERRY CREEK T,Reach-1,3
Up Type=0
Dn Type=3
Dn Slope=0.005
Boundary for River Rch & Prof#=MULBERRY CREEK T,Reach-1,4
Up Type=0
Dn Type=3
Dn Slope=0.005
Boundary for River Rch & Prof#=MULBERRY CREEK T,Reach-1,5
Up Type=0
Dn Type=3
Dn Slope=0.005
Boundary for River Rch & Prof#=MULBERRY CREEK T,Reach-1,6
Up Type=0
Dn Type=3
Dn Slope=0.005
Boundary for River Rch & Prof#=MULBERRY CREEK T,Reach-1,7
Up Type=0
Dn Type=3
Dn Slope=0.005

--- MULBERRY CREEK TRIBUTARY 16.g01 (geometry) ---

Geom Title=Existing Conditions

River Reach=MULBERRY CREEK T,Reach-1
Reach XY= 30
      1511755.00      6831638.00      1512545.21      6832627.57
      1513211.69      6832547.29      1514238.37      6833571.29
      1515410.04      6835782.92      1517349.48      6837135.57
      1518004.14      6838648.31      1517856.87      6840482.31
      1518255.50      6840712.96      1517462.48      6841684.43
      1517847.47      6842638.01      1517558.53      6843086.54
      1518941.90      6844074.76      1519545.30      6845377.26
      1520949.61      6845585.56      1520712.75      6846891.02
      1521351.91      6847239.63      1521054.95      6848072.66
      1521555.10      6848867.90      1520656.22      6849625.97
      1521601.84      6850296.34      1521310.26      6851232.59
      1521872.13      6850954.20      1522810.44      6852232.75
      1524732.14      6853414.16      1525165.47      6854697.85
      1526302.37      6855496.48      1526135.60      6856358.66
      1525206.22      6856391.43      1525105.00      6856788.00

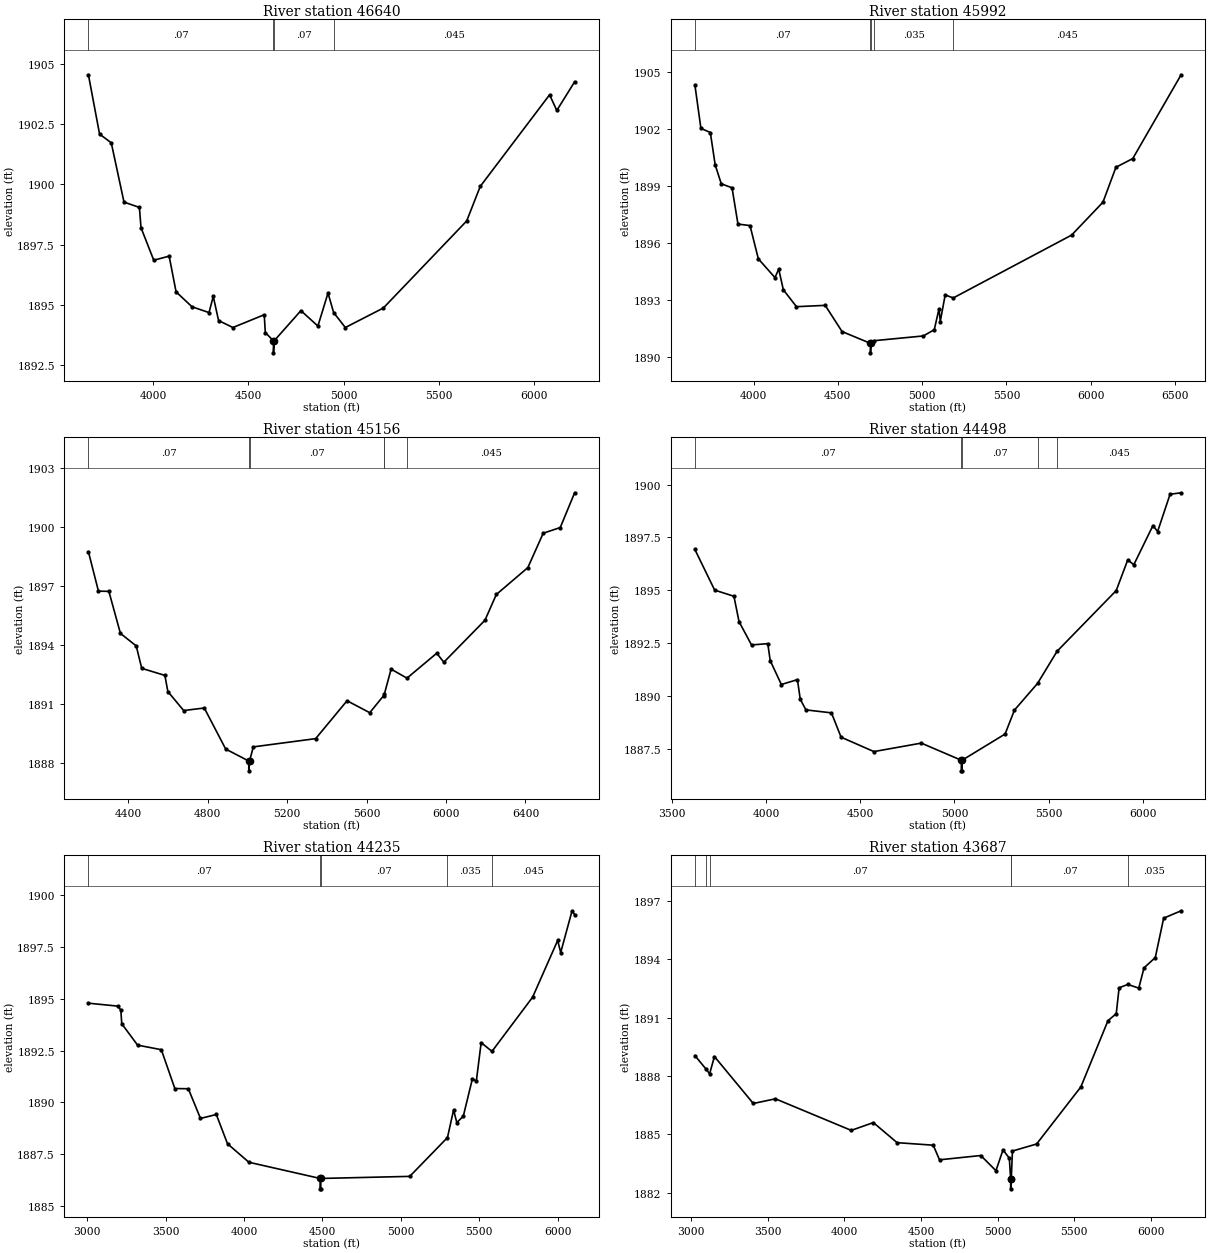
Type RM Length L Ch R = 1,46640,648,648,648
BEGIN DESCRIPTION:
MULBERRY CREEK TRIBUTARY 16 64.0
END DESCRIPTION:
XS GIS Cut Line= 3
      1511255.01      6832837.97      1511855.00      6831638.00
      1512055.01      6830437.96
#Sta/Elev= 30
  3657.9 1904.54  3716.6 1902.08  3778.1 1901.72  3845.1 1899.26  3926.2 1899.04
  3934.6 1898.20  4001.7 1896.85  4082.7 1897.02  4119.1 1895.54  4202.9 1894.92
  4292.4 1894.68  4314.7 1895.35  4342.7 1894.35  4418.1 1894.06  4583.0 1894.59
  4588.6 1893.85  4631.4 1893.51  4631.6 1893.01  4635.4 1893.51  4775.9 1894.76
  4865.3 1894.12  4918.5 1895.49  4948.1 1894.68  5009.6 1894.06  5209.9 1894.87
  5648.3 1898.48  5719.3 1899.91  6084.3 1903.71  6122.3 1903.06  6216.1 1904.25
#Mann=4,-1,0
  3657.9    0.07       0  4631.4   0.045       0  4635.4    0.07       0
  4948.1   0.045       0
Bank Sta=4631.4,4635.4
Exp/Cntr=0.3,0.1

Type RM Length L Ch R = 1,45992,836,836,836
BEGIN DESCRIPTION:
MULBERRY CREEK TRIBUTARY 16 62.0
END DESCRIPTION:
XS GIS Cut Line= 3
      1511455.00      6832938.00      1512324.83      6831908.07
      1513555.02      6830987.99
#Sta/Elev= 30
  3651.9 1904.32  3687.6 1902.03  3743.6 1901.81  3772.2 1900.11  3808.5 1899.11
  3872.3 1898.90  3907.4 1896.99  3978.9 1896.91  4028.3 1895.16  4127.1 1894.17
  4149.2 1894.62  4176.6 1893.53  4254.6 1892.64  4424.9 1892.71  4525.0 1891.33
  4693.3 1890.71  4693.5 1890.21  4697.3 1890.71  4716.0 1890.85  5007.5 1891.10
  5072.1 1891.43  5100.1 1892.53  5107.5 1891.86  5136.7 1893.26  5184.6 1893.10
  5886.8 1896.41  6072.5 1898.14  6149.6 1899.98  6249.6 1900.44  6536.2 1904.85
#Mann=5,-1,0
  3651.9    0.07       0  4693.3   0.035       0  4697.3    0.07       0
  4716.0   0.035       0  5184.6   0.045       0
Bank Sta=4693.3,4697.3
Exp/Cntr=0.3,0.1

Type RM Length L Ch R = 1,45156,658,658,658
BEGIN DESCRIPTION:
MULBERRY CREEK TRIBUTARY 16 61.0
END DESCRIPTION:
XS GIS Cut Line= 3
      1511804.97      6832988.02      1512491.62      6832574.79
      1513455.02      6831237.97
#Sta/Elev= 30
  4198.6 1898.76  4249.1 1896.75  4301.6 1896.74  4359.8 1894.60  4439.5 1893.96
  4467.1 1892.82  4583.8 1892.46  4598.7 1891.64  4678.4 1890.67  4782.2 1890.80
  4890.1 1888.71  5006.3 1888.10  5006.5 1887.60  5010.3 1888.10  5029.2 1888.82
  5343.3 1889.24  5501.4 1891.17  5615.7 1890.56  5685.0 1891.42  5689.7 1891.52
  5723.3 1892.78  5803.3 1892.32  5953.2 1893.59  5988.8 1893.13  6196.2 1895.27
  6253.3 1896.58  6412.1 1897.95  6489.5 1899.70  6575.4 1899.99  6647.8 1901.76
#Mann=6,-1,0
  4198.6    0.07       0  5006.3    0.07       0  5010.3    0.07       0
  5685.0   0.035       0  5689.7    0.07       0  5803.3   0.045       0
Bank Sta=5006.3,5010.3
Exp/Cntr=0.3,0.1

Type RM Length L Ch R = 1,44498,263,263,263
BEGIN DESCRIPTION:
Mapping XS 4fbaa466
END DESCRIPTION:
XS GIS Cut Line= 3
      1512302.43      6833691.03      1513045.49      6832566.03
      1513483.01      6831413.21
#Sta/Elev= 30
  3621.8 1896.93  3726.8 1895.01  3829.1 1894.72  3856.2 1893.52  3922.4 1892.42
  4008.9 1892.48  4021.7 1891.68  4080.8 1890.55  4166.2 1890.78  4181.3 1889.85
  4211.4 1889.35  4346.8 1889.21  4398.0 1888.06  4572.2 1887.38  4823.9 1887.78
  5036.3 1886.97  5036.5 1886.47  5040.0 1886.47  5040.3 1886.97  5268.7 1888.21
  5318.3 1889.34  5440.9 1890.60  5544.6 1892.12  5858.7 1894.99  5919.9 1896.44
  5952.0 1896.21  6053.6 1898.06  6078.4 1897.78  6144.5 1899.54  6203.1 1899.61
#Mann=5,-1,0
  3621.8    0.07       0  5036.3    0.07       0  5040.3    0.07       0
  5440.9   0.035       0  5544.6   0.045       0
Bank Sta=5036.3,5040.3
Exp/Cntr=0.3,0.1

Type RM Length L Ch R = 1,44235,548,548,548
BEGIN DESCRIPTION:
Mapping XS e4a903d0
END DESCRIPTION:
XS GIS Cut Line= 3
      1512420.50      6834371.58      1513024.66      6833517.42
      1513559.15      6831532.14
#Sta/Elev= 30
  3006.8 1894.78  3192.6 1894.64  3213.5 1894.45  3219.6 1893.79  3320.6 1892.76
  3472.0 1892.54  3558.2 1890.67  3644.3 1890.66  3721.8 1889.23  3822.8 1889.42
  3894.2 1888.01  4030.8 1887.12  4485.4 1886.34  4485.6 1885.84  4489.1 1885.84
  4489.4 1886.34  5057.0 1886.44  5297.7 1888.31  5336.6 1889.64  5357.3 1889.03
  5398.7 1889.34  5457.0 1891.15  5481.6 1891.02  5512.6 1892.88  5581.6 1892.46
  5840.9 1895.07  6000.7 1897.80  6020.1 1897.22  6092.6 1899.23  6109.0 1899.04
#Mann=5,-1,0
  3006.8    0.07       0  4485.4    0.07       0  4489.4    0.07       0
  5297.7   0.035       0  5581.6   0.045       0
Bank Sta=4485.4,4489.4
Exp/Cntr=0.3,0.1

Type RM Length L Ch R = 1,43687,930,930,930
BEGIN DESCRIPTION:
Mapping XS 1f0bae6c
END DESCRIPTION:
XS GIS Cut Line= 3
      1512969.10      6834857.71      1513441.32      6832982.70
      1513774.64      6831788.30
#Sta/Elev= 30
  3023.5 1889.05  3095.9 1888.36  3119.6 1888.11  3151.1 1889.00  3404.8 1886.59
  3549.1 1886.83  4044.1 1885.21  4188.5 1885.61  4343.2 1884.58  4579.2 1884.45
  4620.3 1883.70  4889.7 1883.92  4988.6 1883.14  5034.6 1884.21  5076.1 1883.78
  5084.5 1882.71  5084.8 1882.21  5088.5 1882.71  5096.3 1884.15  5253.8 1884.51
  5542.8 1887.44  5719.8 1890.84  5773.8 1891.20  5792.5 1892.53  5849.4 1892.70
  5920.8 1892.51  5955.0 1893.55  6028.6 1894.08  6083.2 1896.10  6197.1 1896.48
#Mann=6,-1,0
  3023.5    0.07       0  3095.9   0.045       0  3119.6    0.07       0
  5084.5    0.07       0  5088.5    0.07       0  5849.4   0.035       0
Bank Sta=5084.5,5088.5
Exp/Cntr=0.3,0.1

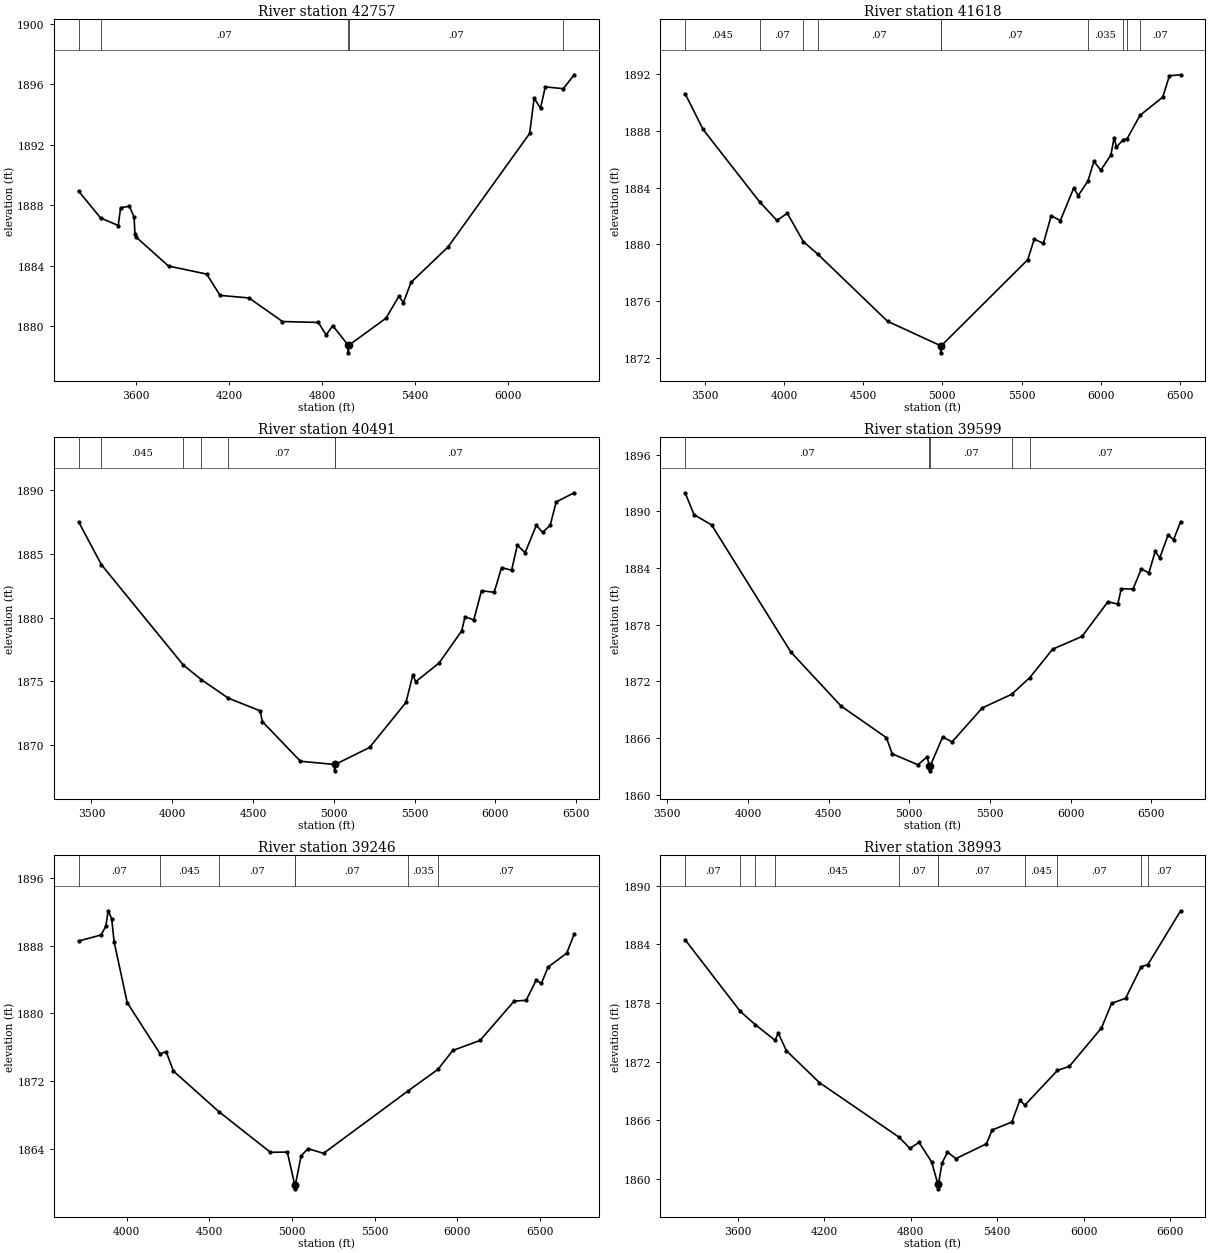
Type RM Length L Ch R = 1,42757,1139,1139,1139
BEGIN DESCRIPTION:
Mapping XS 9630f368
END DESCRIPTION:
XS GIS Cut Line= 3
      1513059.39      6834947.96      1514038.54      6833482.70
      1514378.82      6832086.88
#Sta/Elev= 30
  3228.5 1888.93  3370.4 1887.16  3484.3 1886.66  3499.3 1887.83  3556.4 1887.94
  3586.4 1887.21  3592.4 1886.07  3601.3 1885.88  3808.7 1883.98  4054.9 1883.45
  4142.0 1882.04  4328.2 1881.87  4544.5 1880.31  4775.7 1880.25  4826.8 1879.42
  4868.8 1880.04  4968.9 1878.74  4969.2 1878.24  4972.9 1878.74  5212.5 1880.53
  5295.9 1881.98  5325.0 1881.56  5374.1 1882.90  5613.2 1885.24  6140.1 1892.75
  6169.0 1895.08  6210.2 1894.42  6241.1 1895.83  6357.1 1895.71  6427.5 1896.63
#Mann=5,-1,0
  3228.5   0.045       0  3370.4    0.07       0  4968.9    0.07       0
  4972.9    0.07       0  6357.1   0.035       0
Bank Sta=4968.9,4972.9
Exp/Cntr=0.3,0.1

Type RM Length L Ch R = 1,41618,1127,1127,1127
BEGIN DESCRIPTION:
Mapping XS 26887e7e
END DESCRIPTION:
XS GIS Cut Line= 3
      1513177.41      6835288.26      1514469.10      6834399.36
      1515460.29      6833193.30
#Sta/Elev= 30
  3375.7 1890.61  3489.5 1888.09  3845.9 1883.00  3955.5 1881.69  4021.1 1882.19
  4122.4 1880.20  4214.0 1879.31  4654.2 1874.59  4989.6 1872.87  4989.8 1872.37
  4993.6 1872.87  5539.0 1878.92  5580.6 1880.37  5638.0 1880.07  5687.5 1882.02
  5744.9 1881.68  5829.6 1883.96  5858.3 1883.44  5918.9 1884.45  5957.3 1885.85
  6000.4 1885.22  6064.2 1886.29  6085.0 1887.52  6099.4 1886.85  6141.1 1887.36
  6166.8 1887.44  6248.7 1889.09  6391.4 1890.36  6434.0 1891.87  6504.8 1891.94
#Mann=10,-1,0
  3375.7   0.045       0  3845.9    0.07       0  4122.4   0.045       0
  4214.0    0.07       0  4989.6    0.07       0  4993.6    0.07       0
  5918.9   0.035       0  6141.1    0.07       0  6166.8   0.035       0
  6248.7    0.07       0
Bank Sta=4989.6,4993.6
Exp/Cntr=0.3,0.1

Type RM Length L Ch R = 1,40491,892,892,892
BEGIN DESCRIPTION:
Mapping XS d752dfdf
END DESCRIPTION:
XS GIS Cut Line= 3
      1513849.75      6836151.09      1515099.74      6835158.04
      1515641.40      6833790.01
#Sta/Elev= 30
  3420.5 1887.50  3561.7 1884.14  4068.1 1876.28  4180.2 1875.13  4348.2 1873.67
  4543.7 1872.69  4558.2 1871.84  4793.7 1868.73  5004.7 1868.48  5005.0 1867.98
  5008.7 1868.48  5221.3 1869.81  5447.0 1873.34  5490.2 1875.53  5506.5 1874.96
  5651.6 1876.43  5791.4 1878.94  5812.9 1880.06  5866.7 1879.81  5914.6 1882.10
  5992.9 1881.98  6038.7 1883.91  6101.0 1883.71  6136.1 1885.67  6184.8 1885.08
  6253.8 1887.23  6292.9 1886.68  6339.9 1887.23  6376.7 1889.06  6488.3 1889.78
#Mann=7,-1,0
  3420.5    0.07       0  3561.7   0.045       0  4068.1    0.07       0
  4180.2   0.045       0  4348.2    0.07       0  5004.7    0.07       0
  5008.7    0.07       0
Bank Sta=5004.7,5008.7
Exp/Cntr=0.3,0.1

Type RM Length L Ch R = 1,39599,353,353,353
BEGIN DESCRIPTION:
Mapping XS fb3d1a13
END DESCRIPTION:
XS GIS Cut Line= 3
      1514433.12      6836623.29      1515537.24      6835901.10
      1516002.52      6834213.61
#Sta/Elev= 30
  3610.8 1891.96  3666.5 1889.64  3775.1 1888.56  4266.6 1875.10  4577.3 1869.40
  4857.7 1866.06  4893.9 1864.35  5053.0 1863.19  5109.7 1864.03  5124.7 1863.05
  5125.0 1862.55  5129.1 1863.05  5206.1 1866.12  5265.3 1865.62  5452.0 1869.21
  5634.4 1870.65  5746.0 1872.41  5887.7 1875.42  6069.2 1876.76  6230.0 1880.43
  6291.0 1880.19  6313.0 1881.81  6385.6 1881.78  6437.5 1883.92  6483.6 1883.48
  6523.1 1885.75  6551.6 1885.09  6603.4 1887.52  6636.6 1886.98  6680.6 1888.91
#Mann=5,-1,0
  3610.8    0.07       0  5124.7    0.07       0  5129.1    0.07       0
  5634.4   0.035       0  5746.0    0.07       0
Bank Sta=5124.7,5129.1
Exp/Cntr=0.3,0.1

Type RM Length L Ch R = 1,39246,253,253,253
BEGIN DESCRIPTION:
Mapping XS 4a898936
END DESCRIPTION:
XS GIS Cut Line= 3
      1515134.48      6837046.90      1515835.85      6836067.77
      1516259.46      6834324.72
#Sta/Elev= 30
  3709.0 1888.53  3843.9 1889.24  3873.4 1890.25  3888.1 1892.10  3909.0 1891.16
  3923.7 1888.45  4002.9 1881.26  4202.2 1875.21  4238.2 1875.49  4282.4 1873.19
  4556.7 1868.41  4869.6 1863.60  4971.6 1863.63  5016.3 1859.79  5016.6 1859.29
  5020.7 1859.79  5055.1 1863.18  5096.8 1864.03  5191.0 1863.48  5703.2 1870.86
  5882.4 1873.38  5973.2 1875.62  6137.8 1876.80  6343.6 1881.43  6416.9 1881.54
  6477.4 1883.92  6508.3 1883.52  6549.5 1885.46  6662.3 1887.10  6707.2 1889.35
#Mann=7,-1,0
  3709.0    0.07       0  4202.2   0.045       0  4556.7    0.07       0
  5016.3    0.07       0  5020.7    0.07       0  5703.2   0.035       0
  5882.4    0.07       0
Bank Sta=5016.3,5020.7
Exp/Cntr=0.3,0.1

Type RM Length L Ch R = 1,38993,656,656,656
BEGIN DESCRIPTION:
Mapping XS 85efaf73
END DESCRIPTION:
XS GIS Cut Line= 3
      1515530.30      6837741.38      1516078.91      6836081.65
      1516585.46      6834471.81
#Sta/Elev= 30
  3235.8 1884.47  3618.6 1877.14  3722.1 1875.79  3859.6 1874.19  3881.8 1874.92
  3937.8 1873.13  4166.2 1869.87  4718.3 1864.29  4794.5 1863.14  4858.0 1863.75
  4945.6 1861.73  4987.9 1859.50  4988.3 1859.00  4992.4 1859.50  5017.3 1861.64
  5055.0 1862.75  5113.5 1862.09  5324.5 1863.60  5365.1 1865.02  5501.4 1865.83
  5556.4 1868.05  5591.7 1867.56  5817.6 1871.11  5899.7 1871.52  6122.7 1875.45
  6193.3 1877.97  6289.8 1878.48  6398.3 1881.71  6443.9 1881.92  6671.5 1887.43
#Mann=11,-1,0
  3235.8    0.07       0  3618.6   0.045       0  3722.1    0.07       0
  3859.6   0.045       0  4718.3    0.07       0  4987.9    0.07       0
  4992.4    0.07       0  5591.7   0.045       0  5817.6    0.07       0
  6398.3   0.045       0  6443.9    0.07       0
Bank Sta=4987.9,4992.4
Exp/Cntr=0.3,0.1

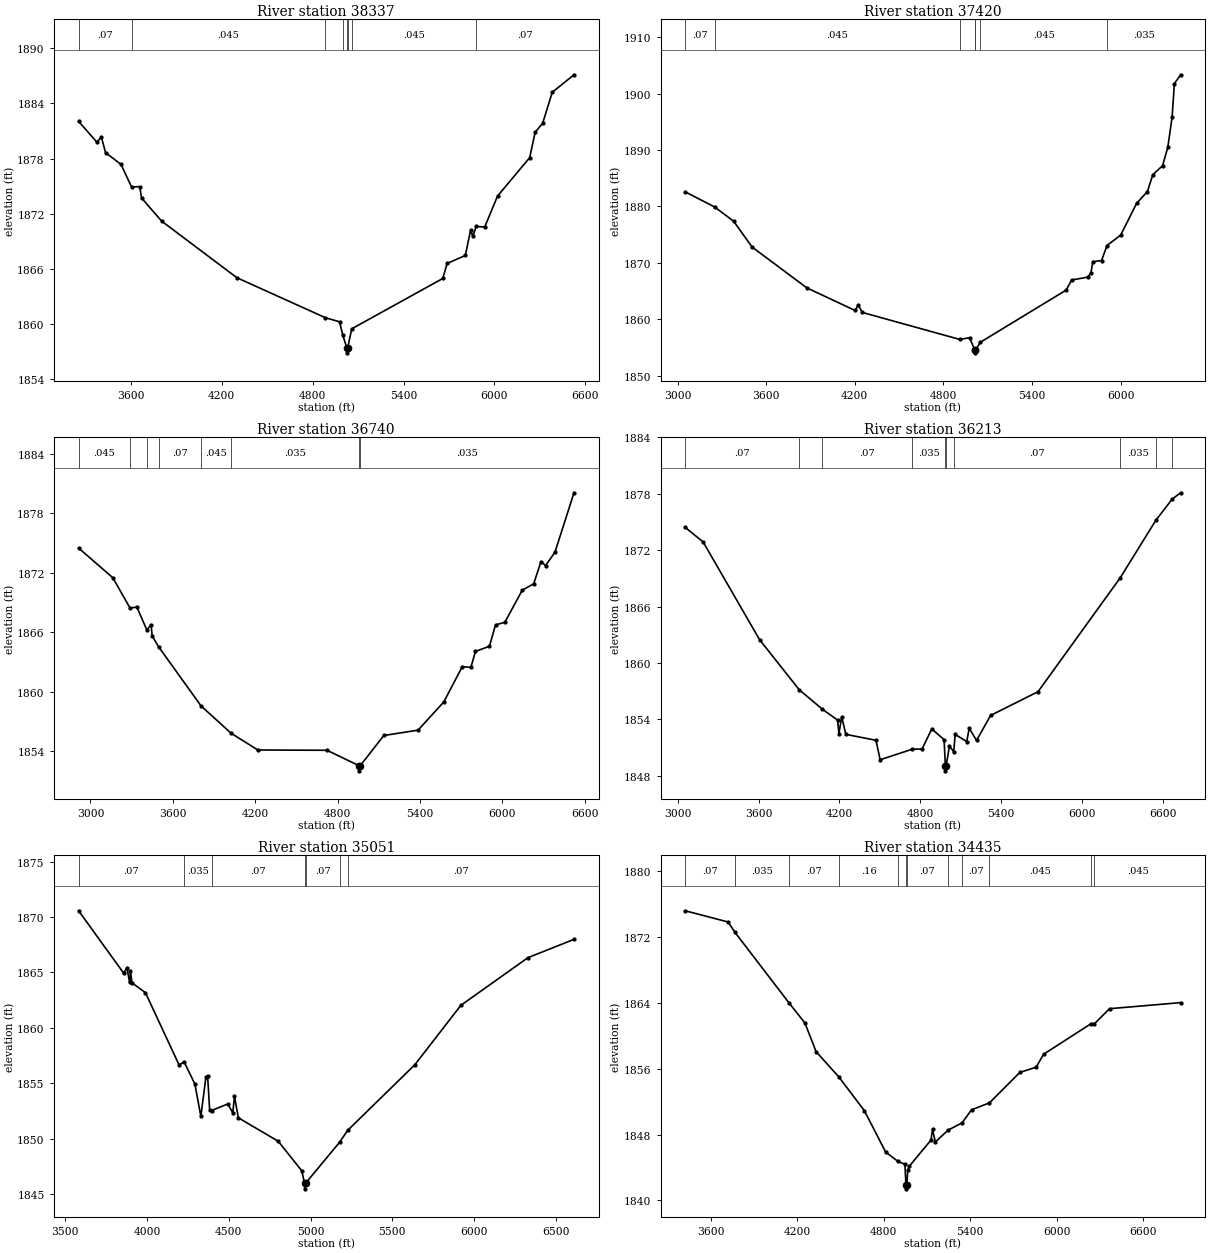
Type RM Length L Ch R = 1,38337,917,917,917
BEGIN DESCRIPTION:
Mapping XS bcb8c7cc
END DESCRIPTION:
XS GIS Cut Line= 3
      1515634.90      6837885.04      1516600.18      6836419.76
      1517607.15      6835287.79
#Sta/Elev= 30
  3255.2 1882.04  3375.5 1879.78  3405.6 1880.33  3432.7 1878.65  3535.1 1877.36
  3604.5 1874.91  3658.6 1874.95  3670.8 1873.71  3802.5 1871.21  4300.0 1865.05
  4883.6 1860.71  4977.6 1860.26  4998.8 1858.81  5026.2 1857.39  5026.5 1856.89
  5030.7 1857.39  5057.9 1859.50  5658.9 1864.97  5687.4 1866.60  5807.8 1867.47
  5842.9 1870.25  5857.1 1869.54  5879.6 1870.62  5935.7 1870.56  6020.2 1873.92
  6232.6 1878.10  6268.5 1880.86  6317.9 1881.82  6381.4 1885.20  6524.9 1887.10
#Mann=8,-1,0
  3255.2    0.07       0  3604.5   0.045       0  4883.6    0.07       0
  4998.8   0.035       0  5026.2   0.035       0  5030.7   0.035       0
  5057.9   0.045       0  5879.6    0.07       0
Bank Sta=5026.2,5030.7
Exp/Cntr=0.3,0.1

Type RM Length L Ch R = 1,37420,680,680,680
BEGIN DESCRIPTION:
Mapping XS 9e06824f
END DESCRIPTION:
XS GIS Cut Line= 3
      1515586.32      6838051.69      1517218.23      6837037.82
      1517980.93      6835824.43
#Sta/Elev= 30
  3052.3 1882.59  3252.5 1879.88  3380.4 1877.36  3504.3 1872.81  3874.8 1865.57
  4202.2 1861.55  4223.4 1862.50  4251.6 1861.20  4910.4 1856.42  4978.0 1856.72
  5012.0 1854.54  5012.4 1854.04  5017.0 1854.54  5051.1 1855.93  5631.7 1865.17
  5668.2 1866.95  5776.5 1867.46  5798.9 1868.18  5811.9 1870.20  5871.0 1870.41
  5908.1 1873.07  6000.9 1874.93  6108.7 1880.56  6181.7 1882.65  6218.2 1885.63
  6284.4 1887.23  6319.8 1890.50  6349.0 1895.87  6364.3 1901.79  6406.7 1903.35
#Mann=7,-1,0
  3052.3    0.07       0  3252.5   0.045       0  4910.4    0.07       0
  5012.0    0.07       0  5017.0    0.07       0  5051.1   0.045       0
  5908.1   0.035       0
Bank Sta=5012,5017
Exp/Cntr=0.3,0.1

Type RM Length L Ch R = 1,36740,527,527,527
BEGIN DESCRIPTION:
Mapping XS 1cda7057
END DESCRIPTION:
XS GIS Cut Line= 4
      1516094.26      6838118.59      1517281.73      6838424.14
      1517483.12      6837618.58      1517906.73      6836125.51
#Sta/Elev= 30
  2913.6 1874.49  3162.2 1871.51  3288.3 1868.45  3337.7 1868.55  3411.0 1866.23
  3441.0 1866.78  3449.6 1865.64  3495.8 1864.55  3805.5 1858.59  4024.9 1855.83
  4219.2 1854.15  4723.3 1854.12  4958.8 1852.55  4959.2 1852.05  4964.0 1852.55
  5136.8 1855.61  5386.5 1856.15  5573.6 1858.99  5708.7 1862.55  5771.1 1862.47
  5804.4 1864.08  5906.1 1864.60  5950.4 1866.75  6018.3 1867.01  6145.3 1870.25
  6228.5 1870.89  6281.6 1873.12  6315.5 1872.73  6383.4 1874.07  6522.1 1880.06
#Mann=8,-1,0
  2913.6   0.045       0  3288.3    0.07       0  3411.0   0.045       0
  3495.8    0.07       0  3805.5   0.045       0  4024.9   0.035       0
  4958.8   0.035       0  4964.0   0.035       0
Bank Sta=4958.8,4964
Exp/Cntr=0.3,0.1

Type RM Length L Ch R = 1,36213,1162,1162,1162
BEGIN DESCRIPTION:
Mapping XS 39111775
END DESCRIPTION:
XS GIS Cut Line= 4
      1516260.93      6838410.26      1517476.17      6838722.75
      1517670.62      6838000.53      1518128.44      6836391.20
#Sta/Elev= 30
  3056.4 1874.42  3188.8 1872.88  3607.8 1862.48  3902.2 1857.15  4072.5 1855.10
  4186.1 1853.93  4196.6 1852.50  4217.0 1854.27  4248.0 1852.41  4471.4 1851.78
  4502.5 1849.71  4742.3 1850.84  4813.2 1850.85  4885.7 1852.99  4976.8 1851.85
  4986.6 1849.03  4987.0 1848.53  4991.9 1849.03  5016.7 1851.18  5048.3 1850.56
  5059.1 1852.40  5144.9 1851.65  5163.5 1853.06  5217.7 1851.76  5321.7 1854.42
  5674.1 1856.95  6283.3 1869.05  6549.0 1875.20  6671.1 1877.46  6732.3 1878.11
#Mann=10,-1,0
  3056.4    0.07       0  3902.2   0.035       0  4072.5    0.07       0
  4742.3   0.035       0  4986.6   0.035       0  4991.9   0.035       0
  5048.3    0.07       0  6283.3   0.035       0  6549.0    0.07       0
  6671.1   0.035       0
Bank Sta=4986.6,4991.9
Exp/Cntr=0.3,0.1

Type RM Length L Ch R = 1,35051,616,616,616
BEGIN DESCRIPTION:
Mapping XS d603de28
END DESCRIPTION:
XS GIS Cut Line= 3
      1516427.42      6838572.10      1517792.02      6838889.81
      1519415.59      6838973.07
#Sta/Elev= 30
  3582.9 1870.57  3857.6 1864.95  3878.2 1865.41  3894.6 1864.10  3899.7 1865.15
  3909.0 1864.06  3991.1 1863.18  4196.5 1856.66  4228.0 1856.92  4293.2 1854.93
  4329.9 1852.01  4360.7 1855.57  4371.0 1855.68  4383.5 1852.59  4395.5 1852.54
  4494.2 1853.13  4525.0 1852.33  4535.3 1853.81  4559.0 1851.88  4802.2 1849.77
  4946.0 1847.11  4963.7 1845.97  4964.2 1845.47  4969.3 1845.97  5178.4 1849.69
  5226.3 1850.74  5637.8 1856.68  5918.2 1862.03  6328.7 1866.34  6609.7 1867.99
#Mann=7,-1,0
  3582.9    0.07       0  4228.0   0.035       0  4395.5    0.07       0
  4963.7    0.07       0  4969.3    0.07       0  5178.4   0.035       0
  5226.3    0.07       0
Bank Sta=4963.7,4969.3
Exp/Cntr=0.3,0.1

Type RM Length L Ch R = 1,34435,1307,1307,1307
BEGIN DESCRIPTION:
Mapping XS 941eb65c
END DESCRIPTION:
XS GIS Cut Line= 4
      1516370.16      6839155.44      1517625.35      6839290.86
      1518562.85      6839379.40      1519755.56      6839686.69
#Sta/Elev= 30
  3424.0 1875.17  3720.6 1873.81  3767.0 1872.59  4143.7 1863.98  4253.6 1861.55
  4331.3 1858.07  4490.6 1854.96  4666.0 1850.90  4813.7 1845.88  4898.4 1844.75
  4947.3 1844.39  4954.4 1841.91  4954.9 1841.41  4960.2 1841.91  4967.4 1843.70
  4977.4 1844.15  5128.1 1847.33  5138.9 1848.62  5158.2 1847.10  5246.4 1848.53
  5343.7 1849.42  5409.3 1851.00  5533.4 1851.85  5744.0 1855.54  5857.5 1856.18
  5909.2 1857.75  6239.2 1861.47  6261.6 1861.45  6366.4 1863.28  6859.8 1864.02
#Mann=12,-1,0
  3424.0    0.07       0  3767.0   0.035       0  4143.7    0.07       0
  4490.6    0.16       0  4898.4    0.07       0  4954.4    0.07       0
  4960.2    0.07       0  5246.4   0.045       0  5343.7    0.07       0
  5533.4   0.045       0  6239.2    0.07       0  6261.6   0.045       0
Bank Sta=4954.4,4960.2
Exp/Cntr=0.3,0.1

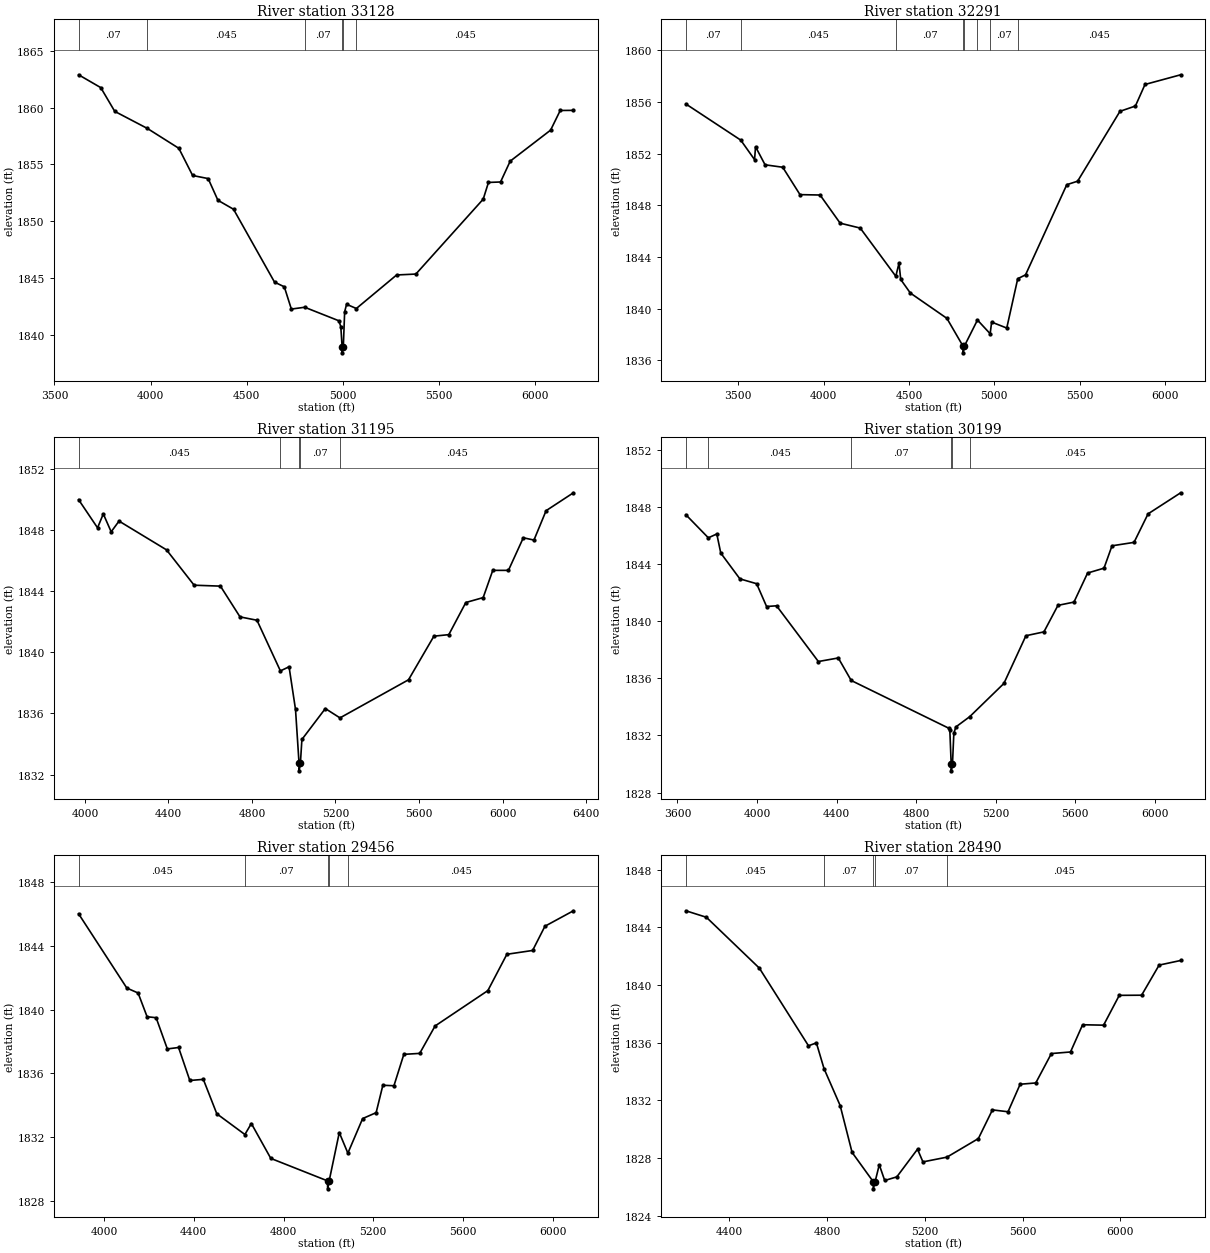
Type RM Length L Ch R = 1,33128,837,837,837
BEGIN DESCRIPTION:
Mapping XS b46785bb
END DESCRIPTION:
XS GIS Cut Line= 3
      1516651.40      6839961.00      1517953.47      6840190.16
      1519203.48      6840132.87
#Sta/Elev= 30
  3625.9 1862.88  3741.2 1861.75  3814.0 1859.66  3983.5 1858.16  4147.4 1856.41
  4219.0 1854.02  4299.7 1853.75  4350.5 1851.84  4431.7 1851.05  4644.9 1844.64
  4695.7 1844.23  4732.4 1842.27  4801.9 1842.43  4979.5 1841.24  4989.6 1840.73
  4996.6 1838.92  4997.1 1838.42  5002.6 1838.92  5009.6 1842.03  5019.6 1842.69
  5070.5 1842.32  5279.9 1845.27  5380.0 1845.35  5730.3 1851.94  5757.5 1853.41
  5820.4 1853.45  5870.5 1855.28  6080.7 1858.01  6130.8 1859.74  6199.3 1859.75
#Mann=6,-1,0
  3625.9    0.07       0  3983.5   0.045       0  4801.9    0.07       0
  4996.6    0.07       0  5002.6    0.07       0  5070.5   0.045       0
Bank Sta=4996.6,5002.6
Exp/Cntr=0.3,0.1

Type RM Length L Ch R = 1,32291,1096,1096,1096
BEGIN DESCRIPTION:
Mapping XS 9ed2afc4
END DESCRIPTION:
XS GIS Cut Line= 4
      1516510.76      6840367.24      1517542.02      6840737.04
      1518359.72      6840684.95      1519338.92      6840783.91
#Sta/Elev= 30
  3192.7 1855.86  3514.3 1853.06  3595.2 1851.55  3600.9 1852.55  3656.7 1851.15
  3760.2 1850.96  3861.4 1848.84  3979.0 1848.81  4096.7 1846.63  4214.4 1846.25
  4422.7 1842.52  4441.5 1843.53  4451.6 1842.27  4507.9 1841.22  4722.1 1839.26
  4817.4 1837.09  4817.9 1836.59  4823.6 1837.09  4901.2 1839.13  4975.5 1838.07
  4984.3 1838.97  5072.8 1838.51  5137.1 1842.33  5182.9 1842.63  5424.5 1849.61
  5487.9 1849.88  5736.1 1855.29  5826.5 1855.70  5882.8 1857.37  6091.8 1858.12
#Mann=8,-1,0
  3192.7    0.07       0  3514.3   0.045       0  4422.7    0.07       0
  4817.4    0.07       0  4823.6    0.07       0  4901.2   0.045       0
  4975.5    0.07       0  5137.1   0.045       0
Bank Sta=4817.4,4823.6
Exp/Cntr=0.3,0.1

Type RM Length L Ch R = 1,31195,996,996,996
BEGIN DESCRIPTION:
Mapping XS 62064515
END DESCRIPTION:
XS GIS Cut Line= 3
      1516701.71      6840808.20      1517561.11      6841287.38
      1518920.24      6841558.17
#Sta/Elev= 30
  3969.7 1849.97  4060.5 1848.13  4088.0 1849.04  4125.7 1847.87  4163.4 1848.57
  4390.8 1846.69  4523.0 1844.38  4649.0 1844.32  4742.8 1842.31  4824.0 1842.09
  4936.2 1838.78  4977.7 1839.05  5008.6 1836.26  5025.5 1832.75  5026.0 1832.25
  5032.0 1832.75  5039.2 1834.30  5151.4 1836.32  5221.5 1835.71  5549.8 1838.20
  5671.4 1841.05  5742.8 1841.15  5824.3 1843.25  5907.3 1843.57  5953.3 1845.35
  6028.3 1845.35  6099.6 1847.48  6150.6 1847.33  6208.7 1849.25  6339.5 1850.42
#Mann=5,-1,0
  3969.7   0.045       0  4936.2    0.07       0  5025.5    0.07       0
  5032.0    0.07       0  5221.5   0.045       0
Bank Sta=5025.5,5032
Exp/Cntr=0.3,0.1

Type RM Length L Ch R = 1,30199,743,743,743
BEGIN DESCRIPTION:
Mapping XS eca68566
END DESCRIPTION:
XS GIS Cut Line= 3
      1516399.69      6841859.43      1517706.08      6841924.54
      1518877.97      6841789.99
#Sta/Elev= 30
  3642.3 1847.49  3755.3 1845.87  3797.8 1846.14  3817.8 1844.80  3913.9 1842.99
  3998.1 1842.65  4048.1 1841.05  4098.2 1841.10  4308.4 1837.19  4408.6 1837.44
  4473.5 1835.86  4964.1 1832.51  4969.4 1832.36  4976.1 1830.02  4976.6 1829.52
  4982.7 1830.02  4989.5 1832.15  4999.6 1832.60  5069.3 1833.32  5241.1 1835.65
  5351.9 1839.00  5442.4 1839.27  5512.9 1841.13  5593.4 1841.36  5662.0 1843.40
  5744.4 1843.74  5784.7 1845.31  5895.4 1845.55  5965.9 1847.55  6129.9 1849.03
#Mann=6,-1,0
  3642.3    0.07       0  3755.3   0.045       0  4473.5    0.07       0
  4976.1    0.07       0  4982.7    0.07       0  5069.3   0.045       0
Bank Sta=4976.1,4982.7
Exp/Cntr=0.3,0.1

Type RM Length L Ch R = 1,29456,966,966,966
BEGIN DESCRIPTION:
Mapping XS 53d08f54
END DESCRIPTION:
XS GIS Cut Line= 3
      1516690.48      6842566.90      1517801.57      6842488.77
      1518820.75      6842098.45
#Sta/Elev= 30
  3886.7 1846.01  4101.7 1841.35  4151.9 1841.04  4192.0 1839.55  4232.2 1839.49
  4282.2 1837.53  4332.3 1837.62  4382.4 1835.55  4442.6 1835.62  4502.7 1833.46
  4627.9 1832.16  4656.6 1832.85  4743.3 1830.66  4996.1 1829.25  4996.6 1828.75
  5003.4 1829.25  5048.5 1832.28  5086.8 1830.99  5152.6 1833.16  5212.7 1833.53
  5242.7 1835.25  5292.1 1835.22  5336.2 1837.19  5406.9 1837.25  5475.4 1838.97
  5710.6 1841.19  5795.4 1843.47  5910.2 1843.71  5965.0 1845.23  6091.9 1846.20
#Mann=5,-1,0
  3886.7   0.045       0  4627.9    0.07       0  4996.1    0.07       0
  5003.4    0.07       0  5086.8   0.045       0
Bank Sta=4996.1,5003.4
Exp/Cntr=0.3,0.1

Type RM Length L Ch R = 1,28490,999,999,999
BEGIN DESCRIPTION:
Mapping XS 6ffeb5ac
END DESCRIPTION:
XS GIS Cut Line= 3
      1516928.55      6843472.30      1517623.04      6843198.84
      1518608.29      6842387.20
#Sta/Elev= 30
  4223.4 1845.16  4307.2 1844.71  4523.8 1841.18  4724.7 1835.79  4757.0 1835.99
  4788.3 1834.20  4854.2 1831.64  4902.9 1828.39  4989.3 1826.36  4989.8 1825.86
  4997.1 1826.36  5014.1 1827.53  5036.3 1826.44  5085.8 1826.69  5170.4 1828.61
  5192.6 1827.73  5290.8 1828.06  5419.3 1829.35  5476.7 1831.34  5540.5 1831.21
  5590.0 1833.12  5653.9 1833.21  5717.7 1835.25  5795.9 1835.36  5845.4 1837.25
  5931.1 1837.22  5995.3 1839.29  6086.6 1839.30  6158.2 1841.39  6246.3 1841.71
#Mann=5,-1,0
  4223.4   0.045       0  4788.3    0.07       0  4989.3    0.07       0
  4997.1    0.07       0  5290.8   0.045       0
Bank Sta=4989.3,4997.1
Exp/Cntr=0.3,0.1

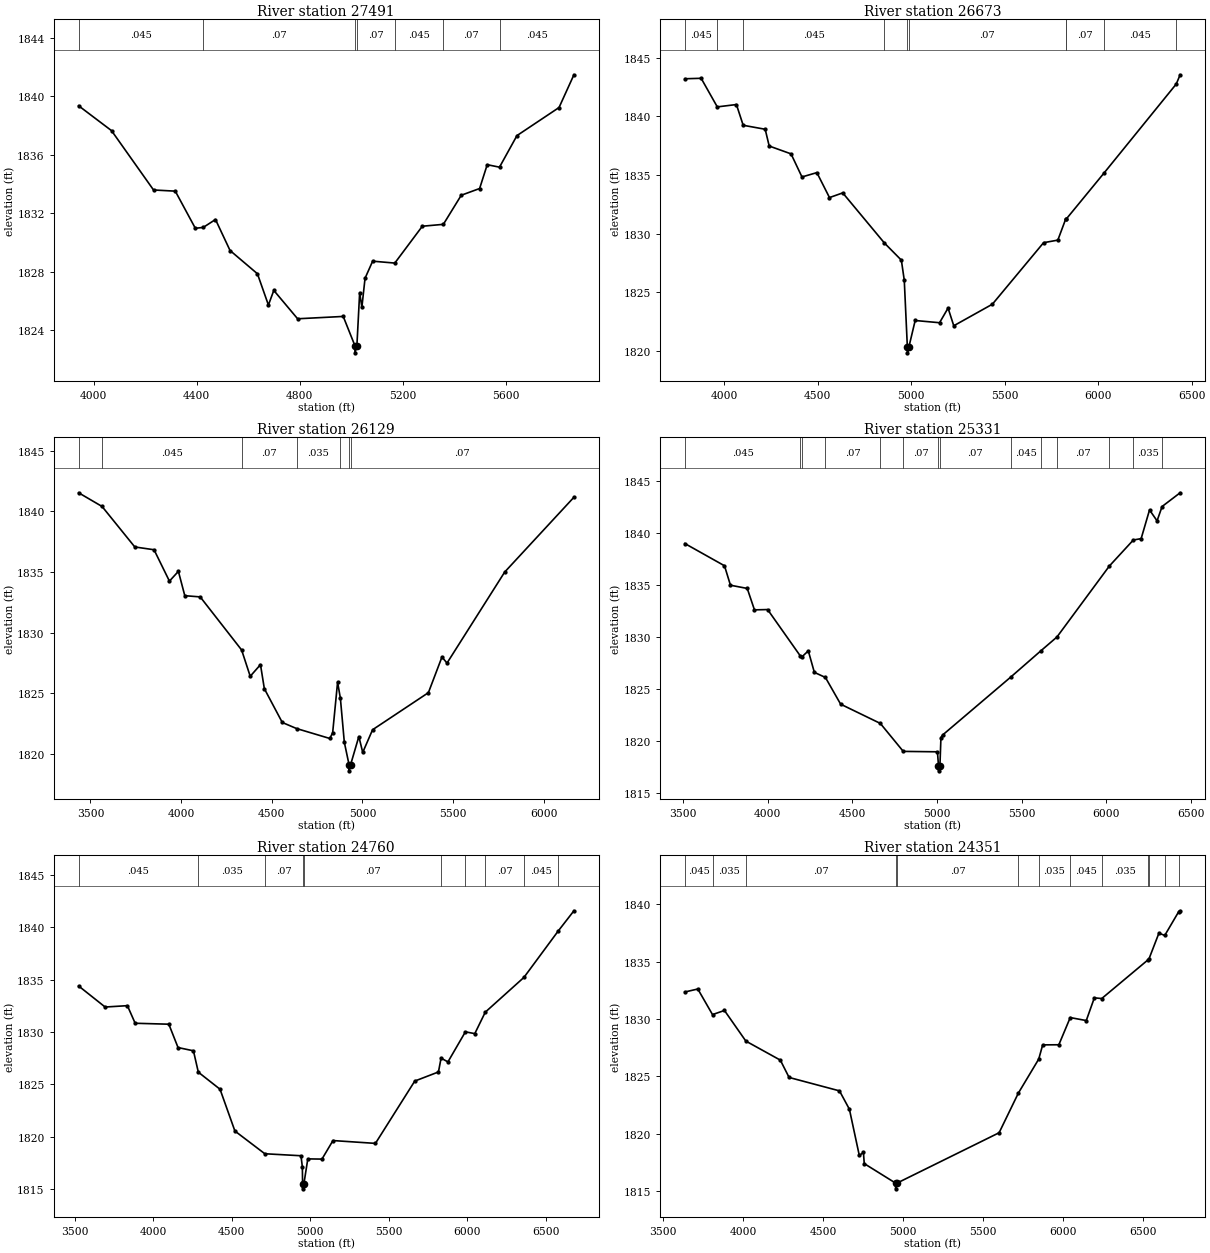
Type RM Length L Ch R = 1,27491,818,818,818
BEGIN DESCRIPTION:
MULBERRY CREEK TRIBUTARY 16 26.0
END DESCRIPTION:
XS GIS Cut Line= 3
      1517454.98      6844038.02      1518255.00      6843338.00
      1518755.01      6842637.98
#Sta/Elev= 30
  3941.1 1839.36  4068.8 1837.66  4232.0 1833.60  4316.5 1833.52  4394.3 1830.98
  4425.0 1831.04  4472.6 1831.58  4529.1 1829.46  4635.4 1827.87  4678.1 1825.73
  4699.0 1826.73  4791.5 1824.79  4968.6 1824.95  5013.7 1822.96  5014.2 1822.46
  5021.7 1822.96  5032.4 1826.58  5041.0 1825.58  5053.3 1827.56  5082.8 1828.73
  5168.8 1828.60  5275.7 1831.12  5357.4 1831.25  5426.9 1833.24  5498.2 1833.70
  5527.7 1835.33  5575.4 1835.16  5643.2 1837.32  5806.6 1839.24  5864.4 1841.48
#Mann=7,-1,0
  3941.1   0.045       0  4425.0    0.07       0  5013.7    0.07       0
  5021.7    0.07       0  5168.8   0.045       0  5357.4    0.07       0
  5575.4   0.045       0
Bank Sta=5013.7,5021.7
Exp/Cntr=0.3,0.1

Type RM Length L Ch R = 1,26673,544,544,544
BEGIN DESCRIPTION:
Mapping XS 8d3883a9
END DESCRIPTION:
XS GIS Cut Line= 3
      1517379.97      6844622.46      1518408.63      6844010.47
      1518977.19      6842673.70
#Sta/Elev= 30
  3788.9 1843.22  3876.2 1843.26  3962.5 1840.82  4064.9 1841.02  4101.1 1839.25
  4218.8 1838.91  4240.2 1837.48  4357.1 1836.81  4415.5 1834.84  4495.3 1835.21
  4562.7 1833.08  4633.6 1833.48  4856.7 1829.20  4947.2 1827.74  4962.8 1826.03
  4979.3 1820.33  4979.8 1819.83  4987.5 1820.33  5021.1 1822.59  5151.5 1822.40
  5197.1 1823.65  5227.6 1822.14  5434.1 1823.98  5708.0 1829.23  5784.3 1829.45
  5825.9 1831.23  5827.3 1831.21  6030.6 1835.16  6417.7 1842.77  6438.5 1843.56
#Mann=10,-1,0
  3788.9   0.045       0  3962.5    0.07       0  4101.1   0.045       0
  4856.7    0.07       0  4979.3    0.07       0  4987.5    0.07       0
  5825.9   0.045       0  5827.3    0.07       0  6030.6   0.045       0
  6417.7   0.035       0
Bank Sta=4979.3,4987.5
Exp/Cntr=0.3,0.1

Type RM Length L Ch R = 1,26129,798,798,798
BEGIN DESCRIPTION:
Mapping XS c5b9afce
END DESCRIPTION:
XS GIS Cut Line= 4
      1517814.01      6845164.98      1518621.30      6844344.67
      1518851.33      6843954.05      1519103.06      6842855.98
#Sta/Elev= 30
  3435.1 1841.53  3564.4 1840.40  3744.8 1837.06  3850.9 1836.83  3935.8 1834.24
  3985.2 1835.05  4020.5 1833.04  4105.4 1832.94  4333.8 1828.56  4381.2 1826.39
  4437.8 1827.35  4459.0 1825.37  4558.0 1822.58  4636.6 1822.08  4820.0 1821.26
  4835.7 1821.73  4862.9 1825.91  4878.3 1824.58  4900.0 1820.95  4926.2 1819.09
  4926.7 1818.59  4934.5 1819.09  4980.1 1821.42  5001.5 1820.11  5055.8 1821.98
  5363.6 1825.04  5438.3 1827.98  5466.2 1827.48  5784.2 1834.99  6165.9 1841.16
#Mann=7,-1,0
  3435.1    0.07       0  3564.4   0.045       0  4333.8    0.07       0
  4636.6   0.035       0  4878.3    0.07       0  4926.2    0.07       0
  4934.5    0.07       0
Bank Sta=4926.2,4934.5
Exp/Cntr=0.3,0.1

Type RM Length L Ch R = 1,25331,571,571,571
BEGIN DESCRIPTION:
Mapping XS e3c78997
END DESCRIPTION:
XS GIS Cut Line= 3
      1518048.12      6845402.23      1519037.68      6844495.14
      1519367.54      6842945.66
#Sta/Elev= 30
  3510.4 1838.96  3744.8 1836.82  3780.0 1834.95  3879.2 1834.64  3921.8 1832.58
  3999.5 1832.61  4192.3 1828.16  4202.9 1828.07  4240.0 1828.64  4275.7 1826.57
  4341.1 1826.08  4431.1 1823.51  4665.5 1821.66  4801.1 1818.97  5003.1 1818.93
  5009.2 1817.60  5009.7 1817.10  5017.7 1817.60  5023.7 1820.30  5033.9 1820.55
  5435.6 1826.11  5612.5 1828.62  5709.1 1829.97  6019.0 1836.80  6160.6 1839.30
  6206.6 1839.43  6256.2 1842.19  6300.7 1841.14  6330.4 1842.52  6437.0 1843.84
#Mann=14,-1,0
  3510.4   0.045       0  4192.3    0.07       0  4202.9   0.045       0
  4341.1    0.07       0  4665.5   0.035       0  4801.1    0.07       0
  5009.2    0.07       0  5017.7    0.07       0  5435.6   0.045       0
  5612.5   0.035       0  5709.1    0.07       0  6019.0   0.045       0
  6160.6   0.035       0  6330.4   0.045       0
Bank Sta=5009.2,5017.7
Exp/Cntr=0.3,0.1

Type RM Length L Ch R = 1,24760,409,409,409
BEGIN DESCRIPTION:
Mapping XS 235c9f23
END DESCRIPTION:
XS GIS Cut Line= 4
      1518560.63      6846133.20      1519248.11      6844862.40
      1519289.78      6844105.45      1519407.71      6843162.03
#Sta/Elev= 30
  3525.6 1834.40  3694.4 1832.39  3836.2 1832.52  3885.6 1830.84  4100.0 1830.75
  4158.6 1828.52  4256.7 1828.21  4287.7 1826.17  4426.0 1824.54  4520.7 1820.55
  4711.2 1818.38  4941.3 1818.19  4950.2 1817.13  4951.6 1815.53  4952.1 1815.03
  4960.2 1815.53  4984.9 1817.89  5075.0 1817.87  5145.1 1819.64  5415.5 1819.37
  5665.9 1825.32  5816.7 1826.19  5833.4 1827.51  5877.1 1827.15  5988.2 1830.02
  6048.1 1829.85  6114.9 1831.90  6361.1 1835.22  6578.3 1839.63  6679.3 1841.58
#Mann=10,-1,0
  3525.6   0.045       0  4287.7   0.035       0  4711.2    0.07       0
  4951.6    0.07       0  4960.2    0.07       0  5833.4   0.045       0
  5988.2   0.035       0  6114.9    0.07       0  6361.1   0.045       0
  6578.3   0.035       0
Bank Sta=4951.6,4960.2
Exp/Cntr=0.3,0.1

Type RM Length L Ch R = 1,24351,634,634,634
BEGIN DESCRIPTION:
Mapping XS 2da3a2d2
END DESCRIPTION:
XS GIS Cut Line= 4
      1518643.96      6846167.94      1519227.28      6845869.34
      1519400.89      6845181.84      1519623.11      6843466.56
#Sta/Elev= 30
  3637.1 1832.36  3718.2 1832.62  3810.0 1830.39  3884.6 1830.75  4018.3 1828.08
  4233.7 1826.42  4288.4 1824.91  4603.2 1823.74  4665.1 1822.14  4727.0 1818.11
  4752.8 1818.37  4757.9 1817.40  4953.6 1815.70  4954.1 1815.20  4962.4 1815.70
  5600.3 1820.09  5720.7 1823.55  5847.8 1826.51  5872.5 1827.75  5973.4 1827.76
  6044.6 1830.13  6144.8 1829.87  6195.2 1831.85  6241.4 1831.79  6532.8 1835.19
  6536.6 1835.25  6598.6 1837.49  6635.0 1837.29  6722.1 1839.36  6731.1 1839.44
#Mann=13,-1,0
  3637.1   0.045       0  3810.0   0.035       0  4018.3    0.07       0
  4953.6    0.07       0  4962.4    0.07       0  5720.7   0.045       0
  5847.8   0.035       0  6044.6   0.045       0  6241.4   0.035       0
  6532.8   0.045       0  6536.6   0.035       0  6635.0   0.045       0
  6722.1   0.035       0
Bank Sta=4953.6,4962.4
Exp/Cntr=0.3,0.1