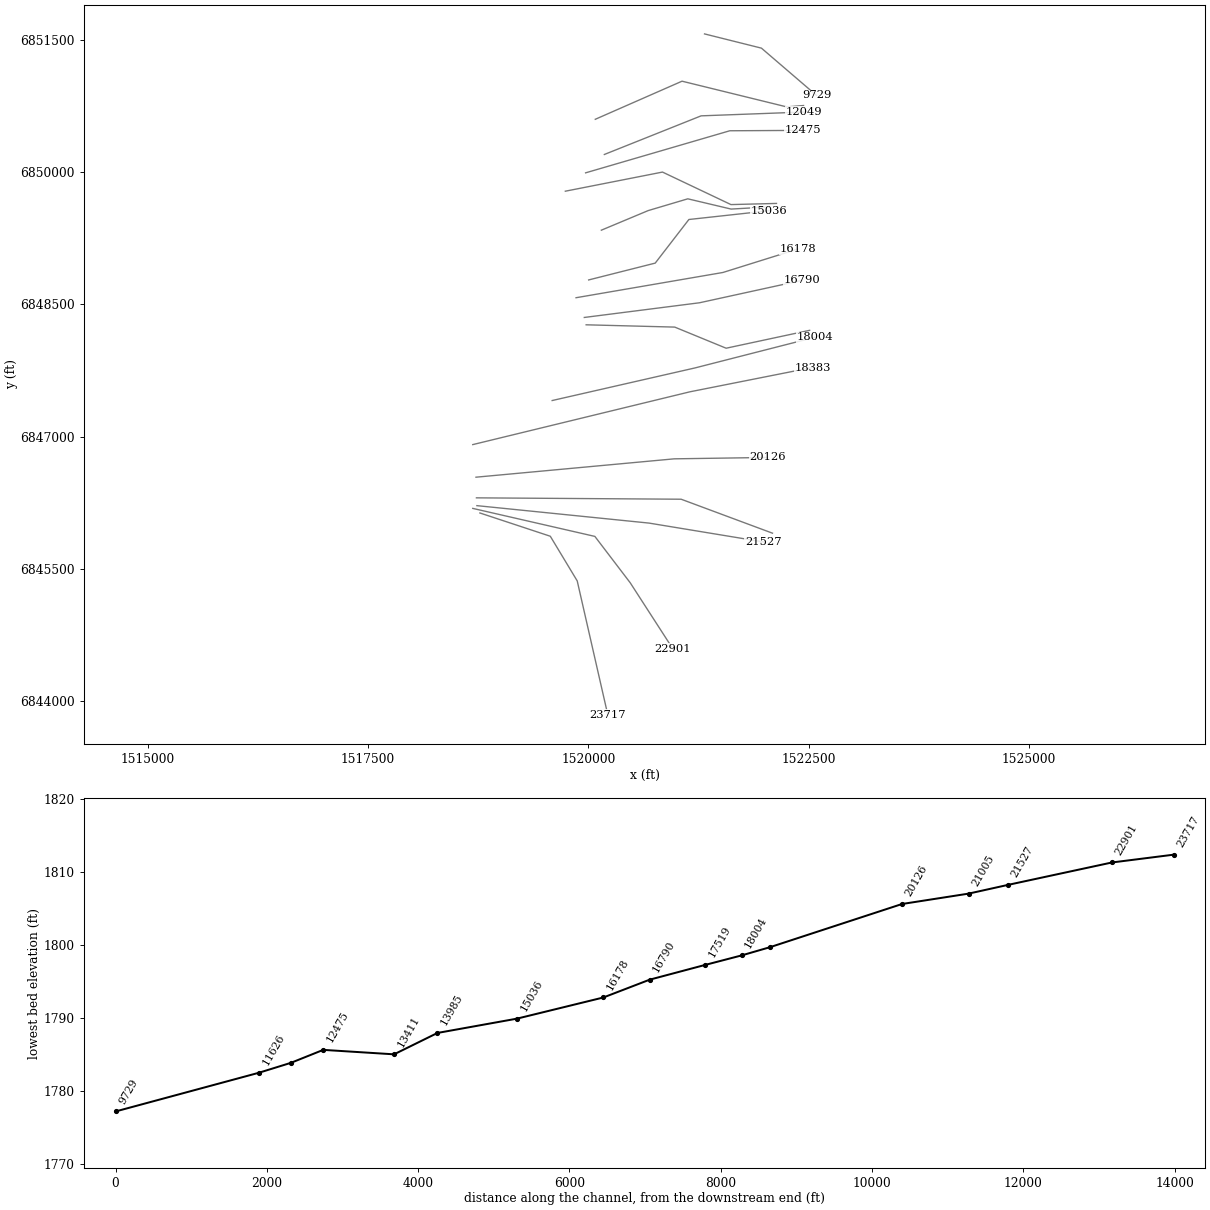
HEC-RAS study MULBERRY CREEK TRIBUTARY 16.prj: MULBERRY CREEK TRIBUTARY 16 Base Level Engineering

--- MULBERRY CREEK TRIBUTARY 16.g01 (geometry) --- (continued)

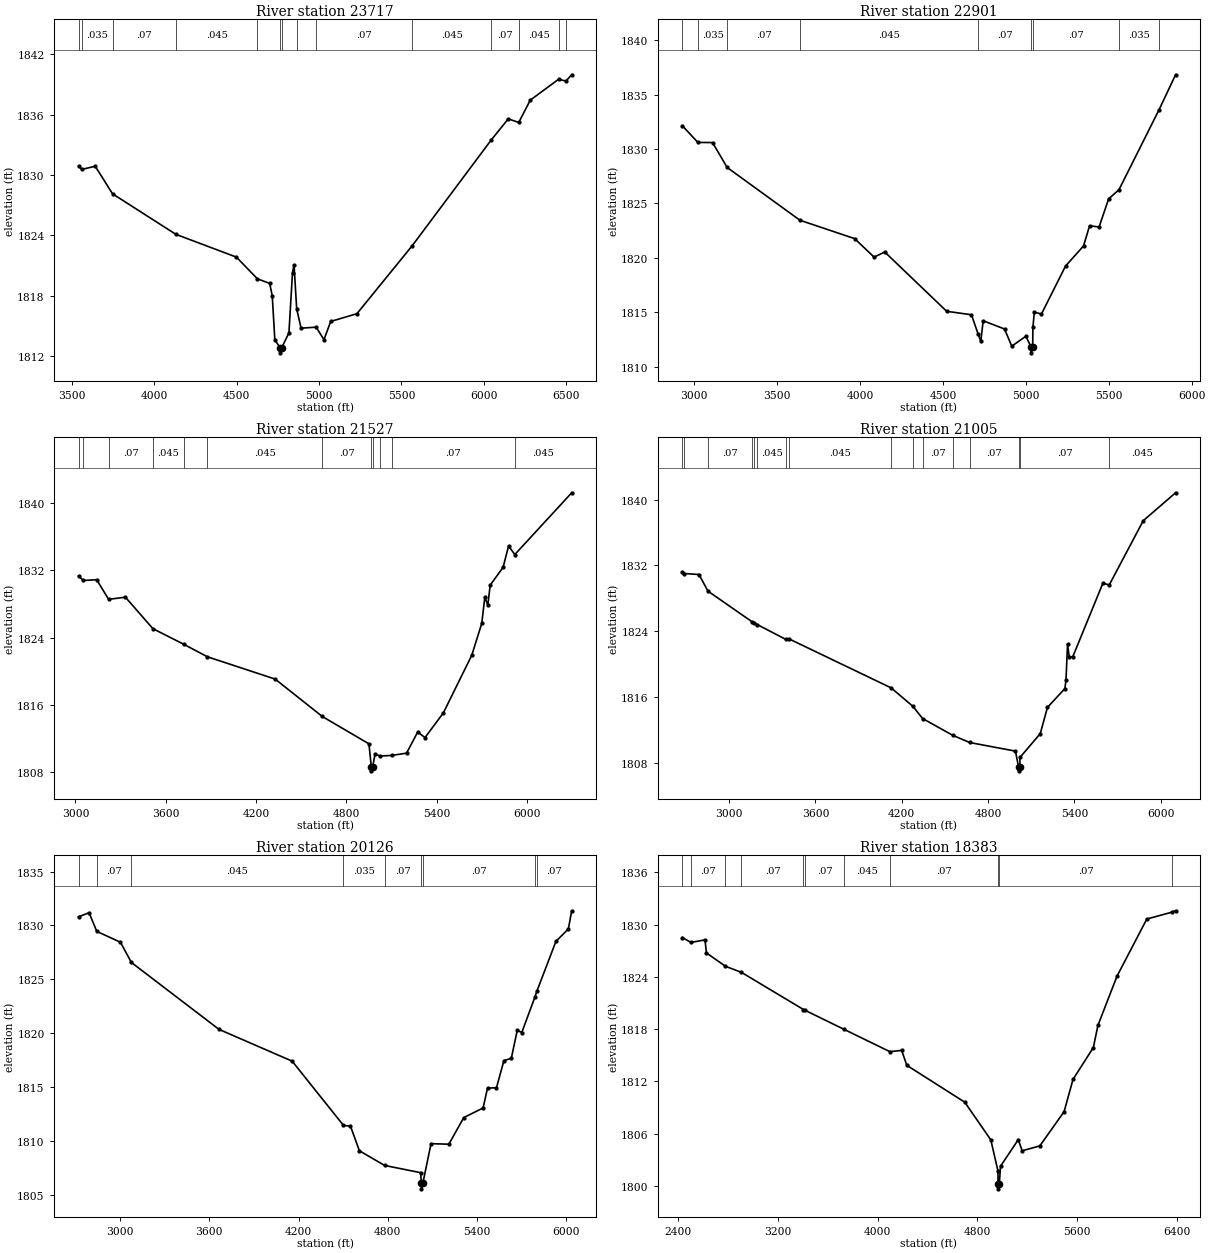
Type RM Length L Ch R = 1,23717,816,816,816
BEGIN DESCRIPTION:
Mapping XS f87c199e
END DESCRIPTION:
XS GIS Cut Line= 4
      1518768.97      6846133.22      1519567.56      6845869.34
      1519873.11      6845362.40      1520219.99      6843843.06
#Sta/Elev= 30
  3541.6 1830.89  3562.1 1830.56  3643.0 1830.87  3748.1 1828.13  4131.7 1824.11
  4499.4 1821.84  4627.0 1819.68  4701.3 1819.23  4716.8 1817.98  4732.4 1813.62
  4764.8 1812.83  4765.3 1812.33  4773.7 1812.83  4817.8 1814.31  4839.6 1820.31
  4848.9 1821.08  4864.9 1816.70  4891.6 1814.78  4983.0 1814.88  5030.4 1813.64
  5071.4 1815.45  5230.3 1816.22  5565.5 1822.97  6044.8 1833.48  6148.4 1835.58
  6211.8 1835.22  6281.8 1837.44  6453.2 1839.51  6497.9 1839.34  6533.0 1839.96
#Mann=14,-1,0
  3541.6   0.045       0  3562.1   0.035       0  3748.1    0.07       0
  4131.7   0.045       0  4627.0    0.07       0  4764.8    0.07       0
  4773.7    0.07       0  4864.9   0.045       0  4983.0    0.07       0
  5565.5   0.045       0  6044.8    0.07       0  6211.8   0.045       0
  6453.2   0.035       0  6497.9   0.045       0
Bank Sta=4764.8,4773.7
Exp/Cntr=0.3,0.1

Type RM Length L Ch R = 1,22901,1374,1374,1374
BEGIN DESCRIPTION:
Mapping XS 481b096c
END DESCRIPTION:
XS GIS Cut Line= 4
      1518687.81      6846185.25      1520073.27      6845867.53
      1520474.31      6845341.49      1520958.19      6844592.26
#Sta/Elev= 30
  2928.2 1832.13  3021.8 1830.60  3110.0 1830.59  3198.4 1828.30  3637.0 1823.45
  3967.0 1821.76  4084.6 1820.06  4148.8 1820.53  4522.2 1815.08  4671.9 1814.76
  4711.2 1813.02  4728.1 1812.32  4742.6 1814.21  4871.5 1813.45  4914.9 1811.87
  5000.3 1812.79  5032.0 1811.76  5032.5 1811.26  5041.1 1811.76  5042.5 1813.61
  5051.0 1815.00  5094.0 1814.83  5239.1 1819.23  5348.0 1821.09  5384.3 1822.94
  5441.7 1822.83  5499.1 1825.41  5561.7 1826.26  5803.5 1833.61  5903.0 1836.82
#Mann=9,-1,0
  2928.2   0.045       0  3021.8   0.035       0  3198.4    0.07       0
  3637.0   0.045       0  4711.2    0.07       0  5032.0    0.07       0
  5041.1    0.07       0  5561.7   0.035       0  5803.5   0.045       0
Bank Sta=5032,5041.1
Exp/Cntr=0.3,0.1

Type RM Length L Ch R = 1,21527,522,522,522
BEGIN DESCRIPTION:
Mapping XS a590eb63
END DESCRIPTION:
XS GIS Cut Line= 3
      1518734.72      6846216.49      1520687.85      6846018.58
      1521984.76      6845805.03
#Sta/Elev= 30
  3020.1 1831.34  3052.4 1830.81  3141.0 1830.90  3220.0 1828.57  3332.0 1828.82
  3514.6 1825.08  3720.5 1823.22  3875.7 1821.75  4327.0 1819.09  4640.0 1814.65
  4950.2 1811.40  4965.7 1808.69  4966.2 1808.19  4975.0 1808.69  4990.5 1810.15
  5026.9 1809.95  5100.3 1810.02  5200.2 1810.29  5274.2 1812.80  5322.6 1812.14
  5444.9 1815.08  5633.5 1821.92  5699.9 1825.71  5720.2 1828.80  5740.4 1827.90
  5755.9 1830.25  5841.8 1832.38  5878.2 1834.91  5919.5 1833.89  6297.6 1841.23
#Mann=12,-1,0
  3020.1   0.045       0  3052.4   0.035       0  3220.0    0.07       0
  3514.6   0.045       0  3720.5    0.07       0  3875.7   0.045       0
  4640.0    0.07       0  4965.7    0.07       0  4975.0    0.07       0
  5026.9    0.16       0  5100.3    0.07       0  5919.5   0.045       0
Bank Sta=4965.7,4975
Exp/Cntr=0.3,0.1

Type RM Length L Ch R = 1,21005,879,879,879
BEGIN DESCRIPTION:
Mapping XS a451edee
END DESCRIPTION:
XS GIS Cut Line= 3
      1518729.51      6846305.03      1521052.43      6846289.41
      1522088.91      6845903.98
#Sta/Elev= 30
  2674.6 1831.22  2689.0 1831.01  2790.1 1830.89  2852.3 1828.87  3157.0 1825.16
  3170.4 1825.01  3195.7 1824.79  3395.0 1822.98  3418.8 1823.03  4126.0 1817.09
  4276.7 1814.85  4344.5 1813.36  4554.6 1811.31  4671.4 1810.44  4990.1 1809.39
  5011.5 1807.49  5012.0 1806.99  5020.8 1807.49  5021.7 1808.62  5162.6 1811.52
  5212.6 1814.71  5334.0 1817.01  5341.7 1818.07  5352.4 1822.42  5364.3 1820.83
  5389.3 1820.90  5597.8 1829.82  5642.6 1829.63  5878.6 1837.44  6103.4 1840.84
#Mann=16,-1,0
  2674.6   0.045       0  2689.0   0.035       0  2852.3    0.07       0
  3157.0   0.045       0  3170.4    0.07       0  3195.7   0.045       0
  3395.0    0.07       0  3418.8   0.045       0  4126.0    0.07       0
  4276.7   0.045       0  4344.5    0.07       0  4554.6   0.035       0
  4671.4    0.07       0  5011.5    0.07       0  5020.8    0.07       0
  5642.6   0.045       0
Bank Sta=5011.5,5020.8
Exp/Cntr=0.3,0.1

Type RM Length L Ch R = 1,20126,1743,1743,1743
BEGIN DESCRIPTION:
Mapping XS fa9d5755
END DESCRIPTION:
XS GIS Cut Line= 3
      1518724.28      6846539.41      1520974.31      6846747.74
      1522030.84      6846763.36
#Sta/Elev= 30
  2720.1 1830.80  2791.1 1831.18  2842.9 1829.45  3002.0 1828.44  3075.3 1826.57
  3664.8 1820.36  4156.9 1817.41  4501.9 1811.45  4548.6 1811.39  4608.9 1809.10
  4778.2 1807.74  5020.5 1807.07  5025.8 1806.07  5026.3 1805.57  5035.2 1806.07
  5090.5 1809.76  5210.5 1809.71  5310.5 1812.18  5440.5 1813.07  5470.5 1814.92
  5530.5 1814.94  5580.5 1817.46  5630.5 1817.68  5670.5 1820.29  5700.5 1820.06
  5789.3 1823.36  5801.9 1823.89  5930.6 1828.53  6013.9 1829.67  6036.4 1831.36
#Mann=9,-1,0
  2720.1   0.035       0  2842.9    0.07       0  3075.3   0.045       0
  4501.9   0.035       0  4778.2    0.07       0  5025.8    0.07       0
  5035.2    0.07       0  5789.3   0.035       0  5801.9    0.07       0
Bank Sta=5025.8,5035.2
Exp/Cntr=0.3,0.1

Type RM Length L Ch R = 1,18383,379,379,379
BEGIN DESCRIPTION:
Mapping XS 81960bff
END DESCRIPTION:
XS GIS Cut Line= 3
      1518687.83      6846909.20      1521151.39      6847508.16
      1522541.05      6847784.01
#Sta/Elev= 30
  2436.2 1828.52  2504.8 1827.95  2617.5 1828.25  2628.8 1826.75  2781.0 1825.22
  2909.3 1824.52  3406.5 1820.25  3421.1 1820.15  3732.3 1817.97  4099.3 1815.41
  4193.1 1815.56  4234.8 1813.84  4699.1 1809.61  4907.9 1805.28  4964.9 1801.72
  4965.9 1800.16  4966.4 1799.66  4975.7 1800.16  4985.4 1802.25  5128.1 1805.32
  5158.7 1804.03  5300.5 1804.59  5495.2 1808.53  5566.5 1812.23  5729.6 1815.89
  5766.1 1818.43  5919.6 1824.10  6157.8 1830.64  6358.5 1831.43  6388.3 1831.59
#Mann=11,-1,0
  2436.2   0.035       0  2504.8    0.07       0  2781.0   0.045       0
  2909.3    0.07       0  3406.5   0.045       0  3421.1    0.07       0
  3732.3   0.045       0  4099.3    0.07       0  4965.9    0.07       0
  4975.7    0.07       0  6358.5   0.045       0
Bank Sta=4965.9,4975.7
Exp/Cntr=0.3,0.1

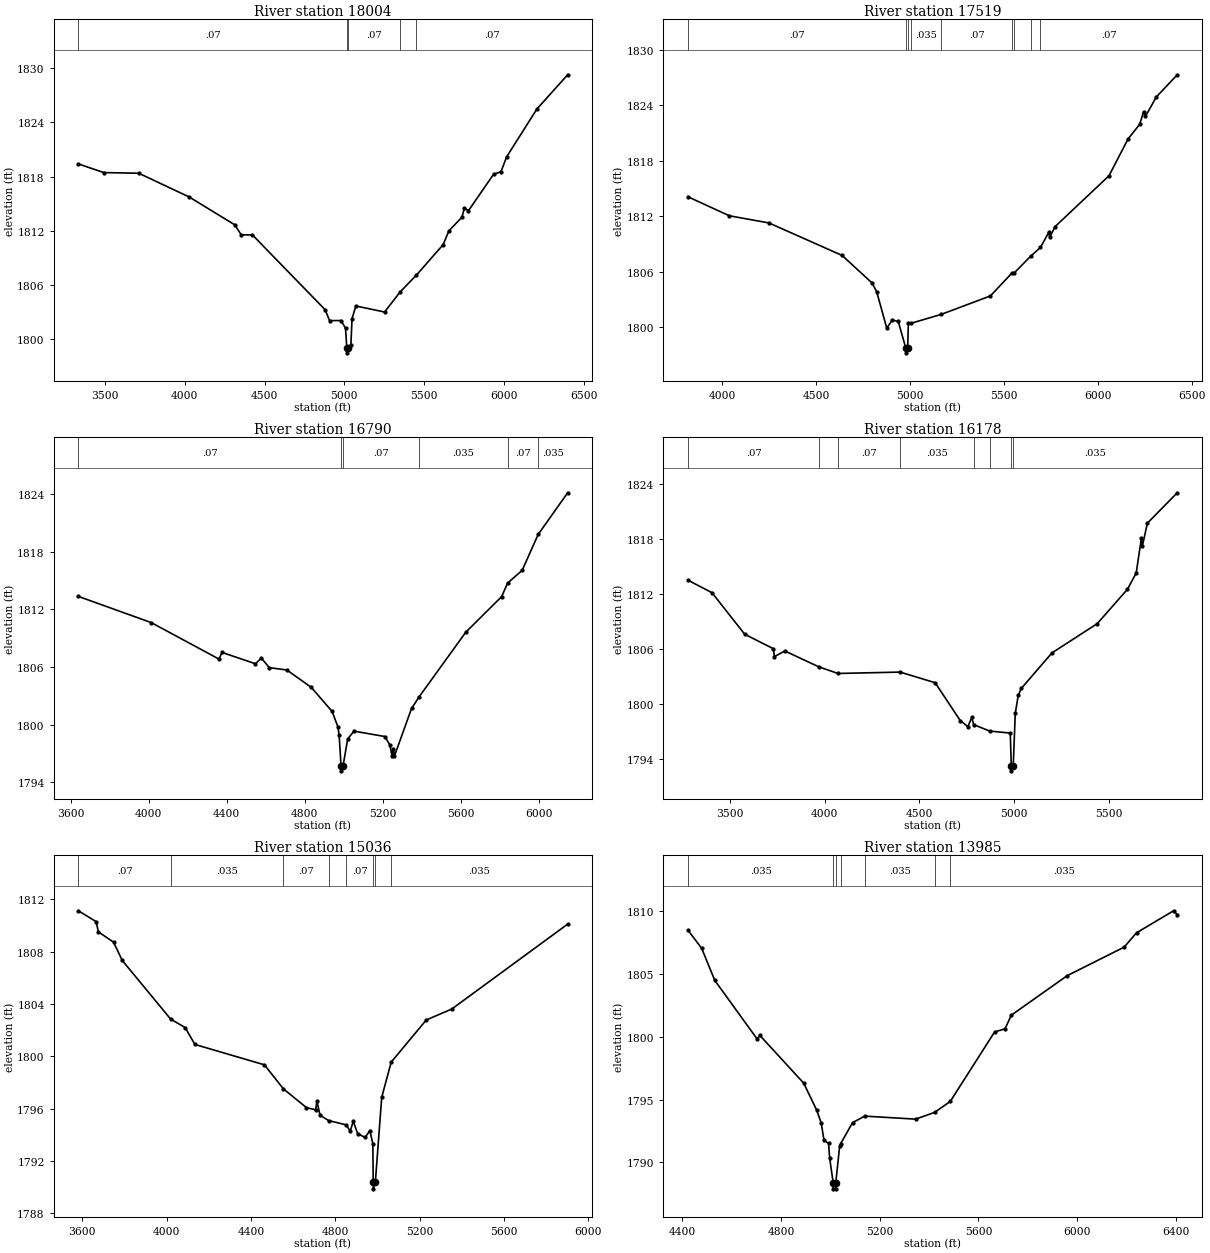
Type RM Length L Ch R = 1,18004,485,485,485
BEGIN DESCRIPTION:
Mapping XS 1256ab11
END DESCRIPTION:
XS GIS Cut Line= 3
      1519588.92      6847409.21      1521208.68      6847778.99
      1522571.59      6848127.52
#Sta/Elev= 30
  3332.2 1819.40  3492.3 1818.44  3710.8 1818.37  4027.0 1815.75  4312.9 1812.67
  4353.9 1811.56  4424.1 1811.55  4879.5 1803.29  4907.8 1802.08  4979.6 1802.09
  5007.6 1801.24  5015.8 1799.02  5016.3 1798.52  5025.7 1799.02  5041.4 1799.42
  5048.4 1802.29  5072.4 1803.70  5252.5 1803.03  5350.6 1805.26  5452.1 1807.11
  5619.9 1810.48  5655.6 1812.00  5737.3 1813.50  5753.6 1814.53  5778.1 1814.22
  5936.2 1818.26  5982.2 1818.53  6017.9 1820.18  6207.8 1825.47  6400.4 1829.25
#Mann=5,-1,0
  3332.2    0.07       0  5015.8    0.07       0  5025.7    0.07       0
  5350.6   0.035       0  5452.1    0.07       0
Bank Sta=5015.8,5025.7
Exp/Cntr=0.3,0.1

Type RM Length L Ch R = 1,17519,729,729,729
BEGIN DESCRIPTION:
Mapping XS 852a03fc
END DESCRIPTION:
XS GIS Cut Line= 4
      1519974.28      6848268.58      1520979.52      6848242.53
      1521562.85      6848002.95      1522510.35      6848205.99
#Sta/Elev= 30
  3818.1 1814.10  4038.9 1812.04  4249.0 1811.27  4639.1 1807.75  4799.1 1804.76
  4823.7 1803.79  4876.7 1799.89  4906.0 1800.75  4937.7 1800.62  4978.4 1797.71
  4978.9 1797.21  4988.3 1797.71  4991.8 1800.48  5007.9 1800.42  5166.6 1801.37
  5428.7 1803.37  5542.6 1805.83  5556.4 1805.88  5643.2 1807.67  5695.3 1808.62
  5739.3 1810.25  5744.4 1809.72  5773.5 1810.88  6059.9 1816.37  6162.2 1820.38
  6223.5 1821.94  6244.0 1823.30  6254.2 1822.80  6312.0 1824.90  6423.3 1827.30
#Mann=9,-1,0
  3818.1    0.07       0  4978.4    0.07       0  4988.3    0.07       0
  5007.9   0.035       0  5166.6    0.07       0  5542.6   0.035       0
  5556.4    0.07       0  5643.2   0.035       0  5695.3    0.07       0
Bank Sta=4978.4,4988.3
Exp/Cntr=0.3,0.1

Type RM Length L Ch R = 1,16790,612,612,612
BEGIN DESCRIPTION:
Mapping XS 471323aa
END DESCRIPTION:
XS GIS Cut Line= 3
      1519953.50      6848351.91      1521260.77      6848518.58
      1522425.67      6848773.40
#Sta/Elev= 30
  3638.8 1813.35  4013.3 1810.62  4360.1 1806.83  4376.2 1807.52  4547.6 1806.34
  4577.8 1806.94  4618.2 1805.94  4708.9 1805.69  4834.2 1803.88  4940.8 1801.38
  4971.2 1799.74  4976.8 1798.90  4986.7 1795.70  4987.2 1795.20  4996.7 1795.70
  5020.7 1798.52  5053.1 1799.33  5211.6 1798.77  5237.4 1797.88  5247.6 1796.79
  5255.4 1797.46  5260.5 1796.74  5348.3 1801.69  5388.2 1802.93  5626.4 1809.62
  5810.6 1813.33  5841.1 1814.73  5915.7 1816.06  5997.8 1819.79  6149.1 1824.13
#Mann=6,-1,0
  3638.8    0.07       0  4986.7    0.07       0  4996.7    0.07       0
  5388.2   0.035       0  5841.1    0.07       0  5997.8   0.035       0
Bank Sta=4986.7,4996.7
Exp/Cntr=0.3,0.1

Type RM Length L Ch R = 1,16178,1142,1142,1142
BEGIN DESCRIPTION:
Mapping XS 3d9c4be0
END DESCRIPTION:
XS GIS Cut Line= 3
      1519859.76      6848575.87      1521526.39      6848862.33
      1522375.34      6849127.95
#Sta/Elev= 30
  3279.2 1813.52  3406.3 1812.15  3578.8 1807.63  3730.2 1806.05  3735.3 1805.19
  3790.2 1805.81  3970.7 1804.07  4070.7 1803.36  4398.4 1803.51  4583.3 1802.35
  4715.2 1798.24  4755.8 1797.57  4776.1 1798.58  4786.3 1797.79  4870.4 1797.09
  4979.3 1796.87  4984.7 1793.26  4985.2 1792.76  4994.8 1793.26  5005.7 1799.03
  5021.2 1800.97  5038.2 1801.75  5199.3 1805.60  5438.2 1808.79  5597.5 1812.53
  5643.5 1814.30  5670.7 1818.07  5675.9 1817.23  5702.3 1819.72  5859.8 1823.03
#Mann=8,-1,0
  3279.2    0.07       0  3970.7   0.035       0  4070.7    0.07       0
  4398.4   0.035       0  4786.3    0.07       0  4870.4   0.035       0
  4984.7   0.035       0  4994.8   0.035       0
Bank Sta=4984.7,4994.8
Exp/Cntr=0.3,0.1

Type RM Length L Ch R = 1,15036,1051,1051,1051
BEGIN DESCRIPTION:
Mapping XS fe905cb6
END DESCRIPTION:
XS GIS Cut Line= 4
      1520002.95      6848777.69      1520758.16      6848968.66
      1521140.11      6849463.45      1522051.61      6849563.28
#Sta/Elev= 30
  3581.0 1811.12  3665.6 1810.29  3676.0 1809.51  3748.2 1808.72  3789.4 1807.32
  4018.8 1802.84  4087.8 1802.19  4133.9 1800.90  4463.9 1799.34  4553.4 1797.51
  4663.1 1796.07  4706.6 1795.90  4712.9 1796.55  4727.4 1795.49  4768.1 1795.08
  4851.9 1794.75  4870.5 1794.26  4885.0 1795.03  4905.9 1794.08  4941.2 1793.79
  4963.9 1794.31  4978.2 1793.29  4979.6 1790.36  4980.1 1789.86  4989.8 1790.36
  5020.1 1796.86  5065.1 1799.55  5231.4 1802.77  5352.7 1803.61  5902.0 1810.10
#Mann=8,-1,0
  3581.0    0.07       0  4018.8   0.035       0  4553.4    0.07       0
  4768.1   0.035       0  4851.9    0.07       0  4979.6    0.07       0
  4989.8    0.07       0  5065.1   0.035       0
Bank Sta=4979.6,4989.8
Exp/Cntr=0.3,0.1

Type RM Length L Ch R = 1,13985,574,574,574
BEGIN DESCRIPTION:
Mapping XS a3bc0471
END DESCRIPTION:
XS GIS Cut Line= 5
      1520146.88      6849342.27      1520678.09      6849564.47
      1521127.74      6849698.15      1521619.06      6849581.83
      1522049.66      6849606.14
#Sta/Elev= 30
  4423.6 1808.46  4479.3 1807.02  4532.3 1804.47  4703.4 1799.82  4715.1 1800.09
  4892.5 1796.30  4945.5 1794.13  4963.5 1793.12  4974.7 1791.75  4993.1 1791.51
  4997.5 1790.34  5011.7 1788.40  5012.2 1787.90  5021.9 1787.90  5022.4 1788.40
  5037.9 1791.29  5042.0 1791.49  5090.1 1793.16  5139.7 1793.68  5345.4 1793.44
  5422.9 1793.98  5485.9 1794.85  5665.3 1800.37  5707.6 1800.62  5732.9 1801.70
  5959.0 1804.84  6189.7 1807.11  6239.8 1808.25  6390.0 1810.00  6404.7 1809.69
#Mann=7,-1,0
  4423.6   0.035       0  5011.7   0.035       0  5022.4   0.035       0
  5042.0    0.07       0  5139.7   0.035       0  5422.9    0.07       0
  5485.9   0.035       0
Bank Sta=5011.7,5022.4
Exp/Cntr=0.3,0.1

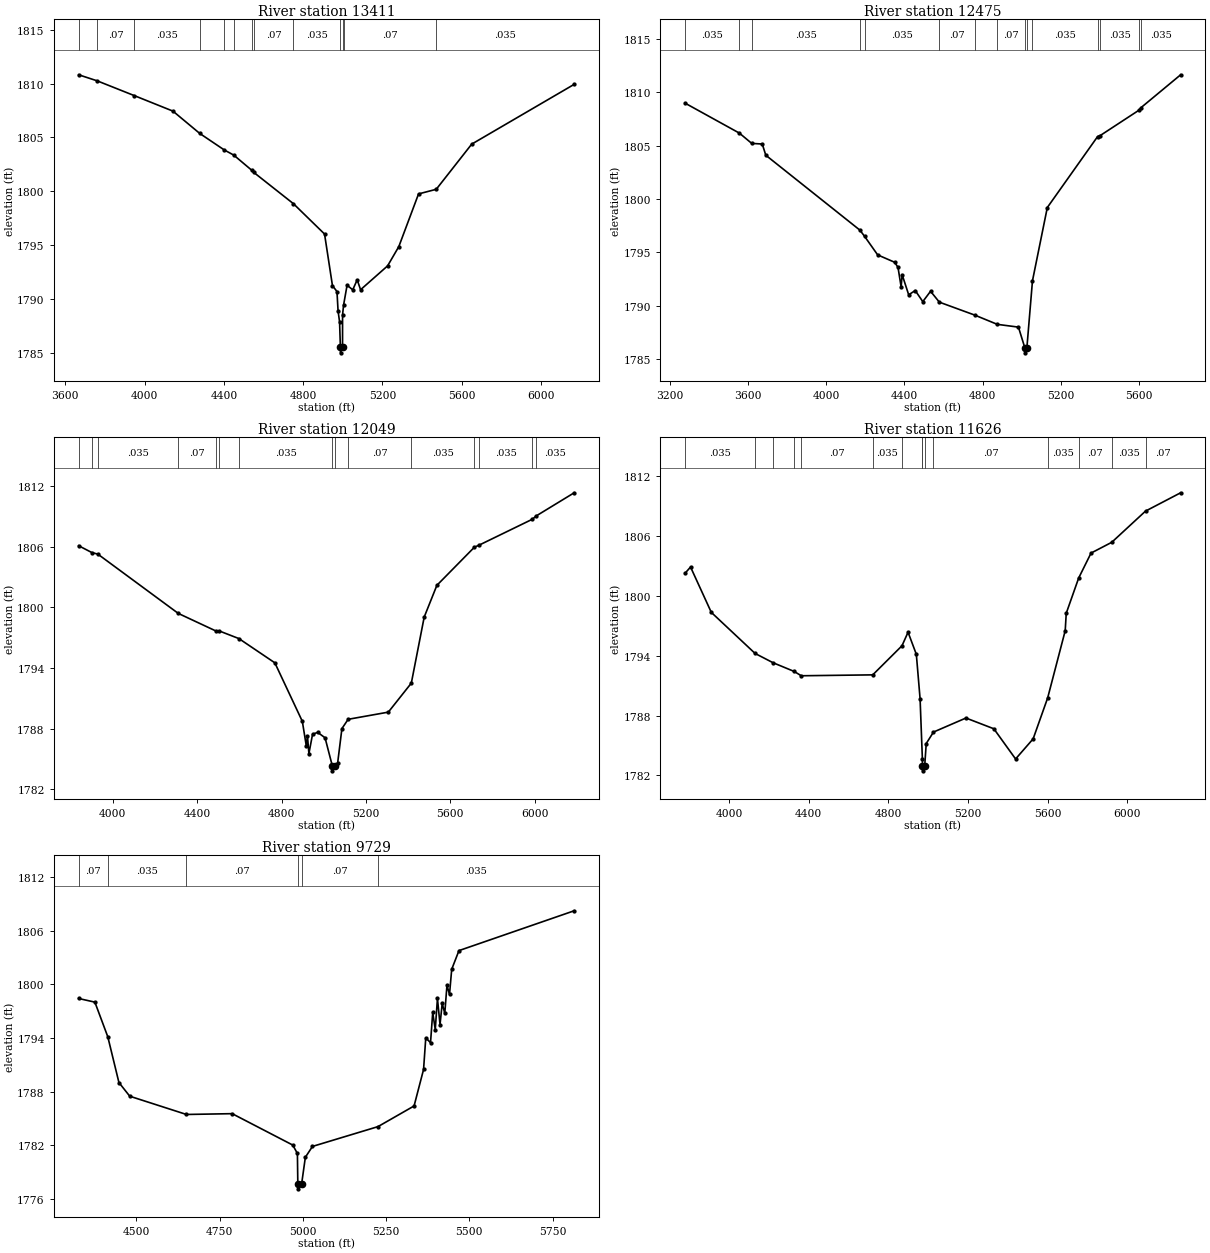
Type RM Length L Ch R = 1,13411,936,936,936
BEGIN DESCRIPTION:
Mapping XS 04aae219
END DESCRIPTION:
XS GIS Cut Line= 4
      1519738.20      6849784.63      1520840.63      6850001.65
      1521617.54      6849632.72      1522134.03      6849645.75
#Sta/Elev= 30
  3667.3 1810.83  3760.3 1810.27  3948.5 1808.89  4143.1 1807.45  4278.7 1805.37
  4402.0 1803.84  4450.0 1803.36  4542.1 1801.93  4550.4 1801.76  4751.1 1798.84
  4908.1 1796.02  4948.0 1791.22  4970.8 1790.67  4976.3 1788.87  4983.9 1787.85
  4988.1 1785.47  4988.6 1784.97  4998.9 1785.47  4999.0 1788.52  5004.3 1789.43
  5021.8 1791.26  5050.3 1790.83  5072.8 1791.76  5089.9 1790.84  5226.3 1793.06
  5282.8 1794.85  5382.4 1799.75  5471.7 1800.18  5650.6 1804.38  6167.6 1809.94
#Mann=13,-1,0
  3667.3   0.035       0  3760.3    0.07       0  3948.5   0.035       0
  4278.7    0.07       0  4402.0   0.035       0  4450.0    0.07       0
  4542.1   0.035       0  4550.4    0.07       0  4751.1   0.035       0
  4988.1   0.035       0  4998.9   0.035       0  5004.3    0.07       0
  5471.7   0.035       0
Bank Sta=4988.1,4998.9
Exp/Cntr=0.3,0.1

Type RM Length L Ch R = 1,12475,426,426,426
BEGIN DESCRIPTION:
Mapping XS f2c53f3d
END DESCRIPTION:
XS GIS Cut Line= 3
      1519968.25      6849992.97      1521604.52      6850470.40
      1522437.81      6850474.74
#Sta/Elev= 30
  3276.6 1808.98  3554.8 1806.17  3617.8 1805.21  3671.8 1805.15  3689.9 1804.10
  4171.8 1797.08  4196.1 1796.49  4262.8 1794.76  4349.6 1794.07  4367.0 1793.59
  4383.0 1791.76  4388.2 1792.90  4421.7 1791.02  4455.2 1791.42  4493.9 1790.38
  4533.7 1791.35  4578.7 1790.33  4759.6 1789.12  4875.4 1788.25  4983.8 1787.99
  5016.0 1786.08  5016.5 1785.58  5027.1 1786.08  5055.6 1792.33  5131.6 1799.20
  5389.2 1805.85  5401.3 1805.93  5601.8 1808.33  5612.1 1808.57  5814.4 1811.64
#Mann=15,-1,0
  3276.6   0.035       0  3554.8    0.07       0  3617.8   0.035       0
  4171.8    0.07       0  4196.1   0.035       0  4578.7    0.07       0
  4759.6   0.035       0  4875.4    0.07       0  5016.0    0.07       0
  5027.1    0.07       0  5055.6   0.035       0  5389.2    0.07       0
  5401.3   0.035       0  5601.8    0.07       0  5612.1   0.035       0
Bank Sta=5016,5027.1
Exp/Cntr=0.3,0.1

Type RM Length L Ch R = 1,12049,423,423,423
BEGIN DESCRIPTION:
Mapping XS 54674d58
END DESCRIPTION:
XS GIS Cut Line= 3
      1520180.94      6850201.32      1521279.00      6850639.67
      1522445.57      6850683.04
#Sta/Elev= 30
  3837.8 1806.09  3900.8 1805.41  3928.8 1805.26  4310.4 1799.39  4489.9 1797.64
  4505.2 1797.65  4597.8 1796.90  4768.2 1794.50  4898.5 1788.71  4917.4 1786.27
  4922.8 1787.26  4929.7 1785.52  4947.0 1787.43  4971.3 1787.62  5006.3 1787.08
  5040.6 1784.31  5041.1 1783.81  5051.7 1784.31  5066.2 1784.62  5086.2 1787.99
  5115.7 1788.91  5306.3 1789.62  5415.3 1792.49  5476.4 1799.03  5536.5 1802.17
  5714.2 1805.94  5737.9 1806.16  5989.1 1808.71  6007.6 1809.04  6187.5 1811.33
#Mann=15,-1,0
  3837.8   0.035       0  3900.8    0.07       0  3928.8   0.035       0
  4310.4    0.07       0  4489.9   0.035       0  4505.2    0.07       0
  4597.8   0.035       0  5040.6   0.035       0  5051.7   0.035       0
  5115.7    0.07       0  5415.3   0.035       0  5714.2    0.07       0
  5737.9   0.035       0  5989.1    0.07       0  6007.6   0.035       0
Bank Sta=5040.6,5051.7
Exp/Cntr=0.3,0.1

Type RM Length L Ch R = 1,11626,1897,1897,1897
BEGIN DESCRIPTION:
Mapping XS 90b40fe5
END DESCRIPTION:
XS GIS Cut Line= 4
      1520078.05      6850600.61      1521062.42      6851032.90
      1522249.92      6850741.23      1522441.29      6850756.75
#Sta/Elev= 30
  3778.5 1802.28  3805.9 1802.90  3910.2 1798.35  4130.1 1794.23  4220.2 1793.30
  4326.9 1792.42  4362.1 1791.99  4721.3 1792.08  4868.3 1795.00  4898.8 1796.36
  4940.4 1794.14  4959.2 1789.69  4970.8 1783.61  4971.3 1782.95  4971.8 1782.45
  4982.4 1782.95  4990.1 1785.19  5026.5 1786.34  5189.7 1787.75  5329.9 1786.67
  5439.1 1783.64  5527.3 1785.66  5600.3 1789.77  5688.4 1796.51  5693.6 1798.26
  5756.1 1801.80  5818.2 1804.30  5922.2 1805.38  6091.9 1808.51  6268.4 1810.35
#Mann=15,-1,0
  3778.5   0.035       0  4130.1    0.07       0  4220.2    0.16       0
  4326.9   0.035       0  4362.1    0.07       0  4721.3   0.035       0
  4868.3    0.07       0  4970.8   0.035       0  4971.3   0.035       0
  4982.4   0.035       0  5026.5    0.07       0  5600.3   0.035       0
  5756.1    0.07       0  5922.2   0.035       0  6091.9    0.07       0
Bank Sta=4971.3,4982.4
Exp/Cntr=0.3,0.1

Type RM Length L Ch R = 1,9729,933,933,933
BEGIN DESCRIPTION:
Mapping XS b55069c5
END DESCRIPTION:
XS GIS Cut Line= 3
      1521317.64      6851569.35      1521963.46      6851407.90
      1522587.58      6850872.19
#Sta/Elev= 30
  4326.8 1798.41  4375.6 1798.00  4414.4 1794.13  4447.8 1789.02  4480.3 1787.49
  4650.6 1785.45  4787.9 1785.54  4969.9 1782.03  4983.8 1781.09  4985.1 1777.64
  4985.6 1777.14  4996.3 1777.64  5007.7 1780.67  5029.1 1781.88  5225.7 1784.09
  5334.2 1786.40  5362.7 1790.48  5369.3 1794.01  5383.6 1793.47  5390.2 1796.85
  5397.8 1794.94  5404.4 1798.41  5412.1 1795.50  5418.7 1797.85  5426.4 1796.75
  5433.0 1799.89  5440.6 1798.86  5447.2 1801.67  5469.0 1803.76  5815.0 1808.21
#Mann=6,-1,0
  4326.8    0.07       0  4414.4   0.035       0  4650.6    0.07       0
  4985.1    0.07       0  4996.3    0.07       0  5225.7   0.035       0
Bank Sta=4985.1,4996.3
Exp/Cntr=0.3,0.1