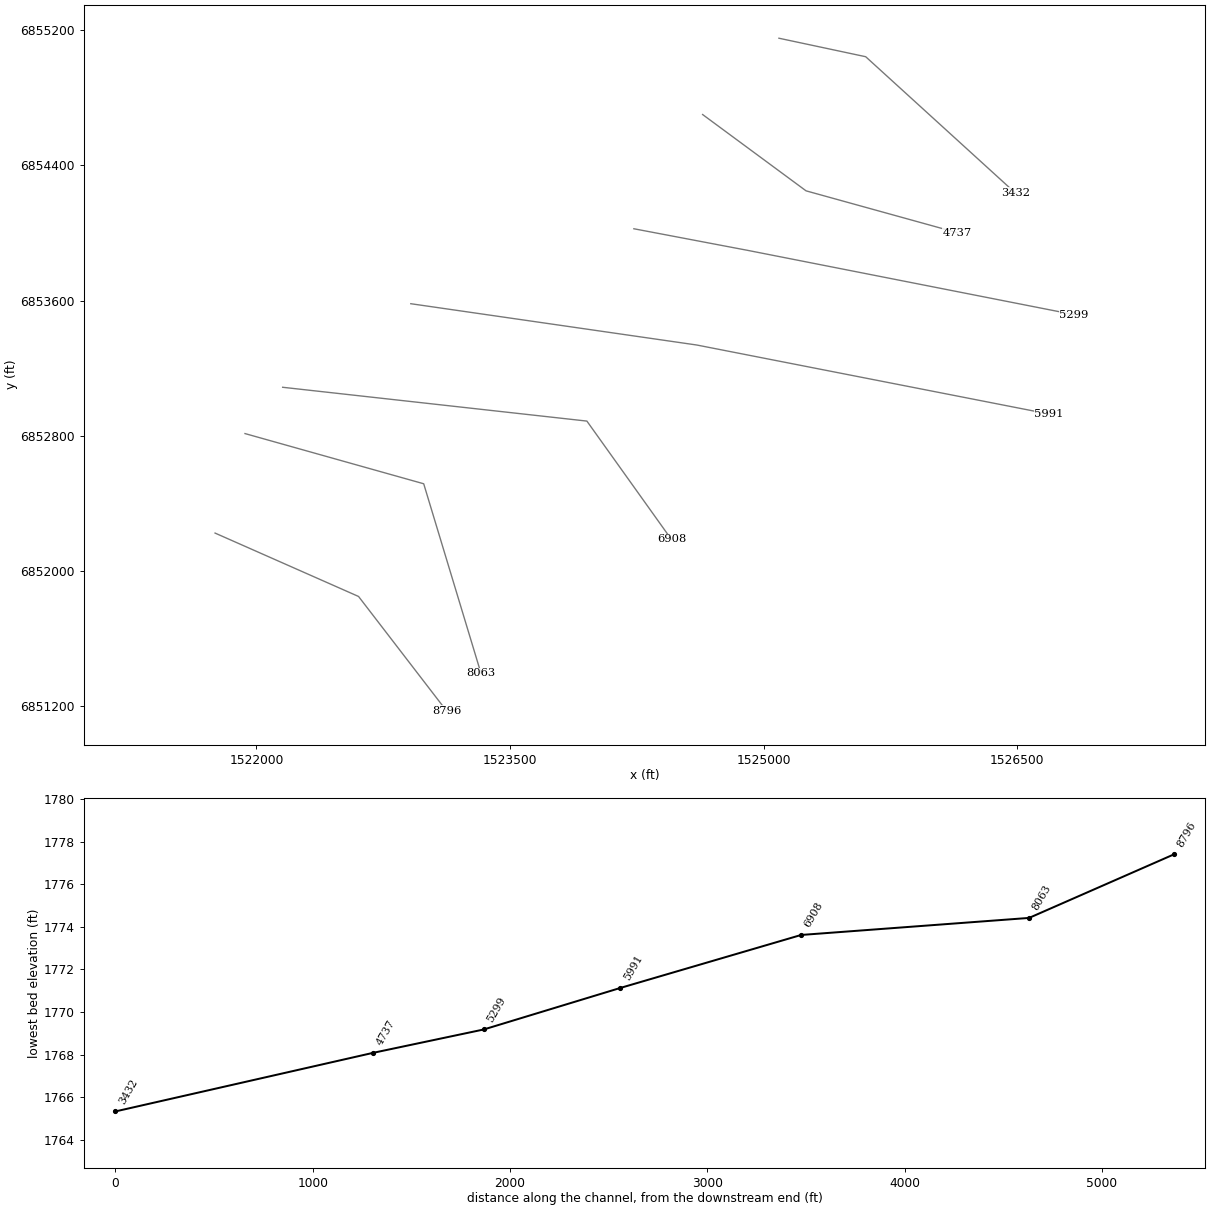
HEC-RAS study MULBERRY CREEK TRIBUTARY 16.prj: MULBERRY CREEK TRIBUTARY 16 Base Level Engineering

--- MULBERRY CREEK TRIBUTARY 16.g01 (geometry) --- (continued)

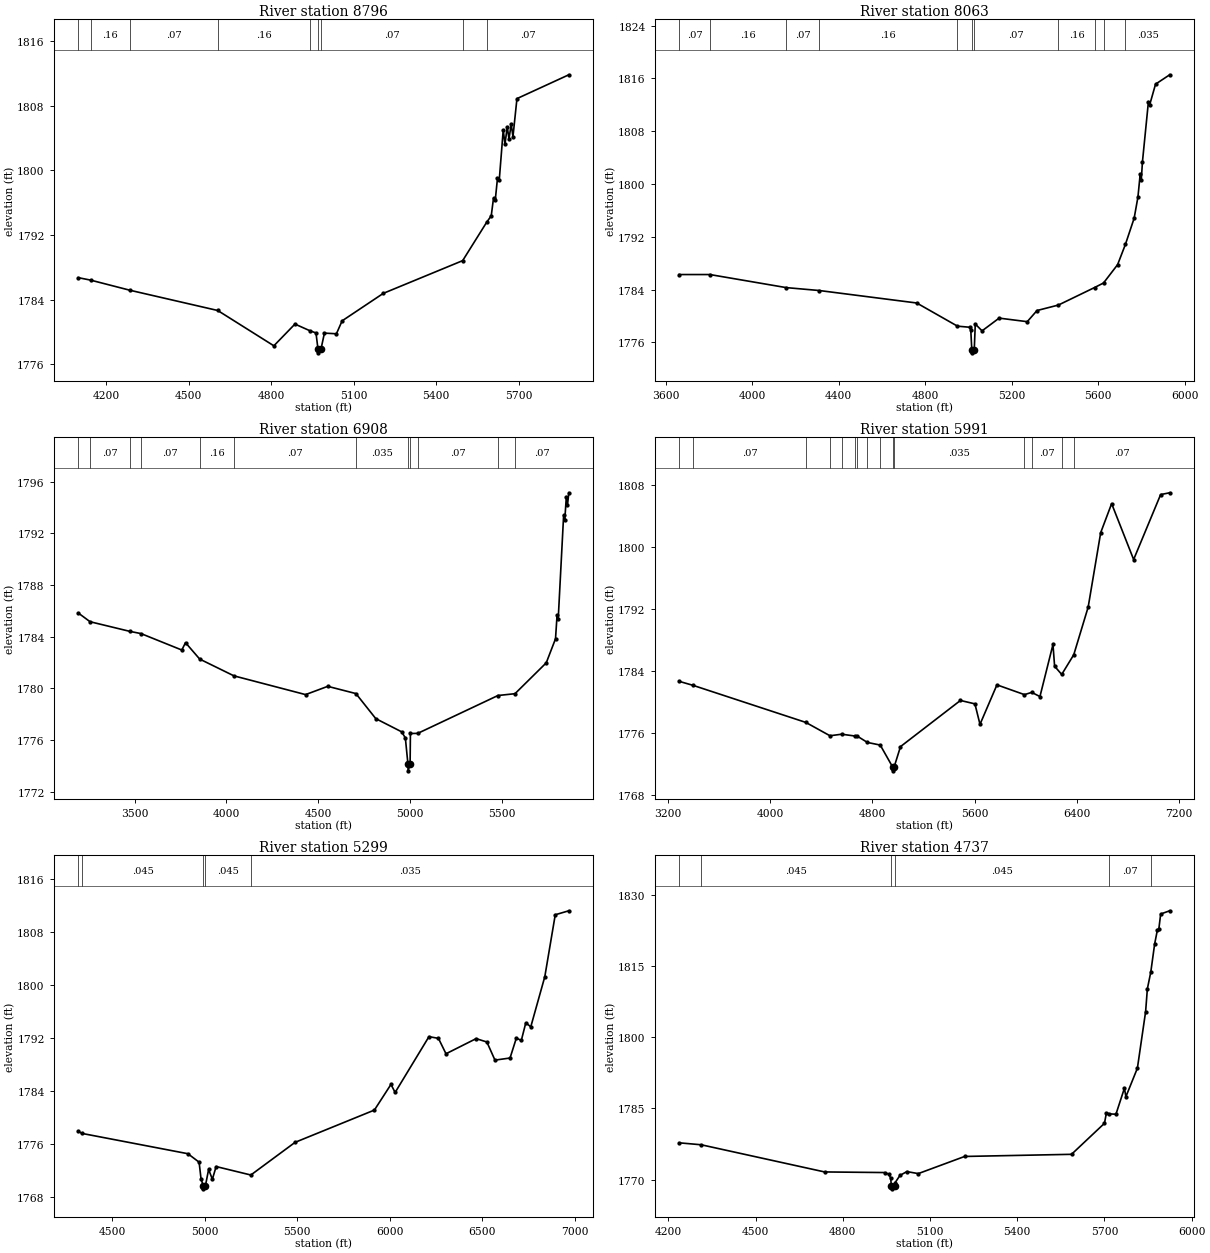
Type RM Length L Ch R = 1,8796,733,733,733
BEGIN DESCRIPTION:
Mapping XS f12c2eb7
END DESCRIPTION:
XS GIS Cut Line= 3
      1521755.13      6852225.60      1522604.08      6851850.61
      1523124.91      6851173.53
#Sta/Elev= 30
  4099.5 1786.70  4143.8 1786.40  4287.5 1785.14  4605.9 1782.64  4809.9 1778.27
  4886.5 1780.96  4940.5 1780.14  4963.0 1779.86  4970.1 1777.90  4970.6 1777.40
  4981.4 1777.90  4993.6 1779.84  5037.2 1779.76  5058.0 1781.36  5207.6 1784.76
  5496.0 1788.81  5583.1 1793.55  5599.9 1794.36  5608.1 1796.55  5614.4 1796.27
  5622.6 1799.03  5628.9 1798.74  5643.4 1804.97  5649.8 1803.23  5658.0 1805.38
  5664.3 1803.88  5672.5 1805.70  5678.8 1804.15  5693.3 1808.86  5881.8 1811.81
#Mann=9,-1,0
  4099.5    0.07       0  4143.8    0.16       0  4287.5    0.07       0
  4605.9    0.16       0  4940.5    0.07       0  4970.1    0.07       0
  4981.4    0.07       0  5496.0   0.035       0  5583.1    0.07       0
Bank Sta=4970.1,4981.4
Exp/Cntr=0.3,0.1

Type RM Length L Ch R = 1,8063,1155,1155,1155
BEGIN DESCRIPTION:
Mapping XS 8613729b
END DESCRIPTION:
XS GIS Cut Line= 3
      1521932.24      6852814.14      1522989.50      6852517.27
      1523328.04      6851397.48
#Sta/Elev= 30
  3662.3 1786.28  3804.0 1786.28  4157.2 1784.30  4309.8 1783.86  4760.5 1781.97
  4949.0 1778.46  5004.6 1778.30  5010.4 1777.94  5015.1 1774.92  5015.6 1774.42
  5026.6 1774.92  5031.3 1778.78  5062.7 1777.75  5141.6 1779.68  5271.6 1779.14
  5316.8 1780.83  5415.7 1781.66  5582.8 1784.31  5624.3 1785.00  5689.5 1787.78
  5725.8 1790.87  5766.1 1794.83  5783.5 1798.03  5793.8 1801.46  5799.0 1800.64
  5804.4 1803.38  5832.0 1812.48  5837.2 1811.92  5864.9 1815.12  5930.3 1816.54
#Mann=11,-1,0
  3662.3    0.07       0  3804.0    0.16       0  4157.2    0.07       0
  4309.8    0.16       0  4949.0    0.07       0  5015.1    0.07       0
  5026.6    0.07       0  5415.7    0.16       0  5582.8   0.035       0
  5624.3    0.07       0  5725.8   0.035       0
Bank Sta=5015.1,5026.6
Exp/Cntr=0.3,0.1

Type RM Length L Ch R = 1,6908,917,917,917
BEGIN DESCRIPTION:
MULBERRY CREEK TRIBUTARY 16 4.0
END DESCRIPTION:
XS GIS Cut Line= 3
      1522155.03      6853088.00      1523955.00      6852888.00
      1524455.01      6852187.99
#Sta/Elev= 30
  3193.5 1785.83  3257.3 1785.16  3472.2 1784.42  3535.1 1784.24  3756.9 1782.97
  3777.0 1783.54  3854.2 1782.27  4041.0 1780.97  4431.0 1779.52  4551.8 1780.16
  4705.1 1779.60  4813.4 1777.66  4954.2 1776.64  4974.4 1776.17  4988.7 1774.12
  4989.2 1773.62  5000.3 1774.12  5002.0 1776.51  5041.9 1776.52  5478.8 1779.45
  5571.6 1779.59  5741.9 1781.98  5792.3 1783.84  5800.9 1785.69  5807.0 1785.37
  5836.5 1793.40  5842.7 1793.02  5851.3 1794.84  5857.4 1794.18  5864.8 1795.14
#Mann=12,-1,0
  3193.5    0.16       0  3257.3    0.07       0  3472.2    0.16       0
  3535.1    0.07       0  3854.2    0.16       0  4041.0    0.07       0
  4705.1   0.035       0  4988.7   0.035       0  5000.3   0.035       0
  5041.9    0.07       0  5478.8   0.035       0  5571.6    0.07       0
Bank Sta=4988.7,5000.3
Exp/Cntr=0.3,0.1

Type RM Length L Ch R = 1,5991,692,692,692
BEGIN DESCRIPTION:
MULBERRY CREEK TRIBUTARY 16 3.0
END DESCRIPTION:
XS GIS Cut Line= 3
      1522913.13      6853582.27      1524605.00      6853338.00
      1526690.47      6852929.57
#Sta/Elev= 30
  3290.6 1782.66  3399.7 1782.14  4280.4 1777.37  4469.0 1775.65  4560.8 1775.85
  4662.5 1775.62  4680.7 1775.62  4761.7 1774.79  4862.1 1774.45  4958.9 1771.63
  4959.4 1771.13  4970.8 1771.63  5020.4 1774.25  5489.1 1780.20  5602.3 1779.76
  5642.0 1777.12  5774.5 1782.21  5989.7 1780.95  6046.6 1781.24  6110.7 1780.70
  6212.6 1787.41  6225.3 1784.61  6280.9 1783.55  6375.1 1786.09  6487.9 1792.24
  6585.8 1801.83  6671.2 1805.56  6843.2 1798.36  7054.3 1806.73  7125.1 1806.96
#Mann=15,-1,0
  3290.6    0.16       0  3399.7    0.07       0  4280.4   0.035       0
  4469.0    0.07       0  4560.8   0.035       0  4662.5    0.07       0
  4680.7   0.035       0  4761.7    0.07       0  4862.1   0.035       0
  4958.9    0.07       0  4970.8   0.035       0  5989.7   0.035       0
  6046.6    0.07       0  6280.9   0.035       0  6375.1    0.07       0
Bank Sta=4958.9,4970.8
Exp/Cntr=0.3,0.1

Type RM Length L Ch R = 1,5299,562,562,562
BEGIN DESCRIPTION:
MULBERRY CREEK TRIBUTARY 16 2.0
END DESCRIPTION:
XS GIS Cut Line= 3
      1524232.89      6854025.63      1524904.80      6853898.12
      1526837.03      6853517.82
#Sta/Elev= 30
  4316.1 1777.88  4335.3 1777.56  4908.6 1774.49  4969.2 1773.21  4979.8 1770.66
  4991.4 1769.68  4991.9 1769.18  5003.7 1769.68  5020.6 1772.11  5041.0 1770.63
  5061.4 1772.55  5249.1 1771.27  5488.4 1776.21  5917.5 1781.09  6007.2 1784.97
  6029.6 1783.75  6212.7 1792.19  6264.0 1791.93  6304.8 1789.60  6467.8 1791.89
  6526.0 1791.38  6569.7 1788.64  6651.3 1788.96  6685.3 1791.96  6712.4 1791.63
  6736.6 1794.29  6763.4 1793.67  6839.4 1801.26  6895.9 1810.62  6969.3 1811.22
#Mann=5,-1,0
  4316.1    0.07       0  4335.3   0.045       0  4991.4   0.045       0
  5003.7   0.045       0  5249.1   0.035       0
Bank Sta=4991.4,5003.7
Exp/Cntr=0.3,0.1

Type RM Length L Ch R = 1,4737,1305,1305,1305
BEGIN DESCRIPTION:
Mapping XS db55eae0
END DESCRIPTION:
XS GIS Cut Line= 3
      1524639.67      6854701.29      1525251.69      6854249.88
      1526144.84      6854002.74
#Sta/Elev= 30
  4237.2 1777.77  4312.8 1777.36  4737.2 1771.64  4943.9 1771.51  4958.5 1771.16
  4964.7 1770.28  4967.0 1768.58  4967.5 1768.08  4979.3 1768.58  4979.4 1769.34
  4996.6 1770.91  5020.1 1771.71  5059.6 1771.29  5219.0 1774.90  5586.7 1775.35
  5700.0 1781.88  5706.7 1784.06  5716.6 1783.87  5739.5 1783.79  5768.6 1789.26
  5773.8 1787.49  5813.3 1793.49  5841.6 1805.41  5847.6 1810.21  5859.4 1813.74
  5872.7 1819.67  5881.9 1822.53  5887.1 1822.83  5893.4 1825.96  5924.4 1826.64
#Mann=6,-1,0
  4237.2   0.035       0  4312.8   0.045       0  4967.0   0.045       0
  4979.3   0.045       0  5716.6    0.07       0  5859.4   0.035       0
Bank Sta=4967,4979.3
Exp/Cntr=0.3,0.1

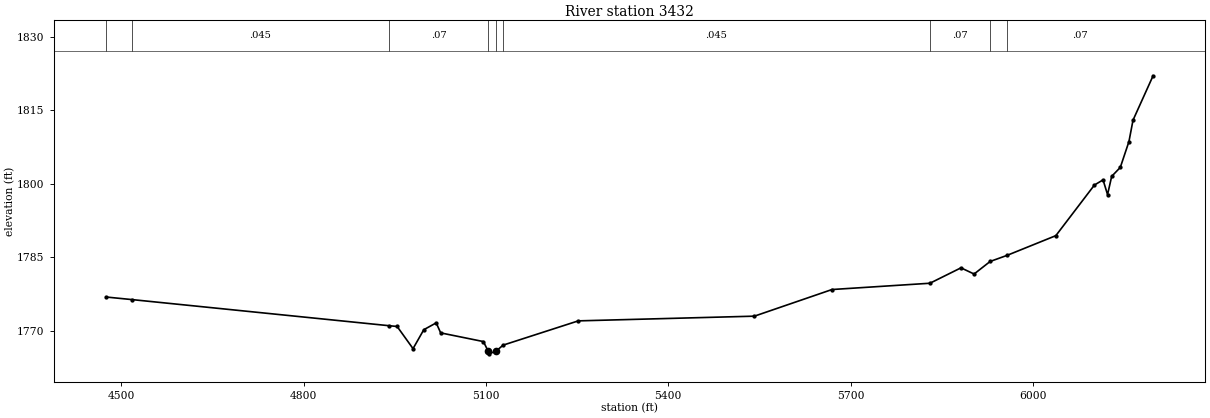
Type RM Length L Ch R = 1,3432,0,0,0
BEGIN DESCRIPTION:
MULBERRY CREEK TRIBUTARY 16 1.0
END DESCRIPTION:
XS GIS Cut Line= 3
      1525091.14      6855152.64      1525604.51      6855043.23
      1526490.23      6854237.01
#Sta/Elev= 30
  4475.1 1776.91  4517.3 1776.39  4940.1 1771.07  4953.8 1770.91  4980.0 1766.39
  4997.7 1770.25  5018.1 1771.64  5025.5 1769.60  5095.8 1767.83  5103.8 1765.83
  5104.3 1765.33  5116.2 1765.83  5128.1 1767.10  5251.9 1772.05  5541.7 1773.01
  5669.4 1778.44  5830.5 1779.72  5881.6 1782.86  5903.2 1781.60  5929.6 1784.16
  5957.4 1785.40  6037.7 1789.42  6101.2 1799.74  6115.4 1800.79  6122.8 1797.79
  6129.6 1801.51  6143.8 1803.34  6158.0 1808.60  6164.7 1812.96  6197.7 1822.01
#Mann=9,-1,0
  4475.1   0.035       0  4517.3   0.045       0  4940.1    0.07       0
  5103.8    0.07       0  5116.2    0.07       0  5128.1   0.045       0
  5830.5    0.07       0  5929.6   0.035       0  5957.4    0.07       0
Bank Sta=5103.8,5116.2
Exp/Cntr=0.3,0.1

Chan Stop Cuts=-1