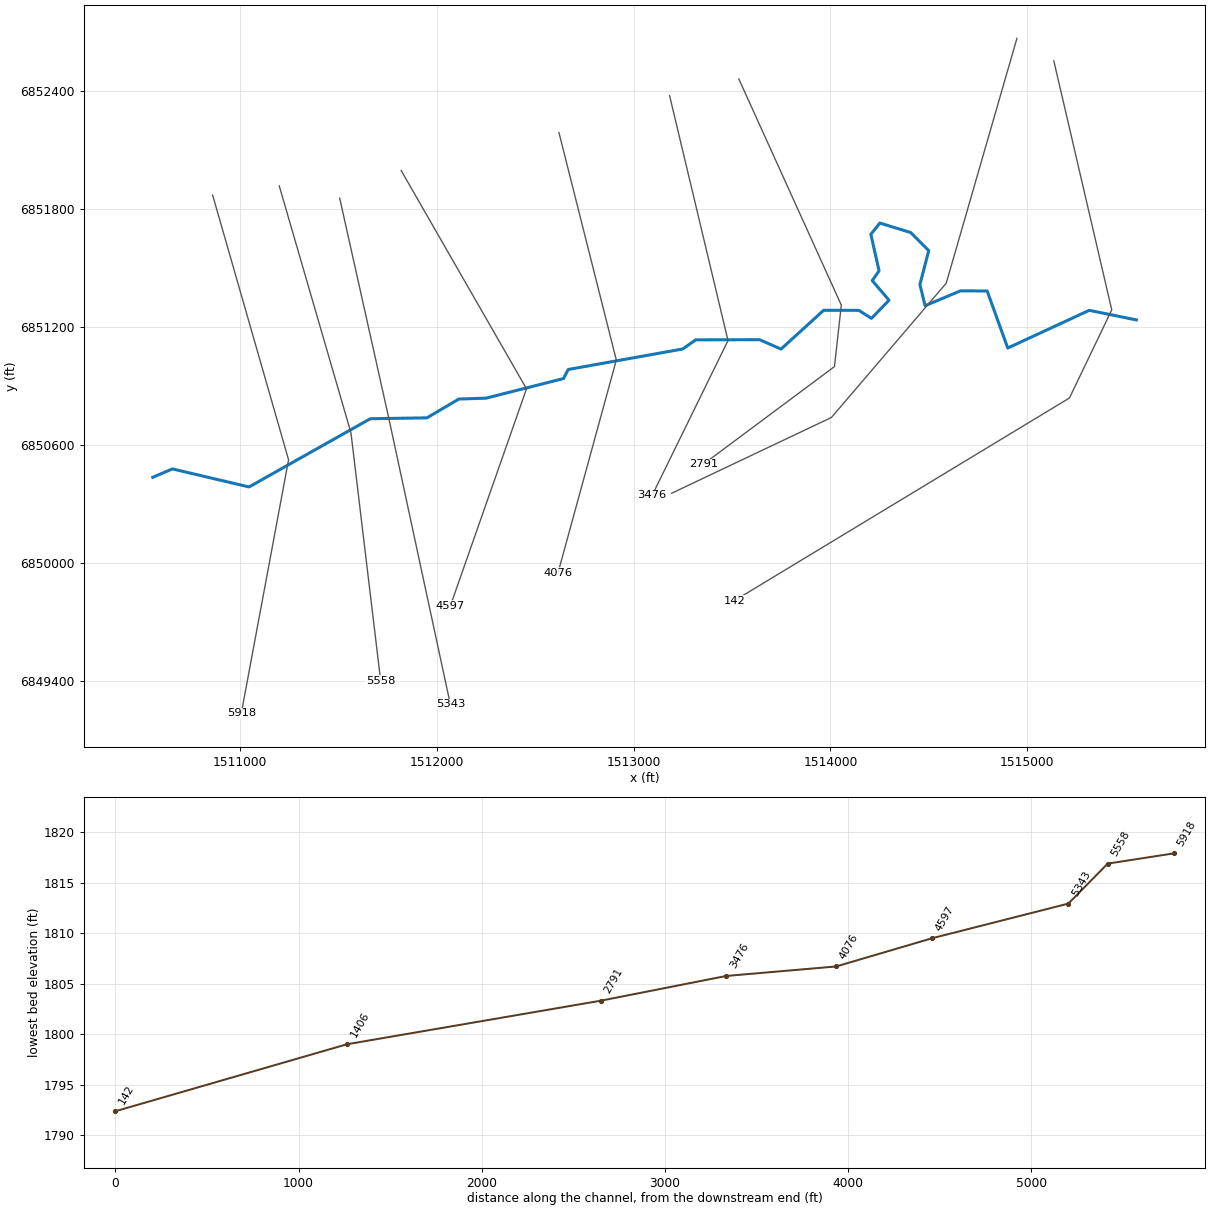
--- MULBERRY CREEK TRIBUTARY 16A.prj (project) ---

Proj Title=MULBERRY CREEK TRIBUTARY 16A Base Level Engineering
Current Plan=p01
Default Exp/Contr=0.3,0.1
English Units
Geom File=g01
Flow File=f01
Plan File=p01
BEGIN DESCRIPTION:
MULBERRY CREEK TRIBUTARY 16A
END DESCRIPTION:

--- MULBERRY CREEK TRIBUTARY 16A.p01 (plan) ---

Plan Title=Multiple Run
Short Identifier=Multiple
Geom File=g01
Flow File=f01
Subcritical Flow
K Sum by GR= 0
Std Step Tol= 0.01
Critical Tol= 0.01
Num of Std Step Trials= 20
Max Error Tol= 0.3
Flow Tol Ratio= 0.001
Split Flow NTrial= 30
Split Flow Tol= 0.02
Split Flow Ratio= 0.02
Log Output Level= 0
Friction Slope Method= 1
Unsteady Friction Slope Method= 2
Unsteady Bridges Friction Slope Method= 1
Parabolic Critical Depth
Global Vel Dist=  1 , 1 , 1
Global Log Level= 0
CheckData=True
Encroach Param= -1, 0, 0, 0
BEGIN DESCRIPTION:
Multiple Run
END DESCRIPTION:

--- MULBERRY CREEK TRIBUTARY 16A.f01 (steady flow) ---

Flow Title=Multiple
Number of Profiles=7
Profile Names=10-year,25-year,50-year,1pct_min,100-year,1pct_plu,500-year
River Rch & RM= MULBERRY CREEK T,Reach-1,5918
     358     506     632     392     782    1560    1215
River Rch & RM= MULBERRY CREEK T,Reach-1,3476
     431     616     772     482     961    1917    1507
River Rch & RM= MULBERRY CREEK T,Reach-1,142
     622     905    1151     727    1451    2894    2335
Boundary for River Rch & Prof#=MULBERRY CREEK T,Reach-1,1
Up Type=0
Dn Type=3
Dn Slope=0.005
Boundary for River Rch & Prof#=MULBERRY CREEK T,Reach-1,2
Up Type=0
Dn Type=3
Dn Slope=0.005
Boundary for River Rch & Prof#=MULBERRY CREEK T,Reach-1,3
Up Type=0
Dn Type=3
Dn Slope=0.005
Boundary for River Rch & Prof#=MULBERRY CREEK T,Reach-1,4
Up Type=0
Dn Type=3
Dn Slope=0.005
Boundary for River Rch & Prof#=MULBERRY CREEK T,Reach-1,5
Up Type=0
Dn Type=3
Dn Slope=0.005
Boundary for River Rch & Prof#=MULBERRY CREEK T,Reach-1,6
Up Type=0
Dn Type=3
Dn Slope=0.005
Boundary for River Rch & Prof#=MULBERRY CREEK T,Reach-1,7
Up Type=0
Dn Type=3
Dn Slope=0.005

--- MULBERRY CREEK TRIBUTARY 16A.g01 (geometry) ---

Geom Title=Existing Conditions

River Reach=MULBERRY CREEK T,Reach-1
Reach XY= 30
      1510555.00      6850438.00      1510654.96      6850480.69
      1511044.52      6850388.94      1511660.93      6850735.76
      1511949.07      6850740.24      1512110.93      6850835.75
      1512249.06      6850840.27      1512643.03      6850939.98
      1512666.97      6850986.02      1513249.06      6851090.26
      1513315.50      6851136.78      1513639.79      6851137.46
      1513748.91      6851089.79      1513965.43      6851286.96
      1514144.57      6851286.61      1514208.45      6851245.79
      1514297.91      6851337.98      1514212.57      6851437.99
      1514247.19      6851487.90      1514205.36      6851673.11
      1514251.29      6851730.33      1514407.44      6851682.49
      1514499.61      6851590.44      1514454.90      6851417.88
      1514481.13      6851310.24      1514660.94      6851385.78
      1514796.72      6851384.95      1514901.29      6851095.09
      1515315.50      6851286.81      1515555.00      6851238.00

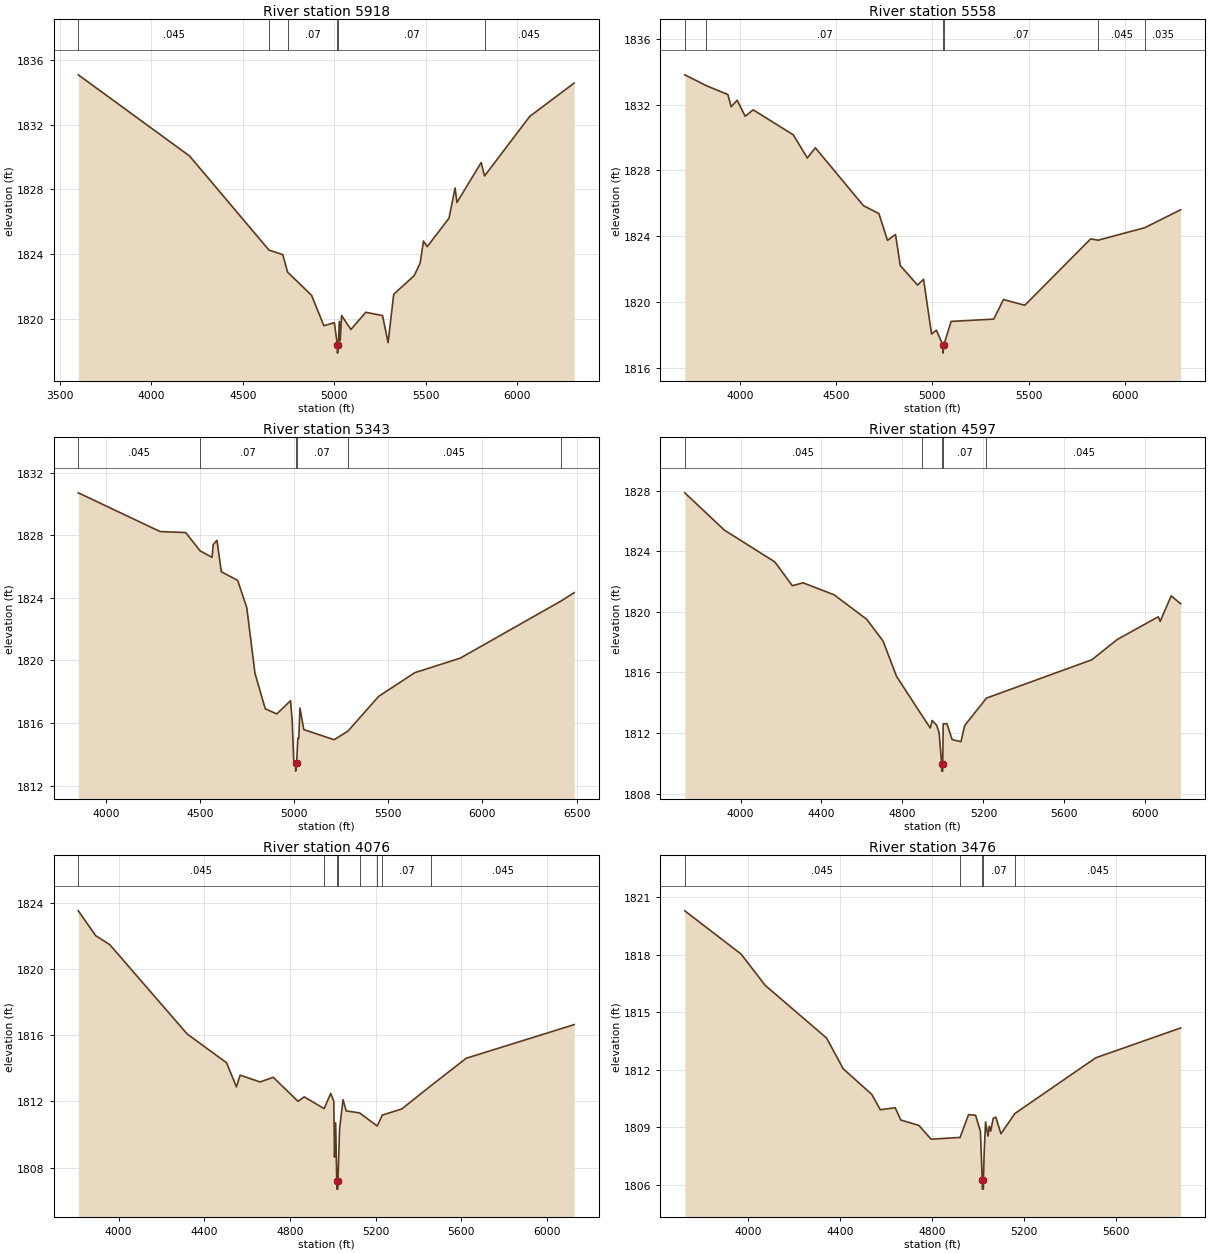
Type RM Length L Ch R = 1,5918,360,360,360
BEGIN DESCRIPTION:
MULBERRY CREEK TRIBUTARY 16A 6.0
END DESCRIPTION:
XS GIS Cut Line= 3
      1510859.47      6851872.55      1511245.45      6850526.92
      1511004.99      6849237.95
#Sta/Elev= 30
  3600.1 1835.07  4208.2 1830.06  4642.7 1824.25  4718.0 1823.97  4744.3 1822.89
  4875.3 1821.46  4942.8 1819.58  5000.0 1819.77  5016.7 1818.39  5017.1 1817.89
  5021.8 1818.39  5027.0 1819.85  5032.1 1818.65  5039.6 1820.21  5090.5 1819.35
  5171.8 1820.41  5263.4 1820.21  5293.9 1818.54  5324.4 1821.52  5436.3 1822.67
  5468.9 1823.44  5487.2 1824.81  5507.5 1824.46  5627.0 1826.22  5660.1 1828.09
  5670.3 1827.19  5802.5 1829.65  5821.3 1828.83  6068.9 1832.51  6311.2 1834.56
#Mann=6,-1,0
  3600.1   0.045       0  4642.7   0.035       0  4744.3    0.07       0
  5016.7    0.07       0  5021.8    0.07       0  5821.3   0.045       0
Bank Sta=5016.7,5021.8
Exp/Cntr=0.3,0.1

Type RM Length L Ch R = 1,5558,215,215,215
BEGIN DESCRIPTION:
Mapping XS 83a6de7f
END DESCRIPTION:
XS GIS Cut Line= 3
      1511198.01      6851919.43      1511562.59      6850664.23
      1511713.63      6849403.82
#Sta/Elev= 30
  3713.4 1833.81  3825.5 1833.15  3937.2 1832.61  3954.4 1831.87  3985.6 1832.26
  4027.3 1831.29  4068.9 1831.68  4277.2 1830.16  4350.1 1828.75  4391.8 1829.37
  4641.7 1825.85  4722.1 1825.37  4766.6 1823.74  4808.3 1824.10  4833.1 1822.21
  4922.8 1821.02  4954.1 1821.37  4995.7 1818.04  5020.5 1818.28  5054.4 1817.38
  5054.8 1816.88  5059.6 1817.38  5097.3 1818.81  5318.8 1818.95  5369.2 1820.14
  5480.0 1819.79  5822.4 1823.83  5861.5 1823.75  6103.3 1824.51  6289.9 1825.60
#Mann=6,-1,0
  3713.4   0.045       0  3825.5    0.07       0  5054.4    0.07       0
  5059.6    0.07       0  5861.5   0.045       0  6103.3   0.035       0
Bank Sta=5054.4,5059.6
Exp/Cntr=0.3,0.1

Type RM Length L Ch R = 1,5343,746,746,746
BEGIN DESCRIPTION:
MULBERRY CREEK TRIBUTARY 16A 5.0
END DESCRIPTION:
XS GIS Cut Line= 3
      1511505.29      6851856.96      1511754.97      6850738.08
      1512067.79      6849284.05
#Sta/Elev= 30
  3853.6 1830.73  4288.2 1828.25  4423.7 1828.19  4501.0 1827.01  4564.3 1826.60
  4569.7 1827.41  4590.2 1827.69  4612.9 1825.68  4699.8 1825.13  4748.3 1823.39
  4791.8 1819.19  4846.4 1816.91  4907.9 1816.58  4980.9 1817.43  4989.8 1816.07
  4997.5 1813.63  5007.7 1813.42  5008.1 1812.92  5012.9 1813.42  5019.7 1815.03
  5024.8 1815.01  5030.8 1816.96  5051.2 1815.58  5211.9 1814.93  5285.8 1815.48
  5448.4 1817.70  5640.7 1819.22  5882.3 1820.15  6416.6 1823.80  6487.3 1824.34
#Mann=6,-1,0
  3853.6   0.045       0  4501.0    0.07       0  5007.7    0.07       0
  5012.9    0.07       0  5285.8   0.045       0  6416.6    0.07       0
Bank Sta=5007.7,5012.9
Exp/Cntr=0.3,0.1

Type RM Length L Ch R = 1,4597,521,521,521
BEGIN DESCRIPTION:
MULBERRY CREEK TRIBUTARY 16A 4.0
END DESCRIPTION:
XS GIS Cut Line= 3
      1511817.82      6851997.52      1512455.00      6850888.00
      1512067.79      6849784.00
#Sta/Elev= 30
  3724.7 1827.85  3920.2 1825.39  4169.5 1823.29  4255.8 1821.72  4308.9 1821.91
  4462.2 1821.12  4623.6 1819.50  4704.3 1818.06  4770.5 1815.74  4895.1 1813.18
  4937.3 1812.33  4946.5 1812.82  4968.9 1812.51  4981.1 1812.01  4993.6 1809.98
  4994.0 1809.48  4998.5 1809.48  4998.9 1809.98  5001.3 1812.61  5019.7 1812.61
  5045.4 1811.56  5088.9 1811.43  5107.4 1812.49  5214.9 1814.30  5735.4 1816.83
  5861.3 1818.17  6063.9 1819.67  6073.0 1819.36  6127.5 1821.05  6174.1 1820.53
#Mann=5,-1,0
  3724.7   0.045       0  4895.1    0.07       0  4993.6    0.07       0
  4998.9    0.07       0  5214.9   0.045       0
Bank Sta=4993.6,4998.9
Exp/Cntr=0.3,0.1

Type RM Length L Ch R = 1,4076,600,600,600
BEGIN DESCRIPTION:
Mapping XS 1d84a73f
END DESCRIPTION:
XS GIS Cut Line= 3
      1512619.88      6852190.27      1512911.55      6851034.02
      1512615.00      6849951.89
#Sta/Elev= 30
  3811.9 1823.50  3892.9 1822.00  3958.6 1821.46  4319.6 1816.07  4503.8 1814.33
  4550.0 1812.87  4567.1 1813.58  4659.9 1813.17  4721.8 1813.45  4837.5 1812.00
  4866.2 1812.27  4959.5 1811.56  4990.0 1812.48  5004.4 1812.00  5007.8 1808.63
  5013.0 1810.70  5018.3 1807.20  5018.7 1806.70  5023.2 1806.70  5023.7 1807.20
  5031.4 1810.34  5047.5 1812.10  5062.5 1811.42  5125.0 1811.30  5207.1 1810.51
  5230.9 1811.17  5321.7 1811.54  5457.8 1812.94  5622.4 1814.60  6126.4 1816.63
#Mann=8,-1,0
  3811.9   0.045       0  4959.5    0.07       0  5018.3    0.07       0
  5023.7    0.07       0  5125.0    0.07       0  5207.1   0.045       0
  5230.9    0.07       0  5457.8   0.045       0
Bank Sta=5018.3,5023.7
Exp/Cntr=0.3,0.1

Type RM Length L Ch R = 1,3476,685,685,685
BEGIN DESCRIPTION:
Mapping XS de4720d5
END DESCRIPTION:
XS GIS Cut Line= 3
      1513182.39      6852377.74      1513479.26      6851132.98
      1513093.83      6850346.51
#Sta/Elev= 30
  3725.5 1820.30  3970.3 1818.04  4074.8 1816.41  4342.1 1813.65  4414.0 1812.05
  4538.4 1810.71  4575.3 1809.91  4640.2 1810.01  4664.7 1809.37  4743.0 1809.09
  4796.2 1808.37  4922.2 1808.46  4958.9 1809.65  4989.7 1809.62  5010.7 1808.78
  5018.5 1806.26  5018.9 1805.76  5023.5 1805.76  5023.9 1806.26  5026.8 1807.63
  5033.0 1809.27  5043.7 1808.53  5049.3 1809.05  5055.3 1808.79  5066.2 1809.46
  5077.5 1809.52  5099.9 1808.65  5160.4 1809.71  5511.8 1812.62  5881.0 1814.18
#Mann=5,-1,0
  3725.5   0.045       0  4922.2    0.07       0  5018.5    0.07       0
  5023.9    0.07       0  5160.4   0.045       0
Bank Sta=5018.5,5023.9
Exp/Cntr=0.3,0.1

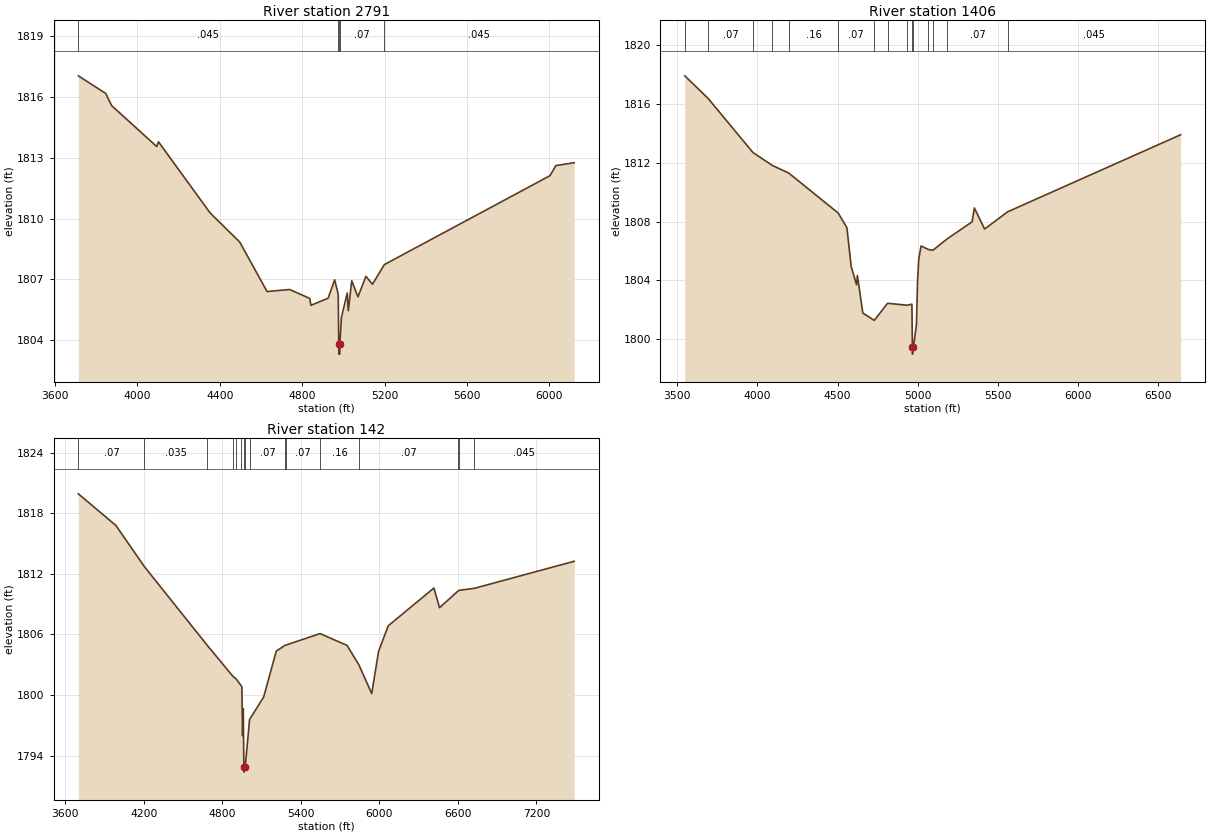
Type RM Length L Ch R = 1,2791,1385,1385,1385
BEGIN DESCRIPTION:
Mapping XS 97e84861
END DESCRIPTION:
XS GIS Cut Line= 4
      1513534.37      6852462.69      1514055.22      6851313.34
      1514020.50      6851000.84      1513353.86      6850504.34
#Sta/Elev= 30
  3712.8 1817.05  3845.9 1816.18  3874.5 1815.58  4093.3 1813.56  4102.2 1813.79
  4352.8 1810.28  4496.8 1808.84  4629.2 1806.40  4738.7 1806.50  4836.6 1806.06
  4842.1 1805.72  4925.6 1806.07  4957.5 1806.98  4974.7 1806.26  4975.4 1805.60
  4977.3 1803.81  4977.7 1803.31  4982.3 1803.31  4982.8 1803.81  4990.1 1805.12
  5018.6 1806.33  5023.6 1805.45  5040.4 1806.93  5070.6 1806.14  5109.2 1807.15
  5141.0 1806.76  5198.7 1807.73  6002.9 1812.12  6031.6 1812.62  6120.3 1812.76
#Mann=5,-1,0
  3712.8   0.045       0  4975.4    0.07       0  4977.3    0.07       0
  4982.8    0.07       0  5198.7   0.045       0
Bank Sta=4977.3,4982.8
Exp/Cntr=0.3,0.1

Type RM Length L Ch R = 1,1406,1264,1264,1264
BEGIN DESCRIPTION:
Mapping XS 91c67024
END DESCRIPTION:
XS GIS Cut Line= 4
      1514948.00      6852669.41      1514588.63      6851424.65
      1514005.30      6850742.35      1513192.83      6850356.95
#Sta/Elev= 30
  3547.3 1817.89  3692.5 1816.36  3972.0 1812.69  4093.0 1811.81  4195.7 1811.29
  4503.9 1808.58  4558.4 1807.58  4585.0 1804.95  4618.6 1803.71  4623.8 1804.34
  4657.5 1801.79  4728.9 1801.29  4812.1 1802.45  4935.2 1802.32  4963.7 1802.39
  4966.9 1799.50  4967.4 1799.00  4973.6 1799.50  4992.2 1801.02  4998.8 1803.86
  5006.5 1805.45  5020.8 1806.34  5067.1 1806.10  5094.8 1806.05  5184.8 1806.83
  5339.1 1807.98  5353.4 1808.92  5417.4 1807.49  5560.9 1808.66  6639.8 1813.89
#Mann=15,-1,0
  3547.3   0.035       0  3692.5    0.07       0  3972.0   0.035       0
  4093.0    0.07       0  4195.7    0.16       0  4503.9    0.07       0
  4728.9    0.16       0  4812.1    0.07       0  4935.2    0.16       0
  4966.9    0.07       0  4973.6    0.16       0  5067.1    0.07       0
  5094.8    0.16       0  5184.8    0.07       0  5560.9   0.045       0
Bank Sta=4966.9,4973.6
Exp/Cntr=0.3,0.1

Type RM Length L Ch R = 1,142,0,0,0
BEGIN DESCRIPTION:
MULBERRY CREEK TRIBUTARY 16A 3.0
END DESCRIPTION:
XS GIS Cut Line= 4
      1515135.50      6852554.88      1515430.00      6851289.04
      1515214.94      6850841.12      1513510.47      6849810.04
#Sta/Elev= 30
  3699.5 1819.93  3986.5 1816.80  4203.7 1812.73  4683.2 1804.95  4881.9 1801.84
  4907.3 1801.57  4944.7 1800.91  4948.9 1800.82  4954.5 1795.99  4959.7 1798.66
  4964.3 1792.87  4964.8 1792.37  4974.5 1792.87  5008.0 1797.58  5115.7 1799.81
  5211.9 1804.35  5279.1 1804.93  5285.9 1804.95  5545.9 1806.09  5753.1 1804.92
  5843.7 1802.98  5941.3 1800.15  5993.7 1804.33  6067.4 1806.86  6416.6 1810.60
  6459.3 1808.65  6598.8 1810.28  6611.9 1810.38  6725.6 1810.57  7488.1 1813.25
#Mann=16,-1,0
  3699.5    0.07       0  4203.7   0.035       0  4683.2    0.07       0
  4881.9   0.035       0  4907.3    0.07       0  4944.7   0.035       0
  4964.3   0.035       0  4974.5   0.035       0  5008.0    0.07       0
  5279.1    0.16       0  5285.9    0.07       0  5545.9    0.16       0
  5843.7    0.07       0  6598.8   0.045       0  6611.9    0.07       0
  6725.6   0.045       0
Bank Sta=4964.3,4974.5
Exp/Cntr=0.3,0.1

Chan Stop Cuts=-1