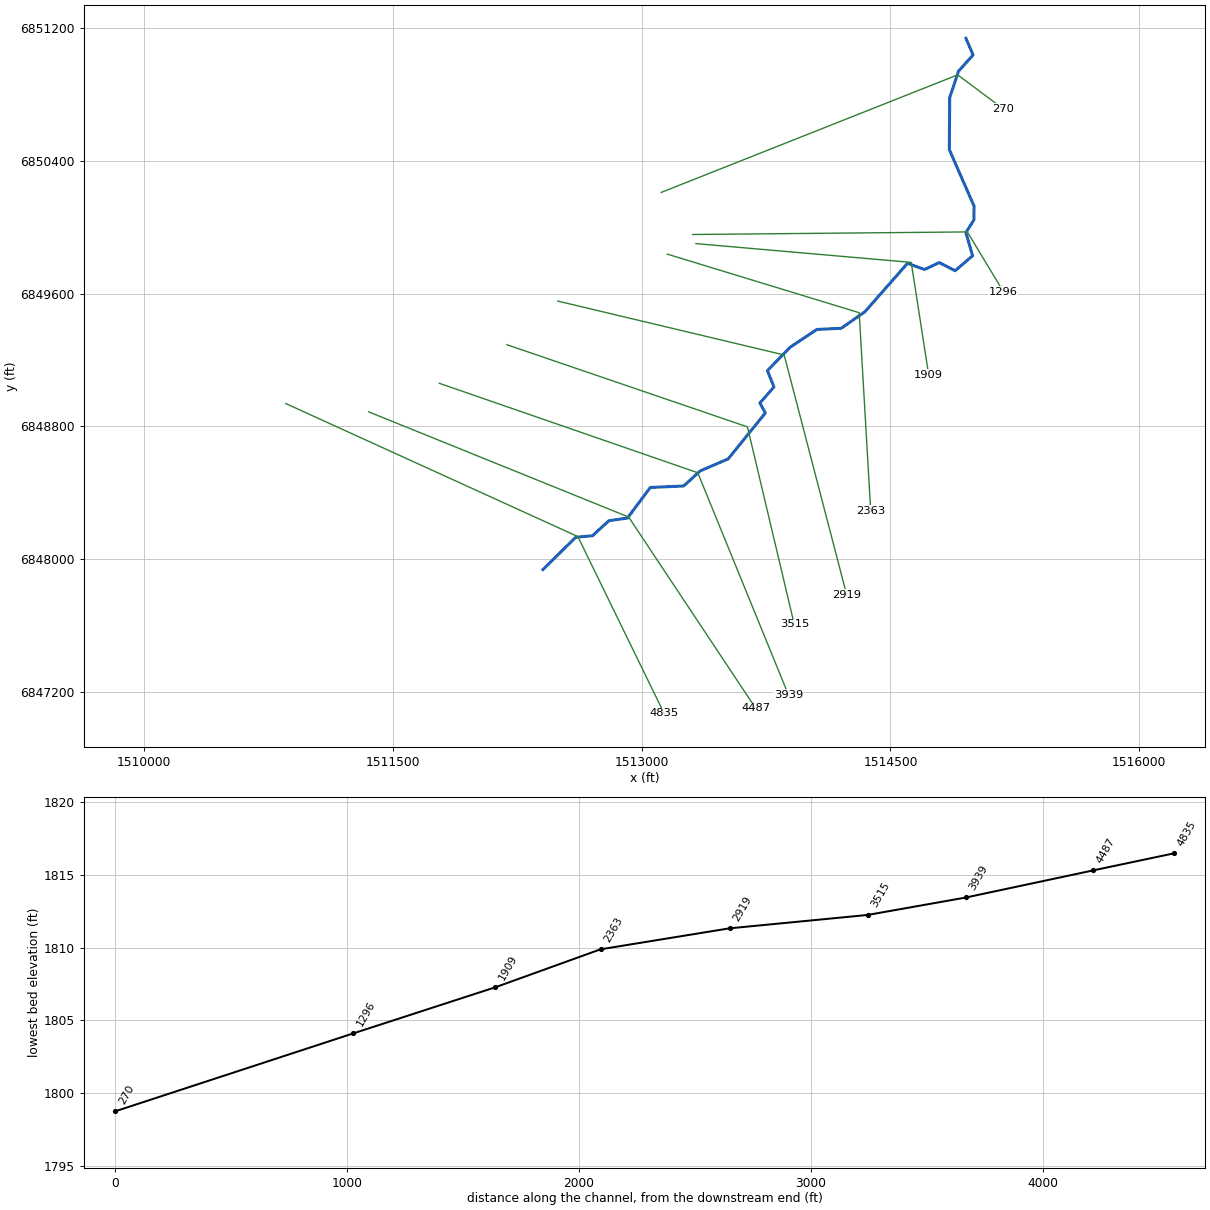
--- MULBERRY CREEK TRIBUTARY 16A_1.prj (project) ---

Proj Title=MULBERRY CREEK TRIBUTARY 16A_1 Base Level Engineering
Current Plan=p01
Default Exp/Contr=0.3,0.1
English Units
Geom File=g01
Flow File=f01
Plan File=p01
BEGIN DESCRIPTION:
MULBERRY CREEK TRIBUTARY 16A_1
END DESCRIPTION:

--- MULBERRY CREEK TRIBUTARY 16A_1.p01 (plan) ---

Plan Title=Multiple Run
Short Identifier=Multiple
Geom File=g01
Flow File=f01
Subcritical Flow
K Sum by GR= 0
Std Step Tol= 0.01
Critical Tol= 0.01
Num of Std Step Trials= 20
Max Error Tol= 0.3
Flow Tol Ratio= 0.001
Split Flow NTrial= 30
Split Flow Tol= 0.02
Split Flow Ratio= 0.02
Log Output Level= 0
Friction Slope Method= 1
Unsteady Friction Slope Method= 2
Unsteady Bridges Friction Slope Method= 1
Parabolic Critical Depth
Global Vel Dist=  1 , 1 , 1
Global Log Level= 0
CheckData=True
Encroach Param= -1, 0, 0, 0
BEGIN DESCRIPTION:
Multiple Run
END DESCRIPTION:

--- MULBERRY CREEK TRIBUTARY 16A_1.f01 (steady flow) ---

Flow Title=Multiple
Number of Profiles=7
Profile Names=10-year,25-year,50-year,1pct_min,100-year,1pct_plu,500-year
River Rch & RM= MULBERRY CREEK T,Reach-1,4835
     279     389     481     296     590    1177     899
Boundary for River Rch & Prof#=MULBERRY CREEK T,Reach-1,1
Up Type=0
Dn Type=3
Dn Slope=0.005
Boundary for River Rch & Prof#=MULBERRY CREEK T,Reach-1,2
Up Type=0
Dn Type=3
Dn Slope=0.005
Boundary for River Rch & Prof#=MULBERRY CREEK T,Reach-1,3
Up Type=0
Dn Type=3
Dn Slope=0.005
Boundary for River Rch & Prof#=MULBERRY CREEK T,Reach-1,4
Up Type=0
Dn Type=3
Dn Slope=0.005
Boundary for River Rch & Prof#=MULBERRY CREEK T,Reach-1,5
Up Type=0
Dn Type=3
Dn Slope=0.005
Boundary for River Rch & Prof#=MULBERRY CREEK T,Reach-1,6
Up Type=0
Dn Type=3
Dn Slope=0.005
Boundary for River Rch & Prof#=MULBERRY CREEK T,Reach-1,7
Up Type=0
Dn Type=3
Dn Slope=0.005

--- MULBERRY CREEK TRIBUTARY 16A_1.g01 (geometry) ---

Geom Title=Existing Conditions

River Reach=MULBERRY CREEK T,Reach-1
Reach XY= 30
      1512405.00      6847938.00      1512602.57      6848132.48
      1512703.50      6848141.63      1512802.58      6848232.46
      1512914.81      6848248.51      1513052.30      6848432.64
      1513253.53      6848441.55      1513352.71      6848532.15
      1513521.71      6848604.63      1513745.70      6848881.33
      1513713.03      6848941.33      1513797.63      6849037.91
      1513758.16      6849136.35      1513895.32      6849277.22
      1514056.47      6849384.45      1514203.53      6849391.55
      1514346.50      6849491.55      1514602.71      6849782.89
      1514705.00      6849745.62      1514794.30      6849787.16
      1514889.67      6849737.95      1514994.82      6849828.29
      1514954.73      6849967.82      1515002.81      6850043.97
      1515003.91      6850127.46      1514854.64      6850467.85
      1514857.26      6850782.06      1514910.55      6850940.43
      1514997.94      6851037.94      1514955.00      6851138.00

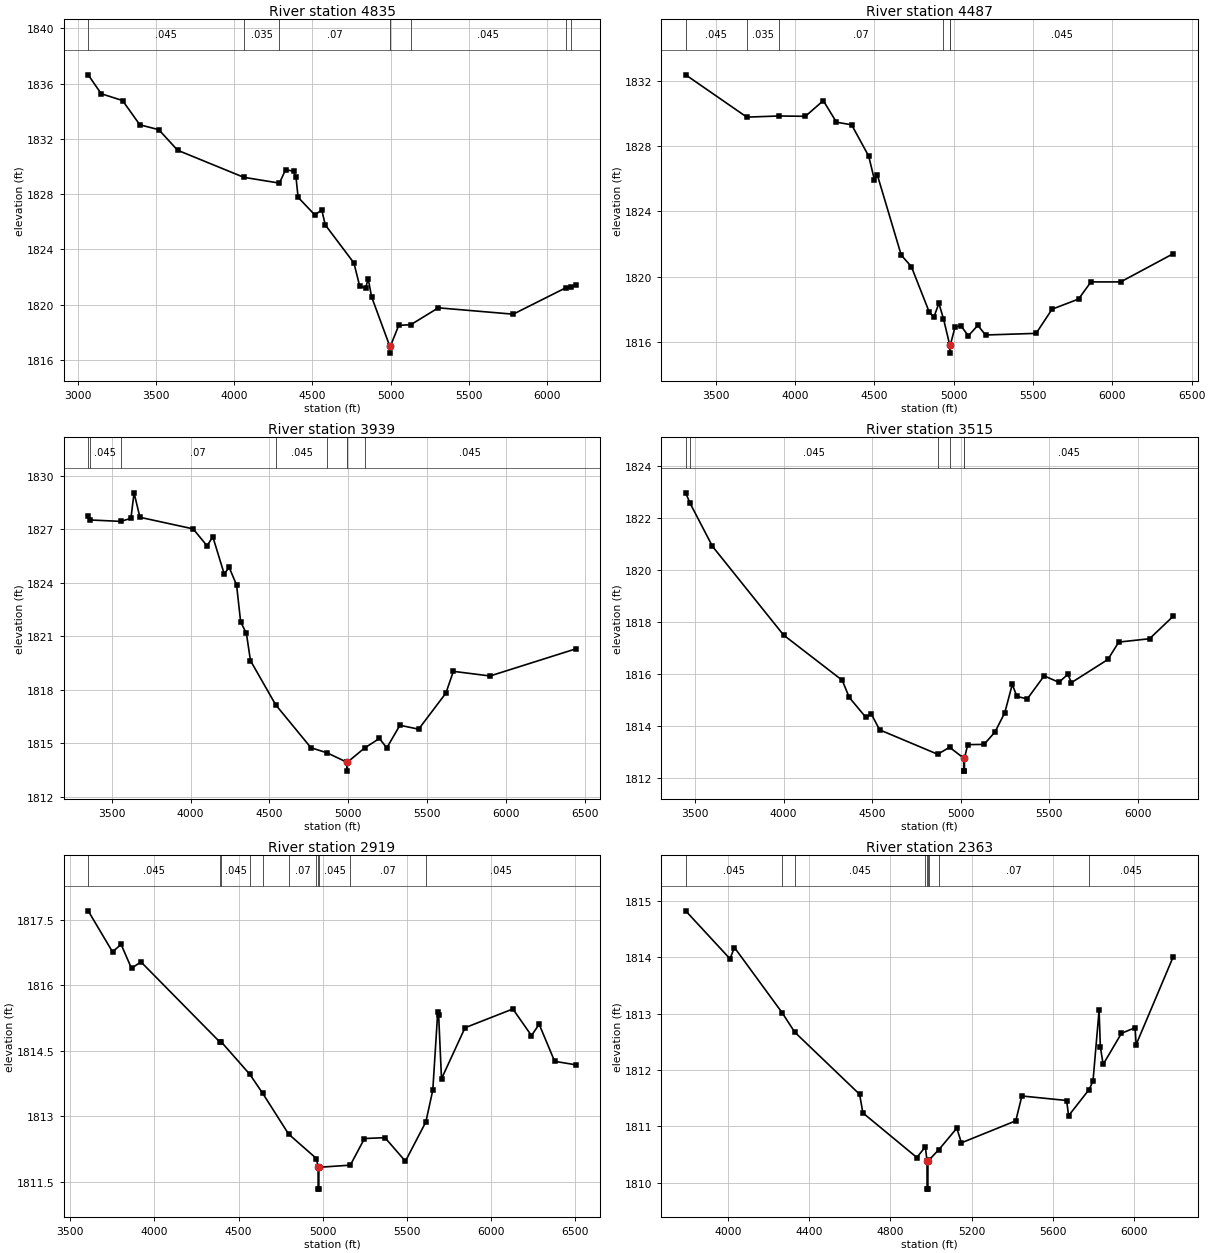
Type RM Length L Ch R = 1,4835,348,348,348
BEGIN DESCRIPTION:
MULBERRY CREEK TRIBUTARY 16A_1 6.0
END DESCRIPTION:
XS GIS Cut Line= 3
      1510855.01      6848938.00      1512615.48      6848136.83
      1513135.32      6847071.83
#Sta/Elev= 30
  3065.8 1836.63  3149.2 1835.26  3285.5 1834.77  3396.3 1833.01  3517.1 1832.66
  3637.9 1831.17  4061.2 1829.21  4289.0 1828.79  4328.5 1829.76  4380.1 1829.65
  4395.2 1829.20  4408.7 1827.76  4516.0 1826.48  4560.0 1826.85  4582.0 1825.77
  4765.5 1823.01  4801.7 1821.37  4840.2 1821.16  4856.6 1821.88  4878.6 1820.56
  4995.0 1816.98  4995.2 1816.48  4999.0 1816.98  5052.3 1818.49  5129.9 1818.54
  5305.7 1819.76  5784.3 1819.30  6119.0 1821.20  6156.1 1821.24  6185.1 1821.42
#Mann=8,-1,0
  3065.8   0.045       0  4061.2   0.035       0  4289.0    0.07       0
  4995.0    0.07       0  4999.0    0.07       0  5129.9   0.045       0
  6119.0   0.035       0  6156.1   0.045       0
Bank Sta=4995,4999
Exp/Cntr=0.3,0.1

Type RM Length L Ch R = 1,4487,548,548,548
BEGIN DESCRIPTION:
MULBERRY CREEK TRIBUTARY 16A_1 5.0
END DESCRIPTION:
XS GIS Cut Line= 3
      1511355.03      6848887.99      1512921.79      6848254.44
      1513688.15      6847101.39
#Sta/Elev= 30
  3310.0 1832.35  3695.6 1829.76  3897.5 1829.83  4064.9 1829.81  4177.6 1830.77
  4260.8 1829.45  4356.3 1829.29  4464.1 1827.37  4499.5 1825.94  4518.1 1826.23
  4669.1 1821.31  4732.8 1820.61  4845.4 1817.83  4874.9 1817.51  4906.4 1818.36
  4935.5 1817.41  4974.8 1815.81  4975.1 1815.31  4978.8 1815.81  5007.7 1816.89
  5043.8 1817.00  5092.4 1816.37  5151.8 1817.01  5200.7 1816.42  5519.4 1816.52
  5620.1 1818.00  5786.9 1818.62  5865.1 1819.67  6052.4 1819.67  6384.5 1821.40
#Mann=6,-1,0
  3310.0   0.045       0  3695.6   0.035       0  3897.5    0.07       0
  4935.5   0.045       0  4974.8   0.045       0  4978.8   0.045       0
Bank Sta=4974.8,4978.8
Exp/Cntr=0.3,0.1

Type RM Length L Ch R = 1,3939,424,424,424
BEGIN DESCRIPTION:
MULBERRY CREEK TRIBUTARY 16A_1 3.0
END DESCRIPTION:
XS GIS Cut Line= 3
      1511779.99      6849060.24      1513338.34      6848521.32
      1513884.17      6847185.22
#Sta/Elev= 30
  3351.1 1827.76  3362.7 1827.52  3557.1 1827.44  3622.1 1827.61  3642.1 1829.04
  3679.2 1827.67  4016.7 1827.02  4105.0 1826.07  4141.4 1826.58  4213.5 1824.50
  4245.2 1824.86  4292.0 1823.88  4317.9 1821.81  4354.3 1821.17  4380.2 1819.64
  4539.7 1817.17  4763.7 1814.76  4867.4 1814.47  4991.0 1813.95  4991.3 1813.45
  4995.0 1813.95  5104.4 1814.75  5198.0 1815.28  5244.5 1814.75  5327.7 1816.02
  5446.5 1815.80  5619.3 1817.82  5666.7 1819.04  5899.1 1818.78  6443.3 1820.30
#Mann=8,-1,0
  3351.1   0.035       0  3362.7   0.045       0  3557.1    0.07       0
  4539.7   0.045       0  4867.4    0.07       0  4991.0    0.07       0
  4995.0    0.07       0  5104.4   0.045       0
Bank Sta=4991,4995
Exp/Cntr=0.3,0.1

Type RM Length L Ch R = 1,3515,596,596,596
BEGIN DESCRIPTION:
Mapping XS d2c070a9
END DESCRIPTION:
XS GIS Cut Line= 3
      1512188.25      6849292.29      1513637.89      6848797.51
      1513920.01      6847608.26
#Sta/Elev= 30
  3446.5 1822.97  3470.5 1822.58  3597.7 1820.91  3999.7 1817.49  4330.6 1815.75
  4370.3 1815.09  4464.3 1814.32  4495.6 1814.44  4542.0 1813.84  4869.7 1812.90
  4937.1 1813.17  5016.6 1812.75  5016.9 1812.25  5020.8 1812.25  5021.1 1812.75
  5039.4 1813.27  5131.9 1813.28  5193.6 1813.76  5248.7 1814.50  5290.9 1815.59
  5316.9 1815.13  5375.4 1815.03  5471.1 1815.92  5554.5 1815.67  5604.7 1815.98
  5625.2 1815.66  5830.8 1816.55  5892.2 1817.22  6066.3 1817.35  6200.5 1818.22
#Mann=6,-1,0
  3446.5    0.07       0  3470.5   0.045       0  4869.7    0.07       0
  4937.1   0.045       0  5016.6   0.045       0  5021.1   0.045       0
Bank Sta=5016.6,5021.1
Exp/Cntr=0.3,0.1

Type RM Length L Ch R = 1,2919,556,556,556
BEGIN DESCRIPTION:
Mapping XS 6e94dc0f
END DESCRIPTION:
XS GIS Cut Line= 3
      1512494.70      6849555.31      1513859.24      6849230.67
      1514235.98      6847786.22
#Sta/Elev= 30
  3607.2 1817.71  3751.7 1816.77  3802.8 1816.94  3864.5 1816.39  3920.3 1816.54
  4387.1 1814.71  4398.6 1814.70  4567.3 1813.96  4642.7 1813.53  4797.6 1812.59
  4962.8 1812.03  4972.3 1811.83  4972.7 1811.33  4976.6 1811.33  4976.9 1811.83
  5163.7 1811.88  5247.8 1812.49  5369.3 1812.51  5490.7 1811.97  5612.1 1812.87
  5653.3 1813.60  5682.8 1815.40  5688.0 1815.32  5705.0 1813.86  5844.7 1815.03
  6128.7 1815.46  6239.2 1814.85  6284.8 1815.11  6376.7 1814.26  6502.6 1814.18
#Mann=11,-1,0
  3607.2   0.045       0  4387.1    0.07       0  4398.6   0.045       0
  4567.3    0.07       0  4642.7   0.045       0  4797.6    0.07       0
  4962.8   0.045       0  4972.3   0.045       0  4976.9   0.045       0
  5163.7    0.07       0  5612.1   0.045       0
Bank Sta=4972.3,4976.9
Exp/Cntr=0.3,0.1

Type RM Length L Ch R = 1,2363,454,454,454
BEGIN DESCRIPTION:
MULBERRY CREEK TRIBUTARY 16A_1 2.0
END DESCRIPTION:
XS GIS Cut Line= 3
      1513155.02      6849837.99      1514311.44      6849485.30
      1514380.82      6848292.71
#Sta/Elev= 30
  3791.0 1814.82  4009.5 1813.97  4031.4 1814.17  4267.5 1813.01  4328.7 1812.67
  4648.3 1811.57  4664.5 1811.24  4930.5 1810.45  4972.4 1810.64  4980.5 1810.39
  4980.9 1809.89  4984.8 1809.89  4985.1 1810.39  4991.2 1810.41  5039.2 1810.59
  5127.5 1810.97  5150.0 1810.71  5418.0 1811.10  5448.1 1811.54  5668.7 1811.46
  5678.4 1811.19  5778.5 1811.65  5798.6 1811.80  5828.7 1813.06  5834.9 1812.41
  5848.7 1812.10  5938.9 1812.65  6006.2 1812.75  6011.2 1812.45  6194.6 1814.01
#Mann=9,-1,0
  3791.0   0.045       0  4267.5   0.035       0  4328.7   0.045       0
  4972.4    0.07       0  4980.5   0.045       0  4985.1    0.07       0
  4991.2   0.045       0  5039.2    0.07       0  5778.5   0.045       0
Bank Sta=4980.5,4985.1
Exp/Cntr=0.3,0.1

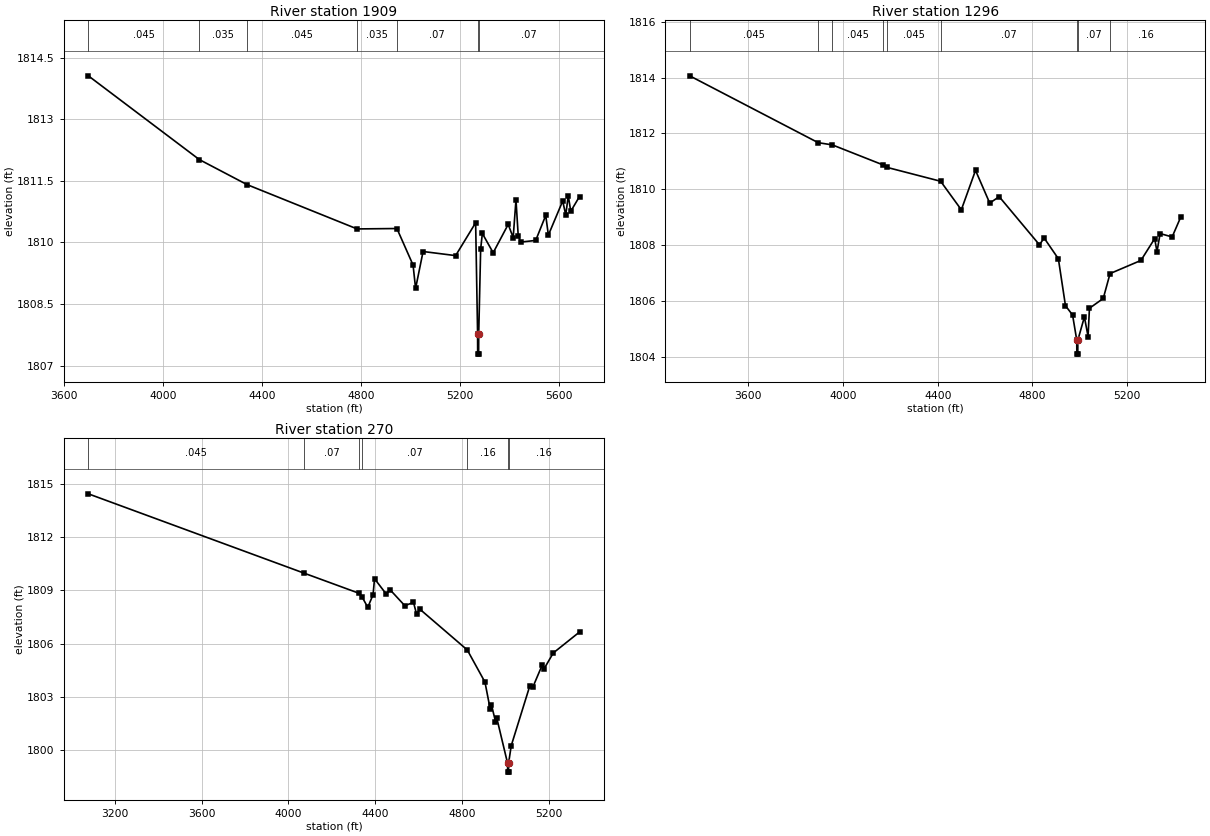
Type RM Length L Ch R = 1,1909,613,613,613
BEGIN DESCRIPTION:
Mapping XS 6faf8e9d
END DESCRIPTION:
XS GIS Cut Line= 3
      1513327.59      6849901.50      1514625.16      6849788.33
      1514730.00      6849113.01
#Sta/Elev= 30
  3697.5 1814.06  4146.1 1812.02  4339.1 1811.41  4784.2 1810.33  4945.1 1810.34
  5010.4 1809.45  5020.6 1808.88  5050.9 1809.78  5182.5 1809.68  5263.4 1810.48
  5271.3 1807.78  5271.6 1807.28  5275.5 1807.28  5275.9 1807.78  5283.7 1809.84
  5290.5 1810.22  5334.3 1809.75  5395.0 1810.44  5415.2 1810.12  5426.5 1811.04
  5435.5 1810.17  5445.6 1810.01  5506.3 1810.05  5546.8 1810.66  5557.5 1810.18
  5615.4 1811.01  5627.8 1810.67  5637.9 1811.14  5648.0 1810.76  5683.4 1811.12
#Mann=7,-1,0
  3697.5   0.045       0  4146.1   0.035       0  4339.1   0.045       0
  4784.2   0.035       0  4945.1    0.07       0  5271.3    0.07       0
  5275.9    0.07       0
Bank Sta=5271.3,5275.9
Exp/Cntr=0.3,0.1

Type RM Length L Ch R = 1,1296,1026,1026,1026
BEGIN DESCRIPTION:
Mapping XS fb74c7b7
END DESCRIPTION:
XS GIS Cut Line= 3
      1513307.12      6849956.36      1514963.41      6849971.99
      1515179.99      6849613.02
#Sta/Elev= 30
  3352.0 1814.06  3895.0 1811.67  3955.0 1811.59  4167.5 1810.88  4184.3 1810.79
  4412.5 1810.29  4499.9 1809.27  4559.9 1810.68  4619.9 1809.51  4659.9 1809.74
  4829.9 1808.02  4849.9 1808.26  4910.0 1807.52  4940.0 1805.84  4970.0 1805.51
  4987.7 1804.61  4988.0 1804.11  4992.0 1804.11  4992.3 1804.61  5020.0 1805.44
  5035.5 1804.74  5041.3 1805.75  5099.6 1806.10  5128.4 1806.99  5258.8 1807.46
  5317.0 1808.24  5326.7 1807.77  5340.0 1808.42  5390.8 1808.30  5427.6 1809.02
#Mann=9,-1,0
  3352.0   0.045       0  3895.0   0.035       0  3955.0   0.045       0
  4167.5    0.07       0  4184.3   0.045       0  4412.5    0.07       0
  4987.7    0.07       0  4992.3    0.07       0  5128.4    0.16       0
Bank Sta=4987.7,4992.3
Exp/Cntr=0.3,0.1

Type RM Length L Ch R = 1,270,0,0,0
BEGIN DESCRIPTION:
MULBERRY CREEK TRIBUTARY 16A_1 1.0
END DESCRIPTION:
XS GIS Cut Line= 3
      1513117.91      6850209.83      1514905.13      6850917.95
      1515180.03      6850712.98
#Sta/Elev= 30
  3077.6 1814.43  4073.4 1809.96  4326.1 1808.83  4340.1 1808.62  4366.4 1808.04
  4390.7 1808.75  4397.5 1809.65  4451.3 1808.79  4469.1 1809.03  4537.3 1808.13
  4577.2 1808.32  4591.1 1807.67  4606.9 1807.93  4825.2 1805.64  4906.8 1803.83
  4931.1 1802.30  4936.5 1802.56  4955.4 1801.61  4960.8 1801.83  5011.1 1799.26
  5011.4 1798.76  5015.4 1798.76  5015.8 1799.26  5028.0 1800.25  5113.5 1803.61
  5128.1 1803.56  5171.9 1804.82  5178.1 1804.55  5221.9 1805.47  5342.9 1806.65
#Mann=7,-1,0
  3077.6   0.045       0  4073.4    0.07       0  4326.1   0.045       0
  4340.1    0.07       0  4825.2    0.16       0  5011.1    0.07       0
  5015.8    0.16       0
Bank Sta=5011.1,5015.8
Exp/Cntr=0.3,0.1

Chan Stop Cuts=-1