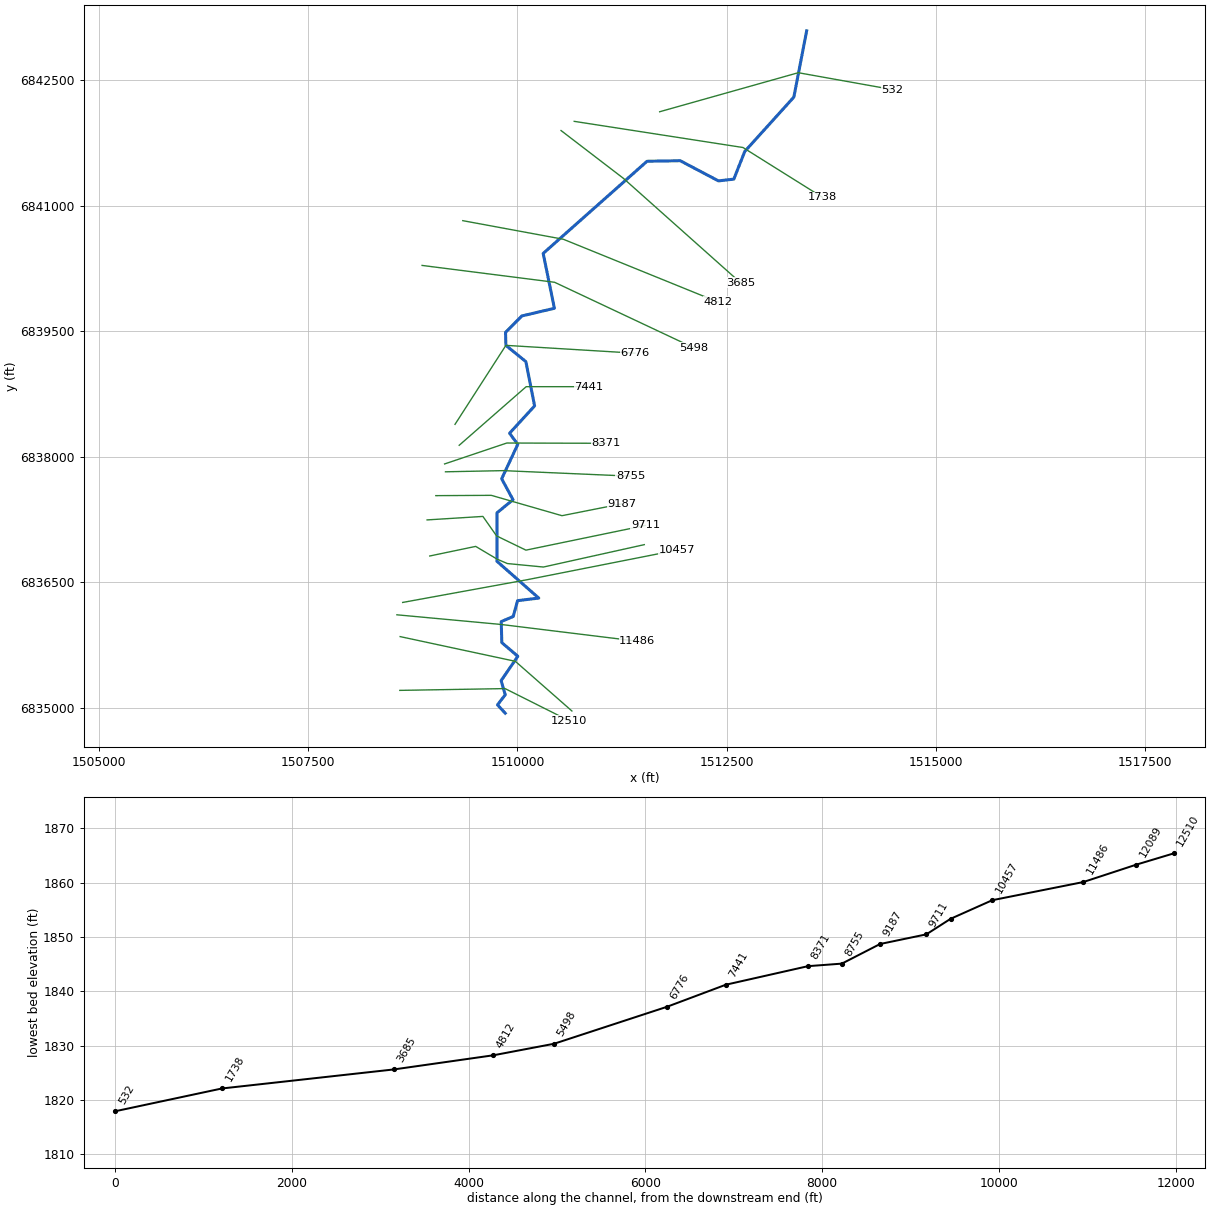
--- MULBERRY CREEK TRIBUTARY 17.prj (project) ---

Proj Title=MULBERRY CREEK TRIBUTARY 17 Base Level Engineering
Current Plan=p01
Default Exp/Contr=0.3,0.1
English Units
Geom File=g01
Flow File=f01
Plan File=p01
BEGIN DESCRIPTION:
MULBERRY CREEK TRIBUTARY 17
END DESCRIPTION:

--- MULBERRY CREEK TRIBUTARY 17.p01 (plan) ---

Plan Title=Multiple Run
Short Identifier=Multiple
Geom File=g01
Flow File=f01
Subcritical Flow
K Sum by GR= 0
Std Step Tol= 0.01
Critical Tol= 0.01
Num of Std Step Trials= 20
Max Error Tol= 0.3
Flow Tol Ratio= 0.001
Split Flow NTrial= 30
Split Flow Tol= 0.02
Split Flow Ratio= 0.02
Log Output Level= 0
Friction Slope Method= 1
Unsteady Friction Slope Method= 2
Unsteady Bridges Friction Slope Method= 1
Parabolic Critical Depth
Global Vel Dist=  1 , 1 , 1
Global Log Level= 0
CheckData=True
Encroach Param= -1, 0, 0, 0
BEGIN DESCRIPTION:
Multiple Run
END DESCRIPTION:

--- MULBERRY CREEK TRIBUTARY 17.f01 (steady flow) ---

Flow Title=Multiple
Number of Profiles=7
Profile Names=10-year,25-year,50-year,1pct_min,100-year,1pct_plu,500-year
River Rch & RM= MULBERRY CREEK T,Reach-1,12510
     322     454     564     349     697    1390    1076
River Rch & RM= MULBERRY CREEK T,Reach-1,7441
     364     516     643     399     796    1588    1236
River Rch & RM= MULBERRY CREEK T,Reach-1,3685
     422     600     751     467     932    1861    1458
Boundary for River Rch & Prof#=MULBERRY CREEK T,Reach-1,1
Up Type=0
Dn Type=3
Dn Slope=0.005
Boundary for River Rch & Prof#=MULBERRY CREEK T,Reach-1,2
Up Type=0
Dn Type=3
Dn Slope=0.005
Boundary for River Rch & Prof#=MULBERRY CREEK T,Reach-1,3
Up Type=0
Dn Type=3
Dn Slope=0.005
Boundary for River Rch & Prof#=MULBERRY CREEK T,Reach-1,4
Up Type=0
Dn Type=3
Dn Slope=0.005
Boundary for River Rch & Prof#=MULBERRY CREEK T,Reach-1,5
Up Type=0
Dn Type=3
Dn Slope=0.005
Boundary for River Rch & Prof#=MULBERRY CREEK T,Reach-1,6
Up Type=0
Dn Type=3
Dn Slope=0.005
Boundary for River Rch & Prof#=MULBERRY CREEK T,Reach-1,7
Up Type=0
Dn Type=3
Dn Slope=0.005

--- MULBERRY CREEK TRIBUTARY 17.g01 (geometry) ---

Geom Title=Existing Conditions

River Reach=MULBERRY CREEK T,Reach-1
Reach XY= 30
      1509855.00      6834938.00      1509762.18      6835037.94
      1509854.90      6835158.35      1509805.74      6835327.33
      1510005.31      6835617.84      1509814.02      6835780.94
      1509806.88      6836032.31      1509950.34      6836093.26
      1510002.54      6836282.60      1510255.54      6836312.86
      1509755.38      6836753.15      1509757.00      6837332.32
      1509947.75      6837487.70      1509812.33      6837737.90
      1510004.60      6838149.02      1509906.58      6838281.91
      1510205.52      6838608.05      1510101.48      6839136.72
      1509862.73      6839331.54      1509858.53      6839486.53
      1510052.55      6839682.54      1510442.06      6839774.37
      1510308.06      6840429.70      1511548.48      6841530.32
      1511944.56      6841536.94      1512401.60      6841295.83
      1512585.10      6841317.03      1512715.76      6841647.68
      1513301.90      6842296.31      1513455.00      6843088.00

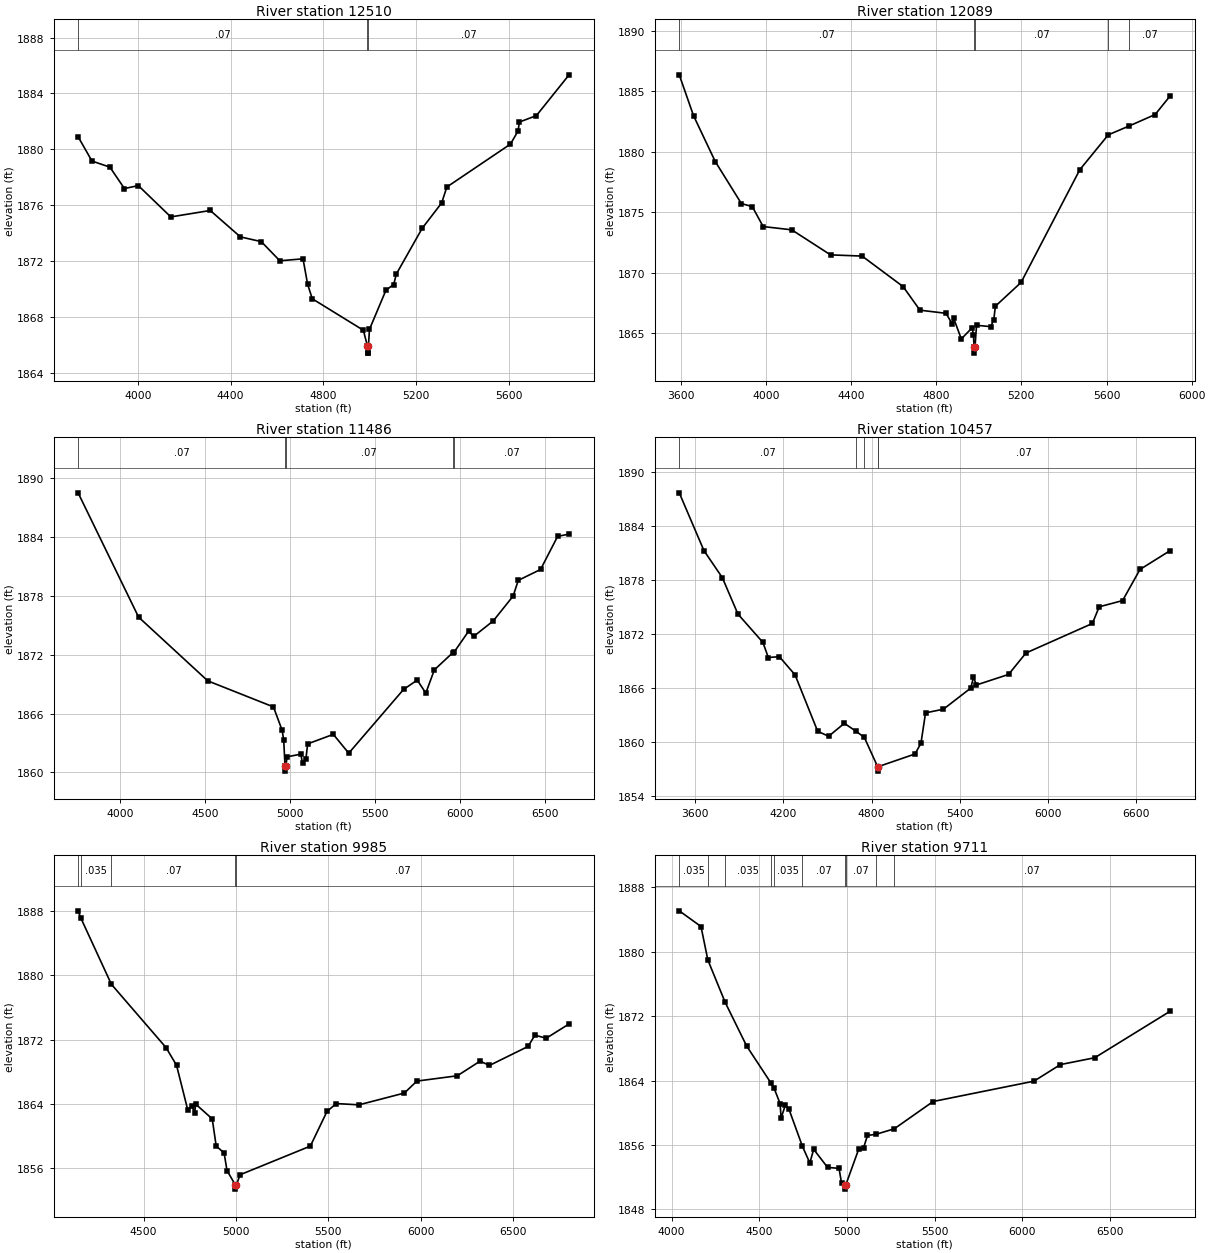
Type RM Length L Ch R = 1,12510,421,421,421
BEGIN DESCRIPTION:
MULBERRY CREEK TRIBUTARY 17 13.0
END DESCRIPTION:
XS GIS Cut Line= 3
      1508595.22      6835210.63      1509852.84      6835231.95
      1510621.10      6834846.58
#Sta/Elev= 30
  3742.2 1880.90  3802.0 1879.16  3879.5 1878.72  3942.0 1877.19  4002.0 1877.40
  4142.0 1875.16  4312.1 1875.62  4442.1 1873.73  4532.1 1873.39  4612.1 1872.02
  4712.1 1872.16  4732.1 1870.33  4752.1 1869.30  4972.2 1867.05  4990.1 1865.91
  4990.4 1865.41  4994.0 1865.41  4994.2 1865.91  4998.6 1867.11  5069.9 1869.92
  5103.1 1870.32  5114.5 1871.07  5226.2 1874.35  5310.0 1876.16  5332.3 1877.30
  5606.5 1880.37  5639.5 1881.31  5645.1 1881.95  5718.4 1882.41  5859.5 1885.33
#Mann=3,-1,0
  3742.2    0.07       0  4990.1    0.07       0  4994.2    0.07       0
Bank Sta=4990.1,4994.2
Exp/Cntr=0.3,0.1

Type RM Length L Ch R = 1,12089,603,603,603
BEGIN DESCRIPTION:
MULBERRY CREEK TRIBUTARY 17 12.0
END DESCRIPTION:
XS GIS Cut Line= 3
      1508599.58      6835852.99      1509975.39      6835557.92
      1510651.25      6834964.36
#Sta/Elev= 30
  3592.9 1886.35  3659.8 1882.98  3762.1 1879.18  3884.8 1875.71  3935.9 1875.46
  3987.1 1873.81  4121.3 1873.54  4303.6 1871.47  4451.8 1871.37  4644.4 1868.85
  4723.5 1866.90  4846.2 1866.64  4876.1 1865.73  4881.2 1866.27  4917.8 1864.52
  4968.9 1865.45  4974.9 1864.85  4977.9 1863.85  4978.2 1863.35  4982.2 1863.85
  4989.4 1865.65  5056.1 1865.54  5070.4 1866.11  5078.0 1867.23  5198.5 1869.19
  5474.6 1878.51  5608.3 1881.39  5704.7 1882.11  5828.5 1883.07  5899.5 1884.62
#Mann=5,-1,0
  3592.9    0.07       0  4977.9    0.07       0  4982.2    0.07       0
  5608.3   0.035       0  5704.7    0.07       0
Bank Sta=4977.9,4982.2
Exp/Cntr=0.3,0.1

Type RM Length L Ch R = 1,11486,1029,1029,1029
BEGIN DESCRIPTION:
MULBERRY CREEK TRIBUTARY 17 11.0
END DESCRIPTION:
XS GIS Cut Line= 3
      1508560.49      6836113.41      1509804.16      6835998.12
      1511431.86      6835798.48
#Sta/Elev= 30
  3751.0 1888.52  4107.0 1875.84  4513.8 1869.34  4900.4 1866.68  4951.4 1864.30
  4960.7 1863.32  4968.5 1860.63  4968.8 1860.13  4972.9 1860.63  4980.8 1861.59
  5061.3 1861.86  5071.4 1860.95  5091.5 1861.39  5101.6 1862.91  5252.7 1863.88
  5343.4 1861.96  5665.8 1868.46  5746.4 1869.42  5796.8 1868.09  5847.1 1870.46
  5954.2 1872.19  5964.1 1872.29  6048.6 1874.40  6078.9 1873.88  6193.4 1875.45
  6310.6 1877.99  6340.8 1879.59  6471.8 1880.70  6572.5 1884.08  6639.9 1884.31
#Mann=5,-1,0
  3751.0    0.07       0  4968.5    0.07       0  4972.9    0.07       0
  5954.2   0.035       0  5964.1    0.07       0
Bank Sta=4968.5,4972.9
Exp/Cntr=0.3,0.1

Type RM Length L Ch R = 1,10457,472,472,472
BEGIN DESCRIPTION:
MULBERRY CREEK TRIBUTARY 17 10.0
END DESCRIPTION:
XS GIS Cut Line= 3
      1508629.95      6836260.98      1510111.76      6836531.51
      1511906.89      6836885.98
#Sta/Elev= 30
  3493.7 1887.70  3661.5 1881.28  3786.0 1878.29  3892.5 1874.23  4062.4 1871.08
  4098.6 1869.41  4174.0 1869.50  4280.5 1867.48  4434.0 1861.22  4508.7 1860.66
  4615.2 1862.10  4692.8 1861.24  4751.1 1860.54  4841.1 1857.29  4841.5 1856.79
  4845.8 1857.29  5095.0 1858.69  5135.8 1859.88  5167.0 1863.26  5288.7 1863.67
  5474.8 1866.02  5492.6 1867.22  5513.0 1866.36  5731.2 1867.53  5849.3 1869.91
  6300.6 1873.19  6346.8 1875.04  6505.7 1875.73  6624.0 1879.19  6829.8 1881.29
#Mann=5,-1,0
  3493.7    0.07       0  4692.8    0.16       0  4751.1    0.07       0
  4841.1    0.07       0  4845.8    0.07       0
Bank Sta=4841.1,4845.8
Exp/Cntr=0.3,0.1

Type RM Length L Ch R = 1,9985,274,274,274
BEGIN DESCRIPTION:
Mapping XS a3548522
END DESCRIPTION:
XS GIS Cut Line= 6
      1508953.24      6836815.78      1509501.88      6836930.37
      1509758.82      6836777.59      1509880.35      6836725.51
      1510310.90      6836683.84      1511515.80      6836951.21
#Sta/Elev= 30
  4145.6 1888.03  4159.3 1887.19  4325.8 1878.88  4621.8 1870.99  4678.6 1868.79
  4739.4 1863.22  4760.8 1863.77  4776.4 1862.84  4782.3 1863.95  4871.9 1862.11
  4893.3 1858.72  4936.1 1857.87  4951.7 1855.68  4997.5 1853.86  4997.8 1853.36
  5002.3 1853.86  5022.6 1855.15  5403.1 1858.72  5493.5 1863.05  5543.8 1864.02
  5666.2 1863.86  5912.0 1865.33  5980.0 1866.82  6198.8 1867.48  6321.7 1869.30
  6373.0 1868.77  6582.2 1871.14  6618.8 1872.54  6680.3 1872.16  6804.0 1873.94
#Mann=5,-1,0
  4145.6    0.07       0  4159.3   0.035       0  4325.8    0.07       0
  4997.5    0.07       0  5002.3    0.07       0
Bank Sta=4997.5,5002.3
Exp/Cntr=0.3,0.1

Type RM Length L Ch R = 1,9711,524,524,524
BEGIN DESCRIPTION:
Mapping XS 6794b15b
END DESCRIPTION:
XS GIS Cut Line= 5
      1508921.38      6837246.73      1509588.08      6837288.40
      1509751.27      6837055.76      1510101.97      6836885.62
      1511529.01      6837180.75
#Sta/Elev= 30
  4043.7 1885.09  4167.6 1883.14  4206.7 1878.98  4305.7 1873.70  4428.1 1868.28
  4564.6 1863.75  4584.8 1863.01  4618.4 1861.14  4624.3 1859.35  4648.5 1860.92
  4668.5 1860.47  4745.3 1855.85  4788.1 1853.75  4809.9 1855.45  4889.2 1853.20
  4954.6 1853.08  4968.7 1851.26  4987.9 1851.00  4988.3 1850.50  4992.7 1851.00
  5066.0 1855.43  5094.2 1855.62  5116.7 1857.17  5166.3 1857.32  5269.6 1858.00
  5490.9 1861.39  6065.9 1863.92  6216.6 1865.98  6412.3 1866.83  6842.9 1872.62
#Mann=10,-1,0
  4043.7   0.035       0  4206.7    0.07       0  4305.7   0.035       0
  4564.6    0.07       0  4584.8   0.035       0  4745.3    0.07       0
  4987.9    0.07       0  4992.7    0.07       0  5166.3    0.16       0
  5269.6    0.07       0
Bank Sta=4987.9,4992.7
Exp/Cntr=0.3,0.1

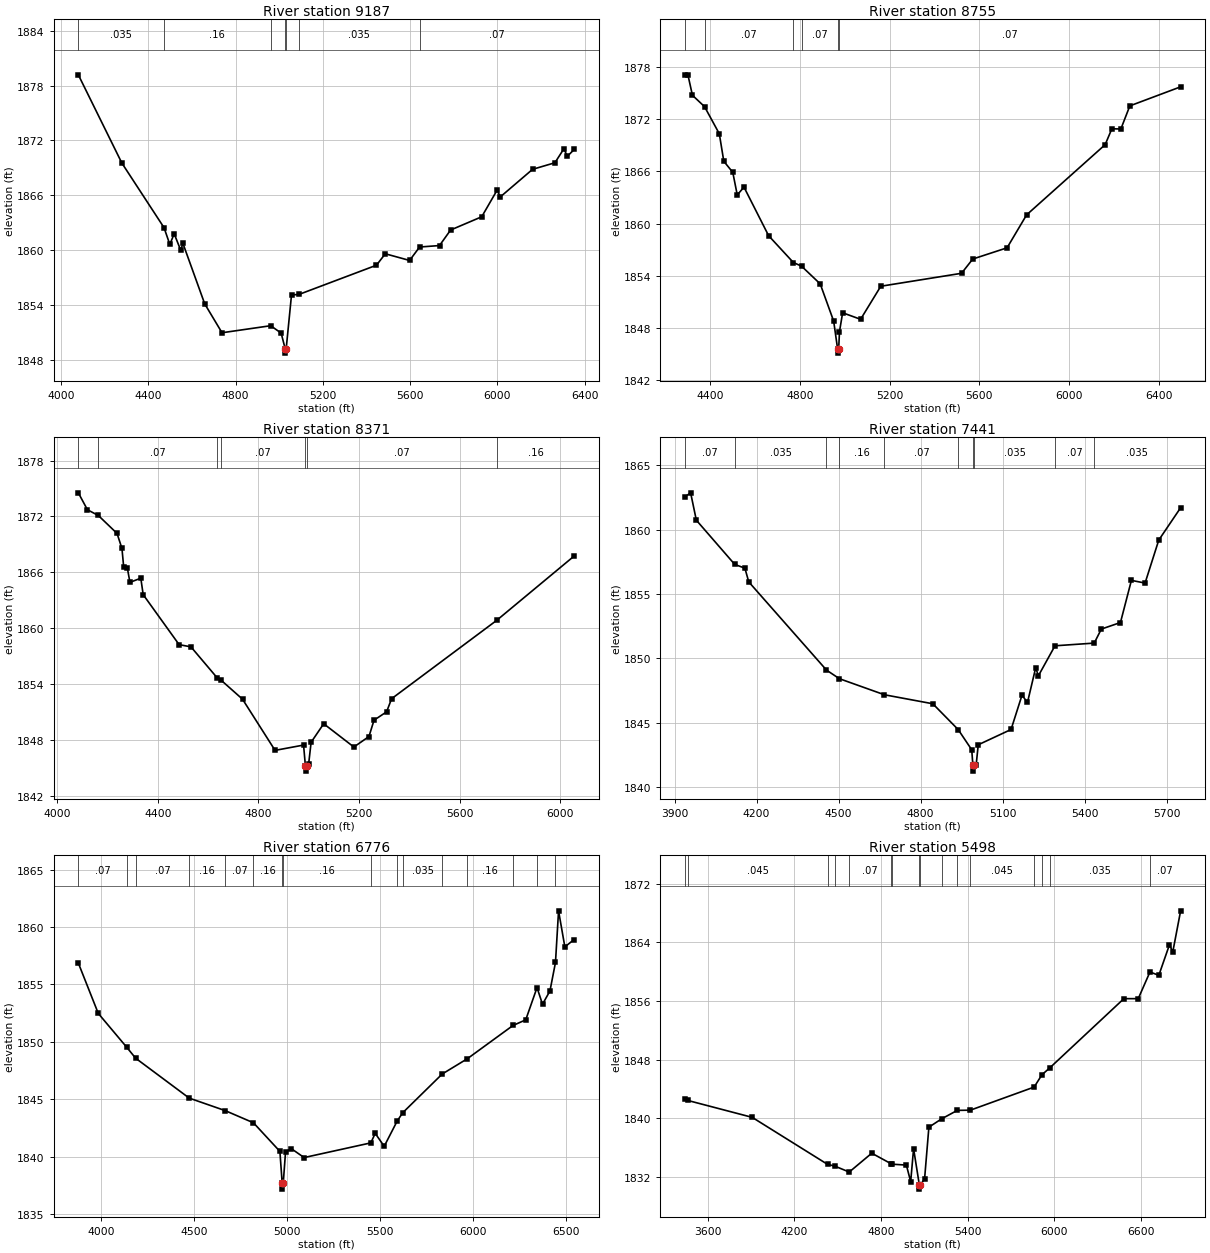
Type RM Length L Ch R = 1,9187,432,432,432
BEGIN DESCRIPTION:
Mapping XS ccd37cba
END DESCRIPTION:
XS GIS Cut Line= 4
      1509025.55      6837536.66      1509688.77      6837540.13
      1510532.52      6837297.08      1511250.68      6837439.32
#Sta/Elev= 30
  4078.7 1879.17  4278.2 1869.52  4471.6 1862.45  4498.2 1860.61  4518.2 1861.78
  4548.2 1859.97  4558.2 1860.73  4658.2 1854.11  4737.5 1850.95  4960.8 1851.72
  5008.6 1850.91  5026.9 1849.22  5027.3 1848.72  5031.8 1849.22  5056.1 1855.08
  5091.2 1855.15  5445.7 1858.34  5486.1 1859.59  5597.6 1858.86  5643.4 1860.33
  5734.7 1860.49  5785.6 1862.19  5928.3 1863.64  5999.7 1866.59  6012.9 1865.80
  6161.4 1868.83  6263.9 1869.55  6305.5 1871.10  6320.2 1870.24  6352.1 1871.00
#Mann=7,-1,0
  4078.7   0.035       0  4471.6    0.16       0  4960.8    0.07       0
  5026.9    0.07       0  5031.8    0.07       0  5091.2   0.035       0
  5643.4    0.07       0
Bank Sta=5026.9,5031.8
Exp/Cntr=0.3,0.1

Type RM Length L Ch R = 1,8755,384,384,384
BEGIN DESCRIPTION:
Mapping XS 95295102
END DESCRIPTION:
XS GIS Cut Line= 3
      1509141.05      6837821.38      1509832.00      6837835.27
      1511351.38      6837769.36
#Sta/Elev= 30
  4285.9 1877.07  4299.8 1877.11  4319.9 1874.76  4374.0 1873.45  4439.9 1870.33
  4459.9 1867.17  4499.9 1865.90  4519.9 1863.30  4549.9 1864.20  4659.9 1858.61
  4770.2 1855.53  4806.7 1855.11  4890.0 1853.07  4950.0 1848.79  4967.5 1845.61
  4967.9 1845.11  4972.4 1845.61  4976.0 1847.59  4990.0 1849.75  5070.1 1849.00
  5160.2 1852.80  5520.5 1854.29  5570.5 1855.93  5723.6 1857.22  5810.8 1861.01
  6161.1 1869.08  6191.1 1870.91  6231.2 1870.88  6271.2 1873.54  6497.8 1875.73
#Mann=6,-1,0
  4285.9   0.035       0  4374.0    0.07       0  4770.2    0.16       0
  4806.7    0.07       0  4967.5    0.07       0  4972.4    0.07       0
Bank Sta=4967.5,4972.4
Exp/Cntr=0.3,0.1

Type RM Length L Ch R = 1,8371,930,930,930
BEGIN DESCRIPTION:
Mapping XS 14d13b77
END DESCRIPTION:
XS GIS Cut Line= 3
      1509130.65      6837915.14      1509873.67      6838165.13
      1511060.62      6838161.66
#Sta/Elev= 30
  4084.2 1874.54  4120.4 1872.72  4163.5 1872.11  4238.0 1870.18  4257.6 1868.56
  4264.3 1866.62  4278.7 1866.51  4289.3 1864.92  4332.5 1865.37  4342.0 1863.60
  4484.8 1858.23  4531.9 1857.99  4636.8 1854.64  4649.6 1854.46  4736.8 1852.37
  4866.2 1846.87  4979.5 1847.44  4987.0 1845.14  4987.4 1844.64  4991.9 1845.14
  4999.5 1845.36  5009.5 1847.74  5059.5 1849.73  5179.5 1847.23  5239.5 1848.36
  5259.5 1850.11  5309.5 1851.01  5329.5 1852.42  5746.8 1860.83  6055.1 1867.75
#Mann=7,-1,0
  4084.2   0.035       0  4163.5    0.07       0  4636.8   0.035       0
  4649.6    0.07       0  4987.0    0.07       0  4991.9    0.07       0
  5746.8    0.16       0
Bank Sta=4987,4991.9
Exp/Cntr=0.3,0.1

Type RM Length L Ch R = 1,7441,665,665,665
BEGIN DESCRIPTION:
MULBERRY CREEK TRIBUTARY 17 4.0
END DESCRIPTION:
XS GIS Cut Line= 3
      1509305.02      6838138.02      1510105.00      6838838.00
      1510855.01      6838838.00
#Sta/Elev= 30
  3937.6 1862.55  3958.9 1862.87  3979.8 1860.74  4120.2 1857.30  4157.3 1857.01
  4171.5 1855.94  4455.7 1849.08  4502.9 1848.41  4667.6 1847.16  4844.5 1846.46
  4937.3 1844.45  4986.8 1842.88  4990.8 1841.72  4991.2 1841.22  4996.2 1841.72
  5003.1 1841.73  5010.6 1843.27  5130.6 1844.46  5170.6 1847.13  5190.6 1846.56
  5220.6 1849.26  5230.6 1848.64  5291.2 1850.97  5434.7 1851.18  5460.6 1852.27
  5530.6 1852.78  5570.6 1856.06  5620.6 1855.85  5670.6 1859.19  5750.6 1861.71
#Mann=10,-1,0
  3937.6    0.07       0  4120.2   0.035       0  4455.7    0.07       0
  4502.9    0.16       0  4667.6    0.07       0  4937.3   0.035       0
  4990.8   0.035       0  4996.2   0.035       0  5291.2    0.07       0
  5434.7   0.035       0
Bank Sta=4990.8,4996.2
Exp/Cntr=0.3,0.1

Type RM Length L Ch R = 1,6776,1278,1278,1278
BEGIN DESCRIPTION:
MULBERRY CREEK TRIBUTARY 17 3.0
END DESCRIPTION:
XS GIS Cut Line= 3
      1509255.01      6838388.02      1509862.73      6839331.54
      1511405.00      6839238.00
#Sta/Elev= 30
  3877.7 1856.86  3985.0 1852.47  4138.6 1849.51  4185.8 1848.57  4474.3 1845.09
  4667.9 1844.00  4819.8 1842.94  4962.0 1840.45  4974.5 1837.66  4974.9 1837.16
  4979.9 1837.66  4992.4 1840.39  5022.3 1840.70  5092.4 1839.91  5451.2 1841.19
  5474.8 1842.02  5523.2 1840.89  5592.9 1843.09  5623.1 1843.82  5835.2 1847.19
  5970.2 1848.52  6216.0 1851.42  6284.6 1851.91  6345.3 1854.72  6374.8 1853.27
  6414.9 1854.43  6444.6 1856.91  6461.2 1861.41  6495.0 1858.27  6545.1 1858.91
#Mann=16,-1,0
  3877.7    0.07       0  4138.6   0.035       0  4185.8    0.07       0
  4474.3    0.16       0  4667.9    0.07       0  4819.8    0.16       0
  4974.5    0.07       0  4979.9    0.16       0  5451.2   0.035       0
  5592.9    0.07       0  5623.1   0.035       0  5835.2    0.07       0
  5970.2    0.16       0  6216.0    0.07       0  6345.3    0.16       0
  6444.6   0.035       0
Bank Sta=4974.5,4979.9
Exp/Cntr=0.3,0.1

Type RM Length L Ch R = 1,5498,686,686,686
BEGIN DESCRIPTION:
Mapping XS 2e00206f
END DESCRIPTION:
XS GIS Cut Line= 3
      1508861.56      6840286.22      1510444.85      6840084.84
      1512110.79      6839300.46
#Sta/Elev= 30
  3439.5 1842.60  3461.1 1842.44  3906.7 1840.14  4429.0 1833.73  4479.3 1833.49
  4579.5 1832.68  4735.7 1835.25  4867.1 1833.84  4877.1 1833.75  4975.5 1833.63
  5005.5 1831.37  5025.6 1835.87  5066.1 1830.85  5066.5 1830.35  5071.7 1830.85
  5102.0 1831.78  5131.7 1838.80  5220.3 1839.94  5328.6 1841.09  5419.2 1841.12
  5861.3 1844.27  5915.5 1845.95  5972.1 1846.93  6483.6 1856.33  6583.1 1856.33
  6664.3 1859.97  6725.7 1859.51  6799.6 1863.69  6822.4 1862.69  6876.9 1868.31
#Mann=16,-1,0
  3439.5    0.07       0  3461.1   0.045       0  4429.0    0.07       0
  4479.3   0.035       0  4579.5    0.07       0  4867.1   0.035       0
  4877.1    0.07       0  5066.1    0.07       0  5071.7    0.07       0
  5220.3   0.045       0  5328.6    0.07       0  5419.2   0.045       0
  5861.3   0.035       0  5915.5    0.16       0  5972.1   0.035       0
  6664.3    0.07       0
Bank Sta=5066.1,5071.7
Exp/Cntr=0.3,0.1

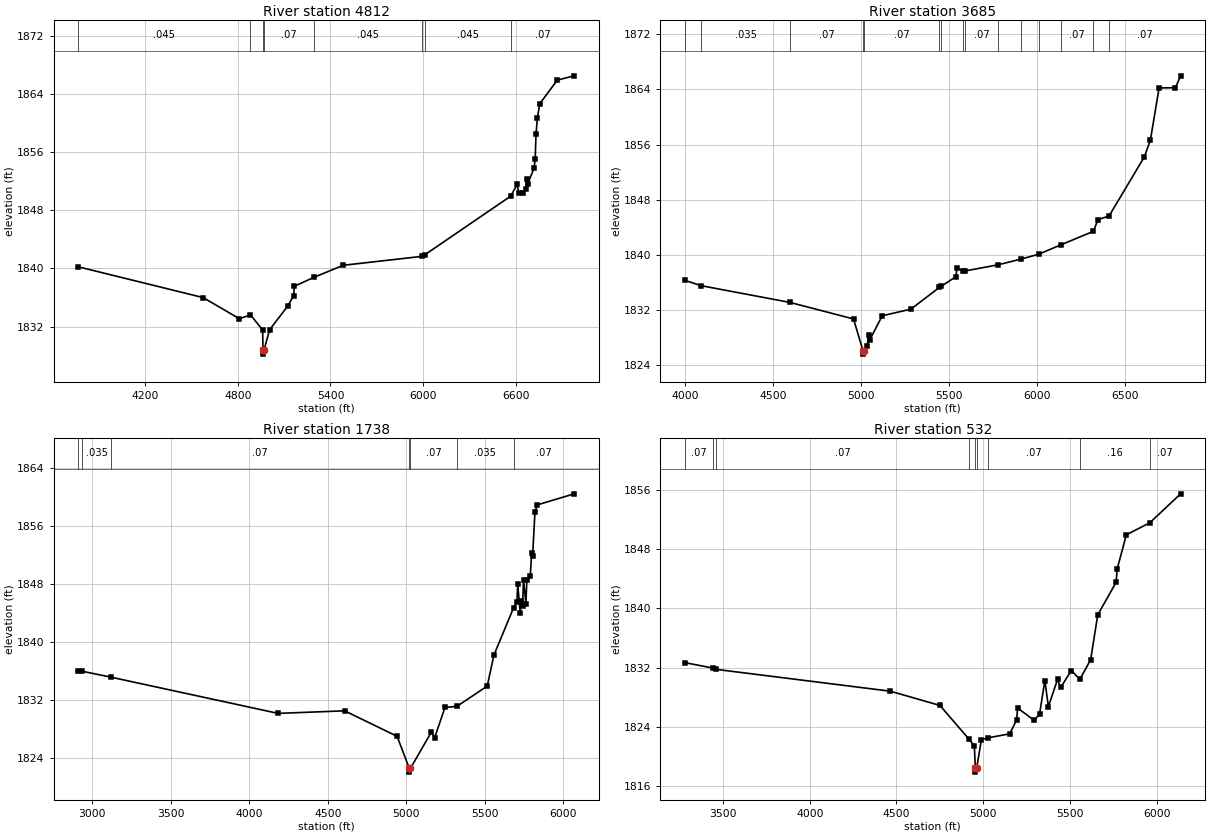
Type RM Length L Ch R = 1,4812,1127,1127,1127
BEGIN DESCRIPTION:
Mapping XS ce5411f9
END DESCRIPTION:
XS GIS Cut Line= 3
      1509347.60      6840820.95      1510549.02      6840598.73
      1512396.27      6839848.71
#Sta/Elev= 30
  3764.9 1840.23  4574.5 1836.00  4809.7 1833.09  4881.3 1833.63  4960.2 1831.55
  4962.4 1828.73  4962.9 1828.23  4968.2 1828.73  5005.6 1831.59  5122.7 1834.83
  5160.9 1836.26  5166.3 1837.56  5291.1 1838.77  5482.3 1840.44  5990.8 1841.66
  6011.7 1841.88  6568.6 1849.94  6612.1 1851.62  6620.5 1850.32  6649.9 1850.36
  6666.0 1850.92  6674.0 1852.33  6679.4 1851.64  6720.0 1853.78  6727.6 1854.98
  6733.0 1858.43  6741.6 1860.64  6757.1 1862.64  6871.1 1865.89  6980.4 1866.48
#Mann=8,-1,0
  3764.9   0.045       0  4881.3    0.07       0  4962.4    0.07       0
  4968.2    0.07       0  5291.1   0.045       0  5990.8    0.07       0
  6011.7   0.045       0  6568.6    0.07       0
Bank Sta=4962.4,4968.2
Exp/Cntr=0.3,0.1

Type RM Length L Ch R = 1,3685,1947,1947,1947
BEGIN DESCRIPTION:
Mapping XS 5392dca2
END DESCRIPTION:
XS GIS Cut Line= 3
      1510521.25      6841897.33      1511264.29      6841327.89
      1512667.10      6840077.86
#Sta/Elev= 30
  4000.3 1836.32  4093.7 1835.54  4596.8 1833.12  4958.2 1830.72  5011.9 1826.12
  5012.4 1825.62  5018.1 1826.12  5035.9 1826.76  5043.4 1828.38  5050.1 1827.67
  5121.2 1831.18  5284.2 1832.14  5445.4 1835.29  5455.2 1835.44  5539.2 1836.84
  5545.9 1838.11  5581.3 1837.71  5588.4 1837.66  5780.5 1838.58  5910.8 1839.41
  6009.8 1840.11  6135.2 1841.46  6320.4 1843.43  6346.1 1845.13  6409.0 1845.64
  6608.6 1854.18  6643.7 1856.63  6693.1 1864.21  6785.8 1864.25  6815.4 1865.97
#Mann=15,-1,0
  4000.3    0.07       0  4093.7   0.035       0  4596.8    0.07       0
  5011.9    0.07       0  5018.1    0.07       0  5445.4   0.045       0
  5455.2    0.07       0  5581.3   0.045       0  5588.4    0.07       0
  5780.5   0.045       0  5910.8    0.07       0  6009.8   0.035       0
  6135.2    0.07       0  6320.4   0.035       0  6409.0    0.07       0
Bank Sta=5011.9,5018.1
Exp/Cntr=0.3,0.1

Type RM Length L Ch R = 1,1738,1206,1206,1206
BEGIN DESCRIPTION:
Mapping XS b8fa7f43
END DESCRIPTION:
XS GIS Cut Line= 3
      1510678.50      6842007.14      1512694.11      6841694.65
      1513642.02      6841100.90
#Sta/Elev= 30
  2911.7 1835.98  2936.0 1836.00  3120.7 1835.18  4183.6 1830.20  4608.2 1830.55
  4942.2 1827.04  5019.9 1822.61  5020.4 1822.11  5026.5 1822.61  5160.3 1827.62
  5181.5 1826.87  5247.4 1831.03  5322.9 1831.16  5516.3 1833.96  5558.7 1838.22
  5684.5 1844.77  5704.9 1845.59  5710.8 1847.95  5726.1 1844.07  5732.0 1845.74
  5741.4 1844.94  5747.3 1848.58  5762.6 1845.31  5768.5 1848.50  5790.2 1849.06
  5799.2 1852.30  5805.1 1851.84  5820.4 1857.99  5835.7 1858.91  6069.9 1860.43
#Mann=7,-1,0
  2911.7    0.07       0  2936.0   0.035       0  3120.7    0.07       0
  5019.9    0.07       0  5026.5    0.07       0  5322.9   0.035       0
  5684.5    0.07       0
Bank Sta=5019.9,5026.5
Exp/Cntr=0.3,0.1

Type RM Length L Ch R = 1,532,0,0,0
BEGIN DESCRIPTION:
MULBERRY CREEK TRIBUTARY 17 1.0
END DESCRIPTION:
XS GIS Cut Line= 3
      1511699.28      6842121.72      1513355.00      6842588.00
      1514475.36      6842387.35
#Sta/Elev= 30
  3279.8 1832.68  3444.8 1831.94  3462.0 1831.77  4464.9 1828.83  4750.6 1826.91
  4916.4 1822.41  4948.9 1821.46  4954.7 1818.42  4955.2 1817.92  4962.0 1818.42
  4989.5 1822.28  5026.5 1822.54  5152.3 1823.08  5192.9 1824.96  5198.2 1826.56
  5294.5 1824.90  5325.0 1825.77  5355.5 1830.26  5375.8 1826.75  5428.5 1830.42
  5446.9 1829.33  5507.9 1831.62  5557.3 1830.43  5619.6 1833.09  5660.3 1839.13
  5766.3 1843.51  5772.0 1845.28  5825.2 1849.92  5960.0 1851.53  6138.1 1855.44
#Mann=9,-1,0
  3279.8    0.07       0  3444.8   0.035       0  3462.0    0.07       0
  4916.4   0.035       0  4954.7   0.035       0  4962.0   0.035       0
  5026.5    0.07       0  5557.3    0.16       0  5960.0    0.07       0
Bank Sta=4954.7,4962
Exp/Cntr=0.3,0.1

Chan Stop Cuts=-1