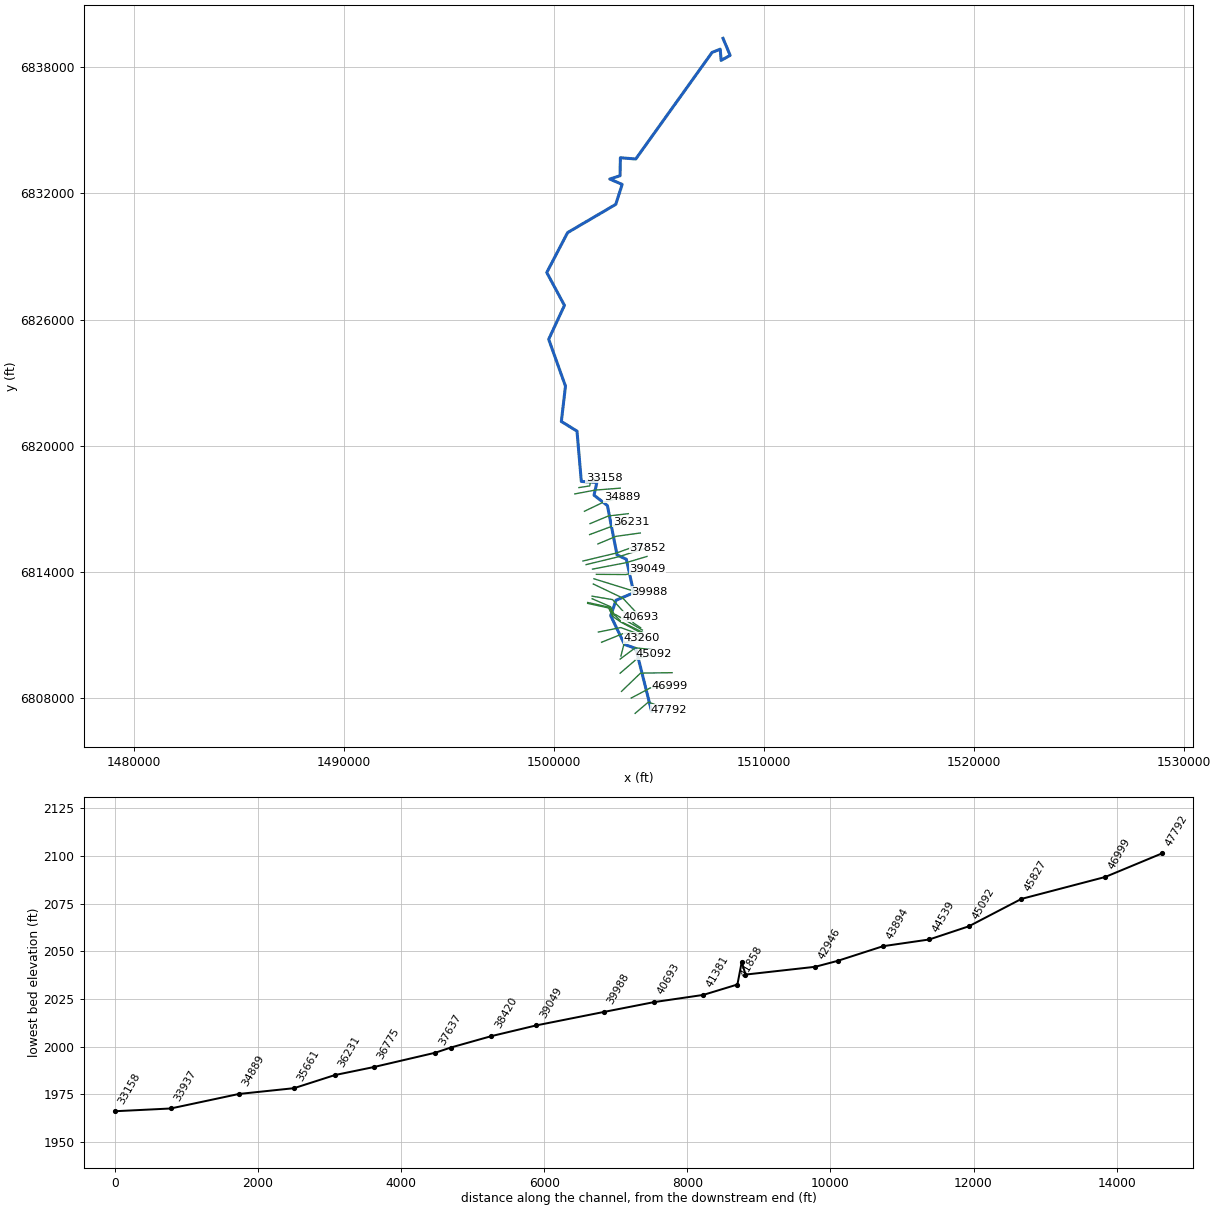
--- MULBERRY CREEK TRIBUTARY 18.prj (project) ---

Proj Title=MULBERRY CREEK TRIBUTARY 18 Base Level Engineering
Current Plan=p01
Default Exp/Contr=0.3,0.1
English Units
Geom File=g01
Flow File=f01
Plan File=p01
Y Axis Title=Elevation
X Axis Title(PF)=Main Channel Distance
X Axis Title(XS)=Station
BEGIN DESCRIPTION:
MULBERRY CREEK TRIBUTARY 18
END DESCRIPTION:
DSS Export Rating Curves= 0
DSS Export Rating Curve Sorted= 0
DSS Export Volume Flow Curves= 0
DXF OffsetX= 0
DXF OffsetY= 0
DXF ScaleX= 1
DXF ScaleY= 10

--- MULBERRY CREEK TRIBUTARY 18.p01 (plan) ---

Plan Title=Multiple Run
Short Identifier=Multiple
Geom File=g01
Flow File=f01
Subcritical Flow
K Sum by GR= 0
Std Step Tol= 0.01
Critical Tol= 0.01
Num of Std Step Trials= 20
Max Error Tol= 0.3
Flow Tol Ratio= 0.001
Split Flow NTrial= 30
Split Flow Tol= 0.02
Split Flow Ratio= 0.02
Log Output Level= 0
Friction Slope Method= 1
Unsteady Friction Slope Method= 2
Unsteady Bridges Friction Slope Method= 1
Parabolic Critical Depth
Global Vel Dist=  1 , 1 , 1
Global Log Level= 0
CheckData=True
Encroach Param= -1, 0, 0, 0
BEGIN DESCRIPTION:
Multiple Run
END DESCRIPTION:

--- MULBERRY CREEK TRIBUTARY 18.f01 (steady flow) ---

Flow Title=Multiple
Program Version=4.10
Number of Profiles= 7
Profile Names=10-year,25-year,50-year,1pct_min,100-year,1pct_plu,500-year
River Rch & RM=MULBERRY CREEK T,Reach-1         ,47792
     664    1001    1305     847    1689    3370    2868
River Rch & RM=MULBERRY CREEK T,Reach-1         ,45827
     803    1213    1584    1028    2051    4092    3484
River Rch & RM=MULBERRY CREEK T,Reach-1         ,39988
     990    1511    1986    1296    2587    5161    4449
River Rch & RM=MULBERRY CREEK T,Reach-1         ,37852
    1068    1632    2145    1401    2795    5577    4808
River Rch & RM=MULBERRY CREEK T,Reach-1         ,33937
    1152    1760    2311    1507    3007    6000    5158
River Rch & RM=MULBERRY CREEK T,Reach-1         ,28674
    1258    1928    2538    1658    3308    6600    5694
River Rch & RM=MULBERRY CREEK T,Reach-1         ,27292
    1209    1841    2412    1568    3128    6242    5332
River Rch & RM=MULBERRY CREEK T,Reach-1         ,22224
    1535    2351    3093    2017    4024    8030    6899
River Rch & RM=MULBERRY CREEK T,Reach-1         ,8778
    1941    2992    3953    2587    5162   10300    8919
Boundary for River Rch & Prof#=MULBERRY CREEK T,Reach-1         , 1
Up Type= 0
Dn Type= 3
Dn Slope=0.005
Boundary for River Rch & Prof#=MULBERRY CREEK T,Reach-1         , 2
Up Type= 0
Dn Type= 3
Dn Slope=0.005
Boundary for River Rch & Prof#=MULBERRY CREEK T,Reach-1         , 3
Up Type= 0
Dn Type= 3
Dn Slope=0.005
Boundary for River Rch & Prof#=MULBERRY CREEK T,Reach-1         , 4
Up Type= 0
Dn Type= 3
Dn Slope=0.005
Boundary for River Rch & Prof#=MULBERRY CREEK T,Reach-1         , 5
Up Type= 0
Dn Type= 3
Dn Slope=0.005
Boundary for River Rch & Prof#=MULBERRY CREEK T,Reach-1         , 6
Up Type= 0
Dn Type= 3
Dn Slope=0.005
Boundary for River Rch & Prof#=MULBERRY CREEK T,Reach-1         , 7
Up Type= 0
Dn Type= 3
Dn Slope=0.005
DSS Import GetInterval= 0
DSS Import GetPeak= 0
DSS Import FillOption= 0

--- MULBERRY CREEK TRIBUTARY 18.g01 (geometry) ---

Geom Title=Existing Conditions
Program Version=4.10

River Reach=MULBERRY CREEK T,Reach-1
Reach XY= 30
        1504655.        6807338.      1503901.57      6810336.78
      1503365.42      6810528.19      1502705.93      6811898.48
      1502960.44      6812632.91        1503805.        6812988.
      1503453.03      6814582.35      1503008.61      6814789.48
      1502549.64       6817140.7      1501912.48      6817634.42
      1502049.71      6818240.75      1501308.45      6818289.48
      1501101.87      6820686.37      1500357.05      6821143.86
      1500554.07      6822827.52      1499754.64      6825058.15
      1500504.62      6826672.73      1499662.29      6828238.09
        1500655.        6830138.      1502947.55      6831481.93
      1503252.93      6832432.16      1502662.32       6832688.1
      1503152.09      6832845.91      1503168.36      6833701.35
      1503899.83      6833642.59      1507534.91      6838718.21
      1507922.22      6838871.79      1507965.47      6838338.48
      1508394.81      6838578.27        1508055.        6839388.

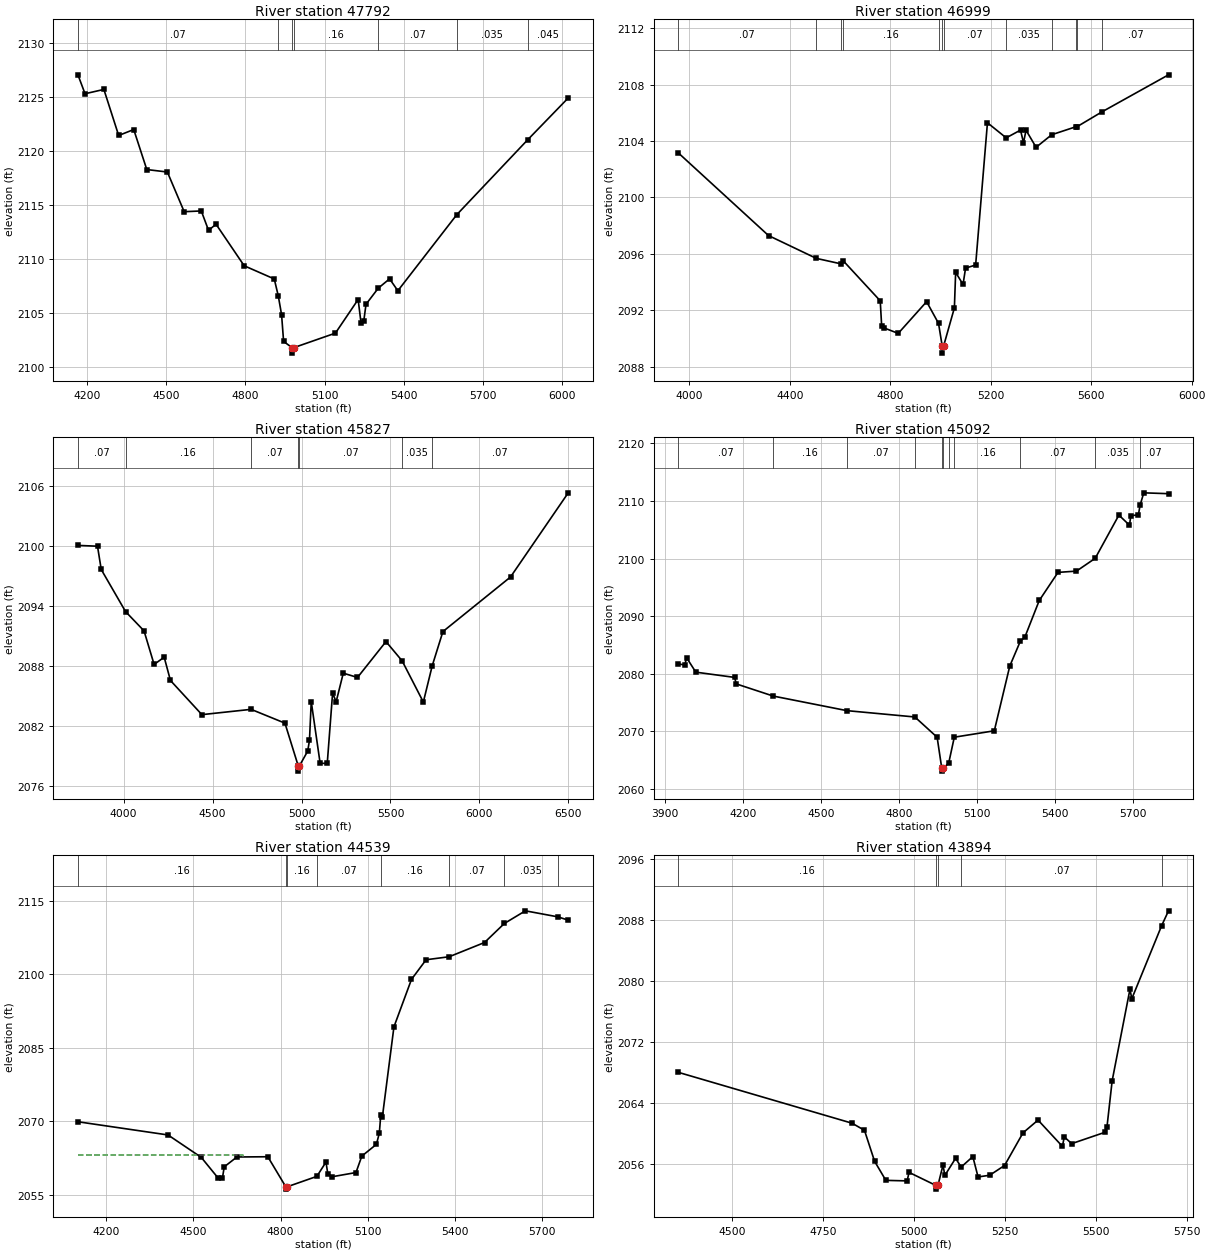
Type RM Length L Ch R = 1 ,47792   ,793,793,793
BEGIN DESCRIPTION:
MULBERRY CREEK TRIBUTARY 18 54.0
END DESCRIPTION:
XS GIS Cut Line= 3
      1503869.02      6807245.93        1504505.        6807788.
      1505455.26      6807412.78
#Sta/Elev= 30
  4165.4 2127.04  4192.3 2125.29  4263.7 2125.69  4319.7 2121.43  4376.8 2121.98
  4426.2 2118.28  4504.2 2118.05  4567.9 2114.38  4632.7 2114.45  4660.1 2112.66
  4688.6 2113.22  4795.2 2109.38  4909.1 2108.16  4924.2 2106.61  4936.8 2104.86
  4944.5 2102.38    4977  2101.8  4977.4  2101.3  4982.3  2101.8  5140.8 2103.15
  5226.8 2106.26  5237.7 2104.12  5248.3 2104.29  5256.7 2105.82  5303.2 2107.31
  5345.9 2108.17  5377.3 2107.07  5600.7 2114.11  5869.8 2121.05  6022.7  2124.9
#Mann= 7 ,-1 , 0
  4165.4     .07       0  4924.2     .16       0    4977     .07       0
  4982.3     .16       0  5303.2     .07       0  5600.7    .035       0
  5869.8    .045       0
Bank Sta=4977,4982.3
XS Rating Curve= 0 ,0
Exp/Cntr=0.3,0.1

Type RM Length L Ch R = 1 ,46999   ,1172,1172,1172
BEGIN DESCRIPTION:
Mapping XS 4d9985c5
END DESCRIPTION:
XS GIS Cut Line= 3
      1503681.45      6807975.05      1504591.21      6808457.71
      1505510.63       6808527.1
#Sta/Elev= 30
  3955.9 2103.16  4315.4 2097.29  4505.8 2095.67  4604.7 2095.28  4611.8 2095.52
  4760.2 2092.66  4765.8  2090.9    4775 2090.74  4831.8 2090.35  4944.8  2092.6
  4992.3 2091.06  5006.9 2089.45  5007.3 2088.95  5012.4 2089.45  5055.4 2092.16
  5060.4 2094.68  5089.8 2093.82  5099.9 2094.98    5140  2095.2    5187 2105.29
  5261.6 2104.22  5318.7 2104.77  5330.5 2103.87  5340.6 2104.76  5380.7 2103.55
  5442.7 2104.44  5537.9    2105  5541.7 2104.99  5643.6 2106.07  5907.8 2108.69
#Mann= 12 ,-1 , 0
  3955.9     .07       0  4505.8    .035       0  4604.7     .07       0
  4611.8     .16       0  4992.3     .07       0  5006.9     .07       0
  5012.4     .07       0  5261.6    .035       0  5442.7    .045       0
  5537.9     .07       0  5541.7    .045       0  5643.6     .07       0
Bank Sta=5006.9,5012.4
XS Rating Curve= 0 ,0
Exp/Cntr=0.3,0.1

Type RM Length L Ch R = 1 ,45827   ,735,735,735
BEGIN DESCRIPTION:
Mapping XS 4de9f75f
END DESCRIPTION:
XS GIS Cut Line= 3
      1503223.13      6808294.49      1504125.93      6809162.57
      1505629.45       6809183.4
#Sta/Elev= 30
    3743 2100.03    3853 2099.95    3874 2097.62  4010.7 2093.41  4114.6 2091.48
  4171.2 2088.12  4227.8 2088.85    4263 2086.52  4439.8  2083.1  4716.4 2083.63
  4906.7 2082.25  4981.7 2077.95  4982.1 2077.45  4987.2 2077.95  5034.5 2079.45
  5044.5 2080.52  5054.5  2084.4  5104.5 2078.23  5144.5 2078.23  5174.5 2085.25
  5194.5 2084.39  5234.5 2087.25  5314.5 2086.82  5474.6 2090.41  5565.4 2088.48
  5684.6 2084.36  5734.4 2087.98  5794.6 2091.41  6174.6 2096.87  6499.1 2105.29
#Mann= 7 ,-1 , 0
    3743     .07       0  4010.7     .16       0  4716.4     .07       0
  4981.7     .07       0  4987.2     .07       0  5565.4    .035       0
  5734.4     .07       0
#XS Ineff= 2 , 0
       0                  5054.5       0  2084.4
Permanent Ineff=
       F       F
Bank Sta=4981.7,4987.2
XS Rating Curve= 0 ,0
Exp/Cntr=0.3,0.1

Type RM Length L Ch R = 1 ,45092   ,553,553,553
BEGIN DESCRIPTION:
Mapping XS 5e16d3c6
END DESCRIPTION:
XS GIS Cut Line= 3
       1503157.2      6809159.98      1503951.46      6809841.39
      1504767.38      6810049.71
#Sta/Elev= 30
  3949.8 2081.73  3974.8 2081.52  3982.5 2082.76  4017.6 2080.28  4166.9 2079.37
  4173.5 2078.24  4315.8 2076.13  4599.5  2073.6  4861.4  2072.5  4947.2 2068.98
    4965  2063.6  4965.5  2063.1    4971  2063.6  4991.7 2064.49  5013.3 2068.99
  5167.4  2070.1    5227 2081.34  5268.2 2085.71  5284.8 2086.33  5340.5 2092.72
  5412.8  2097.6  5483.9 2097.82    5556 2100.04  5647.3 2107.54  5688.1 2105.79
  5693.3 2107.44  5722.4 2107.59  5728.9 2109.26  5743.1 2111.41  5838.4 2111.26
#Mann= 11 ,-1 , 0
  3949.8     .07       0  4315.8     .16       0  4599.5     .07       0
  4861.4     .16       0    4965     .07       0    4971     .16       0
  4991.7     .07       0  5013.3     .16       0  5268.2     .07       0
    5556    .035       0  5728.9     .07       0
Bank Sta=4965,4971
XS Rating Curve= 0 ,0
Exp/Cntr=0.3,0.1

Type RM Length L Ch R = 1 ,44539   ,645,645,645
BEGIN DESCRIPTION:
Mapping XS 7dd4c062
END DESCRIPTION:
XS GIS Cut Line= 3
      1503156.46      6809831.53      1503875.66       6810368.6
      1504661.65      6810284.27
#Sta/Elev= 30
  4102.4 2069.93  4412.6 2067.24  4526.9 2062.68  4585.3 2058.44  4599.8 2058.41
  4606.1 2060.74  4649.7 2062.75  4756.2  2062.8  4817.8  2056.7  4818.3  2056.2
  4823.9  2056.7    4925  2058.8  4956.4 2061.71  4962.6 2059.36  4977.2 2058.72
  5059.7 2059.58  5079.8 2062.93  5130.1 2065.33  5140.1 2067.62  5145.1 2071.36
  5150.7 2070.96  5190.4 2089.27  5250.8 2098.95  5301.1 2102.95  5380.5 2103.56
  5502.2 2106.46  5570.5 2110.34    5643 2112.92  5754.9 2111.69  5790.5 2111.02
#Mann= 8 ,-1 , 0
  4102.4     .16       0  4817.8     .07       0  4823.9     .16       0
    4925     .07       0  5145.1     .16       0  5380.5     .07       0
  5570.5    .035       0  5754.9     .07       0
#XS Ineff= 2 , 0
       0  4670.8 2063.13               0
Permanent Ineff=
       F       F
Bank Sta=4817.8,4823.9
XS Rating Curve= 0 ,0
Exp/Cntr=0.3,0.1

Type RM Length L Ch R = 1 ,43894   ,634,634,634
BEGIN DESCRIPTION:
Mapping XS bed4cd4f
END DESCRIPTION:
XS GIS Cut Line= 4
      1503193.77      6809974.59      1503354.19      6810603.14
      1503764.14      6810706.56      1504038.25       6810748.5
#Sta/Elev= 30
  4351.3 2068.02  4829.6 2061.34  4863.7 2060.41  4891.5 2056.35  4922.5 2053.84
  4981.1 2053.77  4986.3 2054.89  5059.6 2053.19  5060.1 2052.69  5065.9 2053.19
  5079.7 2055.84  5084.9 2054.49  5114.3 2056.73  5129.8 2055.59  5161.8 2056.96
  5176.2 2054.29  5208.1 2054.51  5249.1 2055.79  5299.9 2060.08  5341.2 2061.75
  5408.2  2058.3  5413.4 2059.54  5433.8 2058.66  5524.8 2060.14  5530.7 2060.79
  5545.1 2066.91  5594.1 2078.93  5599.1 2077.67  5681.2 2087.26  5700.1 2089.21
#Mann= 5 ,-1 , 0
  4351.3     .16       0  5059.6     .07       0  5065.9     .16       0
  5129.8     .07       0  5681.2     .16       0
Bank Sta=5059.6,5065.9
XS Rating Curve= 0 ,0
Exp/Cntr=0.3,0.1

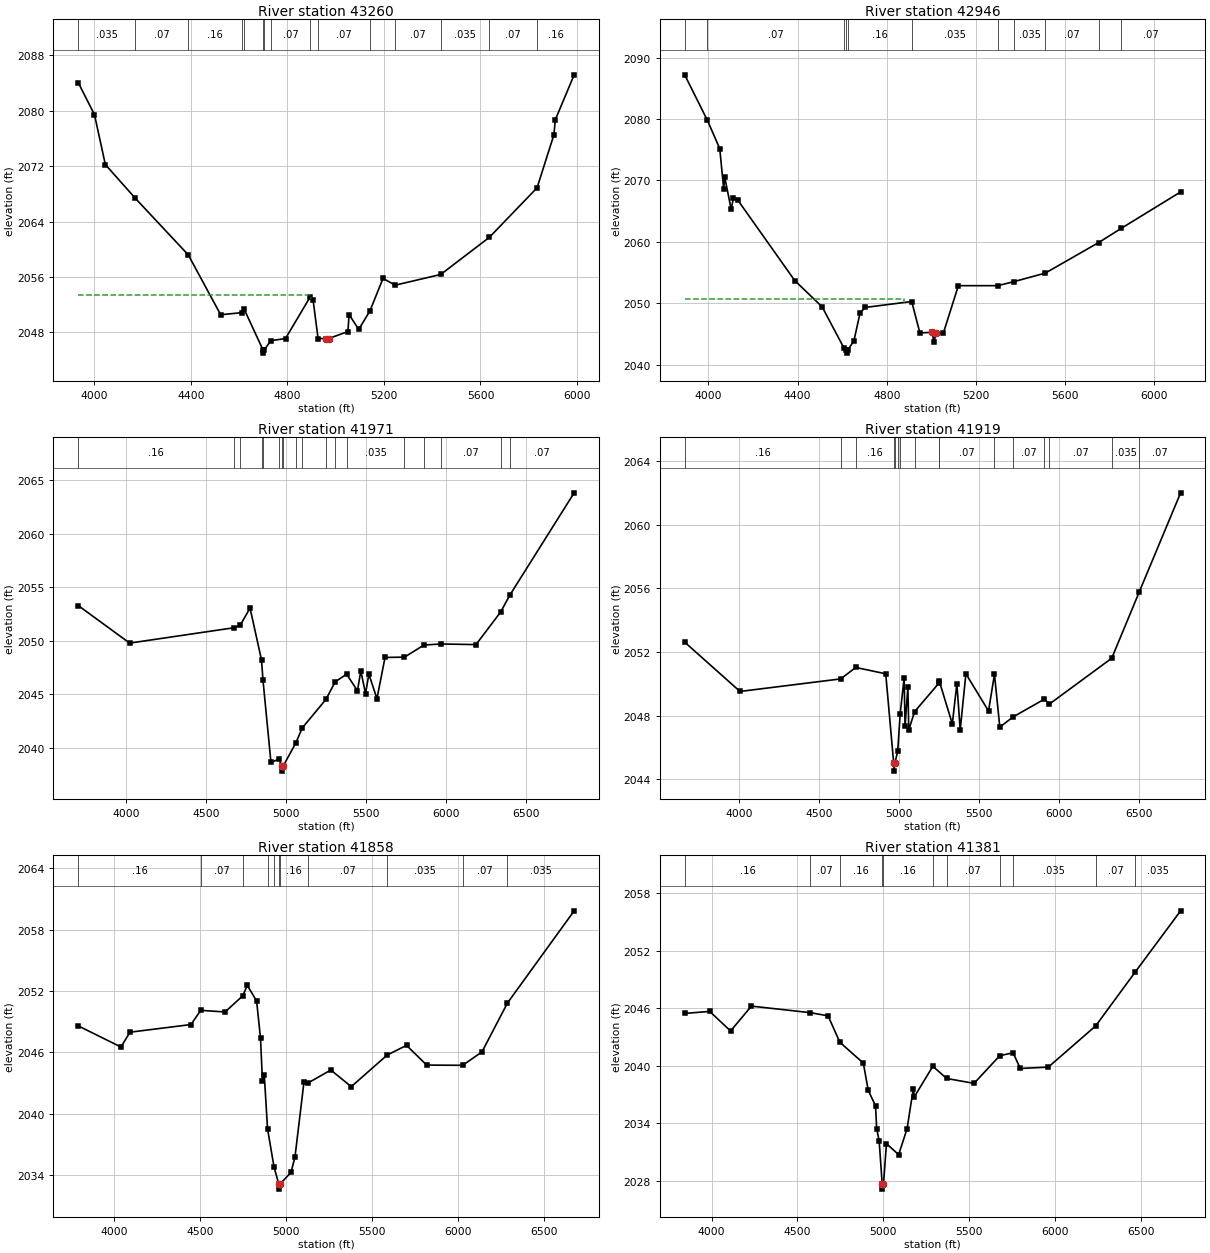
Type RM Length L Ch R = 1 ,43260   ,314,314,314
BEGIN DESCRIPTION:
Mapping XS 6d2df2ab
END DESCRIPTION:
XS GIS Cut Line= 4
      1502272.62      6810632.18      1503283.92      6811040.17
      1503696.25      6811083.58      1504186.68      6810836.19
#Sta/Elev= 30
  3933.6 2084.06  4000.9 2079.44    4046 2072.23  4170.7 2067.34  4389.5 2059.19
  4523.8 2050.55  4610.7 2050.85    4620 2051.43  4698.6 2045.51  4699.1 2045.01
    4705 2045.51  4731.1  2046.8  4792.3 2047.12  4893.9 2053.08  4906.6 2052.65
  4927.3 2047.11  4960.6 2047.12  4971.3 2047.12  5050.7 2048.12  5055.7 2050.58
  5095.6 2048.43  5142.4 2051.13  5196.1 2055.79  5247.1 2054.82  5435.5 2056.37
  5636.6 2061.72  5834.3 2068.87  5904.2 2076.53  5909.8 2078.68    5988 2085.18
#Mann= 15 ,-1 , 0
  3933.6    .035       0  4170.7     .07       0  4389.5     .16       0
  4610.7     .07       0    4620     .16       0  4698.6     .07       0
    4705     .16       0  4731.1     .07       0  4893.9    .035       0
  4927.3     .07       0  5142.4    .035       0  5247.1     .07       0
  5435.5    .035       0  5636.6     .07       0  5834.3     .16       0
#XS Ineff= 2 , 0
       0  4899.6 2053.39               0
Permanent Ineff=
       F       F
Bank Sta=4960.6,4971.3
XS Rating Curve= 0 ,0
Exp/Cntr=0.3,0.1

Type RM Length L Ch R = 1 ,42946   ,975,975,975
BEGIN DESCRIPTION:
Mapping XS 2b618b68
END DESCRIPTION:
XS GIS Cut Line= 3
      1502120.71      6811118.29      1503184.09      6811330.97
      1504256.17      6810944.67
#Sta/Elev= 30
  3893.3  2087.2  3995.5 2079.77  4050.6 2075.18  4068.1 2068.66  4073.2 2070.49
  4101.6 2065.35  4111.8 2067.07  4132.2 2066.77  4387.2  2053.7  4509.6 2049.44
  4607.4 2042.74  4618.5  2042.4    4619  2041.9  4624.9  2042.4  4652.3 2043.92
    4680 2048.47  4703.3 2049.34  4911.4  2050.3  4948.1 2045.19  5003.3 2045.29
  5010.6 2043.71  5021.2 2045.13  5053.1 2045.14  5120.7 2052.88  5297.5 2052.88
    5370 2053.54  5510.1 2054.92  5749.4 2059.89  5850.2 2062.19  6117.3 2068.14
#Mann= 11 ,-1 , 0
  3893.3    .035       0  3995.5     .07       0  4607.4     .16       0
  4618.5    .035       0  4624.9     .16       0  4911.4    .035       0
  5297.5     .07       0    5370    .035       0  5510.1     .07       0
  5749.4    .035       0  5850.2     .07       0
#XS Ineff= 2 , 0
       0  4876.7 2050.72               0
Permanent Ineff=
       F       F
Bank Sta=5003.3,5021.2
XS Rating Curve= 0 ,0
Exp/Cntr=0.3,0.1

Type RM Length L Ch R = 1 ,41971   ,52,52,52
BEGIN DESCRIPTION:
Mapping XS 1079814c
END DESCRIPTION:
XS GIS Cut Line= 5
      1501610.27      6812482.89      1502610.31      6812264.13
      1502797.81       6811868.3      1503188.43      6811592.26
      1504214.49      6811045.37
#Sta/Elev= 30
  3698.4 2053.28  4020.4 2049.77    4675 2051.21    4711 2051.42  4773.4 2053.04
  4845.1  2048.2  4854.4  2046.3  4904.3 2038.62  4952.1 2038.92  4974.5 2038.31
    4975 2037.81  4981.7 2038.31    5059 2040.42  5100.3 2041.85  5248.1 2044.51
  5306.1 2046.15  5377.4 2046.87  5445.4 2045.32  5466.4 2047.18  5495.9 2045.05
  5516.8 2046.87  5567.3 2044.58  5617.8 2048.43  5739.7 2048.46  5861.7 2049.59
  5967.4 2049.69  6186.8 2049.63  6341.1 2052.67  6397.3 2054.22  6801.1 2063.81
#Mann= 18 ,-1 , 0
  3698.4     .16       0    4675     .07       0    4711     .16       0
  4845.1     .07       0  4854.4     .16       0  4952.1     .07       0
  4974.5     .07       0  4981.7     .07       0    5059     .16       0
  5100.3     .07       0  5248.1    .035       0  5306.1     .07       0
  5377.4    .035       0  5739.7     .07       0  5861.7    .035       0
  5967.4     .07       0  6341.1    .035       0  6397.3     .07       0
Bank Sta=4974.5,4981.7
XS Rating Curve= 0 ,0
Exp/Cntr=0.3,0.1

Type RM Length L Ch R = 1 ,41919   ,61,61,61
BEGIN DESCRIPTION:
Mapping XS 7c74aaa3
END DESCRIPTION:
XS GIS Cut Line= 6
      1501610.66      6812526.98      1502652.32      6812297.81
      1502808.57      6811954.06      1502947.46      6811881.14
       1503218.3      6811603.37      1504214.85      6811113.77
#Sta/Elev= 30
  3659.5 2052.62  4005.4 2049.52  4634.7 2050.31    4729 2051.03  4916.2 2050.63
    4966 2045.01  4966.5 2044.51  4973.2 2045.01  4991.1 2045.76  5006.4 2048.09
  5031.4 2050.38  5036.9 2047.32  5054.7  2049.8  5060.2  2047.1  5096.7 2048.25
  5248.5 2050.04  5250.4 2050.19  5332.5 2047.48  5360.8 2050.01  5381.9 2047.11
  5417.3 2050.63  5558.8 2048.29  5595.8  2050.6  5629.3 2047.28  5714.5 2047.93
  5908.5 2049.04  5938.2 2048.72    6329 2051.61  6501.8  2055.8  6759.5 2062.01
#Mann= 16 ,-1 , 0
  3659.5     .16       0  4634.7     .07       0    4729     .16       0
    4966     .07       0  4973.2     .16       0  4991.1     .07       0
  5006.4     .16       0  5096.7     .07       0  5248.5    .035       0
  5250.4     .07       0  5595.8    .035       0  5714.5     .07       0
  5908.5    .035       0  5938.2     .07       0    6329    .035       0
  6501.8     .07       0
Bank Sta=4966,4973.2
XS Rating Curve= 0 ,0
Exp/Cntr=0.3,0.1

Type RM Length L Ch R = 1 ,41858   ,477,477,477
BEGIN DESCRIPTION:
Mapping XS df0257cb
END DESCRIPTION:
XS GIS Cut Line= 5
      1501825.89      6812704.08      1502704.41      6812322.12
      1502857.18      6811988.78       1503030.8      6811898.51
       1504214.8      6811214.49
#Sta/Elev= 30
  3789.3 2048.59  4038.2 2046.52  4090.6 2047.97  4446.1 2048.72  4502.6 2050.11
  4644.5 2049.95  4747.3 2051.53  4773.8 2052.55    4828 2051.03  4850.8 2047.37
    4862 2043.17  4872.8 2043.76  4891.8  2038.5  4929.8 2034.75  4957.2 2033.11
  4957.7 2032.61  4964.4 2033.11  5028.5 2034.25  5051.5 2035.77  5103.8 2043.09
  5127.8    2043  5260.1 2044.27  5379.3 2042.64  5587.9 2045.73  5700.9 2046.68
  5818.6 2044.75  6027.6 2044.73  6140.2 2046.04  6288.7 2050.83    6677 2059.85
#Mann= 11 ,-1 , 0
  3789.3     .16       0  4502.6     .07       0  4747.3     .16       0
  4891.8     .07       0  4929.8     .16       0  4957.2     .07       0
  4964.4     .16       0  5127.8     .07       0  5587.9    .035       0
  6027.6     .07       0  6288.7    .035       0
Bank Sta=4957.2,4964.4
XS Rating Curve= 0 ,0
Exp/Cntr=0.3,0.1

Type RM Length L Ch R = 1 ,41381   ,688,688,688
BEGIN DESCRIPTION:
Mapping XS ce846207
END DESCRIPTION:
XS GIS Cut Line= 4
      1501822.43      6812826.46      1502794.68      6812663.26
      1503815.52      6811534.79      1504130.72      6811326.96
#Sta/Elev= 30
  3843.8 2045.45  3989.5 2045.66  4110.7 2043.62    4232 2046.21  4573.9 2045.53
  4677.9  2045.2  4746.4 2042.45  4883.1 2040.28  4911.5 2037.45  4954.1 2035.83
  4960.8 2033.42    4975 2032.22    4993 2027.66  4993.5 2027.16  5000.3 2027.66
  5017.6 2031.89  5088.6 2030.75  5137.9 2033.47  5173.8 2037.63  5180.5 2036.79
  5287.5 2039.95  5367.5 2038.68  5527.2 2038.17  5676.7 2041.05  5754.1 2041.35
  5796.2 2039.72  5959.1 2039.86  6234.7 2044.15  6463.6 2049.73  6728.9 2056.13
#Mann= 11 ,-1 , 0
  3843.8     .16       0  4573.9     .07       0  4746.4     .16       0
    4993     .07       0  5000.3     .16       0  5287.5     .12       0
  5367.5     .07       0  5676.7     .16       0  5754.1    .035       0
  6234.7     .07       0  6463.6    .035       0
Bank Sta=4993,5000.3
XS Rating Curve= 0 ,0
Exp/Cntr=0.3,0.1

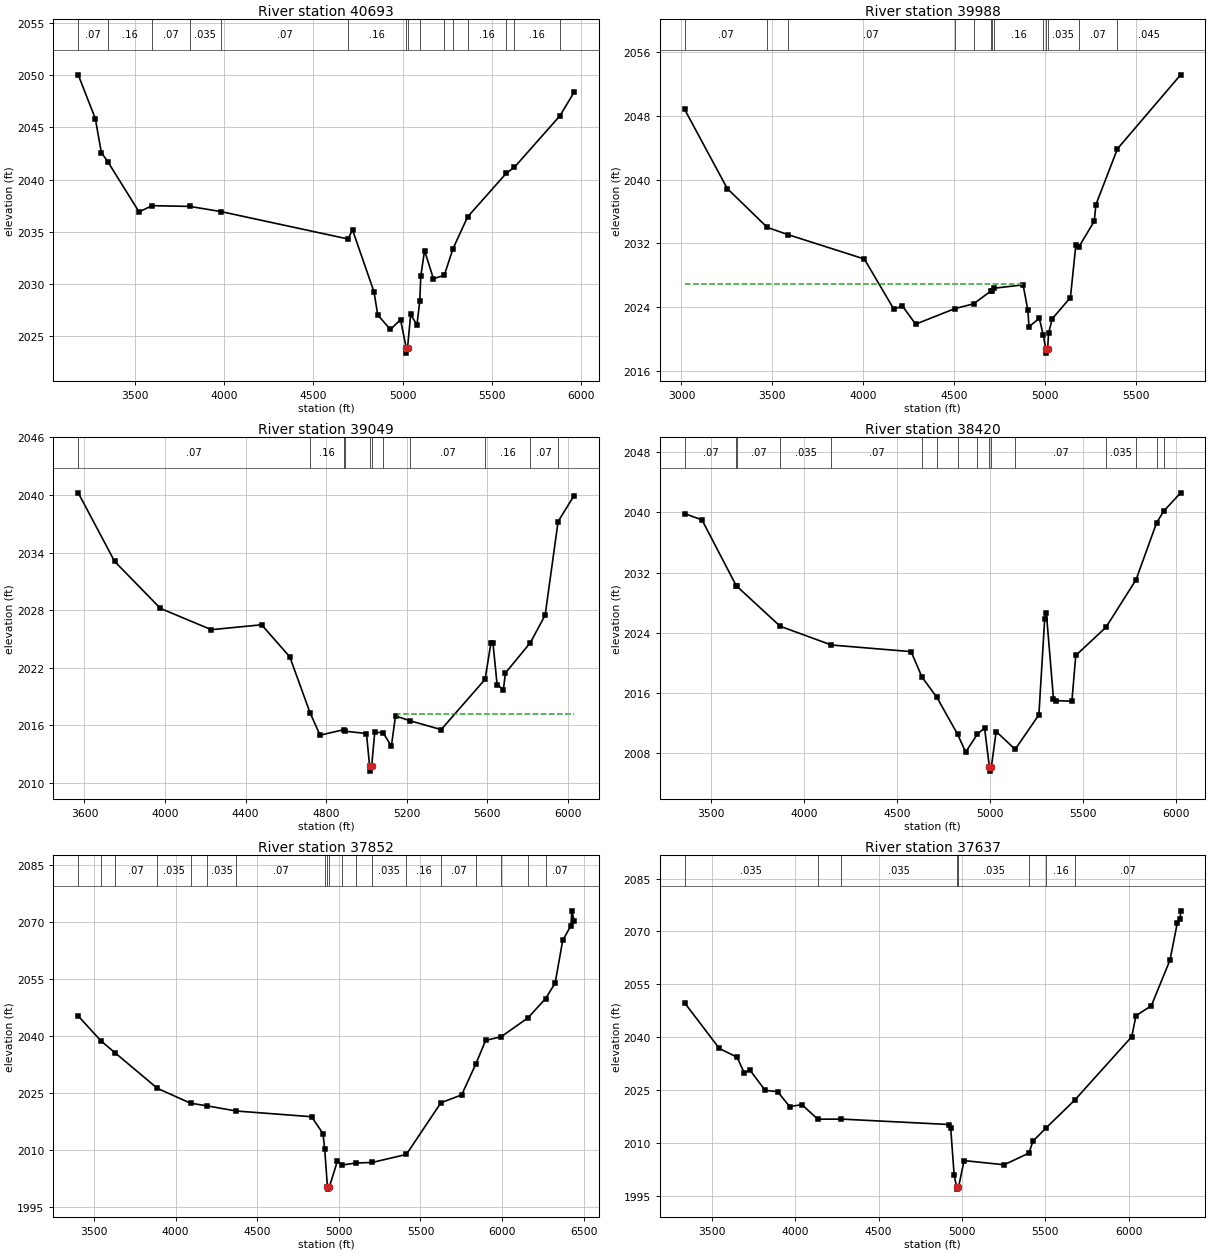
Type RM Length L Ch R = 1 ,40693   ,705,705,705
BEGIN DESCRIPTION:
Mapping XS 820f9c61
END DESCRIPTION:
XS GIS Cut Line= 3
        1501878.      6813406.33       1503280.8      6812736.18
      1504114.12      6811843.83
#Sta/Elev= 30
  3183.6 2050.04  3279.3 2045.85  3313.3 2042.58  3349.2 2041.72  3523.8 2036.92
  3597.8 2037.51  3807.4 2037.44  3980.9 2036.95  4693.6 2034.32  4718.8 2035.19
    4839 2029.26    4860 2027.04  4930.9 2025.66  4987.5 2026.59  5019.4 2023.89
  5019.9 2023.39  5026.7 2023.89  5044.2 2027.09  5079.4 2026.09  5095.1 2028.35
  5100.9 2030.76  5121.9 2033.21  5171.7 2030.51  5232.4 2030.85  5281.1 2033.39
  5363.1 2036.44  5580.2 2040.63  5624.4 2041.18  5879.3 2046.11  5959.2 2048.38
#Mann= 15 ,-1 , 0
  3183.6     .07       0  3349.2     .16       0  3597.8     .07       0
  3807.4    .035       0  3980.9     .07       0  4693.6     .16       0
  5019.4     .07       0  5026.7     .16       0  5095.1     .12       0
  5232.4     .16       0  5281.1     .12       0  5363.1     .16       0
  5580.2     .12       0  5624.4     .16       0  5879.3    .035       0
Bank Sta=5019.4,5026.7
XS Rating Curve= 0 ,0
Exp/Cntr=0.3,0.1

Type RM Length L Ch R = 1 ,39988   ,939,939,939
BEGIN DESCRIPTION:
Mapping XS ba33d34e
END DESCRIPTION:
XS GIS Cut Line= 3
      1501911.32      6813654.24       1503793.3       6813070.9
      1504550.13       6813022.3
#Sta/Elev= 30
  3017.9 2048.84  3252.1  2038.9  3471.9 2034.02  3585.4 2033.11  4006.4 2030.04
  4169.3 2023.71  4215.3 2024.16  4288.5 2021.85  4502.7 2023.79  4607.3 2024.41
  4701.5 2025.99  4710.6 2025.97  4717.9 2026.36  4879.9 2026.79  4906.2 2023.58
  4912.5 2021.54  4969.1 2022.58  4990.3 2020.55  5005.1 2018.71  5005.6 2018.21
  5014.9 2018.71    5020 2020.69    5040 2022.53  5140.2 2025.19  5170.3 2031.83
  5186.3 2031.55  5271.5 2034.79  5280.5 2036.87    5399 2043.89  5746.6 2053.19
#Mann= 13 ,-1 , 0
  3017.9     .07       0  3471.9    .035       0  3585.4     .07       0
  4502.7     .16       0  4607.3     .07       0  4701.5     .16       0
  4710.6     .07       0  4717.9     .16       0  4990.3    .035       0
  5005.1    .035       0  5014.9    .035       0  5186.3     .07       0
    5399    .045       0
#XS Ineff= 2 , 0
       0  4874.7 2026.84               0
Permanent Ineff=
       F       F
Bank Sta=5005.1,5014.9
XS Rating Curve= 0 ,0
Exp/Cntr=0.3,0.1

Type RM Length L Ch R = 1 ,39049   ,629,629,629
BEGIN DESCRIPTION:
Mapping XS 80e39044
END DESCRIPTION:
XS GIS Cut Line= 3
      1502024.16      6813866.04      1503430.45      6813855.62
      1504456.48      6814108.23
#Sta/Elev= 30
  3568.9 2040.23  3749.7 2033.08  3977.1 2028.18  4229.8 2025.96  4479.8 2026.47
  4619.8 2023.12  4720.2  2017.3  4769.8 2014.96  4889.6 2015.54    4892 2015.38
  5000.5 2015.13  5016.2 2011.71  5016.7 2011.21  5026.1 2011.71  5041.7 2015.27
  5083.4 2015.21  5124.1  2013.8  5144.7 2016.97  5217.1 2016.46  5371.3 2015.54
  5589.4 2020.78  5618.4 2024.55  5628.6 2024.59  5649.3 2020.23  5680.4  2019.7
  5690.5 2021.44  5814.6 2024.61  5887.9 2027.48  5952.2 2037.24  6031.9 2039.95
#Mann= 11 ,-1 , 0
  3568.9     .07       0  4720.2     .16       0  4889.6     .07       0
    4892     .16       0  5016.2     .07       0  5026.1     .16       0
  5083.4    .035       0  5217.1     .07       0  5589.4     .16       0
  5814.6     .07       0  5952.2    .035       0
#XS Ineff= 2 , 0
       0                    5155       0 2017.13
Permanent Ineff=
       F       F
Bank Sta=5016.2,5026.1
XS Rating Curve= 0 ,0
Exp/Cntr=0.3,0.1

Type RM Length L Ch R = 1 ,38420   ,568,568,568
BEGIN DESCRIPTION:
Mapping XS 17353702
END DESCRIPTION:
XS GIS Cut Line= 3
      1501841.29      6814114.96      1503435.01      6814419.64
      1504435.04      6814719.13
#Sta/Elev= 30
  3356.5 2039.85  3449.7    2039  3633.9 2030.24  3636.4 2030.19  3869.8 2024.86
  4145.7 2022.36  4573.9 2021.48  4632.5 2018.09  4712.6 2015.39  4824.2 2010.47
  4867.1 2008.11  4930.3  2010.5  4968.9 2011.33    4995 2006.08  4995.5 2005.58
    5005 2006.08  5031.3 2010.85  5133.4 2008.48  5260.9 2013.07  5292.2 2025.82
    5301 2026.66  5339.3 2015.23  5354.9 2014.96  5438.4 2014.88  5459.3 2020.97
  5621.6 2024.72  5783.4 2031.05  5893.7 2038.61  5931.6 2040.16    6023 2042.61
#Mann= 16 ,-1 , 0
  3356.5     .07       0  3633.9    .035       0  3636.4     .07       0
  3869.8    .035       0  4145.7     .07       0  4632.5     .16       0
  4712.6     .07       0  4824.2     .16       0  4930.3    .035       0
    4995    .035       0    5005    .035       0  5133.4     .07       0
  5621.6    .035       0  5783.4     .07       0  5893.7     .16       0
  5931.6     .07       0
Bank Sta=4995,5005
XS Rating Curve= 0 ,0
Exp/Cntr=0.3,0.1

Type RM Length L Ch R = 1 ,37852   ,215,215,215
BEGIN DESCRIPTION:
Mapping XS aadd0fc9
END DESCRIPTION:
XS GIS Cut Line= 3
      1501536.52      6814328.49      1503091.26       6814706.1
      1504461.84      6815137.82
#Sta/Elev= 30
    3404 2045.24  3544.3 2038.64  3628.7 2035.56  3889.2 2026.16  4092.1 2022.24
  4192.7 2021.55  4370.7 2020.19  4832.8 2018.68  4902.9 2014.24  4913.4 2010.13
  4930.3 2000.09  4930.8 1999.59  4941.1 2000.09  4991.6 2007.04  5021.9 2005.96
  5104.9 2006.48  5204.3 2006.62  5413.5 2008.74  5624.8 2022.35  5752.2 2024.45
  5839.7 2032.68    5899 2038.81  5994.3 2039.78  6158.5 2044.76  6265.5 2049.81
  6324.3  2053.9  6370.8 2065.15  6421.4 2069.09  6426.7 2072.97  6440.9 2070.23
#Mann= 19 ,-1 , 0
    3404     .07       0  3544.3     .16       0  3628.7     .07       0
  3889.2    .035       0  4092.1     .07       0  4192.7    .035       0
  4370.7     .07       0  4913.4     .16       0  4930.3     .07       0
  4941.1     .16       0  5021.9     .07       0  5104.9     .16       0
  5204.3    .035       0  5413.5     .16       0  5624.8     .07       0
  5839.7    .035       0  5994.3     .07       0  6158.5     .16       0
  6265.5     .07       0
Bank Sta=4930.3,4941.1
XS Rating Curve= 0 ,0
Exp/Cntr=0.3,0.1

Type RM Length L Ch R = 1 ,37637   ,862,862,862
BEGIN DESCRIPTION:
Mapping XS c1a61ea7
END DESCRIPTION:
XS GIS Cut Line= 3
      1501382.91      6814500.37      1502987.09      6814883.18
      1504233.47      6815333.34
#Sta/Elev= 30
  3336.7 2049.71  3544.5  2036.8    3651 2034.31  3693.1 2029.96  3729.5 2030.57
  3819.4 2024.91    3894 2024.55    3966 2020.32  4040.2 2020.85  4134.2 2016.73
  4276.7 2016.76  4922.1 2015.22  4932.4 2014.09  4952.9 2000.84  4968.1 1997.39
  4968.6 1996.89  4978.9 1997.39  5012.5 2004.98  5252.6  2003.8  5400.9  2007.1
  5425.9 2010.52  5505.1  2014.3  5676.3 2022.16    6018 2040.14  6043.4  2046.1
  6135.4 2048.89  6247.4 2061.88  6291.5 2072.49  6308.8 2073.42  6311.1 2075.84
#Mann= 8 ,-1 , 0
  3336.7    .035       0  4134.2     .07       0  4276.7    .035       0
  4968.1    .035       0  4978.9    .035       0  5400.9     .07       0
  5505.1     .16       0  5676.3     .07       0
Bank Sta=4968.1,4978.9
XS Rating Curve= 0 ,0
Exp/Cntr=0.3,0.1

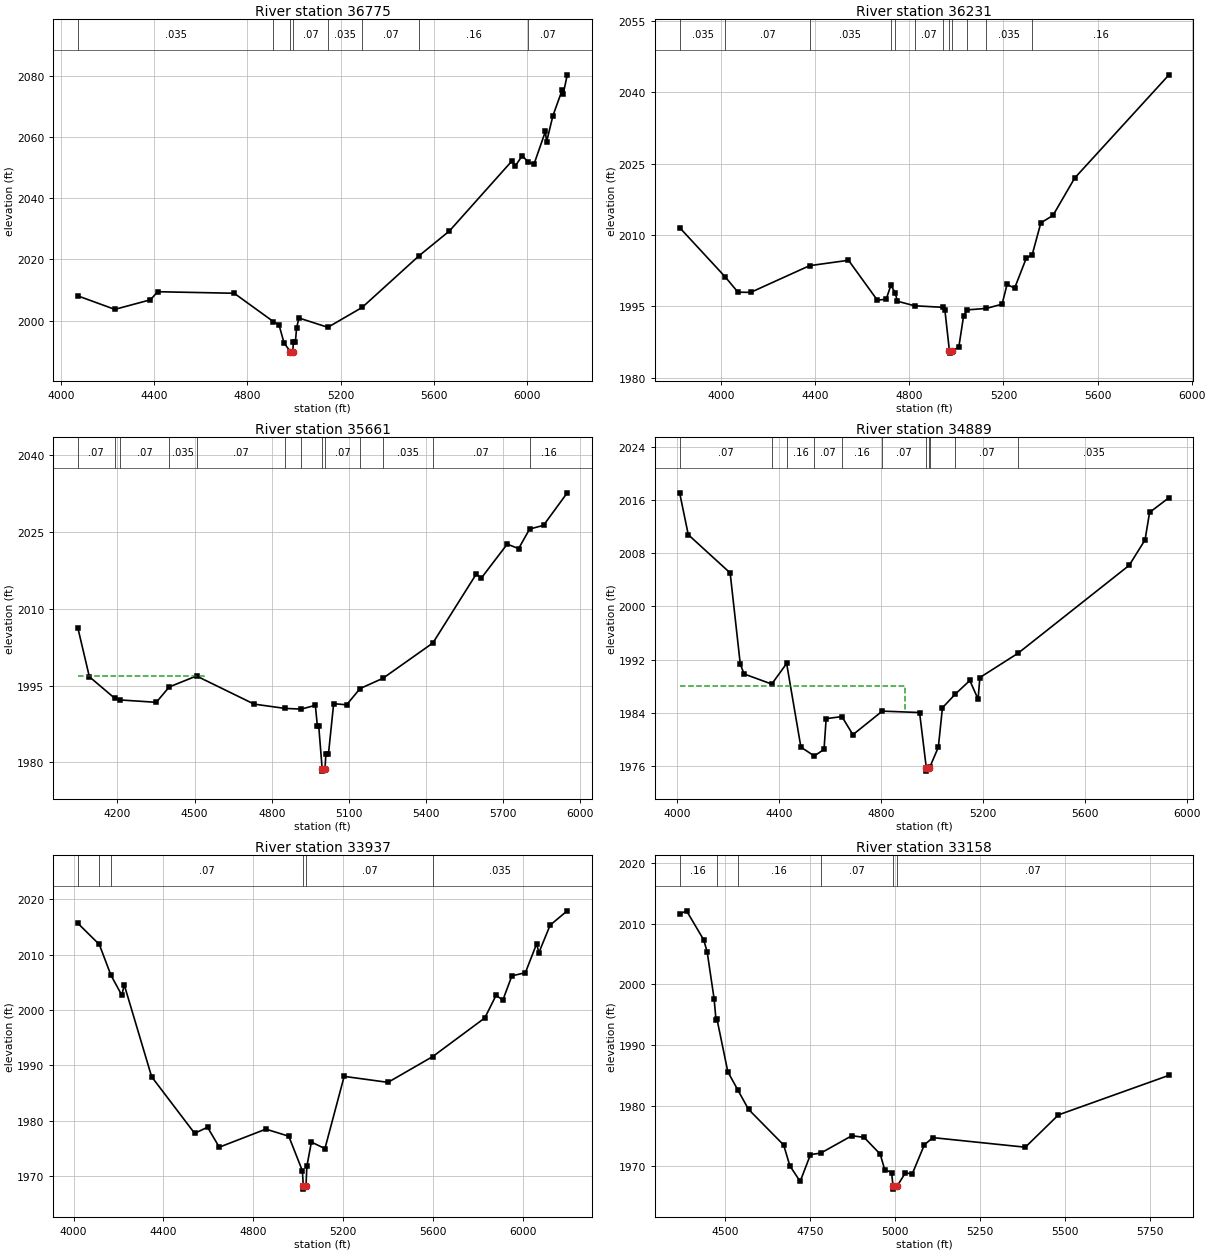
Type RM Length L Ch R = 1 ,36775   ,544,544,544
BEGIN DESCRIPTION:
Mapping XS 7fa21b0e
END DESCRIPTION:
XS GIS Cut Line= 3
      1502098.78      6815314.55      1502959.92      6815675.68
      1504116.15       6815835.4
#Sta/Elev= 30
  4072.2 2008.07  4230.8 2003.67  4383.2 2006.79  4415.1 2009.44  4743.2 2008.94
  4911.3 1999.68  4935.6 1998.64  4957.3 1992.69  4984.4 1989.86  4984.9 1989.36
  4995.3 1989.86  4997.2 1992.95    5006 1992.99  5011.1 1997.55  5021.2 2000.85
  5145.4  1997.8  5292.7 2004.31    5538 2021.27  5667.3  2029.3  5935.6  2052.2
    5950 2050.58  5980.2 2053.92  6006.4 2051.74  6030.7 2051.21  6079.4 2061.87
  6084.4 2058.43  6111.5 2066.95  6151.3 2075.39  6156.3 2074.26  6173.2 2080.37
#Mann= 8 ,-1 , 0
  4072.2    .035       0  4911.3     .07       0  4984.4     .07       0
  4995.3     .07       0  5145.4    .035       0  5292.7     .07       0
    5538     .16       0  6006.4     .07       0
Bank Sta=4984.4,4995.3
XS Rating Curve= 0 ,0
Exp/Cntr=0.3,0.1

Type RM Length L Ch R = 1 ,36231   ,570,570,570
BEGIN DESCRIPTION:
Mapping XS 6aa89fc4
END DESCRIPTION:
XS GIS Cut Line= 3
      1501702.93      6815758.99      1502789.78      6816165.26
      1503685.65      6816370.13
#Sta/Elev= 30
  3824.4 2011.55  4018.4 2001.17  4072.2 1997.97  4126.2 1997.93  4376.7 2003.55
  4541.9 2004.68  4664.4  1996.3    4702 1996.49  4721.9  1999.4  4739.8 1997.89
  4749.9 1996.07  4823.1 1995.11    4944 1994.79  4951.3 1994.29  4970.7 1985.66
  4971.2 1985.16  4981.8 1985.66  5010.6 1986.41  5031.1 1993.02  5046.3 1994.25
  5127.3 1994.56  5194.5 1995.45  5215.7 1999.61  5247.7 1998.81  5297.8 2005.19
  5321.9 2005.75  5359.3 2012.56  5410.6  2014.1    5503 2021.97  5903.7 2043.67
#Mann= 12 ,-1 , 0
  3824.4    .035       0  4018.4     .07       0  4376.7    .035       0
  4721.9     .07       0  4739.8    .035       0  4823.1     .07       0
    4944    .035       0  4970.7    .035       0  4981.8    .035       0
  5046.3     .07       0  5127.3    .035       0  5321.9     .16       0
Bank Sta=4970.7,4981.8
XS Rating Curve= 0 ,0
Exp/Cntr=0.3,0.1

Type RM Length L Ch R = 1 ,35661   ,772,772,772
BEGIN DESCRIPTION:
Mapping XS daead46a
END DESCRIPTION:
XS GIS Cut Line= 3
      1501723.84      6816279.85      1502584.92      6816640.95
      1503546.69      6816755.53
#Sta/Elev= 30
  4046.4 2006.23    4091 1996.72  4189.2 1992.54  4208.5  1992.2  4351.3 1991.73
  4401.4 1994.73  4507.5 1996.87  4731.5 1991.38  4851.6 1990.54  4915.6 1990.41
  4969.4 1991.15  4977.5 1987.05  4982.7 1987.05  4995.9  1978.8  4996.4  1978.3
    5007  1978.8  5010.4 1981.56  5020.5 1981.66  5040.6 1991.46    5091 1991.25
  5143.5 1994.42  5231.9 1996.41  5426.3 2003.31  5594.5 2016.73  5614.7 2015.98
  5715.4 2022.61  5759.5 2021.73  5802.4 2025.55  5856.4 2026.27  5948.7 2032.62
#Mann= 13 ,-1 , 0
  4046.4     .07       0  4189.2    .035       0  4208.5     .07       0
  4401.4    .035       0  4507.5     .07       0  4851.6    .035       0
  4915.6     .07       0  4995.9     .07       0    5007     .07       0
  5143.5     .16       0  5231.9    .035       0  5426.3     .07       0
  5802.4     .16       0
#XS Ineff= 2 , 0
       0  4535.6 1996.92               0
Permanent Ineff=
       F       F
Bank Sta=4995.9,5007
XS Rating Curve= 0 ,0
Exp/Cntr=0.3,0.1

Type RM Length L Ch R = 1 ,34889   ,952,952,952
BEGIN DESCRIPTION:
Mapping XS 3cc3d35a
END DESCRIPTION:
XS GIS Cut Line= 3
      1501457.18      6816869.44      1502318.25      6817282.62
       1503245.3      6817543.03
#Sta/Elev= 30
  4010.8 2017.05  4044.7 2010.76  4208.8 2005.02  4248.5 1991.33  4263.5 1989.85
  4371.8 1988.33  4430.2 1991.43  4486.1 1978.86  4538.5 1977.54  4576.7 1978.52
  4585.1 1983.14  4646.8 1983.45  4689.9 1980.73  4805.1 1984.27  4951.2 1984.06
  4977.6 1975.76  4978.1 1975.26  4988.9 1975.76  4990.9 1975.81  5024.8 1978.86
  5040.8 1984.77  5090.3 1986.79  5148.2 1988.87  5180.6 1986.06  5187.5 1989.31
  5337.1 1992.96  5772.7 2006.16    5835 2009.99  5852.7 2014.11  5928.8 2016.32
#Mann= 11 ,-1 , 0
  4010.8     .07       0  4371.8    .035       0  4430.2     .16       0
  4538.5     .07       0  4646.8     .16       0  4805.1     .07       0
  4977.6     .07       0  4988.9     .07       0  4990.9     .16       0
  5090.3     .07       0  5337.1    .035       0
#XS Ineff= 2 , 0
       0  4893.8    1988               0
Permanent Ineff=
       F       F
Bank Sta=4977.6,4988.9
XS Rating Curve= 0 ,0
Exp/Cntr=0.3,0.1

Type RM Length L Ch R = 1 ,33937   ,779,779,779
BEGIN DESCRIPTION:
Mapping XS 6eecb73c
END DESCRIPTION:
XS GIS Cut Line= 3
      1501002.24      6817695.81      1501957.14      6817876.37
      1503160.98      6817970.04
#Sta/Elev= 30
  4019.2 2015.63  4114.6 2011.82  4165.8 2006.33  4214.8 2002.65  4225.6 2004.54
  4347.7 1987.94  4539.1 1977.73  4596.6 1978.83  4648.9 1975.23  4856.5 1978.49
  4958.3 1977.21    5019 1970.96  5023.1 1968.16  5023.6 1967.66  5034.9 1968.16
    5039  1971.8  5059.1 1976.16  5119.3 1974.97    5205 1988.01  5400.1 1986.93
  5599.5 1991.59  5831.4 1998.56  5881.6 2002.65  5911.7 2001.77  5951.8 2006.15
    6012 2006.72  6062.1 2011.94  6072.1 2010.33  6122.3 2015.31  6198.5 2017.89
#Mann= 6 ,-1 , 0
  4019.2     .07       0  4114.6     .16       0  4165.8     .07       0
  5023.1     .07       0  5034.9     .07       0  5599.5    .035       0
Bank Sta=5023.1,5034.9
XS Rating Curve= 0 ,0
Exp/Cntr=0.3,0.1

Type RM Length L Ch R = 1 ,33158   ,982,982,982
BEGIN DESCRIPTION:
Mapping XS 30285c80
END DESCRIPTION:
XS GIS Cut Line= 4
      1501194.94       6817996.5      1501708.88      6818076.37
      1501750.54      6818340.26      1502389.47      6818465.27
#Sta/Elev= 30
  4367.1 2011.57  4387.4  2012.1    4438  2007.3  4448.1 2005.31  4468.4 1997.61
    4474 1994.15  4476.5 1994.34  4508.8 1985.56  4537.4 1982.64  4569.6 1979.37
  4672.9 1973.49    4691 1970.07  4721.4 1967.49  4751.7 1971.92  4781.6 1972.15
  4873.2 1975.02  4909.1 1974.76  4956.6 1971.99  4969.8 1969.44  4990.1 1968.96
  4994.3 1966.72  4994.8 1966.22  5006.2 1966.72  5030.6 1968.89  5050.8 1968.73
  5086.5 1973.54  5111.6 1974.71  5383.1 1973.13  5480.5 1978.46  5805.4 1984.98
#Mann= 6 ,-1 , 0
  4367.1     .16       0  4476.5     .07       0  4537.4     .16       0
  4781.6     .07       0  4994.3     .07       0  5006.2     .07       0
#XS Ineff= 2 , 0
       0  4873.2 1975.02               0
Permanent Ineff=
       F       F
Bank Sta=4994.3,5006.2
XS Rating Curve= 0 ,0
Exp/Cntr=0.3,0.1