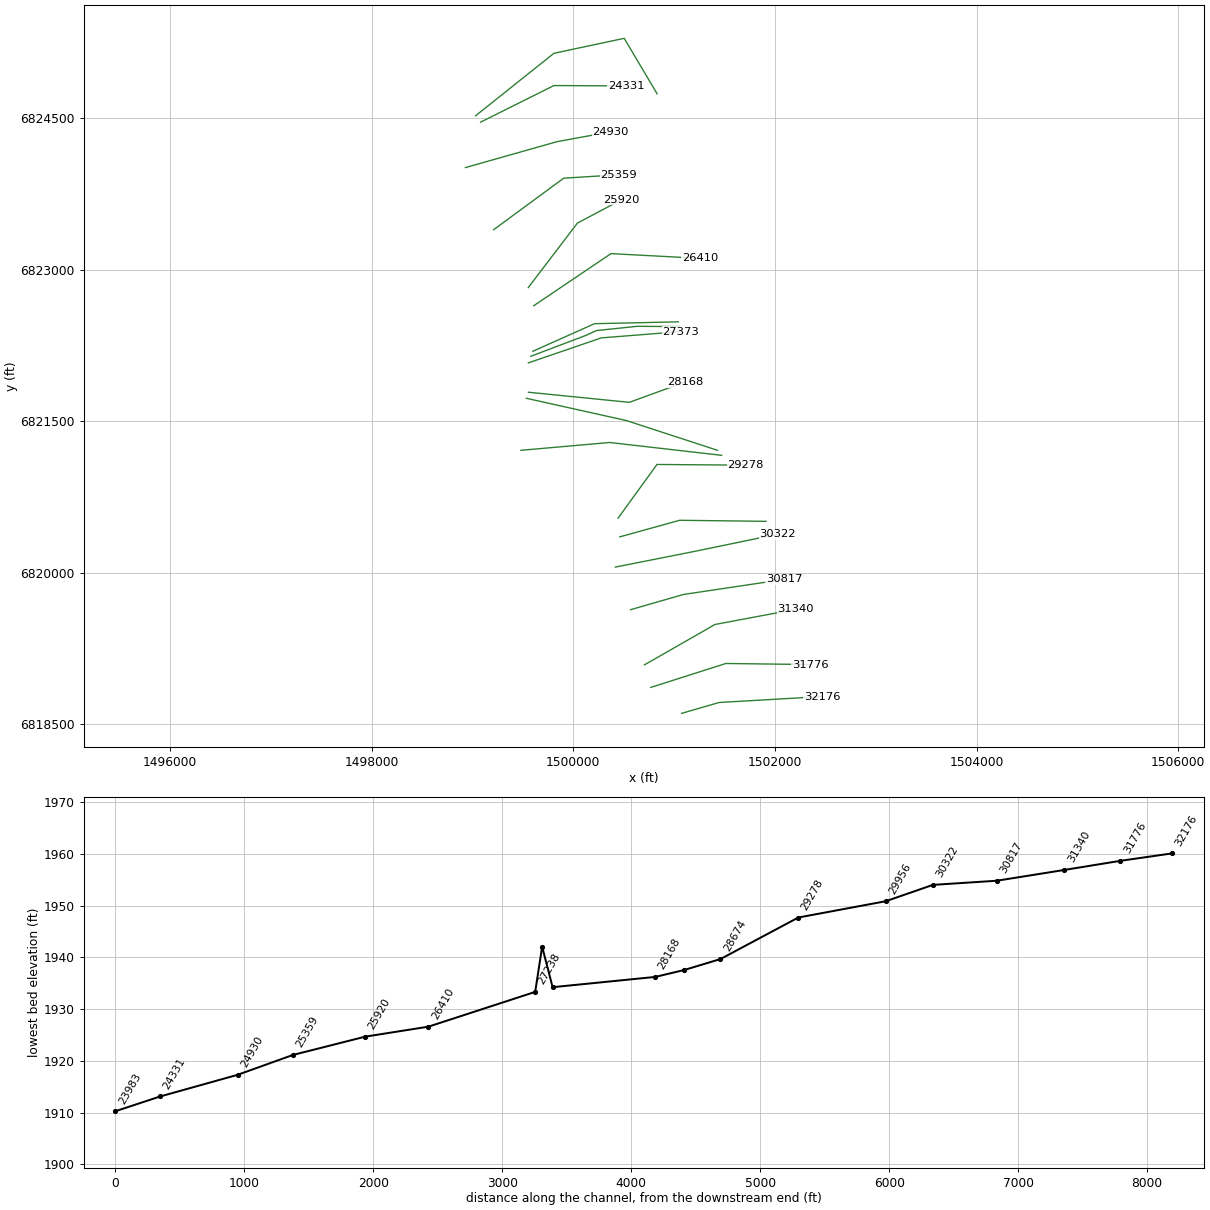
HEC-RAS study MULBERRY CREEK TRIBUTARY 18.prj: MULBERRY CREEK TRIBUTARY 18 Base Level Engineering

--- MULBERRY CREEK TRIBUTARY 18.g01 (geometry) --- (continued)

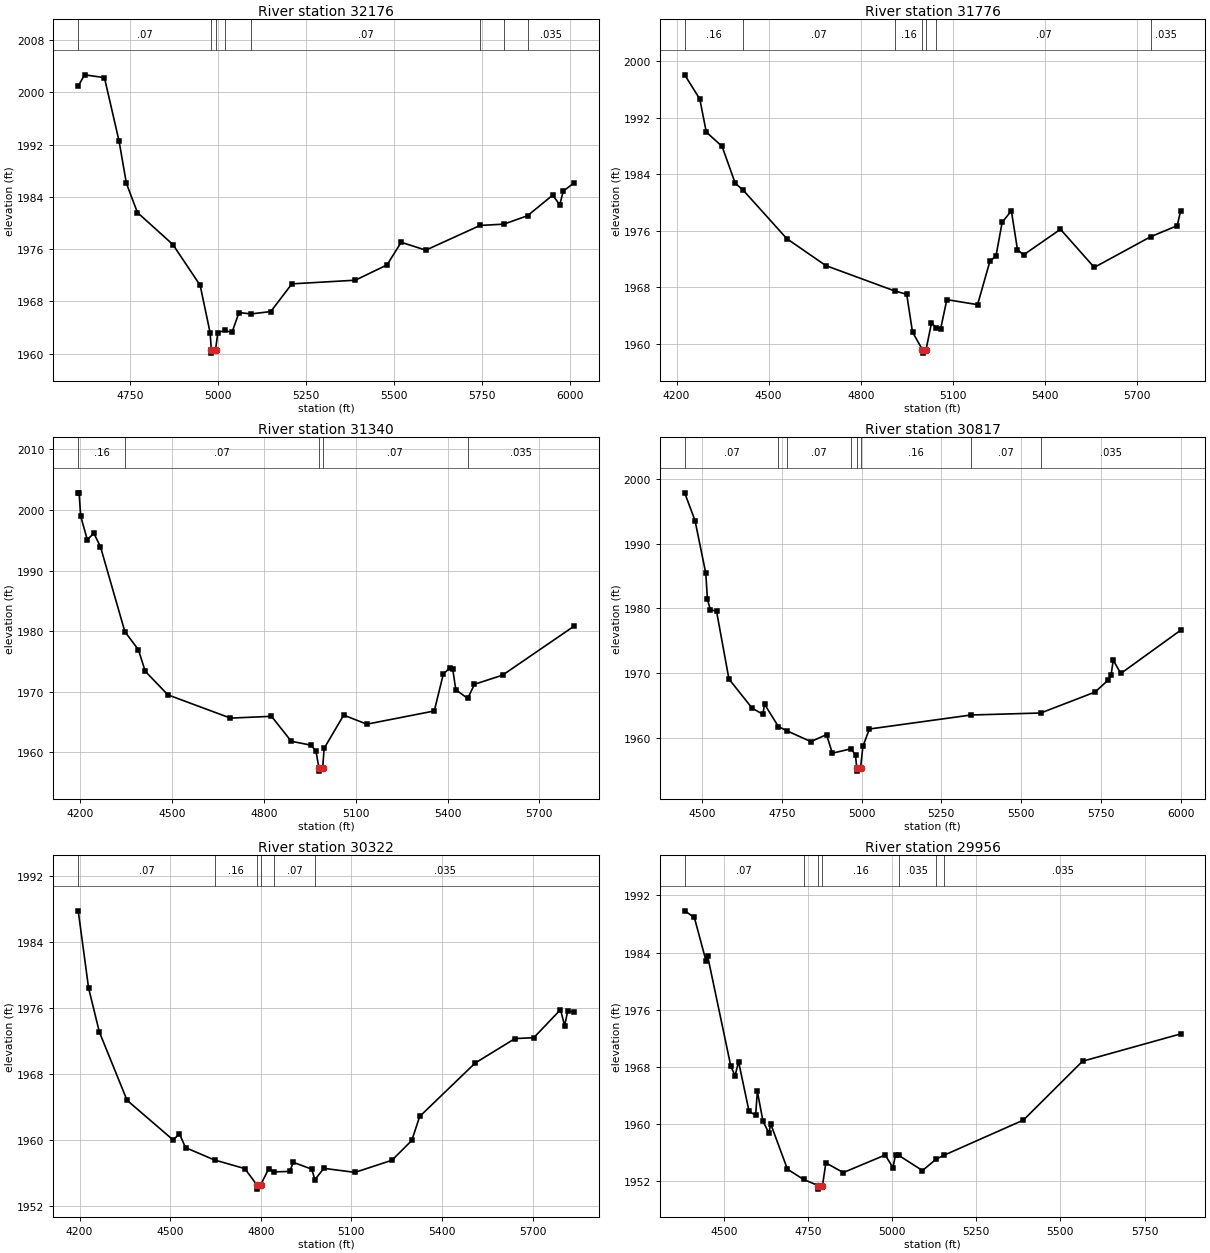
Type RM Length L Ch R = 1 ,32176   ,400,400,400
BEGIN DESCRIPTION:
Mapping XS f6a5786b
END DESCRIPTION:
XS GIS Cut Line= 3
      1501073.49      6818607.63      1501444.99      6818715.26
      1502465.81      6818774.29
#Sta/Elev= 30
  4603.7 2000.97  4621.9 2002.68  4678.2 2002.25  4719.8 1992.53  4740.6 1986.08
  4771.9 1981.61  4872.7 1976.71  4950.2 1970.47  4978.6 1963.19  4981.9 1960.59
  4982.4 1960.09  4993.9 1960.59  5000.5 1963.23    5020 1963.56  5040.6 1963.25
  5060.6  1966.3  5094.8 1966.09  5150.8 1966.45  5210.9 1970.69  5391.2 1971.25
  5481.3 1973.59  5521.4 1977.05  5591.5 1975.85  5745.8 1979.63  5813.3 1979.83
  5880.6 1981.12  5952.1 1984.27  5972.1 1982.79  5982.1 1984.88    6013 1986.16
#Mann= 8 ,-1 , 0
  4603.7     .07       0  4981.9     .07       0  4993.9     .07       0
    5020     .16       0  5094.8     .07       0  5745.8     .16       0
  5813.3     .07       0  5880.6    .035       0
Bank Sta=4981.9,4993.9
XS Rating Curve= 0 ,0
Exp/Cntr=0.3,0.1

Type RM Length L Ch R = 1 ,31776   ,436,436,436
BEGIN DESCRIPTION:
Mapping XS 1fc8d797
END DESCRIPTION:
XS GIS Cut Line= 3
      1500768.05      6818864.73      1501512.87      6819101.72
      1502346.19       6819091.3
#Sta/Elev= 30
  4226.6  1998.1  4275.9 1994.66  4296.9 1989.99  4348.4 1987.96  4391.3 1982.72
  4416.3 1981.79  4559.2 1974.88  4686.5 1971.06  4910.1 1967.48  4949.6    1967
  4968.5 1961.64  5000.7 1959.16  5001.2 1958.66  5012.7 1959.16  5030.3 1962.94
  5046.4 1962.24  5060.3 1962.13  5080.3 1966.24  5180.4 1965.53  5220.4 1971.66
  5240.4 1972.44  5260.4 1977.19  5290.4 1978.84  5310.4  1973.3  5330.4 1972.59
  5450.4 1976.21  5560.4 1970.81  5744.2 1975.16  5830.4 1976.72  5841.6 1978.81
#Mann= 7 ,-1 , 0
  4226.6     .16       0  4416.3     .07       0  4910.1     .16       0
  5000.7     .07       0  5012.7     .16       0  5046.4     .07       0
  5744.2    .035       0
Bank Sta=5000.7,5012.7
XS Rating Curve= 0 ,0
Exp/Cntr=0.3,0.1

Type RM Length L Ch R = 1 ,31340   ,523,523,523
BEGIN DESCRIPTION:
MULBERRY CREEK TRIBUTARY 18 27.0
END DESCRIPTION:
XS GIS Cut Line= 3
      1500704.96      6819087.98        1501405.        6819488.
      1502204.99        6819638.
#Sta/Elev= 30
  4193.3 2002.83  4196.2 2002.83  4201.3    1999  4222.9  1995.1  4244.5 1996.15
  4266.1 1993.91  4345.7 1979.91  4389.9 1976.93  4412.2 1973.38  4486.3 1969.48
  4690.8 1965.64  4824.7 1965.94  4889.4 1961.82  4954.2 1961.17  4970.1 1960.16
  4979.8 1957.39  4980.3 1956.89  4991.9 1957.39  4996.7 1960.65  5060.6 1966.14
  5136.1 1964.64  5356.5 1966.82  5386.2 1972.94  5409.1 1973.99  5416.7 1973.76
  5426.9 1970.32  5465.8 1968.89  5487.9 1971.23  5579.5 1972.73  5813.5 1980.83
#Mann= 5 ,-1 , 0
  4193.3     .16       0  4345.7     .07       0  4979.8     .07       0
  4991.9     .07       0  5465.8    .035       0
Bank Sta=4979.8,4991.9
XS Rating Curve= 0 ,0
Exp/Cntr=0.3,0.1

Type RM Length L Ch R = 1 ,30817   ,495,495,495
BEGIN DESCRIPTION:
Mapping XS 36117e67
END DESCRIPTION:
XS GIS Cut Line= 3
      1500567.45      6819634.44      1501093.53      6819785.49
      1502090.51      6819933.87
#Sta/Elev= 30
    4445  1997.9  4477.4 1993.61  4511.2 1985.44  4516.4 1981.39  4525.7 1979.79
  4544.9 1979.58  4583.8 1969.07  4656.5 1964.56  4690.2 1963.61  4695.4 1965.18
  4738.9 1961.71  4765.9 1961.05  4840.7 1959.38  4889.8 1960.46  4908.1 1957.59
  4967.4 1958.27  4980.8 1957.24  4984.5 1955.31    4985 1954.81  4996.6 1955.31
  5003.9 1958.63  5024.2 1961.33    5343  1963.5  5561.6 1963.81  5731.9 1967.05
  5772.3 1968.87  5782.4 1969.75    5789 1971.99  5812.7 1969.93  6000.3 1976.62
#Mann= 8 ,-1 , 0
    4445     .07       0  4738.9     .16       0  4765.9     .07       0
  4967.4     .16       0  4984.5     .07       0  4996.6     .16       0
    5343     .07       0  5561.6    .035       0
Bank Sta=4984.5,4996.6
XS Rating Curve= 0 ,0
Exp/Cntr=0.3,0.1

Type RM Length L Ch R = 1 ,30322   ,366,366,366
BEGIN DESCRIPTION:
Mapping XS c66acfd7
END DESCRIPTION:
XS GIS Cut Line= 3
      1500416.41      6820056.32      1501218.53      6820215.18
       1502025.8      6820381.84
#Sta/Elev= 30
  4195.5 1987.75  4229.8  1978.4  4265.4 1973.07  4357.2 1964.78  4510.1 1959.96
  4530.5 1960.72  4550.9 1959.04  4647.1 1957.54  4747.1  1956.5  4787.2 1954.51
  4787.7 1954.01  4799.3 1954.51  4826.1 1956.47  4845.3  1956.1  4895.7 1956.16
  4907.7 1957.26  4968.8 1956.43    4979 1955.15  5008.9 1956.53  5111.7 1956.04
  5234.2 1957.51  5299.9 1959.91  5326.1 1962.82  5509.9  1969.3  5641.5 1972.26
  5703.9 1972.37  5792.2 1975.76    5806 1973.83  5816.3 1975.61  5837.5 1975.46
#Mann= 6 ,-1 , 0
  4195.5     .07       0  4647.1     .16       0  4787.2    .035       0
  4799.3     .16       0  4845.3     .07       0    4979    .035       0
Bank Sta=4787.2,4799.3
XS Rating Curve= 0 ,0
Exp/Cntr=0.3,0.1

Type RM Length L Ch R = 1 ,29956   ,678,678,678
BEGIN DESCRIPTION:
Mapping XS 9e3f61ad
END DESCRIPTION:
XS GIS Cut Line= 3
      1500460.68      6820355.79      1501054.46      6820519.87
      1501911.96      6820509.47
#Sta/Elev= 30
  4383.7 1989.85  4412.4 1988.92  4446.8 1982.88    4452 1983.49  4520.6 1968.12
  4533.4 1966.72  4543.8 1968.72  4574.9 1961.77  4594.5 1961.18  4599.7 1964.56
  4616.4 1960.34    4634 1958.71  4639.2    1960  4689.1 1953.64  4737.1  1952.2
  4780.6 1951.35  4781.1 1950.85  4793.2 1951.35  4803.2 1954.53    4855 1953.17
  4979.5 1955.63  5002.5 1953.87  5010.3 1955.69  5020.1 1955.57  5090.3 1953.45
  5130.2 1955.03  5155.3 1955.62  5390.3 1960.53  5565.8 1968.77  5857.3  1972.6
#Mann= 7 ,-1 , 0
  4383.7     .07       0  4737.1     .16       0  4780.6     .07       0
  4793.2     .16       0  5020.1    .035       0  5130.2     .07       0
  5155.3    .035       0
Bank Sta=4780.6,4793.2
XS Rating Curve= 0 ,0
Exp/Cntr=0.3,0.1

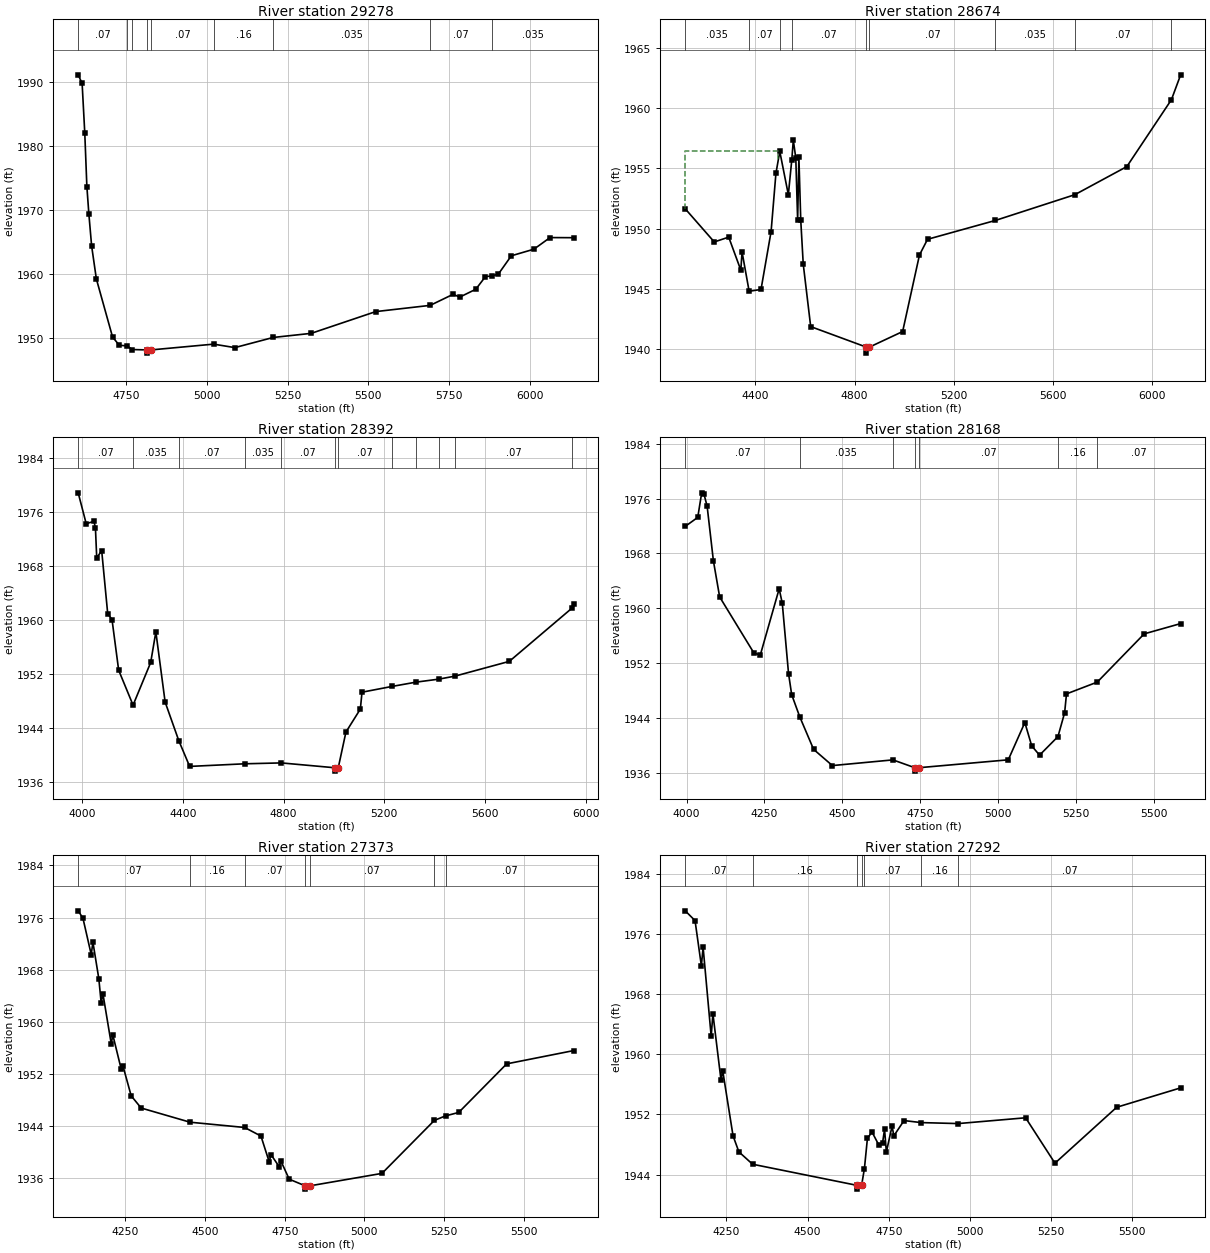
Type RM Length L Ch R = 1 ,29278   ,604,604,604
BEGIN DESCRIPTION:
Mapping XS f7c3c504
END DESCRIPTION:
XS GIS Cut Line= 3
      1500444.05      6820541.45      1500829.49      6821072.74
      1501707.99      6821065.79
#Sta/Elev= 30
  4600.9 1991.05  4613.1 1989.71  4621.3 1981.99  4627.8 1973.65    4634 1969.36
  4642.5 1964.41  4657.2 1959.26  4707.4 1950.21  4728.3 1948.92  4752.4 1948.83
  4768.2 1948.26    4814  1948.2  4814.5  1947.7  4826.6  1948.2  5020.5  1949.1
  5086.2 1948.56    5205 1950.14  5322.8 1950.78  5522.8 1954.17  5691.5 1955.14
  5762.8 1956.87  5782.8 1956.42  5832.8 1957.65  5862.8 1959.63    5882 1959.71
  5902.8 1960.02  5942.8 1962.86  6012.8 1963.89  6062.8  1965.7  6135.8 1965.68
#Mann= 9 ,-1 , 0
  4600.9     .07       0  4752.4     .16       0  4768.2     .07       0
    4814     .07       0  4826.6     .07       0  5020.5     .16       0
    5205    .035       0  5691.5     .07       0    5882    .035       0
Bank Sta=4814,4826.6
XS Rating Curve= 0 ,0
Exp/Cntr=0.3,0.1

Type RM Length L Ch R = 1 ,28674   ,282,282,282
BEGIN DESCRIPTION:
Mapping XS e6fca603
END DESCRIPTION:
XS GIS Cut Line= 3
      1499480.02        6821213.      1500360.53      6821290.42
      1501470.95      6821163.12
#Sta/Elev= 30
  4116.1 1951.64  4233.4 1948.89  4291.8 1949.29  4340.7 1946.55  4345.7 1948.06
  4374.3  1944.8  4422.3 1944.95    4463 1949.75  4482.5 1954.57  4498.1  1956.4
  4532.7 1952.81  4546.7 1955.72  4552.8 1957.33  4562.8 1955.85  4570.3 1950.69
  4575.3 1955.92  4582.9 1950.67  4592.9 1947.05    4623 1941.87  4847.6 1940.17
  4848.1 1939.67  4860.3 1940.17  4994.5 1941.46  5062.5 1947.81  5095.1 1949.11
  5368.6 1950.67  5690.2 1952.81  5900.3 1955.14  6080.5 1960.69  6117.7 1962.75
#Mann= 9 ,-1 , 0
  4116.1    .035       0  4374.3     .07       0  4498.1    .035       0
  4546.7     .07       0  4847.6     .07       0  4860.3     .07       0
  5368.6    .035       0  5690.2     .07       0  6080.5    .035       0
#XS Ineff= 2 , 0
       0  4492.5 1956.46               0
Permanent Ineff=
       F       F
Bank Sta=4847.6,4860.3
XS Rating Curve= 0 ,0
Exp/Cntr=0.3,0.1

Type RM Length L Ch R = 1 ,28392   ,224,224,224
BEGIN DESCRIPTION:
MULBERRY CREEK TRIBUTARY 18 21.0
END DESCRIPTION:
XS GIS Cut Line= 3
      1499533.91      6821728.01      1500525.09        6821508.
      1501430.02      6821212.99
#Sta/Elev= 30
  3984.7 1978.88  4016.5  1974.3  4047.3 1974.64  4053.2 1973.67  4058.3 1969.22
    4078 1970.29  4101.9 1960.94    4119 1960.06  4145.4 1952.54  4202.6 1947.35
  4272.6 1953.69  4293.1 1958.23  4329.9 1947.81    4384 1942.09  4427.3 1938.25
  4646.7 1938.64  4791.3 1938.77  5003.6 1938.05  5004.1 1937.55  5017.3 1938.05
  5047.8 1943.35  5105.1 1946.77  5111.6 1949.27    5231 1950.13    5327 1950.77
  5416.4 1951.21  5480.9 1951.66  5696.5 1953.85  5945.8 1961.77  5951.8 1962.38
#Mann= 12 ,-1 , 0
  3984.7     .07       0  4202.6    .035       0    4384     .07       0
  4646.7    .035       0  4791.3     .07       0  5003.6     .07       0
  5017.3     .07       0    5231    .035       0    5327     .07       0
  5416.4    .035       0  5480.9     .07       0  5945.8    .035       0
Bank Sta=5003.6,5017.3
XS Rating Curve= 0 ,0
Exp/Cntr=0.3,0.1

Type RM Length L Ch R = 1 ,28168   ,795,795,795
BEGIN DESCRIPTION:
MULBERRY CREEK TRIBUTARY 18 20.0
END DESCRIPTION:
XS GIS Cut Line= 3
        1499555.        6821788.        1500555.        6821688.
      1501104.98      6821887.99
#Sta/Elev= 30
  3995.8 1971.93    4036 1973.25  4048.6 1976.83  4056.1 1976.62  4066.1 1974.88
  4086.2 1966.91  4106.3 1961.64  4216.9 1953.41    4237  1953.2  4297.3 1962.82
  4307.3 1960.72  4327.4 1950.46  4337.5 1947.38  4363.2 1944.17  4407.8  1939.4
  4468.1 1937.03  4662.5 1937.86  4732.6 1936.72  4733.1 1936.22  4746.3 1936.72
  5032.7 1937.87  5085.9 1943.31  5107.9 1939.91  5133.1 1938.55  5192.2 1941.26
  5213.6 1944.74  5219.6 1947.49  5318.3 1949.21    5469 1956.25    5586 1957.75
#Mann= 7 ,-1 , 0
  3995.8     .07       0  4363.2    .035       0  4662.5     .07       0
  4732.6     .07       0  4746.3     .07       0  5192.2     .16       0
  5318.3     .07       0
Bank Sta=4732.6,4746.3
XS Rating Curve= 0 ,0
Exp/Cntr=0.3,0.1

Type RM Length L Ch R = 1 ,27373   ,81,81,81
BEGIN DESCRIPTION:
Mapping XS 84e2da55
END DESCRIPTION:
XS GIS Cut Line= 3
      1499553.81      6822078.89      1500277.77      6822326.29
      1501064.23      6822388.79
#Sta/Elev= 30
  4102.2 1977.03  4117.1  1975.9  4143.1 1970.31  4148.4 1972.21  4166.9  1966.6
  4174.4 1962.84  4179.7 1964.31  4205.8 1956.61    4211 1957.92  4237.1 1952.69
  4242.4 1953.22  4268.4 1948.59  4299.7 1946.71    4453 1944.53  4624.2 1943.72
  4675.5  1942.4  4701.5 1938.41  4706.8 1939.56  4732.8 1937.68  4738.1 1938.56
  4764.1 1935.77  4814.6 1934.74  4815.1 1934.24  4828.4 1934.74  5055.1 1936.66
  5219.5 1944.81  5254.4  1945.5  5295.8 1946.03  5446.3  1953.5  5656.2 1955.54
#Mann= 7 ,-1 , 0
  4102.2     .07       0    4453     .16       0  4624.2     .07       0
  4814.6     .07       0  4828.4     .07       0  5219.5     .16       0
  5254.4     .07       0
Bank Sta=4814.6,4828.4
XS Rating Curve= 0 ,0
Exp/Cntr=0.3,0.1

Type RM Length L Ch R = 1 ,27292   ,54,54,54
BEGIN DESCRIPTION:
Mapping XS c41d0a88
END DESCRIPTION:
XS GIS Cut Line= 5
      1499577.27      6822144.01      1500121.52      6822349.73
       1500230.9      6822399.21      1500634.54      6822440.87
      1501051.86      6822438.28
#Sta/Elev= 30
  4123.5 1979.09  4153.7 1977.79  4173.2 1971.77  4178.5 1974.25  4203.4  1962.4
  4208.7  1965.4  4233.6 1956.59  4238.9 1957.82  4270.7 1949.16  4288.6 1947.03
  4330.9 1945.38  4652.6 1942.57  4653.1 1942.07  4666.4 1942.57  4675.1 1944.81
  4684.3 1948.81  4698.4 1949.67  4720.1 1947.88  4731.1 1948.27  4737.1 1950.03
  4742.6    1947  4760.2 1950.45  4765.7 1949.16    4797 1951.19  4849.9 1950.92
  4963.7 1950.79  5171.3 1951.56  5261.6 1945.52  5451.6 1952.96  5648.5 1955.54
#Mann= 7 ,-1 , 0
  4123.5     .07       0  4330.9     .16       0  4652.6     .07       0
  4666.4     .16       0  4675.1     .07       0  4849.9     .16       0
  4963.7     .07       0
Bank Sta=4652.6,4666.4
XS Rating Curve= 0 ,0
Exp/Cntr=0.3,0.1

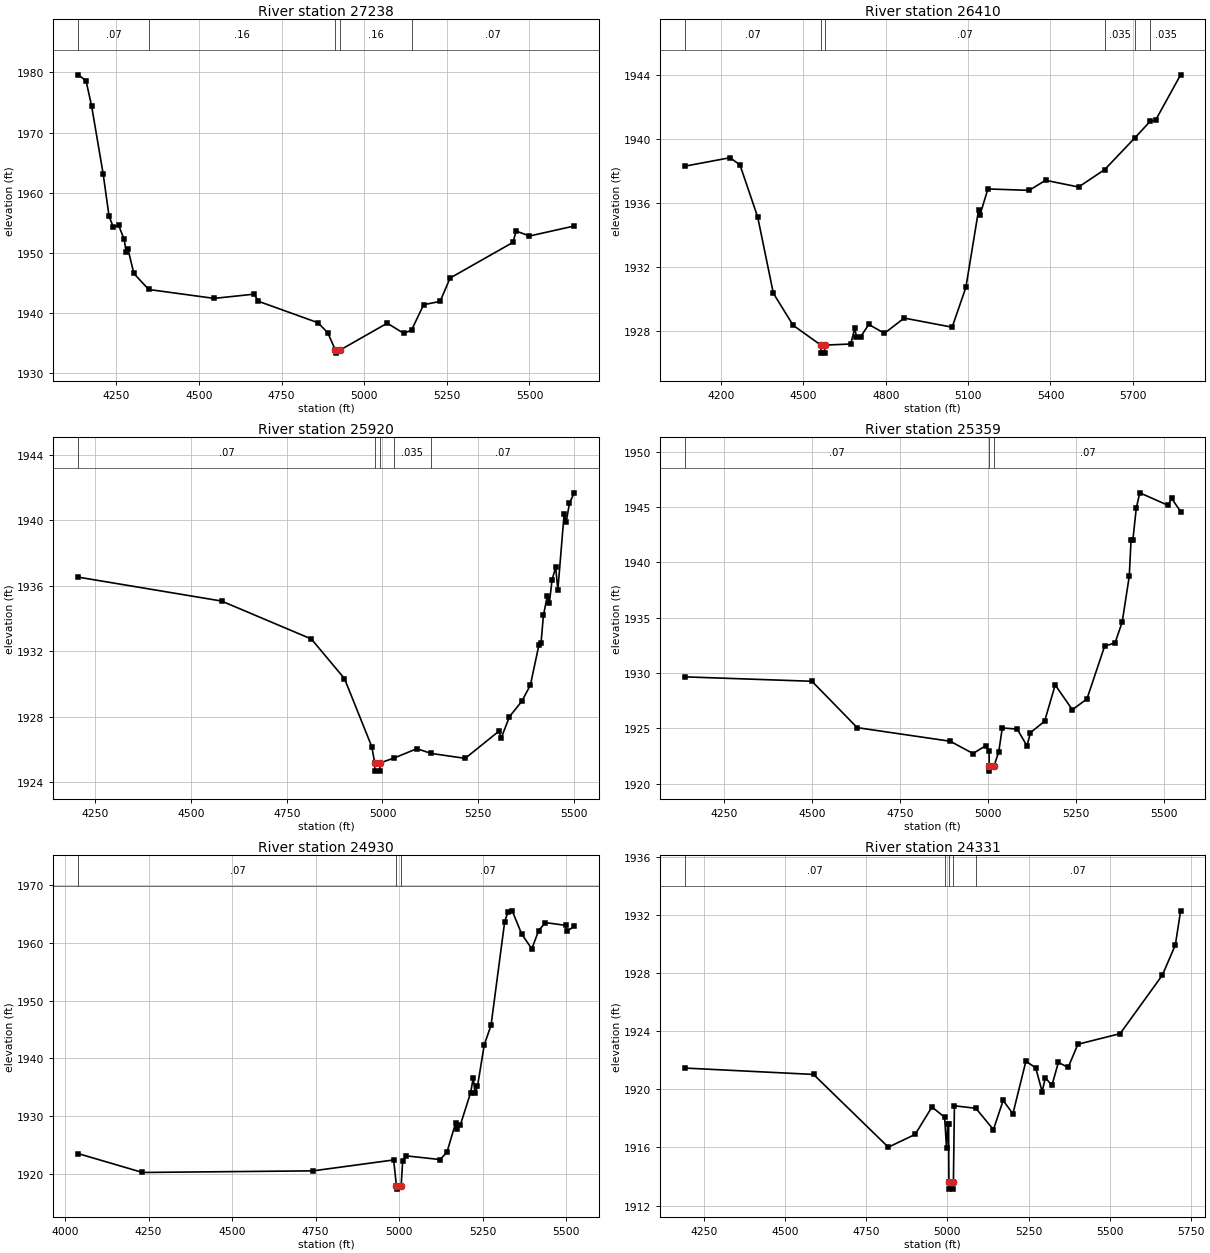
Type RM Length L Ch R = 1 ,27238   ,828,828,828
BEGIN DESCRIPTION:
Mapping XS 14a035f4
END DESCRIPTION:
XS GIS Cut Line= 3
      1499598.11      6822193.49      1500210.06      6822466.92
       1501040.4      6822485.14
#Sta/Elev= 30
  4134.4  1979.6    4158 1978.62  4174.8 1974.46  4209.9 1963.13  4227.7  1956.1
  4240.5 1954.29  4256.4 1954.61  4273.4 1952.26  4279.6 1950.14    4285 1950.62
  4302.8 1946.57  4347.7 1943.91  4545.8 1942.43  4667.3 1943.14  4678.6 1941.97
  4859.6 1938.39  4889.6 1936.72  4912.7 1933.83  4913.2 1933.33  4926.5 1933.83
  5069.7 1938.31  5119.7 1936.61  5143.2 1937.17  5179.7 1941.38  5229.7 1941.93
  5259.7 1945.81  5449.8 1951.74  5459.8 1953.63  5499.8  1952.8  5635.2 1954.46
#Mann= 5 ,-1 , 0
  4134.4     .07       0  4347.7     .16       0  4912.7     .07       0
  4926.5     .16       0  5143.2     .07       0
Bank Sta=4912.7,4926.5
XS Rating Curve= 0 ,0
Exp/Cntr=0.3,0.1

Type RM Length L Ch R = 1 ,26410   ,490,490,490
BEGIN DESCRIPTION:
Mapping XS d93f9bdf
END DESCRIPTION:
XS GIS Cut Line= 3
      1499607.87      6822645.26      1500373.49      6823160.88
      1501256.29      6823114.01
#Sta/Elev= 30
  4067.1 1938.29  4232.4 1938.82  4268.6 1938.37  4333.2 1935.11  4390.2 1930.35
  4462.2 1928.35  4563.3 1927.11  4563.8 1926.61  4576.6 1926.61  4577.1 1927.11
  4672.1 1927.18  4687.1 1928.17  4693.1  1927.6  4708.1 1927.63    4738  1928.4
    4795 1927.85    4867  1928.8  5041.7 1928.23  5091.8 1930.72  5137.9 1935.54
  5142.9 1935.23  5171.9 1936.87  5322.1 1936.78  5382.2 1937.41  5502.4 1936.99
  5597.7 1938.08  5708.5 1940.08  5763.6  1941.1  5782.8 1941.16  5874.2    1944
#Mann= 6 ,-1 , 0
  4067.1     .07       0  4563.3     .07       0  4577.1     .07       0
  5597.7    .035       0  5708.5     .07       0  5763.6    .035       0
Bank Sta=4563.3,4577.1
XS Rating Curve= 0 ,0
Exp/Cntr=0.3,0.1

Type RM Length L Ch R = 1 ,25920   ,561,561,561
BEGIN DESCRIPTION:
Mapping XS 15fa0d28
END DESCRIPTION:
XS GIS Cut Line= 3
       1499553.2      6822824.97      1500040.16      6823462.97
      1500475.98      6823693.85
#Sta/Elev= 30
    4205 1936.53  4579.4 1935.07  4814.2 1932.75  4900.7 1930.33  4972.1 1926.17
  4979.7 1925.18  4980.2 1924.68  4993.1 1924.68  4993.6 1925.18    5029 1925.47
  5089.9 1926.05  5127.3 1925.76  5216.2 1925.46  5304.2 1927.12  5309.9 1926.68
  5331.8 1928.01  5363.9 1928.94  5386.5 1929.94  5408.5 1932.36  5414.2  1932.5
  5420.5 1934.19  5430.5 1935.36  5436.2 1934.98  5443.1 1936.36  5452.5 1937.14
  5458.2 1935.74  5474.5 1940.36  5480.2 1939.92  5488.4 1941.03  5500.8 1941.68
#Mann= 5 ,-1 , 0
    4205     .07       0  4979.7     .07       0  4993.6     .07       0
    5029    .035       0  5127.3     .07       0
Bank Sta=4979.7,4993.6
XS Rating Curve= 0 ,0
Exp/Cntr=0.3,0.1

Type RM Length L Ch R = 1 ,25359   ,429,429,429
BEGIN DESCRIPTION:
Mapping XS 40778e8f
END DESCRIPTION:
XS GIS Cut Line= 3
      1499209.88       6823398.1       1499904.7       6823908.1
      1500450.67      6823941.63
#Sta/Elev= 30
  4138.1 1929.66  4499.6 1929.26  4628.2 1925.07  4892.5 1923.84  4957.3 1922.73
  4992.8 1923.43  5002.7 1922.96  5003.4 1921.64  5003.9 1921.14  5017.3 1921.64
  5030.4  1922.9  5040.4 1925.04  5082.7 1924.94  5110.5 1923.42  5120.5 1924.62
  5160.6 1925.65  5190.7 1928.93  5239.4 1926.69  5280.8 1927.66  5330.9 1932.41
    5361 1932.75    5381 1934.61  5401.1 1938.75  5406.2 1942.05  5411.2 1941.99
  5421.1 1944.92  5431.1 1946.29  5511.3 1945.16  5521.3 1945.79    5547  1944.6
#Mann= 3 ,-1 , 0
  4138.1     .07       0  5003.4     .07       0  5017.3     .07       0
Bank Sta=5003.4,5017.3
XS Rating Curve= 0 ,0
Exp/Cntr=0.3,0.1

Type RM Length L Ch R = 1 ,24930   ,599,599,599
BEGIN DESCRIPTION:
Mapping XS 82f0522d
END DESCRIPTION:
XS GIS Cut Line= 3
      1498929.99        6824013.      1499838.33      6824269.61
      1500369.62      6824366.84
#Sta/Elev= 30
  4039.6 1923.46  4231.9 1920.19  4742.4 1920.47  4983.5 1922.36  4991.9  1917.8
  4992.4  1917.3  5005.8  1917.8  5010.6 1922.24  5020.8 1923.07  5122.4 1922.43
  5142.8 1923.68  5168.6  1928.7  5173.7 1927.74  5183.4 1928.48  5213.9 1934.05
  5221.8 1936.62  5226.9 1933.92  5234.3 1935.11  5254.6 1942.34  5274.9 1945.71
  5315.6 1963.62  5325.8 1965.45  5338.3 1965.57  5366.4 1961.57  5396.9 1958.97
  5417.2 1962.13  5437.6 1963.53  5497.9 1963.05    5503 1962.08  5523.6 1962.87
#Mann= 3 ,-1 , 0
  4039.6     .07       0  4991.9     .07       0  5005.8     .07       0
Bank Sta=4991.9,5005.8
XS Rating Curve= 0 ,0
Exp/Cntr=0.3,0.1

Type RM Length L Ch R = 1 ,24331   ,348,348,348
BEGIN DESCRIPTION:
Mapping XS ed01d5ca
END DESCRIPTION:
XS GIS Cut Line= 3
      1499080.02      6824463.01      1499807.08      6824825.16
      1500521.21       6824821.7
#Sta/Elev= 30
  4191.3 1921.47  4587.9 1921.03  4818.1 1916.02  4900.7  1916.9  4952.4 1918.79
  4991.4 1918.08  4997.2 1915.96  5001.1 1917.62  5003.6 1917.62  5004.5 1913.63
    5005 1913.13  5017.9 1913.13  5018.4 1913.63  5021.5 1918.87  5087.5  1918.7
  5141.5 1917.23  5171.5 1919.24  5201.5 1918.32  5241.5 1921.94  5271.5 1921.49
  5291.5 1919.85  5301.5 1920.81  5321.5 1920.27  5341.5 1921.86  5371.5 1921.51
  5401.5 1923.11  5531.5 1923.84  5661.5 1927.87  5701.5 1929.95  5717.7  1932.3
#Mann= 5 ,-1 , 0
  4191.3     .07       0  4991.4     .16       0  5004.5     .07       0
  5018.4     .16       0  5087.5     .07       0
Bank Sta=5004.5,5018.4
XS Rating Curve= 0 ,0
Exp/Cntr=0.3,0.1

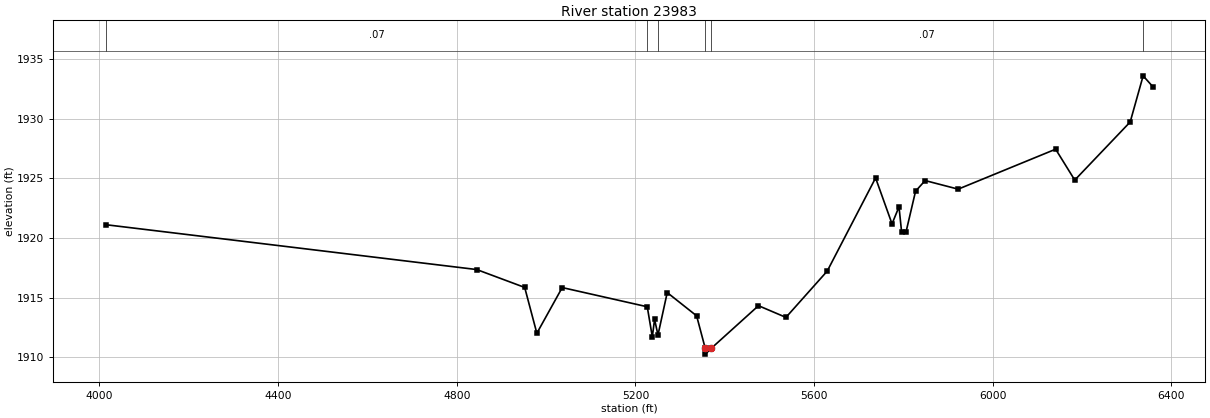
Type RM Length L Ch R = 1 ,23983   ,196,196,196
BEGIN DESCRIPTION:
Mapping XS dbdb07db
END DESCRIPTION:
XS GIS Cut Line= 4
      1499030.01      6824525.85      1499807.08      6825144.61
      1500504.31      6825292.92      1500830.58      6824744.02
#Sta/Elev= 30
  4014.1 1921.12  4844.6 1917.36    4952 1915.86  4979.2 1912.02    5036 1915.85
  5226.4 1914.24  5237.7 1911.72  5242.8 1913.18  5250.4 1911.87  5271.1 1915.43
  5336.9 1913.48  5356.1 1910.77  5356.6 1910.27  5370.1 1910.77  5475.4 1914.33
  5536.9 1913.35  5629.3 1917.23  5737.6 1925.04  5774.4 1921.19    5790 1922.62
  5795.8 1920.53  5805.6 1920.49  5827.1 1923.93  5848.5 1924.82  5922.5  1924.1
  6140.7 1927.45  6183.5 1924.86  6307.6 1929.73  6336.6  1933.6  6358.8 1932.67
#Mann= 6 ,-1 , 0
  4014.1     .07       0  5226.4     .16       0  5250.4     .07       0
  5356.1     .07       0  5370.1     .07       0  6336.6    .035       0
Bank Sta=5356.1,5370.1
XS Rating Curve= 0 ,0
Exp/Cntr=0.3,0.1