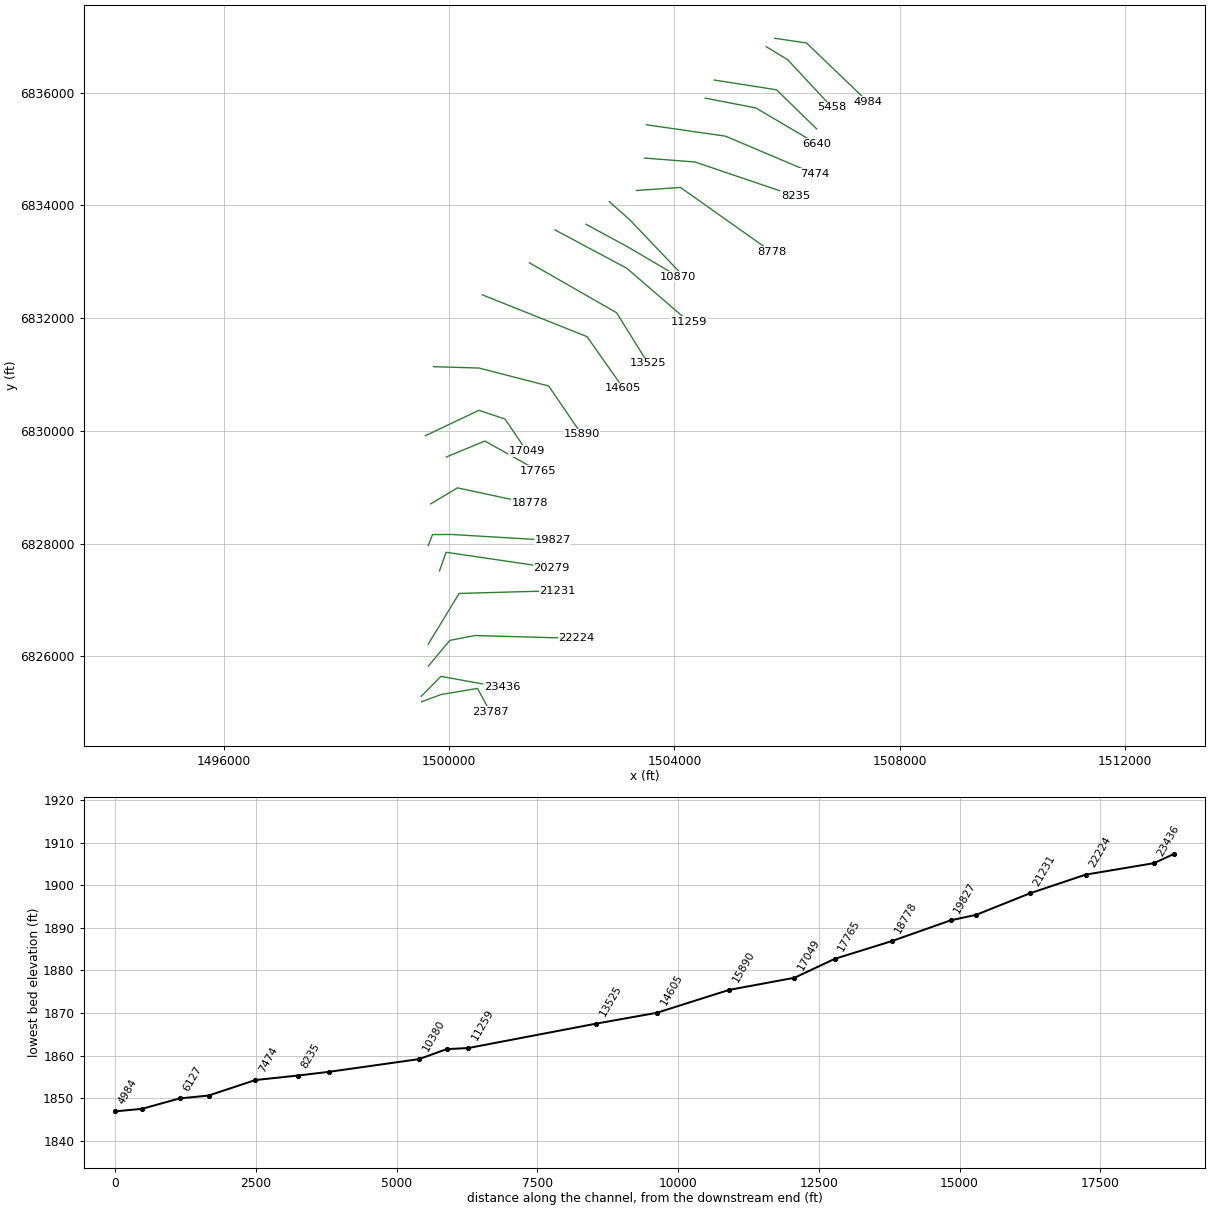
HEC-RAS study MULBERRY CREEK TRIBUTARY 18.prj: MULBERRY CREEK TRIBUTARY 18 Base Level Engineering

--- MULBERRY CREEK TRIBUTARY 18.g01 (geometry) --- (continued)

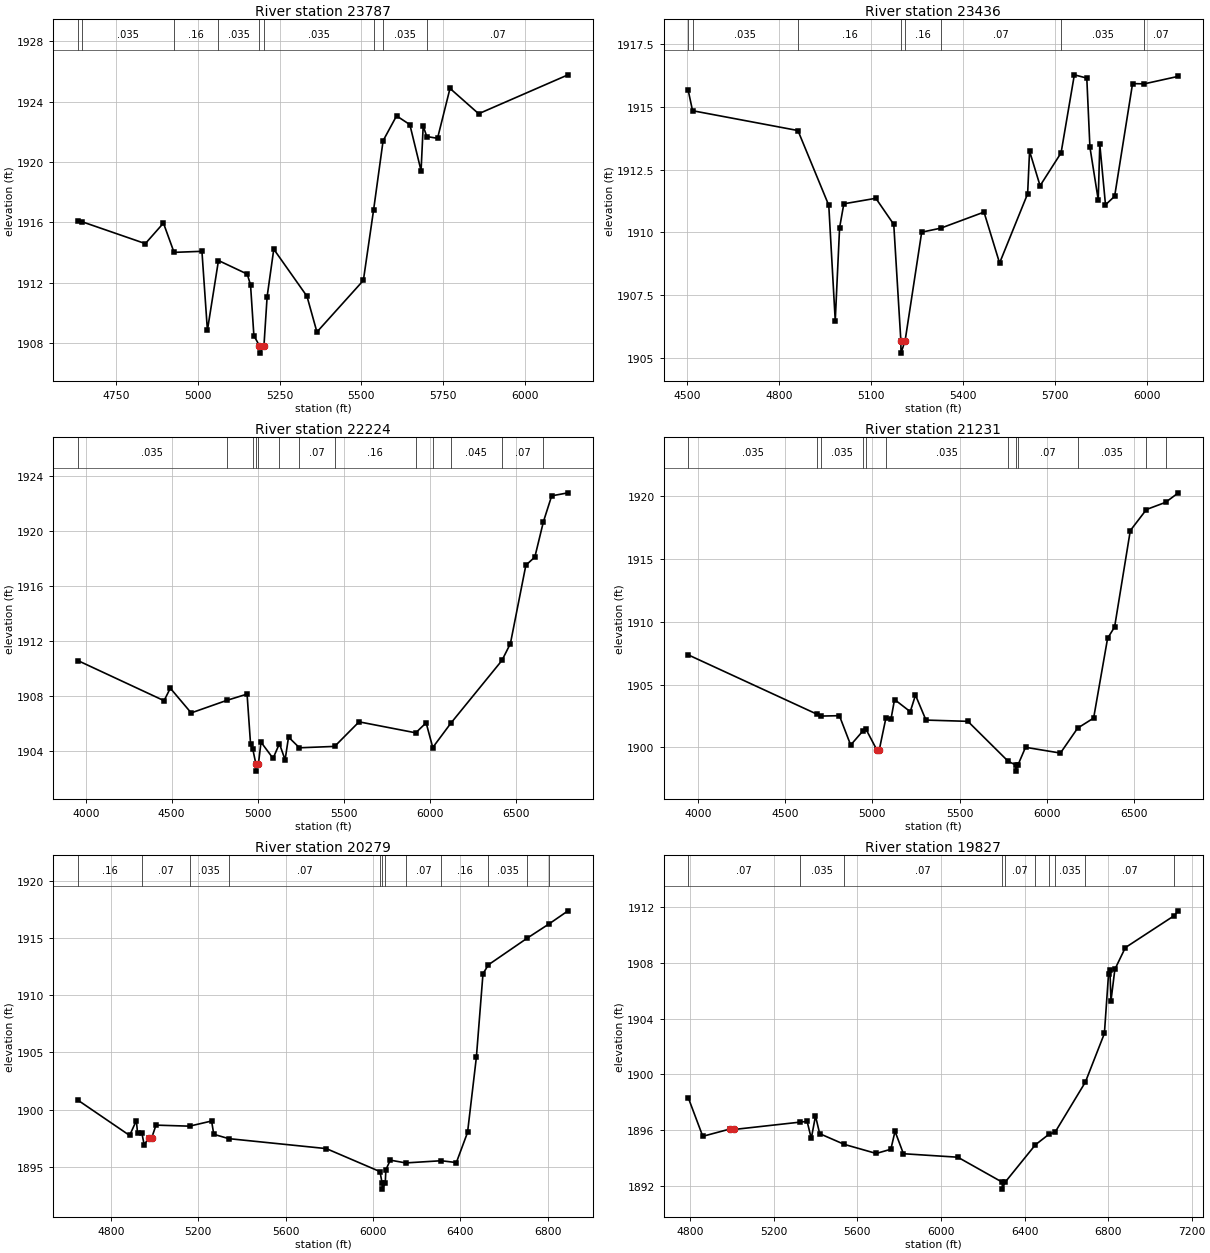
Type RM Length L Ch R = 1 ,23787   ,351,351,351
BEGIN DESCRIPTION:
Mapping XS fffa9001
END DESCRIPTION:
XS GIS Cut Line= 4
       1499513.1      6825192.33      1499859.17      6825321.69
        1500505.      6825429.33      1500729.98      6825013.03
#Sta/Elev= 30
  4634.1  1916.1    4648 1916.03  4840.1 1914.59  4895.4 1915.95  4927.8 1914.01
    5013 1914.08  5029.7 1908.84  5063.5 1913.47  5151.4 1912.57  5161.5 1911.85
  5171.7 1908.49  5188.5 1907.83    5189 1907.33  5202.5 1907.83  5212.2 1911.08
  5232.5 1914.22  5333.9  1911.1  5364.3 1908.73  5506.2 1912.15  5537.5 1916.83
  5566.5 1921.41  5607.6 1923.06  5648.2 1922.48  5682.5 1919.42    5689 1922.39
  5699.8 1921.69  5732.8 1921.57  5770.9 1924.88  5858.4  1923.2  6131.5 1925.78
#Mann= 9 ,-1 , 0
  4634.1     .07       0    4648    .035       0  4927.8     .16       0
  5063.5    .035       0  5188.5     .07       0  5202.5    .035       0
  5537.5     .07       0  5566.5    .035       0  5699.8     .07       0
Bank Sta=5188.5,5202.5
XS Rating Curve= 0 ,0
Exp/Cntr=0.3,0.1

Type RM Length L Ch R = 1 ,23436   ,1212,1212,1212
BEGIN DESCRIPTION:
Mapping XS 70b7271f
END DESCRIPTION:
XS GIS Cut Line= 3
      1499506.02      6825288.66      1499854.91      6825643.04
      1500938.77      6825446.73
#Sta/Elev= 30
  4502.7 1915.66  4516.8 1914.85  4860.6 1914.06  4961.2 1911.08  4982.3 1906.48
  4996.5 1910.19  5010.3 1911.14  5114.7 1911.36  5173.2 1910.32  5196.3 1905.69
  5196.8 1905.19  5210.3 1905.69  5264.3 1910.01  5326.7 1910.17  5467.6 1910.81
  5518.4 1908.78  5609.9 1911.54  5616.2 1913.24  5650.5 1911.86    5719 1913.17
  5762.3 1916.28  5802.9 1916.15  5813.1  1913.4  5840.2  1911.3  5845.3 1913.51
  5863.9  1911.1  5893.7 1911.44  5952.2 1915.93  5990.3 1915.92  6101.5 1916.22
#Mann= 8 ,-1 , 0
  4502.7     .16       0  4516.8    .035       0  4860.6     .16       0
  5196.3     .07       0  5210.3     .16       0  5326.7     .07       0
    5719    .035       0  5990.3     .07       0
Bank Sta=5196.3,5210.3
XS Rating Curve= 0 ,0
Exp/Cntr=0.3,0.1

Type RM Length L Ch R = 1 ,22224   ,993,993,993
BEGIN DESCRIPTION:
Mapping XS f76a980b
END DESCRIPTION:
XS GIS Cut Line= 4
      1499631.88      6825824.77       1500013.8      6826281.69
      1500455.36      6826367.85      1502260.06      6826317.54
#Sta/Elev= 30
  3954.6 1910.55  4455.6 1907.63    4492 1908.54  4613.4 1906.74  4819.7 1907.65
  4938.5 1908.11  4958.9 1904.45  4971.6 1904.11  4990.2    1903  4990.7  1902.5
  5004.3    1903  5019.6 1904.61  5089.7 1903.43  5126.7  1904.5  5159.7 1903.32
  5179.7 1904.98    5243  1904.2  5447.9  1904.3  5589.9 1906.09  5919.5 1905.29
    5980 1906.02  6018.6 1904.22  6124.3    1906  6420.9 1910.56  6470.2 1911.79
  6560.2  1917.5  6612.3 1918.09  6662.3 1920.67  6710.3 1922.55  6805.4 1922.77
#Mann= 13 ,-1 , 0
  3954.6    .035       0  4819.7     .16       0  4971.6     .07       0
  4990.2     .07       0  5004.3     .07       0  5126.7    .035       0
    5243     .07       0  5447.9     .16       0  5919.5     .07       0
  6018.6    .035       0  6124.3    .045       0  6420.9     .07       0
  6662.3    .045       0
Bank Sta=4990.2,5004.3
XS Rating Curve= 0 ,0
Exp/Cntr=0.3,0.1

Type RM Length L Ch R = 1 ,21231   ,952,952,952
BEGIN DESCRIPTION:
Mapping XS 9d42e578
END DESCRIPTION:
XS GIS Cut Line= 3
        1499630.        6826213.      1500178.18      6827114.29
        1501930.        6827163.
#Sta/Elev= 30
  3945.1 1907.37  4682.5 1902.64  4704.8 1902.49  4811.1 1902.52  4875.6 1900.18
  4945.6  1901.3  4964.1 1901.42  5026.8 1899.76 5039.031899.769  5077.2 1902.32
  5106.9 1902.27  5126.9 1903.81  5216.9 1902.84  5246.9 1904.16  5306.9 1902.17
    5547 1902.07  5778.2 1898.88  5820.1  1898.6  5820.6  1898.1  5834.2  1898.6
  5877.2    1900  6077.2 1899.54  6175.9 1901.53  6267.3 1902.33  6347.3 1908.69
  6387.4 1909.59  6477.4 1917.28  6569.8 1918.96  6679.3 1919.53  6752.5 1920.29
#Mann= 12 ,-1 , 0
  3945.1    .035       0  4682.5     .07       0  4704.8    .035       0
  4945.6     .16       0  4964.1     .07       0  5077.2    .035       0
  5778.2     .07       0  5820.1     .07       0  5834.2     .07       0
  6175.9    .035       0  6569.8     .07       0  6679.3    .045       0
Bank Sta=5026.8,5039.03
XS Rating Curve= 0 ,0
Exp/Cntr=0.3,0.1

Type RM Length L Ch R = 1 ,20279   ,452,452,452
BEGIN DESCRIPTION:
Mapping XS f55acb45
END DESCRIPTION:
XS GIS Cut Line= 3
      1499830.01      6827513.03      1499946.99      6827844.38
      1501820.41      6827569.34
#Sta/Elev= 30
  4648.6 1900.83  4885.4 1897.75  4916.3 1899.05  4921.6 1897.98  4941.6 1897.94
  4952.5  1896.9    4972 1897.56 4986.331897.529  5006.3 1898.65  5159.7 1898.56
  5260.8 1899.01  5270.9 1897.85  5339.3 1897.47  5786.3  1896.6  6032.3 1894.59
    6042 1893.56  6042.5 1893.06  6056.2 1893.56  6059.2 1894.76  6079.5 1895.59
  6150.1 1895.35    6313 1895.54    6382 1895.38  6433.2 1898.01  6473.6 1904.56
    6504 1911.88  6529.2 1912.66  6707.1 1914.99  6807.6 1916.24  6893.5 1917.37
#Mann= 12 ,-1 , 0
  4648.6     .16       0  4941.6     .07       0  5159.7    .035       0
  5339.3     .07       0  6032.3     .16       0    6042     .07       0
  6056.2     .16       0  6150.1     .07       0    6313     .16       0
  6529.2    .035       0  6707.1     .07       0  6807.6    .045       0
Bank Sta=4972,4986.33
XS Rating Curve= 0 ,0
Exp/Cntr=0.3,0.1

Type RM Length L Ch R = 1 ,19827   ,1049,1049,1049
BEGIN DESCRIPTION:
Mapping XS bf5287c6
END DESCRIPTION:
XS GIS Cut Line= 4
      1499630.02      6827963.04      1499705.35      6828158.21
      1500045.34      6828160.22      1501838.18      6828053.65
#Sta/Elev= 30
  4790.8 1898.34  4860.4 1895.56  4989.8 1896.08  5009.6 1896.05  5327.4 1896.58
  5359.7 1896.63  5379.7 1895.41  5399.8 1897.02  5419.8 1895.75  5537.7 1894.98
  5690.3 1894.33  5760.4 1894.63  5780.4 1895.92  5820.5 1894.31    6081 1894.06
  6293.2 1892.27  6293.7 1891.77  6307.4 1892.27    6452 1894.95  6518.9 1895.73
  6546.1 1895.85  6691.2 1899.45  6782.2 1902.94  6802.2 1907.24  6808.6 1907.46
  6813.6 1905.27  6832.3 1907.54  6882.4  1909.1    7115 1911.38    7136 1911.74
#Mann= 10 ,-1 , 0
  4790.8     .07       0  5327.4    .035       0  5537.7     .07       0
  6293.2     .07       0  6307.4     .07       0    6452    .035       0
  6518.9     .07       0  6546.1    .035       0  6691.2     .07       0
    7115    .045       0
Bank Sta=4989.8,5009.6
XS Rating Curve= 0 ,0
Exp/Cntr=0.3,0.1

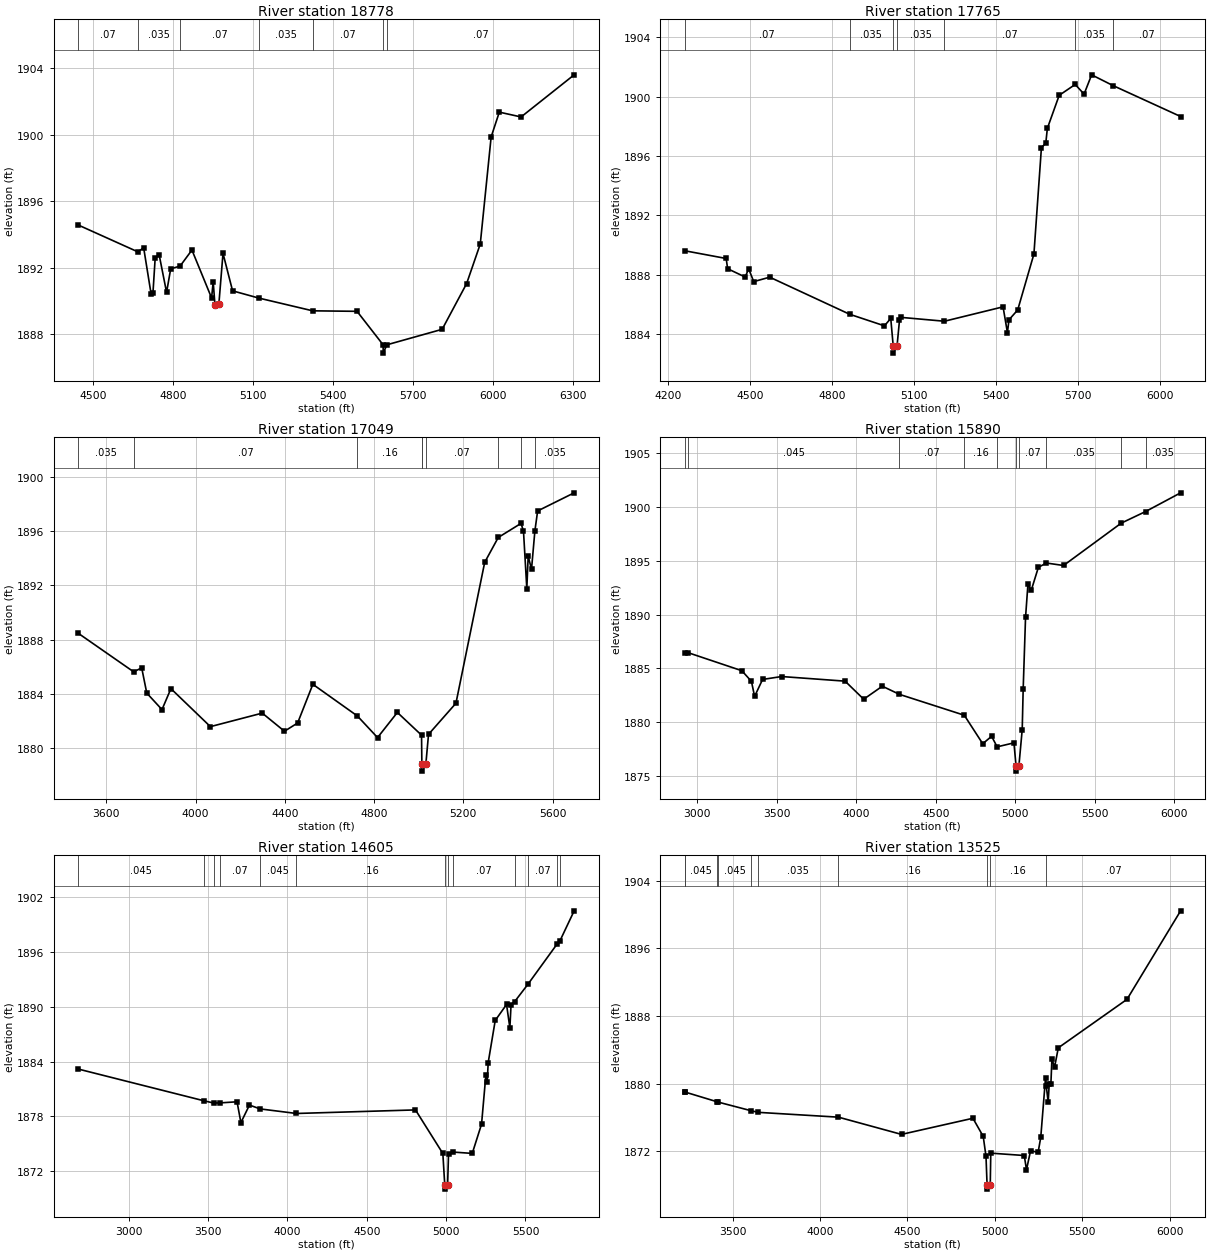
Type RM Length L Ch R = 1 ,18778   ,1013,1013,1013
BEGIN DESCRIPTION:
Mapping XS 421fd419
END DESCRIPTION:
XS GIS Cut Line= 3
      1499674.33      6828703.64      1500148.41      6828986.94
      1501429.98        6828713.
#Sta/Elev= 30
  4443.1 1894.57  4666.9 1892.96  4688.5 1893.21  4716.2 1890.46  4723.5  1890.5
  4731.8 1892.59  4746.8 1892.78  4774.6 1890.53  4790.1 1891.94  4825.6 1892.11
  4869.9 1893.07  4943.8 1890.19  4949.7 1891.17  4956.5 1889.75  4971.1 1889.83
  4986.6 1892.87  5022.6 1890.62  5120.1 1890.19  5323.6 1889.42  5490.2 1889.39
  5588.1 1887.38  5588.6 1886.88  5602.3 1887.38    5810 1888.31    5902 1891.06
  5953.1 1893.43    5994 1899.86  6024.7 1901.35  6106.5 1901.06  6305.9 1903.59
#Mann= 7 ,-1 , 0
  4443.1     .07       0  4666.9    .035       0  4825.6     .07       0
  5120.1    .035       0  5323.6     .07       0  5588.1     .07       0
  5602.3     .07       0
Bank Sta=4956.5,4971.1
XS Rating Curve= 0 ,0
Exp/Cntr=0.3,0.1

Type RM Length L Ch R = 1 ,17765   ,716,716,716
BEGIN DESCRIPTION:
MULBERRY CREEK TRIBUTARY 18 5.0
END DESCRIPTION:
XS GIS Cut Line= 3
       1499950.8      6829534.69      1500634.69      6829818.13
      1501573.71      6829293.58
#Sta/Elev= 30
  4259.7 1889.62  4411.2  1889.1  4416.6 1888.41  4480.7 1887.85  4493.7  1888.4
  4512.1 1887.54  4570.7 1887.84  4863.5 1885.34  4990.8 1884.56    5014 1885.06
  5022.9 1883.22  5023.4 1882.72  5037.1 1883.22    5046 1884.93  5051.7 1885.13
  5210.6 1884.87  5425.3 1885.84  5441.2 1884.11  5447.1 1884.97  5478.9 1885.63
  5538.3  1889.4  5565.8 1896.58  5581.7 1896.86  5587.5 1897.87  5630.9  1900.1
  5689.5 1900.83    5722 1900.18  5749.7 1901.48  5827.5 1900.76  6075.6 1898.67
#Mann= 7 ,-1 , 0
  4259.7     .07       0  4863.5    .035       0  5022.9    .035       0
  5037.1    .035       0  5210.6     .07       0  5689.5    .035       0
  5827.5     .07       0
Bank Sta=5022.9,5037.1
XS Rating Curve= 0 ,0
Exp/Cntr=0.3,0.1

Type RM Length L Ch R = 1 ,17049   ,1159,1159,1159
BEGIN DESCRIPTION:
Mapping XS 4286f913
END DESCRIPTION:
XS GIS Cut Line= 4
      1499579.96      6829912.98        1500530.        6830363.
      1500993.94      6830207.68      1501375.45      6829642.34
#Sta/Elev= 30
  3474.3 1888.46  3722.6 1885.61  3758.3 1885.91  3781.1 1884.04  3849.3 1882.82
  3889.3 1884.37  4066.3 1881.56  4298.7 1882.56  4398.3 1881.22  4457.3 1881.83
  4525.5 1884.69    4725 1882.35  4815.5 1880.75  4904.3 1882.61  5012.7 1880.93
  5014.2 1878.77  5014.7 1878.27  5031.9 1878.77    5044 1880.99  5166.9 1883.29
  5295.8 1893.71  5356.6 1895.55  5458.7 1896.59  5469.7 1896.01  5484.6 1891.77
  5490.7 1894.17  5505.6 1893.19  5520.8 1896.04  5533.1 1897.51  5696.8 1898.85
#Mann= 9 ,-1 , 0
  3474.3    .035       0  3722.6     .07       0    4725     .16       0
  5012.7     .07       0  5014.2     .07       0  5031.9     .07       0
  5356.6    .035       0  5458.7     .07       0  5520.8    .035       0
Bank Sta=5014.2,5031.9
XS Rating Curve= 0 ,0
Exp/Cntr=0.3,0.1

Type RM Length L Ch R = 1 ,15890   ,1285,1285,1285
BEGIN DESCRIPTION:
Mapping XS fe3dc8e3
END DESCRIPTION:
XS GIS Cut Line= 4
      1499726.35      6831136.67        1500530.        6831113.
      1501767.87      6830794.44      1502351.23      6829940.24
#Sta/Elev= 30
  2922.5 1886.45    2945 1886.44  3281.3 1884.77  3341.3 1883.78  3361.3 1882.38
  3411.4 1883.96  3531.4 1884.23  3930.1  1883.8    4047 1882.12    4164 1883.33
    4272 1882.57  4679.2 1880.63  4795.2 1877.98    4851 1878.67  4885.7 1877.69
  4991.4 1878.06  5004.5 1875.93    5005 1875.43  5022.6 1875.93  5043.4  1879.3
  5049.4 1883.04  5064.3 1889.73  5079.3  1892.8  5100.2 1892.25    5145 1894.39
  5195.2 1894.79  5303.1 1894.56  5665.7  1898.5    5819 1899.58  6039.1 1901.32
#Mann= 10 ,-1 , 0
  2922.5     .07       0    2945    .045       0    4272     .07       0
  4679.2     .16       0  4885.7     .07       0  5004.5     .07       0
  5022.6     .07       0  5195.2    .035       0  5665.7     .07       0
    5819    .035       0
Bank Sta=5004.5,5022.6
XS Rating Curve= 0 ,0
Exp/Cntr=0.3,0.1

Type RM Length L Ch R = 1 ,14605   ,1080,1080,1080
BEGIN DESCRIPTION:
Mapping XS d7e48a68
END DESCRIPTION:
XS GIS Cut Line= 3
      1500587.35      6832412.49      1502448.43      6831669.44
      1503094.17       6830752.9
#Sta/Elev= 30
  2681.8 1883.19  3470.9 1879.73  3535.8 1879.47  3576.5 1879.49  3682.2 1879.61
  3706.4 1877.33  3760.3 1879.25  3827.6 1878.83  4056.6 1878.33  4806.8 1878.72
  4979.3 1873.95  4991.1 1870.55  4991.6 1870.05  5009.3 1870.55    5015 1873.85
  5040.8 1874.11  5164.6 1873.96  5223.2 1877.16  5250.2  1882.5  5258.9 1881.75
    5265 1883.89  5309.4 1888.51  5380.8 1890.26  5401.7  1887.7  5409.2 1890.25
  5431.7 1890.57  5514.6 1892.45  5701.1 1896.92  5717.2 1897.22  5806.9 1900.51
#Mann= 13 ,-1 , 0
  2681.8    .045       0  3470.9     .07       0  3535.8    .045       0
  3576.5     .07       0  3827.6    .045       0  4056.6     .16       0
  4991.1     .07       0  5009.3     .16       0  5040.8     .07       0
  5431.7    .035       0  5514.6     .07       0  5701.1    .035       0
  5717.2     .07       0
Bank Sta=4991.1,5009.3
XS Rating Curve= 0 ,0
Exp/Cntr=0.3,0.1

Type RM Length L Ch R = 1 ,13525   ,2266,2266,2266
BEGIN DESCRIPTION:
Mapping XS 8b024b48
END DESCRIPTION:
XS GIS Cut Line= 3
      1501425.84      6832980.22      1502972.73      6832094.79
      1503530.02      6831198.97
#Sta/Elev= 30
  3225.7 1878.97  3229.2 1878.98  3409.4 1877.85  3417.3  1877.8  3605.5 1876.78
  3646.4 1876.59    4105 1876.02  4465.8 1873.98  4874.5 1875.89  4933.5 1873.74
  4949.3 1871.39  4955.5    1868    4956  1867.5  4973.7    1868  4976.7 1871.76
  5168.3 1871.48    5181 1869.79  5204.5 1872.06  5247.4 1871.84  5262.7 1873.63
  5289.9 1880.64  5294.1 1879.74  5305.2  1877.8  5311.1 1879.95  5320.6 1879.93
  5326.5  1882.9  5341.8 1881.95  5363.1 1884.23  5756.2 1889.97  6063.1 1900.45
#Mann= 10 ,-1 , 0
  3225.7     .07       0  3229.2    .045       0  3409.4     .07       0
  3417.3    .045       0  3605.5     .16       0  3646.4    .035       0
    4105     .16       0  4955.5     .07       0  4973.7     .16       0
  5294.1     .07       0
Bank Sta=4955.5,4973.7
XS Rating Curve= 0 ,0
Exp/Cntr=0.3,0.1

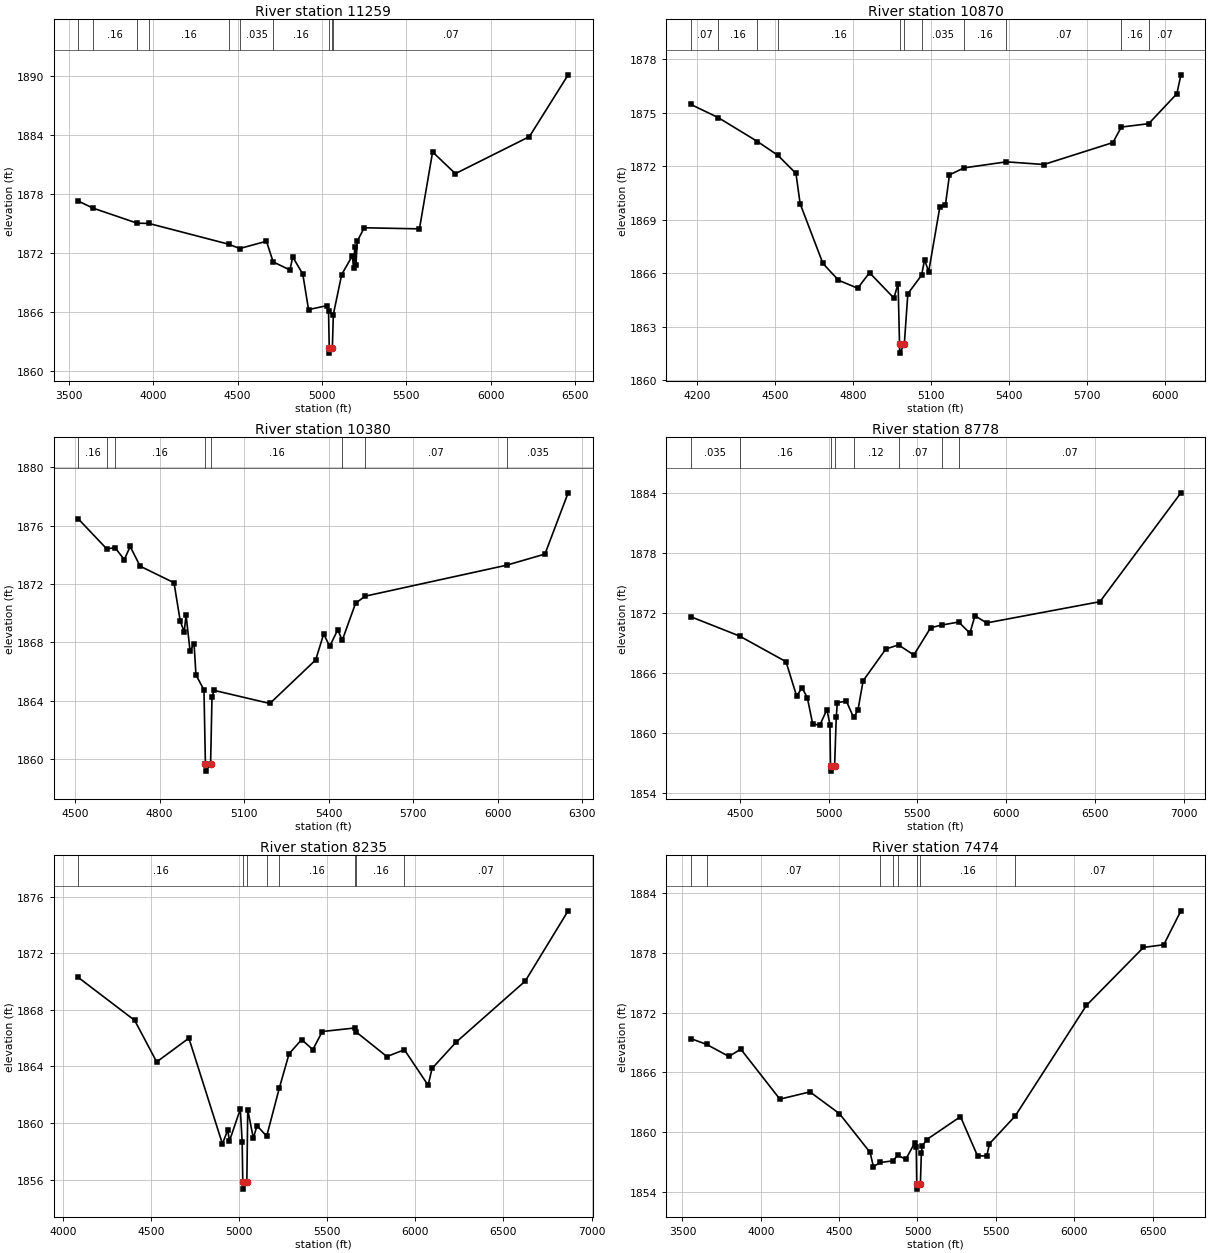
Type RM Length L Ch R = 1 ,11259   ,389,389,389
BEGIN DESCRIPTION:
Mapping XS 3f4eec77
END DESCRIPTION:
XS GIS Cut Line= 3
      1501880.01      6833562.99      1503155.68      6832882.32
      1504260.01      6831929.91
#Sta/Elev= 30
  3554.1 1877.27  3642.9 1876.54  3904.1 1875.01  3974.2 1874.98  4446.1 1872.87
  4512.3 1872.43  4670.5 1873.17  4710.2 1871.07  4809.8 1870.24  4826.1 1871.57
  4885.9 1869.83  4919.9 1866.21  5030.9 1866.62  5038.5 1866.08  5042.7 1862.28
  5043.2 1861.78  5061.1 1862.28  5066.9 1865.71  5116.4 1869.78    5180  1871.7
  5186.6 1870.43  5194.3 1872.62  5200.9 1870.71  5208.6 1873.19  5250.3 1874.54
  5577.2 1874.43  5655.1 1882.26    5790 1880.05  6228.8 1883.82  6458.3 1890.11
#Mann= 10 ,-1 , 0
  3554.1    .035       0  3642.9     .16       0  3904.1     .07       0
  3974.2     .16       0  4446.1     .07       0  4512.3    .035       0
  4710.2     .16       0  5042.7     .07       0  5061.1     .16       0
  5066.9     .07       0
Bank Sta=5042.7,5061.1
XS Rating Curve= 0 ,0
Exp/Cntr=0.3,0.1

Type RM Length L Ch R = 1 ,10870   ,490,490,490
BEGIN DESCRIPTION:
Mapping XS 89d472fd
END DESCRIPTION:
XS GIS Cut Line= 3
        1502430.        6833663.      1503149.46      6833274.48
      1504070.48      6832733.32
#Sta/Elev= 30
  4175.9 1875.46  4281.5 1874.72  4432.4 1873.38  4511.4  1872.6  4580.4 1871.59
  4596.6 1869.89  4684.2 1866.54  4744.1  1865.6    4818 1865.15  4863.5 1866.02
  4957.3  1864.6  4973.5  1865.4    4979 1862.01  4979.5 1861.51  4997.4 1862.01
    5011 1864.84  5063.9 1865.88  5075.4 1866.75  5091.1 1866.07    5134 1869.69
  5155.5  1869.8  5171.2 1871.51  5227.3  1871.9  5389.8 1872.24  5534.4 1872.09
  5800.1 1873.32  5832.4 1874.19  5937.9 1874.38  6046.2 1876.06  6061.8 1877.12
#Mann= 11 ,-1 , 0
  4175.9     .07       0  4281.5     .16       0  4432.4     .07       0
  4511.4     .16       0    4979     .07       0  4997.4     .16       0
  5063.9    .035       0  5227.3     .16       0  5389.8     .07       0
  5832.4     .16       0  5937.9     .07       0
Bank Sta=4979,4997.4
XS Rating Curve= 0 ,0
Exp/Cntr=0.3,0.1

Type RM Length L Ch R = 1 ,10380   ,1602,1602,1602
BEGIN DESCRIPTION:
Mapping XS c0c85a4c
END DESCRIPTION:
XS GIS Cut Line= 3
      1502842.14      6834066.17      1503206.75      6833743.23
      1504070.66      6832837.69
#Sta/Elev= 30
    4511 1876.49    4613 1874.41  4642.1  1874.5  4675.1 1873.68    4696 1874.58
  4731.1 1873.23  4851.5 1872.09  4873.3 1869.48  4887.5 1868.72  4894.2 1869.87
  4908.4 1867.41  4922.6  1867.9  4929.3 1865.77  4957.7 1864.74  4962.8 1859.67
  4963.3 1859.17  4981.2 1859.67  4986.2 1864.26  4993.5 1864.71  5191.5 1863.81
  5354.1  1866.8  5382.4 1868.58  5403.8 1867.73  5432.1 1868.86  5448.4 1868.15
  5495.6 1870.69  5529.5 1871.17  6032.3  1873.3  6167.4 1874.06  6249.6 1878.26
#Mann= 8 ,-1 , 0
    4511     .16       0    4613     .07       0  4642.1     .16       0
  4962.8     .07       0  4981.2     .16       0  5448.4    .035       0
  5529.5     .07       0  6032.3    .035       0
Bank Sta=4962.8,4981.2
XS Rating Curve= 0 ,0
Exp/Cntr=0.3,0.1

Type RM Length L Ch R = 1 ,8778    ,543,543,543
BEGIN DESCRIPTION:
Mapping XS 902f4016
END DESCRIPTION:
XS GIS Cut Line= 3
      1503329.99        6834263.      1504106.49      6834316.87
      1505725.87      6833171.97
#Sta/Elev= 30
  4223.4 1871.64  4497.8 1869.71  4759.7 1867.14  4819.8 1863.69  4849.9 1864.53
    4880 1863.53  4910.1  1860.9  4950.5 1860.79  4990.3 1862.35  5007.3 1860.84
  5010.5 1856.68    5011 1856.18  5033.6 1856.68    5043 1861.63  5049.1 1863.03
  5099.6  1863.2  5140.6 1861.56  5164.8 1862.26  5194.4 1865.23  5322.4 1868.41
  5393.9 1868.82  5479.9 1867.81  5574.8 1870.54  5637.6 1870.81  5732.6 1871.11
    5796    1870  5824.6 1871.74  5889.9 1871.02  6528.8 1873.15    6985 1884.05
#Mann= 8 ,-1 , 0
  4223.4    .035       0  4497.8     .16       0  5010.5     .07       0
  5033.6     .16       0  5140.6     .12       0  5393.9     .07       0
  5637.6     .16       0  5732.6     .07       0
Bank Sta=5010.5,5033.6
XS Rating Curve= 0 ,0
Exp/Cntr=0.3,0.1

Type RM Length L Ch R = 1 ,8235    ,761,761,761
BEGIN DESCRIPTION:
Mapping XS 625a875f
END DESCRIPTION:
XS GIS Cut Line= 3
      1503467.62       6834837.7      1504363.43      6834768.26
      1506148.15       6834164.1
#Sta/Elev= 30
  4084.6 1870.31  4406.1 1867.26    4531 1864.32  4713.9    1866  4904.4 1858.52
  4934.5  1859.5  4944.5 1858.73  5005.9 1860.98  5016.4 1858.68  5019.9 1855.82
  5020.4 1855.32    5043 1855.82  5048.1 1860.94  5079.8 1858.93  5100.9 1859.81
  5155.6 1859.06  5227.4 1862.47  5282.9  1864.9  5354.3  1865.9  5417.6 1865.19
  5471.5 1866.47  5654.5 1866.72  5665.6 1866.42  5838.1  1864.7  5937.7 1865.18
  6072.2 1862.67  6094.8 1863.86  6230.5 1865.71  6623.8 1870.04  6867.3 1875.01
#Mann= 8 ,-1 , 0
  4084.6     .16       0  5019.9     .07       0    5043     .16       0
  5155.6     .12       0  5227.4     .16       0  5654.5     .07       0
  5665.6     .16       0  5937.7     .07       0
Bank Sta=5019.9,5043
XS Rating Curve= 0 ,0
Exp/Cntr=0.3,0.1

Type RM Length L Ch R = 1 ,7474    ,834,834,834
BEGIN DESCRIPTION:
Mapping XS 41d918e5
END DESCRIPTION:
XS GIS Cut Line= 3
      1503502.29      6835427.99       1504905.1      6835226.59
       1506480.7      6834560.26
#Sta/Elev= 30
  3553.3  1869.4  3655.1 1868.81  3796.5  1867.6  3872.1 1868.34  4121.8 1863.31
  4313.7 1864.04  4501.9 1861.85  4697.6 1857.95  4718.6 1856.52  4762.6 1856.94
  4841.3  1857.1    4875 1857.66  4925.2 1857.26  4983.2 1858.93  4992.1 1858.54
  4995.3 1854.76  4995.8 1854.26  5018.5 1854.76  5024.7 1857.94  5030.6  1858.6
  5059.7 1859.25  5274.4 1861.55    5383 1857.61  5442.3 1857.59    5459 1858.82
  5623.4 1861.61  6077.8 1872.73  6442.3 1878.57  6571.7 1878.84  6681.2 1882.25
#Mann= 8 ,-1 , 0
  3553.3     .16       0  3655.1     .07       0  4762.6     .16       0
  4841.3     .07       0    4875     .16       0  4995.3     .07       0
  5018.5     .16       0  5623.4     .07       0
Bank Sta=4995.3,5018.5
XS Rating Curve= 0 ,0
Exp/Cntr=0.3,0.1

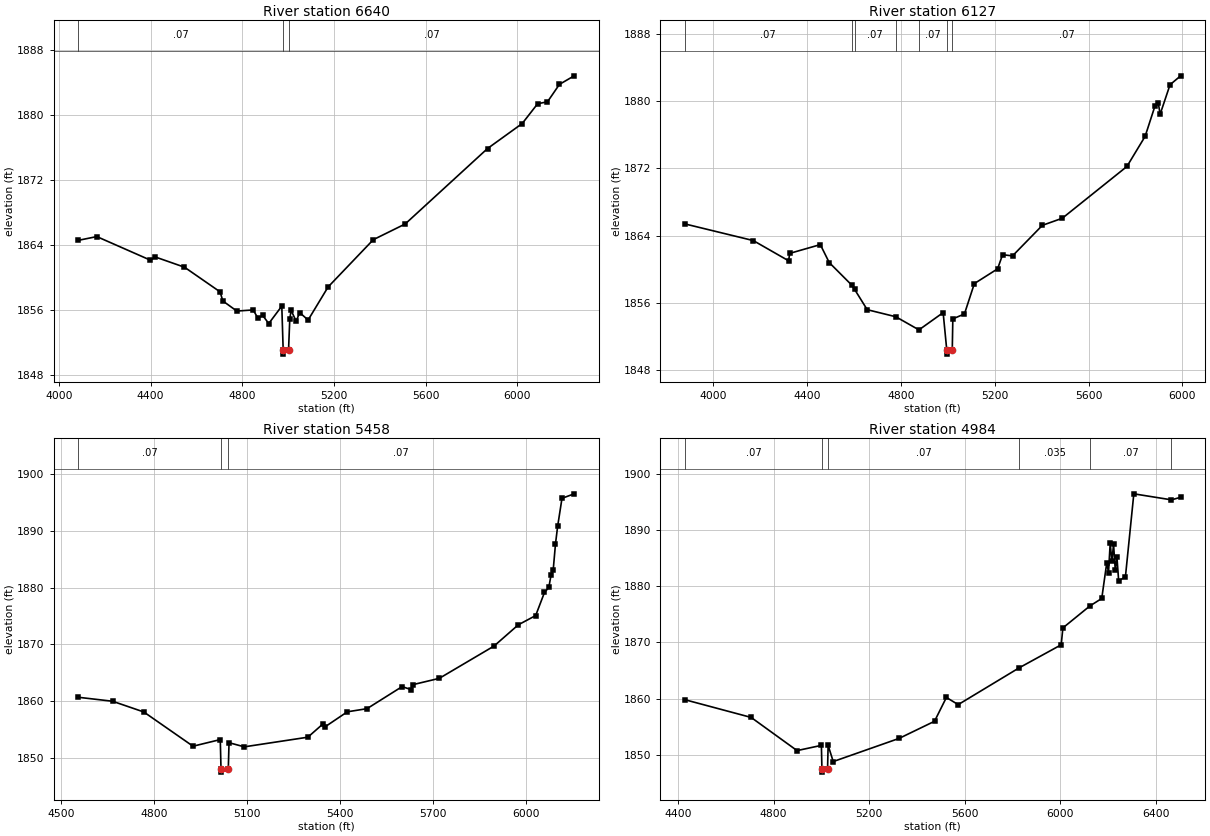
Type RM Length L Ch R = 1 ,6640    ,513,513,513
BEGIN DESCRIPTION:
Mapping XS e426cf8e
END DESCRIPTION:
XS GIS Cut Line= 3
      1504545.87        6835901.       1505444.3      6835727.39
      1506520.33      6835093.92
#Sta/Elev= 30
  4084.7 1864.59  4165.3 1865.05  4399.5 1862.15  4419.9 1862.55  4547.9 1861.29
  4703.3 1858.26  4715.3 1857.14  4776.4  1855.9  4847.7 1856.04  4868.9    1855
  4888.4 1855.39  4915.7 1854.37  4972.6 1856.51  4978.6 1851.11  4979.1 1850.61
    5002 1851.11  5007.4 1854.91  5013.2 1855.99  5035.4 1854.64  5050.3 1855.72
  5087.4  1854.8  5174.6 1858.86  5371.9 1864.67  5511.1  1866.6  5870.4 1875.87
  6021.7 1878.94    6089 1881.37    6132 1881.61  6184.2 1883.75  6248.4  1884.8
#Mann= 3 ,-1 , 0
  4084.7     .07       0  4978.6     .07       0    5002     .07       0
Bank Sta=4978.6,5002
XS Rating Curve= 0 ,0
Exp/Cntr=0.3,0.1

Type RM Length L Ch R = 1 ,6127    ,669,669,669
BEGIN DESCRIPTION:
Mapping XS b87290cb
END DESCRIPTION:
XS GIS Cut Line= 3
      1504706.43      6836222.18      1505813.23      6836048.57
      1506525.05       6835354.1
#Sta/Elev= 30
  3877.7 1865.41  4169.8 1863.43  4320.3 1861.03  4325.4 1861.91  4455.7 1862.95
  4493.7 1860.82  4589.4 1858.15  4602.2 1857.62  4655.7 1855.22  4777.7 1854.38
  4876.4 1852.82  4979.6 1854.87    4995 1850.44  4995.5 1849.94  5018.5 1850.44
  5020.9 1854.13  5070.4 1854.71  5112.7 1858.32  5211.8 1860.07  5233.1 1861.75
  5275.5 1861.61  5402.8 1865.24  5487.7 1866.08  5763.4 1872.23  5841.1 1875.81
  5883.6 1879.46  5897.7 1879.72  5904.9 1878.42  5947.3 1881.94  5992.5    1883
#Mann= 7 ,-1 , 0
  3877.7     .07       0  4589.4    .035       0  4602.2     .07       0
  4777.7    .035       0  4876.4     .07       0    4995     .07       0
  5018.5     .07       0
Bank Sta=4995,5018.5
XS Rating Curve= 0 ,0
Exp/Cntr=0.3,0.1

Type RM Length L Ch R = 1 ,5458    ,474,474,474
BEGIN DESCRIPTION:
Mapping XS ee35e585
END DESCRIPTION:
XS GIS Cut Line= 3
      1505629.97      6836813.02      1506010.65      6836582.37
      1506798.45      6835736.09
#Sta/Elev= 30
  4554.9 1860.69  4665.4 1859.99  4766.3  1858.1  4925.3 1852.06  5013.3 1853.23
  5015.7 1847.99  5016.2 1847.49  5039.2 1847.99  5041.6 1852.68  5090.9 1851.95
  5296.1 1853.65    5346 1856.04  5352.8 1855.52  5423.7 1858.13  5487.2 1858.68
  5600.5 1862.57  5628.9 1862.06  5635.7 1862.92  5720.7 1864.03  5897.6 1869.73
  5975.8 1873.47  6031.9  1875.1  6060.3 1879.17  6074.4 1880.06  6081.8 1882.33
  6088.6 1883.18  6095.9 1887.74  6102.8 1890.82  6116.9 1895.78  6156.2 1896.57
#Mann= 3 ,-1 , 0
  4554.9     .07       0  5015.7     .07       0  5039.2     .07       0
Bank Sta=5015.7,5039.2
XS Rating Curve= 0 ,0
Exp/Cntr=0.3,0.1

Type RM Length L Ch R = 1 ,4984    ,0,0,0
BEGIN DESCRIPTION:
Mapping XS ea1b382c
END DESCRIPTION:
XS GIS Cut Line= 3
      1505780.03        6836963.       1506345.8      6836878.81
      1507431.04      6835836.96
#Sta/Elev= 30
    4428 1859.79    4706 1856.63  4898.1 1850.73    5000 1851.66  5002.3  1847.4
  5002.8  1846.9  5025.8  1847.4  5028.2 1851.67  5049.6 1848.78  5325.4  1852.9
  5473.8 1855.95  5523.5 1860.19  5572.9 1858.91  5828.7 1865.47  6004.3 1869.56
  6011.3 1872.56  6124.2 1876.46  6174.1  1877.8  6195.2 1884.19  6202.4 1882.38
  6209.4  1887.6  6216.6 1884.39  6223.5 1887.44  6230.7 1882.88  6237.7 1885.15
  6244.9 1880.94  6273.2 1881.65  6308.4 1896.42  6465.9 1895.35  6504.4  1895.8
#Mann= 6 ,-1 , 0
    4428     .07       0  5002.3     .07       0  5025.8     .07       0
  5828.7    .035       0  6124.2     .07       0  6465.9    .035       0
Bank Sta=5002.3,5025.8
XS Rating Curve= 0 ,0
Exp/Cntr=0.3,0.1

Chan Stop Cuts=-1
Use User Specified Reach Order=0
Composite Channel Slope=5