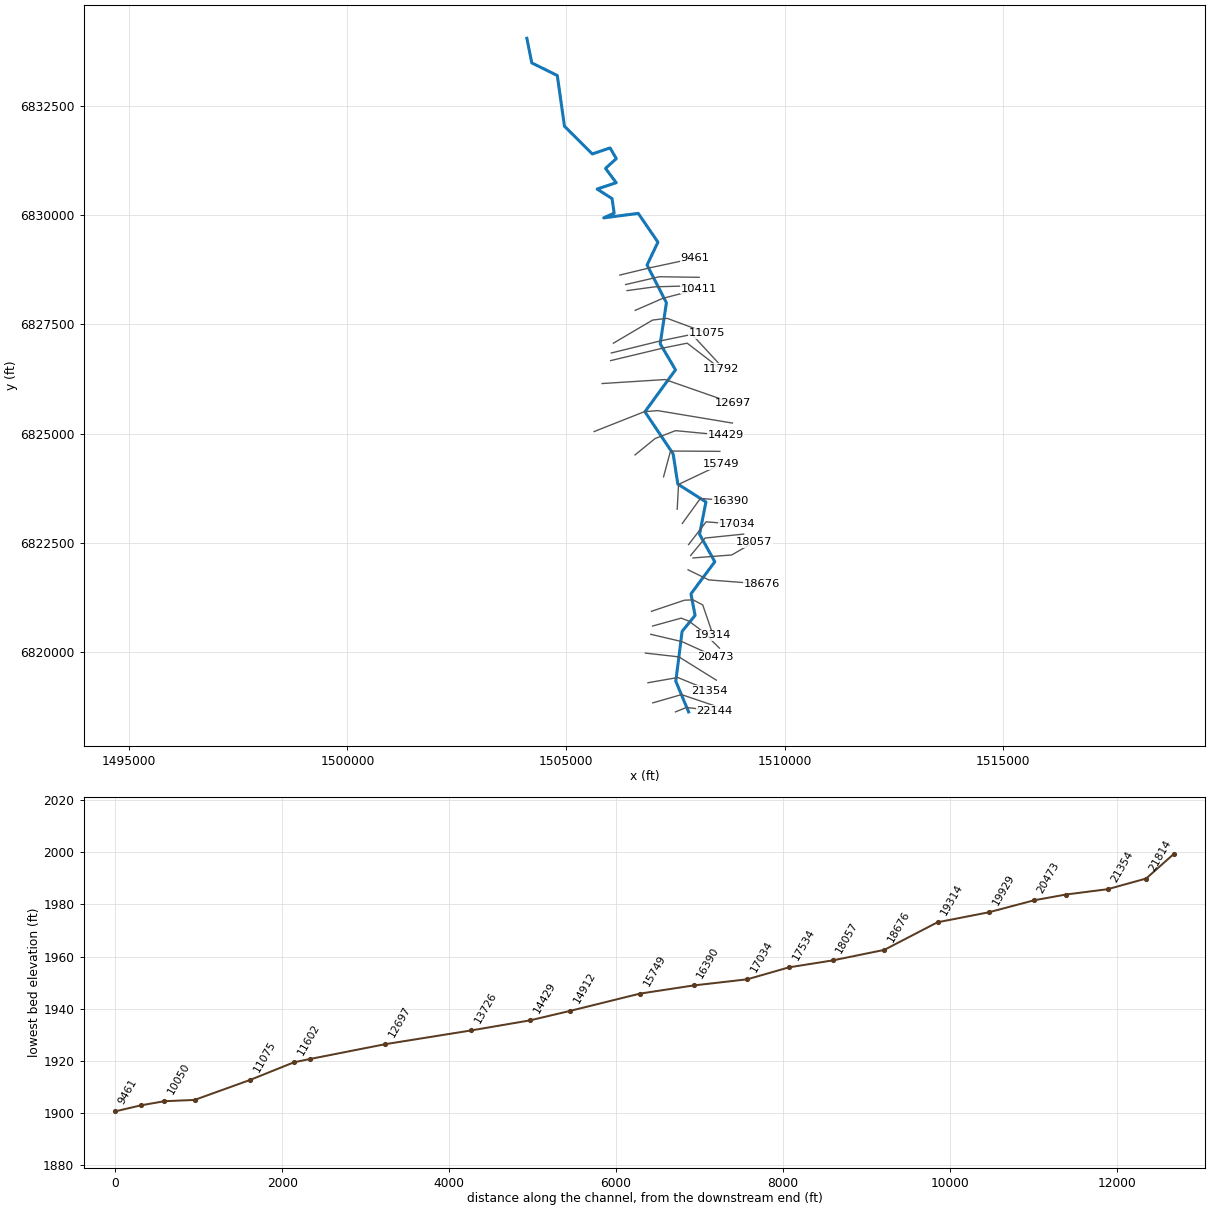
--- MULBERRY CREEK TRIBUTARY 18_1.prj (project) ---

Proj Title=MULBERRY CREEK TRIBUTARY 18_1 Base Level Engineering
Current Plan=p01
Default Exp/Contr=0.3,0.1
English Units
Geom File=g01
Flow File=f01
Plan File=p01
Y Axis Title=Elevation
X Axis Title(PF)=Main Channel Distance
X Axis Title(XS)=Station
BEGIN DESCRIPTION:
MULBERRY CREEK TRIBUTARY 18_1
END DESCRIPTION:
DSS Export Rating Curves= 0
DSS Export Rating Curve Sorted= 0
DSS Export Volume Flow Curves= 0
DXF OffsetX= 0
DXF OffsetY= 0
DXF ScaleX= 1
DXF ScaleY= 10

--- MULBERRY CREEK TRIBUTARY 18_1.p01 (plan) ---

Plan Title=Multiple Run
Short Identifier=Multiple
Geom File=g01
Flow File=f01
Subcritical Flow
K Sum by GR= 0
Std Step Tol= 0.01
Critical Tol= 0.01
Num of Std Step Trials= 20
Max Error Tol= 0.3
Flow Tol Ratio= 0.001
Split Flow NTrial= 30
Split Flow Tol= 0.02
Split Flow Ratio= 0.02
Log Output Level= 0
Friction Slope Method= 1
Unsteady Friction Slope Method= 2
Unsteady Bridges Friction Slope Method= 1
Parabolic Critical Depth
Global Vel Dist=  1 , 1 , 1
Global Log Level= 0
CheckData=True
Encroach Param= -1, 0, 0, 0
BEGIN DESCRIPTION:
Multiple Run
END DESCRIPTION:

--- MULBERRY CREEK TRIBUTARY 18_1.f01 (steady flow) ---

Flow Title=Multiple
Program Version=4.10
Number of Profiles= 7
Profile Names=10-year,25-year,50-year,1pct_min,100-year,1pct_plu,500-year
River Rch & RM=MULBERRY CREEK T,Reach-1         ,22144
     377     555     713     457     913    1821    1513
River Rch & RM=MULBERRY CREEK T,Reach-1         ,21354
     693    1057    1389     910    1816    3624    3147
River Rch & RM=MULBERRY CREEK T,Reach-1         ,20473
     665    1008    1319     860    1716    3423    2944
River Rch & RM=MULBERRY CREEK T,Reach-1         ,18676
     813    1239    1626    1063    2121    4231    3657
River Rch & RM=MULBERRY CREEK T,Reach-1         ,13726
     873    1329    1744    1138    2271    4531    3906
River Rch & RM=MULBERRY CREEK T,Reach-1         ,9765
     861    1303    1701    1105    2205    4399    3754
River Rch & RM=MULBERRY CREEK T,Reach-1         ,2637
     945    1435    1877    1220    2435    4858    4155
Boundary for River Rch & Prof#=MULBERRY CREEK T,Reach-1         , 1
Up Type= 0
Dn Type= 3
Dn Slope=0.005
Boundary for River Rch & Prof#=MULBERRY CREEK T,Reach-1         , 2
Up Type= 0
Dn Type= 3
Dn Slope=0.005
Boundary for River Rch & Prof#=MULBERRY CREEK T,Reach-1         , 3
Up Type= 0
Dn Type= 3
Dn Slope=0.005
Boundary for River Rch & Prof#=MULBERRY CREEK T,Reach-1         , 4
Up Type= 0
Dn Type= 3
Dn Slope=0.005
Boundary for River Rch & Prof#=MULBERRY CREEK T,Reach-1         , 5
Up Type= 0
Dn Type= 3
Dn Slope=0.005
Boundary for River Rch & Prof#=MULBERRY CREEK T,Reach-1         , 6
Up Type= 0
Dn Type= 3
Dn Slope=0.005
Boundary for River Rch & Prof#=MULBERRY CREEK T,Reach-1         , 7
Up Type= 0
Dn Type= 3
Dn Slope=0.005
DSS Import GetInterval= 0
DSS Import GetPeak= 0
DSS Import FillOption= 0

--- MULBERRY CREEK TRIBUTARY 18_1.g01 (geometry) ---

Geom Title=Existing Conditions
Program Version=4.10

River Reach=MULBERRY CREEK T,Reach-1
Reach XY= 30
        1507805.        6818638.      1507512.33       6819337.9
       1507656.2       6820477.5      1507953.45      6820843.85
      1507858.34      6821336.28      1508404.88       6822069.8
      1508055.49      6822698.49      1508201.56      6823436.75
      1507558.06      6823846.28      1507451.45      6824536.53
      1506805.76      6825498.69      1507505.47      6826458.16
      1507155.39      6827053.16       1507297.5      6827991.13
      1506854.74       6828853.7      1507103.52      6829376.51
      1506653.55      6830034.47      1505862.45      6829931.96
      1506102.14      6830039.73      1506054.09      6830372.06
      1505712.39      6830591.44      1506149.94       6830735.7
      1505904.46      6831063.12       1506151.7      6831286.24
      1506008.59      6831530.51      1505602.57       6831393.4
       1504965.3       6832027.9      1504801.25      6833186.45
      1504218.23      6833474.27        1504105.        6834038.

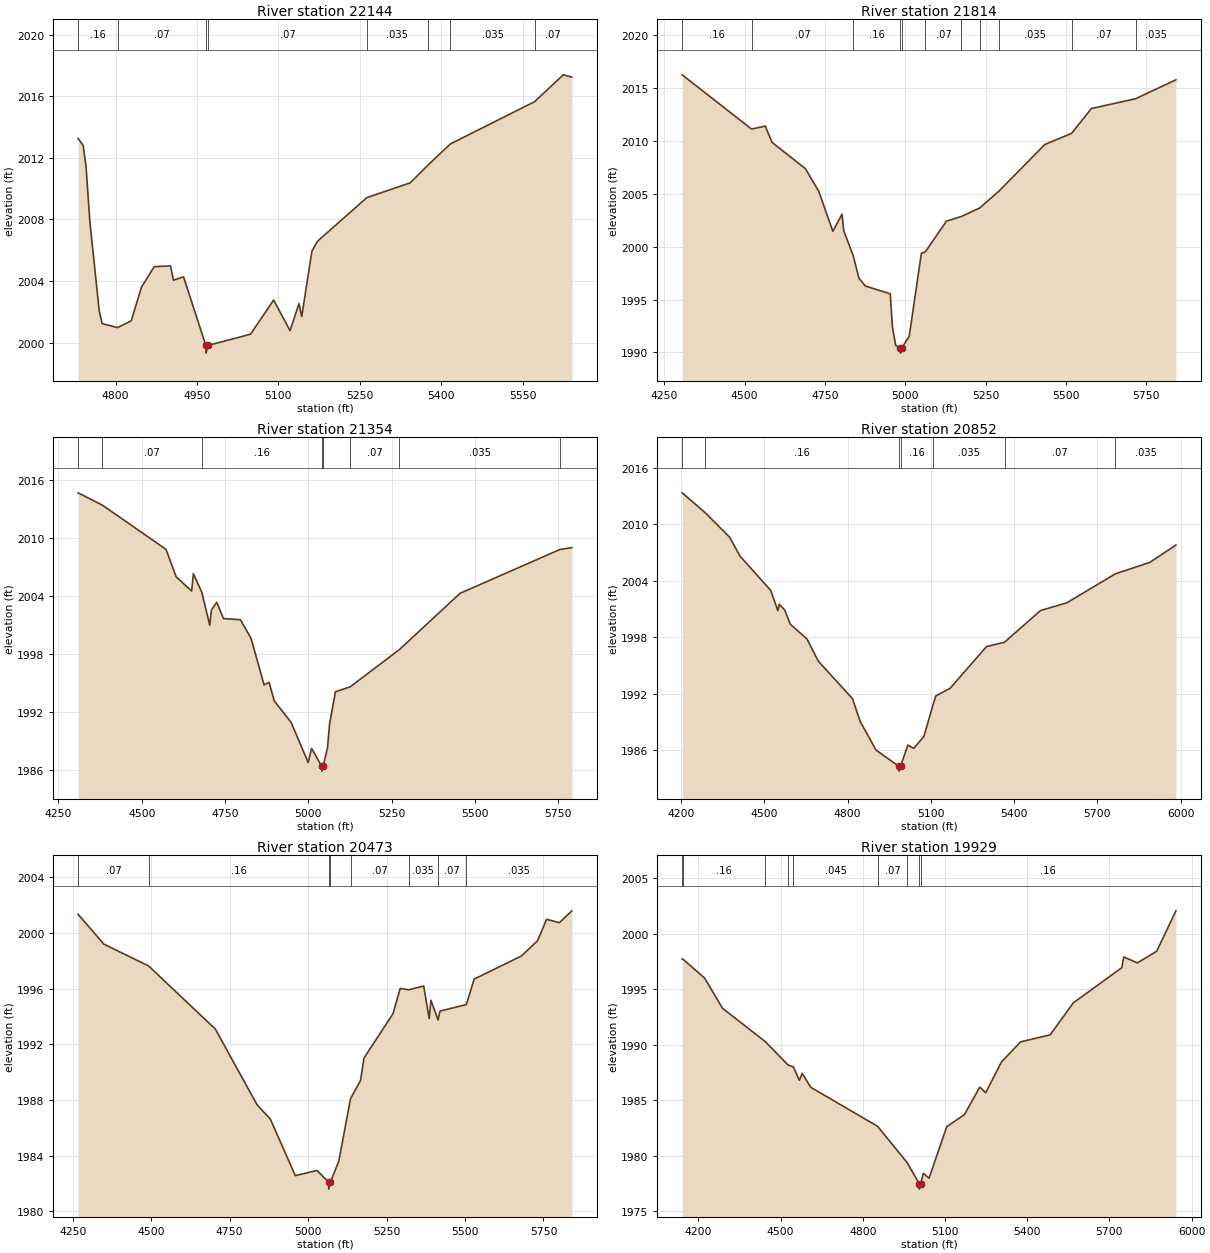
Type RM Length L Ch R = 1 ,22144   ,330,330,330
BEGIN DESCRIPTION:
MULBERRY CREEK TRIBUTARY 18_1 35.0
END DESCRIPTION:
XS GIS Cut Line= 3
      1507504.99        6818638.      1507754.38      6818738.83
      1508390.72      6818665.99
#Sta/Elev= 30
    4731 2013.26  4740.4  2012.8  4745.8 2011.37  4752.6 2007.88  4769.9 2002.05
  4775.3 2001.23  4803.6 2000.97  4828.9 2001.41  4847.7  2003.6  4871.2 2004.93
  4901.3 2004.98  4906.7 2004.05  4925.2 2004.27  4966.3 1999.81  4966.6 1999.31
  4970.3 1999.81  5048.6 2000.54  5091.2 2002.76  5121.4 2000.77  5137.8 2002.53
  5142.9 2001.69  5161.7 2005.94  5171.7 2006.57  5262.9 2009.42  5342.8 2010.38
  5375.4 2011.53  5416.8 2012.91  5571.8 2015.65  5624.7  2017.4  5640.5 2017.25
#Mann= 8 ,-1 , 0
    4731     .16       0  4803.6     .07       0  4966.3     .07       0
  4970.3     .07       0  5262.9    .035       0  5375.4     .07       0
  5416.8    .035       0  5571.8     .07       0
Bank Sta=4966.3,4970.3
XS Rating Curve= 0 ,0
Exp/Cntr=0.3,0.1

Type RM Length L Ch R = 1 ,21814   ,460,460,460
BEGIN DESCRIPTION:
Mapping XS 8a2c3452
END DESCRIPTION:
XS GIS Cut Line= 3
      1506986.19      6818843.85      1507642.45      6819033.09
       1508451.6      6818759.33
#Sta/Elev= 30
  4305.5 2016.26  4521.5 2011.13  4564.4 2011.41  4585.3 2009.87  4689.3 2007.38
  4730.6 2005.25  4774.7 2001.45  4803.2 2003.08  4808.4 2001.52  4837.8 1999.17
  4855.9 1997.02  4875.7 1996.28  4953.4 1995.54  4959.9 1992.44  4970.3 1990.65
  4985.1 1990.43  4985.3 1989.93  4989.1 1990.43  5012.3 1991.51  5050.2 1999.37
  5062.5 1999.51  5128.4 2002.42  5174.9 2002.86  5231.8 2003.66  5291.5 2005.25
  5434.6 2009.67  5517.9 2010.72  5579.4 2013.07  5717.4    2014  5842.7 2015.79
#Mann= 11 ,-1 , 0
  4305.5     .16       0  4521.5     .07       0  4837.8     .16       0
  4985.1     .07       0  4989.1     .16       0  5062.5     .07       0
  5174.9    .035       0  5231.8     .07       0  5291.5    .035       0
  5517.9     .07       0  5717.4    .035       0
Bank Sta=4985.1,4989.1
XS Rating Curve= 0 ,0
Exp/Cntr=0.3,0.1

Type RM Length L Ch R = 1 ,21354   ,502,502,502
BEGIN DESCRIPTION:
Mapping XS 662188e0
END DESCRIPTION:
XS GIS Cut Line= 3
      1506875.05      6819303.91      1507557.38      6819423.71
      1508288.27      6819125.11
#Sta/Elev= 30
    4309 2014.71    4382 2013.43  4572.9 2008.85  4603.4    2006  4649.9 2004.53
    4655 2006.32  4680.5 2004.39  4704.2 2000.99  4709.3 2002.56  4725.2 2003.36
  4745.5 2001.67  4796.3 2001.55    4828 1999.64  4867.4 1994.79  4882.3 1995.06
  4897.8 1993.14  4948.6  1990.9  4999.7 1986.74    5010  1988.2  5040.4 1986.35
  5040.7 1985.85  5044.4 1986.35  5057.6 1988.23    5064 1990.75  5081.6 1994.08
  5125.8 1994.59  5273.8 1998.46  5455.7 2004.29  5755.1 2008.83  5791.3 2009.03
#Mann= 8 ,-1 , 0
    4309     .16       0    4382     .07       0  4680.5     .16       0
  5040.4     .07       0  5044.4     .16       0  5125.8     .07       0
  5273.8    .035       0  5755.1     .07       0
Bank Sta=5040.4,5044.4
XS Rating Curve= 0 ,0
Exp/Cntr=0.3,0.1

Type RM Length L Ch R = 1 ,20852   ,379,379,379
BEGIN DESCRIPTION:
Mapping XS 9a548fc6
END DESCRIPTION:
XS GIS Cut Line= 3
      1506817.87      6819981.87      1507583.51      6819895.07
      1508439.87      6819362.88
#Sta/Elev= 30
  4204.1 2013.34  4286.7 2011.24  4374.5 2008.65  4412.6 2006.62  4523.3 2002.97
  4548.8 2000.83  4553.8  2001.5  4573.6  2000.9  4593.7 1999.39  4654.1 1997.81
  4694.4 1995.47  4817.8 1991.48  4845.3 1989.07  4902.4 1986.03  4985.4 1984.29
  4985.9 1983.79  4990.9 1984.29    5017 1986.56  5038.3 1986.21  5074.9 1987.46
  5107.1 1990.75  5117.7 1991.77  5169.3 1992.58  5300.4 1997.01  5365.5 1997.48
  5495.2 2000.84  5589.7 2001.66  5764.9 2004.74  5888.4 2005.95  5982.9 2007.79
#Mann= 7 ,-1 , 0
  4204.1    .035       0  4286.7     .16       0  4985.4     .07       0
  4990.9     .16       0  5107.1    .035       0  5365.5     .07       0
  5764.9    .035       0
Bank Sta=4985.4,4990.9
XS Rating Curve= 0 ,0
Exp/Cntr=0.3,0.1

Type RM Length L Ch R = 1 ,20473   ,544,544,544
BEGIN DESCRIPTION:
Mapping XS 760828cb
END DESCRIPTION:
XS GIS Cut Line= 3
       1506939.4      6820411.56      1507651.22      6820244.89
      1508418.55      6819897.68
#Sta/Elev= 30
  4267.2 2001.33  4349.3 1999.19    4492 1997.62  4704.5 1993.09  4837.8 1987.64
  4879.5 1986.64  4959.3 1982.57  5028.5 1982.94  5065.5  1982.1    5066  1981.6
    5071  1982.1  5097.8  1983.6  5135.2 1988.09  5167.1  1989.4  5178.1 1991.01
  5270.5 1994.19  5293.6 1996.01  5320.3 1995.91  5368.4 1996.18    5386 1993.85
  5391.5 1995.16  5414.3 1993.74  5420.1 1994.38  5504.2 1994.85  5529.3 1996.68
  5679.8 1998.34  5731.5 1999.44    5760 2000.97  5800.8 2000.73  5840.5 2001.58
#Mann= 8 ,-1 , 0
  4267.2     .07       0    4492     .16       0  5065.5     .07       0
    5071     .16       0  5135.2     .07       0  5320.3    .035       0
  5414.3     .07       0  5504.2    .035       0
Bank Sta=5065.5,5071
XS Rating Curve= 0 ,0
Exp/Cntr=0.3,0.1

Type RM Length L Ch R = 1 ,19929   ,615,615,615
BEGIN DESCRIPTION:
Mapping XS cdfc51da
END DESCRIPTION:
XS GIS Cut Line= 5
       1506982.8      6820600.79      1507635.59      6820781.35
      1507814.41      6820711.91      1508107.81      6820491.42
      1508511.17      6820094.99
#Sta/Elev= 30
  4140.9 1997.71  4143.2 1997.71  4222.6    1996  4288.4 1993.27  4444.9 1990.26
    4527 1988.17  4546.8 1987.99  4568.6 1986.79    4579 1987.41  4610.1 1986.16
  4854.4 1982.64  4961.8 1979.38  5005.7 1977.49  5006.2 1976.99  5011.3 1977.49
  5020.9 1978.41  5041.8 1977.98  5106.3 1982.61  5170.9  1983.7  5227.1 1986.18
  5248.4 1985.67  5306.3 1988.45  5375.7 1990.25  5483.6 1990.88  5568.5 1993.77
  5745.2 1996.93  5752.2  1997.9  5801.8 1997.36  5872.5 1998.41  5942.6 2002.05
#Mann= 9 ,-1 , 0
  4140.9     .07       0  4143.2     .16       0  4444.9    .045       0
    4527     .16       0  4546.8    .045       0  4854.4     .07       0
  4961.8     .16       0  5005.7     .07       0  5011.3     .16       0
Bank Sta=5005.7,5011.3
XS Rating Curve= 0 ,0
Exp/Cntr=0.3,0.1

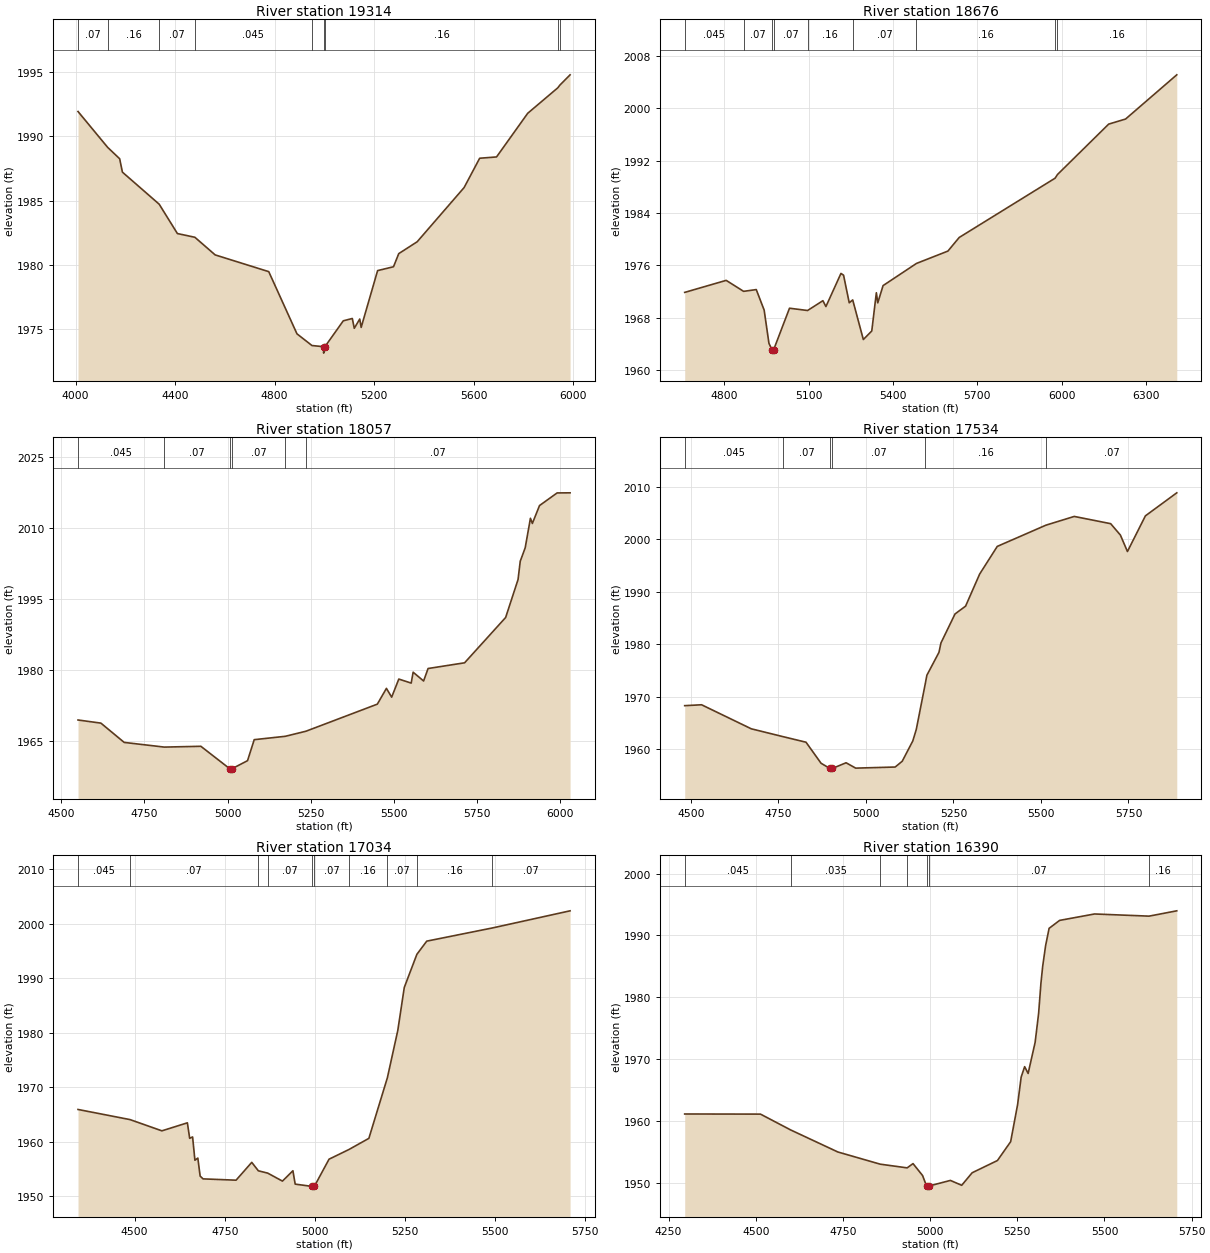
Type RM Length L Ch R = 1 ,19314   ,638,638,638
BEGIN DESCRIPTION:
Mapping XS 6cb03cbf
END DESCRIPTION:
XS GIS Cut Line= 5
      1506956.34       6820937.6      1507711.55      6821191.51
      1507909.03      6821198.02      1508128.21        6821083.
      1508366.91      6820386.43
#Sta/Elev= 30
  4009.6 1991.93    4129 1989.14    4177 1988.26  4188.1 1987.22  4335.9 1984.73
  4409.1 1982.45  4479.4 1982.16    4561 1980.79  4776.4 1979.49  4889.8 1974.66
  4950.1 1973.75  4996.6 1973.66  4997.1 1973.16  5002.2 1973.66    5076 1975.67
  5112.3 1975.85  5120.2 1975.09  5142.2 1975.81  5147.9 1975.16    5214 1979.57
  5277.9 1979.87    5299 1980.89    5373 1981.81  5561.7 1986.02  5624.3  1988.3
  5692.1  1988.4  5817.3 1991.79  5938.9 1993.78  5946.2 1993.97  5987.8 1994.78
#Mann= 9 ,-1 , 0
  4009.6     .07       0    4129     .16       0  4335.9     .07       0
  4479.4    .045       0  4950.1     .16       0  4996.6     .07       0
  5002.2     .16       0  5938.9     .07       0  5946.2     .16       0
Bank Sta=4996.6,5002.2
XS Rating Curve= 0 ,0
Exp/Cntr=0.3,0.1

Type RM Length L Ch R = 1 ,18676   ,619,619,619
BEGIN DESCRIPTION:
MULBERRY CREEK TRIBUTARY 18_1 27.0
END DESCRIPTION:
XS GIS Cut Line= 3
      1507793.49      6821885.86      1508265.71      6821654.96
      1509486.51      6821561.77
#Sta/Elev= 30
  4659.5 1971.86    4807  1973.7    4869 1972.02    4914 1972.29  4942.1 1969.15
  4959.1 1964.07  4970.1 1963.07  4970.5 1962.57  4975.7 1963.07  5032.2 1969.44
  5096.5 1969.09    5151 1970.59  5161.7 1969.69  5215.2 1974.76  5224.5 1974.49
  5244.6 1970.27    5257 1970.71  5294.8 1964.65  5324.8 1965.96  5341.1 1971.81
  5346.1 1970.26    5365  1972.9  5483.8 1976.29  5595.6 1978.18  5635.7 1980.26
  5976.8 1989.33    5985 1989.88  6167.3  1997.6  6227.5 1998.38  6409.5 2005.14
#Mann= 9 ,-1 , 0
  4659.5    .045       0    4869     .07       0  4970.1     .07       0
  4975.7     .07       0  5096.5     .16       0    5257     .07       0
  5483.8     .16       0  5976.8     .07       0    5985     .16       0
#XS Ineff= 2 , 0
       0                  5215.2       0 1974.76
Permanent Ineff=
       F       F
Bank Sta=4970.1,4975.7
XS Rating Curve= 0 ,0
Exp/Cntr=0.3,0.1

Type RM Length L Ch R = 1 ,18057   ,523,523,523
BEGIN DESCRIPTION:
Mapping XS fc8e3e68
END DESCRIPTION:
XS GIS Cut Line= 3
      1507906.39      6822157.29      1508791.77        6822225.
       1509304.8      6822521.88
#Sta/Elev= 30
    4550 1969.34  4618.8 1968.68    4689  1964.6  4809.5 1963.61  4919.7 1963.78
  5006.7 1959.03  5007.2 1958.53  5013.2 1959.03  5060.1 1960.74  5080.2 1965.18
  5173.7 1965.89  5236.1 1966.97  5450.7 1972.69    5478 1976.02  5493.8 1974.17
  5515.3 1977.99  5552.6 1977.14  5558.4 1979.44  5589.9 1977.58  5603.4 1980.22
  5713.3 1981.43  5836.8 1991.01  5874.1 1999.03  5880.7 2002.89  5895.6 2005.74
  5911.4 2011.98  5917.2 2010.89  5938.7 2014.67  5991.7 2017.34  6030.7 2017.36
#Mann= 6 ,-1 , 0
    4550    .045       0  4809.5     .07       0  5006.7     .07       0
  5013.2     .07       0  5173.7    .035       0  5236.1     .07       0
Bank Sta=5006.7,5013.2
XS Rating Curve= 0 ,0
Exp/Cntr=0.3,0.1

Type RM Length L Ch R = 1 ,17534   ,500,500,500
BEGIN DESCRIPTION:
Mapping XS c42a8b40
END DESCRIPTION:
XS GIS Cut Line= 3
      1507851.58      6822213.01      1508181.82       6822611.7
      1509065.15      6822702.59
#Sta/Elev= 30
  4482.3 1968.33  4530.5  1968.5  4672.5 1963.93    4763 1962.44  4828.8 1961.38
  4871.8 1957.38  4897.2 1956.38  4897.7 1955.88  4903.7 1956.38  4943.3 1957.47
  4970.8 1956.45  5083.6 1956.66  5103.7 1957.76  5133.9 1961.62  5143.9 1963.82
  5169.8 1972.59  5174.1 1974.11  5208.7 1978.48  5214.3 1980.25  5254.5 1985.77
  5284.7 1987.26  5324.9 1993.36  5375.2 1998.62  5514.3 2002.66  5595.1 2004.32
  5699.2 2002.94    5727 2000.77  5747.1 1997.65  5798.4 2004.43    5888 2008.81
#Mann= 6 ,-1 , 0
  4482.3    .045       0    4763     .07       0  4897.2     .07       0
  4903.7     .07       0  5169.8     .16       0  5514.3     .07       0
Bank Sta=4897.2,4903.7
XS Rating Curve= 0 ,0
Exp/Cntr=0.3,0.1

Type RM Length L Ch R = 1 ,17034   ,644,644,644
BEGIN DESCRIPTION:
Mapping XS cdbd35a6
END DESCRIPTION:
XS GIS Cut Line= 3
       1507804.7        6822463.      1508205.81      6822982.97
      1508911.16      6822926.64
#Sta/Elev= 30
  4343.3  1965.9  4487.6 1964.04  4575.9 1961.98  4646.5 1963.45  4652.9 1960.61
    4661 1960.86  4667.4 1956.59  4675.5 1956.98  4681.9 1953.68    4690 1953.17
  4781.5 1952.93    4825  1956.2  4843.3 1954.65  4869.1 1954.23  4910.1 1952.76
  4939.1 1954.66  4945.4 1952.21  4991.9 1951.79  4992.4 1951.29  4998.5 1951.79
  5039.3 1956.78  5094.3 1958.55  5149.7  1960.6    5201 1971.71  5229.9 1980.39
  5247.9 1988.28  5282.8 1994.35  5310.2 1996.77  5492.4 1999.19  5707.6 2002.33
#Mann= 10 ,-1 , 0
  4343.3    .045       0  4487.6     .07       0  4843.3     .16       0
  4869.1     .07       0  4991.9     .07       0  4998.5     .07       0
  5094.3     .16       0    5201     .07       0  5282.8     .16       0
  5492.4     .07       0
Bank Sta=4991.9,4998.5
XS Rating Curve= 0 ,0
Exp/Cntr=0.3,0.1

Type RM Length L Ch R = 1 ,16390   ,641,641,641
BEGIN DESCRIPTION:
Mapping XS 79c1acbd
END DESCRIPTION:
XS GIS Cut Line= 3
      1507662.34      6822947.38      1508074.71      6823517.72
      1508779.99        6823463.
#Sta/Elev= 30
  4296.2 1961.09  4513.5 1961.07  4600.4  1958.5  4735.5 1954.94  4856.8 1952.97
  4934.2 1952.37    4951 1953.06  4978.4 1951.13  4989.8 1949.43  4990.3 1948.93
  4996.4 1949.43  5058.2 1950.34  5090.6 1949.55  5120.6 1951.58  5193.1 1953.56
    5231 1956.61    5251 1962.64  5261.1 1967.06  5271.1 1968.75  5281.1 1967.65
  5301.2 1972.69  5311.2 1977.37  5317.9 1982.29  5322.9 1985.01  5331.3 1988.36
  5341.3 1991.14  5371.4 1992.42  5471.7 1993.46  5627.9 1993.11  5707.4 1993.97
#Mann= 7 ,-1 , 0
  4296.2    .045       0  4600.4    .035       0  4856.8    .045       0
  4934.2     .07       0  4989.8     .07       0  4996.4     .07       0
  5627.9     .16       0
Bank Sta=4989.8,4996.4
XS Rating Curve= 0 ,0
Exp/Cntr=0.3,0.1

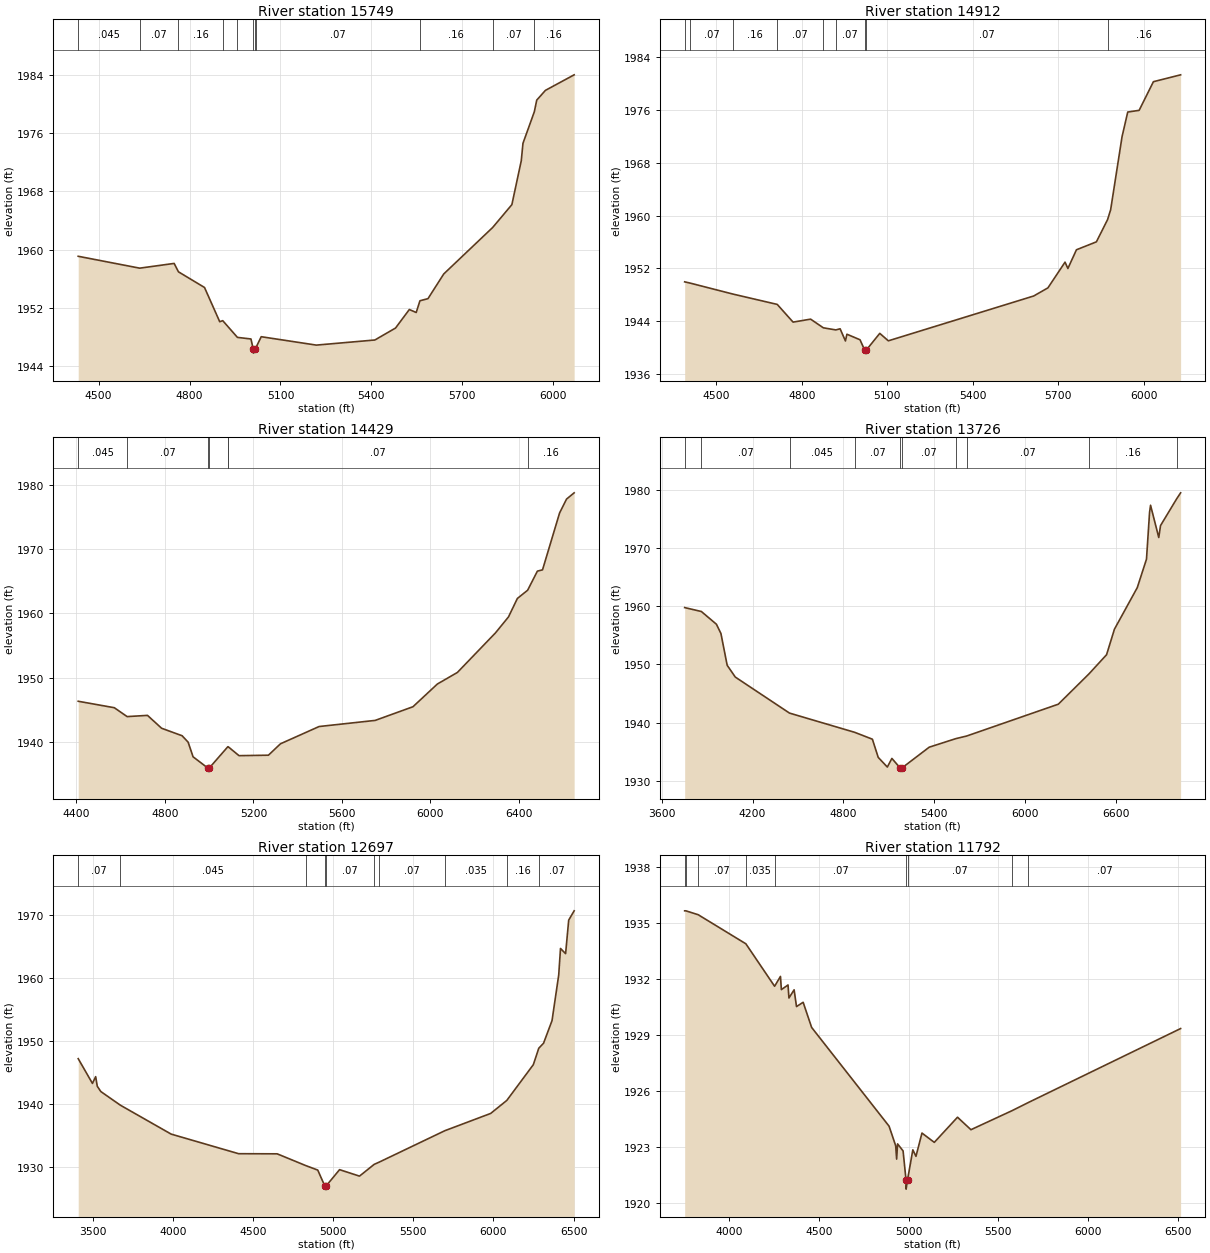
Type RM Length L Ch R = 1 ,15749   ,837,837,837
BEGIN DESCRIPTION:
Mapping XS 302da244
END DESCRIPTION:
XS GIS Cut Line= 3
      1507544.29      6823272.03      1507575.09       6823838.3
      1508540.57      6824296.29
#Sta/Elev= 30
  4432.9 1959.09  4635.7 1957.46  4749.3 1958.11  4763.5 1956.96  4849.5 1954.81
  4899.6 1950.12  4909.6 1950.26    4958 1947.97  5002.7 1947.75  5010.4 1946.31
  5010.9 1945.81  5017.1 1946.31  5018.7 1946.53  5036.5 1948.06  5218.3 1946.91
  5411.3 1947.61  5479.5 1949.25    5525 1951.79  5547.7 1951.38    5560 1952.99
  5586.5 1953.28  5638.6 1956.67  5799.9 1963.04  5863.2 1966.17  5894.2 1972.19
  5899.8 1974.58  5937.3 1978.91  5945.2  1980.5  5973.9 1981.84  6068.6 1983.97
#Mann= 11 ,-1 , 0
  4432.9    .045       0  4635.7     .07       0  4763.5     .16       0
  4909.6     .07       0    4958     .16       0  5010.4     .07       0
  5017.1     .16       0  5018.7     .07       0    5560     .16       0
  5799.9     .07       0  5937.3     .16       0
Bank Sta=5010.4,5017.1
XS Rating Curve= 0 ,0
Exp/Cntr=0.3,0.1

Type RM Length L Ch R = 1 ,14912   ,483,483,483
BEGIN DESCRIPTION:
Mapping XS d344bd27
END DESCRIPTION:
XS GIS Cut Line= 3
      1507231.78      6824011.57      1507391.44      6824601.24
      1508520.52      6824594.13
#Sta/Elev= 30
  4389.1 1949.97  4408.3 1949.78  4558.5 1948.12  4713.8 1946.56  4769.4 1943.88
  4830.9 1944.33  4875.6 1943.02  4919.4  1942.7  4934.5 1942.87  4953.1 1941.03
  4958.3 1942.05  5004.3 1941.21  5020.2 1939.69  5020.7 1939.19    5027 1939.69
  5073.6 1942.18  5103.6 1941.05  5613.6 1947.83  5663.6 1949.06  5723.6 1952.95
  5733.6 1951.99  5763.6 1954.82  5833.6 1956.02  5872.8 1959.38  5883.6 1960.87
  5923.6 1971.92  5943.6 1975.65  5983.6 1975.91  6033.6 1980.24  6129.1 1981.28
#Mann= 9 ,-1 , 0
  4389.1     .16       0  4408.3     .07       0  4558.5     .16       0
  4713.8     .07       0  4875.6     .16       0  4919.4     .07       0
  5020.2     .07       0    5027     .07       0  5872.8     .16       0
Bank Sta=5020.2,5027
XS Rating Curve= 0 ,0
Exp/Cntr=0.3,0.1

Type RM Length L Ch R = 1 ,14429   ,703,703,703
BEGIN DESCRIPTION:
Mapping XS 4f7920a2
END DESCRIPTION:
XS GIS Cut Line= 4
      1506579.98      6824512.98      1507039.23      6824886.86
      1507505.14      6825067.04      1508650.46      6824959.45
#Sta/Elev= 30
  4407.8 1946.38  4570.8 1945.38  4629.1    1944    4721 1944.19  4784.9 1942.19
  4877.5 1941.03  4904.8 1940.03  4927.1 1937.76  4993.1 1936.04  4993.6 1935.54
  5000.7 1936.04  5084.2 1939.32  5085.6 1939.33  5134.8 1937.94  5267.7 1938.01
  5322.2 1939.78  5496.8 1942.46  5750.5 1943.41  5921.2 1945.53  6031.7 1949.06
  6122.1 1950.85  6294.5    1957  6353.1 1959.47  6393.2 1962.33  6439.7 1963.61
  6483.7 1966.57  6506.9 1966.77  6584.1  1975.6  6615.6 1977.75  6649.9 1978.72
#Mann= 7 ,-1 , 0
  4407.8    .045       0  4629.1     .07       0  4993.1     .07       0
  5000.7     .07       0  5084.2     .16       0  5085.6     .07       0
  6439.7     .16       0
Bank Sta=4993.1,5000.7
XS Rating Curve= 0 ,0
Exp/Cntr=0.3,0.1

Type RM Length L Ch R = 1 ,13726   ,1029,1029,1029
BEGIN DESCRIPTION:
Mapping XS 412e4b22
END DESCRIPTION:
XS GIS Cut Line= 4
      1505644.05      6825046.22      1506793.33      6825501.07
      1507095.41      6825525.38      1508807.23      6825240.65
#Sta/Elev= 30
    3752 1959.76  3862.2 1959.09  3961.7  1956.9  3991.4 1955.31  4032.6 1949.86
  4086.4 1947.83  4444.2 1941.65  4874.6 1938.35  4991.4 1937.17  5029.8 1934.05
    5090 1932.39  5120.1 1933.87  5176.3 1932.19  5176.8 1931.69  5184.3 1932.19
  5366.6  1935.8  5541.4 1937.26  5614.3 1937.72    6219 1943.18  6420.5 1948.36
  6537.5 1951.67  6589.4 1956.05  6740.3 1963.19  6801.1 1968.08  6821.4 1976.11
  6827.9 1977.33  6882.2 1971.79  6893.8 1973.84  6999.6  1978.4  7026.4 1979.46
#Mann= 10 ,-1 , 0
    3752     .16       0  3862.2     .07       0  4444.2    .045       0
  4874.6     .07       0  5176.3     .07       0  5184.3     .07       0
  5541.4    .035       0  5614.3     .07       0  6420.5     .16       0
  6999.6     .07       0
Bank Sta=5176.3,5184.3
XS Rating Curve= 0 ,0
Exp/Cntr=0.3,0.1

Type RM Length L Ch R = 1 ,12697   ,905,905,905
BEGIN DESCRIPTION:
Mapping XS 82a1e41c
END DESCRIPTION:
XS GIS Cut Line= 3
      1505826.35       6826144.3      1507267.29      6826235.45
      1508825.32      6825692.95
#Sta/Elev= 30
  3409.9 1947.19  3498.7 1943.25  3518.8 1944.33  3528.8  1942.8  3550.8 1941.96
  3673.1 1939.78  3989.7 1935.18  4410.5 1932.06    4651 1932.04  4830.1 1930.16
  4904.2 1929.45  4948.1 1926.92  4948.6 1926.42  4956.2 1926.92  5040.1 1929.52
  5164.5 1928.49  5255.9 1930.36  5286.7 1930.71  5696.7 1935.72  5982.7 1938.47
  6083.3 1940.54    6249 1946.24  6282.8 1948.85  6312.6 1949.65  6365.5 1953.25
  6407.3 1960.53  6418.4 1964.74  6450.2 1963.91  6469.5 1969.25  6503.5 1970.73
#Mann= 10 ,-1 , 0
  3409.9     .07       0  3673.1    .045       0  4830.1     .07       0
  4948.1     .07       0  4956.2     .07       0  5255.9    .035       0
  5286.7     .07       0  5696.7    .035       0  6083.3     .16       0
  6282.8     .07       0
Bank Sta=4948.1,4956.2
XS Rating Curve= 0 ,0
Exp/Cntr=0.3,0.1

Type RM Length L Ch R = 1 ,11792   ,190,190,190
BEGIN DESCRIPTION:
Mapping XS 59f0abea
END DESCRIPTION:
XS GIS Cut Line= 4
      1506022.49      6826668.89      1507243.85      6826960.56
       1507772.5      6827067.33      1508538.11       6826478.8
#Sta/Elev= 30
  3753.6 1935.66  3760.4 1935.66    3829 1935.45  4094.2 1933.89  4254.2 1931.61
  4286.8 1932.14  4291.9 1931.43  4328.9 1931.68    4334 1930.98  4362.8 1931.42
  4376.1 1930.52  4413.1 1930.75  4460.3  1929.4  4891.4  1924.1  4928.2 1923.05
  4933.5 1922.33  4938.7 1923.15  4969.4 1922.77  4985.7 1921.22  4986.2 1920.72
  4994.2 1921.22  5023.7 1922.83  5041.1 1922.48  5074.5 1923.73  5143.1 1923.23
  5272.4 1924.58  5347.1 1923.91  5575.5 1924.93  5666.8 1925.37  6514.3 1929.34
#Mann= 9 ,-1 , 0
  3753.6     .07       0  3760.4    .045       0    3829     .07       0
  4094.2    .035       0  4254.2     .07       0  4985.7     .07       0
  4994.2     .07       0  5575.5    .035       0  5666.8     .07       0
Bank Sta=4985.7,4994.2
XS Rating Curve= 0 ,0
Exp/Cntr=0.3,0.1

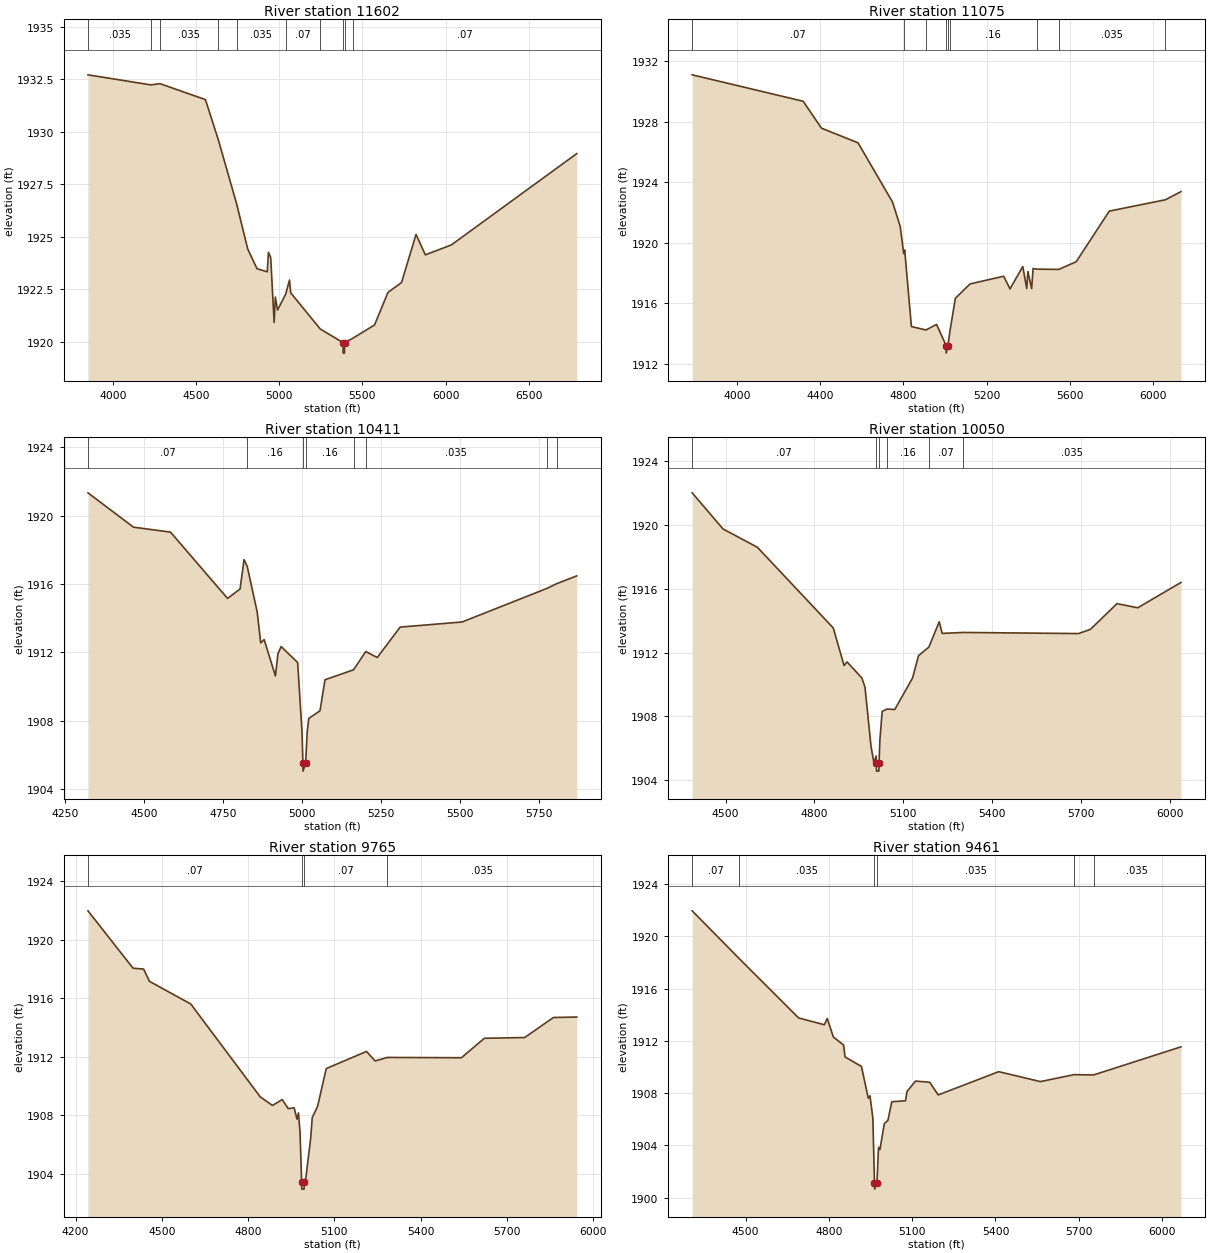
Type RM Length L Ch R = 1 ,11602   ,527,527,527
BEGIN DESCRIPTION:
Mapping XS 7239fdac
END DESCRIPTION:
XS GIS Cut Line= 4
      1506038.11      6826843.37      1507170.94      6827122.02
      1507881.87      6827267.85      1508592.78      6826499.66
#Sta/Elev= 30
    3850 1932.72    4229 1932.24  4282.7  1932.3  4556.2 1931.54    4634 1929.62
    4744 1926.57  4810.5 1924.43  4866.3 1923.49  4928.1 1923.34  4935.1 1924.27
  4948.7 1924.02  4969.3 1920.93  4976.6 1922.14  4989.9 1921.52  5038.7 1922.28
  5061.6 1922.95    5069 1922.34  5246.6 1920.62    5384 1919.97  5384.5 1919.47
    5392 1919.47  5392.5 1919.97  5440.6 1920.17    5573 1920.81  5653.6 1922.36
  5735.3 1922.83  5822.5 1925.12  5878.6 1924.15  6034.6 1924.62    6789 1928.97
#Mann= 10 ,-1 , 0
    3850    .035       0    4229     .07       0  4282.7    .035       0
    4634     .07       0    4744    .035       0  5038.7     .07       0
  5246.6    .035       0    5384    .035       0  5392.5    .035       0
  5440.6     .07       0
Bank Sta=5384,5392.5
XS Rating Curve= 0 ,0
Exp/Cntr=0.3,0.1

Type RM Length L Ch R = 1 ,11075   ,664,664,664
BEGIN DESCRIPTION:
Mapping XS 0466eb25
END DESCRIPTION:
XS GIS Cut Line= 4
        1506085.      6827067.33      1506983.44      6827595.98
      1507314.16      6827635.04      1508228.23       6827296.5
#Sta/Elev= 30
  3784.3 1931.11    4318 1929.36  4405.9 1927.58  4581.7 1926.61  4747.6 1922.69
  4784.7 1921.07  4801.4 1919.27  4806.1 1919.51  4838.4 1914.45  4908.4 1914.22
  4959.2 1914.59  5005.3 1913.19  5005.8 1912.69  5013.9 1913.19  5023.4 1914.12
  5049.8 1916.32  5120.3 1917.27    5282 1917.78  5312.4 1916.94  5373.9 1918.42
  5392.9 1916.97  5398.3 1918.09  5416.6 1916.96  5423.3 1918.29    5440 1918.25
  5546.7 1918.23  5630.8 1918.74  5789.8 1922.09  6059.6 1922.84  6134.5 1923.38
#Mann= 9 ,-1 , 0
  3784.3     .07       0  4801.4     .16       0  4908.4     .07       0
  5005.3     .07       0  5013.9     .07       0  5023.4     .16       0
    5440     .07       0  5546.7    .035       0  6059.6     .07       0
Bank Sta=5005.3,5013.9
XS Rating Curve= 0 ,0
Exp/Cntr=0.3,0.1

Type RM Length L Ch R = 1 ,10411   ,361,361,361
BEGIN DESCRIPTION:
Mapping XS aa24c8d0
END DESCRIPTION:
XS GIS Cut Line= 3
      1506583.49      6827817.53      1507212.86      6828090.98
      1508046.16      6828307.98
#Sta/Elev= 30
    4322 1921.33    4466 1919.32  4583.3 1919.03  4763.8 1915.15  4803.4  1915.7
  4816.1 1917.42  4826.3 1917.01  4857.6 1914.36  4868.8 1912.55  4879.7 1912.74
  4915.4 1910.61  4923.3 1911.91  4933.4 1912.33  4985.7  1911.4  4999.6 1907.31
  5002.3 1905.54  5002.8 1905.04    5011 1905.54  5015.9 1907.33  5021.1 1908.13
  5056.4 1908.57  5072.4 1910.39  5162.6 1910.97  5201.2 1912.04  5237.8 1911.69
  5310.1 1913.47  5506.4 1913.77  5775.5 1915.74  5805.4 1916.01  5869.3 1916.47
#Mann= 8 ,-1 , 0
    4322     .07       0  4826.3     .16       0  5002.3     .07       0
    5011     .16       0  5162.6     .07       0  5201.2    .035       0
  5775.5     .07       0  5805.4    .035       0
Bank Sta=5002.3,5011
XS Rating Curve= 0 ,0
Exp/Cntr=0.3,0.1

Type RM Length L Ch R = 1 ,10050   ,285,285,285
BEGIN DESCRIPTION:
Mapping XS 98bebf7c
END DESCRIPTION:
XS GIS Cut Line= 3
      1506396.85      6828268.92      1507034.91      6828355.73
      1508040.93      6828381.75
#Sta/Elev= 30
  4387.2 1922.03  4491.5 1919.76  4607.4 1918.61  4863.6 1913.54    4900 1911.18
  4910.1 1911.41  4960.6 1910.39  4970.7 1909.81  4990.9 1906.12    5001 1905.06
  5008.4  1905.5    5009 1905.05  5009.5 1904.55  5017.5 1904.55    5018 1905.05
  5021.1 1906.54  5028.7  1908.3    5045 1908.45  5071.2 1908.42  5131.3  1910.4
  5151.3  1911.8  5186.3 1912.34  5221.3 1913.93  5231.3  1913.2  5301.8 1913.26
  5691.5 1913.19  5731.5 1913.45  5821.5 1915.07  5891.5 1914.81  6037.5  1916.4
#Mann= 6 ,-1 , 0
  4387.2     .07       0    5009     .07       0    5018     .07       0
    5045     .16       0  5186.3     .07       0  5301.8    .035       0
Bank Sta=5009,5018
XS Rating Curve= 0 ,0
Exp/Cntr=0.3,0.1

Type RM Length L Ch R = 1 ,9765    ,304,304,304
BEGIN DESCRIPTION:
Mapping XS bfb14b5a
END DESCRIPTION:
XS GIS Cut Line= 3
      1506366.55      6828407.83      1507134.73      6828585.77
      1508046.22      6828572.75
#Sta/Elev= 30
  4243.3 1921.97    4400 1918.05  4436.7 1917.99  4457.3 1917.15    4601  1915.6
  4842.3 1909.26  4884.9 1908.67  4919.2 1909.07  4939.7 1908.45  4960.2 1908.51
  4970.3 1907.73  4975.4 1908.16  4980.8 1906.84  4986.5 1903.45    4987 1902.95
    4995 1902.95  4995.5 1903.45  5001.3 1903.74  5018.1 1906.46  5023.3 1907.83
  5042.1 1908.62  5072.1 1911.19  5212.1 1912.36  5242.1 1911.71  5284.8 1911.95
  5542.1 1911.93  5622.1 1913.26  5762.2 1913.31  5862.2 1914.68  5943.4 1914.71
#Mann= 4 ,-1 , 0
  4243.3     .07       0  4986.5     .07       0  4995.5     .07       0
  5284.8    .035       0
Bank Sta=4986.5,4995.5
XS Rating Curve= 0 ,0
Exp/Cntr=0.3,0.1

Type RM Length L Ch R = 1 ,9461    ,576,576,576
BEGIN DESCRIPTION:
Mapping XS 3e037b29
END DESCRIPTION:
XS GIS Cut Line= 3
      1506231.94      6828624.83      1506917.72      6828789.76
      1507950.34      6829011.04
#Sta/Elev= 30
  4307.2 1921.96  4475.1 1918.34  4690.9 1913.76  4783.5 1913.24  4793.8 1913.72
    4816  1912.3  4852.8 1911.69    4858 1910.78  4917.2 1910.05  4941.9 1907.61
    4948 1907.81  4958.3 1906.08  4964.1 1901.16  4964.6 1900.66  4973.1 1901.16
  4978.7 1903.85  4983.8 1903.68  4999.5 1905.67  5012.5 1905.92  5026.5 1907.35
    5076 1907.42  5081.3 1908.13    5112 1908.93  5163.2 1908.84  5193.8 1907.87
  5411.8 1909.65    5562 1908.89  5682.8 1909.42  5753.9  1909.4  6068.6 1911.55
#Mann= 6 ,-1 , 0
  4307.2     .07       0  4475.1    .035       0  4964.1    .035       0
  4973.1    .035       0  5682.8     .07       0  5753.9    .035       0
Bank Sta=4964.1,4973.1
XS Rating Curve= 0 ,0
Exp/Cntr=0.3,0.1