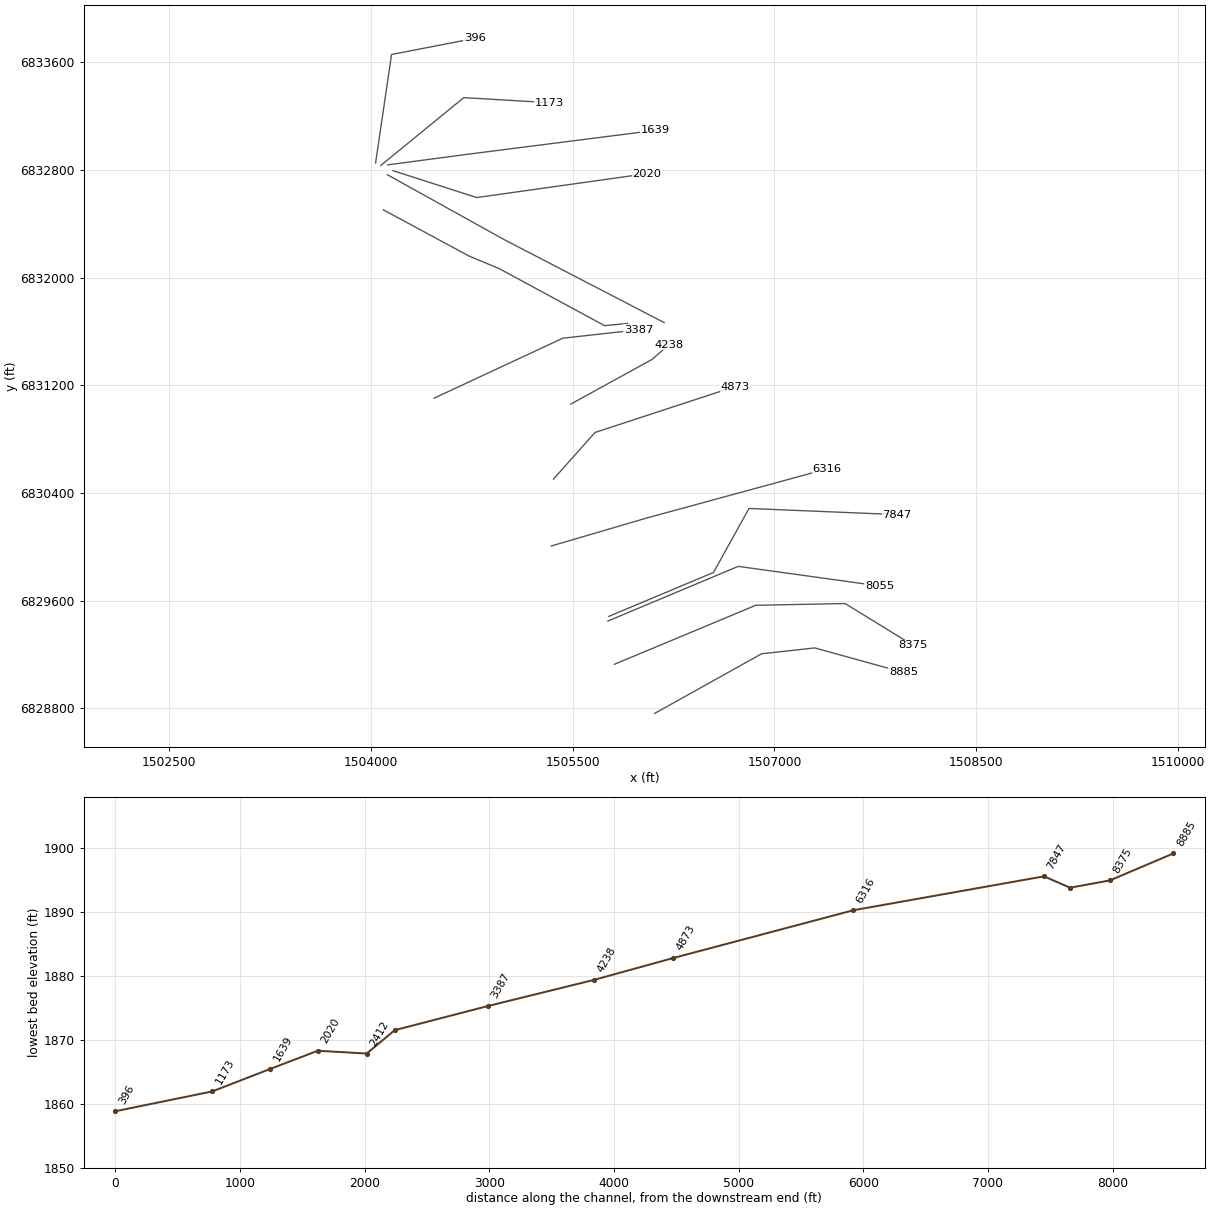
HEC-RAS study MULBERRY CREEK TRIBUTARY 18_1.prj: MULBERRY CREEK TRIBUTARY 18_1 Base Level Engineering

--- MULBERRY CREEK TRIBUTARY 18_1.g01 (geometry) --- (continued)

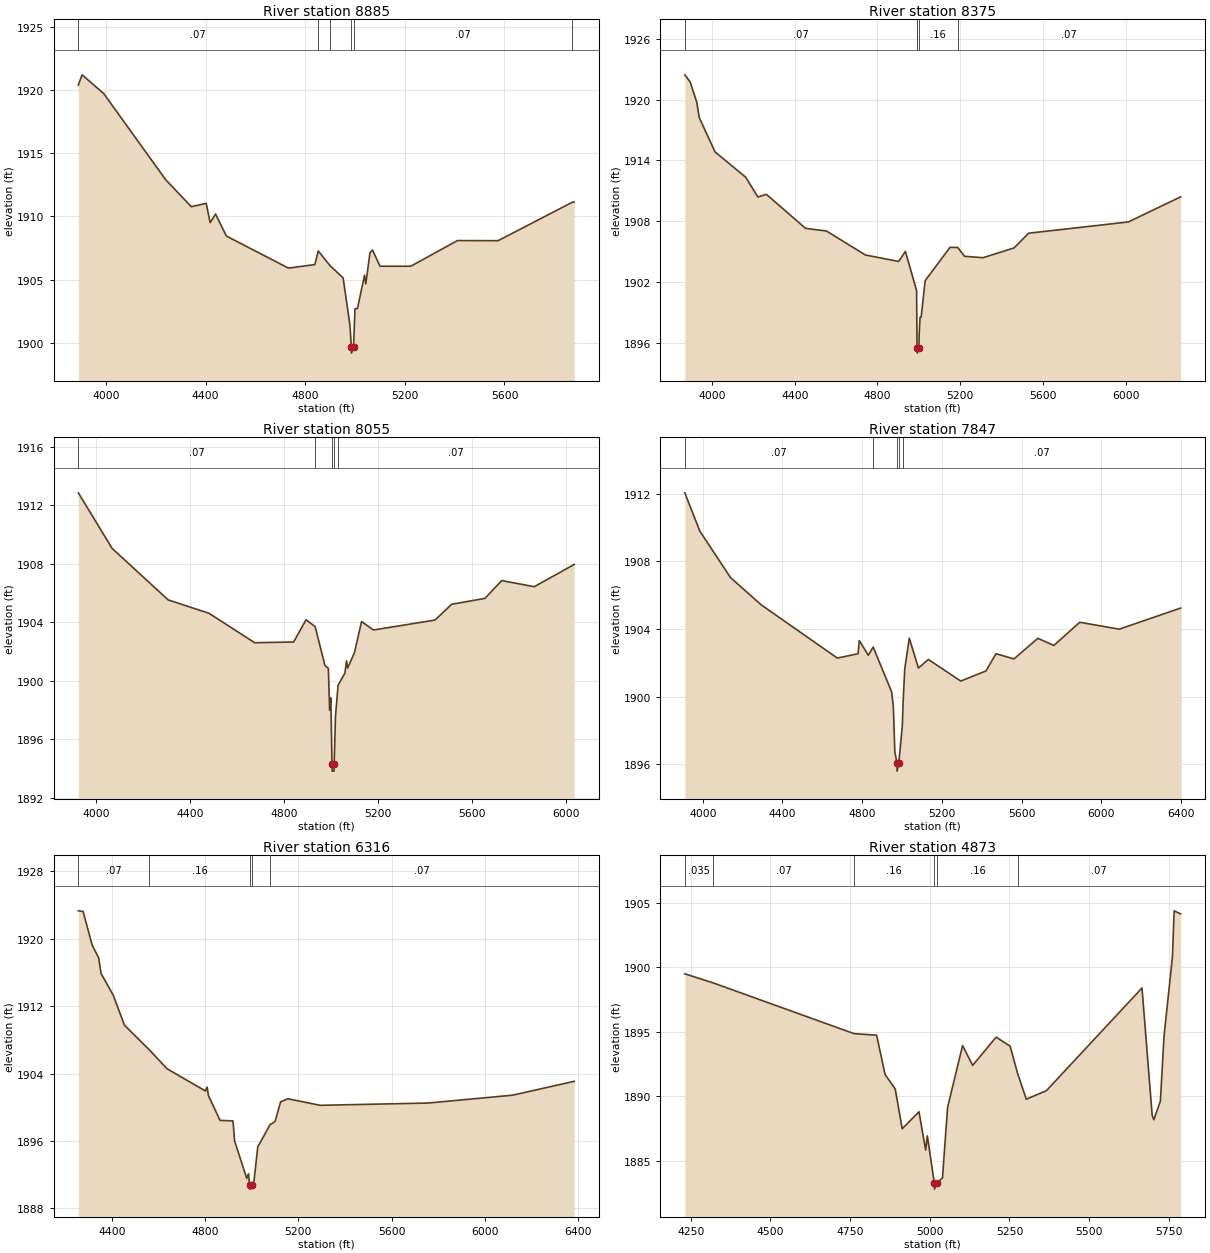
Type RM Length L Ch R = 1 ,8885    ,510,510,510
BEGIN DESCRIPTION:
Mapping XS ef2d5b84
END DESCRIPTION:
XS GIS Cut Line= 4
       1506110.4       6828763.7       1506904.7      6829206.43
      1507299.66      6829249.83      1507959.35      6829067.55
#Sta/Elev= 30
  3888.7  1920.4  3903.7 1921.21  3990.6 1919.73  4239.8  1912.9  4342.7 1910.77
  4402.1 1911.04  4418.1 1909.51  4439.8 1910.19  4483.2 1908.45  4732.4 1905.91
  4838.6 1906.19  4852.1 1907.27  4900.2 1906.09    4952 1905.14  4979.4  1901.4
    4985 1899.68  4985.5 1899.18    4994 1899.68  4999.6 1902.69  5009.6 1902.71
    5038 1905.35  5043.1 1904.66  5059.9 1907.13    5070 1907.34  5100.2 1906.06
  5223.9 1906.06  5411.2 1908.09  5574.4 1908.08    5873 1911.13  5879.8 1911.14
#Mann= 6 ,-1 , 0
  3888.7     .07       0  4852.1     .16       0  4900.2     .07       0
    4985     .07       0    4994     .07       0    5873    .035       0
Bank Sta=4985,4994
XS Rating Curve= 0 ,0
Exp/Cntr=0.3,0.1

Type RM Length L Ch R = 1 ,8375    ,320,320,320
BEGIN DESCRIPTION:
Mapping XS 30a6c572
END DESCRIPTION:
XS GIS Cut Line= 4
      1505810.96      6829128.31       1506861.3      6829566.67
      1507525.36      6829579.69      1508031.56      6829268.18
#Sta/Elev= 30
  3868.8 1922.45  3894.8 1921.75  3927.4 1919.69  3938.3 1918.24  4015.1 1914.83
  4163.5 1912.33  4221.9 1910.38  4263.3 1910.64  4452.5 1907.28  4553.2 1907.02
  4741.6 1904.65  4902.6 1904.01  4935.1    1905  4989.3 1901.13  4990.3 1898.55
  4991.5 1895.45    4992 1894.95  5000.7 1895.45  5001.5 1896.74  5006.2 1898.51
  5011.3 1898.51  5030.6 1902.11  5150.7  1905.4  5188.3 1905.39  5220.7 1904.52
  5310.7 1904.38  5460.7 1905.35  5530.7  1906.8  6012.7 1907.91  6265.5 1910.39
#Mann= 5 ,-1 , 0
  3868.8     .07       0  4990.3     .16       0  4991.5     .07       0
  5000.7     .16       0  5188.3     .07       0
Bank Sta=4991.5,5000.7
XS Rating Curve= 0 ,0
Exp/Cntr=0.3,0.1

Type RM Length L Ch R = 1 ,8055    ,208,208,208
BEGIN DESCRIPTION:
Mapping XS 8d1dbcae
END DESCRIPTION:
XS GIS Cut Line= 3
      1505762.32      6829449.48      1506731.09      6829855.73
      1507781.54      6829710.13
#Sta/Elev= 30
  3925.5 1912.84  4069.4 1909.04  4307.9 1905.52  4482.2  1904.6  4676.6 1902.59
  4842.2 1902.64  4895.1 1904.16  4933.8 1903.69  4975.4 1901.04    4990 1900.83
  4995.5 1897.98  5000.5 1898.82  5005.6 1894.31  5006.1 1893.81  5014.3 1893.81
  5014.8 1894.31  5020.3 1897.55  5031.3 1899.68  5060.7 1900.52  5067.3 1901.35
  5072.3 1900.86  5101.1 1901.91  5131.4 1904.04  5181.9 1903.46  5444.3 1904.14
    5515 1905.22  5656.4 1905.62  5728.2 1906.84  5866.6 1906.42  6036.5 1907.94
#Mann= 5 ,-1 , 0
  3925.5     .07       0  4933.8     .16       0  5005.6     .07       0
  5014.8     .16       0  5031.3     .07       0
Bank Sta=5005.6,5014.8
XS Rating Curve= 0 ,0
Exp/Cntr=0.3,0.1

Type RM Length L Ch R = 1 ,7847    ,1531,1531,1531
BEGIN DESCRIPTION:
Mapping XS c0f90300
END DESCRIPTION:
XS GIS Cut Line= 4
      1505769.29      6829484.21      1506547.06      6829810.59
      1506810.79      6830285.93      1507910.57      6830240.37
#Sta/Elev= 30
  3910.1 1912.06  3985.7 1909.79  4139.1 1907.05  4292.5 1905.44  4675.4 1902.28
  4779.7 1902.54  4785.4 1903.32  4830.7 1902.45  4855.5 1902.93  4947.9 1900.28
  4956.5  1899.4    4964 1896.73  4974.7 1896.09  4975.2 1895.59  4983.9 1896.09
  5001.7  1898.3  5005.4 1899.64  5013.6 1901.63  5036.5 1903.46  5082.3 1901.69
  5132.2  1902.2  5294.7 1900.92  5421.5 1901.52  5471.5 1902.54  5561.6 1902.23
  5681.7 1903.45  5761.8 1903.03  5891.9  1904.4  6089.9 1903.99  6397.9 1905.24
#Mann= 5 ,-1 , 0
  3910.1     .07       0  4855.5     .16       0  4974.7     .07       0
  4983.9     .16       0  5005.4     .07       0
Bank Sta=4974.7,4983.9
XS Rating Curve= 0 ,0
Exp/Cntr=0.3,0.1

Type RM Length L Ch R = 1 ,6316    ,1443,1443,1443
BEGIN DESCRIPTION:
Mapping XS 858a65a3
END DESCRIPTION:
XS GIS Cut Line= 3
      1505341.33      6830006.95      1506052.27      6830215.28
      1507390.38      6830579.75
#Sta/Elev= 30
  4256.1 1923.32  4276.6 1923.25  4315.2 1919.27  4343.3 1917.74  4353.8 1915.88
  4405.8 1913.31  4454.1 1909.74    4561 1906.81  4636.8 1904.57  4801.8 1901.93
    4809  1902.4  4814.2  1901.4  4864.3 1898.44  4919.7 1898.38  4926.8 1895.99
  4978.9 1891.55  4986.5 1892.11    4991 1890.78  4991.5 1890.28  5000.5 1890.78
  5010.1 1891.29    5026 1895.28  5078.7 1897.93  5100.3 1898.31  5124.1 1900.63
  5155.2 1901.01  5293.9 1900.23  5756.4  1900.5  6119.1 1901.43  6383.8 1903.08
#Mann= 5 ,-1 , 0
  4256.1     .07       0    4561     .16       0    4991     .07       0
  5000.5     .16       0  5078.7     .07       0
Bank Sta=4991,5000.5
XS Rating Curve= 0 ,0
Exp/Cntr=0.3,0.1

Type RM Length L Ch R = 1 ,4873    ,635,635,635
BEGIN DESCRIPTION:
Mapping XS bc699945
END DESCRIPTION:
XS GIS Cut Line= 3
      1505358.49      6830504.24      1505667.14      6830850.41
      1506705.31      6831190.68
#Sta/Elev= 30
  4231.1  1899.5  4320.7 1898.79  4762.5 1894.86  4833.2 1894.74  4859.7  1891.7
  4891.6 1890.57  4913.6 1887.49  4966.2 1888.81  4987.1 1885.84  4992.4 1886.94
  5014.1 1883.31  5014.6 1882.81  5023.6 1883.31  5039.9 1883.68    5056 1889.15
    5103 1893.94  5134.6  1892.4  5208.3 1894.59  5252.3 1893.89  5275.5  1891.8
    5303 1889.78  5366.1 1890.44  5666.2  1898.4  5698.1 1888.53  5703.3 1888.19
  5723.9 1889.63  5735.2 1894.63  5761.8 1900.84    5767 1904.38  5787.4 1904.14
#Mann= 6 ,-1 , 0
  4231.1    .035       0  4320.7     .07       0  4762.5     .16       0
  5014.1     .07       0  5023.6     .16       0  5275.5     .07       0
#XS Ineff= 2 , 0
       0                  5208.3       0 1894.59
Permanent Ineff=
       F       F
Bank Sta=5014.1,5023.6
XS Rating Curve= 0 ,0
Exp/Cntr=0.3,0.1

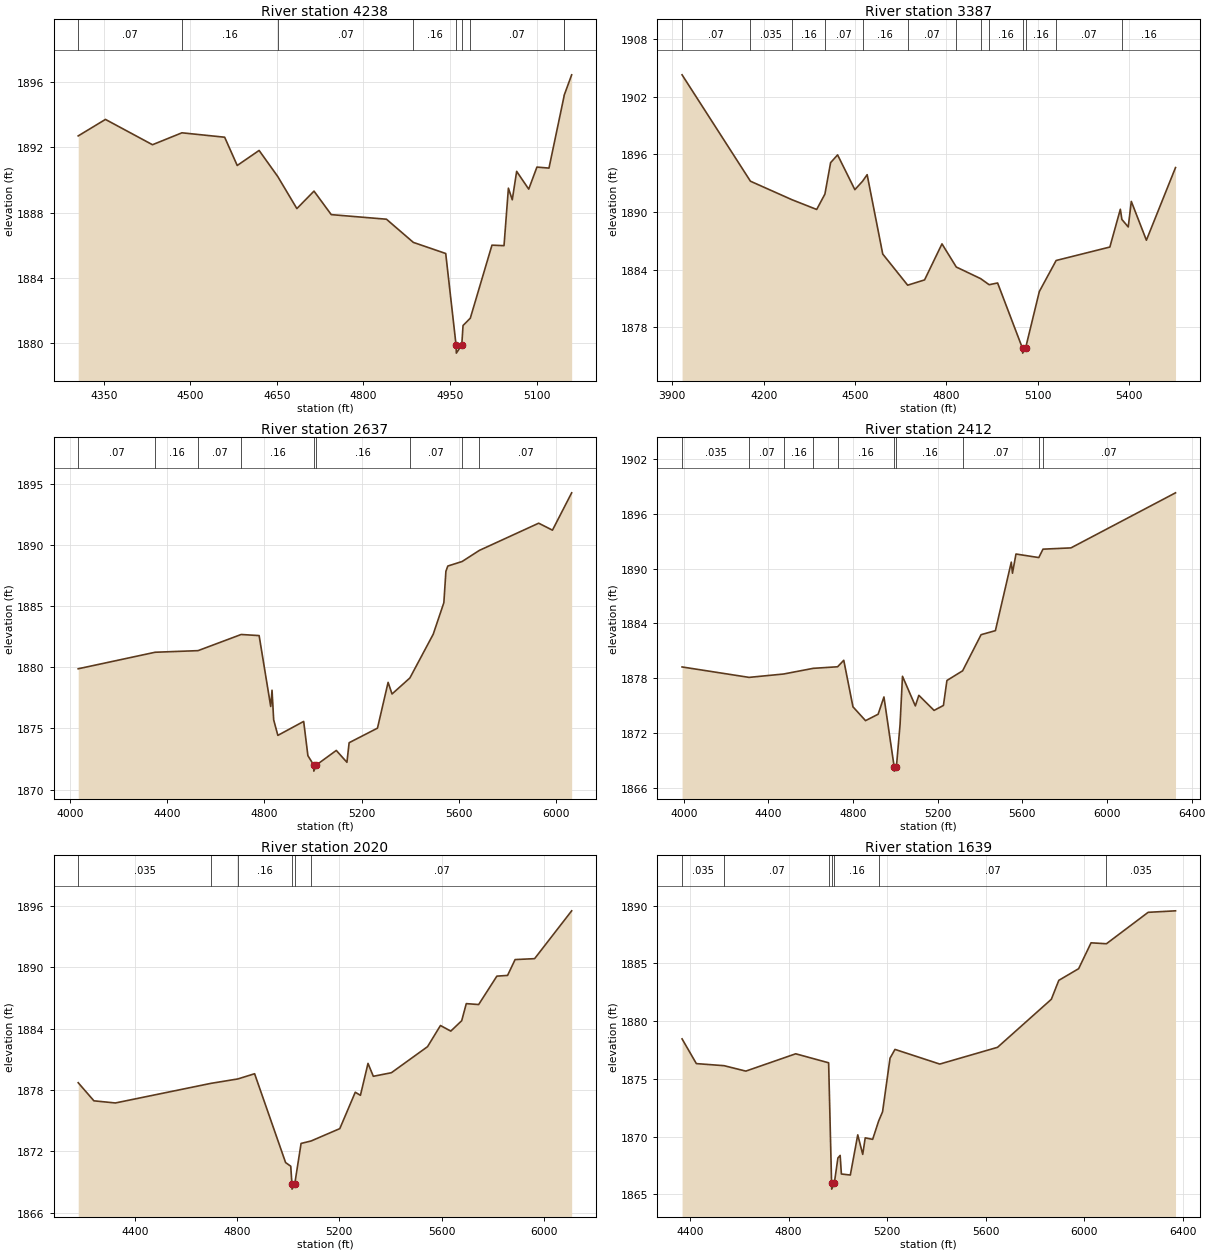
Type RM Length L Ch R = 1 ,4238    ,851,851,851
BEGIN DESCRIPTION:
Mapping XS f5979d5c
END DESCRIPTION:
XS GIS Cut Line= 3
      1505487.01      6831061.13      1506089.02      6831392.08
       1506215.9      6831502.06
#Sta/Elev= 30
  4305.8 1892.69    4353  1893.7  4434.5 1892.15  4485.5 1892.88  4559.5 1892.61
  4581.3 1890.88  4619.2  1891.8  4651.4 1890.21  4684.6 1888.24  4714.3 1889.31
  4744.2 1887.87  4839.8 1887.59  4886.4 1886.17  4942.5 1885.49  4960.4 1879.89
  4960.9 1879.39  4970.3 1879.89  4972.5 1881.08  4985.1 1881.53  5022.6    1886
  5043.5 1885.97  5051.1 1889.49  5057.8 1888.78  5065.4 1890.52  5086.3 1889.43
  5100.5 1890.78  5121.4 1890.72  5147.4  1895.1  5147.6 1895.17  5160.7 1896.43
#Mann= 9 ,-1 , 0
  4305.8     .07       0  4485.5     .16       0  4651.4     .07       0
  4886.4     .16       0  4960.4     .07       0  4970.3     .16       0
  4985.1     .07       0  5147.4     .16       0  5147.6     .07       0
Bank Sta=4960.4,4970.3
XS Rating Curve= 0 ,0
Exp/Cntr=0.3,0.1

Type RM Length L Ch R = 1 ,3387    ,750,750,750
BEGIN DESCRIPTION:
Mapping XS e66f1a6f
END DESCRIPTION:
XS GIS Cut Line= 3
      1504471.83      6831105.38      1505427.54      6831550.68
      1505989.22      6831613.09
#Sta/Elev= 30
  3932.3 1904.26  4156.7 1893.19  4293.3 1891.26  4374.1 1890.25  4401.1 1891.85
  4419.8 1895.12  4442.7 1895.93  4499.4 1892.31  4524.7 1893.19  4539.7 1893.87
  4590.9 1885.61  4672.7 1882.37  4728.2 1882.92  4785.3 1886.67  4832.3 1884.26
  4912.3 1883.05  4940.1 1882.42  4967.9  1882.6  5049.6  1875.8  5050.1  1875.3
  5059.5  1875.8  5104.8 1881.71    5160 1884.94  5336.3 1886.34  5370.7 1890.27
  5375.8 1889.21  5396.6 1888.43  5406.7 1891.09  5456.2 1887.05  5551.8 1894.61
#Mann= 13 ,-1 , 0
  3932.3     .07       0  4156.7    .035       0  4293.3     .16       0
  4401.1     .07       0  4524.7     .16       0  4672.7     .07       0
  4832.3     .16       0  4912.3     .07       0  4940.1     .16       0
  5049.6     .07       0  5059.5     .16       0    5160     .07       0
  5375.8     .16       0
Bank Sta=5049.6,5059.5
XS Rating Curve= 0 ,0
Exp/Cntr=0.3,0.1

Type RM Length L Ch R = 1 ,2637    ,225,225,225
BEGIN DESCRIPTION:
Mapping XS 739ca2a9
END DESCRIPTION:
XS GIS Cut Line= 5
      1504094.09      6832504.29      1504731.97      6832160.35
       1504954.3      6832067.85      1505737.98      6831643.81
      1505909.93       6831660.5
#Sta/Elev= 30
  4034.5 1879.87  4351.2 1881.22  4527.2 1881.35  4704.6 1882.67  4778.5 1882.58
  4826.2 1876.79  4831.6 1878.12  4838.3  1875.7  4855.5 1874.43  4961.7 1875.57
  4979.1 1872.77  5002.9 1872.01  5003.4 1871.51  5013.8 1872.01  5095.8  1873.2
  5139.6 1872.23  5148.6 1873.83  5265.2 1875.02  5308.9 1878.76  5325.1 1877.81
  5398.5 1879.12  5494.4 1882.69  5538.2 1885.27  5546.6 1887.83  5554.4 1888.26
  5613.2 1888.63  5684.4 1889.54  5928.2 1891.76  5984.8 1891.19  6063.8 1894.24
#Mann= 9 ,-1 , 0
  4034.5     .07       0  4351.2     .16       0  4527.2     .07       0
  4704.6     .16       0  5002.9     .07       0  5013.8     .16       0
  5398.5     .07       0  5613.2     .16       0  5684.4     .07       0
Bank Sta=5002.9,5013.8
XS Rating Curve= 0 ,0
Exp/Cntr=0.3,0.1

Type RM Length L Ch R = 1 ,2412    ,392,392,392
BEGIN DESCRIPTION:
Mapping XS 7b35ba6b
END DESCRIPTION:
XS GIS Cut Line= 3
      1504124.01      6832765.14      1504991.23      6832283.35
      1506180.63      6831666.53
#Sta/Elev= 30
  3991.9 1879.24  4308.6  1878.1  4472.1 1878.47  4611.9 1879.09  4726.9 1879.26
    4756 1879.97  4799.5 1874.88  4858.9 1873.37  4918.4 1874.07  4945.9 1875.96
    4994 1868.35  4994.5 1867.85  5004.9 1868.35    5022 1872.92  5033.5 1878.22
  5094.3 1874.98  5110.8 1876.14  5182.8 1874.49    5227 1875.03  5243.5 1877.76
  5317.7 1878.82    5405 1882.77  5472.6 1883.21  5547.7  1890.7  5553.3 1889.49
  5569.8 1891.59  5677.7  1891.2  5697.5 1892.12  5829.7 1892.26  6323.8 1898.28
#Mann= 10 ,-1 , 0
  3991.9    .035       0  4308.6     .07       0  4472.1     .16       0
  4611.9     .07       0  4726.9     .16       0    4994     .07       0
  5004.9     .16       0  5317.7     .07       0  5677.7    .045       0
  5697.5     .07       0
Bank Sta=4994,5004.9
XS Rating Curve= 0 ,0
Exp/Cntr=0.3,0.1

Type RM Length L Ch R = 1 ,2020    ,381,381,381
BEGIN DESCRIPTION:
Mapping XS 937f95aa
END DESCRIPTION:
XS GIS Cut Line= 3
      1504166.57      6832795.07      1504787.24      6832595.42
      1506053.33      6832773.19
#Sta/Elev= 30
  4178.3  1878.7  4239.7 1876.93  4323.7 1876.72  4697.8 1878.64  4802.7 1879.07
  4868.4 1879.58  4989.6 1870.89  5009.8 1870.53  5014.4 1868.79  5014.9 1868.29
  5025.4 1868.79  5050.2 1872.76  5089.3    1873  5201.7 1874.21  5262.2 1877.77
  5282.4 1877.47    5312 1880.59  5332.9 1879.33  5403.6 1879.68    5545 1882.23
  5595.5  1884.3  5635.9 1883.75  5678.6 1884.77  5696.5 1886.44  5744.9 1886.35
  5816.2 1889.13    5858  1889.2  5887.5 1890.75  5963.8 1890.84  6108.8 1895.52
#Mann= 6 ,-1 , 0
  4178.3    .035       0  4697.8     .07       0  4802.7     .16       0
  5014.4     .07       0  5025.4     .16       0  5089.3     .07       0
Bank Sta=5014.4,5025.4
XS Rating Curve= 0 ,0
Exp/Cntr=0.3,0.1

Type RM Length L Ch R = 1 ,1639    ,466,466,466
BEGIN DESCRIPTION:
Mapping XS 4140390c
END DESCRIPTION:
XS GIS Cut Line= 3
      1504127.48      6832838.47      1504717.79       6832916.6
      1506115.34      6833094.55
#Sta/Elev= 30
  4367.1 1878.46  4425.1 1876.32  4537.8 1876.14  4626.1 1875.67  4828.6 1877.17
  4962.4 1876.39  4974.4 1865.95  4974.9 1865.45  4985.4 1865.95  5000.1 1868.15
  5009.2 1868.37  5014.2 1866.76  5050.5 1866.67  5080.7 1870.15  5100.9 1868.46
    5111 1869.89  5141.2 1869.76  5165.6 1871.35  5181.5 1872.15  5211.8 1876.79
  5231.9 1877.55  5413.8 1876.28  5648.4 1877.73    5867 1881.89  5897.3 1883.53
  5977.9 1884.54  6028.3 1886.78  6090.8  1886.7  6260.2 1889.42  6371.4 1889.55
#Mann= 7 ,-1 , 0
  4367.1    .035       0  4537.8     .07       0  4962.4     .16       0
  4974.4     .07       0  4985.4     .16       0  5165.6     .07       0
  6090.8    .035       0
Bank Sta=4974.4,4985.4
XS Rating Curve= 0 ,0
Exp/Cntr=0.3,0.1

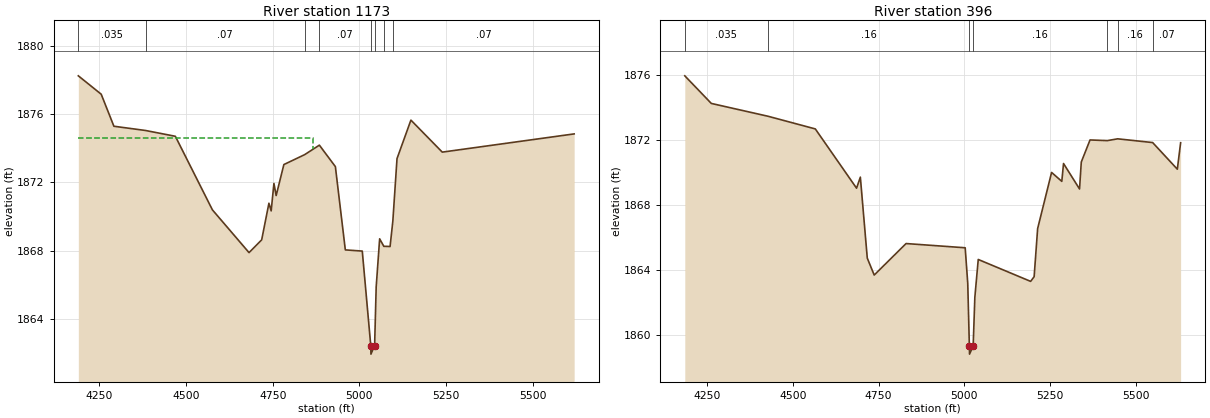
Type RM Length L Ch R = 1 ,1173    ,777,777,777
BEGIN DESCRIPTION:
Mapping XS 86c93441
END DESCRIPTION:
XS GIS Cut Line= 3
      1504075.42      6832834.13      1504691.75      6833337.61
      1505325.13      6833300.42
#Sta/Elev= 30
  4189.3 1878.26  4255.3 1877.18  4291.9  1875.3  4383.3 1875.05  4469.2 1874.71
  4576.1 1870.39  4681.7 1867.88  4718.2 1868.63  4739.1 1870.78  4745.6 1870.33
  4753.5 1871.94    4760 1871.23  4782.2 1873.05    4842 1873.63  4884.6 1874.19
  4930.8 1872.93  4959.5 1868.04  5008.4 1867.97  5032.9 1862.42  5033.4 1861.92
    5044 1862.42  5048.5 1865.86  5058.5 1868.69  5070.6 1868.25  5088.6 1868.24
  5096.6 1869.74  5108.6  1873.4  5148.7 1875.66  5239.1 1873.78  5619.6 1874.85
#Mann= 8 ,-1 , 0
  4189.3    .035       0  4383.3     .07       0    4842     .16       0
  4884.6     .07       0  5032.9     .07       0    5044     .07       0
  5070.6     .16       0  5096.6     .07       0
#XS Ineff= 2 , 0
       0  4866.9 1874.61               0
Permanent Ineff=
       F       F
Bank Sta=5032.9,5044
XS Rating Curve= 0 ,0
Exp/Cntr=0.3,0.1

Type RM Length L Ch R = 1 ,396     ,0,0,0
BEGIN DESCRIPTION:
MULBERRY CREEK TRIBUTARY 18_1 1.0
END DESCRIPTION:
XS GIS Cut Line= 3
      1504036.37      6832851.51      1504155.24       6833658.1
      1504774.41      6833778.15
#Sta/Elev= 30
  4184.7 1875.96    4262 1874.26  4427.4 1873.47  4565.3 1872.69  4685.6 1869.04
  4696.7 1869.72  4716.9 1864.73  4737.1 1863.69    4830 1865.63  5002.4 1865.37
  5009.9 1863.18  5014.6 1859.32  5015.1 1858.82  5025.7 1859.32  5030.6 1862.32
  5040.5 1864.65  5193.3  1863.3  5203.5 1863.59  5213.7 1866.55  5254.4 1870.01
  5284.2 1869.46  5289.2 1870.56  5335.9 1868.99    5341 1870.65  5366.5 1872.01
  5417.1 1871.97    5447 1872.08  5549.1 1871.85  5621.1 1870.21  5630.7 1871.84
#Mann= 7 ,-1 , 0
  4184.7    .035       0  4427.4     .16       0  5014.6     .07       0
  5025.7     .16       0  5417.1     .07       0    5447     .16       0
  5549.1     .07       0
Bank Sta=5014.6,5025.7
XS Rating Curve= 0 ,0
Exp/Cntr=0.3,0.1

Chan Stop Cuts=-1
Use User Specified Reach Order=0
Composite Channel Slope=5