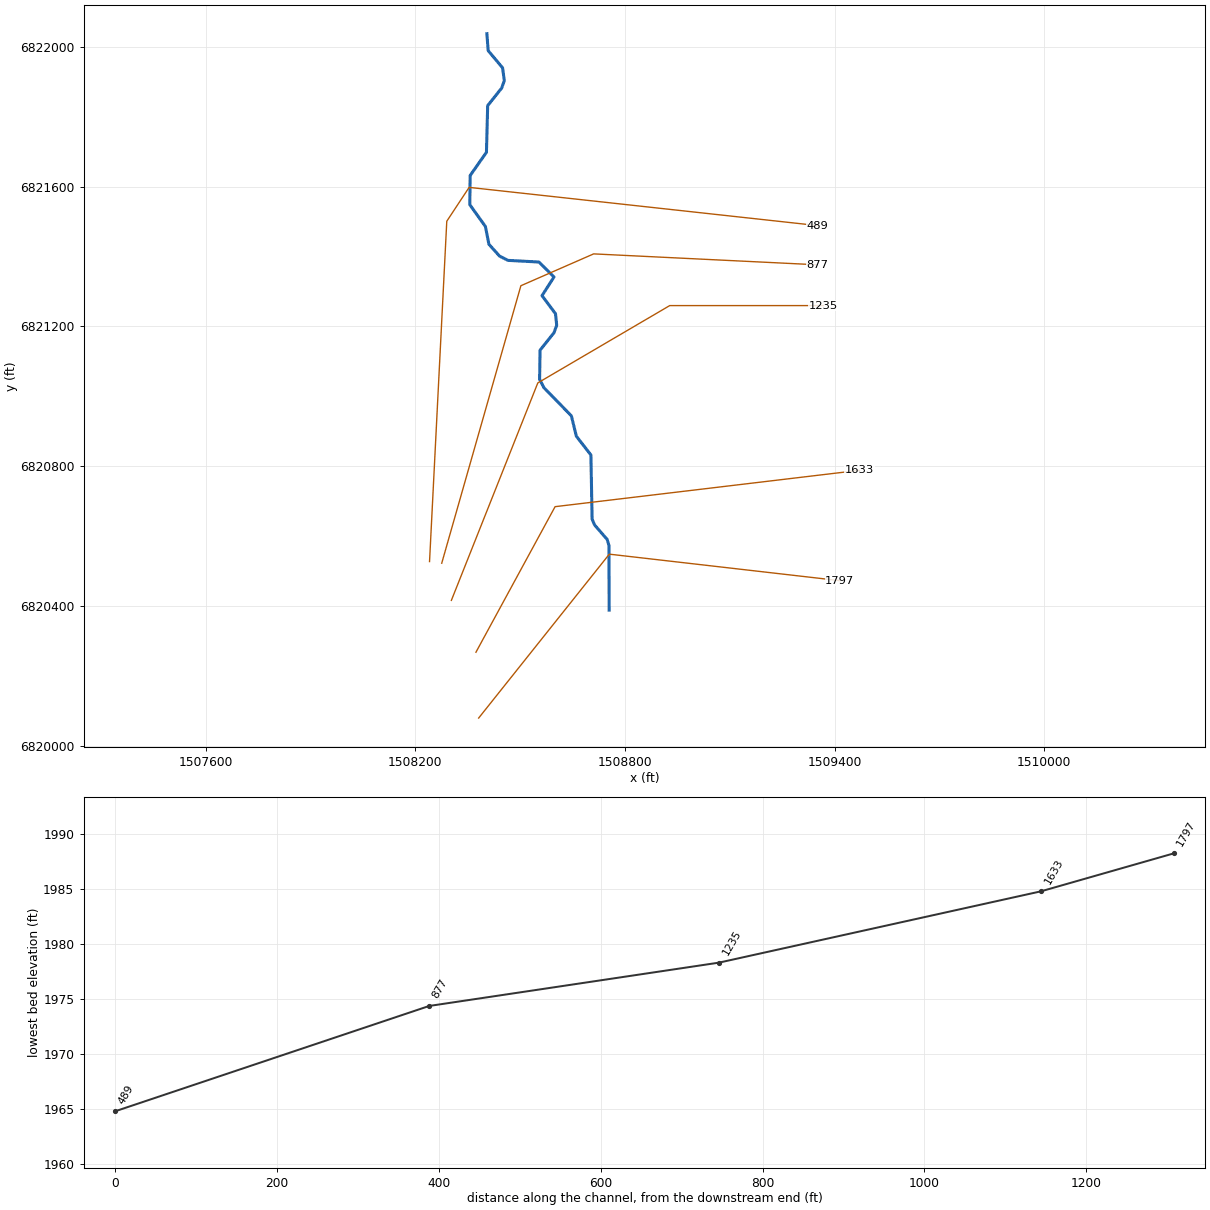
--- MULBERRY CREEK TRIBUTARY 18_1_1.prj (project) ---

Proj Title=MULBERRY CREEK TRIBUTARY 18_1_1 Base Level Engineering
Current Plan=p01
Default Exp/Contr=0.3,0.1
English Units
Geom File=g01
Flow File=f01
Plan File=p01
BEGIN DESCRIPTION:
MULBERRY CREEK TRIBUTARY 18_1_1
END DESCRIPTION:

--- MULBERRY CREEK TRIBUTARY 18_1_1.p01 (plan) ---

Plan Title=Multiple Run
Short Identifier=Multiple
Geom File=g01
Flow File=f01
Subcritical Flow
K Sum by GR= 0
Std Step Tol= 0.01
Critical Tol= 0.01
Num of Std Step Trials= 20
Max Error Tol= 0.3
Flow Tol Ratio= 0.001
Split Flow NTrial= 30
Split Flow Tol= 0.02
Split Flow Ratio= 0.02
Log Output Level= 0
Friction Slope Method= 1
Unsteady Friction Slope Method= 2
Unsteady Bridges Friction Slope Method= 1
Parabolic Critical Depth
Global Vel Dist=  1 , 1 , 1
Global Log Level= 0
CheckData=True
Encroach Param= -1, 0, 0, 0
BEGIN DESCRIPTION:
Multiple Run
END DESCRIPTION:

--- MULBERRY CREEK TRIBUTARY 18_1_1.f01 (steady flow) ---

Flow Title=Multiple
Number of Profiles=7
Profile Names=10-year,25-year,50-year,1pct_min,100-year,1pct_plu,500-year
River Rch & RM= MULBERRY CREEK T,Reach-1,1797
     145     200     247     153     305     608     468
Boundary for River Rch & Prof#=MULBERRY CREEK T,Reach-1,1
Up Type=0
Dn Type=3
Dn Slope=0.005
Boundary for River Rch & Prof#=MULBERRY CREEK T,Reach-1,2
Up Type=0
Dn Type=3
Dn Slope=0.005
Boundary for River Rch & Prof#=MULBERRY CREEK T,Reach-1,3
Up Type=0
Dn Type=3
Dn Slope=0.005
Boundary for River Rch & Prof#=MULBERRY CREEK T,Reach-1,4
Up Type=0
Dn Type=3
Dn Slope=0.005
Boundary for River Rch & Prof#=MULBERRY CREEK T,Reach-1,5
Up Type=0
Dn Type=3
Dn Slope=0.005
Boundary for River Rch & Prof#=MULBERRY CREEK T,Reach-1,6
Up Type=0
Dn Type=3
Dn Slope=0.005
Boundary for River Rch & Prof#=MULBERRY CREEK T,Reach-1,7
Up Type=0
Dn Type=3
Dn Slope=0.005

--- MULBERRY CREEK TRIBUTARY 18_1_1.g01 (geometry) ---

Geom Title=Existing Conditions

River Reach=MULBERRY CREEK T,Reach-1
Reach XY= 30
      1508755.00      6820388.00      1508754.49      6820572.79
      1508749.26      6820590.34      1508713.14      6820631.94
      1508706.22      6820648.51      1508702.76      6820832.07
      1508661.14      6820885.83      1508646.84      6820944.05
      1508568.36      6821024.71      1508555.94      6821048.48
      1508557.19      6821132.03      1508597.16      6821182.09
      1508604.85      6821203.42      1508601.41      6821236.37
      1508562.84      6821288.10      1508597.13      6821341.62
      1508553.97      6821384.38      1508465.34      6821389.10
      1508441.35      6821401.26      1508410.71      6821435.42
      1508400.76      6821486.22      1508356.08      6821548.54
      1508357.17      6821632.02      1508403.77      6821698.51
      1508407.29      6821832.07      1508447.19      6821882.08
      1508454.95      6821903.39      1508449.88      6821940.25
      1508408.69      6821989.49      1508405.00      6822038.00

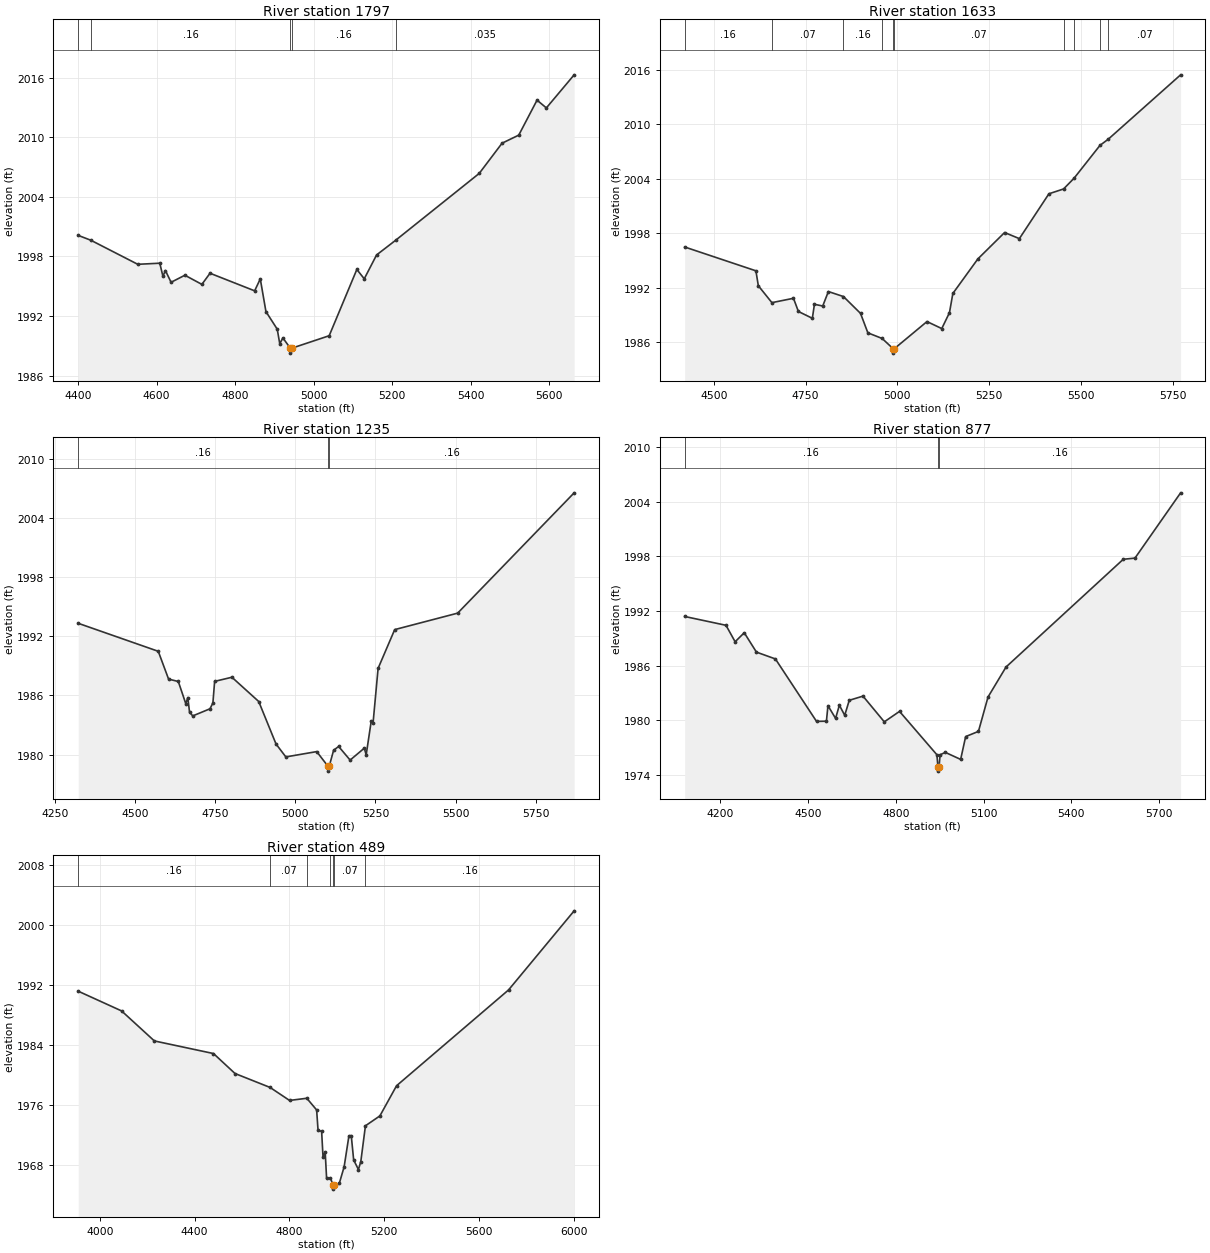
Type RM Length L Ch R = 1,1797,164,164,164
BEGIN DESCRIPTION:
MULBERRY CREEK TRIBUTARY 18_1_1 2.0
END DESCRIPTION:
XS GIS Cut Line= 3
      1508381.51      6820079.12      1508755.47      6820548.19
      1509415.32      6820472.36
#Sta/Elev= 30
  4400.1 2000.12  4432.4 1999.63  4551.9 1997.21  4608.0 1997.32  4616.0 1996.01
  4622.4 1996.58  4636.8 1995.40  4672.0 1996.11  4715.3 1995.19  4736.1 1996.31
  4849.8 1994.54  4864.2 1995.74  4878.6 1992.45  4907.4 1990.68  4913.8 1989.22
  4921.8 1989.80  4940.7 1988.77  4940.9 1988.27  4944.7 1988.77  5039.8 1990.02
  5110.3 1996.69  5129.2 1995.75  5160.6 1998.15  5208.9 1999.62  5422.3 2006.36
  5480.5 2009.40  5523.0 2010.21  5569.6 2013.73  5593.4 2012.95  5664.2 2016.28
#Mann=5,-1,0
  4400.1   0.035       0  4432.4    0.16       0  4940.7    0.07       0
  4944.7    0.16       0  5208.9   0.035       0
Bank Sta=4940.7,4944.7
Exp/Cntr=0.3,0.1

Type RM Length L Ch R = 1,1633,398,398,398
BEGIN DESCRIPTION:
Mapping XS 61b5fcc6
END DESCRIPTION:
XS GIS Cut Line= 3
      1508373.72      6820267.52      1508600.27      6820684.16
      1509471.32      6820788.17
#Sta/Elev= 30
  4420.6 1996.49  4614.7 1993.87  4621.3 1992.23  4658.3 1990.37  4717.1 1990.85
  4730.5 1989.40  4768.5 1988.65  4774.2 1990.19  4796.8 1990.00  4812.2 1991.59
  4853.3 1991.04  4899.8 1989.19  4919.8 1987.05  4958.8 1986.43  4988.3 1985.32
  4988.5 1984.82  4992.3 1985.32  5080.9 1988.29  5121.2 1987.52  5142.2 1989.27
  5151.4 1991.38  5219.6 1995.18  5292.4 1998.08  5332.7 1997.41  5413.2 2002.34
  5453.1 2002.87  5481.7 2004.05  5552.5 2007.67  5574.6 2008.33  5772.1 2015.42
#Mann=10,-1,0
  4420.6    0.16       0  4658.3    0.07       0  4853.3    0.16       0
  4958.8    0.07       0  4988.3    0.07       0  4992.3    0.07       0
  5453.1    0.16       0  5481.7    0.07       0  5552.5    0.16       0
  5574.6    0.07       0
Bank Sta=4988.3,4992.3
Exp/Cntr=0.3,0.1

Type RM Length L Ch R = 1,1235,358,358,358
BEGIN DESCRIPTION:
Mapping XS d7d543a3
END DESCRIPTION:
XS GIS Cut Line= 4
      1508303.38      6820415.91      1508550.79      6821038.33
      1508928.39      6821259.68      1509368.50      6821259.68
#Sta/Elev= 30
  4322.4 1993.32  4572.2 1990.48  4604.4 1987.66  4634.7 1987.42  4658.2 1985.16
  4664.4 1985.79  4669.8 1984.31  4679.8 1983.93  4733.6 1984.65  4742.7 1985.24
  4748.1 1987.43  4802.0 1987.85  4885.7 1985.39  4939.7 1981.08  4970.3 1979.77
  5066.6 1980.31  5101.7 1978.83  5102.0 1978.33  5105.7 1978.83  5119.4 1980.45
  5135.1 1980.83  5170.9 1979.45  5215.2 1980.66  5221.0 1979.98  5236.7 1983.38
  5242.5 1983.21  5258.2 1988.75  5310.0 1992.68  5506.5 1994.35  5870.0 2006.55
#Mann=3,-1,0
  4322.4    0.16       0  5101.7    0.07       0  5105.7    0.16       0
Bank Sta=5101.7,5105.7
Exp/Cntr=0.3,0.1

Type RM Length L Ch R = 1,877,388,388,388
BEGIN DESCRIPTION:
Mapping XS 02f760d9
END DESCRIPTION:
XS GIS Cut Line= 4
      1508275.78      6820522.28      1508502.34      6821316.53
      1508710.67      6821407.68      1509350.69      6821376.45
#Sta/Elev= 30
  4079.2 1991.40  4220.3 1990.43  4251.5 1988.62  4282.7 1989.61  4324.3 1987.48
  4389.1 1986.73  4529.6 1979.86  4563.4 1979.88  4568.6 1981.59  4594.7 1980.19
  4607.6 1981.64  4625.9 1980.53  4641.4 1982.18  4688.3 1982.64  4761.1 1979.81
  4813.1 1980.96  4940.8 1976.19  4944.2 1974.89  4944.5 1974.39  4948.2 1974.89
  4951.7 1976.19  4969.6 1976.45  5021.9 1975.68  5039.0 1978.19  5082.7 1978.76
  5115.4 1982.54  5176.9 1985.84  5577.4 1997.69  5617.4 1997.82  5773.3 2005.00
#Mann=3,-1,0
  4079.2    0.16       0  4944.2    0.07       0  4948.2    0.16       0
Bank Sta=4944.2,4948.2
Exp/Cntr=0.3,0.1

Type RM Length L Ch R = 1,489,0,0,0
BEGIN DESCRIPTION:
MULBERRY CREEK TRIBUTARY 18_1_1 1.0
END DESCRIPTION:
XS GIS Cut Line= 4
      1508240.89      6820527.01      1508290.24      6821501.14
      1508354.22      6821598.05      1509350.16      6821488.86
#Sta/Elev= 30
  3908.5 1991.19  4091.6 1988.56  4229.9 1984.56  4479.5 1982.88  4570.3 1980.22
  4718.5 1978.36  4800.6 1976.63  4873.4 1976.92  4914.9 1975.36  4920.9 1972.64
  4936.0 1972.51  4941.9 1969.08  4951.0 1969.78  4957.0 1966.23  4973.1 1966.27
  4985.1 1965.31  4985.4 1964.81  4989.1 1965.31  5010.8 1965.60  5031.0 1967.79
  5051.2 1971.91  5061.1 1971.93  5071.2 1968.70  5091.3 1967.42  5101.4 1968.49
  5120.9 1973.25  5181.9 1974.57  5252.3 1978.59  5725.1 1991.36  6001.9 2001.90
#Mann=7,-1,0
  3908.5    0.16       0  4718.5    0.07       0  4873.4    0.16       0
  4973.1    0.07       0  4985.1    0.07       0  4989.1    0.07       0
  5120.9    0.16       0
Bank Sta=4985.1,4989.1
Exp/Cntr=0.3,0.1

Chan Stop Cuts=-1