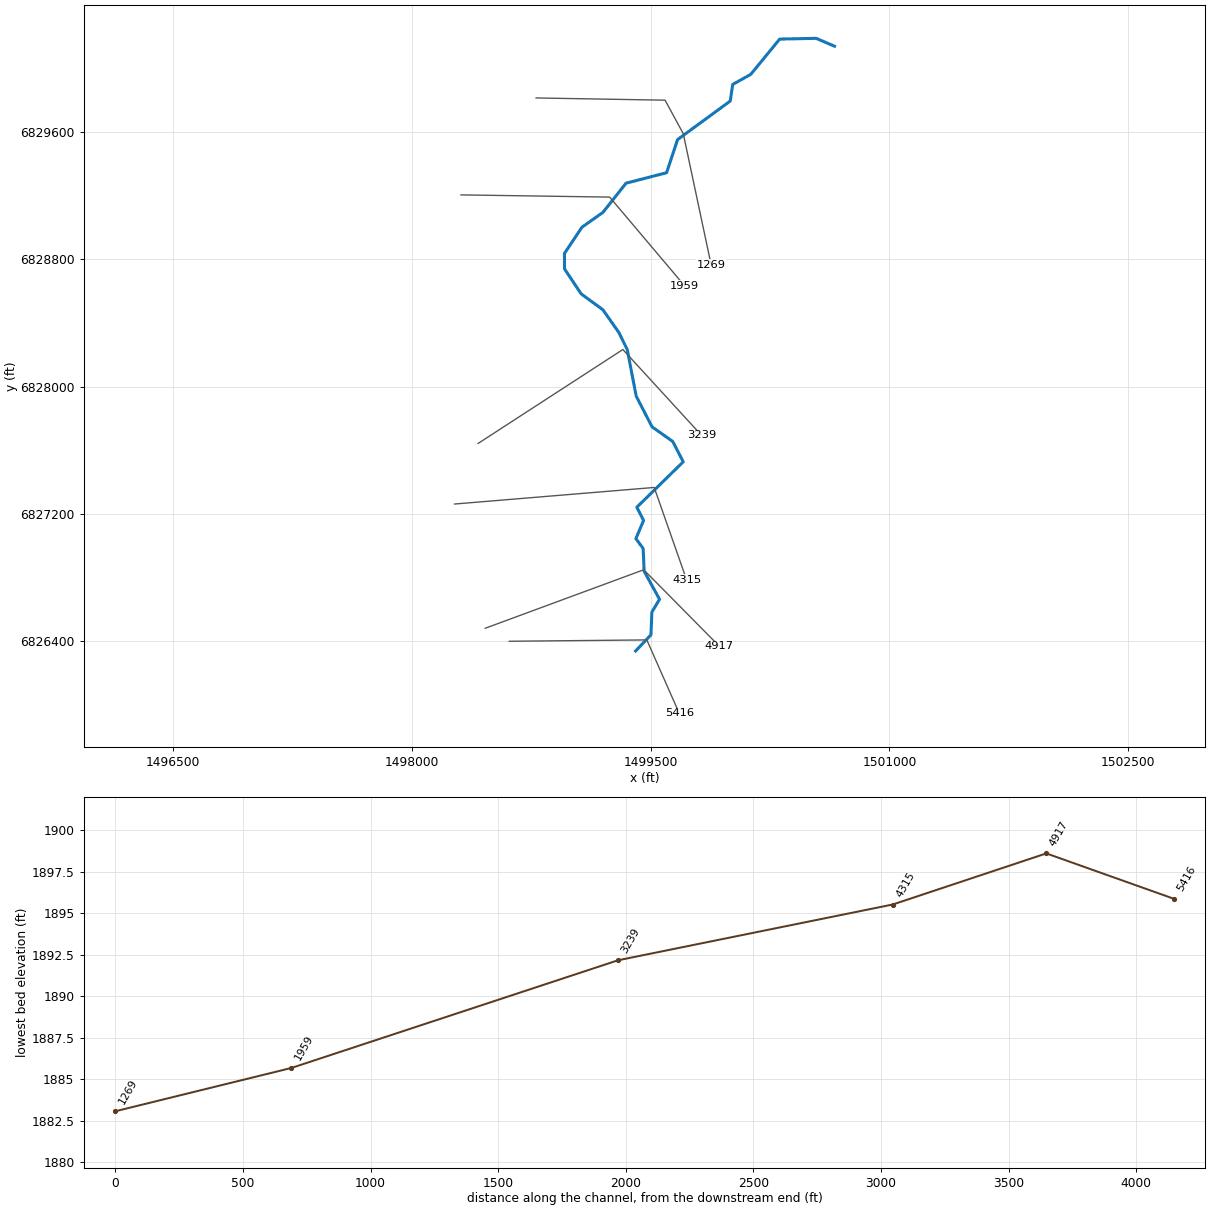
--- MULBERRY CREEK TRIBUTARY 18_2.prj (project) ---

Proj Title=MULBERRY CREEK TRIBUTARY 18_2 Base Level Engineering
Current Plan=p01
Default Exp/Contr=0.3,0.1
English Units
Geom File=g01
Flow File=f01
Plan File=p01
BEGIN DESCRIPTION:
MULBERRY CREEK TRIBUTARY 18_2
END DESCRIPTION:

--- MULBERRY CREEK TRIBUTARY 18_2.p01 (plan) ---

Plan Title=Multiple Run
Short Identifier=Multiple
Geom File=g01
Flow File=f01
Subcritical Flow
K Sum by GR= 0
Std Step Tol= 0.01
Critical Tol= 0.01
Num of Std Step Trials= 20
Max Error Tol= 0.3
Flow Tol Ratio= 0.001
Split Flow NTrial= 30
Split Flow Tol= 0.02
Split Flow Ratio= 0.02
Log Output Level= 0
Friction Slope Method= 1
Unsteady Friction Slope Method= 2
Unsteady Bridges Friction Slope Method= 1
Parabolic Critical Depth
Global Vel Dist=  1 , 1 , 1
Global Log Level= 0
CheckData=True
Encroach Param= -1, 0, 0, 0
BEGIN DESCRIPTION:
Multiple Run
END DESCRIPTION:

--- MULBERRY CREEK TRIBUTARY 18_2.f01 (steady flow) ---

Flow Title=Multiple
Number of Profiles=7
Profile Names=10-year,25-year,50-year,1pct_min,100-year,1pct_plu,500-year
River Rch & RM= MULBERRY CREEK T,Reach-1,5416
     238     329     403     246     491     980     736
River Rch & RM= MULBERRY CREEK T,Reach-1,1959
     272     380     470     289     576    1149     876
Boundary for River Rch & Prof#=MULBERRY CREEK T,Reach-1,1
Up Type=0
Dn Type=3
Dn Slope=0.005
Boundary for River Rch & Prof#=MULBERRY CREEK T,Reach-1,2
Up Type=0
Dn Type=3
Dn Slope=0.005
Boundary for River Rch & Prof#=MULBERRY CREEK T,Reach-1,3
Up Type=0
Dn Type=3
Dn Slope=0.005
Boundary for River Rch & Prof#=MULBERRY CREEK T,Reach-1,4
Up Type=0
Dn Type=3
Dn Slope=0.005
Boundary for River Rch & Prof#=MULBERRY CREEK T,Reach-1,5
Up Type=0
Dn Type=3
Dn Slope=0.005
Boundary for River Rch & Prof#=MULBERRY CREEK T,Reach-1,6
Up Type=0
Dn Type=3
Dn Slope=0.005
Boundary for River Rch & Prof#=MULBERRY CREEK T,Reach-1,7
Up Type=0
Dn Type=3
Dn Slope=0.005

--- MULBERRY CREEK TRIBUTARY 18_2.g01 (geometry) ---

Geom Title=Existing Conditions

River Reach=MULBERRY CREEK T,Reach-1
Reach XY= 30
      1499405.00      6826338.00      1499501.51      6826439.45
      1499507.30      6826582.07      1499555.41      6826663.00
      1499458.76      6826839.56      1499452.70      6826982.07
      1499406.83      6827044.12      1499455.19      6827158.20
      1499412.82      6827241.41      1499704.46      6827526.91
      1499638.37      6827654.71      1499508.51      6827746.48
      1499408.83      6827939.58      1499352.75      6828232.07
      1499299.16      6828340.29      1499199.38      6828482.38
      1499063.15      6828581.93      1498958.46      6828739.49
      1498958.18      6828836.59      1499068.56      6829001.26
      1499199.38      6829093.62      1499345.21      6829277.48
      1499599.89      6829343.11      1499668.61      6829551.24
      1499999.74      6829793.48      1500015.40      6829898.06
      1500128.46      6829961.02      1500310.44      6830182.82
      1500539.81      6830187.55      1500655.00      6830138.00

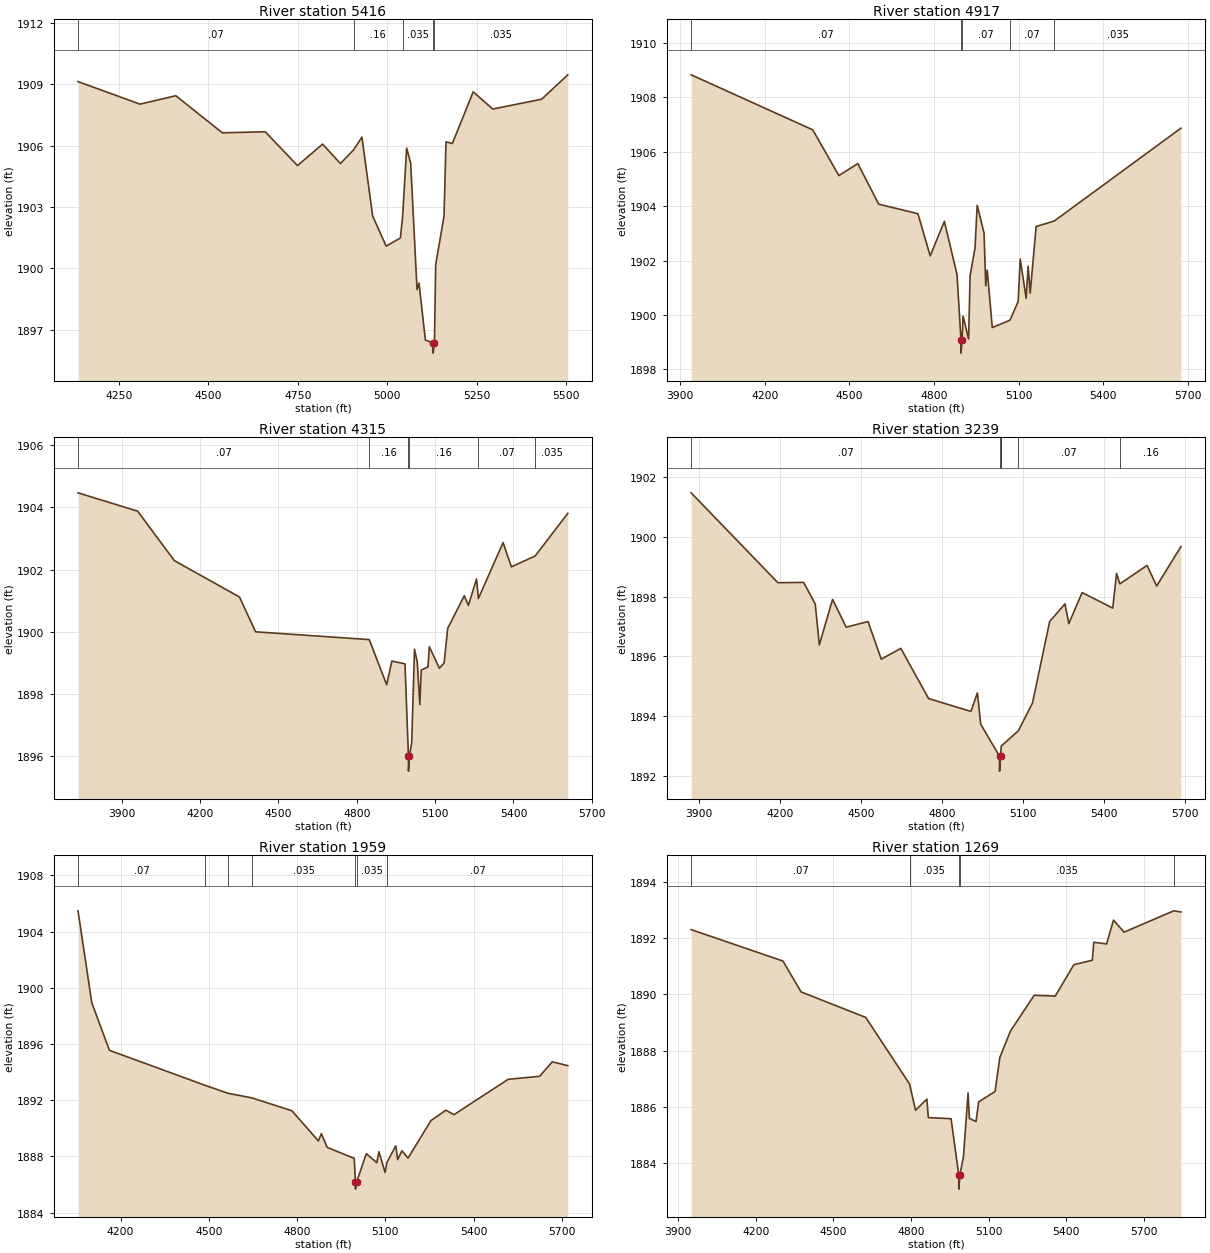
Type RM Length L Ch R = 1,5416,499,499,499
BEGIN DESCRIPTION:
MULBERRY CREEK TRIBUTARY 18_2 2.0
END DESCRIPTION:
XS GIS Cut Line= 3
      1498611.85      6826399.30      1499475.60      6826407.75
      1499679.56      6825946.21
#Sta/Elev= 30
  4136.2 1909.12  4309.4 1908.02  4409.4 1908.43  4539.4 1906.62  4659.4 1906.67
  4749.4 1905.02  4819.4 1906.07  4869.4 1905.12  4906.2 1905.79  4929.4 1906.41
  4959.4 1902.56  4997.2 1901.09  5036.8 1901.49  5043.0 1902.52  5054.4 1905.87
  5065.6 1905.14  5083.4 1898.97  5088.9 1899.29  5106.7 1896.51  5128.0 1896.37
  5128.3 1895.87  5132.0 1896.37  5135.5 1900.19  5158.8 1902.55  5164.3 1906.18
  5182.1 1906.10  5240.3 1908.62  5294.9 1907.78  5431.5 1908.26  5504.6 1909.45
#Mann=5,-1,0
  4136.2    0.07       0  4906.2    0.16       0  5043.0   0.035       0
  5128.0    0.07       0  5132.0   0.035       0
Bank Sta=5128,5132
Exp/Cntr=0.3,0.1

Type RM Length L Ch R = 1,4917,602,602,602
BEGIN DESCRIPTION:
MULBERRY CREEK TRIBUTARY 18_2 1.0
END DESCRIPTION:
XS GIS Cut Line= 3
      1498460.37      6826480.97      1499456.21      6826848.50
      1499931.22      6826367.94
#Sta/Elev= 30
  3938.5 1908.82  4369.8 1906.80  4462.3 1905.12  4529.7 1905.56  4603.8 1904.07
  4742.9 1903.72  4786.4 1902.17  4836.6 1903.44  4881.5 1901.49  4895.5 1899.10
  4895.7 1898.60  4899.5 1899.10  4902.8 1899.96  4922.6 1899.12  4927.9 1901.44
  4945.4 1902.46  4953.0 1904.03  4977.4 1903.01  4983.4 1901.07  4988.7 1901.65
  5006.6 1899.54  5069.4 1899.81  5098.5 1900.50  5105.6 1902.06  5126.8 1900.61
  5133.8 1901.79  5141.0 1900.80  5162.1 1903.25  5226.2 1903.45  5675.7 1906.86
#Mann=5,-1,0
  3938.5    0.07       0  4895.5    0.07       0  4899.5    0.07       0
  5069.4    0.07       0  5226.2   0.035       0
Bank Sta=4895.5,4899.5
Exp/Cntr=0.3,0.1

Type RM Length L Ch R = 1,4315,1076,1076,1076
BEGIN DESCRIPTION:
Mapping XS 9a707f3d
END DESCRIPTION:
XS GIS Cut Line= 3
      1498267.58      6827261.55      1499521.96      6827365.72
      1499725.94      6826784.15
#Sta/Elev= 30
  3732.9 1904.47  3961.1 1903.88  4101.6 1902.29  4351.0 1901.12  4412.7 1900.00
  4847.8 1899.75  4914.4 1898.30  4934.4 1899.06  4984.6 1898.97  4997.8 1896.02
  4998.0 1895.52  5001.8 1896.02  5010.4 1896.44  5021.1 1899.44  5031.6 1899.03
  5041.5 1897.66  5046.8 1898.77  5072.5 1898.87  5077.8 1899.52  5116.3 1898.83
  5134.5 1899.00  5148.1 1900.11  5211.7 1901.16  5227.5 1900.85  5258.5 1901.70
  5265.6 1901.07  5360.1 1902.87  5391.9 1902.09  5483.0 1902.44  5607.9 1903.81
#Mann=6,-1,0
  3732.9    0.07       0  4847.8    0.16       0  4997.8    0.07       0
  5001.8    0.16       0  5265.6    0.07       0  5483.0   0.035       0
Bank Sta=4997.8,5001.8
Exp/Cntr=0.3,0.1

Type RM Length L Ch R = 1,3239,1280,1280,1280
BEGIN DESCRIPTION:
Mapping XS 4e9c3361
END DESCRIPTION:
XS GIS Cut Line= 3
      1498415.48      6827642.11      1499325.16      6828232.36
      1499818.22      6827694.17
#Sta/Elev= 30
  3870.9 1901.48  4192.2 1898.47  4287.5 1898.48  4330.5 1897.76  4345.7 1896.39
  4394.8 1897.91  4445.3 1896.98  4526.0 1897.17  4575.1 1895.91  4647.6 1896.27
  4750.4 1894.59  4907.4 1894.16  4931.3 1894.78  4943.6 1893.73  5013.2 1892.66
  5013.4 1892.16  5017.2 1892.66  5019.6 1893.00  5082.9 1893.51  5135.4 1894.44
  5198.9 1897.17  5255.7 1897.76  5269.8 1897.10  5319.2 1898.14  5432.6 1897.62
  5446.8 1898.78  5459.0 1898.43  5559.7 1899.05  5595.4 1898.36  5685.2 1899.68
#Mann=6,-1,0
  3870.9    0.07       0  5013.2    0.07       0  5017.2    0.07       0
  5019.6   0.035       0  5082.9    0.07       0  5459.0    0.16       0
Bank Sta=5013.2,5017.2
Exp/Cntr=0.3,0.1

Type RM Length L Ch R = 1,1959,690,690,690
BEGIN DESCRIPTION:
Mapping XS 1496ef0f
END DESCRIPTION:
XS GIS Cut Line= 3
      1498308.18      6829203.89      1499242.18      6829190.00
      1499713.57      6828631.96
#Sta/Elev= 30
  4055.6 1905.48  4102.4 1898.93  4162.4 1895.55  4487.4 1893.06  4565.7 1892.49
  4645.7 1892.17  4782.5 1891.25  4872.5 1889.10  4882.5 1889.62  4902.5 1888.64
  4994.3 1887.86  4998.3 1886.17  4998.6 1885.67  5002.3 1886.17  5035.5 1888.19
  5070.9 1887.56  5078.4 1888.33  5099.2 1886.86  5105.3 1887.56  5135.5 1888.75
  5142.1 1887.77  5156.4 1888.40  5177.2 1887.88  5255.2 1890.55  5305.9 1891.29
  5333.2 1890.97  5517.8 1893.49  5624.4 1893.70  5667.3 1894.73  5720.2 1894.46
#Mann=7,-1,0
  4055.6    0.07       0  4487.4   0.035       0  4565.7    0.07       0
  4645.7   0.035       0  4998.3   0.035       0  5002.3   0.035       0
  5105.3    0.07       0
Bank Sta=4998.3,5002.3
Exp/Cntr=0.3,0.1

Type RM Length L Ch R = 1,1269,0,0,0
BEGIN DESCRIPTION:
MULBERRY CREEK TRIBUTARY 18_2 0.0
END DESCRIPTION:
XS GIS Cut Line= 4
      1498779.97      6829813.00      1499590.34      6829798.96
      1499704.67      6829588.28      1499880.00      6828763.00
#Sta/Elev= 30
  3949.8 1892.31  4304.9 1891.19  4374.9 1890.09  4624.9 1889.18  4794.2 1886.81
  4817.5 1885.87  4861.3 1886.27  4866.9 1885.61  4954.8 1885.57  4984.7 1883.56
  4984.9 1883.06  4988.8 1883.56  5002.7 1884.21  5020.6 1886.49  5025.8 1885.58
  5051.4 1885.47  5061.6 1886.17  5125.0 1886.54  5143.4 1887.75  5184.3 1888.69
  5276.3 1889.97  5357.7 1889.94  5429.7 1891.06  5501.2 1891.22  5506.6 1891.86
  5556.2 1891.80  5583.0 1892.65  5623.9 1892.22  5816.0 1892.98  5843.7 1892.94
#Mann=5,-1,0
  3949.8    0.07       0  4794.2   0.035       0  4984.7   0.035       0
  4988.8   0.035       0  5816.0    0.07       0
Bank Sta=4984.7,4988.8
Exp/Cntr=0.3,0.1

Chan Stop Cuts=-1