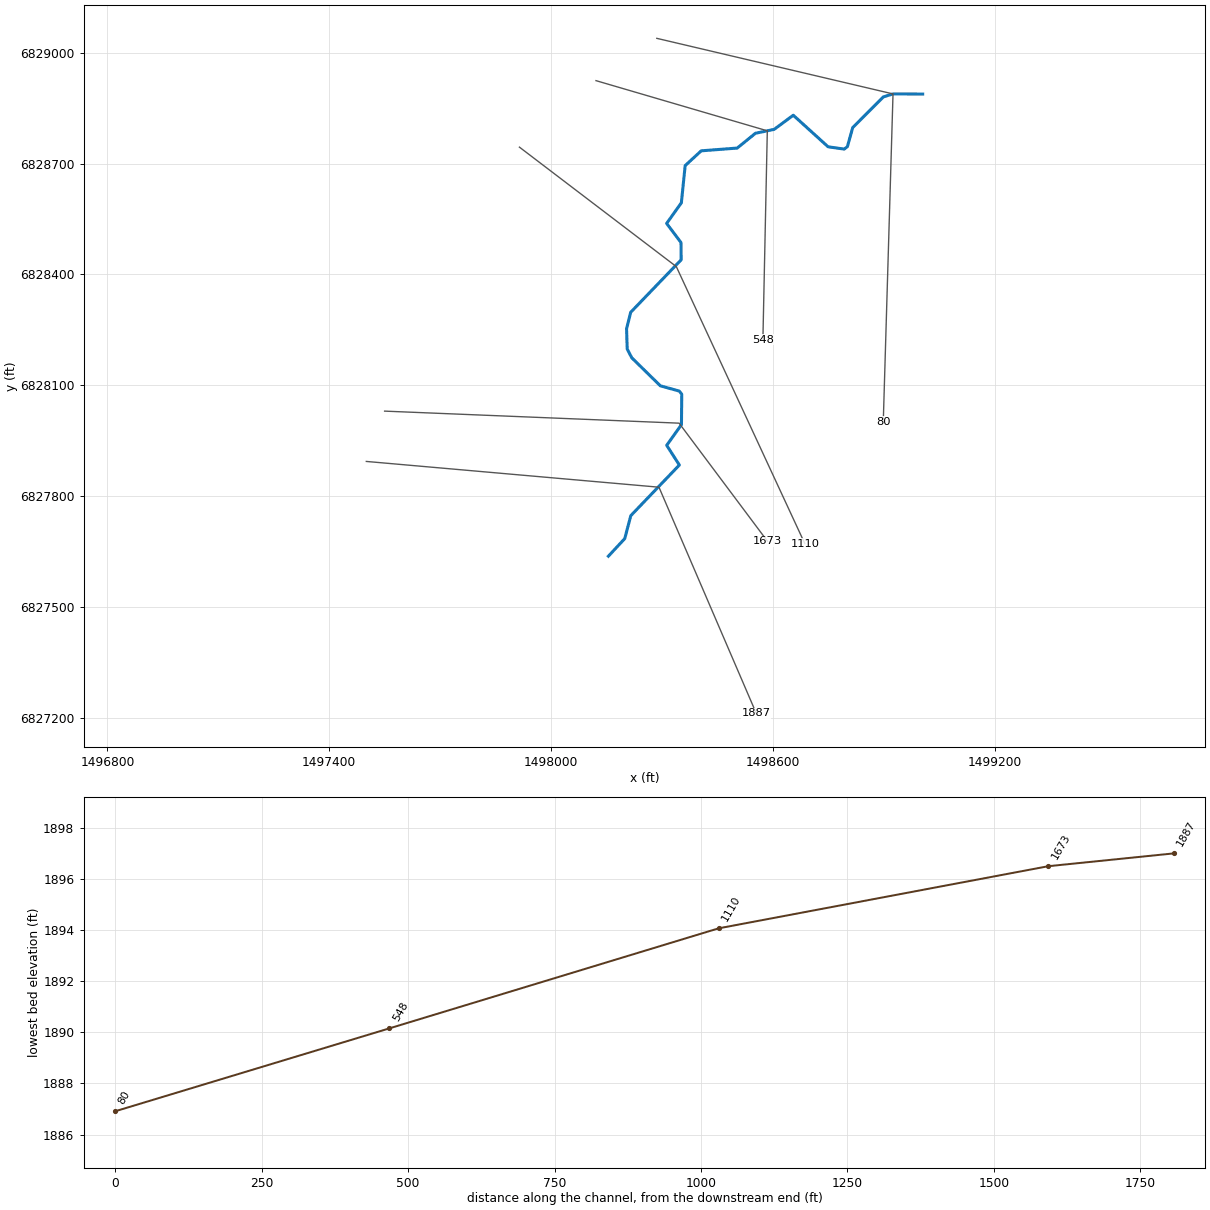
--- MULBERRY CREEK TRIBUTARY 18_2_1.prj (project) ---

Proj Title=MULBERRY CREEK TRIBUTARY 18_2_1 Base Level Engineering
Current Plan=p01
Default Exp/Contr=0.3,0.1
English Units
Geom File=g01
Flow File=f01
Plan File=p01
Y Axis Title=Elevation
X Axis Title(PF)=Main Channel Distance
X Axis Title(XS)=Station
BEGIN DESCRIPTION:
MULBERRY CREEK TRIBUTARY 18_2_1
END DESCRIPTION:
DSS Export Rating Curves= 0
DSS Export Rating Curve Sorted= 0
DSS Export Volume Flow Curves= 0
DXF OffsetX= 0
DXF OffsetY= 0
DXF ScaleX= 1
DXF ScaleY= 10

--- MULBERRY CREEK TRIBUTARY 18_2_1.p01 (plan) ---

Plan Title=Multiple Run
Short Identifier=Multiple
Geom File=g01
Flow File=f01
Subcritical Flow
K Sum by GR= 0
Std Step Tol= 0.01
Critical Tol= 0.01
Num of Std Step Trials= 20
Max Error Tol= 0.3
Flow Tol Ratio= 0.001
Split Flow NTrial= 30
Split Flow Tol= 0.02
Split Flow Ratio= 0.02
Log Output Level= 0
Friction Slope Method= 1
Unsteady Friction Slope Method= 2
Unsteady Bridges Friction Slope Method= 1
Parabolic Critical Depth
Global Vel Dist=  1 , 1 , 1
Global Log Level= 0
CheckData=True
Encroach Param= -1, 0, 0, 0
BEGIN DESCRIPTION:
Multiple Run
END DESCRIPTION:

--- MULBERRY CREEK TRIBUTARY 18_2_1.f01 (steady flow) ---

Flow Title=Multiple
Program Version=4.10
Number of Profiles= 7
Profile Names=10-year,25-year,50-year,1pct_min,100-year,1pct_plu,500-year
River Rch & RM=MULBERRY CREEK T,Reach-1         ,1887
      82     106     124      73     146     291     203
Boundary for River Rch & Prof#=MULBERRY CREEK T,Reach-1         , 1
Up Type= 0
Dn Type= 3
Dn Slope=0.007
Boundary for River Rch & Prof#=MULBERRY CREEK T,Reach-1         , 2
Up Type= 0
Dn Type= 3
Dn Slope=0.007
Boundary for River Rch & Prof#=MULBERRY CREEK T,Reach-1         , 3
Up Type= 0
Dn Type= 3
Dn Slope=0.007
Boundary for River Rch & Prof#=MULBERRY CREEK T,Reach-1         , 4
Up Type= 0
Dn Type= 3
Dn Slope=0.007
Boundary for River Rch & Prof#=MULBERRY CREEK T,Reach-1         , 5
Up Type= 0
Dn Type= 3
Dn Slope=0.007
Boundary for River Rch & Prof#=MULBERRY CREEK T,Reach-1         , 6
Up Type= 0
Dn Type= 3
Dn Slope=0.007
Boundary for River Rch & Prof#=MULBERRY CREEK T,Reach-1         , 7
Up Type= 0
Dn Type= 3
Dn Slope=0.007
DSS Import GetInterval= 0
DSS Import GetPeak= 0
DSS Import FillOption= 0

--- MULBERRY CREEK TRIBUTARY 18_2_1.g01 (geometry) ---

Geom Title=Existing Conditions

River Reach=MULBERRY CREEK T,Reach-1
Reach XY= 30
      1498155.00      6827638.00      1498199.29      6827685.65
      1498215.70      6827747.71      1498347.01      6827884.66
      1498312.81      6827937.90      1498352.68      6827993.98
      1498353.48      6828076.12      1498346.95      6828084.59
      1498295.61      6828098.89      1498218.33      6828174.67
      1498205.93      6828198.48      1498204.21      6828253.08
      1498215.43      6828297.78      1498351.84      6828439.65
      1498351.43      6828486.35      1498312.59      6828537.99
      1498352.44      6828593.90      1498362.72      6828694.50
      1498406.25      6828734.49      1498503.41      6828741.83
      1498552.83      6828781.91      1498603.37      6828792.43
      1498655.09      6828830.70      1498749.25      6828745.38
      1498792.97      6828739.13      1498801.45      6828745.72
      1498815.88      6828797.35      1498898.76      6828880.27
      1498924.86      6828888.33      1499005.00      6828888.00

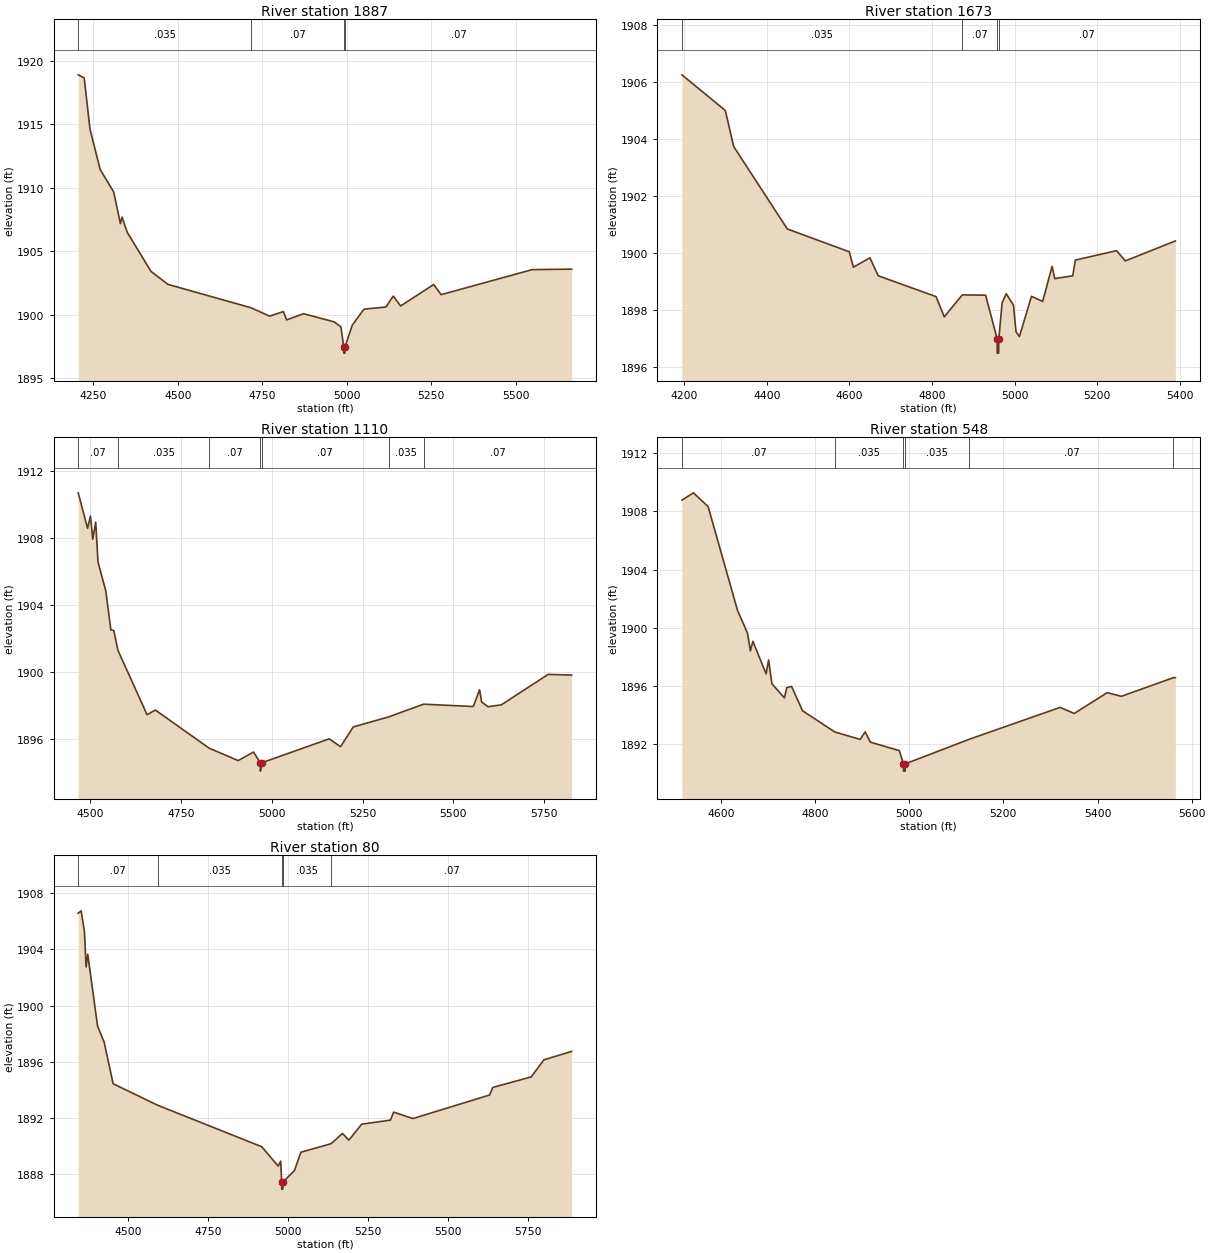
Type RM Length L Ch R = 1,1887,214,214,214
BEGIN DESCRIPTION:
MULBERRY CREEK TRIBUTARY 18_2_1 2.0
END DESCRIPTION:
XS GIS Cut Line= 3
      1497500.34      6827894.37      1498291.87      6827824.68
      1498555.03      6827212.98
#Sta/Elev= 30
  4205.4 1918.89  4223.1 1918.65  4240.2 1914.63  4270.3 1911.45  4310.5 1909.67
  4330.3 1907.18  4335.3 1907.69  4350.6 1906.49  4420.9 1903.42  4471.1 1902.40
  4716.9 1900.56  4772.2 1899.90  4812.4 1900.26  4822.4 1899.61  4872.6 1900.09
  4963.0 1899.45  4983.1 1899.05  4991.1 1897.49  4991.4 1896.99  4994.9 1896.99
  4995.1 1897.49  5016.6 1899.19  5051.1 1900.45  5116.1 1900.62  5137.9 1901.48
  5159.7 1900.70  5257.7 1902.39  5279.4 1901.59  5549.0 1903.56  5665.9 1903.60
#Mann=4,-1,0
  4205.4   0.035       0  4716.9    0.07       0  4991.1    0.07       0
  4995.1    0.07       0
Bank Sta=4991.1,4995.1
Exp/Cntr=0.3,0.1

Type RM Length L Ch R = 1,1673,563,563,563
BEGIN DESCRIPTION:
Mapping XS b93112f3
END DESCRIPTION:
XS GIS Cut Line= 3
      1497549.85      6828030.43      1498346.32      6827997.88
      1498585.05      6827678.85
#Sta/Elev= 30
  4194.1 1906.24  4299.3 1904.99  4319.4 1903.73  4449.5 1900.84  4599.6 1900.04
  4609.6 1899.50  4649.6 1899.83  4669.7 1899.20  4809.8 1898.47  4829.8 1897.76
  4873.4 1898.53  4929.9 1898.52  4957.9 1896.99  4958.1 1896.49  4961.6 1896.49
  4961.9 1896.99  4969.9 1898.25  4979.9 1898.57  4997.4 1898.17  5003.6 1897.24
  5011.9 1897.07  5041.0 1898.48  5068.2 1898.30  5091.0 1899.53  5097.4 1899.10
  5141.0 1899.20  5147.4 1899.75  5247.4 1900.08  5268.3 1899.72  5389.7 1900.42
#Mann=4,-1,0
  4194.1   0.035       0  4873.4    0.07       0  4957.9    0.07       0
  4961.9    0.07       0
Bank Sta=4957.9,4961.9
Exp/Cntr=0.3,0.1

Type RM Length L Ch R = 1,1110,562,562,562
BEGIN DESCRIPTION:
MULBERRY CREEK TRIBUTARY 18_2_1 1.0
END DESCRIPTION:
XS GIS Cut Line= 3
      1497914.47      6828744.40      1498338.77      6828421.33
      1498686.27      6827672.20
#Sta/Elev= 30
  4466.7 1910.69  4492.5 1908.57  4500.4 1909.30  4506.7 1907.92  4514.9 1908.94
  4521.2 1906.56  4542.8 1904.82  4556.6 1902.50  4564.8 1902.46  4575.9 1901.29
  4656.4 1897.43  4679.2 1897.71  4827.6 1895.43  4907.3 1894.69  4949.5 1895.20
  4968.3 1894.56  4968.6 1894.06  4972.3 1894.56  5158.0 1895.99  5189.3 1895.52
  5224.1 1896.70  5321.6 1897.30  5417.8 1898.06  5554.9 1897.92  5572.3 1898.92
  5577.8 1898.19  5595.2 1897.91  5632.0 1898.02  5761.1 1899.84  5825.8 1899.80
#Mann=7,-1,0
  4466.7    0.07       0  4575.9   0.035       0  4827.6    0.07       0
  4968.3    0.07       0  4972.3    0.07       0  5321.6   0.035       0
  5417.8    0.07       0
Bank Sta=4968.3,4972.3
Exp/Cntr=0.3,0.1

Type RM Length L Ch R = 1,548,468,468,468
BEGIN DESCRIPTION:
Mapping XS 1a6aa1fe
END DESCRIPTION:
XS GIS Cut Line= 3
      1498121.53      6828924.25      1498584.87      6828788.55
      1498572.94      6828223.27
#Sta/Elev= 30
  4517.2 1908.77  4541.7 1909.27  4572.9 1908.32  4635.4 1901.18  4656.3 1899.65
  4662.7 1898.41  4667.9 1899.07  4696.1 1896.83  4701.3 1897.79  4708.4 1896.15
  4734.8 1895.19  4740.0 1895.89  4750.1 1895.97  4773.4 1894.30  4842.0 1892.84
  4895.9 1892.33  4906.4 1892.85  4917.5 1892.14  4979.1 1891.56  4987.7 1890.65
  4988.0 1890.15  4991.5 1890.15  4991.7 1890.65  5127.7 1892.34  5320.6 1894.53
  5350.6 1894.11  5420.6 1895.54  5450.6 1895.29  5561.2 1896.57  5565.4 1896.57
#Mann=6,-1,0
  4517.2    0.07       0  4842.0   0.035       0  4987.7   0.035       0
  4991.7   0.035       0  5127.7    0.07       0  5561.2   0.035       0
Bank Sta=4987.7,4991.7
Exp/Cntr=0.3,0.1

Type RM Length L Ch R = 1,80,0,0,0
BEGIN DESCRIPTION:
MULBERRY CREEK TRIBUTARY 18_2_1 3.0
END DESCRIPTION:
XS GIS Cut Line= 3
      1498286.01      6829038.67      1498924.86      6828888.33
      1498898.51      6828001.42
#Sta/Elev= 30
  4343.7 1906.58  4352.9 1906.75  4363.2 1905.27  4368.4 1902.75  4373.5 1903.66
  4404.3 1898.53  4424.8 1897.39  4453.1 1894.42  4592.3 1892.89  4918.0 1889.93
  4969.3 1888.55  4977.0 1888.91  4980.2 1887.41  4980.4 1886.91  4983.9 1886.91
  4984.2 1887.41  5020.3 1888.24  5040.3 1889.54  5135.0 1890.15  5170.4 1890.88
  5190.4 1890.40  5230.4 1891.54  5320.5 1891.83  5330.5 1892.40  5390.5 1891.94
  5630.6 1893.62  5640.6 1894.16  5760.7 1894.91  5800.7 1896.13  5887.3 1896.73
#Mann=5,-1,0
  4343.7    0.07       0  4592.3   0.035       0  4980.2   0.035       0
  4984.2   0.035       0  5135.0    0.07       0
Bank Sta=4980.2,4984.2
Exp/Cntr=0.3,0.1

Chan Stop Cuts=-1