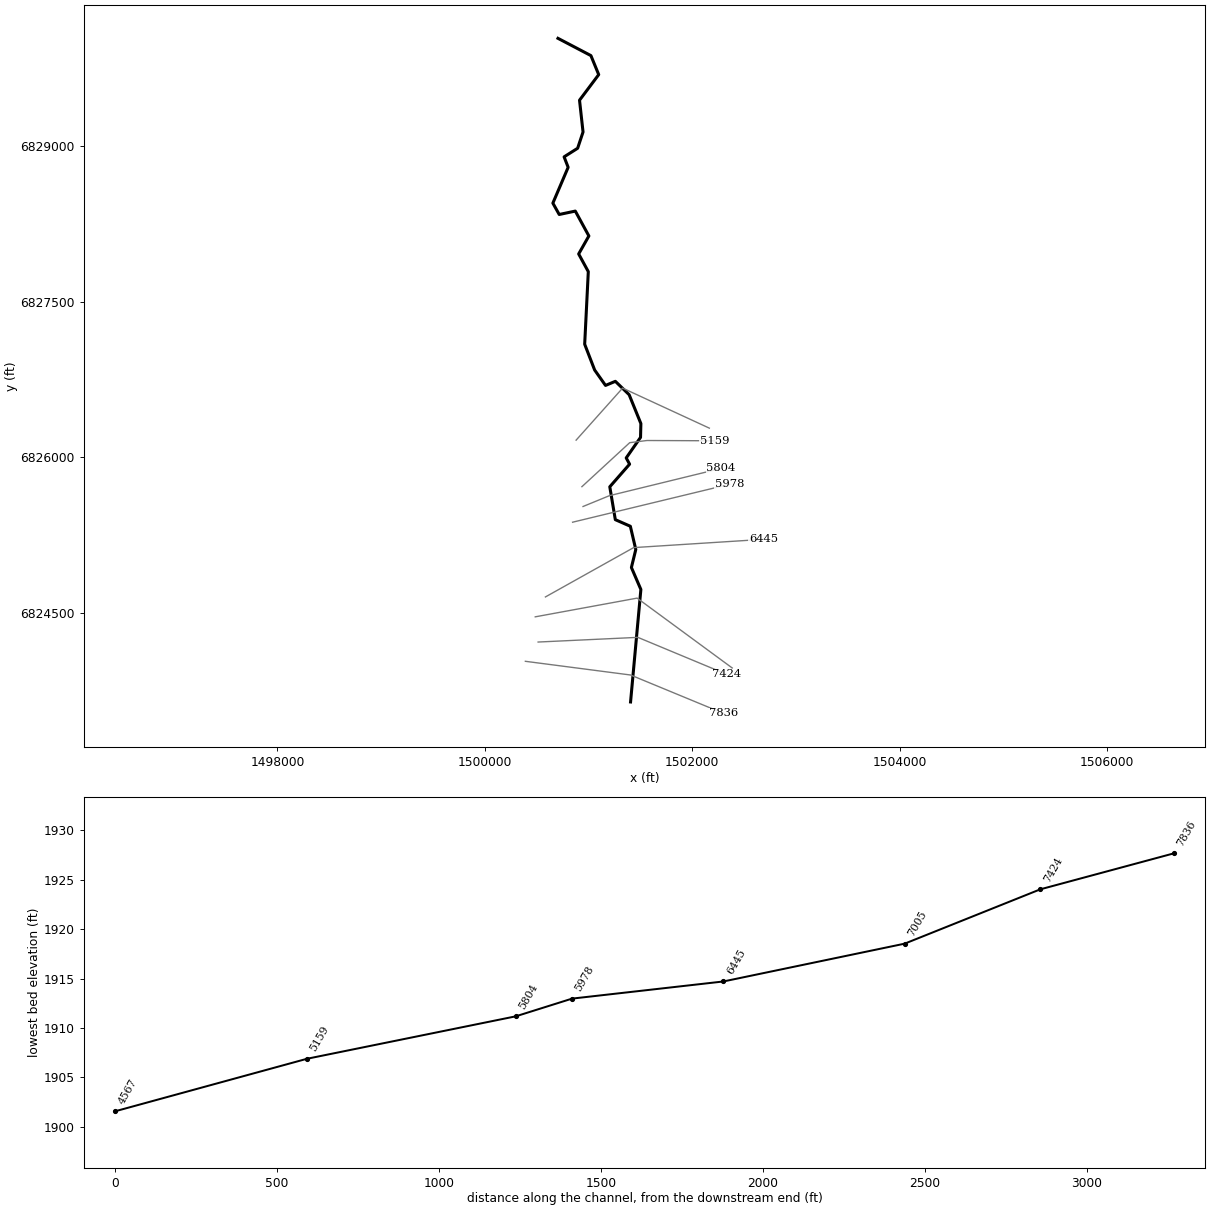
--- MULBERRY CREEK TRIBUTARY 18_3.prj (project) ---

Proj Title=MULBERRY CREEK TRIBUTARY 18_3 Base Level Engineering
Current Plan=p01
Default Exp/Contr=0.3,0.1
English Units
Geom File=g01
Flow File=f01
Plan File=p01
Y Axis Title=Elevation
X Axis Title(PF)=Main Channel Distance
X Axis Title(XS)=Station
BEGIN DESCRIPTION:
MULBERRY CREEK TRIBUTARY 18_3
END DESCRIPTION:
DSS Export Rating Curves= 0
DSS Export Rating Curve Sorted= 0
DSS Export Volume Flow Curves= 0
DXF OffsetX= 0
DXF OffsetY= 0
DXF ScaleX= 1
DXF ScaleY= 10

--- MULBERRY CREEK TRIBUTARY 18_3.p01 (plan) ---

Plan Title=Multiple Run
Short Identifier=Multiple
Geom File=g01
Flow File=f01
Subcritical Flow
K Sum by GR= 0
Std Step Tol= 0.01
Critical Tol= 0.01
Num of Std Step Trials= 20
Max Error Tol= 0.3
Flow Tol Ratio= 0.001
Split Flow NTrial= 30
Split Flow Tol= 0.02
Split Flow Ratio= 0.02
Log Output Level= 0
Friction Slope Method= 1
Unsteady Friction Slope Method= 2
Unsteady Bridges Friction Slope Method= 1
Parabolic Critical Depth
Global Vel Dist=  1 , 1 , 1
Global Log Level= 0
CheckData=True
Encroach Param= -1, 0, 0, 0
BEGIN DESCRIPTION:
Multiple Run
END DESCRIPTION:

--- MULBERRY CREEK TRIBUTARY 18_3.f01 (steady flow) ---

Flow Title=Multiple
Program Version=4.10
Number of Profiles= 7
Profile Names=10-year,25-year,50-year,1pct_min,100-year,1pct_plu,500-year
River Rch & RM=MULBERRY CREEK T,Reach-1         ,7836
     268     376     466     288     575    1147     884
River Rch & RM=MULBERRY CREEK T,Reach-1         ,4567
     297     417     518     320     639    1275     983
Boundary for River Rch & Prof#=MULBERRY CREEK T,Reach-1         , 1
Up Type= 0
Dn Type= 3
Dn Slope=0.00808
Boundary for River Rch & Prof#=MULBERRY CREEK T,Reach-1         , 2
Up Type= 0
Dn Type= 3
Dn Slope=0.00808
Boundary for River Rch & Prof#=MULBERRY CREEK T,Reach-1         , 3
Up Type= 0
Dn Type= 3
Dn Slope=0.00808
Boundary for River Rch & Prof#=MULBERRY CREEK T,Reach-1         , 4
Up Type= 0
Dn Type= 3
Dn Slope=0.00808
Boundary for River Rch & Prof#=MULBERRY CREEK T,Reach-1         , 5
Up Type= 0
Dn Type= 3
Dn Slope=0.00808
Boundary for River Rch & Prof#=MULBERRY CREEK T,Reach-1         , 6
Up Type= 0
Dn Type= 3
Dn Slope=0.00808
Boundary for River Rch & Prof#=MULBERRY CREEK T,Reach-1         , 7
Up Type= 0
Dn Type= 3
Dn Slope=0.00808
DSS Import GetInterval= 0
DSS Import GetPeak= 0
DSS Import FillOption= 0

--- MULBERRY CREEK TRIBUTARY 18_3.g01 (geometry) ---

Geom Title=Existing Conditions

River Reach=MULBERRY CREEK T,Reach-1
Reach XY= 30
      1501405.00      6823638.00      1501504.48      6824722.78
      1501413.08      6824934.70      1501455.39      6825108.13
      1501403.02      6825332.35      1501258.03      6825396.01
      1501204.70      6825713.12      1501395.70      6825931.33
      1501363.02      6825991.33      1501501.26      6826189.56
      1501504.50      6826322.78      1501391.38      6826601.22
      1501258.39      6826730.17      1501163.50      6826690.67
      1501058.55      6826839.47      1500962.56      6827088.00
      1500997.47      6827788.01      1500904.53      6827958.46
      1501003.03      6828132.10      1500872.13      6828371.97
      1500716.99      6828339.17      1500655.74      6828448.66
      1500803.14      6828794.14      1500764.03      6828895.01
      1500894.61      6828977.90      1500946.72      6829134.78
      1500912.81      6829441.41      1501097.89      6829688.00
      1501022.61      6829871.54      1500705.00      6830038.00

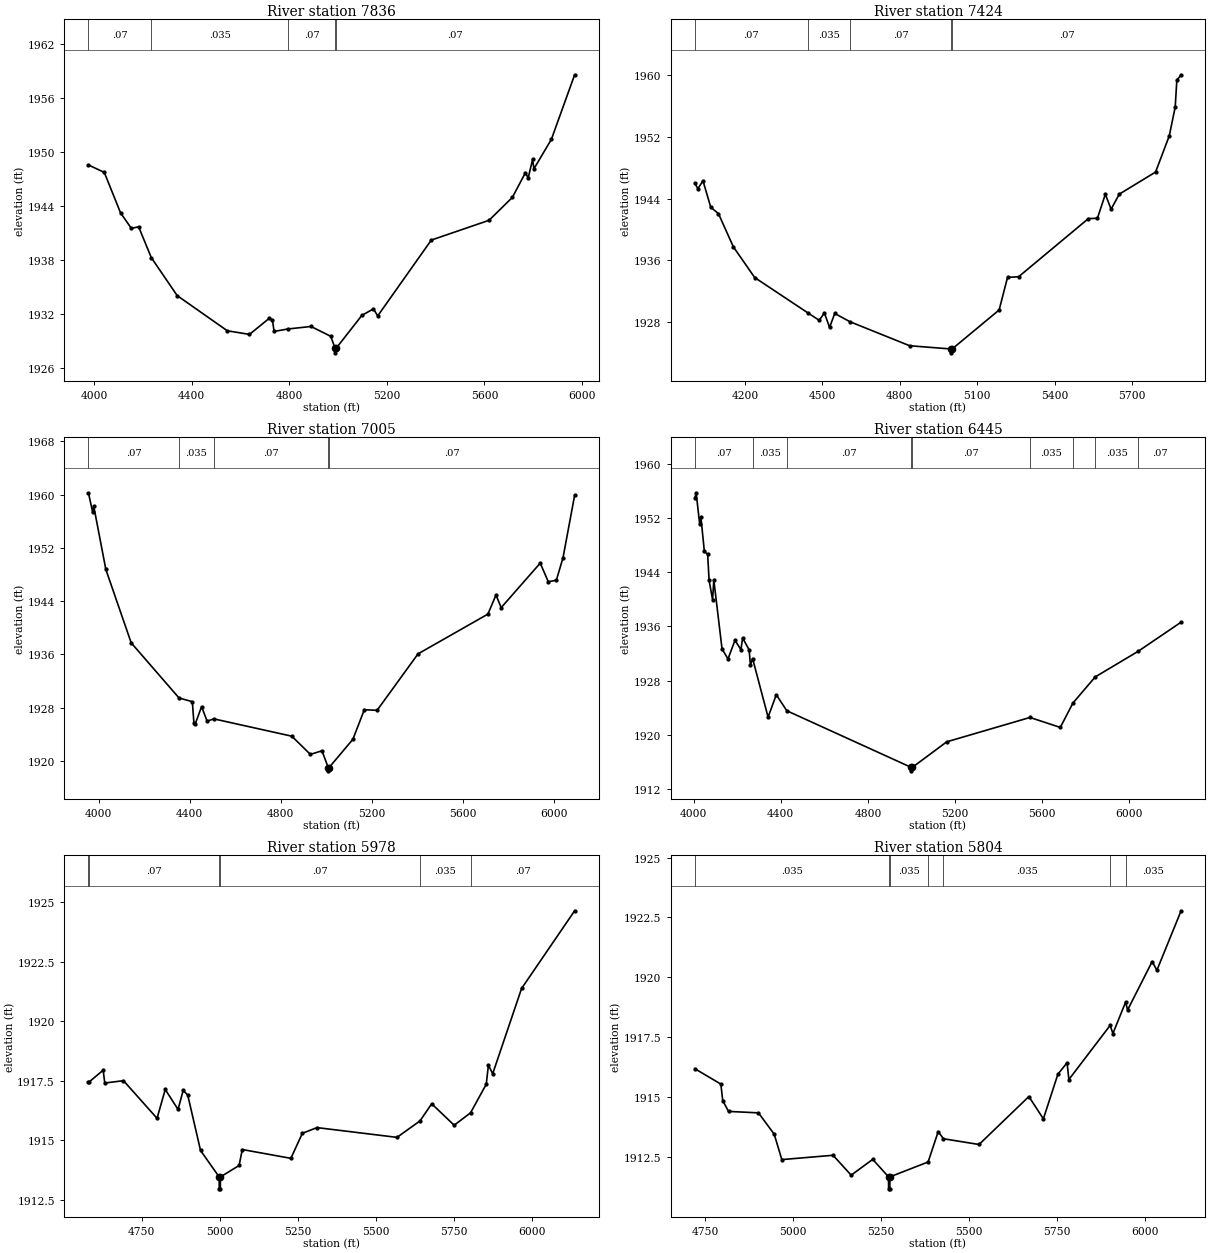
Type RM Length L Ch R = 1,7836,412,412,412
BEGIN DESCRIPTION:
MULBERRY CREEK TRIBUTARY 18_3 7.0
END DESCRIPTION:
XS GIS Cut Line= 3
      1500390.45      6824030.13      1501404.98      6823898.00
      1502300.95      6823527.91
#Sta/Elev= 30
  3976.9 1948.52  4042.0 1947.69  4108.5 1943.20  4152.9 1941.47  4182.6 1941.65
  4234.6 1938.22  4340.7 1934.00  4546.2 1930.09  4637.0 1929.69  4717.7 1931.47
  4730.9 1931.30  4737.8 1930.02  4794.0 1930.29  4889.1 1930.57  4969.8 1929.48
  4987.9 1928.14  4988.2 1927.64  4991.9 1928.14  5097.4 1931.80  5145.1 1932.53
  5162.3 1931.74  5382.0 1940.17  5618.8 1942.37  5714.1 1944.91  5767.8 1947.66
  5779.0 1947.06  5797.1 1949.13  5802.5 1948.09  5874.2 1951.37  5969.4 1958.54
#Mann=5,-1,0
  3976.9    0.07       0  4234.6   0.035       0  4794.0    0.07       0
  4987.9    0.07       0  4991.9    0.07       0
Bank Sta=4987.9,4991.9
Exp/Cntr=0.3,0.1

Type RM Length L Ch R = 1,7424,419,419,419
BEGIN DESCRIPTION:
Mapping XS d7f3a4b6
END DESCRIPTION:
XS GIS Cut Line= 3
      1500513.59      6824215.90      1501475.39      6824261.04
      1502326.05      6823906.89
#Sta/Elev= 30
  4006.0 1946.05  4017.4 1945.29  4037.4 1946.33  4067.5 1942.90  4097.5 1942.06
  4155.0 1937.77  4237.7 1933.78  4444.0 1929.19  4487.9 1928.23  4508.0 1929.18
  4528.0 1927.31  4548.0 1929.12  4606.7 1928.05  4838.3 1924.93  4998.9 1924.51
  4999.2 1924.01  5002.9 1924.51  5185.1 1929.57  5217.6 1933.79  5260.9 1933.89
  5531.2 1941.43  5565.9 1941.46  5596.7 1944.58  5619.0 1942.65  5650.9 1944.60
  5791.3 1947.46  5844.4 1952.15  5867.5 1955.91  5873.7 1959.36  5890.3 1960.08
#Mann=5,-1,0
  4006.0    0.07       0  4444.0   0.035       0  4606.7    0.07       0
  4998.9    0.07       0  5002.9    0.07       0
Bank Sta=4998.9,5002.9
Exp/Cntr=0.3,0.1

Type RM Length L Ch R = 1,7005,560,560,560
BEGIN DESCRIPTION:
Mapping XS 8633a76d
END DESCRIPTION:
XS GIS Cut Line= 3
      1500485.78      6824458.95      1501468.45      6824639.51
      1502385.14      6823965.88
#Sta/Elev= 30
  3955.2 1960.26  3973.6 1957.39  3978.7 1958.22  4031.8 1948.75  4143.1 1937.74
  4353.3 1929.46  4411.9 1928.90  4418.7 1925.75  4423.7 1925.48  4452.6 1928.16
  4476.8 1925.98  4506.4 1926.32  4849.1 1923.72  4930.5 1920.99  4981.6 1921.53
  5008.9 1919.02  5009.2 1918.52  5012.9 1919.02  5117.4 1923.25  5167.6 1927.69
  5223.9 1927.61  5403.7 1936.08  5710.8 1942.05  5746.3 1944.92  5769.1 1943.02
  5940.7 1949.70  5976.2 1946.90  6011.7 1947.14  6041.0 1950.54  6091.9 1959.88
#Mann=5,-1,0
  3955.2    0.07       0  4353.3   0.035       0  4506.4    0.07       0
  5008.9    0.07       0  5012.9    0.07       0
Bank Sta=5008.9,5012.9
Exp/Cntr=0.3,0.1

Type RM Length L Ch R = 1,6445,467,467,467
BEGIN DESCRIPTION:
Mapping XS 0a1f503b
END DESCRIPTION:
XS GIS Cut Line= 3
      1500583.86      6824650.77      1501434.59      6825126.49
      1502688.04      6825206.35
#Sta/Elev= 30
  4006.1 1954.93  4011.9 1955.70  4027.9 1951.14  4033.6 1952.15  4049.6 1947.05
  4064.7 1946.63  4071.3 1942.78  4087.3 1939.94  4093.0 1942.84  4130.7 1932.67
  4158.1 1931.20  4190.0 1933.94  4217.5 1932.57  4225.1 1934.30  4255.1 1932.53
  4260.9 1930.29  4270.9 1931.26  4341.9 1922.62  4379.6 1925.92  4427.8 1923.56
  4999.3 1915.20  4999.5 1914.70  5003.3 1915.20  5161.6 1918.98  5543.5 1922.57
  5682.6 1921.10  5740.5 1924.70  5842.9 1928.55  6039.1 1932.31  6236.8 1936.62
#Mann=9,-1,0
  4006.1    0.07       0  4270.9   0.035       0  4427.8    0.07       0
  4999.3    0.07       0  5003.3    0.07       0  5543.5   0.035       0
  5740.5    0.07       0  5842.9   0.035       0  6039.1    0.07       0
Bank Sta=4999.3,5003.3
Exp/Cntr=0.3,0.1

Type RM Length L Ch R = 1,5978,174,174,174
BEGIN DESCRIPTION:
Mapping XS 855ca511
END DESCRIPTION:
XS GIS Cut Line= 2
      1500845.73      6825371.49      1502360.23      6825737.50
#Sta/Elev= 30
  4579.5 1917.45  4582.2 1917.46  4626.8 1917.95  4631.9 1917.41  4691.9 1917.51
  4799.4 1915.93  4825.7 1917.14  4866.8 1916.30  4883.1 1917.10  4897.7 1916.91
  4938.8 1914.58  4998.5 1913.47  4998.8 1912.97  5002.3 1912.97  5002.5 1913.47
  5062.3 1913.95  5072.6 1914.62  5228.3 1914.25  5265.0 1915.30  5312.0 1915.54
  5568.3 1915.13  5642.0 1915.82  5679.5 1916.54  5751.6 1915.64  5804.0 1916.16
  5854.4 1917.36  5861.3 1918.16  5875.0 1917.80  5967.6 1921.38  6137.6 1924.64
#Mann=6,-1,0
  4579.5   0.035       0  4582.2    0.07       0  4998.5    0.07       0
  5002.5    0.07       0  5642.0   0.035       0  5804.0    0.07       0
Bank Sta=4998.5,5002.5
Exp/Cntr=0.3,0.1

Type RM Length L Ch R = 1,5804,645,645,645
BEGIN DESCRIPTION:
Mapping XS 5b373dce
END DESCRIPTION:
XS GIS Cut Line= 3
      1500946.68      6825523.02      1501200.61      6825627.20
      1502274.81      6825889.78
#Sta/Elev= 30
  4721.2 1916.19  4794.9 1915.55  4800.3 1914.86  4816.7 1914.41  4901.7 1914.35
  4946.4 1913.46  4968.0 1912.40  5113.4 1912.58  5164.9 1911.75  5226.1 1912.41
  5270.9 1911.68  5271.1 1911.18  5274.6 1911.18  5274.9 1911.68  5383.3 1912.30
  5412.0 1913.57  5426.7 1913.27  5527.9 1913.03  5669.3 1915.03  5710.5 1914.10
  5751.7 1915.96  5777.8 1916.44  5782.9 1915.74  5900.1 1918.00  5907.9 1917.66
  5944.0 1918.97  5949.5 1918.64  6019.3 1920.66  6032.8 1920.30  6101.5 1922.78
#Mann=7,-1,0
  4721.2   0.035       0  5270.9   0.035       0  5274.9   0.035       0
  5383.3    0.07       0  5426.7   0.035       0  5900.1    0.07       0
  5944.0   0.035       0
Bank Sta=5270.9,5274.9
Exp/Cntr=0.3,0.1

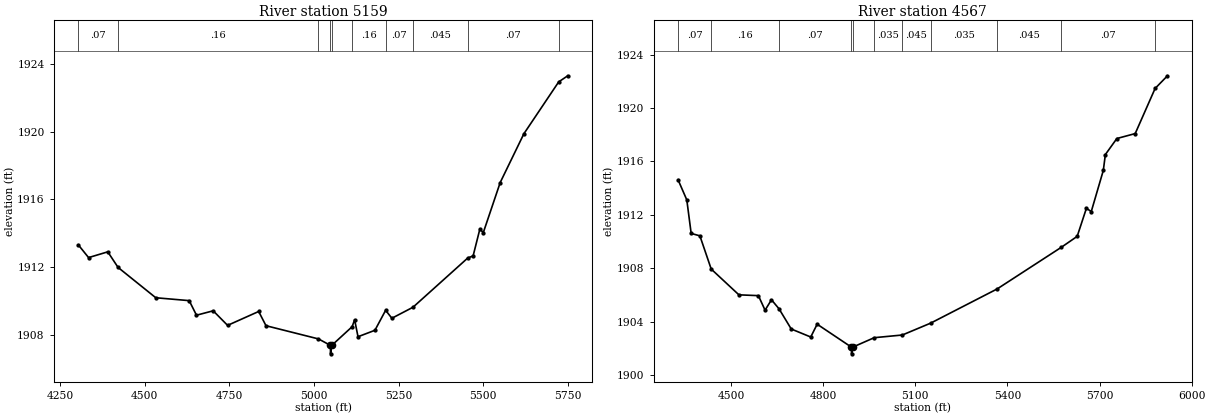
Type RM Length L Ch R = 1,5159,592,592,592
BEGIN DESCRIPTION:
Mapping XS d75aff5a
END DESCRIPTION:
XS GIS Cut Line= 4
      1500935.87      6825714.17      1501396.78      6826138.62
      1501563.45      6826159.45      1502214.51      6826156.85
#Sta/Elev= 30
  4303.7 1913.32  4334.0 1912.57  4390.7 1912.91  4421.1 1911.99  4532.5 1910.20
  4631.2 1910.03  4652.7 1909.17  4702.0 1909.43  4744.6 1908.57  4836.4 1909.39
  4858.0 1908.55  5013.1 1907.77  5048.3 1907.39  5048.6 1906.89  5052.3 1907.39
  5112.4 1908.49  5119.8 1908.90  5129.8 1907.90  5179.8 1908.28  5211.4 1909.46
  5229.8 1908.99  5292.2 1909.64  5454.2 1912.55  5469.8 1912.67  5489.8 1914.26
  5499.8 1914.04  5549.8 1917.00  5619.8 1919.88  5722.6 1922.94  5749.3 1923.30
#Mann=10,-1,0
  4303.7    0.07       0  4421.1    0.16       0  5013.1    0.07       0
  5048.3    0.07       0  5052.3    0.07       0  5112.4    0.16       0
  5211.4    0.07       0  5292.2   0.045       0  5454.2    0.07       0
  5722.6   0.045       0
Bank Sta=5048.3,5052.3
Exp/Cntr=0.3,0.1

Type RM Length L Ch R = 1,4567,0,0,0
BEGIN DESCRIPTION:
Mapping XS 4fff3b57
END DESCRIPTION:
XS GIS Cut Line= 3
      1500879.97      6826162.97      1501328.38      6826664.82
      1502164.74      6826278.66
#Sta/Elev= 30
  4327.0 1914.63  4355.5 1913.12  4369.7 1910.61  4398.1 1910.43  4435.0 1907.94
  4525.2 1906.01  4588.7 1905.95  4610.4 1904.86  4631.3 1905.64  4656.0 1904.96
  4695.7 1903.45  4759.2 1902.85  4780.1 1903.81  4891.8 1902.09  4892.1 1901.59
  4895.8 1902.09  4966.0 1902.80  5057.5 1903.00  5149.8 1903.89  5366.3 1906.45
  5576.0 1909.58  5627.1 1910.39  5657.1 1912.49  5673.0 1912.25  5712.2 1915.33
  5718.9 1916.52  5756.3 1917.72  5816.1 1918.09  5880.9 1921.47  5921.2 1922.42
#Mann=11,-1,0
  4327.0    0.07       0  4435.0    0.16       0  4656.0    0.07       0
  4891.8   0.035       0  4895.8    0.07       0  4966.0   0.035       0
  5057.5   0.045       0  5149.8   0.035       0  5366.3   0.045       0
  5576.0    0.07       0  5880.9   0.045       0
Bank Sta=4891.8,4895.8
Exp/Cntr=0.3,0.1

Chan Stop Cuts=-1