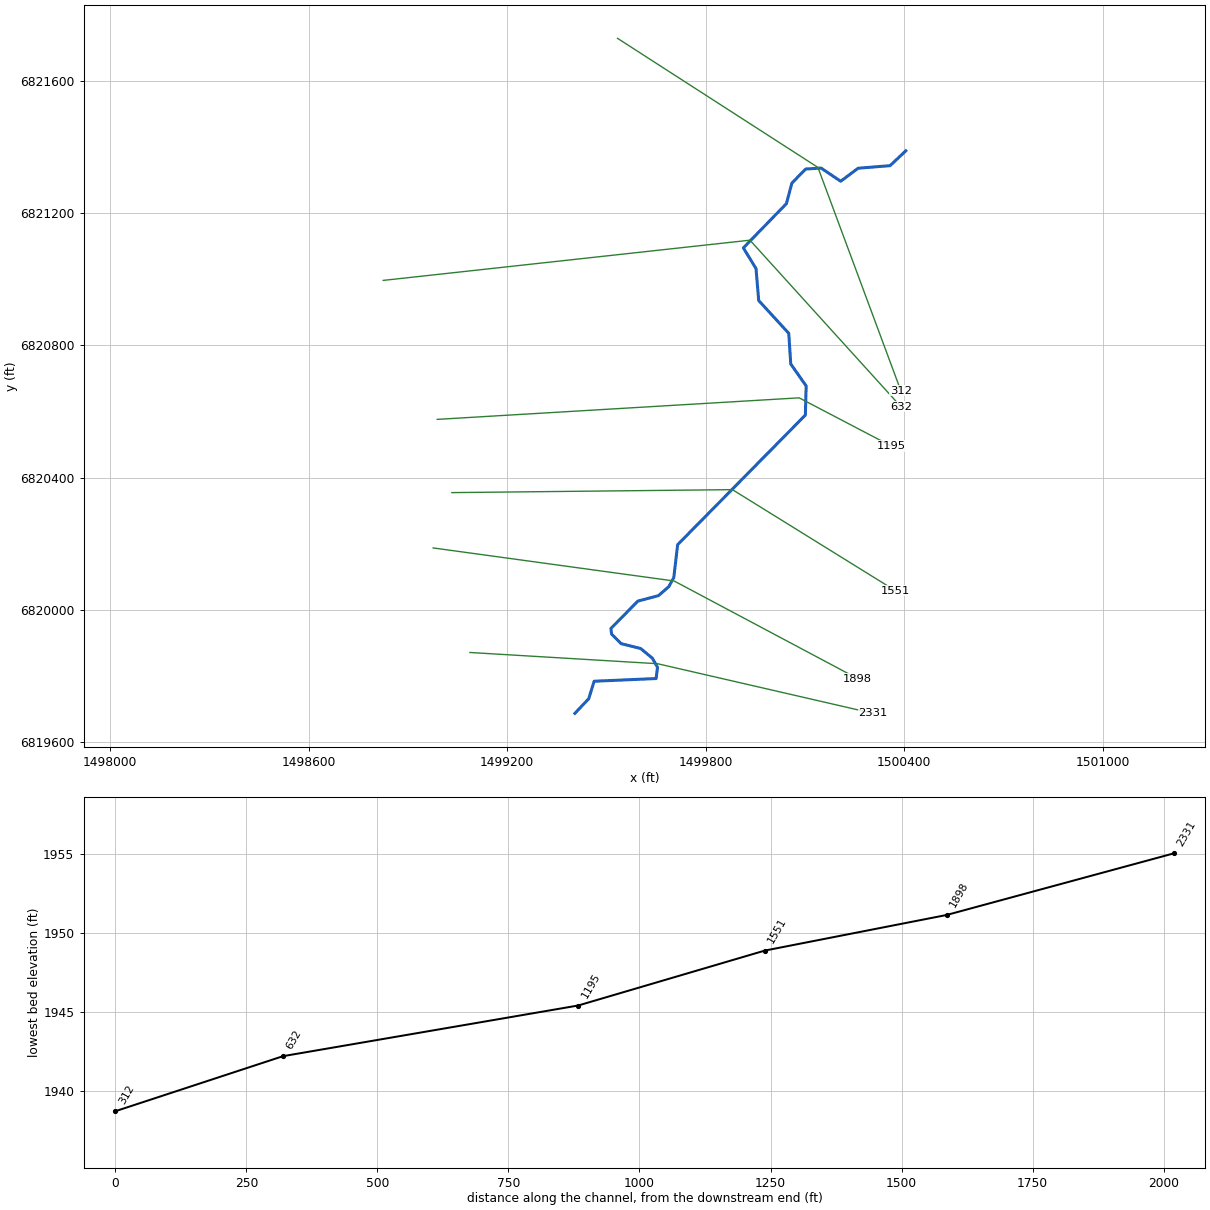
--- MULBERRY CREEK TRIBUTARY 18_4.prj (project) ---

Proj Title=MULBERRY CREEK TRIBUTARY 18_4 Base Level Engineering
Current Plan=p01
Default Exp/Contr=0.3,0.1
English Units
Geom File=g01
Flow File=f01
Plan File=p01
BEGIN DESCRIPTION:
MULBERRY CREEK TRIBUTARY 18_4
END DESCRIPTION:

--- MULBERRY CREEK TRIBUTARY 18_4.p01 (plan) ---

Plan Title=Multiple Run
Short Identifier=Multiple
Geom File=g01
Flow File=f01
Subcritical Flow
K Sum by GR= 0
Std Step Tol= 0.01
Critical Tol= 0.01
Num of Std Step Trials= 20
Max Error Tol= 0.3
Flow Tol Ratio= 0.001
Split Flow NTrial= 30
Split Flow Tol= 0.02
Split Flow Ratio= 0.02
Log Output Level= 0
Friction Slope Method= 1
Unsteady Friction Slope Method= 2
Unsteady Bridges Friction Slope Method= 1
Parabolic Critical Depth
Global Vel Dist=  1 , 1 , 1
Global Log Level= 0
CheckData=True
Encroach Param= -1, 0, 0, 0
BEGIN DESCRIPTION:
Multiple Run
END DESCRIPTION:

--- MULBERRY CREEK TRIBUTARY 18_4.f01 (steady flow) ---

Flow Title=Multiple
Number of Profiles=7
Profile Names=10-year,25-year,50-year,1pct_min,100-year,1pct_plu,500-year
River Rch & RM= MULBERRY CREEK T,Reach-1,2331
     189     258     313     190     379     756     559
Boundary for River Rch & Prof#=MULBERRY CREEK T,Reach-1,1
Up Type=0
Dn Type=3
Dn Slope=0.005
Boundary for River Rch & Prof#=MULBERRY CREEK T,Reach-1,2
Up Type=0
Dn Type=3
Dn Slope=0.005
Boundary for River Rch & Prof#=MULBERRY CREEK T,Reach-1,3
Up Type=0
Dn Type=3
Dn Slope=0.005
Boundary for River Rch & Prof#=MULBERRY CREEK T,Reach-1,4
Up Type=0
Dn Type=3
Dn Slope=0.005
Boundary for River Rch & Prof#=MULBERRY CREEK T,Reach-1,5
Up Type=0
Dn Type=3
Dn Slope=0.005
Boundary for River Rch & Prof#=MULBERRY CREEK T,Reach-1,6
Up Type=0
Dn Type=3
Dn Slope=0.005
Boundary for River Rch & Prof#=MULBERRY CREEK T,Reach-1,7
Up Type=0
Dn Type=3
Dn Slope=0.005

--- MULBERRY CREEK TRIBUTARY 18_4.g01 (geometry) ---

Geom Title=Existing Conditions

River Reach=MULBERRY CREEK T,Reach-1
Reach XY= 30
      1499405.00      6819688.00      1499446.85      6819732.37
      1499463.14      6819785.05      1499650.45      6819793.21
      1499654.72      6819827.01      1499639.03      6819854.83
      1499603.58      6819884.08      1499544.59      6819898.79
      1499515.82      6819927.69      1499513.88      6819944.53
      1499595.29      6820027.21      1499657.57      6820043.74
      1499688.70      6820070.87      1499703.90      6820098.33
      1499715.52      6820197.78      1500101.54      6820589.50
      1500103.90      6820677.45      1500057.36      6820743.98
      1500051.38      6820836.50      1499960.53      6820935.58
      1499952.44      6821032.11      1499914.13      6821094.74
      1500044.21      6821228.34      1500060.75      6821290.61
      1500102.46      6821332.99      1500148.91      6821336.04
      1500208.29      6821296.10      1500260.88      6821335.48
      1500357.55      6821343.22      1500405.00      6821388.00

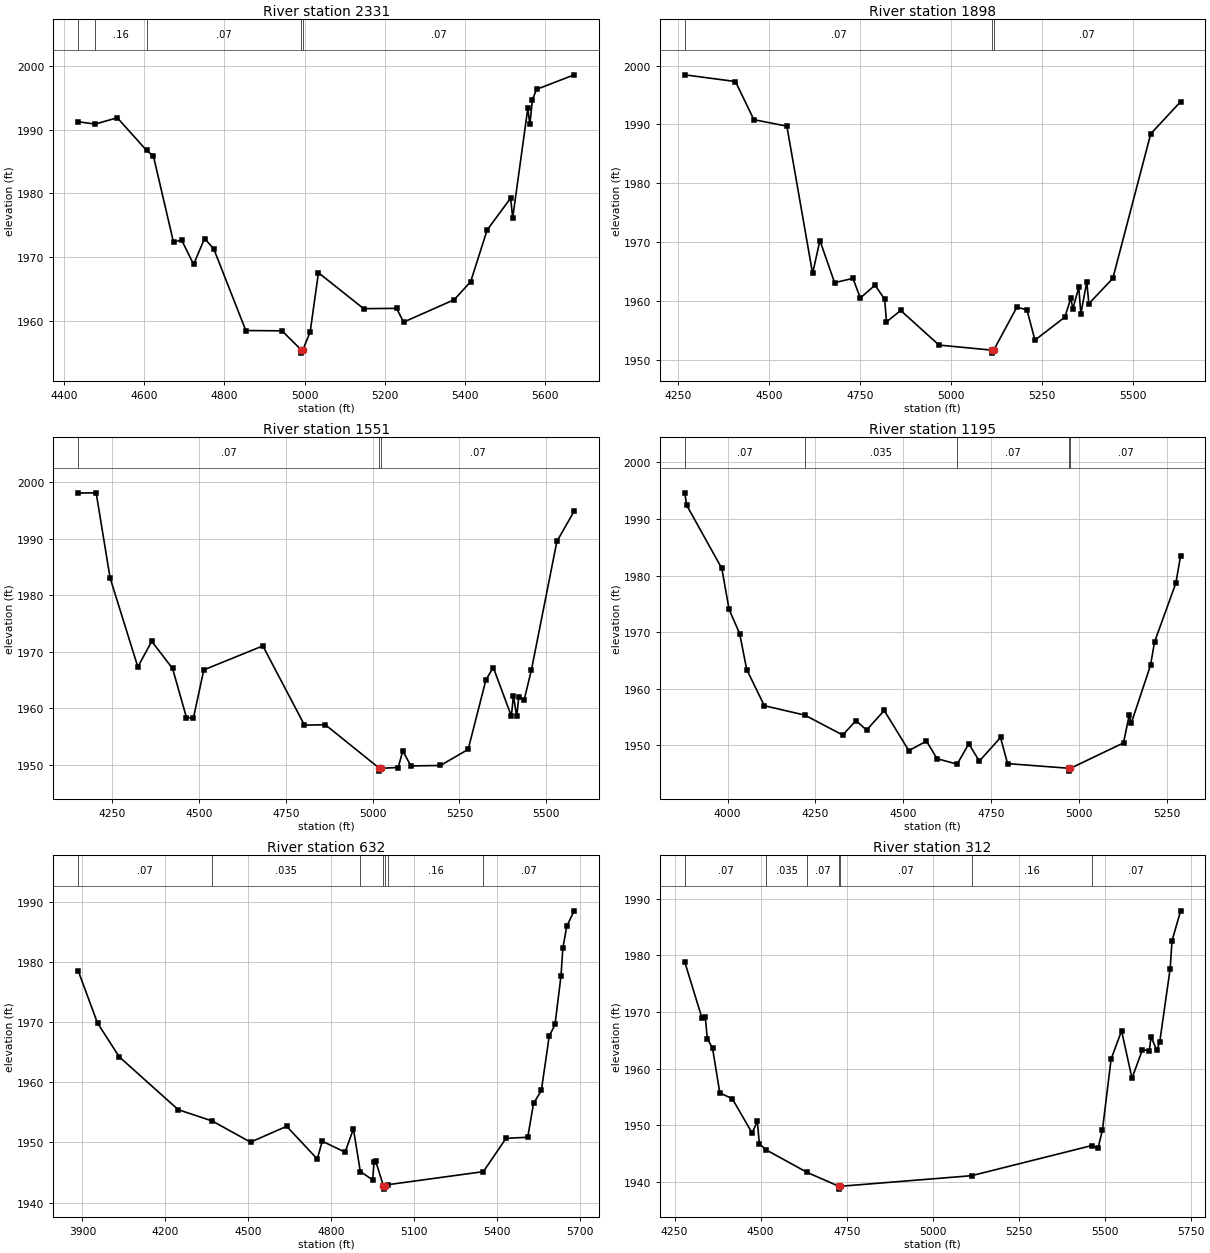
Type RM Length L Ch R = 1,2331,433,433,433
BEGIN DESCRIPTION:
MULBERRY CREEK TRIBUTARY 18_4 5.0
END DESCRIPTION:
XS GIS Cut Line= 3
      1499087.75      6819871.96      1499655.00      6819838.00
      1500306.47      6819687.93
#Sta/Elev= 30
  4435.6 1991.21  4478.1 1990.85  4533.0 1991.84  4606.0 1986.74  4623.2 1985.83
  4673.3 1972.37  4693.3 1972.74  4723.4 1968.92  4750.6 1972.95  4773.5 1971.36
  4853.6 1958.57  4943.8 1958.53  4991.9 1955.54  4992.1 1955.04  4995.9 1955.54
  5014.1 1958.37  5034.7 1967.61  5147.5 1961.99  5229.6 1962.04  5247.0 1959.89
  5373.3 1963.39  5414.3 1966.21  5455.4 1974.29  5514.0 1979.28  5519.1 1976.17
  5556.8 1993.30  5561.9 1990.82  5568.3 1994.63  5578.5 1996.27  5672.4 1998.55
#Mann=5,-1,0
  4435.6    0.07       0  4478.1    0.16       0  4606.0    0.07       0
  4991.9    0.07       0  4995.9    0.07       0
Bank Sta=4991.9,4995.9
Exp/Cntr=0.3,0.1

Type RM Length L Ch R = 1,1898,347,347,347
BEGIN DESCRIPTION:
MULBERRY CREEK TRIBUTARY 18_4 4.0
END DESCRIPTION:
XS GIS Cut Line= 3
      1498976.60      6820187.93      1499705.00      6820088.00
      1500259.79      6819792.92
#Sta/Elev= 30
  4268.7 1998.43  4408.4 1997.29  4458.9 1990.81  4549.7 1989.71  4620.4 1964.68
  4640.5 1970.28  4680.9 1963.12  4731.4 1963.85  4751.6 1960.51  4792.0 1962.70
  4818.6 1960.29  4823.6 1956.45  4862.6 1958.40  4967.9 1952.52  5114.3 1951.65
  5114.5 1951.15  5118.3 1951.65  5182.2 1958.97  5209.8 1958.49  5231.8 1953.36
  5314.1 1957.27  5330.4 1960.48  5336.0 1958.70  5352.3 1962.33  5358.0 1957.83
  5374.3 1963.25  5380.0 1959.55  5445.9 1963.85  5550.1 1988.41  5632.3 1993.87
#Mann=3,-1,0
  4268.7    0.07       0  5114.3    0.07       0  5118.3    0.07       0
Bank Sta=5114.3,5118.3
Exp/Cntr=0.3,0.1

Type RM Length L Ch R = 1,1551,356,356,356
BEGIN DESCRIPTION:
MULBERRY CREEK TRIBUTARY 18_4 3.0
END DESCRIPTION:
XS GIS Cut Line= 3
      1499033.32      6820355.11      1499881.08      6820364.10
      1500374.45      6820058.22
#Sta/Elev= 30
  4152.2 1998.06  4203.9 1998.10  4243.9 1983.08  4323.9 1967.32  4363.9 1971.85
  4423.9 1967.05  4463.9 1958.38  4483.9 1958.26  4513.9 1966.80  4683.9 1971.04
  4803.9 1957.03  4863.9 1957.10  5019.7 1949.40  5019.9 1948.90  5023.7 1949.40
  5073.7 1949.54  5087.0 1952.47  5110.3 1949.82  5195.3 1949.90  5275.2 1952.74
  5326.4 1965.03  5347.7 1967.22  5399.7 1958.62  5405.6 1962.23  5415.1 1958.56
  5421.0 1961.96  5436.3 1961.46  5457.6 1966.84  5530.8 1989.52  5580.5 1994.85
#Mann=3,-1,0
  4152.2    0.07       0  5019.7    0.07       0  5023.7    0.07       0
Bank Sta=5019.7,5023.7
Exp/Cntr=0.3,0.1

Type RM Length L Ch R = 1,1195,563,563,563
BEGIN DESCRIPTION:
Mapping XS b18b0b9e
END DESCRIPTION:
XS GIS Cut Line= 3
      1498989.03      6820576.46      1500082.77      6820641.56
      1500360.73      6820496.09
#Sta/Elev= 30
  3878.3 1994.62  3884.3 1992.39  3983.9 1981.25  4004.5 1974.01  4034.5 1969.75
  4054.6 1963.39  4104.7 1956.99  4219.7 1955.33  4327.5 1951.81  4365.1 1954.37
  4395.2 1952.68  4445.3 1956.15  4515.4 1949.05  4565.5 1950.74  4595.5 1947.63
  4652.6 1946.66  4685.7 1950.26  4715.7 1947.20  4775.9 1951.38  4795.9 1946.76
  4970.6 1945.93  4970.8 1945.43  4974.6 1945.93  5125.4 1950.42  5141.8 1955.37
  5147.4 1953.89  5202.2 1964.14  5213.6 1968.26  5274.2 1978.67  5287.7 1983.52
#Mann=5,-1,0
  3878.3    0.07       0  4219.7   0.035       0  4652.6    0.07       0
  4970.6    0.07       0  4974.6    0.07       0
Bank Sta=4970.6,4974.6
Exp/Cntr=0.3,0.1

Type RM Length L Ch R = 1,632,320,320,320
BEGIN DESCRIPTION:
MULBERRY CREEK TRIBUTARY 18_4 2.0
END DESCRIPTION:
XS GIS Cut Line= 3
      1498825.61      6820996.45      1499934.06      6821118.02
      1500389.78      6820615.34
#Sta/Elev= 30
  3884.9 1978.57  3954.7 1969.87  4033.4 1964.25  4246.4 1955.46  4369.8 1953.57
  4508.0 1950.05  4638.8 1952.69  4749.4 1947.25  4767.5 1950.21  4850.0 1948.38
  4880.2 1952.25  4905.2 1945.16  4949.8 1943.76  4954.8 1946.77  4960.7 1946.91
  4988.9 1942.73  4989.1 1942.23  4992.9 1942.73  5006.8 1942.98  5350.1 1945.14
  5432.2 1950.69  5510.6 1950.86  5531.6 1956.49  5559.9 1958.65  5588.3 1967.69
  5609.3 1969.64  5630.9 1977.72  5637.7 1982.40  5651.9 1986.00  5678.5 1988.56
#Mann=7,-1,0
  3884.9    0.07       0  4369.8   0.035       0  4905.2    0.07       0
  4988.9    0.07       0  4992.9    0.07       0  5006.8    0.16       0
  5350.1    0.07       0
Bank Sta=4988.9,4992.9
Exp/Cntr=0.3,0.1

Type RM Length L Ch R = 1,312,0,0,0
BEGIN DESCRIPTION:
MULBERRY CREEK TRIBUTARY 18_4 1.0
END DESCRIPTION:
XS GIS Cut Line= 3
      1499533.87      6821728.03      1500139.58      6821337.86
      1500390.05      6820663.15
#Sta/Elev= 30
  4279.5 1978.88  4330.0 1968.87  4339.3 1969.18  4345.2 1965.30  4360.4 1963.62
  4381.5 1955.73  4417.8 1954.69  4475.3 1948.65  4490.5 1950.69  4496.4 1946.75
  4515.9 1945.68  4635.1 1941.70  4727.4 1939.25  4727.7 1938.75  4731.4 1939.25
  5112.5 1941.12  5461.4 1946.43  5479.9 1945.97  5492.8 1949.23  5517.8 1961.68
  5548.2 1966.69  5578.5 1958.31  5608.9 1963.37  5628.6 1963.14  5633.9 1965.60
  5650.5 1963.25  5659.0 1964.68  5689.3 1977.65  5694.7 1982.56  5719.7 1987.85
#Mann=7,-1,0
  4279.5    0.07       0  4515.9   0.035       0  4635.1    0.07       0
  4727.4    0.07       0  4731.4    0.07       0  5112.5    0.16       0
  5461.4    0.07       0
Bank Sta=4727.4,4731.4
Exp/Cntr=0.3,0.1

Chan Stop Cuts=-1