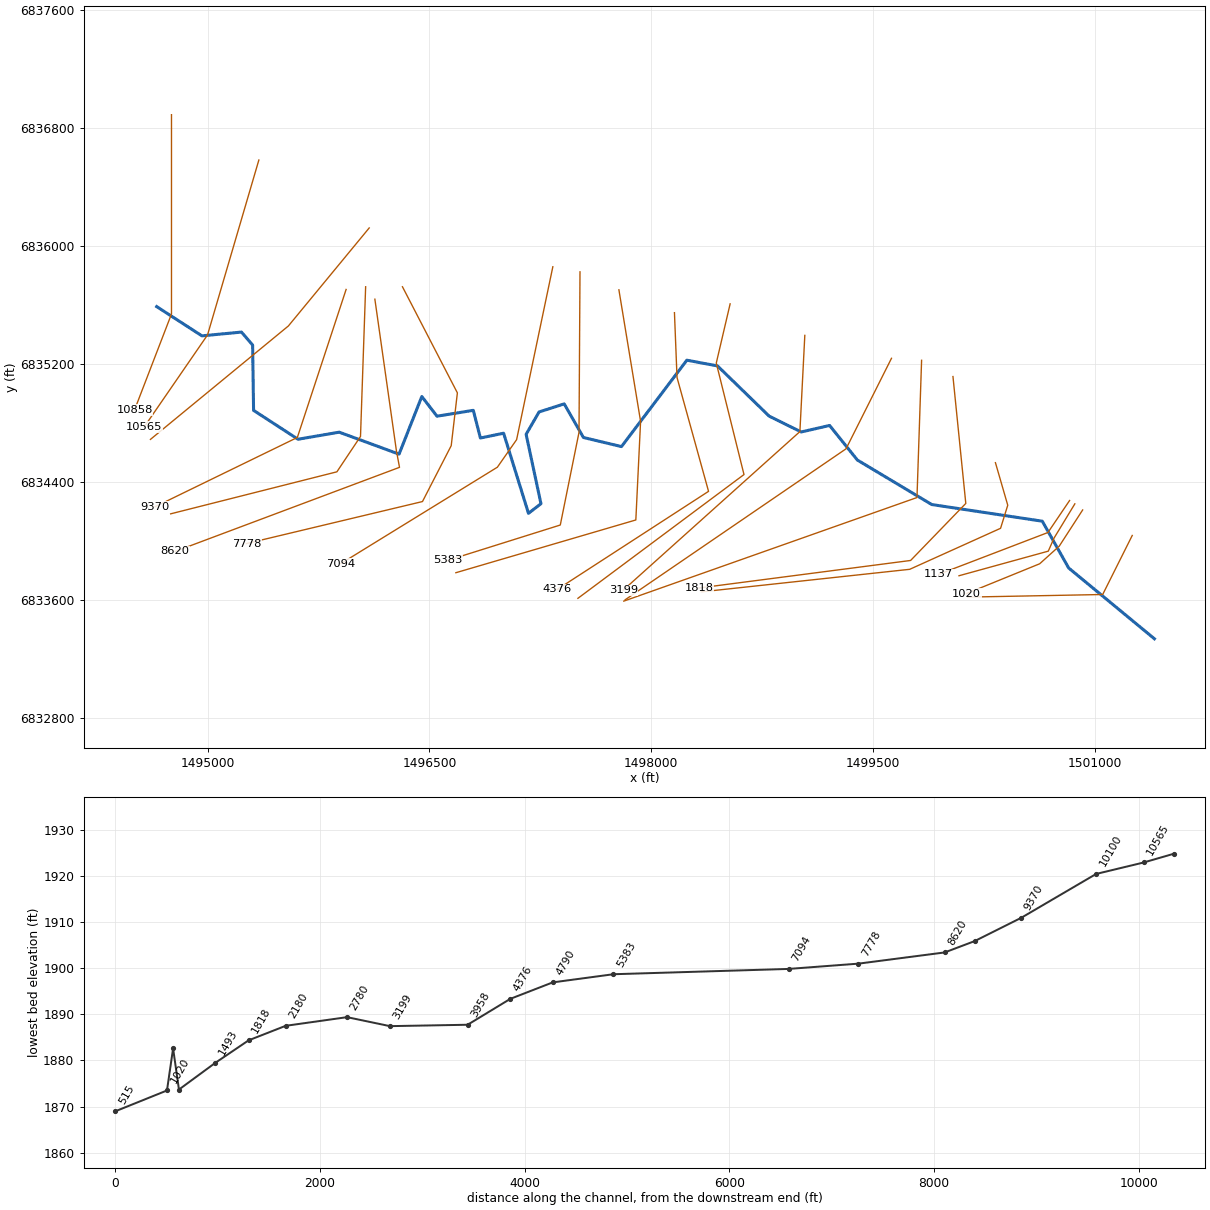
--- MULBERRY CREEK TRIBUTARY 19.prj (project) ---

Proj Title=MULBERRY CREEK TRIBUTARY 19 Base Level Engineering
Current Plan=p01
Default Exp/Contr=0.3,0.1
English Units
Geom File=g01
Flow File=f01
Plan File=p01
Y Axis Title=Elevation
X Axis Title(PF)=Main Channel Distance
X Axis Title(XS)=Station
BEGIN DESCRIPTION:
MULBERRY CREEK TRIBUTARY 19
END DESCRIPTION:
DSS Export Rating Curves= 0
DSS Export Rating Curve Sorted= 0
DSS Export Volume Flow Curves= 0
DXF OffsetX= 0
DXF OffsetY= 0
DXF ScaleX= 1
DXF ScaleY= 10

--- MULBERRY CREEK TRIBUTARY 19.p01 (plan) ---

Plan Title=Multiple Run
Short Identifier=Multiple
Geom File=g01
Flow File=f01
Subcritical Flow
K Sum by GR= 0
Std Step Tol= 0.01
Critical Tol= 0.01
Num of Std Step Trials= 20
Max Error Tol= 0.3
Flow Tol Ratio= 0.001
Split Flow NTrial= 30
Split Flow Tol= 0.02
Split Flow Ratio= 0.02
Log Output Level= 0
Friction Slope Method= 1
Unsteady Friction Slope Method= 2
Unsteady Bridges Friction Slope Method= 1
Parabolic Critical Depth
Global Vel Dist=  1 , 1 , 1
Global Log Level= 0
CheckData=True
Encroach Param= -1, 0, 0, 0
BEGIN DESCRIPTION:
Multiple Run
END DESCRIPTION:

--- MULBERRY CREEK TRIBUTARY 19.f01 (steady flow) ---

Flow Title=Multiple
Number of Profiles=7
Profile Names=10-year,25-year,50-year,1pct_min,100-year,1pct_plu,500-year
River Rch & RM= MULBERRY CREEK T,Reach-1,10858
     200     271     329     199     396     791     581
River Rch & RM= MULBERRY CREEK T,Reach-1,4790
     269     373     458     280     558    1114     839
Boundary for River Rch & Prof#=MULBERRY CREEK T,Reach-1,1
Up Type=0
Dn Type=3
Dn Slope=0.005
Boundary for River Rch & Prof#=MULBERRY CREEK T,Reach-1,2
Up Type=0
Dn Type=3
Dn Slope=0.005
Boundary for River Rch & Prof#=MULBERRY CREEK T,Reach-1,3
Up Type=0
Dn Type=3
Dn Slope=0.005
Boundary for River Rch & Prof#=MULBERRY CREEK T,Reach-1,4
Up Type=0
Dn Type=3
Dn Slope=0.005
Boundary for River Rch & Prof#=MULBERRY CREEK T,Reach-1,5
Up Type=0
Dn Type=3
Dn Slope=0.005
Boundary for River Rch & Prof#=MULBERRY CREEK T,Reach-1,6
Up Type=0
Dn Type=3
Dn Slope=0.005
Boundary for River Rch & Prof#=MULBERRY CREEK T,Reach-1,7
Up Type=0
Dn Type=3
Dn Slope=0.005

--- MULBERRY CREEK TRIBUTARY 19.g01 (geometry) ---

Geom Title=Existing Conditions
Program Version=4.10

River Reach=MULBERRY CREEK T,Reach-1
Reach XY= 30
        1494655.        6835588.       1494960.9      6835389.97
      1495228.39      6835415.51      1495303.95      6835327.58
      1495310.36       6834885.3      1495611.04      6834689.63
      1495889.78      6834737.48      1496294.71       6834588.6
      1496448.45      6834979.11      1496551.34      6834845.72
      1496796.89      6834885.49      1496844.94      6834698.03
      1497001.93      6834730.45      1497170.28      6834187.81
      1497254.67        6834253.      1497154.27      6834722.95
      1497241.64      6834874.36      1497411.99      6834929.17
      1497541.64      6834701.64      1497799.31      6834639.88
      1498241.66      6835225.13      1498448.96      6835186.35
      1498798.83      6834845.86      1499015.48      6834738.94
      1499207.31      6834782.92       1499395.3      6834548.77
      1499898.38      6834247.42      1500646.52      6834134.49
      1500824.61       6833817.8        1501405.        6833338.

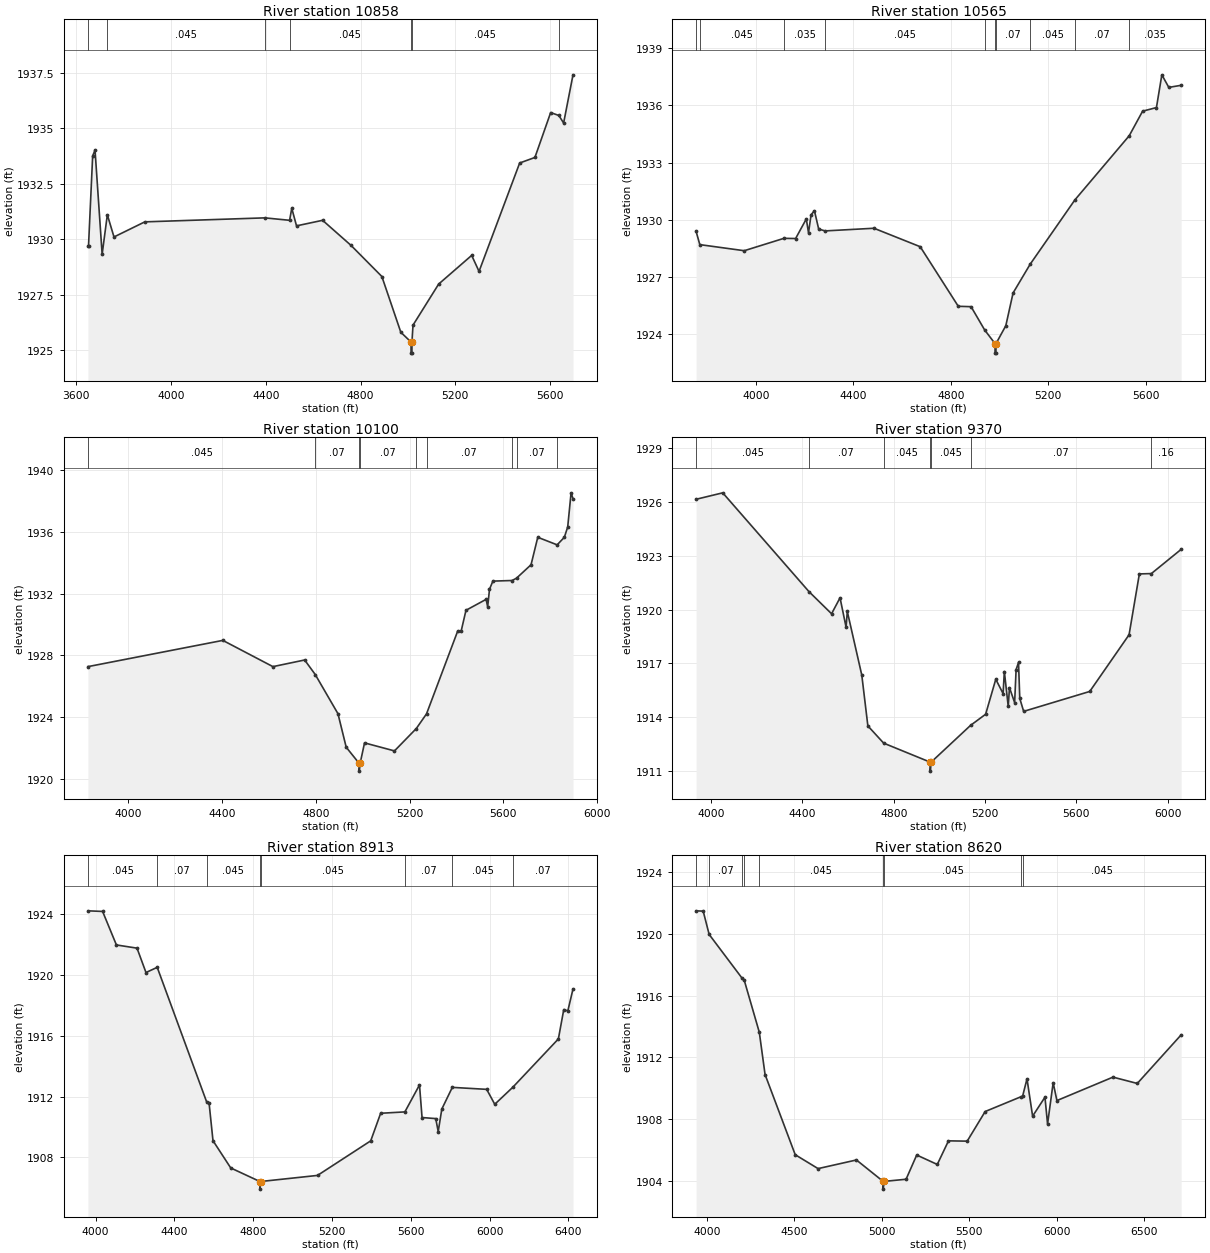
Type RM Length L Ch R = 1 ,10858   ,293,293,293
BEGIN DESCRIPTION:
MULBERRY CREEK TRIBUTARY 19 13.0
END DESCRIPTION:
XS GIS Cut Line= 3
        1494755.      6836888.01        1494755.        6835538.
      1494505.01      6834888.03
#Sta/Elev= 30
  3649.9  1929.7  3652.4  1929.7  3669.9 1933.76  3679.9 1934.02  3709.9 1929.33
  3731.8 1931.11  3759.9 1930.11  3889.9 1930.79  4396.4 1930.97  4500.7 1930.86
  4509.9  1931.4  4529.9 1930.61  4639.9 1930.86  4759.9 1929.73  4889.9 1928.33
  4969.9 1925.82  5012.9 1925.38  5013.2 1924.88  5016.7 1924.88  5016.9 1925.38
  5021.3 1926.14  5129.6 1927.99  5268.8 1929.28  5299.9 1928.56  5471.3 1933.44
  5535.6 1933.69    5602 1935.71  5636.5 1935.58  5656.7 1935.24  5696.3 1937.41
#Mann= 7 ,-1 , 0
  3649.9     .07       0  3731.8    .045       0  4396.4    .035       0
  4500.7    .045       0  5012.9    .045       0  5016.9    .045       0
  5636.5    .035       0
Bank Sta=5012.9,5016.9
XS Rating Curve= 0 ,0
Exp/Cntr=0.3,0.1

Type RM Length L Ch R = 1 ,10565   ,465,465,465
BEGIN DESCRIPTION:
Mapping XS d06490bc
END DESCRIPTION:
XS GIS Cut Line= 3
      1495346.12      6836581.01      1494998.89      6835396.09
      1494570.28      6834772.66
#Sta/Elev= 30
  3754.5 1929.39  3769.9 1928.69  3952.2 1928.37  4115.1 1929.02  4163.1 1929.01
    4207 1930.04  4216.1 1929.31  4226.6 1930.26  4240.4 1930.47  4257.8 1929.51
  4283.9 1929.41  4484.7 1929.55  4674.6 1928.58  4830.9 1925.45  4883.4 1925.43
    4939 1924.21  4981.7 1923.49  4981.9 1922.99  4985.4 1922.99  4985.7 1923.49
    5026 1924.43  5055.8 1926.15  5125.9 1927.66  5309.6 1931.04  5532.6 1934.41
  5587.5  1935.7  5644.3 1935.89  5666.5 1937.61  5695.1 1936.95  5745.8 1937.06
#Mann= 10 ,-1 , 0
  3754.5     .07       0  3769.9    .045       0  4115.1    .035       0
  4283.9    .045       0    4939     .07       0  4981.7     .07       0
  4985.7     .07       0  5125.9    .045       0  5309.6     .07       0
  5532.6    .035       0
Bank Sta=4981.7,4985.7
XS Rating Curve= 0 ,0
Exp/Cntr=0.3,0.1

Type RM Length L Ch R = 1 ,10100   ,730,730,730
BEGIN DESCRIPTION:
Mapping XS dc805829
END DESCRIPTION:
XS GIS Cut Line= 3
      1496092.65      6836120.93      1495545.77      6835456.86
      1494612.59      6834688.61
#Sta/Elev= 30
  3828.1 1927.27  4403.5 1928.97  4617.2 1927.27  4752.5  1927.7  4797.6 1926.76
  4894.6 1924.22  4929.7 1922.05  4985.1    1921  4985.3  1920.5  4989.1    1921
  5007.9 1922.33  5135.6 1921.81  5228.7 1923.26  5272.3 1924.21  5405.4 1929.58
  5419.7 1929.55  5440.6 1930.92  5526.6 1931.63  5533.1 1931.14  5540.9 1932.28
  5555.3 1932.81  5637.3 1932.85  5656.1    1933  5718.1 1933.87  5746.8 1935.65
  5829.4 1935.16  5860.2 1935.65  5874.5 1936.32  5888.9 1938.53  5897.1 1938.15
#Mann= 9 ,-1 , 0
  3828.1    .045       0  4797.6     .07       0  4985.1     .07       0
  4989.1     .07       0  5228.7    .045       0  5272.3     .07       0
  5637.3    .035       0  5656.1     .07       0  5829.4    .035       0
Bank Sta=4985.1,4989.1
XS Rating Curve= 0 ,0
Exp/Cntr=0.3,0.1

Type RM Length L Ch R = 1 ,9370    ,457,457,457
BEGIN DESCRIPTION:
Mapping XS 222fad43
END DESCRIPTION:
XS GIS Cut Line= 3
      1495936.39      6835704.24      1495606.53      6834701.65
      1494645.03      6834232.97
#Sta/Elev= 30
  3933.9 1926.15  4050.7 1926.51  4428.1 1921.01  4527.5 1919.77  4564.6 1920.66
  4591.1 1919.02  4596.4  1919.9  4659.9 1916.35  4686.5 1913.52  4755.7 1912.56
  4959.6  1911.5  4959.9    1911  4963.6  1911.5  5136.4 1913.55  5202.4 1914.17
  5246.9 1916.12  5278.9 1915.32  5284.4 1916.55  5301.4 1914.61  5306.9 1915.65
  5329.5 1914.82  5335.9 1916.66  5346.5 1917.06    5352 1915.05    5369 1914.33
  5658.5 1915.44  5830.8  1918.6  5875.9 1921.99  5928.5 1922.01    6059 1923.36
#Mann= 7 ,-1 , 0
  3933.9    .045       0  4428.1     .07       0  4755.7    .045       0
  4959.6    .045       0  4963.6    .045       0  5136.4     .07       0
  5928.5     .16       0
Bank Sta=4959.6,4963.6
XS Rating Curve= 0 ,0
Exp/Cntr=0.3,0.1

Type RM Length L Ch R = 1 ,8913    ,293,293,293
BEGIN DESCRIPTION:
Mapping XS 78bcc9ab
END DESCRIPTION:
XS GIS Cut Line= 4
      1496068.51      6835722.53      1496033.79      6834708.59
      1495874.07      6834469.01       1494749.5       6834184.4
#Sta/Elev= 30
  3960.9 1924.19  4035.5 1924.15  4105.5 1921.95  4210.1 1921.74  4255.6 1920.14
  4312.7 1920.48  4563.5 1911.65  4575.8 1911.59  4595.8  1909.1  4685.9 1907.31
  4833.9 1906.42  4834.2 1905.92  4837.9 1906.42  5126.4 1906.82  5396.5 1909.09
  5446.9  1910.9  5569.9 1910.99  5644.1 1912.76  5657.1 1910.62  5726.6 1910.55
  5739.1  1909.7  5757.5 1911.18  5810.7  1912.6  5985.2 1912.47  6026.2 1911.49
  6117.9 1912.61  6349.1 1915.78  6376.5 1917.71  6397.1 1917.62  6423.4 1919.06
#Mann= 8 ,-1 , 0
  3960.9    .045       0  4312.7     .07       0  4563.5    .045       0
  4833.9    .045       0  4837.9    .045       0  5569.9     .07       0
  5810.7    .045       0  6117.9     .07       0
Bank Sta=4833.9,4837.9
XS Rating Curve= 0 ,0
Exp/Cntr=0.3,0.1

Type RM Length L Ch R = 1 ,8620    ,842,842,842
BEGIN DESCRIPTION:
Mapping XS 036e4fa5
END DESCRIPTION:
XS GIS Cut Line= 4
      1496131.01      6835638.33      1496276.85       6834610.5
      1496297.68      6834499.39      1494780.28      6833929.93
#Sta/Elev= 30
  3938.5  1921.5  3979.2 1921.48  4013.2 1919.97  4198.9 1917.17  4213.5 1917.01
  4299.8 1913.63  4332.7 1910.89  4505.1 1905.69  4635.7 1904.79  4854.8 1905.35
  5007.7 1903.96  5007.9 1903.46  5011.7 1903.96  5138.5  1904.1  5199.3 1905.67
  5316.8 1905.06  5380.9 1906.59  5487.7 1906.57  5590.4 1908.49  5795.4 1909.45
  5804.3 1909.48  5829.5 1910.61  5861.6 1908.19  5932.1 1909.42    5947 1907.68
    5979 1910.36  6000.4  1909.2  6320.8 1910.72  6459.7 1910.31  6710.4 1913.46
#Mann= 9 ,-1 , 0
  3938.5    .045       0  4013.2     .07       0  4198.9    .045       0
  4213.5     .07       0  4299.8    .045       0  5007.7    .045       0
  5011.7    .045       0  5795.4     .07       0  5804.3    .045       0
Bank Sta=5007.7,5011.7
XS Rating Curve= 0 ,0
Exp/Cntr=0.3,0.1

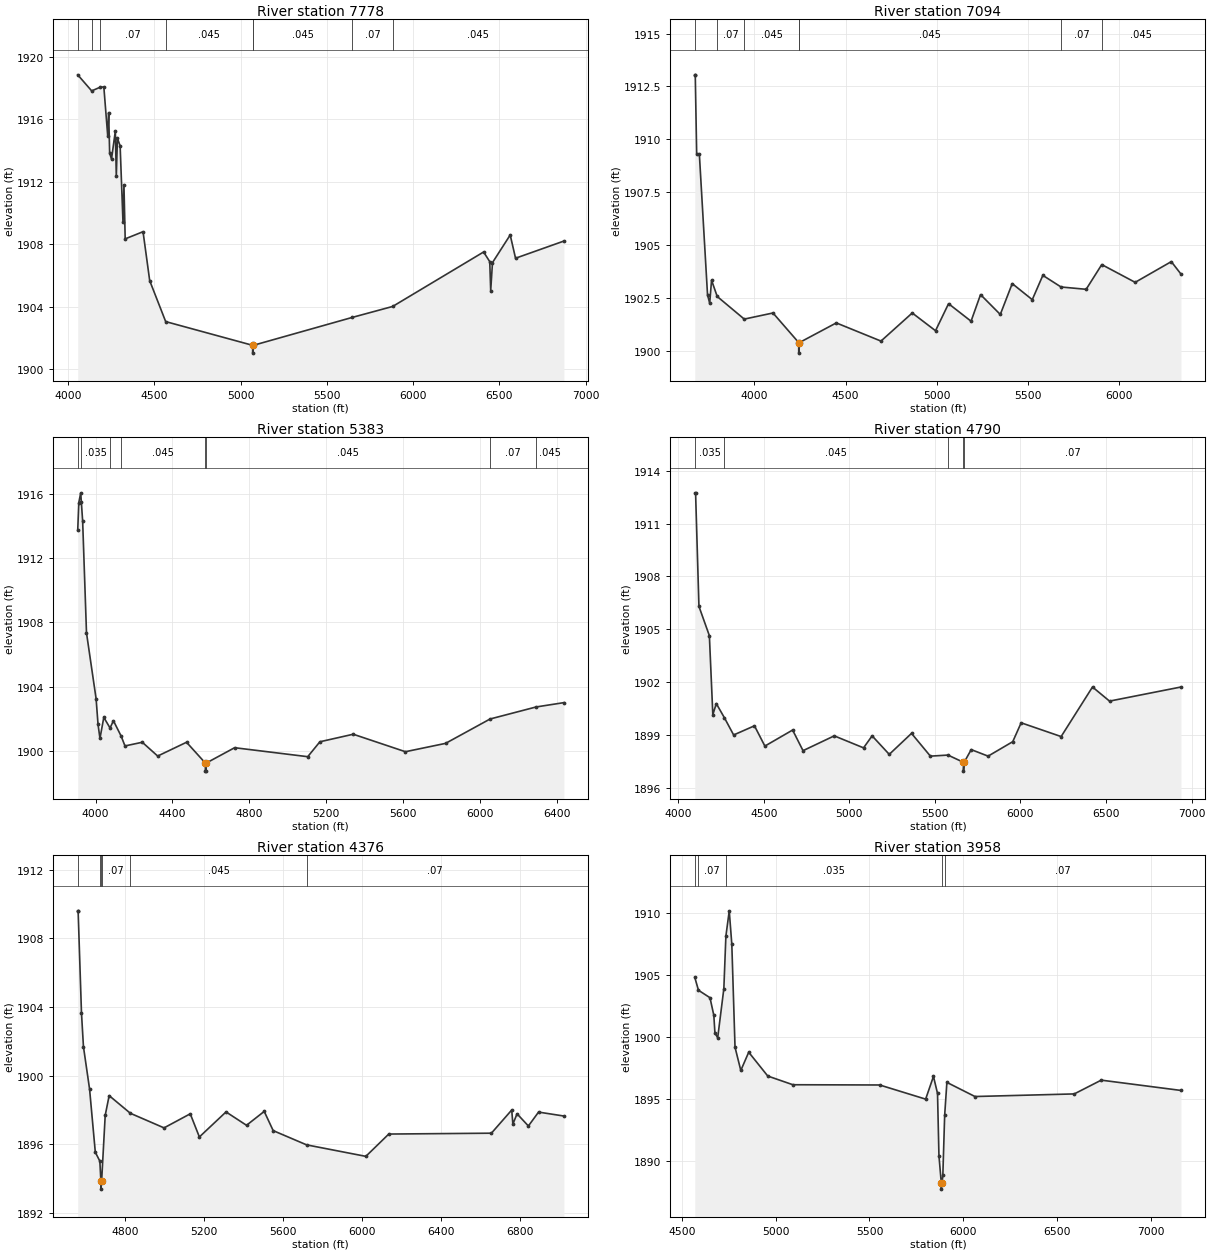
Type RM Length L Ch R = 1 ,7778    ,684,684,684
BEGIN DESCRIPTION:
Mapping XS 7b5b92d0
END DESCRIPTION:
XS GIS Cut Line= 5
      1496317.65      6835722.47      1496689.17      6835003.73
      1496647.51      6834646.09      1496453.06      6834267.62
      1495262.25      6833982.94
#Sta/Elev= 30
  4055.4 1918.86  4136.4 1917.83  4181.9 1918.05  4206.8 1918.09  4229.2 1914.97
  4234.8 1916.44  4240.5 1913.85  4251.3 1913.46  4273.5 1915.26  4279.1 1912.36
  4285.6 1914.79  4301.3 1914.31  4317.8 1909.44  4323.4 1911.82  4330.6 1908.35
  4434.1 1908.81  4472.8 1905.67  4565.4 1903.05  5069.6 1901.53  5069.9 1901.03
  5073.6 1901.53  5647.8 1903.32  5881.5 1904.02  6408.9 1907.51  6444.5 1906.89
    6450 1905.04  6460.3 1906.83  6563.1  1908.6    6594 1907.11  6874.4 1908.21
#Mann= 8 ,-1 , 0
  4055.4     .07       0  4136.4     .16       0  4181.9     .07       0
  4565.4    .045       0  5069.6    .045       0  5073.6    .045       0
  5647.8     .07       0  5881.5    .045       0
Bank Sta=5069.6,5073.6
XS Rating Curve= 0 ,0
Exp/Cntr=0.3,0.1

Type RM Length L Ch R = 1 ,7094    ,1711,1711,1711
BEGIN DESCRIPTION:
Mapping XS 60ef028a
END DESCRIPTION:
XS GIS Cut Line= 4
      1497335.02      6835857.95      1497089.95      6834686.87
      1496959.74      6834500.23        1495901.       6833847.5
#Sta/Elev= 30
  3672.6 1913.05  3675.1 1913.05  3682.8 1909.31  3697.6 1909.29  3742.4 1902.64
  3754.3 1902.24  3764.5 1903.33  3795.6 1902.56  3943.9 1901.49  4101.6 1901.78
  4242.7 1900.38  4242.9 1899.88  4246.7 1900.38    4449 1901.31  4694.2 1900.45
  4865.8 1901.78  4993.5 1900.94    5065 1902.22  5188.5 1901.39  5240.5 1902.65
  5348.9 1901.71  5414.4 1903.17  5524.4 1902.41  5582.4 1903.56  5682.2 1903.01
    5820  1902.9  5905.7 1904.07    6089 1903.23  6287.3 1904.21  6340.4 1903.62
#Mann= 7 ,-1 , 0
  3672.6    .035       0  3795.6     .07       0  3943.9    .045       0
  4242.7    .045       0  4246.7    .045       0  5682.2     .07       0
  5905.7    .045       0
Bank Sta=4242.7,4246.7
XS Rating Curve= 0 ,0
Exp/Cntr=0.3,0.1

Type RM Length L Ch R = 1 ,5383    ,593,593,593
BEGIN DESCRIPTION:
Mapping XS a818a462
END DESCRIPTION:
XS GIS Cut Line= 4
      1497518.77      6835823.65      1497512.09      6834736.37
      1497385.42      6834108.67      1496622.25      6833868.59
#Sta/Elev= 30
  3907.3 1913.74  3912.9 1915.47  3922.9 1916.08    3926 1915.53  3932.9 1914.32
  3952.9 1907.35  4002.9 1903.24  4012.9 1901.64  4022.9 1900.77  4042.9 1902.08
  4075.3 1901.42    4093 1901.87  4133.2 1900.91    4153  1900.3    4243 1900.53
    4323 1899.67    4473 1900.53    4571 1899.23  4571.2 1898.73  4574.7 1898.73
    4575 1899.23    4723 1900.19  5103.2 1899.63  5166.4 1900.56  5339.8 1901.03
    5611 1899.94  5819.7 1900.46  6051.2 1901.98  6290.6 1902.73    6435    1903
#Mann= 8 ,-1 , 0
  3907.3     .07       0    3926    .035       0  4075.3     .07       0
  4133.2    .045       0    4571    .045       0    4575    .045       0
  6051.2     .07       0  6290.6    .045       0
Bank Sta=4571,4575
XS Rating Curve= 0 ,0
Exp/Cntr=0.3,0.1

Type RM Length L Ch R = 1 ,4790    ,414,414,414
BEGIN DESCRIPTION:
Mapping XS 21b131bb
END DESCRIPTION:
XS GIS Cut Line= 4
      1497781.94      6835701.92      1497928.68      6834810.93
      1497896.52      6834142.88      1496678.88      6833785.57
#Sta/Elev= 30
    4097 1912.74  4101.5 1912.74  4121.2  1906.3  4182.1 1904.64  4202.3 1900.16
  4222.6 1900.79  4270.3 1899.98  4323.9 1899.01  4445.6 1899.53  4506.4 1898.38
  4668.5 1899.29  4729.3 1898.12  4911.8 1898.96    5083 1898.28  5133.1 1898.96
  5233.2 1897.91  5363.3  1899.1  5473.5 1897.81  5576.3 1897.87  5666.8 1897.46
    5667 1896.96  5670.8 1897.46  5712.1 1898.18  5810.8 1897.81  5954.8 1898.63
  6003.9  1899.7  6237.5 1898.92  6420.8 1901.73  6520.3 1900.93  6937.8 1901.73
#Mann= 5 ,-1 , 0
    4097    .035       0  4270.3    .045       0  5576.3     .07       0
  5666.8    .045       0  5670.8     .07       0
Bank Sta=5666.8,5670.8
XS Rating Curve= 0 ,0
Exp/Cntr=0.3,0.1

Type RM Length L Ch R = 1 ,4376    ,418,418,418
BEGIN DESCRIPTION:
Mapping XS 5d6b9e52
END DESCRIPTION:
XS GIS Cut Line= 4
      1498157.79      6835546.98      1498175.18      6835107.92
      1498388.45      6834336.74      1497364.22      6833671.93
#Sta/Elev= 30
  4560.6 1909.61  4562.6 1909.61  4579.6 1903.66  4589.6 1901.69  4620.6 1899.22
  4649.6 1895.54  4672.6 1895.02  4677.7 1893.89  4677.9 1893.39  4681.7 1893.89
  4699.7 1897.69  4719.7 1898.84  4827.1 1897.81  4997.5 1896.96  5130.1 1897.78
  5176.3 1896.43  5311.2 1897.89  5414.9 1897.11  5504.5 1897.92  5549.8  1896.8
  5718.9 1895.97  6018.8  1895.3  6134.9  1896.6  6654.3 1896.65  6757.1    1898
    6763 1897.18  6784.1 1897.78  6841.5 1897.07  6892.9 1897.88  7021.2 1897.65
#Mann= 6 ,-1 , 0
  4560.6    .035       0  4672.6     .07       0  4677.7    .045       0
  4681.7     .07       0  4827.1    .045       0  5718.9     .07       0
Bank Sta=4677.7,4681.7
XS Rating Curve= 0 ,0
Exp/Cntr=0.3,0.1

Type RM Length L Ch R = 1 ,3958    ,759,759,759
BEGIN DESCRIPTION:
Mapping XS efd1ff02
END DESCRIPTION:
XS GIS Cut Line= 4
      1498534.53      6835606.76      1498440.77      6835205.68
      1498628.27      6834450.47      1497504.75      6833612.21
#Sta/Elev= 30
    4569 1904.81  4588.6 1903.78  4649.9 1903.18  4670.4 1901.76  4676.2 1900.34
    4691 1899.95  4723.8 1903.91  4734.7 1908.14  4752.6 1910.18  4766.3 1907.48
  4783.4 1899.19  4814.2 1897.32  4856.4 1898.79    4958 1896.87  5091.8 1896.17
  5554.5 1896.15  5799.6 1895.01  5841.3 1896.84  5862.9 1895.47  5870.5 1890.46
    5883 1888.26  5883.3 1887.76  5887.2 1888.26  5891.3 1888.89    5901  1893.7
  5912.8 1896.36  6062.5 1895.22  6591.9 1895.43  6735.7 1896.54  7160.8 1895.71
#Mann= 5 ,-1 , 0
    4569    .035       0  4588.6     .07       0  4734.7    .035       0
  5887.2    .035       0    5901     .07       0
Bank Sta=5883,5887.2
XS Rating Curve= 0 ,0
Exp/Cntr=0.3,0.1

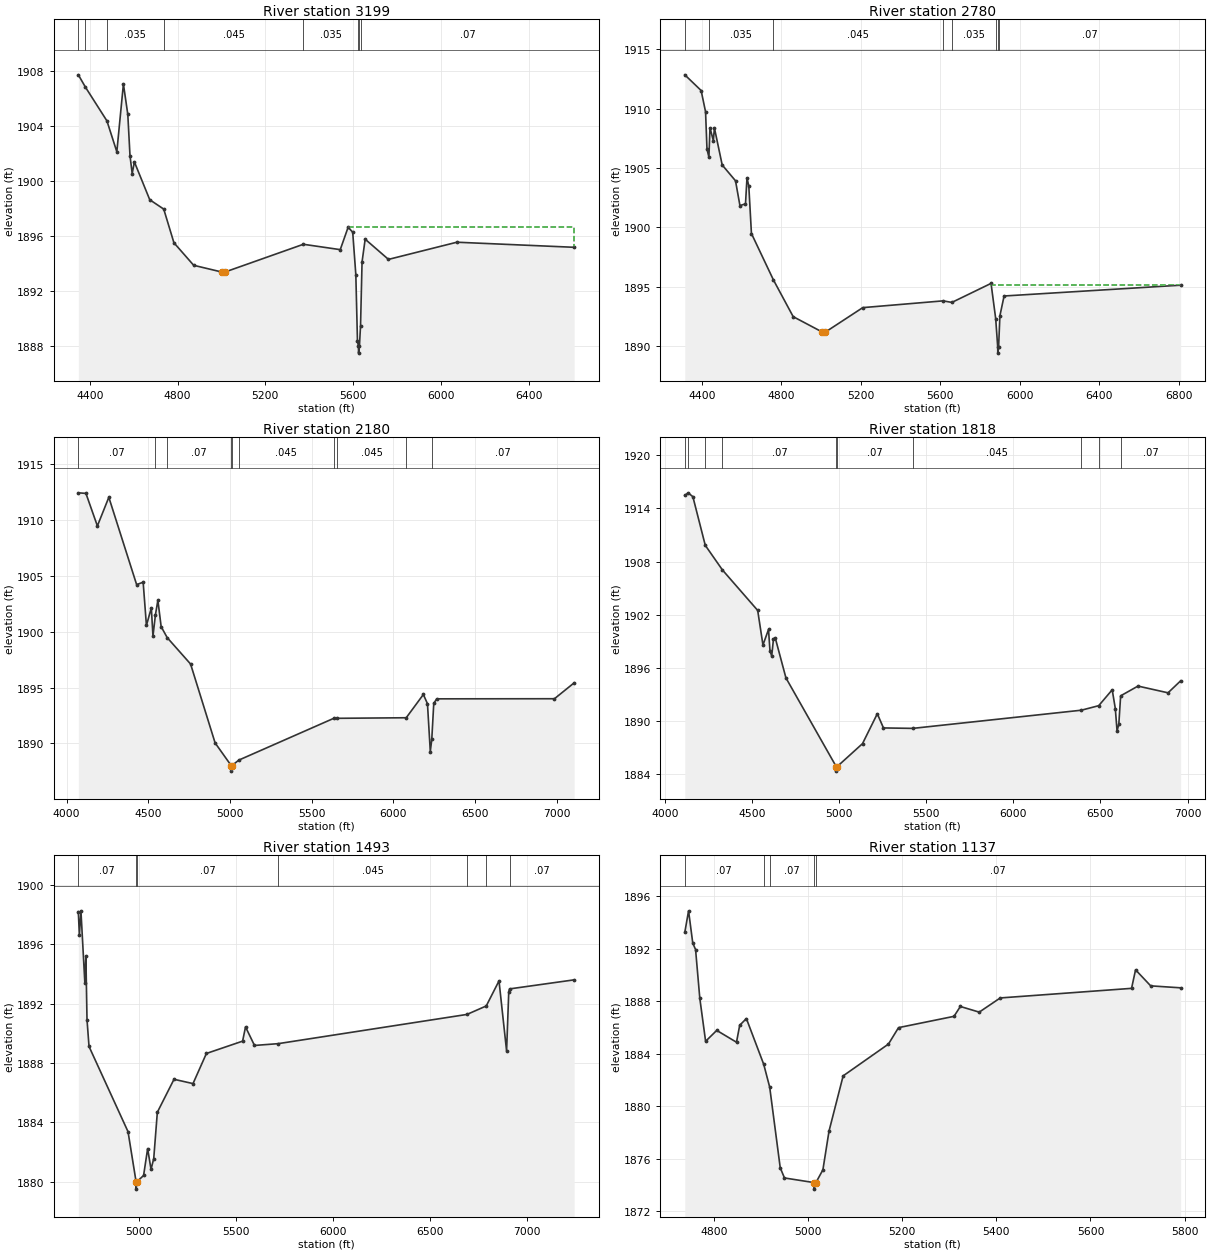
Type RM Length L Ch R = 1 ,3199    ,419,419,419
BEGIN DESCRIPTION:
Mapping XS 2412f179
END DESCRIPTION:
XS GIS Cut Line= 3
      1499039.73      6835393.23       1499006.5      6834741.47
      1497810.63      6833666.95
#Sta/Elev= 30
  4347.4 1907.71  4379.5 1906.82  4477.7 1904.36  4522.9 1902.11  4552.9 1907.04
  4572.9 1904.83  4582.9 1901.83  4592.9 1900.53    4603 1901.37    4673 1898.62
  4736.7 1897.94  4783.2 1895.49  4873.3 1893.85  5004.4 1893.35  5017.4 1893.37
  5373.3 1895.38  5541.4 1894.99  5577.3 1896.62  5598.2 1896.26  5612.4 1893.17
  5619.9 1888.33  5624.5 1887.96  5624.8 1887.46  5628.8 1887.96  5633.9 1889.46
  5640.8  1894.1    5655 1895.75  5761.2 1894.28  6072.9 1895.53  6607.7 1895.16
#Mann= 8 ,-1 , 0
  4347.4    .035       0  4379.5     .07       0  4477.7    .035       0
  4736.7    .045       0  5373.3    .035       0  5624.5    .045       0
  5628.8    .035       0  5633.9     .07       0
#XS Ineff= 2 , 0
       0                  5577.3       0 1896.62
Permanent Ineff=
       F       F
Bank Sta=5004.4,5017.4
XS Rating Curve= 0 ,0
Exp/Cntr=0.3,0.1

Type RM Length L Ch R = 1 ,2780    ,600,600,600
BEGIN DESCRIPTION:
MULBERRY CREEK TRIBUTARY 19 6.0
END DESCRIPTION:
XS GIS Cut Line= 3
      1499626.11      6835237.88      1499318.62      6834624.76
       1497824.5      6833602.43
#Sta/Elev= 30
  4314.1 1912.84  4396.3 1911.52  4418.6 1909.73  4425.8 1906.58  4435.5 1905.91
  4440.9 1908.38  4457.7 1907.31  4463.3 1908.36  4502.4 1905.25  4569.4 1903.92
  4591.7 1901.83  4619.7 1901.98  4627.2 1904.16  4636.4 1903.47  4649.6 1899.48
  4760.4 1895.57  4859.8 1892.48  5006.8 1891.18  5021.7 1891.18    5210 1893.24
  5614.5 1893.81  5658.8 1893.68  5855.9 1895.28  5879.3 1892.32  5889.6 1889.91
  5889.9 1889.41  5893.9 1889.91  5900.6 1892.56  5921.6 1894.22  6810.4 1895.13
#Mann= 8 ,-1 , 0
  4314.1     .07       0  4435.5    .035       0  4760.4    .045       0
  5614.5     .07       0  5658.8    .035       0  5879.3     .07       0
  5889.6    .045       0  5893.9     .07       0
#XS Ineff= 2 , 0
       0                  5849.8       0 1895.18
Permanent Ineff=
       F       F
Bank Sta=5006.8,5021.7
XS Rating Curve= 0 ,0
Exp/Cntr=0.3,0.1

Type RM Length L Ch R = 1 ,2180    ,362,362,362
BEGIN DESCRIPTION:
Mapping XS b39ff30c
END DESCRIPTION:
XS GIS Cut Line= 3
      1499829.84      6835224.49      1499798.59       6834294.8
      1497815.11      6833593.25
#Sta/Elev= 30
  4071.7  1912.4  4118.2 1912.35  4188.3 1909.44  4258.3    1912  4428.4  1904.2
  4468.4 1904.41  4488.4 1900.55  4518.4 1902.12  4528.4 1899.59  4543.5  1901.5
  4558.5  1902.8  4578.5 1900.44  4615.5 1899.46  4758.6  1897.1  4908.7 1890.05
    5007 1888.03  5007.3 1887.53  5011.4 1888.03  5054.4 1888.52  5633.4 1892.24
  5657.2 1892.25  6078.2  1892.3  6183.1 1894.38  6208.2 1893.55  6225.5 1889.28
  6234.5 1890.36  6246.7 1893.58  6264.8 1893.99  6985.3    1894  7105.8 1895.42
#Mann= 10 ,-1 , 0
  4071.7     .07       0  4543.5    .035       0  4615.5     .07       0
    5007     .07       0  5011.4     .07       0  5054.4    .045       0
  5633.4     .07       0  5657.2    .045       0  6078.2    .035       0
  6234.5     .07       0
#XS Ineff= 2 , 0
       0                  6177.3       0 1894.18
Permanent Ineff=
       F       F
Bank Sta=5007,5011.4
XS Rating Curve= 0 ,0
Exp/Cntr=0.3,0.1

Type RM Length L Ch R = 1 ,1818    ,325,325,325
BEGIN DESCRIPTION:
Mapping XS f54e5a67
END DESCRIPTION:
XS GIS Cut Line= 4
      1500042.05      6835114.21      1500128.86      6834254.84
      1499755.59      6833868.56      1498323.31      6833681.93
#Sta/Elev= 30
    4115 1915.47  4134.4 1915.76  4161.4 1915.32  4232.5 1909.84  4330.7 1907.07
  4533.3  1902.5  4563.5  1898.6  4595.4 1900.35  4603.7 1897.97  4613.7 1897.35
  4623.8 1899.27  4633.8 1899.42  4695.4 1894.89  4984.2 1884.88  4984.5 1884.38
  4988.6 1884.88  5134.8 1887.48  5219.7 1890.85    5255 1889.25  5423.2  1889.2
  6390.8 1891.25  6490.3 1891.76  6567.7 1893.55  6585.5 1891.44  6595.5 1888.91
  6605.6 1889.66  6616.1 1892.87  6715.7 1893.97    6888 1893.21  6960.3 1894.56
#Mann= 10 ,-1 , 0
    4115    .035       0  4134.4     .07       0  4232.5    .035       0
  4330.7     .07       0  4984.2     .07       0  4988.6     .07       0
  5423.2    .045       0  6390.8     .07       0  6490.3    .035       0
  6616.1     .07       0
Bank Sta=4984.2,4988.6
XS Rating Curve= 0 ,0
Exp/Cntr=0.3,0.1

Type RM Length L Ch R = 1 ,1493    ,356,356,356
BEGIN DESCRIPTION:
Mapping XS 2e02ce19
END DESCRIPTION:
XS GIS Cut Line= 5
      1500329.37      6834530.92      1500412.71      6834242.69
       1500364.1      6834086.44      1499749.52      6833808.66
      1498339.88      6833655.89
#Sta/Elev= 30
  4686.4 1898.19  4691.7 1896.61  4699.8 1898.25  4720.1 1893.38  4725.3  1895.2
  4731.1 1890.92  4741.5 1889.11  4942.6 1883.37  4984.1    1880  4984.4  1879.5
  4988.5    1880  5022.8 1880.42  5043.7 1882.23  5061.2 1880.83  5075.1 1881.56
  5093.7 1884.68  5179.6  1886.9  5277.6 1886.61  5346.6 1888.64  5533.2 1889.47
  5548.3 1890.43  5594.5 1889.18  5716.1  1889.3  6689.9 1891.27  6789.2 1891.84
    6855 1893.53  6894.1 1888.81  6905.3 1892.81  6909.6 1892.99  7242.4  1893.6
#Mann= 7 ,-1 , 0
  4686.4     .07       0  4984.1     .07       0  4988.5     .07       0
  5716.1    .045       0  6689.9     .07       0  6789.2    .035       0
  6909.6     .07       0
Bank Sta=4984.1,4988.5
XS Rating Curve= 0 ,0
Exp/Cntr=0.3,0.1

Type RM Length L Ch R = 1 ,1137    ,57,57,57
BEGIN DESCRIPTION:
MULBERRY CREEK TRIBUTARY 19 2.0
END DESCRIPTION:
XS GIS Cut Line= 3
      1500831.06      6834274.61      1500684.66      6834057.94
      1499945.61      6833774.59
#Sta/Elev= 30
  4738.5 1893.23  4746.5 1894.87  4755.4 1892.42  4761.4 1891.92  4770.4  1888.2
  4782.7 1884.94  4806.3 1885.77  4848.3 1884.87  4855.1 1886.16  4869.3 1886.67
  4906.1 1883.19  4918.8 1881.45  4941.2 1875.31  4950.2 1874.54  5012.5 1874.19
  5012.8 1873.69    5017 1874.19  5031.8 1875.16  5044.8 1878.11  5074.8 1882.31
    5171 1884.73  5192.4 1885.98  5310.2 1886.84  5323.7 1887.59  5363.8 1887.16
  5408.4 1888.24  5687.3 1888.97  5695.8 1890.38  5727.9 1889.16  5791.5 1889.01
#Mann= 5 ,-1 , 0
  4738.5     .07       0  4906.1     .16       0  4918.8     .07       0
  5012.5     .07       0    5017     .07       0
Bank Sta=5012.5,5017
XS Rating Curve= 0 ,0
Exp/Cntr=0.3,0.1

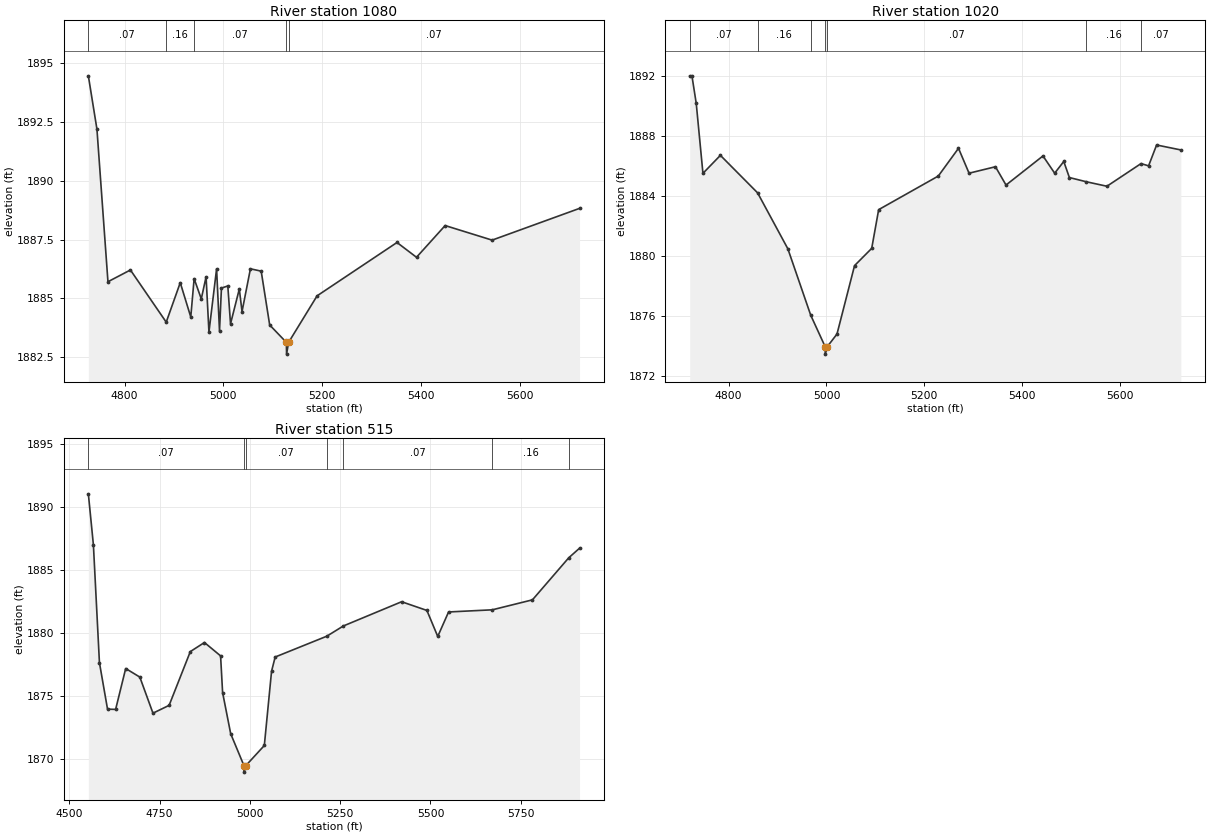
Type RM Length L Ch R = 1 ,1080    ,60,60,60
BEGIN DESCRIPTION:
Mapping XS 6747f0e6
END DESCRIPTION:
XS GIS Cut Line= 4
      1500866.57      6834251.97      1500725.93      6834020.18
      1500686.87      6833931.64      1500082.73      6833764.98
#Sta/Elev= 30
  4726.5 1894.47  4743.9  1892.2  4766.2 1885.71  4811.7 1886.21  4884.2 1883.99
  4912.6 1885.67  4933.9 1884.21  4940.7 1885.84  4955.2 1884.98  4964.9 1885.92
  4970.7 1883.57  4986.2 1886.26  4992.1 1883.61    4996 1885.44  5008.9 1885.53
  5014.4 1883.92  5032.2  1885.4  5037.7 1884.44  5054.7 1886.26  5076.5 1886.16
  5093.7 1883.87  5127.5 1883.13  5127.9 1882.63    5132 1883.13  5189.7 1885.11
  5351.5 1887.38    5391 1886.75    5449  1888.1  5544.1 1887.48  5721.1 1888.83
#Mann= 5 ,-1 , 0
  4726.5     .07       0  4884.2     .16       0  4940.7     .07       0
  5127.5     .07       0    5132     .07       0
Bank Sta=5127.5,5132
XS Rating Curve= 0 ,0
Exp/Cntr=0.3,0.1

Type RM Length L Ch R = 1 ,1020    ,505,505,505
BEGIN DESCRIPTION:
Mapping XS 44480c8e
END DESCRIPTION:
XS GIS Cut Line= 4
      1500919.52      6834210.74      1500761.09      6833965.49
      1500628.71      6833846.13      1500133.91      6833644.31
#Sta/Elev= 30
  4720.3 1892.04  4724.9 1892.04  4733.7  1890.2  4747.4 1885.54  4783.1 1886.74
  4859.2 1884.24  4921.1 1880.51  4967.9 1876.08  4997.3 1873.99  4997.6 1873.49
  5001.8 1873.99  5021.6 1874.83  5057.5 1879.39  5092.6 1880.54  5106.8 1883.12
  5228.8 1885.36  5270.1 1887.21  5291.7 1885.55  5345.7 1885.98  5367.3 1884.76
  5442.9  1886.7  5466.8 1885.55  5485.4 1886.33  5496.9 1885.26  5531.4 1884.98
  5573.7 1884.68  5643.4 1886.19  5658.9 1886.04  5675.3 1887.43  5724.9  1887.1
#Mann= 7 ,-1 , 0
  4720.3     .07       0  4859.2     .16       0  4967.9     .07       0
  4997.3     .07       0  5001.8     .07       0  5531.4     .16       0
  5643.4     .07       0
Bank Sta=4997.3,5001.8
XS Rating Curve= 0 ,0
Exp/Cntr=0.3,0.1

Type RM Length L Ch R = 1 ,515     ,0,0,0
BEGIN DESCRIPTION:
MULBERRY CREEK TRIBUTARY 19 1.0
END DESCRIPTION:
XS GIS Cut Line= 3
        1501255.      6834037.99        1501055.        6833638.
      1500142.57      6833620.44
#Sta/Elev= 30
  4552.8 1891.02  4566.8 1886.97  4583.5 1877.64  4605.9 1873.96  4628.3 1873.94
  4656.2 1877.18  4695.3  1876.5  4731.7 1873.64  4776.4 1874.26  4835.1 1878.52
  4874.2 1879.24  4918.9 1878.18  4924.5 1875.27  4946.9 1872.01  4983.8 1869.47
  4984.1 1868.97  4988.3 1869.47    5040 1871.08    5060 1876.96    5070 1878.09
    5213 1879.74  5258.8 1880.55  5420.1 1882.47  5490.1 1881.78  5520.1 1879.72
  5550.1 1881.66  5671.1 1881.83  5782.3 1882.62  5882.7 1885.95  5912.6 1886.71
#Mann= 7 ,-1 , 0
  4552.8     .07       0  4983.8     .07       0  4988.3     .07       0
    5213     .16       0  5258.8     .07       0  5671.1     .16       0
  5882.7     .07       0
Bank Sta=4983.8,4988.3
XS Rating Curve= 0 ,0
Exp/Cntr=0.3,0.1

Chan Stop Cuts=-1
Use User Specified Reach Order=0
Composite Channel Slope=5