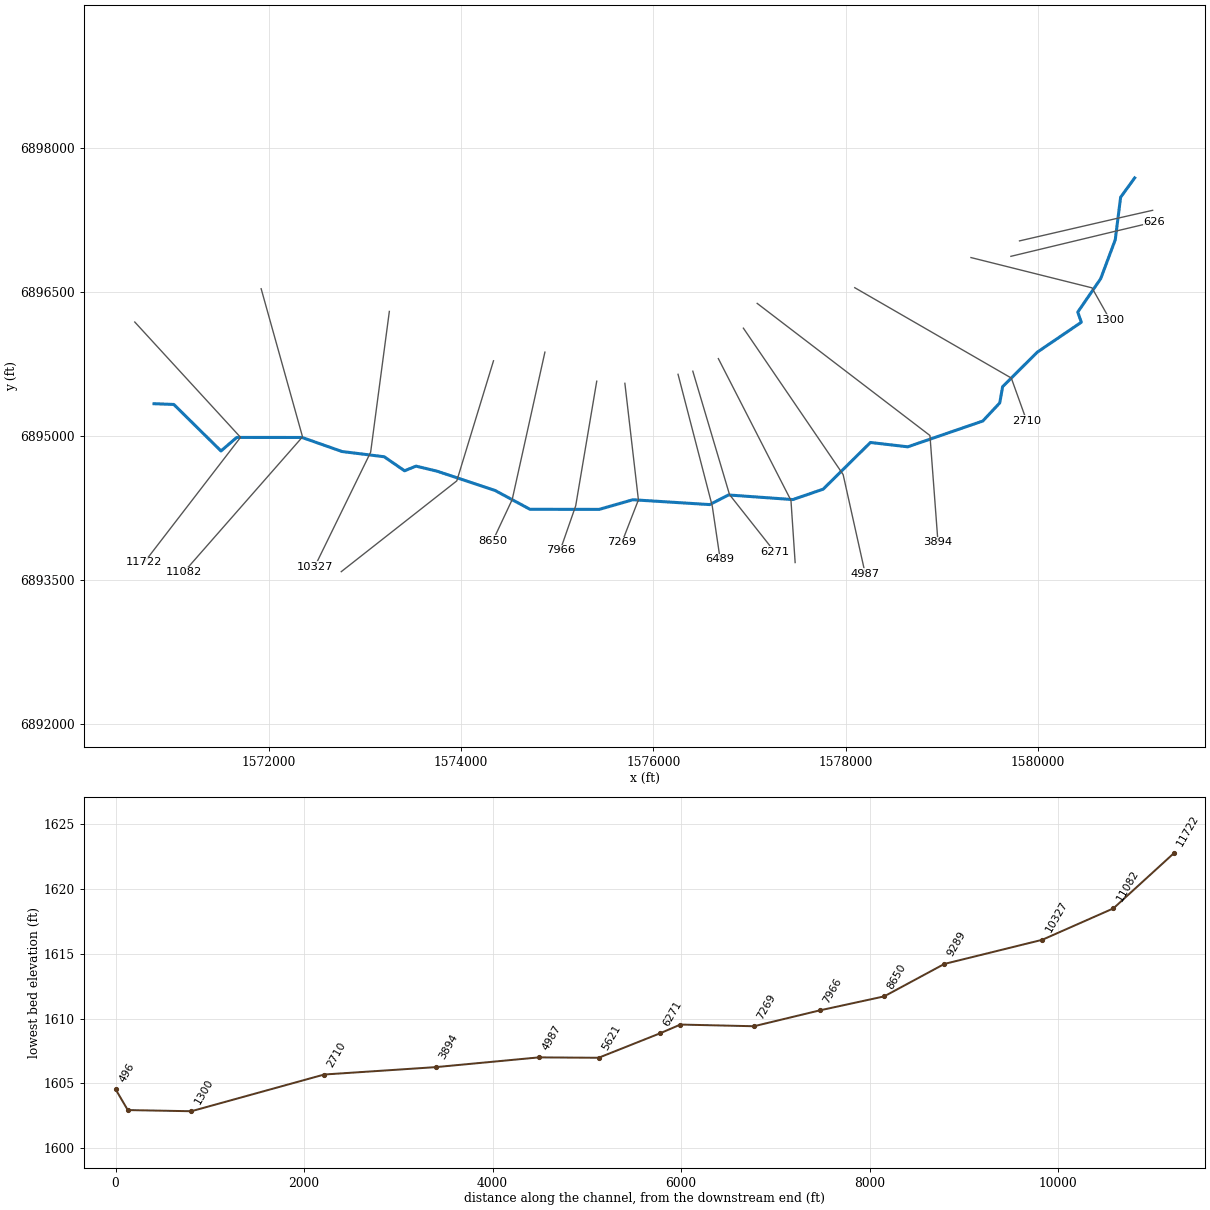
--- MULBERRY CREEK TRIBUTARY 1_1.prj (project) ---

Proj Title=MULBERRY CREEK TRIBUTARY 1_1 Base Level Engineering
Current Plan=p01
Default Exp/Contr=0.3,0.1
English Units
Geom File=g01
Flow File=f01
Plan File=p01
BEGIN DESCRIPTION:
MULBERRY CREEK TRIBUTARY 1_1
END DESCRIPTION:

--- MULBERRY CREEK TRIBUTARY 1_1.p01 (plan) ---

Plan Title=Multiple Run
Short Identifier=Multiple
Geom File=g01
Flow File=f01
Subcritical Flow
K Sum by GR= 0
Std Step Tol= 0.01
Critical Tol= 0.01
Num of Std Step Trials= 20
Max Error Tol= 0.3
Flow Tol Ratio= 0.001
Split Flow NTrial= 30
Split Flow Tol= 0.02
Split Flow Ratio= 0.02
Log Output Level= 0
Friction Slope Method= 1
Unsteady Friction Slope Method= 2
Unsteady Bridges Friction Slope Method= 1
Parabolic Critical Depth
Global Vel Dist=  1 , 1 , 1
Global Log Level= 0
CheckData=True
Encroach Param= -1, 0, 0, 0
BEGIN DESCRIPTION:
Multiple Run
END DESCRIPTION:

--- MULBERRY CREEK TRIBUTARY 1_1.f01 (steady flow) ---

Flow Title=Multiple
Number of Profiles=7
Profile Names=10-year,25-year,50-year,1pct_min,100-year,1pct_plu,500-year
River Rch & RM= MULBERRY CREEK T,Reach-1,11722
     252     346     422     256     511    1020     760
River Rch & RM= MULBERRY CREEK T,Reach-1,7269
     313     432     530     322     643    1284     963
Boundary for River Rch & Prof#=MULBERRY CREEK T,Reach-1,1
Up Type=0
Dn Type=3
Dn Slope=0.005
Boundary for River Rch & Prof#=MULBERRY CREEK T,Reach-1,2
Up Type=0
Dn Type=3
Dn Slope=0.005
Boundary for River Rch & Prof#=MULBERRY CREEK T,Reach-1,3
Up Type=0
Dn Type=3
Dn Slope=0.005
Boundary for River Rch & Prof#=MULBERRY CREEK T,Reach-1,4
Up Type=0
Dn Type=3
Dn Slope=0.005
Boundary for River Rch & Prof#=MULBERRY CREEK T,Reach-1,5
Up Type=0
Dn Type=3
Dn Slope=0.005
Boundary for River Rch & Prof#=MULBERRY CREEK T,Reach-1,6
Up Type=0
Dn Type=3
Dn Slope=0.005
Boundary for River Rch & Prof#=MULBERRY CREEK T,Reach-1,7
Up Type=0
Dn Type=3
Dn Slope=0.005

--- MULBERRY CREEK TRIBUTARY 1_1.g01 (geometry) ---

Geom Title=Existing Conditions

River Reach=MULBERRY CREEK T,Reach-1
Reach XY= 30
      1570805.00      6895338.00      1571011.21      6895330.20
      1571501.77      6894845.83      1571665.43      6894986.95
      1572344.50      6894986.78      1572760.93      6894840.24
      1573199.14      6894785.93      1573411.11      6894639.80
      1573530.00      6894688.39      1573749.06      6894635.73
      1574353.50      6894434.38      1574715.50      6894239.22
      1575434.97      6894238.07      1575784.85      6894338.36
      1576584.97      6894288.06      1576779.91      6894388.21
      1577449.06      6894340.26      1577764.79      6894448.52
      1578256.47      6894934.47      1578644.49      6894889.22
      1579425.09      6895157.78      1579601.59      6895346.44
      1579631.17      6895514.87      1579991.79      6895874.38
      1580449.88      6896185.71      1580412.84      6896291.40
      1580651.39      6896639.50      1580802.76      6897043.93
      1580858.55      6897486.53      1581005.00      6897688.00

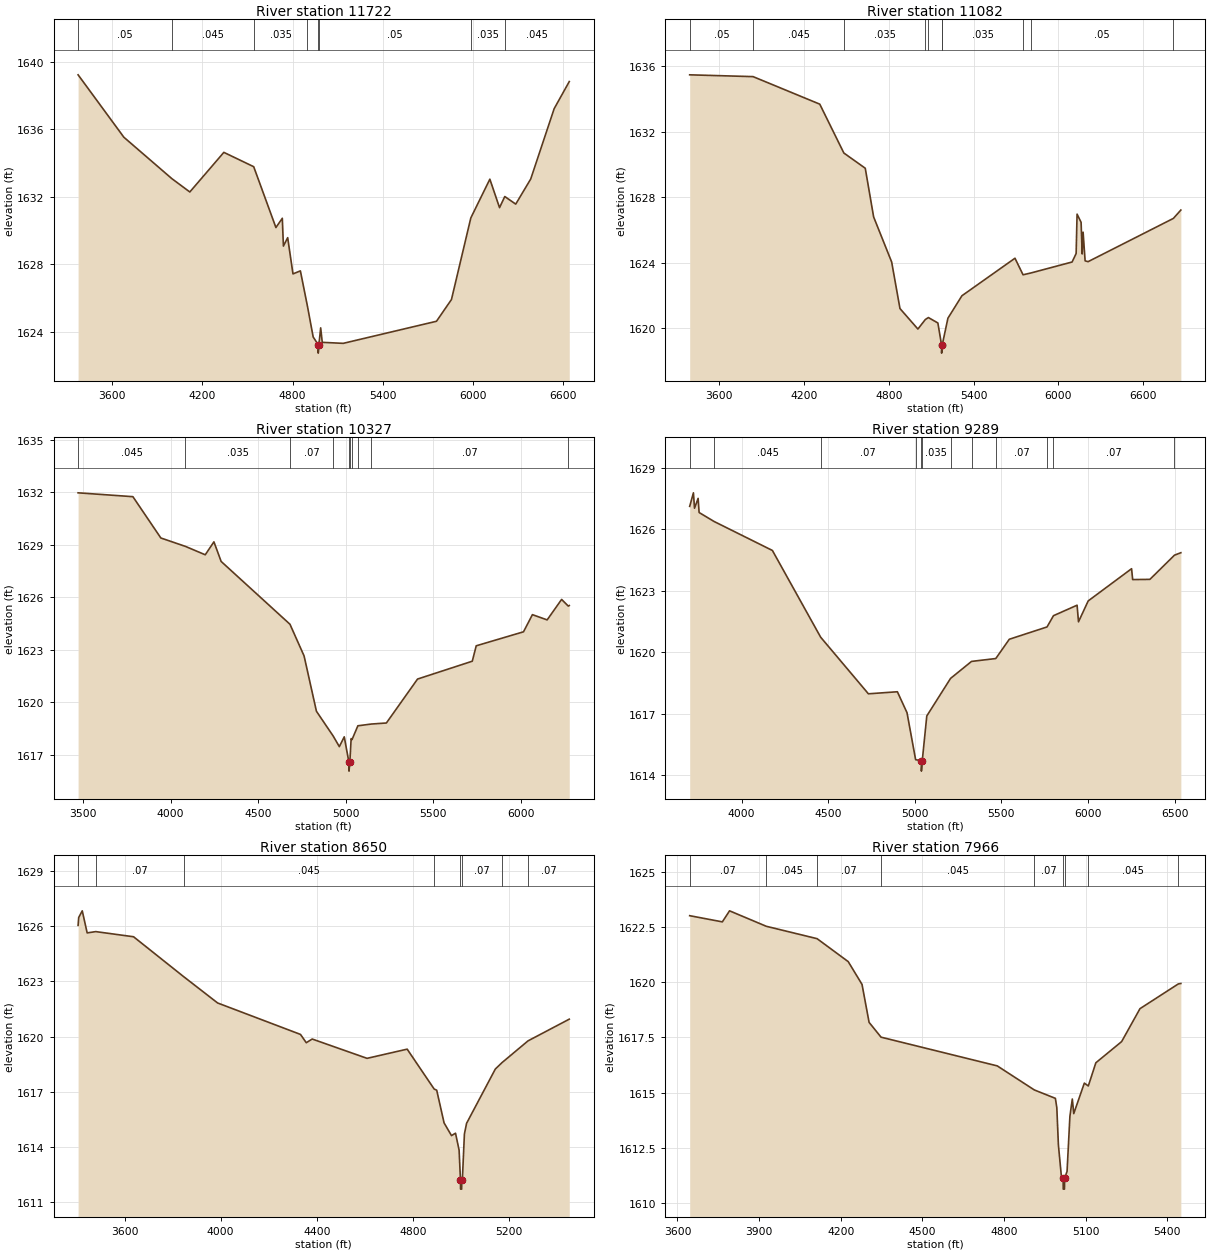
Type RM Length L Ch R = 1,11722,640,640,640
BEGIN DESCRIPTION:
MULBERRY CREEK TRIBUTARY 1_1 10.0
END DESCRIPTION:
XS GIS Cut Line= 3
      1570604.99      6896188.01      1571705.00      6894988.00
      1570705.01      6893688.02
#Sta/Elev= 30
  3372.7 1639.24  3677.0 1635.54  3996.7 1633.08  4116.1 1632.29  4342.4 1634.64
  4541.1 1633.79  4688.9 1630.18  4731.4 1630.73  4738.8 1629.08  4767.2 1629.58
  4802.4 1627.43  4851.7 1627.61  4899.0 1625.50  4936.8 1623.69  4970.2 1623.23
  4970.5 1622.73  4974.9 1623.23  4986.7 1624.23  4997.2 1623.37  5136.5 1623.31
  5757.3 1624.62  5856.9 1625.91  5985.7 1630.75  6112.4 1633.05  6176.8 1631.36
  6211.6 1632.02  6284.6 1631.57  6384.3 1633.06  6540.1 1637.23  6640.7 1638.84
#Mann=8,-1,0
  3372.7    0.05       0  3996.7   0.045       0  4541.1   0.035       0
  4899.0    0.05       0  4970.2    0.05       0  4974.9    0.05       0
  5985.7   0.035       0  6211.6   0.045       0
Bank Sta=4970.2,4974.9
Exp/Cntr=0.3,0.1

Type RM Length L Ch R = 1,11082,755,755,755
BEGIN DESCRIPTION:
Mapping XS 53435b62
END DESCRIPTION:
XS GIS Cut Line= 3
      1571919.32      6896534.56      1572349.89      6894992.87
      1571113.78      6893583.15
#Sta/Elev= 30
  3391.2 1635.47  3839.8 1635.36  4311.7 1633.68  4482.1 1630.70  4633.6 1629.77
  4692.8 1626.80  4820.4 1624.05  4879.2 1621.21  5006.0 1619.96  5058.6 1620.54
  5080.4 1620.66  5147.4 1620.33  5173.5 1618.99  5173.8 1618.49  5178.2 1618.99
  5218.5 1620.62  5317.6 1621.99  5693.0 1624.28  5750.1 1623.27  5805.6 1623.38
  6097.3 1624.05  6125.8 1624.57  6132.4 1626.97  6160.9 1626.47  6168.5 1624.54
  6175.1 1625.87  6189.3 1624.12  6210.2 1624.07  6814.0 1626.71  6866.8 1627.22
#Mann=10,-1,0
  3391.2    0.05       0  3839.8   0.045       0  4482.1   0.035       0
  5058.6    0.07       0  5080.4   0.035       0  5173.5   0.035       0
  5178.2   0.035       0  5750.1   0.045       0  5805.6    0.05       0
  6814.0   0.035       0
Bank Sta=5173.5,5178.2
Exp/Cntr=0.3,0.1

Type RM Length L Ch R = 1,10327,1038,1038,1038
BEGIN DESCRIPTION:
Mapping XS dd67365a
END DESCRIPTION:
XS GIS Cut Line= 3
      1573252.67      6896298.45      1573058.22      6894833.14
      1572474.90      6893638.73
#Sta/Elev= 30
  3471.2 1631.97  3784.4 1631.75  3944.2 1629.39  4084.6 1628.91  4198.0 1628.43
  4247.5 1629.17  4288.8 1628.05  4682.3 1624.46  4762.9 1622.65  4833.5 1619.49
  4928.9 1618.08  4964.4 1617.47  4992.5 1618.03  5019.3 1616.57  5019.7 1616.07
  5024.4 1616.57  5031.9 1617.93  5036.9 1617.87  5070.3 1618.66  5147.4 1618.76
  5233.3 1618.82  5411.4 1621.33  5724.3 1622.35  5746.8 1623.23  6017.1 1624.03
  6068.0 1625.01  6152.2 1624.71  6234.9 1625.88  6272.9 1625.50  6278.6 1625.53
#Mann=10,-1,0
  3471.2   0.045       0  4084.6   0.035       0  4682.3    0.07       0
  4928.9   0.035       0  5019.3   0.035       0  5024.4   0.035       0
  5036.9    0.07       0  5070.3   0.035       0  5147.4    0.07       0
  6272.9   0.045       0
Bank Sta=5019.3,5024.4
Exp/Cntr=0.3,0.1

Type RM Length L Ch R = 1,9289,639,639,639
BEGIN DESCRIPTION:
Mapping XS 2211531a
END DESCRIPTION:
XS GIS Cut Line= 3
      1574336.01      6895784.57      1573954.06      6894534.53
      1572752.64      6893590.07
#Sta/Elev= 30
  3700.7 1627.12  3722.3 1627.78  3728.5 1627.03  3749.4 1627.51  3755.1 1626.82
  3842.2 1626.38  4178.1 1624.97  4456.8 1620.74  4732.3 1617.98  4899.6 1618.08
  4955.2 1617.06  5004.9 1614.77  5037.9 1614.71  5038.3 1614.21  5043.1 1614.71
  5069.4 1616.90  5206.5 1618.73  5327.7 1619.56  5467.7 1619.70  5545.7 1620.64
  5763.5 1621.24  5800.8 1621.79  5937.0 1622.30  5945.1 1621.49  6001.2 1622.51
  6251.5 1624.08  6257.8 1623.55  6357.3 1623.56  6499.2 1624.74  6536.0 1624.86
#Mann=12,-1,0
  3700.7   0.035       0  3842.2   0.045       0  4456.8    0.07       0
  5004.9   0.035       0  5037.9    0.07       0  5043.1   0.035       0
  5206.5    0.07       0  5327.7   0.035       0  5467.7    0.07       0
  5763.5   0.035       0  5800.8    0.07       0  6499.2   0.045       0
Bank Sta=5037.9,5043.1
Exp/Cntr=0.3,0.1

Type RM Length L Ch R = 1,8650,684,684,684
BEGIN DESCRIPTION:
Mapping XS 1f68ca5d
END DESCRIPTION:
XS GIS Cut Line= 3
      1574870.73      6895874.85      1574530.44      6894340.09
      1574330.01      6893913.02
#Sta/Elev= 30
  3406.8 1626.05  3409.4 1626.48  3424.1 1626.84  3444.5 1625.64  3480.3 1625.71
  3637.6 1625.43  3846.2 1623.26  3987.4 1621.83  4332.3 1620.12  4356.2 1619.67
  4381.0 1619.87  4609.2 1618.82  4776.1 1619.32  4888.5 1617.15  4899.0 1617.09
  4929.7 1615.31  4960.5 1614.62  4977.3 1614.75  4992.2 1613.83  4997.9 1612.21
  4998.3 1611.71  5002.8 1611.71  5003.2 1612.21  5006.1 1612.31  5014.3 1614.71
  5023.4 1615.29  5143.0 1618.24  5171.0 1618.59  5279.0 1619.77  5450.6 1620.95
#Mann=8,-1,0
  3406.8   0.035       0  3480.3    0.07       0  3846.2   0.045       0
  4888.5    0.07       0  4997.9    0.07       0  5003.2    0.07       0
  5171.0   0.045       0  5279.0    0.07       0
Bank Sta=4997.9,5003.2
Exp/Cntr=0.3,0.1

Type RM Length L Ch R = 1,7966,697,697,697
BEGIN DESCRIPTION:
Mapping XS 00db0b7f
END DESCRIPTION:
XS GIS Cut Line= 3
      1575409.78      6895572.45      1575191.03      6894275.59
      1575030.00      6893813.00
#Sta/Elev= 30
  3645.0 1623.01  3765.0 1622.73  3791.5 1623.23  3926.5 1622.53  4113.1 1621.97
  4227.6 1620.93  4278.3 1619.90  4304.3 1618.18  4348.2 1617.51  4775.2 1616.21
  4911.6 1615.12  4988.9 1614.74  4994.2 1614.31  5000.0 1612.63  5010.6 1611.25
  5017.4 1611.13  5017.8 1610.63  5022.3 1610.63  5022.7 1611.13  5031.8 1611.43
  5042.3 1613.93  5051.1 1614.71  5056.4 1614.05  5095.3 1615.43  5109.9 1615.30
  5137.6 1616.35  5232.4 1617.31  5299.8 1618.80  5440.6 1619.92  5450.0 1619.94
#Mann=9,-1,0
  3645.0    0.07       0  3926.5   0.045       0  4113.1    0.07       0
  4348.2   0.045       0  4911.6    0.07       0  5017.4    0.07       0
  5022.7    0.07       0  5109.9   0.045       0  5440.6    0.07       0
Bank Sta=5017.4,5022.7
Exp/Cntr=0.3,0.1

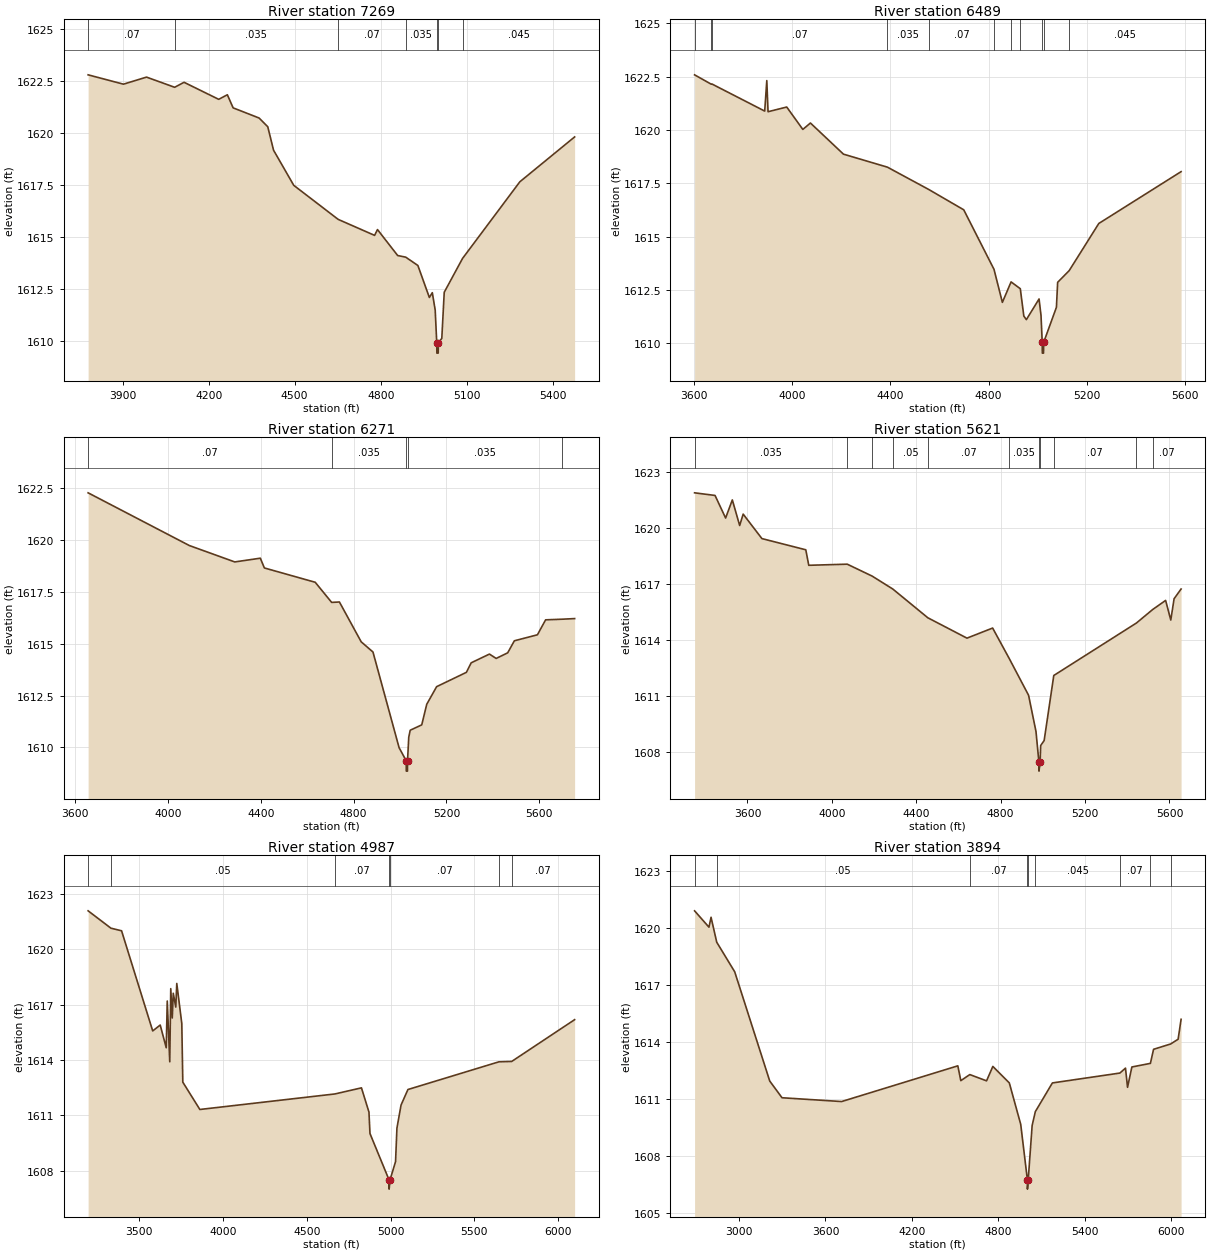
Type RM Length L Ch R = 1,7269,780,780,780
BEGIN DESCRIPTION:
Mapping XS 8cb3755c
END DESCRIPTION:
XS GIS Cut Line= 3
      1575702.47      6895550.37      1575843.10      6894336.79
      1575671.22      6893894.08
#Sta/Elev= 30
  3779.7 1622.81  3902.9 1622.36  3983.4 1622.70  4081.5 1622.21  4114.3 1622.45
  4235.1 1621.63  4265.3 1621.85  4285.4 1621.22  4376.0 1620.73  4406.2 1620.31
  4426.4 1619.18  4496.8 1617.49  4651.7 1615.85  4778.7 1615.08  4788.8 1615.36
  4859.2 1614.11  4887.4 1614.03  4929.7 1613.63  4969.7 1612.09  4980.0 1612.32
  4990.1 1611.48  4995.5 1609.91  4996.0 1609.41  5000.6 1609.41  5001.0 1609.91
  5013.1 1610.12  5021.6 1612.34  5085.5 1613.97  5285.3 1617.66  5476.3 1619.82
#Mann=7,-1,0
  3779.7    0.07       0  4081.5   0.035       0  4651.7    0.07       0
  4887.4   0.035       0  4995.5   0.035       0  5001.0   0.035       0
  5085.5   0.045       0
Bank Sta=4995.5,5001
Exp/Cntr=0.3,0.1

Type RM Length L Ch R = 1,6489,218,218,218
BEGIN DESCRIPTION:
Mapping XS b7c8a629
END DESCRIPTION:
XS GIS Cut Line= 3
      1576255.42      6895644.09      1576611.33      6894272.55
      1576693.79      6893717.00
#Sta/Elev= 30
  3604.2 1622.59  3672.0 1622.15  3674.8 1622.16  3889.4 1620.89  3897.9 1622.32
  3903.0 1620.86  3979.0 1621.08  4044.4 1620.03  4075.4 1620.33  4209.7 1618.87
  4388.6 1618.26  4557.1 1617.21  4698.9 1616.26  4821.9 1613.47  4856.0 1611.92
  4891.4 1612.88  4928.9 1612.56  4943.2 1611.28  4953.5 1611.11  5005.2 1612.08
  5013.1 1611.31  5018.1 1610.04  5018.5 1609.54  5023.3 1609.54  5023.8 1610.04
  5075.8 1611.69  5080.8 1612.86  5127.8 1613.41  5248.2 1615.62  5582.8 1618.05
#Mann=11,-1,0
  3604.2    0.07       0  3672.0   0.035       0  3674.8    0.07       0
  4388.6   0.035       0  4557.1    0.07       0  4821.9   0.035       0
  4891.4    0.07       0  4928.9   0.035       0  5018.1   0.035       0
  5023.8   0.035       0  5127.8   0.045       0
Bank Sta=5018.1,5023.8
Exp/Cntr=0.3,0.1

Type RM Length L Ch R = 1,6271,650,650,650
BEGIN DESCRIPTION:
Mapping XS 27ea778d
END DESCRIPTION:
XS GIS Cut Line= 3
      1576409.06      6895676.24      1576791.01      6894391.48
      1577259.75      6893797.74
#Sta/Elev= 30
  3655.8 1622.27  4092.1 1619.73  4287.9 1618.94  4398.0 1619.12  4415.5 1618.65
  4634.6 1617.96  4705.4 1616.99  4738.9 1617.01  4832.8 1615.09  4883.5 1614.60
  4996.1 1609.99  5026.7 1609.36  5027.2 1608.86  5032.0 1608.86  5032.5 1609.36
  5037.7 1610.49  5044.0 1610.83  5093.7 1611.09  5115.2 1612.08  5157.9 1612.93
  5286.1 1613.62  5306.9 1614.08  5385.5 1614.50  5414.4 1614.29  5464.1 1614.56
  5492.9 1615.14  5592.3 1615.43  5627.6 1616.15  5698.4 1616.18  5752.6 1616.21
#Mann=5,-1,0
  3655.8    0.07       0  4705.4   0.035       0  5026.7   0.035       0
  5032.5   0.035       0  5698.4    0.07       0
Bank Sta=5026.7,5032.5
Exp/Cntr=0.3,0.1

Type RM Length L Ch R = 1,5621,634,634,634
BEGIN DESCRIPTION:
Mapping XS 554fade8
END DESCRIPTION:
XS GIS Cut Line= 3
      1576674.70      6895807.26      1577429.90      6894331.58
      1577473.31      6893684.83
#Sta/Elev= 30
  3349.2 1621.88  3446.2 1621.74  3496.3 1620.53  3528.1 1621.50  3562.9 1620.13
  3579.5 1620.74  3668.3 1619.43  3876.3 1618.83  3890.4 1618.00  4072.8 1618.06
  4191.0 1617.42  4288.6 1616.73  4454.8 1615.19  4640.2 1614.10  4761.9 1614.64
  4839.6 1613.03  4932.3 1611.04  4967.4 1609.10  4981.1 1607.48  4981.6 1606.98
  4986.9 1607.48  4989.6 1608.35  5006.1 1608.62  5051.7 1612.10  5443.5 1614.91
  5520.2 1615.63  5581.8 1616.12  5606.3 1615.07  5621.9 1616.21  5655.1 1616.73
#Mann=11,-1,0
  3349.2   0.035       0  4072.8    0.05       0  4191.0   0.035       0
  4288.6    0.05       0  4454.8    0.07       0  4839.6   0.035       0
  4981.1   0.035       0  4986.9   0.035       0  5051.7    0.07       0
  5443.5   0.035       0  5520.2    0.07       0
Bank Sta=4981.1,4986.9
Exp/Cntr=0.3,0.1

Type RM Length L Ch R = 1,4987,1093,1093,1093
BEGIN DESCRIPTION:
Mapping XS 29505ed7
END DESCRIPTION:
XS GIS Cut Line= 3
      1576935.10      6896124.14      1577972.44      6894600.68
      1578202.47      6893567.68
#Sta/Elev= 30
  3196.3 1622.07  3332.4 1621.13  3395.8 1620.99  3581.5 1615.57  3626.3 1615.89
  3662.2 1614.66  3668.2 1617.19  3683.2 1613.90  3689.2 1617.86  3698.1 1616.27
  3704.1 1617.61  3719.1 1616.86  3725.1 1618.14  3755.0 1615.97  3761.0 1612.80
  3862.7 1611.32  4667.8 1612.16  4826.4 1612.49  4871.2 1611.18  4877.2 1610.02
  4991.0 1607.51  4991.4 1607.01  4996.8 1607.51  5029.8 1608.50  5038.0 1610.31
  5062.6 1611.56  5103.6 1612.40  5646.5 1613.90  5722.6 1613.92  6097.7 1616.18
#Mann=7,-1,0
  3196.3    0.07       0  3332.4    0.05       0  4667.8    0.07       0
  4991.0    0.07       0  4996.8    0.07       0  5646.5   0.035       0
  5722.6    0.07       0
Bank Sta=4991,4996.8
Exp/Cntr=0.3,0.1

Type RM Length L Ch R = 1,3894,1184,1184,1184
BEGIN DESCRIPTION:
Mapping XS 35f235a2
END DESCRIPTION:
XS GIS Cut Line= 3
      1577078.61      6896381.94      1578875.50      6895006.93
      1578958.83      6893897.58
#Sta/Elev= 30
  2692.1 1620.91  2791.8 1620.05  2806.4 1620.57  2845.7 1619.26  2970.5 1617.70
  3213.5 1611.95  3298.7 1611.07  3712.2 1610.87  4518.3 1612.75  4539.1 1611.97
  4601.4 1612.29  4717.7 1611.96  4761.3 1612.72  4875.6 1611.85  4954.7 1609.67
  5000.8 1606.76  5001.3 1606.26  5006.8 1606.76  5033.9 1609.61  5056.1 1610.34
  5174.3 1611.85  5642.7 1612.37  5681.5 1612.63  5695.7 1611.62  5725.8 1612.69
  5854.4 1612.88  5876.2 1613.62  5994.5 1613.90  6046.7 1614.15  6067.2 1615.20
#Mann=9,-1,0
  2692.1   0.035       0  2845.7    0.05       0  4601.4    0.07       0
  5000.8    0.07       0  5006.8    0.07       0  5056.1   0.045       0
  5642.7    0.07       0  5854.4   0.035       0  5994.5    0.07       0
Bank Sta=5000.8,5006.8
Exp/Cntr=0.3,0.1

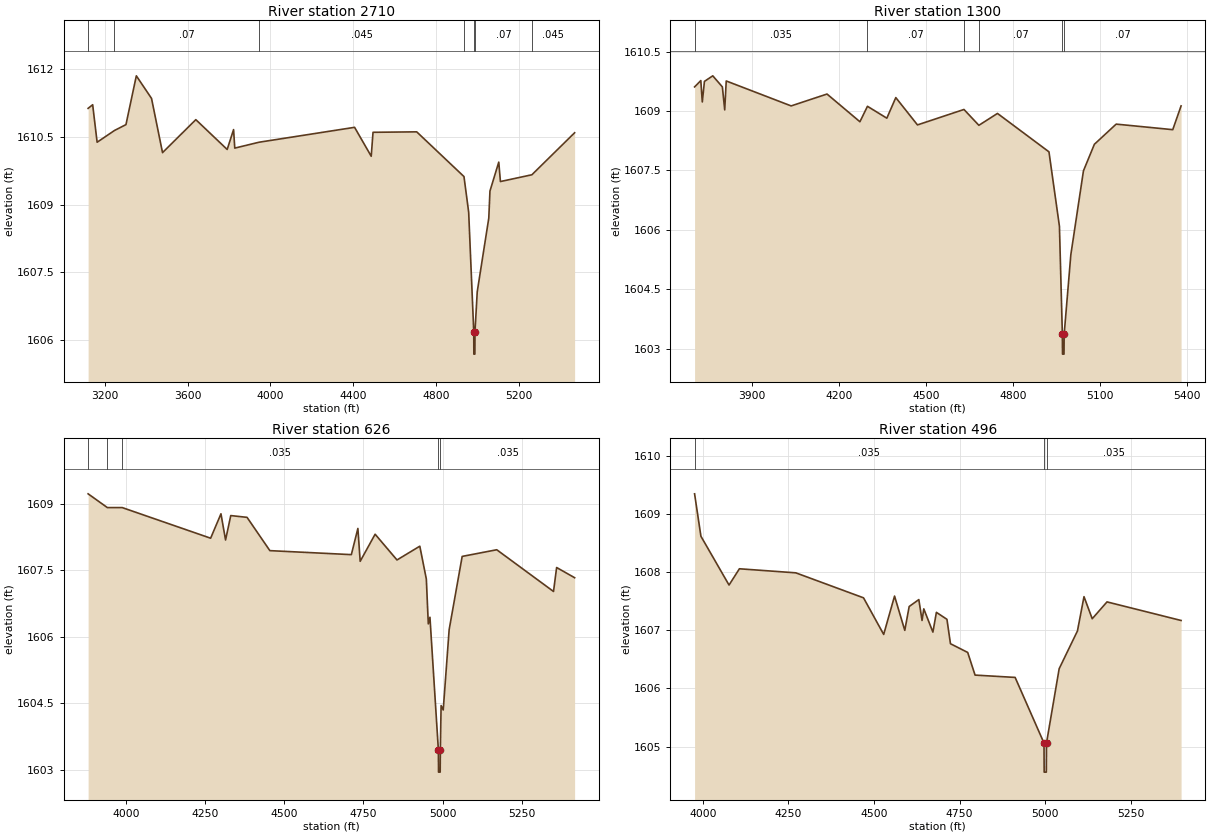
Type RM Length L Ch R = 1,2710,1410,1410,1410
BEGIN DESCRIPTION:
Mapping XS 5e8c04ea
END DESCRIPTION:
XS GIS Cut Line= 3
      1578093.31      6896545.35      1579721.59      6895605.01
      1579879.99      6895163.04
#Sta/Elev= 30
  3119.7 1611.13  3141.7 1611.21  3163.2 1610.38  3247.0 1610.64  3302.5 1610.77
  3352.6 1611.85  3426.0 1611.35  3479.1 1610.15  3639.9 1610.88  3791.4 1610.22
  3822.3 1610.66  3828.0 1610.25  3945.0 1610.38  4406.7 1610.71  4487.1 1610.07
  4495.8 1610.60  4706.8 1610.61  4935.1 1609.62  4957.8 1608.83  4982.3 1606.19
  4982.8 1605.69  4987.8 1605.69  4988.3 1606.19  4999.1 1607.07  5054.9 1608.70
  5060.6 1609.30  5103.1 1609.94  5111.1 1609.51  5263.1 1609.66  5469.5 1610.59
#Mann=7,-1,0
  3119.7   0.035       0  3247.0    0.07       0  3945.0   0.045       0
  4935.1    0.07       0  4982.3    0.07       0  4988.3    0.07       0
  5263.1   0.045       0
Bank Sta=4982.3,4988.3
Exp/Cntr=0.3,0.1

Type RM Length L Ch R = 1,1300,674,674,674
BEGIN DESCRIPTION:
Mapping XS ef3f8a3f
END DESCRIPTION:
XS GIS Cut Line= 3
      1579302.05      6896858.94      1580560.63      6896543.92
      1580747.07      6896213.03
#Sta/Elev= 30
  3702.6 1609.61  3724.1 1609.77  3729.2 1609.23  3736.6 1609.75  3765.3 1609.89
  3798.4 1609.61  3806.5 1609.03  3811.7 1609.76  4035.5 1609.13  4159.2 1609.43
  4272.6 1608.73  4298.6 1609.12  4365.4 1608.82  4396.3 1609.34  4471.0 1608.65
  4631.3 1609.04  4682.7 1608.64  4746.8 1608.94  4924.3 1607.97  4960.4 1606.09
  4970.5 1603.36  4971.0 1602.86  4976.2 1602.86  4976.7 1603.36  4999.7 1605.37
  5043.2 1607.49  5080.8 1608.16  5156.0 1608.67  5351.1 1608.53  5379.8 1609.13
#Mann=6,-1,0
  3702.6   0.035       0  4298.6    0.07       0  4631.3    0.16       0
  4682.7    0.07       0  4970.5    0.07       0  4976.7    0.07       0
Bank Sta=4970.5,4976.7
Exp/Cntr=0.3,0.1

Type RM Length L Ch R = 1,626,130,130,130
BEGIN DESCRIPTION:
Mapping XS b01003e2
END DESCRIPTION:
XS GIS Cut Line= 3
      1579717.37      6896871.86      1580800.70      6897132.28
      1581210.24      6897229.46
#Sta/Elev= 30
  3881.3 1609.22  3942.0 1608.91  3988.9 1608.91  4267.9 1608.22  4300.5 1608.77
  4315.0 1608.18  4331.4 1608.73  4382.8 1608.69  4454.8 1607.94  4711.9 1607.85
  4732.5 1608.44  4739.8 1607.70  4786.9 1608.31  4855.9 1607.73  4927.9 1608.04
  4948.5 1607.30  4954.7 1606.29  4959.9 1606.44  4986.5 1603.45  4987.0 1602.95
  4992.2 1602.95  4992.7 1603.45  4995.1 1604.45  5001.8 1604.35  5020.5 1606.16
  5061.6 1607.81  5170.7 1607.96  5349.8 1607.02  5359.6 1607.56  5416.4 1607.33
#Mann=5,-1,0
  3881.3   0.035       0  3942.0    0.07       0  3988.9   0.035       0
  4986.5   0.035       0  4992.7   0.035       0
Bank Sta=4986.5,4992.7
Exp/Cntr=0.3,0.1

Type RM Length L Ch R = 1,496,0,0,0
BEGIN DESCRIPTION:
MULBERRY CREEK TRIBUTARY 1_1 1.0
END DESCRIPTION:
XS GIS Cut Line= 3
      1579807.00      6897032.48      1580804.80      6897263.08
      1581191.50      6897350.67
#Sta/Elev= 30
  3975.9 1609.35  3994.4 1608.62  4076.5 1607.78  4106.8 1608.06  4271.5 1607.99
  4469.2 1607.56  4528.1 1606.93  4559.8 1607.59  4589.7 1607.00  4602.5 1607.41
  4630.7 1607.53  4640.1 1607.17  4645.2 1607.37  4671.8 1606.97  4682.0 1607.31
  4712.8 1607.19  4723.1 1606.77  4773.4 1606.62  4794.9 1606.23  4911.9 1606.19
  4996.2 1605.06  4996.7 1604.56  5003.0 1604.56  5003.5 1605.06  5040.5 1606.34
  5093.9 1606.99  5113.0 1607.58  5137.0 1607.20  5180.2 1607.49  5396.5 1607.17
#Mann=3,-1,0
  3975.9   0.035       0  4996.2   0.035       0  5003.5   0.035       0
Bank Sta=4996.2,5003.5
Exp/Cntr=0.3,0.1

Chan Stop Cuts=-1