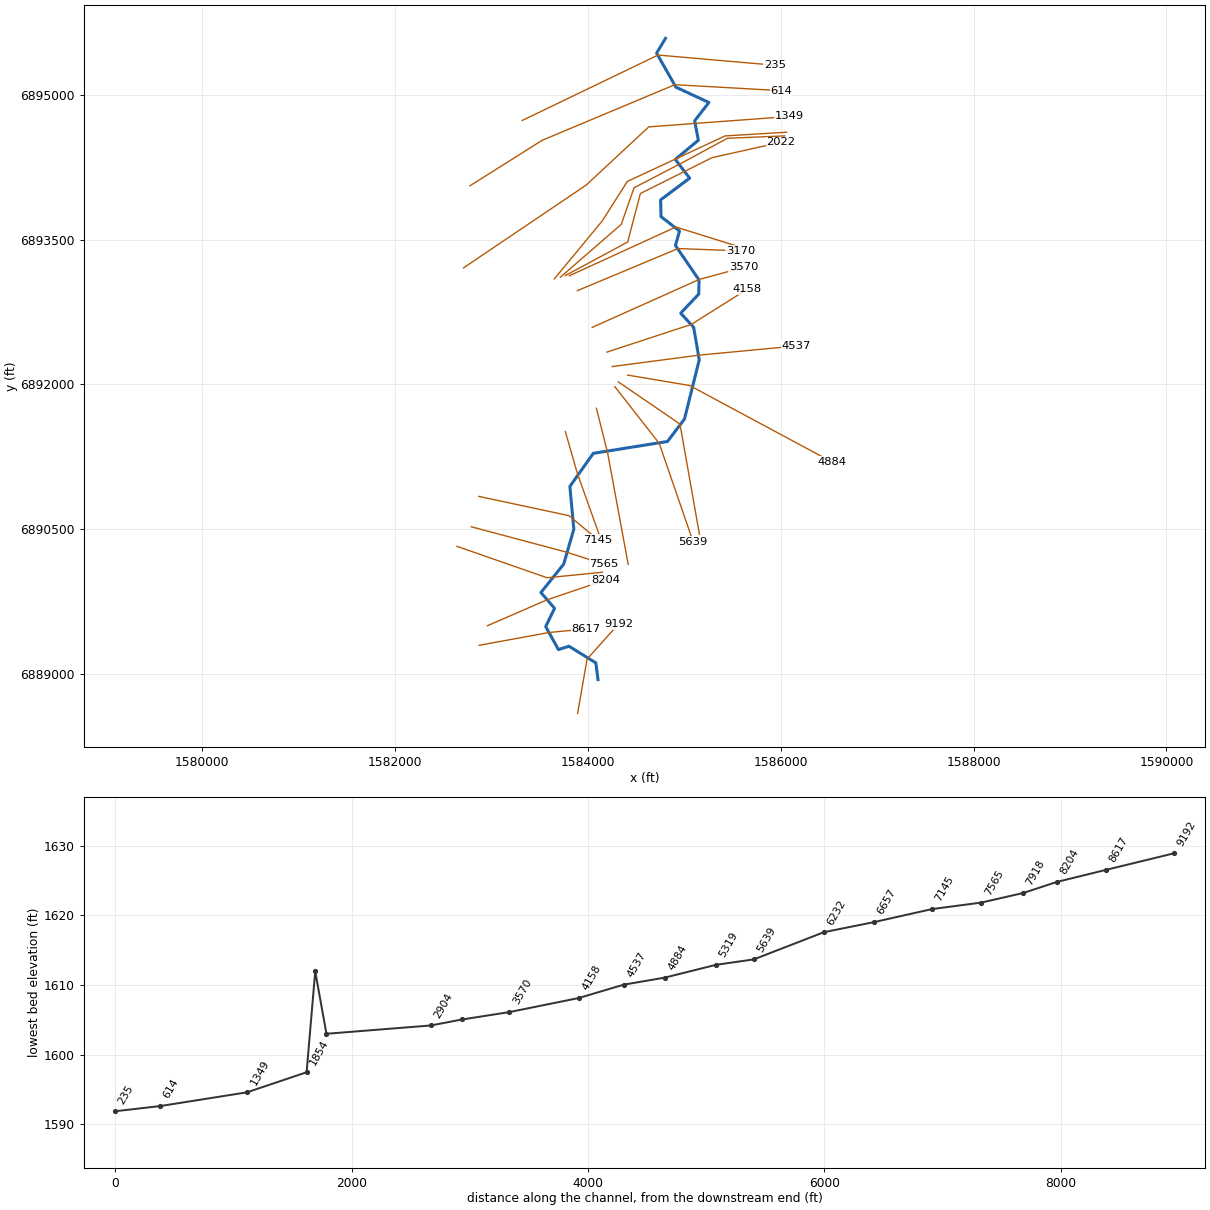
--- MULBERRY CREEK TRIBUTARY 2.prj (project) ---

Proj Title=MULBERRY CREEK TRIBUTARY 2 Base Level Engineering
Current Plan=p01
Default Exp/Contr=0.3,0.1
English Units
Geom File=g01
Flow File=f01
Plan File=p01
Y Axis Title=Elevation
X Axis Title(PF)=Main Channel Distance
X Axis Title(XS)=Station
BEGIN DESCRIPTION:
MULBERRY CREEK TRIBUTARY 2
END DESCRIPTION:
DSS Export Rating Curves= 0
DSS Export Rating Curve Sorted= 0
DSS Export Volume Flow Curves= 0
DXF OffsetX= 0
DXF OffsetY= 0
DXF ScaleX= 1
DXF ScaleY= 10

--- MULBERRY CREEK TRIBUTARY 2.p01 (plan) ---

Plan Title=Multiple Run
Short Identifier=Multiple
Geom File=g01
Flow File=f01
Subcritical Flow
K Sum by GR= 0
Std Step Tol= 0.01
Critical Tol= 0.01
Num of Std Step Trials= 20
Max Error Tol= 0.3
Flow Tol Ratio= 0.001
Split Flow NTrial= 30
Split Flow Tol= 0.02
Split Flow Ratio= 0.02
Log Output Level= 0
Friction Slope Method= 1
Unsteady Friction Slope Method= 2
Unsteady Bridges Friction Slope Method= 1
Parabolic Critical Depth
Global Vel Dist=  1 , 1 , 1
Global Log Level= 0
CheckData=True
Encroach Param= -1, 0, 0, 0
BEGIN DESCRIPTION:
Multiple Run
END DESCRIPTION:

--- MULBERRY CREEK TRIBUTARY 2.f01 (steady flow) ---

Flow Title=Multiple
Number of Profiles=7
Profile Names=10-year,25-year,50-year,1pct_min,100-year,1pct_plu,500-year
River Rch & RM= MULBERRY CREEK T,Reach-1,9192
     205     281     344     210     419     836     629
River Rch & RM= MULBERRY CREEK T,Reach-1,8617
     348     492     613     380     757    1511    1173
River Rch & RM= MULBERRY CREEK T,Reach-1,2022
     455     652     820     512    1022    2040    1613
River Rch & RM= MULBERRY CREEK T,Reach-1,1927
     493     709     895     561    1120    2235    1778
Boundary for River Rch & Prof#=MULBERRY CREEK T,Reach-1,1
Up Type=0
Dn Type=3
Dn Slope=0.005
Boundary for River Rch & Prof#=MULBERRY CREEK T,Reach-1,2
Up Type=0
Dn Type=3
Dn Slope=0.005
Boundary for River Rch & Prof#=MULBERRY CREEK T,Reach-1,3
Up Type=0
Dn Type=3
Dn Slope=0.005
Boundary for River Rch & Prof#=MULBERRY CREEK T,Reach-1,4
Up Type=0
Dn Type=3
Dn Slope=0.005
Boundary for River Rch & Prof#=MULBERRY CREEK T,Reach-1,5
Up Type=0
Dn Type=3
Dn Slope=0.005
Boundary for River Rch & Prof#=MULBERRY CREEK T,Reach-1,6
Up Type=0
Dn Type=3
Dn Slope=0.005
Boundary for River Rch & Prof#=MULBERRY CREEK T,Reach-1,7
Up Type=0
Dn Type=3
Dn Slope=0.005

--- MULBERRY CREEK TRIBUTARY 2.g01 (geometry) ---

Geom Title=Existing Conditions
Program Version=4.10

River Reach=MULBERRY CREEK T,Reach-1
Reach XY= 30
        1584105.        6888938.      1584082.64      6889111.71
      1583803.26      6889284.63      1583694.92       6889249.1
      1583562.53      6889488.01      1583654.41      6889677.38
      1583512.84      6889841.23      1583749.27      6890135.45
      1583854.23      6890498.69      1583813.24      6890941.23
      1584056.25      6891284.55      1584825.55      6891407.44
      1585001.39       6891639.5      1585154.62      6892253.28
       1585097.2      6892591.42      1584962.07        6892738.
      1585149.55      6892935.55      1585152.95      6893082.14
      1584908.14      6893439.64      1584949.91      6893590.31
      1584758.07      6893739.43      1584754.56      6893913.09
        1585055.        6894138.       1584906.5      6894332.13
      1585145.87      6894531.26      1585106.97      6894732.32
      1585254.82      6894922.92      1584912.68      6895081.48
      1584712.79      6895434.58        1584805.        6895588.

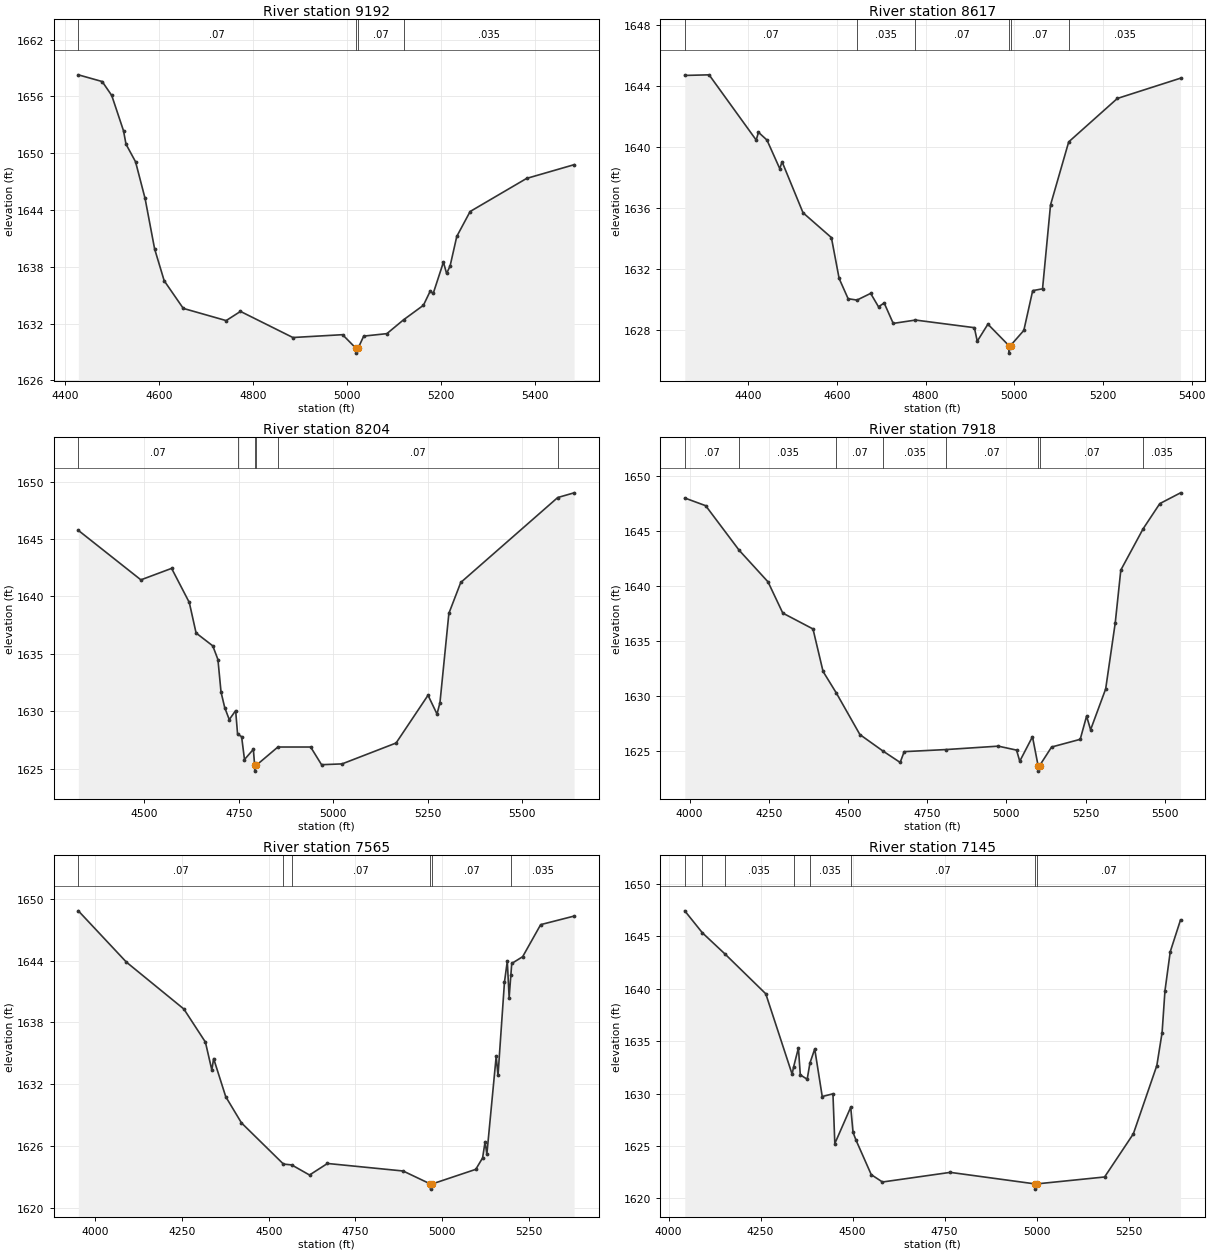
Type RM Length L Ch R = 1 ,9192    ,575,575,575
BEGIN DESCRIPTION:
MULBERRY CREEK TRIBUTARY 2 17.0
END DESCRIPTION:
XS GIS Cut Line= 3
      1583893.52      6888587.97      1583991.83      6889151.66
      1584314.98      6889511.04
#Sta/Elev= 30
  4427.8 1658.29  4478.6 1657.58  4498.9 1656.11    4524 1652.37  4529.3 1650.96
  4549.6  1649.1  4569.9 1645.22  4590.2 1639.89  4610.6 1636.52  4651.2  1633.6
  4742.5 1632.31    4773 1633.28  4884.6 1630.52  4990.3 1630.82  5019.2 1629.37
  5019.5 1628.87  5023.2 1629.37  5035.4 1630.67  5084.7 1630.93  5120.1 1632.39
  5162.5 1633.93  5176.7  1635.4  5183.4 1635.19  5205.1 1638.49  5211.8 1637.29
  5219.3 1638.09  5233.5 1641.21  5261.9 1643.84  5382.2 1647.34  5483.3 1648.79
#Mann= 4 ,-1 , 0
  4427.8     .07       0  5019.2     .07       0  5023.2     .07       0
  5120.1    .035       0
Bank Sta=5019.2,5023.2
XS Rating Curve= 0 ,0
Exp/Cntr=0.3,0.1

Type RM Length L Ch R = 1 ,8617    ,413,413,413
BEGIN DESCRIPTION:
Mapping XS 9fe1390c
END DESCRIPTION:
XS GIS Cut Line= 3
      1582872.66      6889293.71      1583596.65      6889426.53
      1583976.83      6889462.99
#Sta/Elev= 30
    4257 1644.72  4311.9 1644.76  4418.1 1640.48  4423.2 1640.99  4442.4 1640.48
  4471.3  1638.6  4476.4 1639.06  4523.7 1635.71  4587.7 1634.08  4605.1  1631.4
  4625.4 1630.07  4645.3 1629.98  4676.2 1630.42  4693.9 1629.54  4706.7 1629.79
  4727.1 1628.45  4777.3 1628.67  4910.1 1628.17  4916.6 1627.28  4940.6  1628.4
  4987.7    1627  4987.9  1626.5  4991.7    1627  5021.6 1627.99  5041.6  1630.6
  5063.8 1630.72  5081.8 1636.22  5122.8 1640.36  5232.5 1643.21    5375 1644.54
#Mann= 6 ,-1 , 0
    4257     .07       0  4645.3    .035       0  4777.3     .07       0
  4987.7     .07       0  4991.7     .07       0  5122.8    .035       0
Bank Sta=4987.7,4991.7
XS Rating Curve= 0 ,0
Exp/Cntr=0.3,0.1

Type RM Length L Ch R = 1 ,8204    ,286,286,286
BEGIN DESCRIPTION:
Mapping XS 2da967ad
END DESCRIPTION:
XS GIS Cut Line= 3
      1582958.59      6889496.83      1583575.81      6889765.07
      1584181.27      6889970.35
#Sta/Elev= 30
  4325.4 1645.75    4491 1641.44  4572.3 1642.44  4619.1 1639.47  4637.1 1636.81
  4681.3 1635.69  4694.9  1634.5  4703.1 1631.67  4712.9 1630.31  4724.9 1629.27
  4741.8 1630.05  4746.9 1628.01  4757.6 1627.78  4765.2 1625.79  4788.7 1626.68
  4792.1 1625.28  4792.4 1624.78  4796.1 1625.28  4853.6 1626.88  4940.3 1626.88
  4969.2 1625.34  5023.5 1625.41  5166.5 1627.23    5251 1631.39  5274.8 1629.75
  5282.6 1630.74  5306.2 1638.52  5337.6 1641.21  5594.3 1648.61  5637.7 1649.02
#Mann= 6 ,-1 , 0
  4325.4     .07       0  4746.9    .035       0  4792.1     .07       0
  4796.1    .035       0  4853.6     .07       0  5594.3    .035       0
Bank Sta=4792.1,4796.1
XS Rating Curve= 0 ,0
Exp/Cntr=0.3,0.1

Type RM Length L Ch R = 1 ,7918    ,353,353,353
BEGIN DESCRIPTION:
Mapping XS af90691e
END DESCRIPTION:
XS GIS Cut Line= 3
      1582642.62      6890319.77      1583577.55      6889994.24
      1584150.21       6890051.5
#Sta/Elev= 30
  3984.6 1648.01  4050.7 1647.31  4156.4 1643.26  4247.5 1640.39  4294.2 1637.55
  4389.5 1636.11  4421.3 1632.25  4463.6 1630.27  4537.7 1626.51  4610.3 1625.02
  4664.8 1623.98  4677.5 1624.96  4809.6 1625.15  4974.6 1625.46  5032.3  1625.1
  5042.4 1624.09  5082.6 1626.32  5100.3 1623.69  5100.6 1623.19  5105.1 1623.69
  5142.9 1625.38  5233.3 1626.08  5253.4 1628.19  5266.1 1626.95  5313.7 1630.66
  5343.9 1636.66  5361.5 1641.46  5432.1 1645.22  5484.6  1647.5  5550.1 1648.48
#Mann= 8 ,-1 , 0
  3984.6     .07       0  4156.4    .035       0  4463.6     .07       0
  4610.3    .035       0  4809.6     .07       0  5100.3     .07       0
  5105.1     .07       0  5432.1    .035       0
Bank Sta=5100.3,5105.1
XS Rating Curve= 0 ,0
Exp/Cntr=0.3,0.1

Type RM Length L Ch R = 1 ,7565    ,420,420,420
BEGIN DESCRIPTION:
Mapping XS e08ab971
END DESCRIPTION:
XS GIS Cut Line= 3
       1582791.1      6890522.88      1583778.07      6890259.86
      1584166.12      6890134.85
#Sta/Elev= 30
  3951.1 1648.83  4089.7 1643.85  4255.3  1639.3  4317.4 1636.09  4335.9 1633.38
  4341.1 1634.49    4376 1630.79  4421.3 1628.25  4542.4 1624.25  4566.2 1624.17
  4617.5 1623.19  4669.2 1624.31  4887.2 1623.58  4965.9 1622.32  4966.3 1621.82
  4970.7 1622.32  5096.7 1623.74  5116.4 1624.85  5123.5  1626.4  5128.7 1625.22
  5155.6 1634.72  5160.8 1632.85  5179.4  1641.9  5187.6 1643.95  5192.9 1640.41
  5197.8 1642.57  5200.4 1643.72  5231.9 1644.38  5283.8 1647.49  5380.2 1648.32
#Mann= 6 ,-1 , 0
  3951.1     .07       0  4542.4    .035       0  4566.2     .07       0
  4965.9     .07       0  4970.7     .07       0  5197.8    .035       0
Bank Sta=4965.9,4970.7
XS Rating Curve= 0 ,0
Exp/Cntr=0.3,0.1

Type RM Length L Ch R = 1 ,7145    ,488,488,488
BEGIN DESCRIPTION:
MULBERRY CREEK TRIBUTARY 2 13.0
END DESCRIPTION:
XS GIS Cut Line= 3
      1582869.71      6890837.89        1583805.        6890638.
      1584104.98      6890388.01
#Sta/Elev= 30
    4044 1647.45  4091.9 1645.35  4153.3 1643.33  4264.1 1639.53  4335.7 1631.85
  4339.6 1632.53  4352.8 1634.36  4357.9 1631.79  4376.6 1631.37  4384.1 1632.92
  4397.1 1634.26  4417.5 1629.72  4446.6 1629.98  4451.7 1625.23  4494.9  1628.7
  4501.2 1626.29  4509.6 1625.53  4550.7 1622.26  4581.1 1621.56  4765.2 1622.48
  4995.4 1621.38  4995.8 1620.88  5000.3 1621.38  5184.6 1622.04  5262.7 1626.16
  5326.5 1632.68  5340.8 1635.83  5348.6 1639.82  5362.9 1643.54  5390.9 1646.59
#Mann= 8 ,-1 , 0
    4044    .035       0  4091.9     .07       0  4153.3    .035       0
  4339.6     .07       0  4384.1    .035       0  4494.9     .07       0
  4995.4     .07       0  5000.3     .07       0
Bank Sta=4995.4,5000.3
XS Rating Curve= 0 ,0
Exp/Cntr=0.3,0.1

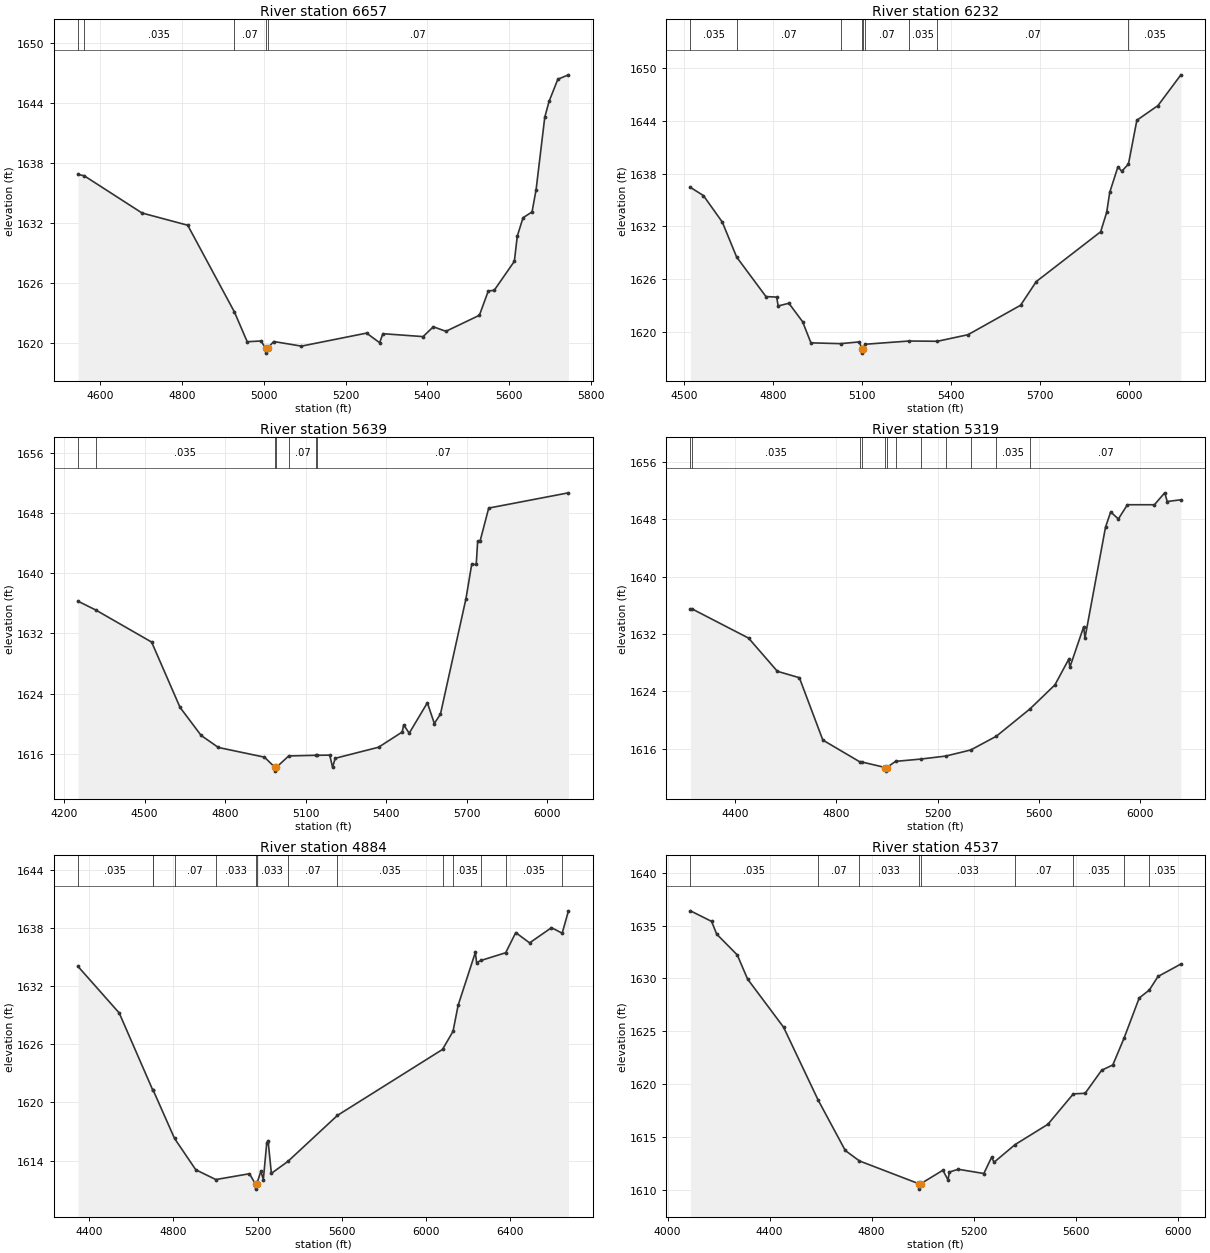
Type RM Length L Ch R = 1 ,6657    ,425,425,425
BEGIN DESCRIPTION:
MULBERRY CREEK TRIBUTARY 2 12.0
END DESCRIPTION:
XS GIS Cut Line= 3
      1583766.02      6891510.66      1583891.32      6891074.81
      1584141.45      6890373.48
#Sta/Elev= 30
  4546.5 1636.86  4561.5 1636.73  4702.9 1633.01  4814.4 1631.79  4928.6 1623.12
  4959.7 1620.16  4993.4 1620.23  5004.7 1619.52  5005.1 1619.02  5009.8 1619.52
  5024.5 1620.18  5092.2 1619.72  5251.4 1621.02  5283.3 1620.06  5291.2 1620.96
  5389.4 1620.67  5414.4 1621.65  5445.2  1621.2    5527  1622.8  5548.7 1625.23
  5563.1 1625.29  5612.4 1628.19  5619.5  1630.7  5633.6 1632.54  5655.6 1633.12
  5665.5 1635.34  5686.7 1642.58  5697.3 1644.17  5718.6 1646.37  5744.6 1646.81
#Mann= 5 ,-1 , 0
  4546.5     .07       0  4561.5    .035       0  4928.6     .07       0
  5004.7     .07       0  5009.8     .07       0
Bank Sta=5004.7,5009.8
XS Rating Curve= 0 ,0
Exp/Cntr=0.3,0.1

Type RM Length L Ch R = 1 ,6232    ,593,593,593
BEGIN DESCRIPTION:
MULBERRY CREEK TRIBUTARY 2 11.0
END DESCRIPTION:
XS GIS Cut Line= 3
       1584088.5      6891751.98        1584205.        6891288.
      1584418.16      6890131.97
#Sta/Elev= 30
  4521.5 1636.44  4565.2 1635.51  4628.7  1632.5  4677.2 1628.51  4776.1 1624.01
  4812.1 1623.95  4817.3 1622.94  4853.3 1623.25  4899.6 1621.15  4927.7 1618.74
  5027.9 1618.65  5091.4 1618.85    5099 1618.07  5099.4 1617.57  5104.1 1618.07
    5110 1618.58  5259.2 1618.95  5354.5 1618.92  5457.5 1619.67  5634.7 1623.02
  5687.7 1625.72  5904.8 1631.39  5925.2 1633.61  5935.4 1635.88  5962.9 1638.77
  5976.1 1638.29  5998.5 1639.09  6026.9 1644.09  6098.1 1645.76  6175.4 1649.26
#Mann= 9 ,-1 , 0
  4521.5    .035       0  4677.2     .07       0  5027.9    .035       0
    5099     .07       0  5104.1    .035       0    5110     .07       0
  5259.2    .035       0  5354.5     .07       0  5998.5    .035       0
Bank Sta=5099,5104.1
XS Rating Curve= 0 ,0
Exp/Cntr=0.3,0.1

Type RM Length L Ch R = 1 ,5639    ,320,320,320
BEGIN DESCRIPTION:
MULBERRY CREEK TRIBUTARY 2 10.0
END DESCRIPTION:
XS GIS Cut Line= 3
      1584279.04      6891976.34      1584740.05      6891387.68
      1585091.53        6890367.
#Sta/Elev= 30
  4252.3 1636.29  4317.8 1635.13  4526.4 1630.85  4632.2 1622.16  4710.9 1618.42
  4775.1 1616.82  4946.8 1615.53  4985.9 1614.17  4986.3 1613.67  4991.1 1614.17
    5037 1615.69  5139.6 1615.78  5141.1 1615.78    5190  1615.8  5200.6 1614.19
  5210.4 1615.38  5371.8 1616.85  5460.1 1618.88  5465.4 1619.83  5486.1 1618.72
  5553.8 1622.77  5579.7 1620.01  5602.5 1621.26  5697.7 1636.65  5718.9 1641.19
  5735.8 1641.18  5741.1 1644.25  5750.6 1644.35  5782.3 1648.69  6079.5 1650.72
#Mann= 7 ,-1 , 0
  4252.3     .07       0  4317.8    .035       0  4985.9    .035       0
  4991.1    .035       0    5037     .07       0  5139.6    .035       0
  5141.1     .07       0
Bank Sta=4985.9,4991.1
XS Rating Curve= 0 ,0
Exp/Cntr=0.3,0.1

Type RM Length L Ch R = 1 ,5319    ,435,435,435
BEGIN DESCRIPTION:
MULBERRY CREEK TRIBUTARY 2 9.0
END DESCRIPTION:
XS GIS Cut Line= 3
       1584315.5      6892025.81        1584955.        6891588.
      1585156.65      6890445.06
#Sta/Elev= 30
  4224.7 1635.45  4231.1 1635.51    4454 1631.44  4567.7 1626.81  4654.4 1625.92
  4747.1 1617.22  4893.3 1614.18  4901.4 1614.16  4994.1 1613.39  4994.5 1612.89
  4999.3 1613.39  5034.1 1614.25    5133 1614.57  5231.9 1614.99  5330.9 1615.84
    5432 1617.76  5564.1 1621.55  5663.2 1624.92  5717.4 1628.48  5722.4 1627.41
  5776.6 1633.02  5781.7 1631.45  5862.8 1646.91  5883.1 1649.03  5913.6 1648.06
  5949.2 1650.04  6055.8 1650.04  6096.4  1651.7  6106.5 1650.49  6160.3 1650.73
#Mann= 12 ,-1 , 0
  4224.7     .07       0  4231.1    .035       0  4893.3     .07       0
  4901.4    .033       0  4994.1    .033       0  4999.3    .033       0
  5034.1     .07       0    5133     .07       0  5231.9    .035       0
  5330.9     .07       0    5432    .035       0  5564.1     .07       0
Bank Sta=4994.1,4999.3
XS Rating Curve= 0 ,0
Exp/Cntr=0.3,0.1

Type RM Length L Ch R = 1 ,4884    ,347,347,347
BEGIN DESCRIPTION:
MULBERRY CREEK TRIBUTARY 2 8.0
END DESCRIPTION:
XS GIS Cut Line= 3
      1584411.82      6892096.13        1585055.        6891988.
      1586531.27      6891194.97
#Sta/Elev= 30
  4348.2 1634.05  4543.5 1629.25  4702.3 1621.31  4704.8 1621.27  4806.1 1616.29
    4907 1613.05  5002.2 1612.04  5161.9 1612.64  5190.8 1611.55  5191.2 1611.05
    5196 1611.55  5216.1  1612.9  5227.7 1612.04  5243.9 1615.83  5250.1 1616.06
  5265.9 1612.68  5344.2 1613.91  5579.7 1618.67  6078.2 1625.48  6128.2 1627.35
  6152.3 1630.04  6234.3 1635.51    6240 1634.45  6261.8 1634.68  6378.1 1635.47
  6425.9 1637.55  6491.7 1636.49  6595.6 1638.06  6646.3 1637.49  6676.2  1639.8
#Mann= 14 ,-1 , 0
  4348.2    .035       0  4702.3     .07       0  4704.8    .035       0
  4806.1     .07       0  5002.2    .033       0  5190.8     .07       0
    5196    .033       0  5344.2     .07       0  5579.7    .035       0
  6078.2     .07       0  6128.2    .035       0  6261.8     .07       0
  6378.1    .035       0  6646.3     .07       0
Bank Sta=5190.8,5196
XS Rating Curve= 0 ,0
Exp/Cntr=0.3,0.1

Type RM Length L Ch R = 1 ,4537    ,379,379,379
BEGIN DESCRIPTION:
MULBERRY CREEK TRIBUTARY 2 7.0
END DESCRIPTION:
XS GIS Cut Line= 3
        1584253.      6892184.67      1585155.77      6892303.09
      1586164.49      6892398.21
#Sta/Elev= 30
  4089.5  1636.4  4172.2  1635.4  4192.4 1634.19  4273.1 1632.22  4313.4 1629.94
  4454.6 1625.38  4590.4 1618.47  4696.7  1613.7  4752.3 1612.71  4986.4 1610.54
  4986.8 1610.04  4991.9 1610.54  5079.6 1611.83  5099.7 1610.91  5105.1 1611.66
  5139.8 1611.92  5240.3 1611.52  5270.4 1613.05  5280.5 1612.59  5362.9 1614.26
  5491.4 1616.18  5591.2 1619.06  5637.6 1619.12  5702.3  1621.3  5746.1  1621.8
  5790.2 1624.34  5849.6 1628.14  5889.4  1628.9  5923.3 1630.18  6013.2 1631.36
#Mann= 9 ,-1 , 0
  4089.5    .035       0  4590.4     .07       0  4752.3    .033       0
  4986.4    .033       0  4991.9    .033       0  5362.9     .07       0
  5591.2    .035       0  5790.2     .07       0  5889.4    .035       0
Bank Sta=4986.4,4991.9
XS Rating Curve= 0 ,0
Exp/Cntr=0.3,0.1

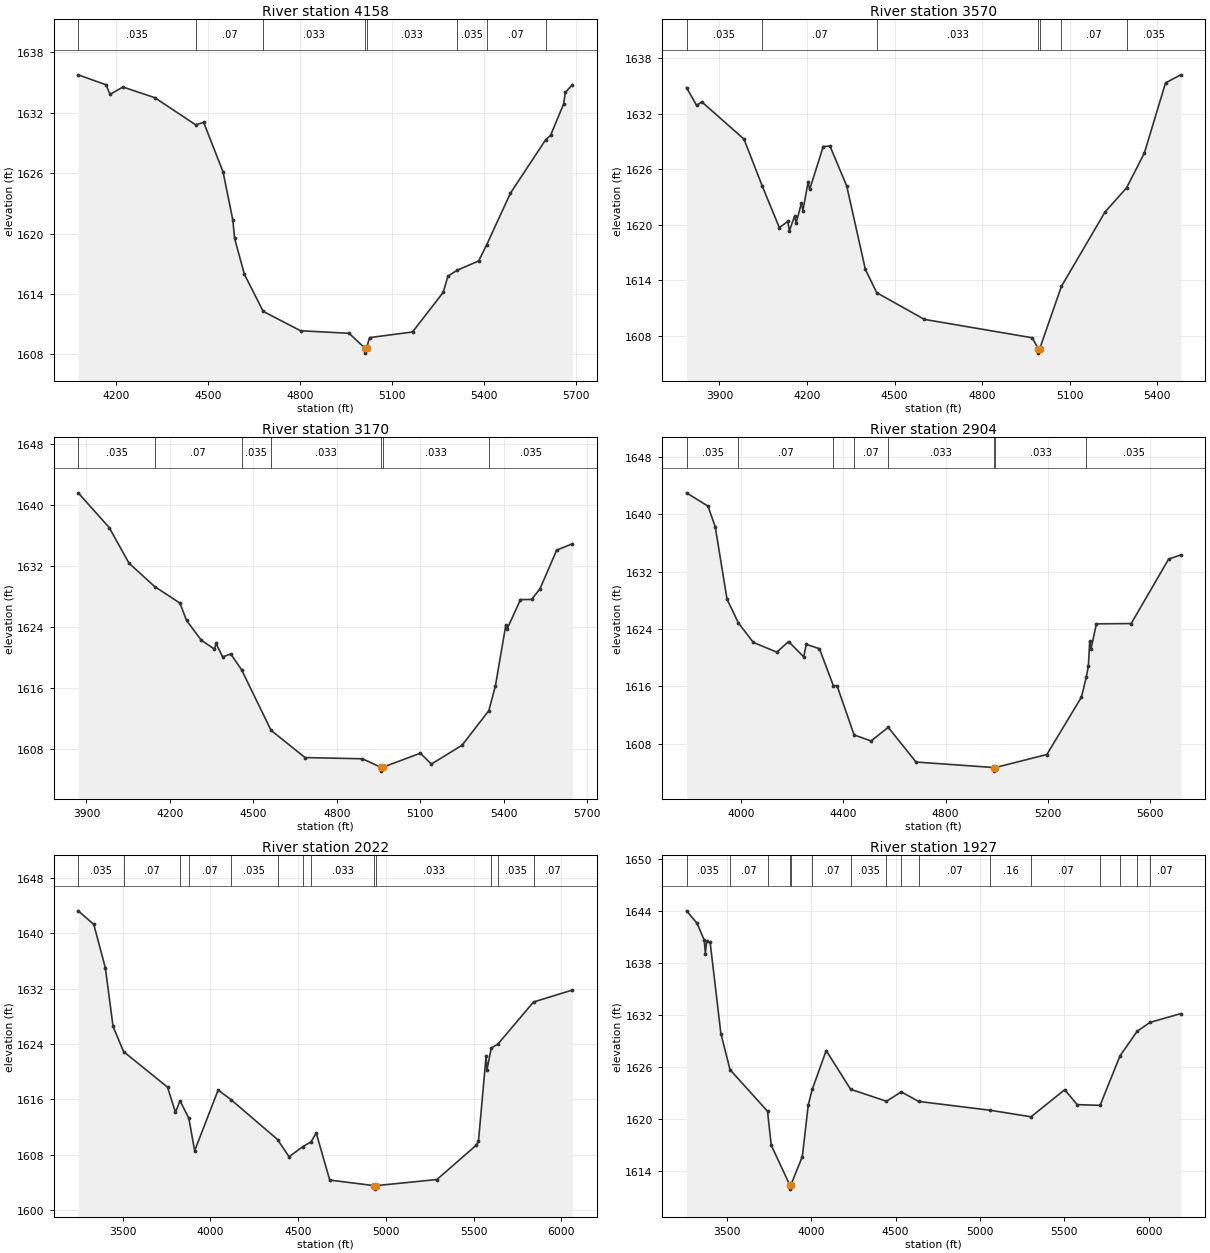
Type RM Length L Ch R = 1 ,4158    ,588,588,588
BEGIN DESCRIPTION:
MULBERRY CREEK TRIBUTARY 2 6.0
END DESCRIPTION:
XS GIS Cut Line= 3
      1584196.58      6892333.97      1585072.55      6892621.35
      1585654.96      6892987.98
#Sta/Elev= 30
  4078.1 1635.75  4168.6 1634.76  4181.7 1633.81  4223.8 1634.54  4327.7 1633.48
  4460.6 1630.79  4486.8 1631.03    4550 1626.11  4581.6 1621.37  4587.6 1619.51
  4619.4 1615.96  4680.8 1612.27  4802.6 1610.35  4960.5  1610.1  5011.9 1608.63
  5012.4 1608.13  5017.5 1608.63  5027.2 1609.67  5167.2 1610.23  5267.3 1614.16
  5282.6 1615.77  5312.4 1616.35  5382.7 1617.28    5409 1618.89  5486.3 1624.01
  5601.1 1629.31    5617 1629.74  5659.4 1632.85  5665.3 1634.01  5688.2 1634.78
#Mann= 8 ,-1 , 0
  4078.1    .035       0  4460.6     .07       0  4680.8    .033       0
  5011.9    .033       0  5017.5    .033       0  5312.4    .035       0
    5409     .07       0  5601.1    .035       0
Bank Sta=5011.9,5017.5
XS Rating Curve= 0 ,0
Exp/Cntr=0.3,0.1

Type RM Length L Ch R = 1 ,3570    ,400,400,400
BEGIN DESCRIPTION:
MULBERRY CREEK TRIBUTARY 2 5.0
END DESCRIPTION:
XS GIS Cut Line= 3
      1584044.85      6892590.47        1585155.        6893088.
      1585615.22      6893212.88
#Sta/Elev= 30
  3787.3 1634.81  3821.9 1632.88  3839.6 1633.27  3984.2 1629.24  4046.9 1624.16
  4105.3 1619.67  4134.2 1620.35  4139.7 1619.33  4157.4 1620.91  4162.9 1620.16
  4180.6  1622.3  4186.1 1621.51  4203.8 1624.61  4209.3  1623.8  4255.6 1628.44
  4278.8 1628.49  4336.1 1624.19  4400.2 1615.15  4439.1 1612.64  4602.1 1609.76
  4971.8 1607.77  4992.1 1606.61  4992.6 1606.11  4997.8 1606.61  5071.8 1613.32
  5221.4 1621.37  5295.3 1623.98  5356.1 1627.73  5428.7 1635.32  5480.7 1636.19
#Mann= 7 ,-1 , 0
  3787.3    .035       0  4046.9     .07       0  4439.1    .033       0
  4992.1    .033       0  4997.8    .033       0  5071.8     .07       0
  5295.3    .035       0
Bank Sta=4992.1,4997.8
XS Rating Curve= 0 ,0
Exp/Cntr=0.3,0.1

Type RM Length L Ch R = 1 ,3170    ,266,266,266
BEGIN DESCRIPTION:
MULBERRY CREEK TRIBUTARY 2 4.0
END DESCRIPTION:
XS GIS Cut Line= 3
      1583892.57      6892972.01      1584934.48      6893407.87
      1585581.55      6893384.38
#Sta/Elev= 30
  3870.6 1641.57  3981.9 1637.01  4053.3 1632.33  4145.5 1629.27  4236.2  1627.1
  4259.9 1624.83    4313 1622.23  4360.5 1621.06    4366 1621.81  4389.8 1620.04
    4419 1620.43  4457.8 1618.36  4563.9  1610.4  4686.2 1606.83  4892.2 1606.67
  4959.2 1605.55  4959.6 1605.05  4964.9 1605.55  5100.6  1607.4  5140.6 1605.98
  5250.7 1608.45    5347 1612.99  5370.8 1616.27  5407.8 1624.18  5412.8 1623.72
  5460.8 1627.56  5500.9 1627.58  5530.9 1628.98  5590.9 1634.05  5647.5 1634.88
#Mann= 7 ,-1 , 0
  3870.6    .035       0  4145.5     .07       0  4457.8    .035       0
  4563.9    .033       0  4959.2    .033       0  4964.9    .033       0
    5347    .035       0
Bank Sta=4959.2,4964.9
XS Rating Curve= 0 ,0
Exp/Cntr=0.3,0.1

Type RM Length L Ch R = 1 ,2904    ,882,882,882
BEGIN DESCRIPTION:
MULBERRY CREEK TRIBUTARY 2 3.0
END DESCRIPTION:
XS GIS Cut Line= 3
      1583807.93      6893126.08      1584912.28      6893631.47
      1585600.21      6893416.95
#Sta/Elev= 30
  3785.5 1643.02  3869.5 1641.16    3898 1638.25    3944 1628.19  3988.6 1624.86
  4047.1 1622.15  4139.1 1620.79  4185.1 1622.27  4244.2 1620.14  4254.2 1621.88
  4305.7 1621.28  4360.3 1616.13  4374.8 1616.11  4441.7 1609.24  4508.1  1608.4
  4575.3  1610.3  4684.1 1605.46  4989.1 1604.69  4989.6 1604.19  4994.8 1604.69
  5196.5 1606.51  5331.8 1614.51  5350.7 1617.28    5359 1618.85  5364.3 1622.36
  5369.5 1621.27  5390.4 1624.74  5526.6 1624.78  5673.2 1633.77  5720.6 1634.36
#Mann= 8 ,-1 , 0
  3785.5    .035       0  3988.6     .07       0  4360.3    .035       0
  4441.7     .07       0  4575.3    .033       0  4989.1    .033       0
  4994.8    .033       0  5350.7    .035       0
Bank Sta=4989.1,4994.8
XS Rating Curve= 0 ,0
Exp/Cntr=0.3,0.1

Type RM Length L Ch R = 1 ,2022    ,95,95,95
BEGIN DESCRIPTION:
Mapping XS bf734681
END DESCRIPTION:
XS GIS Cut Line= 5
      1583766.79      6893128.34       1584412.6      6893475.55
      1584544.54      6893979.02       1585287.6      6894350.55
      1586001.45      6894509.96
#Sta/Elev= 30
  3247.4 1643.23  3336.1 1641.26  3401.9 1634.98  3445.7 1626.52    3506 1622.87
  3756.3 1617.74  3801.2  1614.1  3827.4 1615.77  3877.7 1613.23  3910.7 1608.55
  4044.6 1617.33  4117.1 1615.95  4383.2 1610.17  4448.6 1607.68  4527.8 1609.16
  4573.8 1609.83  4603.6 1611.11  4680.5 1604.31  4935.2  1603.5  4935.7    1603
  4942.9  1603.5  5291.2 1604.39  5513.6 1609.31  5527.8 1609.89  5571.3 1622.19
  5576.4 1620.24  5600.9 1623.39  5638.9 1623.97  5841.6 1630.05  6063.3 1631.78
#Mann= 13 ,-1 , 0
  3247.4    .035       0    3506     .07       0  3827.4    .035       0
  3877.7     .07       0  4117.1    .035       0  4383.2    .033       0
  4527.8    .035       0  4573.8    .033       0  4935.2    .033       0
  4942.9    .033       0  5600.9     .07       0  5638.9    .035       0
  5841.6     .07       0
Bank Sta=4935.2,4942.9
XS Rating Curve= 0 ,0
Exp/Cntr=0.3,0.1

Type RM Length L Ch R = 1 ,1927    ,73,73,73
BEGIN DESCRIPTION:
Mapping XS 651b16b0
END DESCRIPTION:
XS GIS Cut Line= 6
      1583714.71      6893110.99      1584346.62      6893659.58
      1584478.57      6894038.05      1584985.51      6894301.94
      1585447.32      6894551.94      1586040.54      6894576.23
#Sta/Elev= 30
  3261.3    1644  3323.3 1642.57  3366.1 1640.63  3372.7 1639.08  3380.3  1640.5
  3401.2 1640.36  3464.8 1629.86  3518.8 1625.71  3741.1 1620.92    3763 1617.02
  3872.1 1612.45  3872.6 1611.95  3879.8 1612.45  3947.2 1615.69  3982.4 1621.63
  4005.9 1623.43  4088.7 1627.91  4233.3 1623.45    4446 1622.07  4533.6 1623.15
  4636.8 1622.05    5062 1621.03  5302.5 1620.28    5502  1623.4  5576.3 1621.68
  5711.7  1621.6    5829 1627.27  5930.7 1630.12  6006.8 1631.15  6189.3 1632.16
#Mann= 16 ,-1 , 0
  3261.3    .035       0  3518.8     .07       0  3741.1    .035       0
  3872.1     .07       0  3879.8    .035       0  4005.9     .07       0
  4233.3    .035       0    4446     .07       0  4533.6    .035       0
  4636.8     .07       0    5062     .16       0  5302.5     .07       0
  5711.7    .035       0    5829     .07       0  5930.7    .035       0
  6006.8     .07       0
Bank Sta=3872.1,3879.8
XS Rating Curve= 0 ,0
Exp/Cntr=0.3,0.1

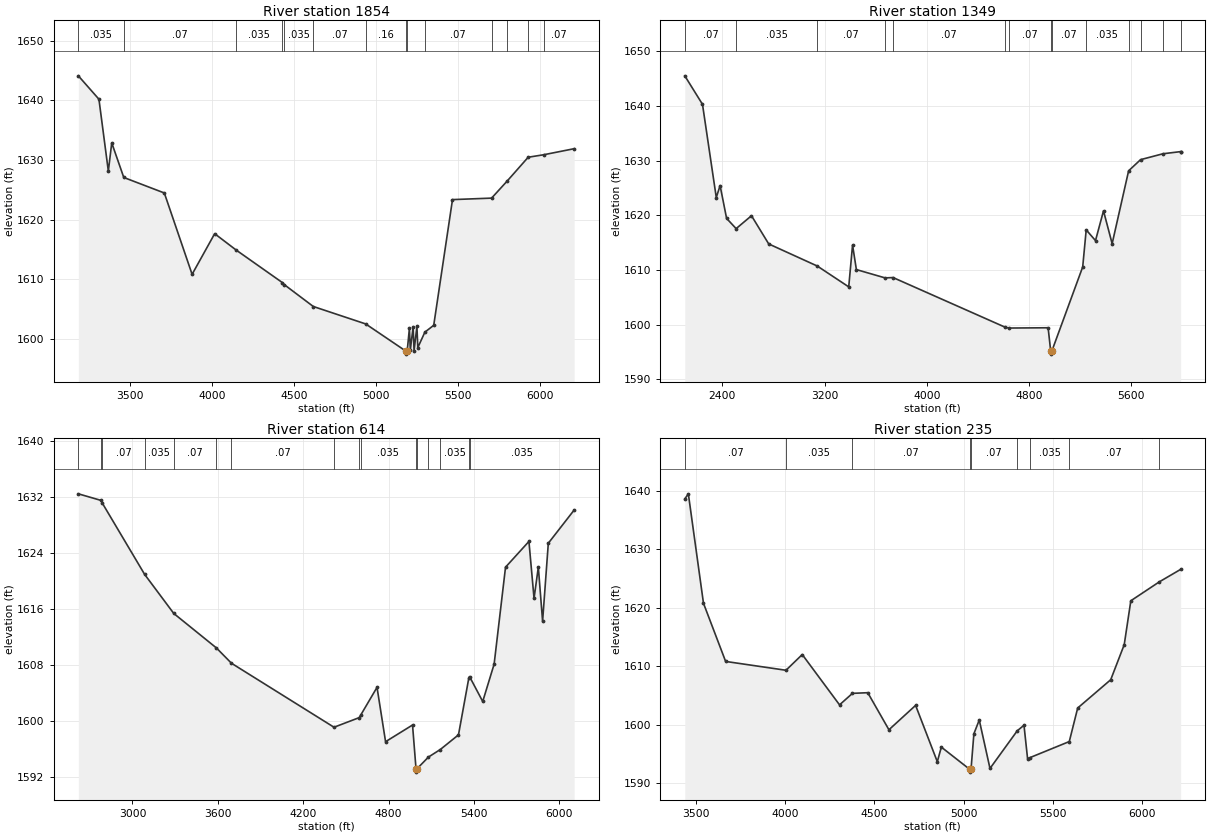
Type RM Length L Ch R = 1 ,1854    ,505,505,505
BEGIN DESCRIPTION:
Mapping XS 29ef661b
END DESCRIPTION:
XS GIS Cut Line= 5
      1583652.16      6893093.59      1584148.71       6893694.3
      1584409.12      6894104.02      1585423.01      6894576.25
      1586060.97      6894614.39
#Sta/Elev= 30
  3184.9 1644.11  3310.5 1640.19  3367.8 1628.15  3388.6 1632.87  3461.9 1627.08
  3709.1 1624.48  3878.4 1610.85    4016 1617.66  4146.4 1614.93  4428.5 1609.47
  4439.5 1609.14  4617.2 1605.46  4936.5 1602.54  5181.8 1597.98  5182.3 1597.48
  5189.5 1597.98    5203 1601.78  5208.6 1598.19  5225.9 1602.08  5231.4 1598.08
  5248.8 1602.11  5254.3 1598.57  5297.2 1601.16  5351.3 1602.31  5465.7 1623.37
    5704 1623.62    5798 1626.45  5927.1 1630.47  6020.5 1630.88  6207.3  1631.9
#Mann= 14 ,-1 , 0
  3184.9    .035       0  3461.9     .07       0  4146.4    .035       0
  4428.5     .07       0  4439.5    .035       0  4617.2     .07       0
  4936.5     .16       0  5181.8     .07       0  5189.5     .16       0
  5297.2     .07       0    5704    .035       0    5798     .07       0
  5927.1    .035       0  6020.5     .07       0
Bank Sta=5181.8,5189.5
XS Rating Curve= 0 ,0
Exp/Cntr=0.3,0.1

Type RM Length L Ch R = 1 ,1349    ,735,735,735
BEGIN DESCRIPTION:
Mapping XS 2a48edf1
END DESCRIPTION:
XS GIS Cut Line= 4
       1582711.2      6893208.19      1583982.04      6894065.83
      1584631.35        6894670.       1586089.7      6894777.64
#Sta/Elev= 30
  2105.5 1645.49    2244 1640.28    2352 1623.24  2381.9 1625.42  2432.8 1619.42
  2507.5 1617.55  2627.7 1619.91  2762.6 1614.75  3142.8 1610.71  3389.1  1606.9
  3419.1 1614.54    3449 1610.06  3673.8 1608.54  3736.5  1608.6  4611.1 1599.55
  4642.6 1599.37  4950.4 1599.42  4970.8  1595.1  4971.3  1594.6  4978.6  1595.1
  5221.1 1610.54  5248.6 1617.32  5321.4 1615.36    5384  1620.8  5451.7  1614.8
  5580.7 1628.12  5674.2 1630.16    5850 1631.24  5987.8 1631.63  5987.9 1631.63
#Mann= 14 ,-1 , 0
  2105.5     .07       0  2507.5    .035       0  3142.8     .07       0
  3673.8    .035       0  3736.5     .07       0  4611.1     .16       0
  4642.6     .07       0  4970.8     .07       0  4978.6     .07       0
  5248.6    .035       0  5580.7     .07       0  5674.2    .035       0
    5850     .07       0  5987.8    .035       0
Bank Sta=4970.8,4978.6
XS Rating Curve= 0 ,0
Exp/Cntr=0.3,0.1

Type RM Length L Ch R = 1 ,614     ,379,379,379
BEGIN DESCRIPTION:
Mapping XS 97d5aa28
END DESCRIPTION:
XS GIS Cut Line= 4
      1582777.18      6894058.89      1583527.18      6894531.11
      1584902.18       6895107.5      1586006.31        6895045.
#Sta/Elev= 30
    2620  1632.5  2780.7 1631.55  2789.3 1631.14  3085.7 1620.96  3290.5 1615.36
  3589.5 1610.43  3695.7 1608.23  4416.1 1599.06  4593.4 1600.44  4603.4 1600.79
  4718.3 1604.78  4778.3 1596.99  4967.7 1599.38  4992.1 1593.13  4992.6 1592.63
  4999.9 1593.13  5079.6 1594.79  5162.8 1595.87  5290.5 1597.97  5363.4 1606.15
  5368.4 1606.31  5460.8 1602.75  5540.9  1608.1    5621 1621.99  5785.4 1625.68
  5821.3 1617.52  5851.4    1622  5881.4 1614.25  5921.5 1625.42  6103.1 1630.18
#Mann= 16 ,-1 , 0
    2620     .07       0  2780.7    .035       0  2789.3     .07       0
  3085.7    .035       0  3290.5     .07       0  3589.5    .035       0
  3695.7     .07       0  4416.1    .035       0  4593.4     .07       0
  4603.4    .035       0  4992.1    .035       0  4999.9    .035       0
  5079.6     .07       0  5162.8    .035       0  5363.4     .07       0
  5368.4    .035       0
Bank Sta=4992.1,4999.9
XS Rating Curve= 0 ,0
Exp/Cntr=0.3,0.1

Type RM Length L Ch R = 1 ,235     ,0,0,0
BEGIN DESCRIPTION:
MULBERRY CREEK TRIBUTARY 2 1.0
END DESCRIPTION:
XS GIS Cut Line= 3
      1583318.82      6894735.96      1584727.45      6895414.64
      1585940.15      6895308.91
#Sta/Elev= 30
  3436.4 1638.64  3456.3 1639.51  3541.2 1620.78  3665.4 1610.83  4003.8 1609.32
  4095.2 1612.01  4304.3  1603.4  4376.8 1605.37  4462.6 1605.48  4581.3 1599.14
  4730.9 1603.31  4852.7 1593.67  4875.2 1596.17  5033.5 1592.39    5034 1591.89
  5041.8 1592.39  5057.8 1598.45  5087.9 1600.81  5148.1 1592.52  5301.2 1598.97
  5338.8 1599.91  5358.9  1594.2  5372.8 1594.38  5592.8 1597.12    5640 1602.86
  5825.2  1607.7    5901  1613.7    5938 1621.21  6097.9 1624.45  6217.3 1626.58
#Mann= 9 ,-1 , 0
  3436.4     .07       0  4003.8    .035       0  4376.8     .07       0
  5033.5     .07       0  5041.8     .07       0  5301.2     .07       0
  5372.8    .035       0  5592.8     .07       0  6097.9    .035       0
Bank Sta=5033.5,5041.8
XS Rating Curve= 0 ,0
Exp/Cntr=0.3,0.1

Chan Stop Cuts=-1
Use User Specified Reach Order=0
Composite Channel Slope=5