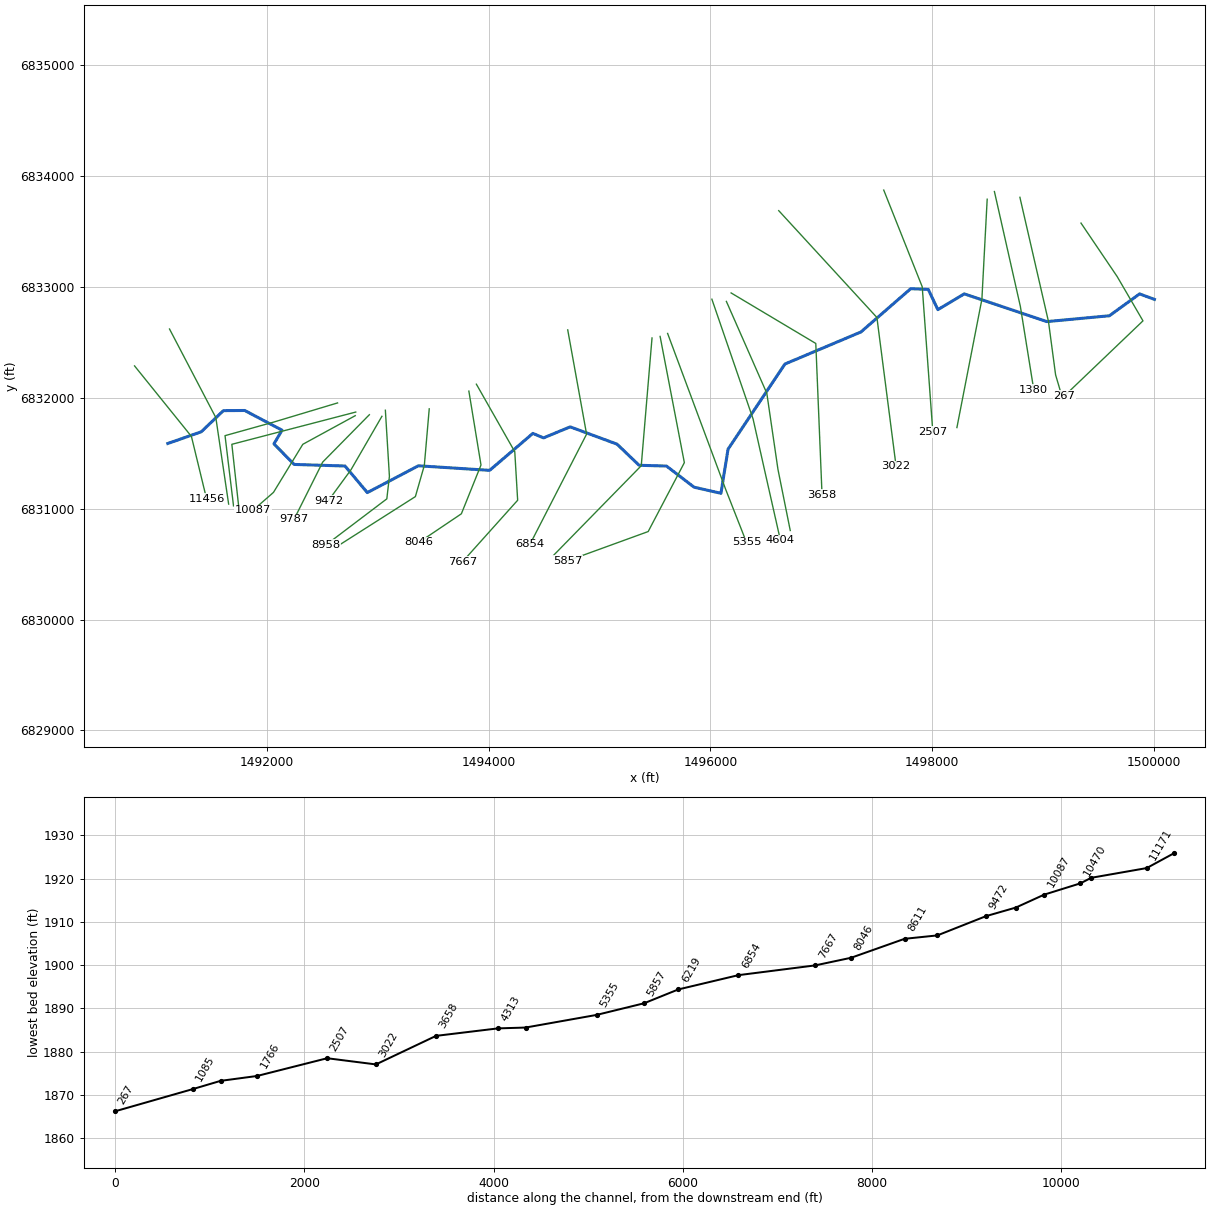
--- MULBERRY CREEK TRIBUTARY 20.prj (project) ---

Proj Title=MULBERRY CREEK TRIBUTARY 20 Base Level Engineering
Current Plan=p01
Default Exp/Contr=0.3,0.1
English Units
Geom File=g01
Flow File=f01
Plan File=p01
BEGIN DESCRIPTION:
MULBERRY CREEK TRIBUTARY 20
END DESCRIPTION:

--- MULBERRY CREEK TRIBUTARY 20.p01 (plan) ---

Plan Title=Multiple Run
Short Identifier=Multiple
Geom File=g01
Flow File=f01
Subcritical Flow
K Sum by GR= 0
Std Step Tol= 0.01
Critical Tol= 0.01
Num of Std Step Trials= 20
Max Error Tol= 0.3
Flow Tol Ratio= 0.001
Split Flow NTrial= 30
Split Flow Tol= 0.02
Split Flow Ratio= 0.02
Log Output Level= 0
Friction Slope Method= 1
Unsteady Friction Slope Method= 2
Unsteady Bridges Friction Slope Method= 1
Parabolic Critical Depth
Global Vel Dist=  1 , 1 , 1
Global Log Level= 0
CheckData=True
Encroach Param= -1, 0, 0, 0
BEGIN DESCRIPTION:
Multiple Run
END DESCRIPTION:

--- MULBERRY CREEK TRIBUTARY 20.f01 (steady flow) ---

Flow Title=Multiple
Number of Profiles=7
Profile Names=10-year,25-year,50-year,1pct_min,100-year,1pct_plu,500-year
River Rch & RM= MULBERRY CREEK T,Reach-1,11456
     177     241     293     178     354     707     522
River Rch & RM= MULBERRY CREEK T,Reach-1,7667
     259     360     444     272     544    1085     824
River Rch & RM= MULBERRY CREEK T,Reach-1,4313
     369     523     653     405     808    1612    1252
Boundary for River Rch & Prof#=MULBERRY CREEK T,Reach-1,1
Up Type=0
Dn Type=3
Dn Slope=0.005
Boundary for River Rch & Prof#=MULBERRY CREEK T,Reach-1,2
Up Type=0
Dn Type=3
Dn Slope=0.005
Boundary for River Rch & Prof#=MULBERRY CREEK T,Reach-1,3
Up Type=0
Dn Type=3
Dn Slope=0.005
Boundary for River Rch & Prof#=MULBERRY CREEK T,Reach-1,4
Up Type=0
Dn Type=3
Dn Slope=0.005
Boundary for River Rch & Prof#=MULBERRY CREEK T,Reach-1,5
Up Type=0
Dn Type=3
Dn Slope=0.005
Boundary for River Rch & Prof#=MULBERRY CREEK T,Reach-1,6
Up Type=0
Dn Type=3
Dn Slope=0.005
Boundary for River Rch & Prof#=MULBERRY CREEK T,Reach-1,7
Up Type=0
Dn Type=3
Dn Slope=0.005

--- MULBERRY CREEK TRIBUTARY 20.g01 (geometry) ---

Geom Title=Existing Conditions

River Reach=MULBERRY CREEK T,Reach-1
Reach XY= 30
      1491105.00      6831588.00      1491407.30      6831693.83
      1491606.46      6831884.47      1491799.06      6831885.74
      1492135.79      6831708.00      1492062.61      6831584.67
      1492244.94      6831399.10      1492703.38      6831384.87
      1492904.99      6831145.07      1493365.55      6831386.91
      1494008.42      6831345.80      1494397.99      6831678.97
      1494494.35      6831638.66      1494734.96      6831737.95
      1495157.29      6831582.19      1495356.46      6831391.54
      1495603.54      6831384.46      1495852.68      6831193.77
      1496094.69      6831138.86      1496158.75      6831536.45
      1496671.64      6832304.71      1497357.30      6832593.83
      1497806.47      6832984.47      1497965.17      6832977.68
      1498051.38      6832795.47      1498289.72      6832937.62
      1499034.64      6832687.64      1499599.06      6832740.26
      1499870.85      6832937.50      1500005.00      6832888.00

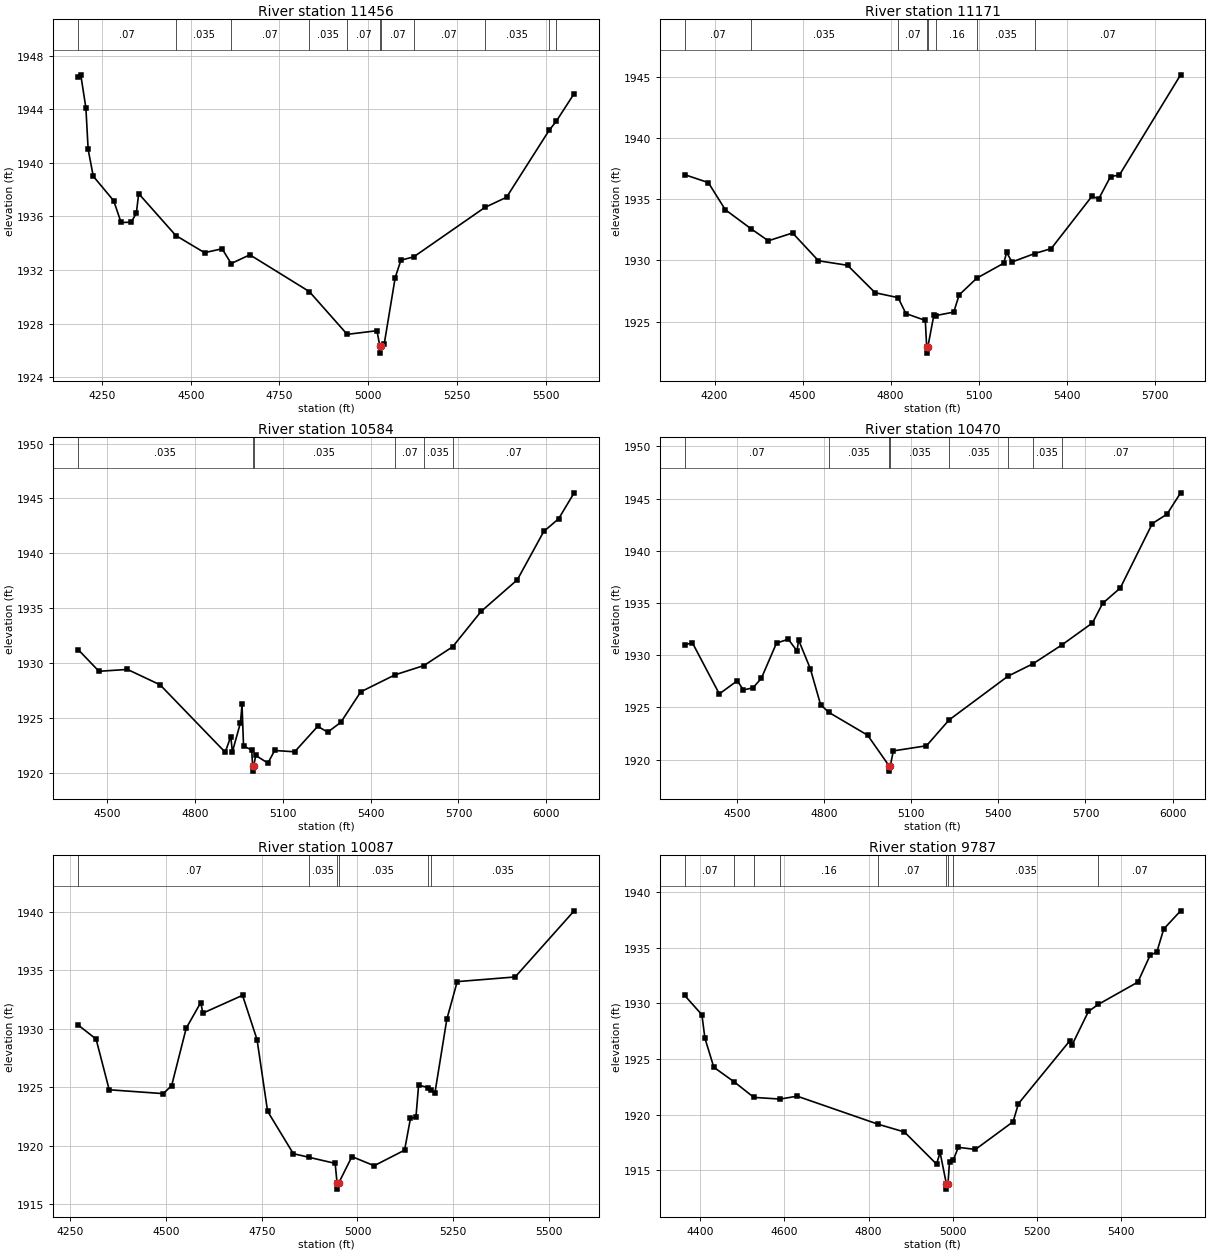
Type RM Length L Ch R = 1,11456,285,285,285
BEGIN DESCRIPTION:
MULBERRY CREEK TRIBUTARY 20 16.0
END DESCRIPTION:
XS GIS Cut Line= 3
      1490804.99      6832288.02      1491318.07      6831651.97
      1491455.01      6831087.95
#Sta/Elev= 30
  4182.8 1946.39  4190.0 1946.56  4204.4 1944.10  4210.8 1941.00  4225.2 1939.00
  4282.8 1937.17  4303.6 1935.55  4332.4 1935.57  4346.7 1936.26  4353.2 1937.70
  4457.8 1934.58  4538.7 1933.30  4588.3 1933.59  4613.8 1932.49  4666.6 1933.14
  4834.0 1930.40  4940.8 1927.21  5024.7 1927.48  5033.0 1926.31  5033.2 1925.81
  5037.0 1926.31  5045.2 1926.50  5076.1 1931.44  5092.2 1932.74  5128.4 1932.99
  5328.6 1936.67  5389.8 1937.43  5509.6 1942.41  5530.3 1943.11  5580.4 1945.16
#Mann=11,-1,0
  4182.8    0.07       0  4457.8   0.035       0  4613.8    0.07       0
  4834.0   0.035       0  4940.8    0.07       0  5033.0    0.07       0
  5037.0    0.07       0  5128.4    0.07       0  5328.6   0.035       0
  5509.6    0.07       0  5530.3   0.035       0
Bank Sta=5033,5037
Exp/Cntr=0.3,0.1

Type RM Length L Ch R = 1,11171,587,587,587
BEGIN DESCRIPTION:
Mapping XS 2239015d
END DESCRIPTION:
XS GIS Cut Line= 3
      1491120.66      6832620.59      1491538.29      6831821.43
      1491653.79      6831041.64
#Sta/Elev= 30
  4098.3 1936.99  4178.9 1936.34  4236.6 1934.13  4323.4 1932.59  4383.3 1931.59
  4465.9 1932.23  4554.2 1929.96  4653.3 1929.59  4747.3 1927.35  4825.5 1926.95
  4852.1 1925.65  4918.3 1925.09  4922.9 1922.92  4923.1 1922.42  4926.9 1922.92
  4947.5 1925.54  4954.8 1925.49  5015.1 1925.77  5033.8 1927.18  5093.8 1928.54
  5185.4 1929.76  5195.5 1930.64  5213.6 1929.86  5291.0 1930.55  5347.2 1930.95
  5486.5 1935.24  5508.9 1935.00  5549.4 1936.83  5579.7 1936.96  5788.3 1945.14
#Mann=8,-1,0
  4098.3    0.07       0  4323.4   0.035       0  4825.5    0.07       0
  4922.9    0.07       0  4926.9    0.07       0  4954.8    0.16       0
  5093.8   0.035       0  5291.0    0.07       0
Bank Sta=4922.9,4926.9
Exp/Cntr=0.3,0.1

Type RM Length L Ch R = 1,10584,114,114,114
BEGIN DESCRIPTION:
Mapping XS 2cdbc9b9
END DESCRIPTION:
XS GIS Cut Line= 4
      1492636.23      6831953.93      1492060.16      6831781.08
      1491621.36      6831658.69      1491697.91      6831025.09
#Sta/Elev= 30
  4400.2 1931.23  4471.2 1929.26  4568.5 1929.43  4680.0 1928.03  4902.6 1921.89
  4921.8 1923.32  4927.1 1921.92  4954.8 1924.58  4960.1 1926.24  4965.3 1922.46
  4993.2 1922.09  4996.3 1920.67  4996.6 1920.17  5000.3 1920.67  5007.0 1921.60
  5048.5 1920.90  5071.7 1922.05  5140.1 1921.93  5218.8 1924.25  5253.0 1923.72
  5297.7 1924.61  5365.9 1927.39  5483.3 1928.94  5581.7 1929.78  5680.0 1931.49
  5777.3 1934.71  5901.1 1937.59  5991.7 1942.00  6042.1 1943.14  6095.4 1945.51
#Mann=6,-1,0
  4400.2   0.035       0  4996.3   0.035       0  5000.3   0.035       0
  5483.3    0.07       0  5581.7   0.035       0  5680.0    0.07       0
Bank Sta=4996.3,5000.3
Exp/Cntr=0.3,0.1

Type RM Length L Ch R = 1,10470,383,383,383
BEGIN DESCRIPTION:
Mapping XS af91ea86
END DESCRIPTION:
XS GIS Cut Line= 3
      1492800.35      6831871.49      1491682.71      6831580.68
      1491743.28      6831031.26
#Sta/Elev= 30
  4320.1 1930.97  4346.3 1931.21  4439.3 1926.29  4501.3 1927.55  4522.0 1926.67
  4555.2 1926.87  4584.0 1927.78  4636.3 1931.16  4676.9 1931.53  4707.0 1930.40
  4712.2 1931.46  4752.7 1928.71  4788.0 1925.26  4815.9 1924.53  4950.1 1922.33
  5024.0 1919.39  5024.3 1918.89  5028.0 1919.39  5038.6 1920.83  5152.7 1921.32
  5230.3 1923.79  5433.3 1927.99  5519.4 1929.18  5617.6 1930.96  5724.1 1933.09
  5759.3 1934.97  5820.0 1936.44  5930.4 1942.62  5980.7 1943.51  6027.7 1945.56
#Mann=8,-1,0
  4320.1    0.07       0  4815.9   0.035       0  5024.0   0.035       0
  5028.0   0.035       0  5230.3   0.035       0  5433.3    0.07       0
  5519.4   0.035       0  5617.6    0.07       0
Bank Sta=5024,5028
Exp/Cntr=0.3,0.1

Type RM Length L Ch R = 1,10087,300,300,300
BEGIN DESCRIPTION:
Mapping XS aa2adb9f
END DESCRIPTION:
XS GIS Cut Line= 4
      1492795.98      6831838.92      1492322.90      6831580.68
      1492058.14      6831146.65      1491871.52      6830983.90
#Sta/Elev= 30
  4270.8 1930.30  4317.5 1929.10  4351.7 1924.77  4493.0 1924.44  4514.8 1925.13
  4552.8 1930.03  4590.7 1932.22  4596.4 1931.32  4699.9 1932.84  4737.8 1929.05
  4765.3 1922.93  4832.5 1919.31  4873.3 1919.00  4941.8 1918.48  4946.7 1916.78
  4946.9 1916.28  4950.7 1916.78  4985.5 1919.06  5043.6 1918.28  5123.0 1919.61
  5138.4 1922.33  5152.6 1922.41  5159.7 1925.17  5183.5 1924.96  5191.6 1924.71
  5202.4 1924.53  5233.3 1930.79  5260.4 1934.01  5411.8 1934.41  5565.8 1940.06
#Mann=6,-1,0
  4270.8    0.07       0  4873.3   0.035       0  4946.7   0.035       0
  4950.7   0.035       0  5183.5    0.07       0  5191.6   0.035       0
Bank Sta=4946.7,4950.7
Exp/Cntr=0.3,0.1

Type RM Length L Ch R = 1,9787,315,315,315
BEGIN DESCRIPTION:
Mapping XS 453652de
END DESCRIPTION:
XS GIS Cut Line= 3
      1492923.20      6831847.64      1492502.16      6831420.09
      1492243.92      6830903.62
#Sta/Elev= 30
  4363.4 1930.71  4404.3 1928.97  4411.4 1926.87  4432.6 1924.25  4480.8 1922.94
  4527.7 1921.54  4590.1 1921.39  4630.5 1921.65  4822.4 1919.13  4885.1 1918.43
  4961.4 1915.54  4969.8 1916.59  4984.6 1913.79  4984.9 1913.29  4988.6 1913.79
  4992.2 1915.77  5001.1 1915.90  5013.0 1917.05  5053.7 1916.86  5143.1 1919.35
  5155.9 1920.98  5277.3 1926.61  5282.9 1926.24  5322.0 1929.27  5345.2 1929.90
  5439.4 1931.91  5468.9 1934.36  5484.1 1934.58  5500.9 1936.69  5540.9 1938.32
#Mann=9,-1,0
  4363.4    0.07       0  4480.8   0.035       0  4527.7    0.07       0
  4590.1    0.16       0  4822.4    0.07       0  4984.6    0.07       0
  4988.6    0.07       0  5001.1   0.035       0  5345.2    0.07       0
Bank Sta=4984.6,4988.6
Exp/Cntr=0.3,0.1

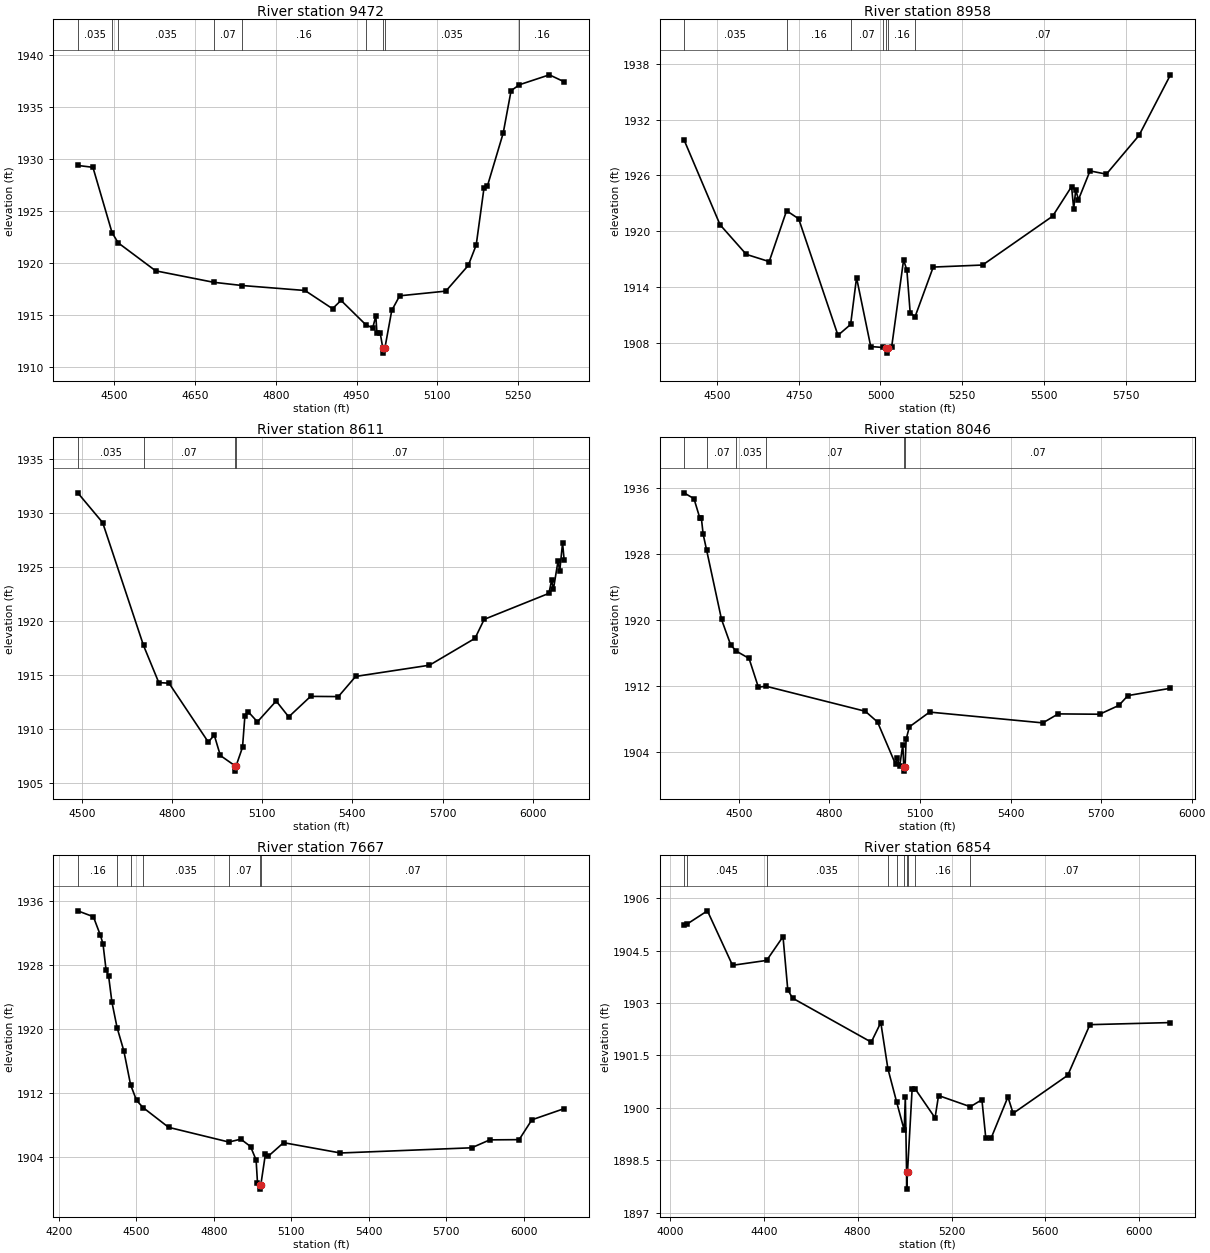
Type RM Length L Ch R = 1,9472,514,514,514
BEGIN DESCRIPTION:
Mapping XS bfff444a
END DESCRIPTION:
XS GIS Cut Line= 3
      1493036.45      6831833.30      1492757.80      6831351.52
      1492553.09      6831071.66
#Sta/Elev= 30
  4432.3 1929.35  4460.5 1929.17  4496.0 1922.89  4507.4 1921.91  4577.0 1919.22
  4684.5 1918.12  4737.3 1917.81  4854.3 1917.33  4905.4 1915.58  4921.2 1916.38
  4967.2 1914.04  4980.0 1913.73  4985.8 1914.87  4988.0 1913.20  4994.1 1913.20
  4998.7 1911.81  4999.0 1911.31  5002.7 1911.81  5015.4 1915.41  5030.1 1916.82
  5115.8 1917.27  5157.5 1919.74  5172.2 1921.70  5186.8 1927.22  5193.0 1927.37
  5222.3 1932.45  5237.0 1936.54  5252.6 1937.11  5308.1 1938.06  5335.6 1937.39
#Mann=9,-1,0
  4432.3   0.035       0  4496.0    0.07       0  4507.4   0.035       0
  4684.5    0.07       0  4737.3    0.16       0  4967.2   0.035       0
  4998.7   0.035       0  5002.7   0.035       0  5252.6    0.16       0
Bank Sta=4998.7,5002.7
Exp/Cntr=0.3,0.1

Type RM Length L Ch R = 1,8958,347,347,347
BEGIN DESCRIPTION:
Mapping XS 3ea8070e
END DESCRIPTION:
XS GIS Cut Line= 4
      1493067.69      6831888.00      1493104.15      6831291.62
      1493080.71      6831088.50      1492533.85      6830674.44
#Sta/Elev= 30
  4399.2 1929.84  4509.4 1920.69  4589.6 1917.50  4659.7 1916.72  4712.9 1922.20
  4749.9 1921.33  4870.1 1908.78  4908.8 1909.95  4926.9 1914.99  4970.3 1907.57
  5006.8 1907.47  5018.5 1907.36  5018.7 1906.86  5022.5 1907.36  5034.2 1907.50
  5070.8 1916.91  5080.9 1915.78  5090.9 1911.23  5105.7 1910.76  5161.4 1916.13
  5312.3 1916.35  5526.6 1921.61  5584.6 1924.80  5591.1 1922.41  5597.4 1924.47
  5605.6 1923.39  5641.0 1926.49  5691.0 1926.14  5790.8 1930.31  5887.1 1936.84
#Mann=7,-1,0
  4399.2   0.035       0  4712.9    0.16       0  4908.8    0.07       0
  5006.8    0.16       0  5018.5    0.07       0  5022.5    0.16       0
  5105.7    0.07       0
Bank Sta=5018.5,5022.5
Exp/Cntr=0.3,0.1

Type RM Length L Ch R = 1,8611,565,565,565
BEGIN DESCRIPTION:
Mapping XS 3668a69e
END DESCRIPTION:
XS GIS Cut Line= 4
      1493463.38      6831900.58      1493419.11      6831390.18
      1493338.38      6831108.93      1492652.08      6830672.19
#Sta/Elev= 30
  4486.1 1931.87  4569.0 1929.11  4704.9 1917.72  4755.7 1914.28  4789.8 1914.22
  4920.3 1908.77  4940.4 1909.40  4960.5 1907.52  5009.1 1906.57  5009.3 1906.07
  5013.1 1906.57  5034.3 1908.28  5042.3 1911.22  5052.7 1911.59  5083.9 1910.64
  5146.3 1912.57  5188.0 1911.10  5260.8 1913.00  5353.2 1912.98  5410.7 1914.85
  5656.3 1915.89  5807.8 1918.38  5838.3 1920.14  6053.6 1922.55  6062.7 1923.76
  6068.6 1922.92  6083.8 1925.52  6089.7 1924.64  6099.1 1927.23  6104.5 1925.60
#Mann=4,-1,0
  4486.1   0.035       0  4704.9    0.07       0  5009.1    0.07       0
  5013.1    0.07       0
Bank Sta=5009.1,5013.1
Exp/Cntr=0.3,0.1

Type RM Length L Ch R = 1,8046,379,379,379
BEGIN DESCRIPTION:
Mapping XS fd155ec6
END DESCRIPTION:
XS GIS Cut Line= 4
      1493820.90      6832060.55      1493930.28      6831393.88
      1493753.20      6830953.78      1493370.39      6830695.97
#Sta/Elev= 30
  4318.3 1935.44  4351.3 1934.73  4370.5 1932.40  4375.6 1932.41  4381.7 1930.43
  4392.8 1928.55  4442.5 1920.10  4472.9 1916.98  4491.6 1916.24  4533.7 1915.36
  4564.5 1911.88  4590.4 1911.98  4918.8 1908.95  4959.3 1907.65  5018.9 1902.54
  5024.3 1903.33  5032.6 1902.27  5043.1 1904.91  5046.5 1902.19  5046.7 1901.69
  5050.5 1902.19  5054.1 1905.56  5064.9 1907.06  5131.8 1908.85  5506.9 1907.54
  5557.9 1908.63  5695.2 1908.59  5758.8 1909.66  5788.8 1910.85  5929.8 1911.74
#Mann=6,-1,0
  4318.3    0.16       0  4392.8    0.07       0  4491.6   0.035       0
  4590.4    0.07       0  5046.5    0.07       0  5050.5    0.07       0
Bank Sta=5046.5,5050.5
Exp/Cntr=0.3,0.1

Type RM Length L Ch R = 1,7667,813,813,813
BEGIN DESCRIPTION:
Mapping XS 793cbffd
END DESCRIPTION:
XS GIS Cut Line= 4
      1493888.61      6832123.06      1494234.97      6831513.68
      1494261.01      6831076.18      1493764.31      6830522.27
#Sta/Elev= 30
  4273.6 1934.74  4334.2 1934.00  4361.5 1931.66  4371.4 1930.61  4383.1 1927.40
  4393.3 1926.54  4405.9 1923.33  4425.9 1920.13  4452.0 1917.23  4478.2 1912.98
  4501.4 1911.02  4526.9 1910.12  4625.3 1907.66  4858.6 1905.82  4905.0 1906.18
  4942.5 1905.26  4964.1 1903.58  4969.5 1900.71  4978.2 1900.43  4978.5 1899.93
  4982.2 1900.43  5000.3 1904.35  5010.3 1904.02  5070.4 1905.74  5290.8 1904.45
  5798.5 1905.10  5868.7 1906.09  5982.4 1906.12  6031.7 1908.60  6156.8 1910.00
#Mann=7,-1,0
  4273.6    0.16       0  4425.9   0.035       0  4478.2    0.07       0
  4526.9   0.035       0  4858.6    0.07       0  4978.2    0.07       0
  4982.2    0.07       0
Bank Sta=4978.2,4982.2
Exp/Cntr=0.3,0.1

Type RM Length L Ch R = 1,6854,635,635,635
BEGIN DESCRIPTION:
Mapping XS 36a27fe1
END DESCRIPTION:
XS GIS Cut Line= 3
      1494712.61      6832613.09      1494882.75      6831672.10
      1494372.34      6830679.04
#Sta/Elev= 30
  4060.0 1905.23  4072.8 1905.26  4159.7 1905.64  4266.7 1904.08  4412.1 1904.22
  4481.8 1904.90  4502.1 1903.38  4522.5 1903.14  4857.8 1901.88  4898.5 1902.44
  4928.7 1901.12  4965.8 1900.17  4998.2 1899.36  5003.0 1900.32  5008.3 1898.17
  5008.5 1897.67  5012.3 1898.17  5032.1 1900.55  5045.0 1900.54  5129.7 1899.71
  5144.5 1900.35  5280.0 1900.03  5329.3 1900.23  5345.9 1899.13  5368.0 1899.12
  5440.2 1900.31  5462.4 1899.84  5695.1 1900.93  5789.5 1902.38  6132.8 1902.44
#Mann=10,-1,0
  4060.0   0.035       0  4072.8   0.045       0  4412.1   0.035       0
  4928.7    0.07       0  4965.8    0.16       0  4998.2    0.07       0
  5008.3    0.07       0  5012.3    0.07       0  5045.0    0.16       0
  5280.0    0.07       0
Bank Sta=5008.3,5012.3
Exp/Cntr=0.3,0.1

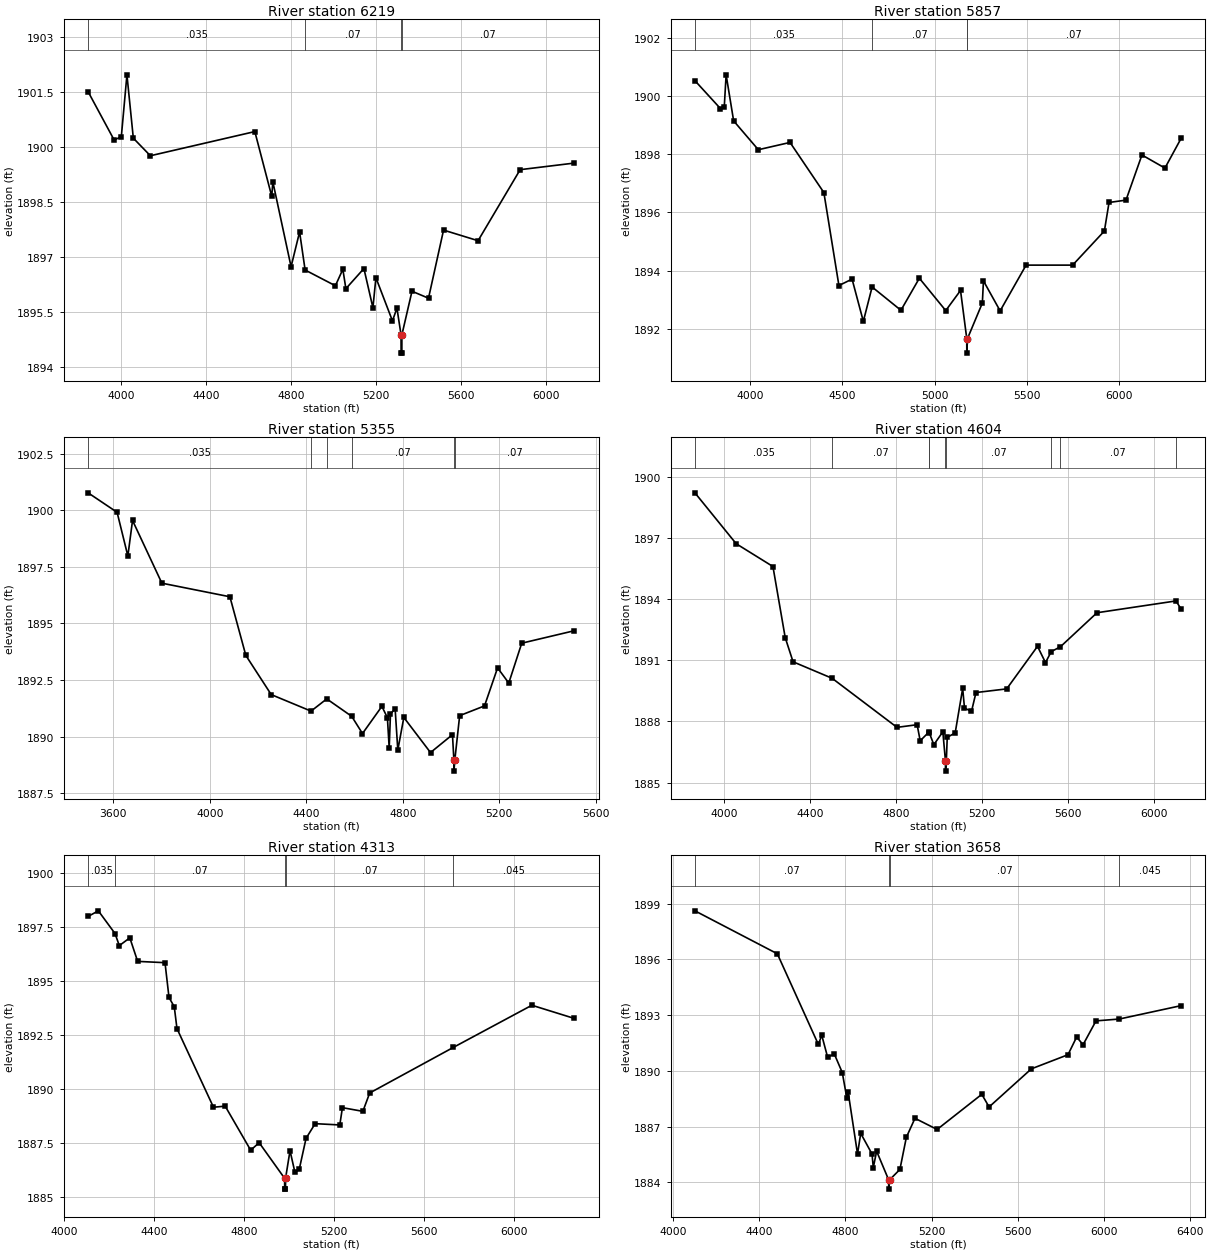
Type RM Length L Ch R = 1,6219,362,362,362
BEGIN DESCRIPTION:
Mapping XS ed3b5d33
END DESCRIPTION:
XS GIS Cut Line= 3
      1495473.03      6832540.12      1495375.81      6831387.37
      1494584.12      6830578.32
#Sta/Elev= 30
  3843.7 1901.51  3966.3 1900.19  4000.1 1900.28  4026.5 1901.97  4056.6 1900.24
  4136.9 1899.76  4628.6 1900.42  4708.3 1898.65  4713.3 1899.05  4799.2 1896.73
  4839.3 1897.68  4865.3 1896.64  5007.8 1896.21  5043.0 1896.66  5057.2 1896.13
  5142.1 1896.68  5184.5 1895.61  5198.6 1896.43  5276.5 1895.25  5297.6 1895.60
  5316.9 1894.87  5317.2 1894.37  5320.7 1894.37  5320.9 1894.87  5368.4 1896.06
  5446.2 1895.87  5517.0 1897.73  5679.5 1897.44  5877.6 1899.38  6132.5 1899.56
#Mann=4,-1,0
  3843.7   0.035       0  4865.3    0.07       0  5316.9    0.07       0
  5320.9    0.07       0
Bank Sta=5316.9,5320.9
Exp/Cntr=0.3,0.1

Type RM Length L Ch R = 1,5857,502,502,502
BEGIN DESCRIPTION:
Mapping XS 8170af73
END DESCRIPTION:
XS GIS Cut Line= 4
      1495545.94      6832554.07      1495764.70      6831415.15
      1495438.31      6830793.62      1494712.65      6830529.75
#Sta/Elev= 30
  3701.7 1900.52  3840.3 1899.56  3860.6 1899.61  3870.8 1900.72  3911.5 1899.14
  4045.2 1898.15  4217.0 1898.40  4400.3 1896.68  4481.8 1893.49  4553.1 1893.71
  4614.1 1892.26  4661.6 1893.44  4817.8 1892.64  4917.5 1893.74  5060.5 1892.63
  5140.6 1893.32  5174.4 1891.67  5174.6 1891.17  5178.4 1891.67  5258.9 1892.89
  5264.8 1893.65  5355.2 1892.62  5495.8 1894.19  5747.9 1894.19  5919.9 1895.36
  5945.2 1896.34  6037.0 1896.42  6123.4 1897.97  6248.0 1897.52  6335.6 1898.54
#Mann=4,-1,0
  3701.7   0.035       0  4661.6    0.07       0  5174.4    0.07       0
  5178.4    0.07       0
Bank Sta=5174.4,5178.4
Exp/Cntr=0.3,0.1

Type RM Length L Ch R = 1,5355,751,751,751
BEGIN DESCRIPTION:
Mapping XS 6bd0613d
END DESCRIPTION:
XS GIS Cut Line= 3
      1495613.68      6832580.66      1496138.76      6831170.76
      1496325.50      6830695.21
#Sta/Elev= 30
  3495.5 1900.77  3615.7 1899.91  3660.3 1897.98  3679.7 1899.55  3801.3 1896.78
  4083.3 1896.18  4149.3 1893.59  4254.6 1891.86  4419.7 1891.13  4484.8 1891.67
  4588.2 1890.90  4632.9 1890.14  4713.3 1891.34  4736.2 1890.84  4743.6 1889.50
  4748.9 1891.00  4768.2 1891.24  4779.3 1889.41  4804.3 1890.85  4914.9 1889.30
  5005.9 1890.09  5011.7 1888.98  5012.0 1888.48  5015.7 1888.98  5035.7 1890.93
  5138.7 1891.36  5192.9 1893.04  5239.3 1892.37  5293.0 1894.13  5510.9 1894.68
#Mann=6,-1,0
  3495.5   0.035       0  4419.7    0.07       0  4484.8    0.16       0
  4588.2    0.07       0  5011.7    0.07       0  5015.7    0.07       0
Bank Sta=5011.7,5015.7
Exp/Cntr=0.3,0.1

Type RM Length L Ch R = 1,4604,291,291,291
BEGIN DESCRIPTION:
Mapping XS 2bfd0e9c
END DESCRIPTION:
XS GIS Cut Line= 4
      1496012.98      6832889.69      1496384.51      6831809.83
      1496492.15      6831330.67      1496631.05      6830716.06
#Sta/Elev= 30
  3863.9 1899.23  4056.0 1896.73  4227.1 1895.61  4284.2 1892.12  4320.8 1890.93
  4502.7 1890.12  4804.6 1887.71  4898.3 1887.84  4912.6 1887.05  4952.2 1887.47
  4955.0 1887.44  4976.1 1886.86  5018.0 1887.49  5030.2 1886.06  5030.4 1885.56
  5034.2 1886.06  5038.5 1887.22  5075.5 1887.44  5110.3 1889.62  5118.8 1888.66
  5151.3 1888.49  5172.3 1889.42  5315.2 1889.60  5458.7 1891.69  5495.8 1890.89
  5522.5 1891.43  5565.5 1891.67  5735.5 1893.34  6103.3 1893.92  6127.1 1893.52
#Mann=9,-1,0
  3863.9   0.035       0  4502.7    0.07       0  4952.2    0.16       0
  4955.0    0.07       0  5030.2    0.07       0  5034.2    0.07       0
  5522.5   0.045       0  5565.5    0.07       0  6103.3   0.045       0
Bank Sta=5030.2,5034.2
Exp/Cntr=0.3,0.1

Type RM Length L Ch R = 1,4313,655,655,655
BEGIN DESCRIPTION:
Mapping XS 4007fe39
END DESCRIPTION:
XS GIS Cut Line= 4
      1496143.87      6832869.58      1496508.47      6832041.43
      1496609.16      6831353.93      1496720.03      6830803.07
#Sta/Elev= 30
  4107.9 1897.99  4153.4 1898.25  4227.5 1897.20  4246.7 1896.64  4293.4 1897.00
  4328.2 1895.91  4449.8 1895.85  4467.6 1894.24  4491.0 1893.81  4503.0 1892.80
  4665.3 1889.16  4717.4 1889.21  4830.8 1887.17  4868.3 1887.52  4981.6 1885.87
  4981.9 1885.37  4985.5 1885.37  4985.8 1885.87  5005.6 1887.15  5027.4 1886.15
  5046.5 1886.28  5076.9 1887.72  5117.3 1888.40  5226.9 1888.34  5238.6 1889.14
  5329.5 1888.97  5359.9 1889.82  5731.9 1891.93  6080.9 1893.88  6269.5 1893.27
#Mann=5,-1,0
  4107.9   0.035       0  4227.5    0.07       0  4981.6    0.07       0
  4985.8    0.07       0  5731.9   0.045       0
Bank Sta=4981.6,4985.8
Exp/Cntr=0.3,0.1

Type RM Length L Ch R = 1,3658,636,636,636
BEGIN DESCRIPTION:
Mapping XS fb3d0805
END DESCRIPTION:
XS GIS Cut Line= 3
      1496186.48      6832946.13      1496950.39      6832490.38
      1497006.81      6831123.18
#Sta/Elev= 30
  4101.1 1898.61  4483.8 1896.30  4674.5 1891.42  4690.1 1891.92  4717.3 1890.74
  4748.5 1890.91  4785.5 1889.91  4806.9 1888.52  4812.7 1888.86  4856.3 1885.53
  4871.1 1886.64  4923.6 1885.53  4929.5 1884.80  4945.0 1885.68  5000.8 1884.14
  5001.1 1883.64  5005.3 1884.14  5053.1 1884.70  5083.1 1886.43  5123.1 1887.45
  5225.9 1886.85  5433.4 1888.74  5467.3 1888.06  5663.6 1890.11  5833.7 1890.87
  5873.8 1891.82  5903.8 1891.41  5963.8 1892.69  6072.2 1892.79  6359.0 1893.51
#Mann=4,-1,0
  4101.1    0.07       0  5000.8    0.07       0  5005.3    0.07       0
  6072.2   0.045       0
Bank Sta=5000.8,5005.3
Exp/Cntr=0.3,0.1

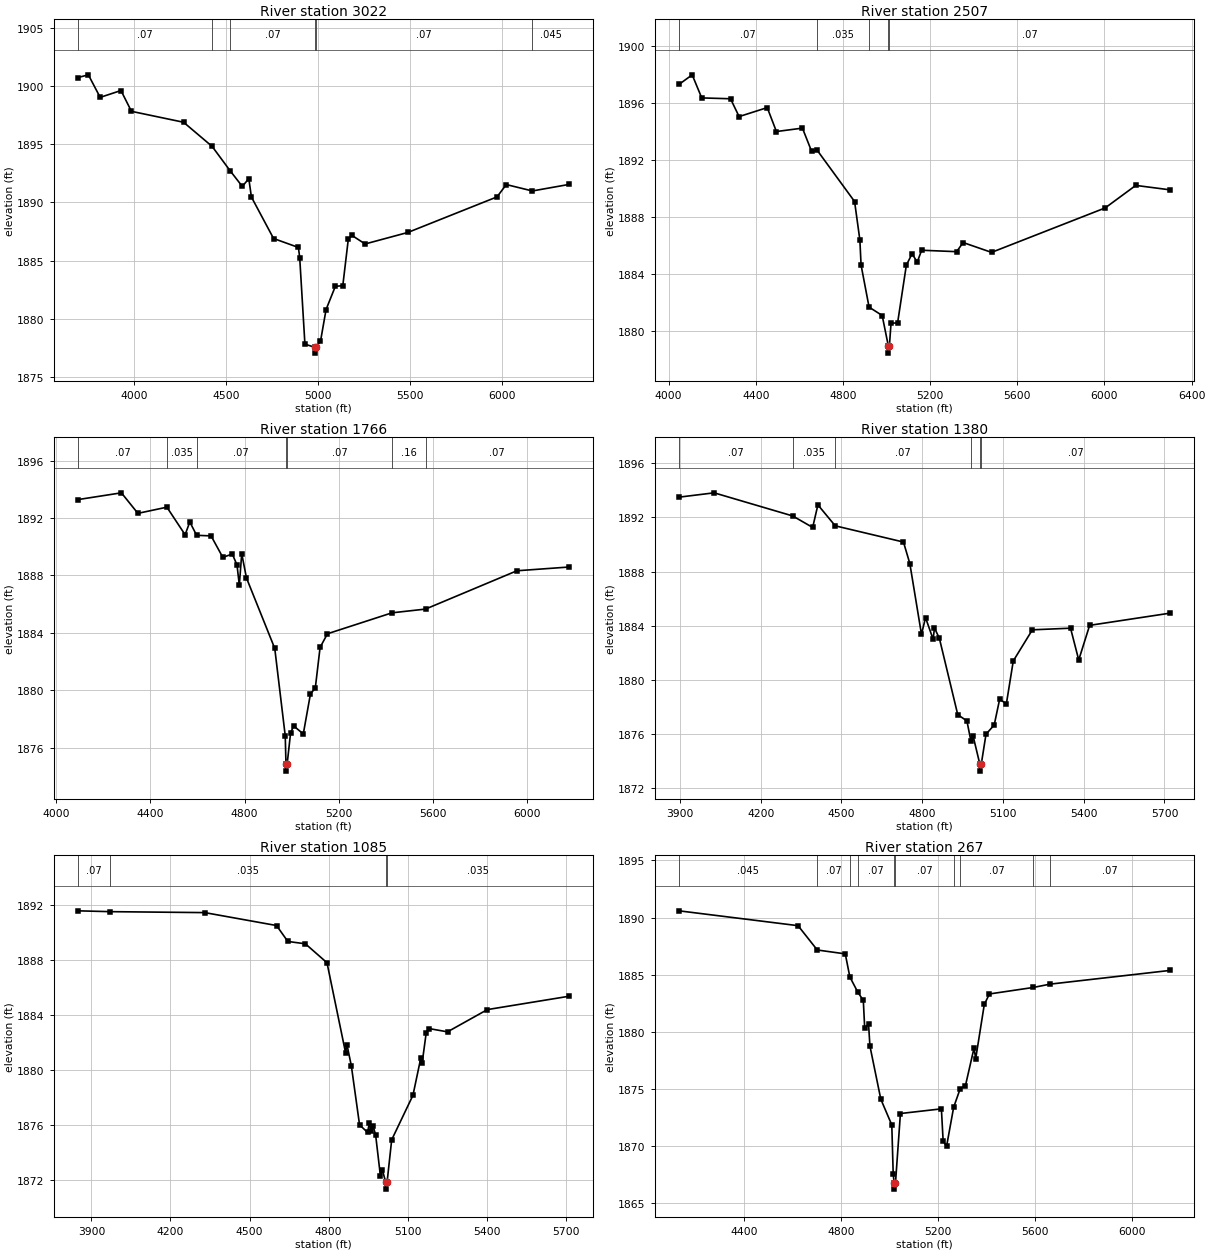
Type RM Length L Ch R = 1,3022,515,515,515
BEGIN DESCRIPTION:
Mapping XS 7095978d
END DESCRIPTION:
XS GIS Cut Line= 3
      1496616.16      6833688.33      1497501.61      6832724.76
      1497674.98      6831381.11
#Sta/Elev= 30
  3697.2 1900.75  3753.0 1900.98  3817.1 1899.04  3929.9 1899.63  3986.7 1897.84
  4269.7 1896.90  4424.7 1894.82  4522.6 1892.72  4588.4 1891.38  4623.6 1892.05
  4637.7 1890.47  4758.0 1886.90  4892.8 1886.13  4899.8 1885.26  4928.1 1877.81
  4982.6 1877.54  4982.9 1877.04  4987.2 1877.54  5012.6 1878.05  5042.9 1880.79
  5093.3 1882.79  5133.6 1882.84  5163.9 1886.89  5184.0 1887.16  5254.6 1886.43
  5486.5 1887.42  5970.5 1890.48  6020.9 1891.54  6162.3 1890.99  6360.6 1891.55
#Mann=6,-1,0
  3697.2    0.07       0  4424.7   0.035       0  4522.6    0.07       0
  4982.6    0.07       0  4987.2    0.07       0  6162.3   0.045       0
Bank Sta=4982.6,4987.2
Exp/Cntr=0.3,0.1

Type RM Length L Ch R = 1,2507,741,741,741
BEGIN DESCRIPTION:
Mapping XS 924448bb
END DESCRIPTION:
XS GIS Cut Line= 3
      1497563.25      6833874.04      1497910.46      6833001.67
      1498005.87      6831691.96
#Sta/Elev= 30
  4047.9 1897.33  4108.2 1898.00  4152.0 1896.38  4284.1 1896.32  4323.5 1895.07
  4452.6 1895.70  4494.6 1894.02  4614.1 1894.26  4656.4 1892.62  4682.0 1892.70
  4853.3 1889.11  4877.6 1886.41  4883.1 1884.65  4919.8 1881.70  4980.0 1881.11
  5008.2 1878.97  5008.5 1878.47  5013.0 1878.97  5020.6 1880.57  5050.7 1880.59
  5090.8 1884.64  5117.0 1885.44  5140.9 1884.86  5161.0 1885.69  5321.4 1885.59
  5351.5 1886.23  5481.8 1885.54  6003.2 1888.66  6143.6 1890.24  6300.0 1889.93
#Mann=5,-1,0
  4047.9    0.07       0  4682.0   0.035       0  4919.8    0.07       0
  5008.2    0.07       0  5013.0    0.07       0
Bank Sta=5008.2,5013
Exp/Cntr=0.3,0.1

Type RM Length L Ch R = 1,1766,386,386,386
BEGIN DESCRIPTION:
Mapping XS a9878d40
END DESCRIPTION:
XS GIS Cut Line= 3
      1498496.40      6833791.56      1498448.65      6832888.82
      1498223.25      6831731.47
#Sta/Elev= 30
  4093.0 1893.29  4276.8 1893.76  4346.9 1892.33  4469.9 1892.76  4547.2 1890.84
  4567.2 1891.73  4596.1 1890.80  4657.4 1890.76  4707.4 1889.26  4747.5 1889.50
  4767.5 1888.73  4777.3 1887.33  4787.5 1889.52  4807.6 1887.83  4927.7 1882.92
  4972.2 1876.83  4975.3 1874.87  4975.7 1874.37  4980.3 1874.87  4994.9 1877.03
  5008.0 1877.52  5048.8 1876.96  5079.3 1879.76  5099.7 1880.15  5120.1 1882.99
  5151.3 1883.94  5425.4 1885.40  5567.6 1885.66  5955.5 1888.33  6176.1 1888.59
#Mann=7,-1,0
  4093.0    0.07       0  4469.9   0.035       0  4596.1    0.07       0
  4975.3    0.07       0  4980.3    0.07       0  5425.4    0.16       0
  5567.6    0.07       0
Bank Sta=4975.3,4980.3
Exp/Cntr=0.3,0.1

Type RM Length L Ch R = 1,1380,295,295,295
BEGIN DESCRIPTION:
Mapping XS ec247d55
END DESCRIPTION:
XS GIS Cut Line= 3
      1498561.51      6833861.01      1498795.88      6832823.72
      1498916.55      6832073.81
#Sta/Elev= 30
  3897.0 1893.50  4027.3 1893.82  4319.1 1892.11  4393.3 1891.26  4412.7 1892.93
  4477.1 1891.38  4730.5 1890.18  4754.2 1888.59  4797.4 1883.36  4812.5 1884.59
  4840.6 1882.99  4845.7 1883.82  4863.8 1883.07  4932.1 1877.42  4966.2 1876.95
  4981.0 1875.47  4989.0 1875.85  5014.4 1873.74  5014.7 1873.24  5019.4 1873.74
  5037.1 1875.97  5067.5 1876.65  5087.8 1878.56  5112.7 1878.21  5138.4 1881.39
  5209.3 1883.69  5351.1 1883.81  5381.5 1881.46  5422.0 1884.02  5720.0 1884.92
#Mann=6,-1,0
  3897.0    0.07       0  4319.1   0.035       0  4477.1    0.07       0
  4981.0    0.16       0  5014.4    0.07       0  5019.4    0.07       0
Bank Sta=5014.4,5019.4
Exp/Cntr=0.3,0.1

Type RM Length L Ch R = 1,1085,818,818,818
BEGIN DESCRIPTION:
Mapping XS 80eeb606
END DESCRIPTION:
XS GIS Cut Line= 4
      1498791.53      6833808.98      1499049.46      6832687.46
      1499113.51      6832207.12      1499178.12      6831988.46
#Sta/Elev= 30
  3849.2 1891.59  3970.9 1891.53  4330.3 1891.46  4602.6 1890.52  4645.5 1889.36
  4712.1 1889.19  4794.2 1887.81  4864.7 1881.26  4869.9 1881.85  4886.6 1880.31
  4917.8 1876.01  4948.1 1875.46  4955.5 1876.18  4960.7 1875.54  4968.7 1875.96
  4978.9 1875.26  4997.2 1872.26  5004.3 1872.74  5017.0 1871.83  5017.4 1871.33
  5022.3 1871.83  5039.8 1874.92  5120.5 1878.16  5150.6 1880.90  5155.6 1880.54
  5171.0 1882.73  5181.0 1883.02  5251.7 1882.78  5403.0 1884.40  5712.6 1885.37
#Mann=4,-1,0
  3849.2    0.07       0  3970.9   0.035       0  5017.0   0.035       0
  5022.3   0.035       0
Bank Sta=5017,5022.3
Exp/Cntr=0.3,0.1

Type RM Length L Ch R = 1,267,0,0,0
BEGIN DESCRIPTION:
MULBERRY CREEK TRIBUTARY 20 1.0
END DESCRIPTION:
XS GIS Cut Line= 4
      1499342.69      6833576.30      1499669.09      6833093.64
      1499901.73      6832694.34      1499193.38      6832017.24
#Sta/Elev= 30
  4130.6 1890.59  4621.5 1889.29  4700.8 1887.16  4816.3 1886.82  4835.2 1884.80
  4868.4 1883.45  4890.7 1882.75  4896.5 1880.29  4912.2 1880.71  4918.0 1878.75
  4962.8 1874.10  5008.2 1871.84  5014.0 1867.56  5018.0 1866.72  5018.4 1866.22
  5023.3 1866.72  5043.8 1872.84  5212.8 1873.25  5220.0 1870.44  5234.2 1869.97
  5263.4 1873.39  5290.5 1875.02  5311.8 1875.26  5347.4 1878.57  5354.3 1877.64
  5389.8 1882.39  5410.9 1883.31  5592.1 1883.88  5660.9 1884.17  6155.3 1885.37
#Mann=10,-1,0
  4130.6   0.045       0  4700.8    0.07       0  4835.2   0.035       0
  4868.4    0.07       0  5018.0    0.07       0  5023.3    0.07       0
  5263.4    0.16       0  5290.5    0.07       0  5592.1    0.16       0
  5660.9    0.07       0
Bank Sta=5018,5023.3
Exp/Cntr=0.3,0.1

Chan Stop Cuts=-1