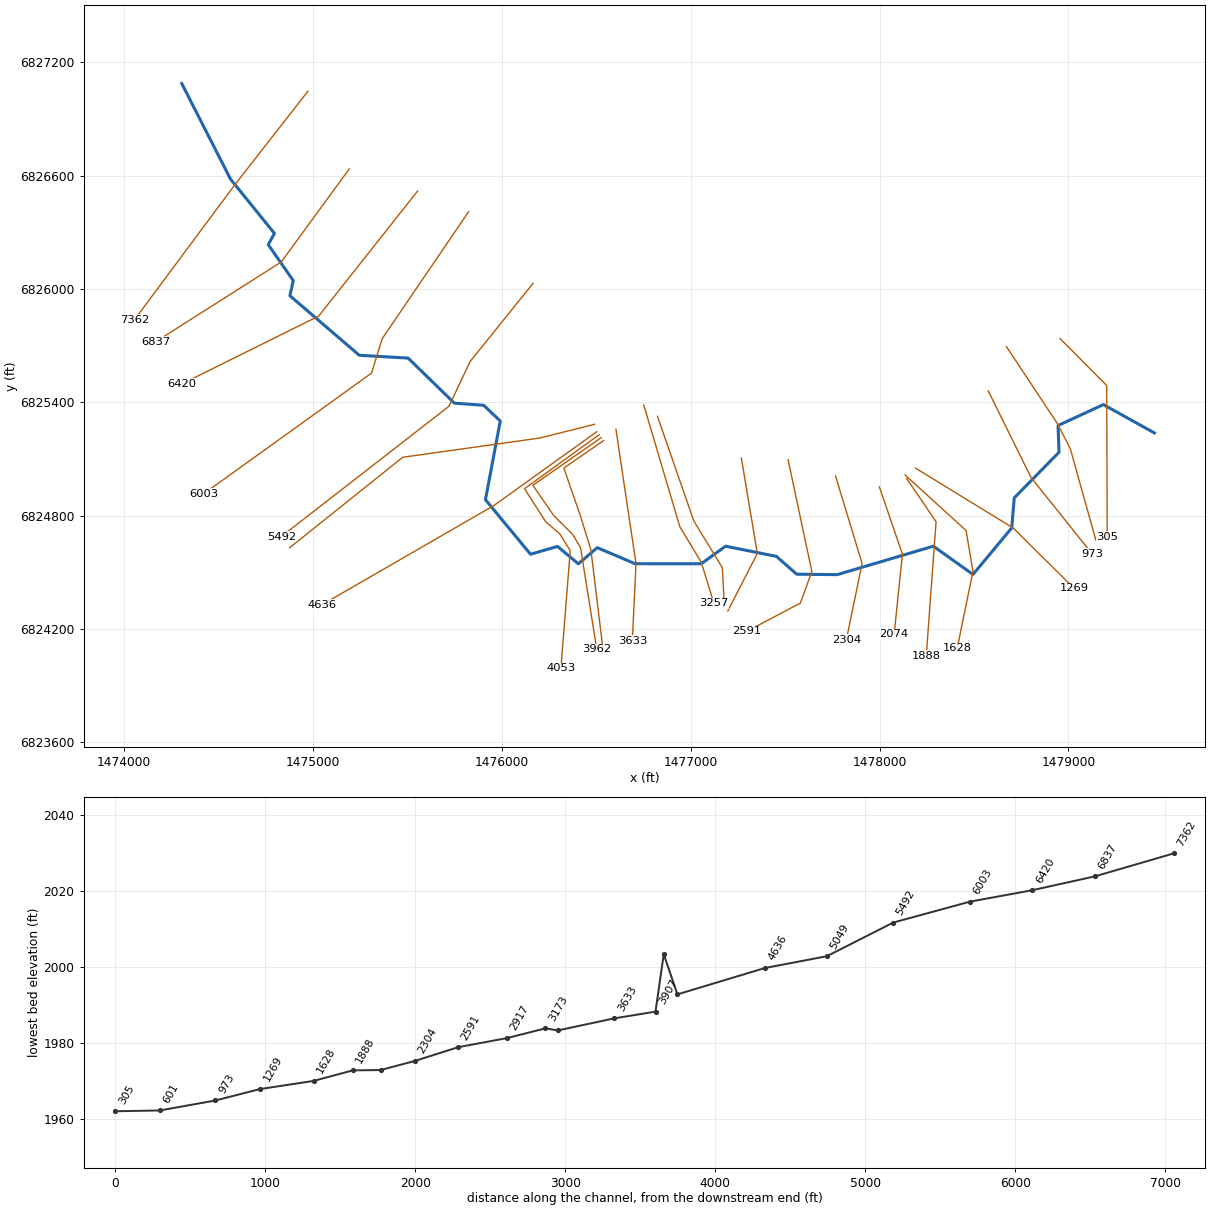
--- MULBERRY CREEK TRIBUTARY 21.prj (project) ---

Proj Title=MULBERRY CREEK TRIBUTARY 21 Base Level Engineering
Current Plan=p01
Default Exp/Contr=0.3,0.1
English Units
Geom File=g01
Flow File=f01
Plan File=p01
BEGIN DESCRIPTION:
MULBERRY CREEK TRIBUTARY 21
END DESCRIPTION:

--- MULBERRY CREEK TRIBUTARY 21.p01 (plan) ---

Plan Title=Multiple Run
Short Identifier=Multiple
Geom File=g01
Flow File=f01
Subcritical Flow
K Sum by GR= 0
Std Step Tol= 0.01
Critical Tol= 0.01
Num of Std Step Trials= 20
Max Error Tol= 0.3
Flow Tol Ratio= 0.001
Split Flow NTrial= 30
Split Flow Tol= 0.02
Split Flow Ratio= 0.02
Log Output Level= 0
Friction Slope Method= 1
Unsteady Friction Slope Method= 2
Unsteady Bridges Friction Slope Method= 1
Parabolic Critical Depth
Global Vel Dist=  1 , 1 , 1
Global Log Level= 0
CheckData=True
Encroach Param= -1, 0, 0, 0
BEGIN DESCRIPTION:
Multiple Run
END DESCRIPTION:

--- MULBERRY CREEK TRIBUTARY 21.f01 (steady flow) ---

Flow Title=Multiple
Number of Profiles=7
Profile Names=10-year,25-year,50-year,1pct_min,100-year,1pct_plu,500-year
River Rch & RM= MULBERRY CREEK T,Reach-1,7362
     570     848    1095     704    1404    2802    2336
River Rch & RM= MULBERRY CREEK T,Reach-1,3257
     713    1072    1394     901    1798    3587    3027
Boundary for River Rch & Prof#=MULBERRY CREEK T,Reach-1,1
Up Type=0
Dn Type=3
Dn Slope=0.005
Boundary for River Rch & Prof#=MULBERRY CREEK T,Reach-1,2
Up Type=0
Dn Type=3
Dn Slope=0.005
Boundary for River Rch & Prof#=MULBERRY CREEK T,Reach-1,3
Up Type=0
Dn Type=3
Dn Slope=0.005
Boundary for River Rch & Prof#=MULBERRY CREEK T,Reach-1,4
Up Type=0
Dn Type=3
Dn Slope=0.005
Boundary for River Rch & Prof#=MULBERRY CREEK T,Reach-1,5
Up Type=0
Dn Type=3
Dn Slope=0.005
Boundary for River Rch & Prof#=MULBERRY CREEK T,Reach-1,6
Up Type=0
Dn Type=3
Dn Slope=0.005
Boundary for River Rch & Prof#=MULBERRY CREEK T,Reach-1,7
Up Type=0
Dn Type=3
Dn Slope=0.005

--- MULBERRY CREEK TRIBUTARY 21.g01 (geometry) ---

Geom Title=Existing Conditions

River Reach=MULBERRY CREEK T,Reach-1
Reach XY= 30
      1474305.00      6827088.00      1474563.16      6826581.95
      1474795.70      6826294.67      1474763.02      6826234.67
      1474895.41      6826044.55      1474877.49      6825964.62
      1475245.00      6825649.24      1475503.44      6825634.24
      1475748.53      6825395.70      1475903.56      6825384.46
      1475991.37      6825301.36      1475913.01      6824884.67
      1476151.58      6824595.80      1476294.52      6824637.05
      1476405.00      6824545.11      1476504.90      6824630.66
      1476705.00      6824545.56      1477055.10      6824545.33
      1477184.79      6824638.35      1477453.53      6824584.45
      1477560.86      6824490.07      1477775.15      6824487.64
      1478284.87      6824638.40      1478494.37      6824488.54
      1478699.60      6824735.32      1478712.82      6824894.19
      1478949.88      6825135.71      1478944.59      6825277.23
      1479184.90      6825388.11      1479455.00      6825238.00

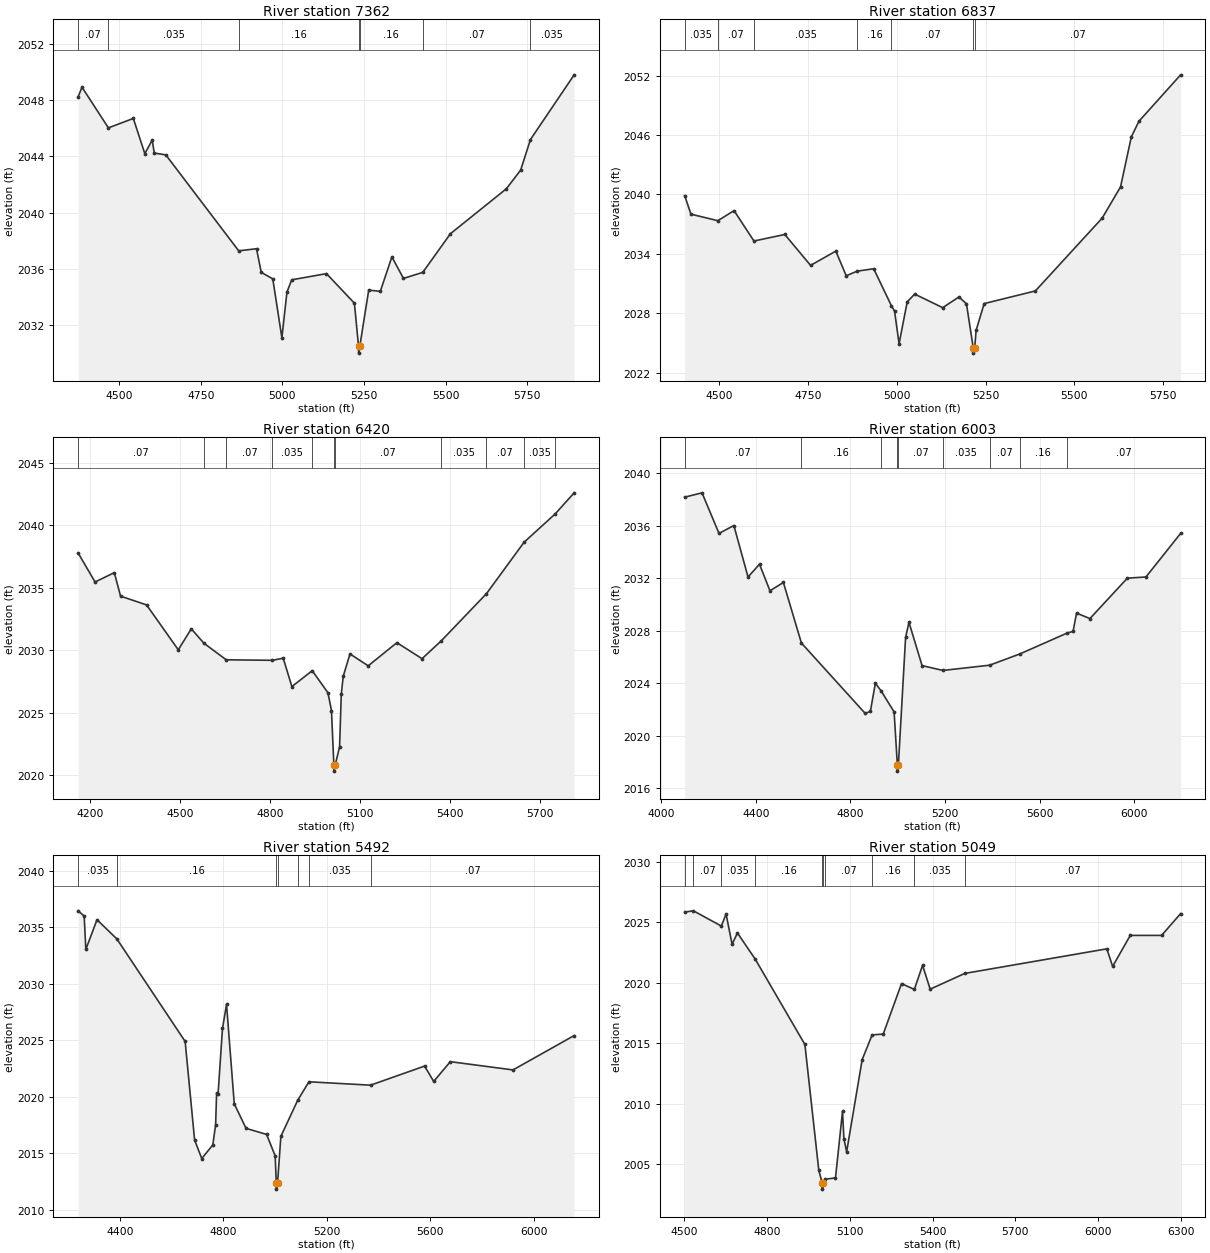
Type RM Length L Ch R = 1,7362,525,525,525
BEGIN DESCRIPTION:
MULBERRY CREEK TRIBUTARY 21 17.0
END DESCRIPTION:
XS GIS Cut Line= 3
      1474972.85      6827047.17      1474588.04      6826554.55
      1474054.98      6825837.98
#Sta/Elev= 30
  4374.9 2048.24  4386.5 2048.91  4467.3 2046.02  4543.6 2046.69  4578.8 2044.19
  4601.4 2045.15  4607.8 2044.23  4643.1 2044.10  4866.2 2037.28  4920.7 2037.43
  4935.2 2035.75  4970.5 2035.29  4998.4 2031.10  5013.9 2034.35  5028.5 2035.22
  5134.9 2035.66  5220.4 2033.56  5233.0 2030.51  5233.3 2030.01  5237.0 2030.51
  5264.2 2034.49  5299.7 2034.40  5335.1 2036.85  5370.6 2035.32  5429.7 2035.75
  5514.5 2038.50  5685.5 2041.69  5729.4 2043.02  5759.3 2045.19  5893.1 2049.79
#Mann=7,-1,0
  4374.9    0.07       0  4467.3   0.035       0  4866.2    0.16       0
  5233.0    0.07       0  5237.0    0.16       0  5429.7    0.07       0
  5759.3   0.035       0
Bank Sta=5233,5237
Exp/Cntr=0.3,0.1

Type RM Length L Ch R = 1,6837,417,417,417
BEGIN DESCRIPTION:
Mapping XS 2eeb291a
END DESCRIPTION:
XS GIS Cut Line= 3
      1475191.59      6826635.70      1474832.22      6826143.52
      1474168.12      6825721.62
#Sta/Elev= 30
  4402.8 2039.87  4420.5 2038.00  4496.2 2037.34  4541.8 2038.36  4597.8 2035.29
  4684.7 2035.95  4757.2 2032.83  4828.3 2034.27  4857.6 2031.78  4888.7 2032.25
  4934.9 2032.49  4985.0 2028.74  4993.6 2028.22  5006.4 2024.92  5029.3 2029.15
  5050.4 2029.93  5129.2 2028.56  5174.8 2029.64  5196.1 2028.95  5215.3 2024.47
  5215.5 2023.97  5219.3 2024.47  5223.2 2026.26  5245.9 2028.97  5390.1 2030.25
  5578.1 2037.60  5629.8 2040.75  5660.2 2045.80  5681.4 2047.37  5799.0 2052.07
#Mann=7,-1,0
  4402.8   0.035       0  4496.2    0.07       0  4597.8   0.035       0
  4888.7    0.16       0  4985.0    0.07       0  5215.3    0.07       0
  5219.3    0.07       0
Bank Sta=5215.3,5219.3
Exp/Cntr=0.3,0.1

Type RM Length L Ch R = 1,6420,417,417,417
BEGIN DESCRIPTION:
Mapping XS f9c70269
END DESCRIPTION:
XS GIS Cut Line= 3
      1475553.56      6826518.51      1475030.13      6825857.06
      1474306.22      6825497.70
#Sta/Elev= 30
  4161.0 2037.76  4217.1 2035.45  4281.2 2036.20  4302.0 2034.32  4388.6 2033.62
  4494.3 2030.03  4537.6 2031.71  4579.4 2030.56  4654.0 2029.23  4808.0 2029.19
  4843.7 2029.36  4872.6 2027.09  4940.5 2028.36  4992.8 2026.59  5004.5 2025.17
  5012.4 2020.83  5012.7 2020.33  5017.0 2020.83  5031.5 2022.28  5037.1 2026.47
  5043.7 2027.92  5066.1 2029.70  5126.8 2028.75  5222.4 2030.60  5306.0 2029.32
  5370.3 2030.75  5520.7 2034.52  5645.9 2038.63  5749.3 2040.89  5812.7 2042.58
#Mann=11,-1,0
  4161.0    0.07       0  4579.4   0.035       0  4654.0    0.07       0
  4808.0   0.035       0  4940.5    0.07       0  5012.4    0.07       0
  5017.0    0.07       0  5370.3   0.035       0  5520.7    0.07       0
  5645.9   0.035       0  5749.3    0.07       0
Bank Sta=5012.4,5017
Exp/Cntr=0.3,0.1

Type RM Length L Ch R = 1,6003,511,511,511
BEGIN DESCRIPTION:
Mapping XS b4d91470
END DESCRIPTION:
XS GIS Cut Line= 4
      1475824.00      6826409.61      1475366.07      6825736.83
      1475309.65      6825554.54      1474422.03      6824916.50
#Sta/Elev= 30
  4098.9 2038.18  4172.2 2038.51  4244.1 2035.42  4307.0 2036.02  4366.8 2032.10
  4415.4 2033.07  4459.6 2031.05  4516.5 2031.68  4592.6 2027.07  4862.9 2021.70
  4884.5 2021.87  4905.5 2024.01  4929.8 2023.42  4984.8 2021.82  4998.4 2017.81
  4998.7 2017.31  5003.0 2017.81  5033.3 2027.49  5047.6 2028.65  5103.0 2025.35
  5191.2 2024.98  5389.2 2025.38  5517.0 2026.24  5714.6 2027.81  5741.8 2027.96
  5756.5 2029.35  5813.0 2028.93  5971.4 2032.01  6050.0 2032.10  6196.7 2035.42
#Mann=9,-1,0
  4098.9    0.07       0  4592.6    0.16       0  4929.8    0.07       0
  4998.4    0.07       0  5003.0    0.07       0  5191.2   0.035       0
  5389.2    0.07       0  5517.0    0.16       0  5714.6    0.07       0
Bank Sta=4998.4,5003
Exp/Cntr=0.3,0.1

Type RM Length L Ch R = 1,5492,443,443,443
BEGIN DESCRIPTION:
Mapping XS 485c0d61
END DESCRIPTION:
XS GIS Cut Line= 4
      1476165.09      6826030.20      1475831.78      6825616.17
      1475719.80      6825379.19      1474831.75      6824689.07
#Sta/Elev= 30
  4238.6 2036.44  4261.7 2035.97  4268.1 2033.03  4311.3 2035.65  4387.9 2033.96
  4652.2 2024.88  4688.8 2016.16  4716.4 2014.52  4759.2 2015.72  4770.1 2017.50
  4774.0 2020.34  4779.5 2020.22  4796.7 2026.03  4812.3 2028.16  4842.2 2019.36
  4887.8 2017.19  4967.2 2016.65  5000.4 2014.76  5004.8 2012.31  5005.1 2011.81
  5009.5 2012.31  5022.5 2016.48  5087.5 2019.67  5131.0 2021.31  5369.3 2021.01
  5578.3 2022.70  5613.6 2021.34  5677.9 2023.09  5920.4 2022.36  6156.9 2025.40
#Mann=7,-1,0
  4238.6   0.035       0  4387.9    0.16       0  5004.8    0.07       0
  5009.5    0.16       0  5087.5    0.07       0  5131.0   0.035       0
  5369.3    0.07       0
Bank Sta=5004.8,5009.5
Exp/Cntr=0.3,0.1

Type RM Length L Ch R = 1,5049,413,413,413
BEGIN DESCRIPTION:
Mapping XS 25422dc7
END DESCRIPTION:
XS GIS Cut Line= 4
      1476490.66      6825283.71      1476198.97      6825210.79
      1475475.01      6825109.23      1474876.02      6824630.04
#Sta/Elev= 30
  4501.0 2025.84  4532.8 2025.94  4634.1 2024.68  4651.1 2025.68  4672.9 2023.18
  4692.4 2024.11  4756.8 2021.95  4937.0 2014.90  4987.4 2004.52  4999.7 2003.45
  5000.1 2002.95  5004.5 2003.45  5011.7 2003.77  5048.0 2003.88  5073.5 2009.37
  5078.5 2007.13  5088.4 2006.03  5144.8 2013.65  5180.9 2015.69  5221.2 2015.76
  5287.5 2019.93  5334.0 2019.45  5363.9 2021.44  5391.4 2019.47  5517.1 2020.77
  6032.2 2022.80  6053.2 2021.35  6117.2 2023.91  6230.8 2023.91  6299.8 2025.71
#Mann=10,-1,0
  4501.0   0.035       0  4532.8    0.07       0  4634.1   0.035       0
  4756.8    0.16       0  4999.7    0.07       0  5004.5    0.16       0
  5011.7    0.07       0  5180.9    0.16       0  5334.0   0.035       0
  5517.1    0.07       0
Bank Sta=4999.7,5004.5
Exp/Cntr=0.3,0.1

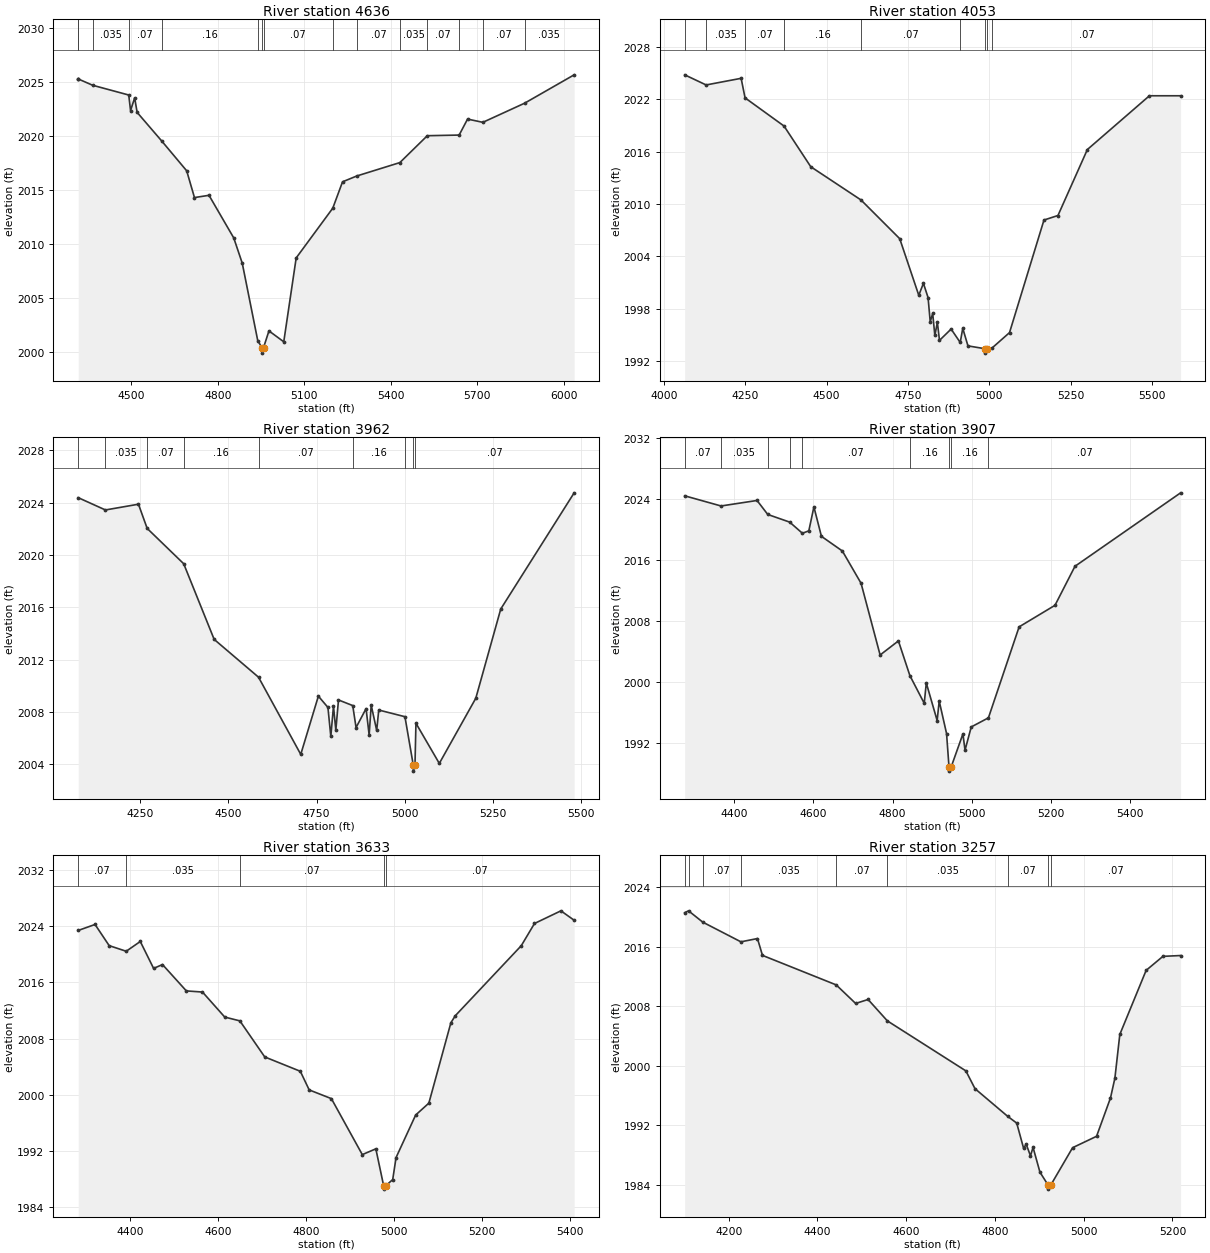
Type RM Length L Ch R = 1,4636,583,583,583
BEGIN DESCRIPTION:
Mapping XS 5fa56df6
END DESCRIPTION:
XS GIS Cut Line= 3
      1476502.57      6825244.64      1475958.30      6824854.02
      1475048.41      6824328.88
#Sta/Elev= 30
  4315.6 2025.27  4316.2 2025.24  4366.1 2024.66  4490.9 2023.76  4497.2 2022.32
  4511.4 2023.50  4520.0 2022.15  4605.0 2019.51  4691.9 2016.74  4718.9 2014.26
  4769.3 2014.47  4855.2 2010.52  4884.7 2008.18  4938.6 2000.99  4953.4 2000.35
  4953.8 1999.85  4958.4 2000.35  4977.3 2001.91  5028.7 2000.90  5071.8 2008.67
  5198.8 2013.28  5232.6 2015.72  5282.1 2016.26  5431.4 2017.50  5526.7 2019.99
  5637.1 2020.05  5666.3 2021.53  5719.4 2021.23  5864.1 2023.00  6036.1 2025.63
#Mann=15,-1,0
  4315.6   0.035       0  4316.2    0.07       0  4366.1   0.035       0
  4490.9    0.07       0  4605.0    0.16       0  4938.6    0.07       0
  4953.4    0.07       0  4958.4    0.07       0  5198.8    0.16       0
  5282.1    0.07       0  5431.4   0.035       0  5526.7    0.07       0
  5637.1   0.035       0  5719.4    0.07       0  5864.1   0.035       0
Bank Sta=4953.4,4958.4
Exp/Cntr=0.3,0.1

Type RM Length L Ch R = 1,4053,91,91,91
BEGIN DESCRIPTION:
Mapping XS 9f9a2025
END DESCRIPTION:
XS GIS Cut Line= 6
      1476515.59      6825229.02      1476119.76      6824942.56
      1476231.74      6824768.08      1476307.26      6824702.98
      1476361.95      6824614.44      1476312.51      6823992.53
#Sta/Elev= 30
  4064.0 2024.81  4129.9 2023.65  4237.5 2024.41  4249.6 2022.17  4369.4 2018.94
  4451.5 2014.28  4605.9 2010.47  4725.0 2006.03  4783.5 1999.55  4797.8 2000.92
  4812.1 1999.28  4818.7 1996.51  4826.3 1997.47  4832.9 1994.94  4840.6 1996.45
  4847.2 1994.38  4882.9 1995.68  4910.9 1994.14  4918.7 1995.76  4934.7 1993.75
  4987.9 1993.42  4988.3 1992.92  4993.0 1993.42  5009.1 1993.52  5062.4 1995.27
  5168.3 2008.17  5211.3 2008.69  5301.7 2016.25  5492.4 2022.41  5588.3 2022.41
#Mann=9,-1,0
  4064.0    0.07       0  4129.9   0.035       0  4249.6    0.07       0
  4369.4    0.16       0  4605.9    0.07       0  4910.9    0.16       0
  4987.9    0.07       0  4993.0    0.16       0  5009.1    0.07       0
Bank Sta=4987.9,4993
Exp/Cntr=0.3,0.1

Type RM Length L Ch R = 1,3962,55,55,55
BEGIN DESCRIPTION:
Mapping XS de1c0c1c
END DESCRIPTION:
XS GIS Cut Line= 6
      1476526.02      6825213.40      1476164.03      6824960.79
      1476273.41      6824801.94      1476374.97      6824700.37
      1476416.64      6824630.06      1476502.44      6824091.99
#Sta/Elev= 30
  4074.3 2024.39  4151.4 2023.45  4245.0 2023.89  4269.7 2022.04  4373.2 2019.34
  4459.5 2013.56  4585.2 2010.67  4704.9 2004.77  4754.8 2009.22  4781.9 2008.36
  4790.1 2006.14  4797.6 2008.46  4804.3 2006.62  4811.8 2008.93  4852.2 2008.50
  4861.6 2006.82  4890.0 2008.27  4898.7 2006.25  4904.5 2008.53  4920.1 2006.60
  4925.9 2008.16  5000.1 2007.65  5023.5 2003.99  5023.9 2003.49  5028.6 2003.99
  5031.3 2007.15  5097.5 2004.08  5200.9 2009.06  5271.6 2015.88  5479.6 2024.76
#Mann=9,-1,0
  4074.3    0.07       0  4151.4   0.035       0  4269.7    0.07       0
  4373.2    0.16       0  4585.2    0.07       0  4852.2    0.16       0
  5000.1    0.07       0  5023.5    0.07       0  5028.6    0.07       0
Bank Sta=5023.5,5028.6
Exp/Cntr=0.3,0.1

Type RM Length L Ch R = 1,3907,274,274,274
BEGIN DESCRIPTION:
Mapping XS bc1936cf
END DESCRIPTION:
XS GIS Cut Line= 5
      1476539.00      6825197.75      1476328.09      6825051.94
      1476414.03      6824804.54      1476471.32      6824619.64
      1476536.43      6824083.15
#Sta/Elev= 30
  4275.0 2024.39  4366.8 2023.06  4457.7 2023.78  4484.8 2021.95  4540.1 2020.95
  4572.3 2019.49  4588.5 2019.81  4601.3 2022.94  4620.3 2019.09  4673.2 2017.17
  4720.4 2012.95  4768.5 2003.57  4814.7 2005.41  4843.7 2000.87  4879.9 1997.25
  4885.1 1999.91  4912.5 1995.00  4917.7 1997.55  4936.3 1993.29  4942.5 1988.88
  4942.9 1988.38  4947.6 1988.88  4977.6 1993.25  4982.9 1991.12  4998.6 1994.16
  5042.0 1995.35  5119.5 2007.25  5210.1 2010.07  5260.5 2015.17  5527.3 2024.78
#Mann=9,-1,0
  4275.0    0.07       0  4366.8   0.035       0  4484.8    0.07       0
  4540.1    0.16       0  4572.3    0.07       0  4843.7    0.16       0
  4942.5    0.07       0  4947.6    0.16       0  5042.0    0.07       0
Bank Sta=4942.5,4947.6
Exp/Cntr=0.3,0.1

Type RM Length L Ch R = 1,3633,376,376,376
BEGIN DESCRIPTION:
Mapping XS 16eb85b4
END DESCRIPTION:
XS GIS Cut Line= 3
      1476603.85      6825257.62      1476710.18      6824545.86
      1476690.65      6824137.88
#Sta/Elev= 30
  4281.3 2023.40  4319.6 2024.25  4351.7 2021.24  4390.5 2020.44  4422.5 2021.83
  4452.8 2018.00  4473.0 2018.55  4527.3 2014.80  4564.0 2014.64  4614.6 2011.08
  4649.0 2010.54  4705.6 2005.41  4786.5 2003.37  4806.7 2000.72  4857.2 1999.48
  4927.5 1991.52  4958.3 1992.34  4976.0 1987.11  4976.4 1986.61  4981.1 1987.11
  4996.7 1987.97  5004.3 1991.10  5048.9 1997.15  5078.9 1998.84  5129.0 2010.27
  5139.0 2011.27  5289.1 2021.23  5319.2 2024.39  5379.3 2026.19  5409.4 2024.85
#Mann=5,-1,0
  4281.3    0.07       0  4390.5   0.035       0  4649.0    0.07       0
  4976.0    0.07       0  4981.1    0.07       0
Bank Sta=4976,4981.1
Exp/Cntr=0.3,0.1

Type RM Length L Ch R = 1,3257,84,84,84
BEGIN DESCRIPTION:
Mapping XS ffd4ecdb
END DESCRIPTION:
XS GIS Cut Line= 4
      1476751.42      6825385.27      1476942.39      6824740.74
      1477055.24      6824554.11      1477122.50      6824337.12
#Sta/Elev= 30
  4100.9 2020.55  4109.6 2020.80  4141.7 2019.28  4227.6 2016.64  4264.9 2017.08
  4276.2 2014.82  4442.3 2010.86  4486.1 2008.37  4514.2 2008.90  4557.6 2006.03
  4734.5 1999.32  4755.1 1996.93  4828.5 1993.23  4849.1 1992.31  4864.6 1988.93
  4870.4 1989.48  4880.1 1987.92  4885.9 1989.05  4901.4 1985.73  4920.2 1983.95
  4920.6 1983.45  4925.4 1983.95  4975.0 1989.01  5029.0 1990.54  5060.4 1995.69
  5070.3 1998.34  5081.4 2004.21  5140.7 2012.81  5178.5 2014.69  5218.4 2014.80
#Mann=9,-1,0
  4100.9    0.07       0  4109.6   0.035       0  4141.7    0.07       0
  4227.6   0.035       0  4442.3    0.07       0  4557.6   0.035       0
  4828.5    0.07       0  4920.2    0.07       0  4925.4    0.07       0
Bank Sta=4920.2,4925.4
Exp/Cntr=0.3,0.1

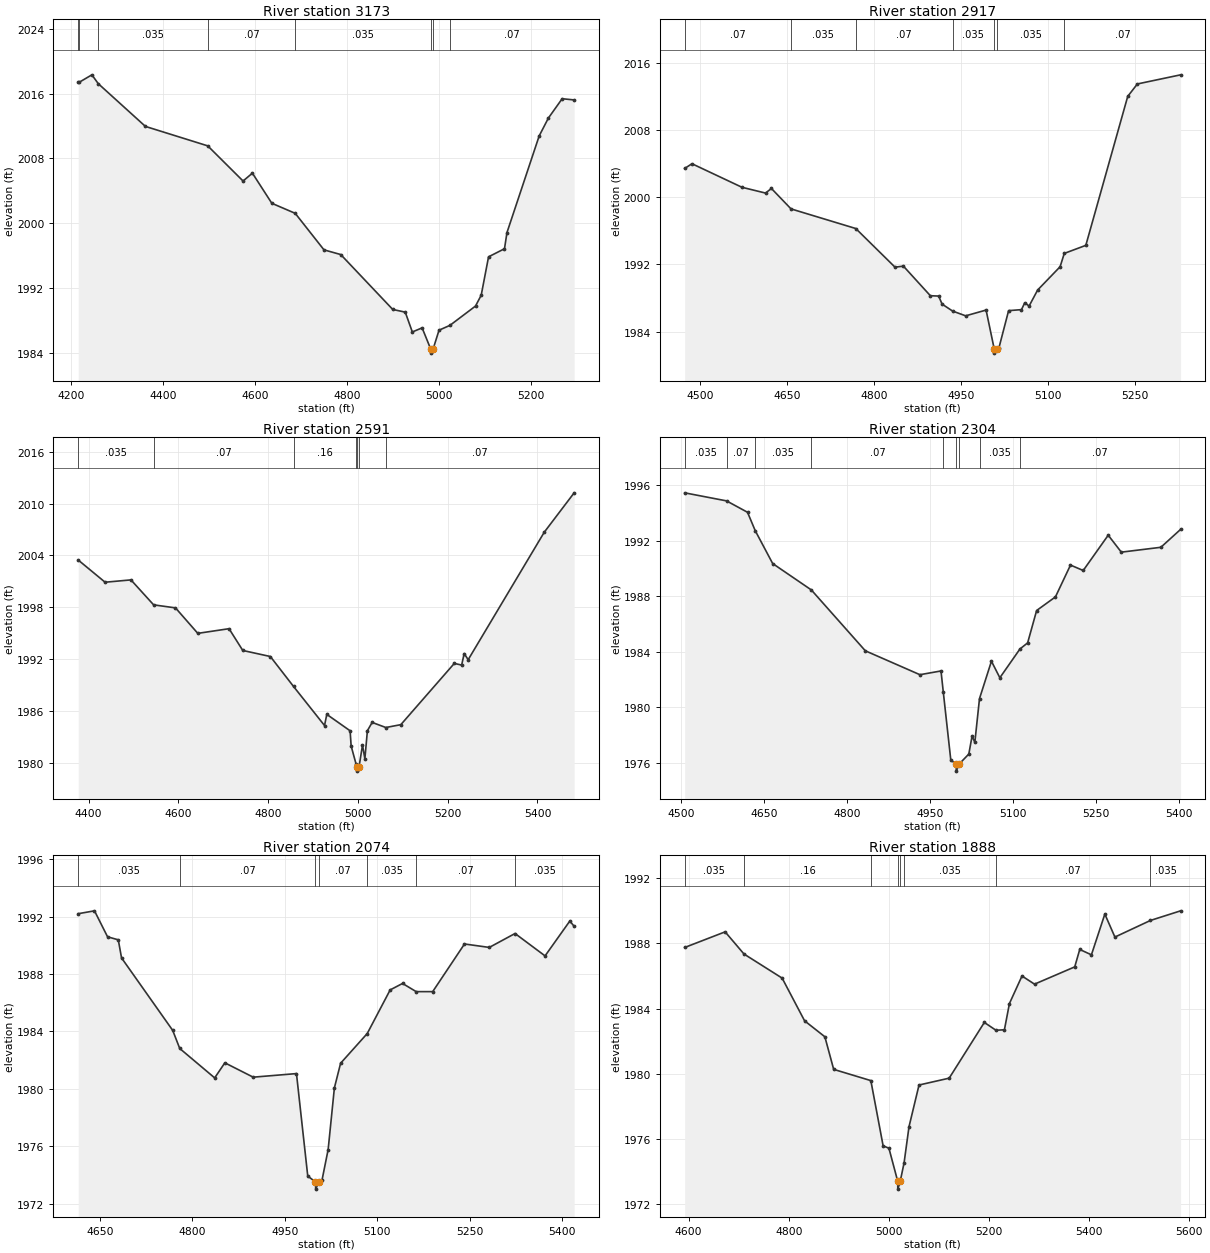
Type RM Length L Ch R = 1,3173,256,256,256
BEGIN DESCRIPTION:
Mapping XS 02510e33
END DESCRIPTION:
XS GIS Cut Line= 4
      1476823.68      6825326.11      1477016.38      6824771.44
      1477167.42      6824524.04      1477177.78      6824321.96
#Sta/Elev= 30
  4215.2 2017.41  4217.0 2017.40  4245.0 2018.33  4258.8 2017.24  4361.5 2011.96
  4497.1 2009.56  4574.0 2005.22  4594.3 2006.19  4636.6 2002.47  4687.5 2001.23
  4750.1 1996.72  4786.6 1996.14  4899.8 1989.36  4927.0 1989.03  4942.4 1986.58
  4963.7 1987.09  4982.4 1984.47  4982.8 1983.97  4987.6 1984.47  5000.5 1986.80
  5024.3 1987.40  5079.9 1989.78  5092.3 1991.12  5108.3 1995.86  5143.0 1996.86
  5148.4 1998.86  5218.5 2010.79  5238.5 2012.99  5268.5 2015.38  5294.6 2015.23
#Mann=8,-1,0
  4215.2   0.035       0  4217.0    0.07       0  4258.8   0.035       0
  4497.1    0.07       0  4687.5   0.035       0  4982.4   0.035       0
  4987.6   0.035       0  5024.3    0.07       0
Bank Sta=4982.4,4987.6
Exp/Cntr=0.3,0.1

Type RM Length L Ch R = 1,2917,326,326,326
BEGIN DESCRIPTION:
Mapping XS a2aa74a1
END DESCRIPTION:
XS GIS Cut Line= 3
      1477267.90      6825105.35      1477352.54      6824599.68
      1477196.32      6824295.90
#Sta/Elev= 30
  4474.1 2003.46  4486.7 2004.02  4572.8 2001.21  4613.4 2000.52  4623.5 2001.07
  4657.3 1998.63  4768.8 1996.29  4836.4 1991.68  4850.9 1991.80  4897.3 1988.27
  4911.6 1988.23  4917.5 1987.27  4935.6 1986.44  4958.1 1985.87  4993.3 1986.56
  5007.3 1981.92  5007.7 1981.42  5012.5 1981.92  5015.5 1982.07  5032.1 1986.49
  5054.3 1986.61  5059.9 1987.43  5067.4 1987.04  5082.1 1988.95  5120.8 1991.73
  5128.0 1993.32  5165.1 1994.28  5237.3 2012.06  5253.9 2013.54  5328.4 2014.63
#Mann=7,-1,0
  4474.1    0.07       0  4657.3   0.035       0  4768.8    0.07       0
  4935.6   0.035       0  5007.3   0.035       0  5012.5   0.035       0
  5128.0    0.07       0
Bank Sta=5007.3,5012.5
Exp/Cntr=0.3,0.1

Type RM Length L Ch R = 1,2591,287,287,287
BEGIN DESCRIPTION:
Mapping XS 869f4030
END DESCRIPTION:
XS GIS Cut Line= 4
      1477515.31      6825096.64      1477641.17      6824504.19
      1477580.41      6824337.09      1477296.11      6824187.35
#Sta/Elev= 30
  4376.9 2003.46  4436.8 2000.89  4494.4 2001.16  4544.9 1998.27  4593.6 1997.92
  4643.3 1994.97  4712.9 1995.51  4743.5 1992.99  4804.9 1992.29  4856.6 1988.82
  4925.6 1984.30  4930.7 1985.59  4982.6 1983.69  4984.9 1981.93  4995.6 1979.89
  4997.2 1979.52  4997.6 1979.02  5002.5 1979.52  5010.2 1982.03  5015.5 1980.45
  5021.1 1983.70  5031.7 1984.66  5062.2 1984.07  5095.6 1984.40  5214.7 1991.49
  5231.1 1991.30  5236.7 1992.63  5245.6 1991.92  5415.1 2006.68  5481.7 2011.24
#Mann=7,-1,0
  4376.9   0.035       0  4544.9    0.07       0  4856.6    0.16       0
  4995.6   0.035       0  4997.2   0.035       0  5002.5   0.035       0
  5062.2    0.07       0
Bank Sta=4997.2,5002.5
Exp/Cntr=0.3,0.1

Type RM Length L Ch R = 1,2304,230,230,230
BEGIN DESCRIPTION:
Mapping XS 1159bbda
END DESCRIPTION:
XS GIS Cut Line= 3
      1477766.61      6825010.27      1477907.23      6824546.73
      1477823.89      6824143.04
#Sta/Elev= 30
  4507.0 1995.45  4582.7 1994.87  4620.6 1994.05  4634.5 1992.73  4666.1 1990.36
  4736.0 1988.46  4833.6 1984.08  4932.3 1982.36  4970.4 1982.63  4974.6 1981.09
  4988.1 1976.22  4997.7 1975.92  4998.1 1975.42  5003.0 1975.92  5020.7 1976.65
  5026.5 1977.93  5031.6 1977.50  5040.0 1980.64  5061.6 1983.33  5076.8 1982.14
  5113.1 1984.21  5127.0 1984.65  5143.3 1986.98  5177.3 1987.96  5204.5 1990.25
  5227.5 1989.86  5272.7 1992.40  5296.4 1991.18  5367.9 1991.53  5403.6 1992.82
#Mann=9,-1,0
  4507.0   0.035       0  4582.7    0.07       0  4634.5   0.035       0
  4736.0    0.07       0  4974.6    0.16       0  4997.7    0.07       0
  5003.0    0.16       0  5040.0   0.035       0  5113.1    0.07       0
Bank Sta=4997.7,5003
Exp/Cntr=0.3,0.1

Type RM Length L Ch R = 1,2074,186,186,186
BEGIN DESCRIPTION:
Mapping XS aa85bc7a
END DESCRIPTION:
XS GIS Cut Line= 3
      1477998.38      6824952.99      1478120.77      6824596.21
      1478076.71      6824171.07
#Sta/Elev= 30
  4614.7 1992.20  4641.1 1992.40  4662.3 1990.59  4679.7 1990.38  4685.0 1989.12
  4768.0 1984.07  4779.4 1982.81  4836.1 1980.76  4852.6 1981.81  4898.6 1980.81
  4968.8 1981.06  4987.1 1973.92  4999.6 1973.51  5000.0 1973.01  5004.9 1973.51
  5010.2 1973.63  5020.2 1975.77  5030.3 1980.06  5040.4 1981.78  5083.6 1983.85
  5120.8 1986.89  5140.9 1987.34  5163.0 1986.77  5189.8 1986.77  5241.4 1990.09
  5281.6 1989.85  5323.4 1990.82  5372.1 1989.26  5412.3 1991.69  5419.3 1991.32
#Mann=7,-1,0
  4614.7   0.035       0  4779.4    0.07       0  4999.6    0.07       0
  5004.9    0.07       0  5083.6   0.035       0  5163.0    0.07       0
  5323.4   0.035       0
Bank Sta=4999.6,5004.9
Exp/Cntr=0.3,0.1

Type RM Length L Ch R = 1,1888,260,260,260
BEGIN DESCRIPTION:
Mapping XS 49aac4ea
END DESCRIPTION:
XS GIS Cut Line= 3
      1478142.71      6824997.22      1478298.94      6824768.08
      1478246.86      6824057.12
#Sta/Elev= 30
  4592.3 1987.75  4673.1 1988.71  4710.7 1987.35  4786.9 1985.87  4831.7 1983.25
  4872.2 1982.27  4889.8 1980.27  4964.0 1979.58  4988.5 1975.58  5000.1 1975.43
  5017.5 1973.42  5017.9 1972.92  5022.8 1973.42  5030.4 1974.54  5040.2 1976.75
  5060.2 1979.31  5120.4 1979.73  5190.6 1983.15  5213.8 1982.67  5230.7 1982.70
  5240.7 1984.31  5265.8 1986.00  5290.8 1985.50  5371.1 1986.56  5381.1 1987.63
  5404.4 1987.30  5431.2 1989.80  5451.3 1988.39  5522.3 1989.41  5582.5 1990.00
#Mann=8,-1,0
  4592.3   0.035       0  4710.7    0.16       0  4964.0    0.07       0
  5017.5    0.07       0  5022.8    0.07       0  5030.4   0.035       0
  5213.8    0.07       0  5522.3   0.035       0
Bank Sta=5017.5,5022.8
Exp/Cntr=0.3,0.1

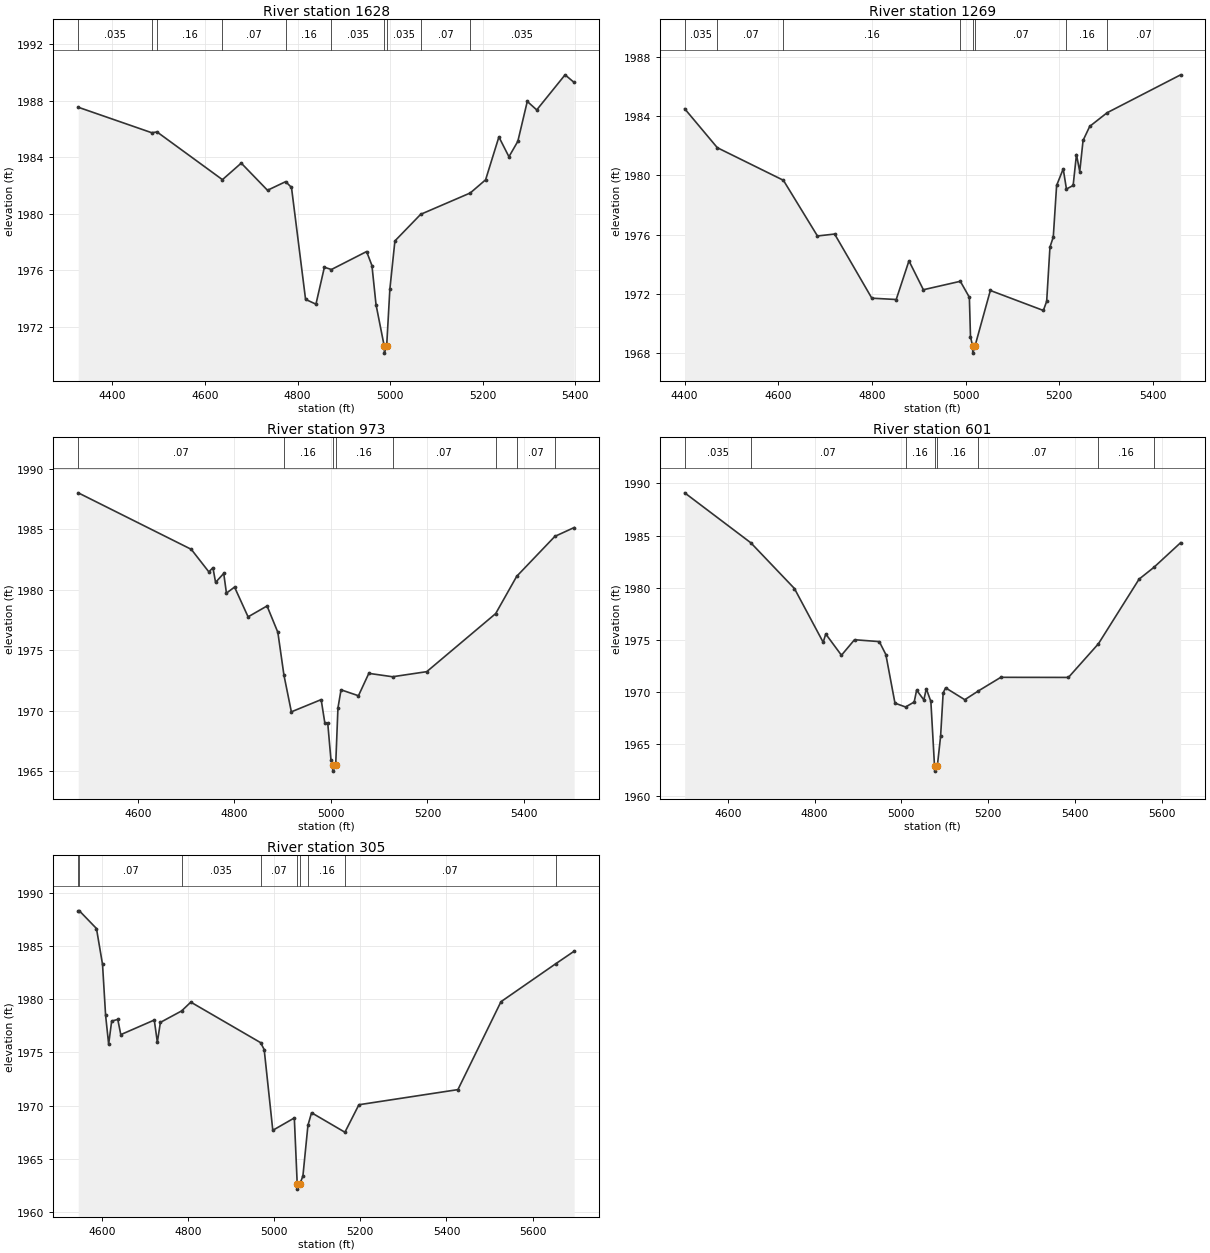
Type RM Length L Ch R = 1,1628,359,359,359
BEGIN DESCRIPTION:
Mapping XS fb4f0e6a
END DESCRIPTION:
XS GIS Cut Line= 4
      1478134.85      6825015.51      1478457.80      6824721.21
      1478494.25      6824505.06      1478410.93      6824098.85
#Sta/Elev= 30
  4326.5 1987.53  4485.0 1985.73  4496.8 1985.78  4637.9 1982.41  4678.5 1983.58
  4735.2 1981.66  4774.4 1982.27  4787.0 1981.86  4817.4 1973.95  4839.8 1973.61
  4858.0 1976.22  4873.2 1976.06  4949.2 1977.33  4960.7 1976.34  4969.5 1973.58
  4987.2 1970.65  4987.6 1970.15  4992.5 1970.65  4999.4 1974.67  5010.3 1978.08
  5065.9 1979.96  5173.0 1981.47  5206.1 1982.40  5234.8 1985.43  5256.5 1984.03
  5275.7 1985.12  5296.1 1987.94  5316.5 1987.34  5377.7 1989.82  5397.3 1989.28
#Mann=10,-1,0
  4326.5   0.035       0  4485.0    0.07       0  4496.8    0.16       0
  4637.9    0.07       0  4774.4    0.16       0  4873.2   0.035       0
  4987.2   0.035       0  4992.5   0.035       0  5065.9    0.07       0
  5173.0   0.035       0
Bank Sta=4987.2,4992.5
Exp/Cntr=0.3,0.1

Type RM Length L Ch R = 1,1269,296,296,296
BEGIN DESCRIPTION:
Mapping XS 1577c78e
END DESCRIPTION:
XS GIS Cut Line= 3
      1478189.55      6825051.95      1478707.80      6824734.23
      1479028.08      6824416.55
#Sta/Elev= 30
  4400.0 1984.50  4469.7 1981.87  4610.8 1979.67  4683.5 1975.91  4720.2 1976.04
  4799.6 1971.71  4851.7 1971.62  4878.9 1974.23  4909.7 1972.28  4988.6 1972.85
  5007.9 1971.77  5010.3 1969.11  5014.7 1968.50  5015.2 1968.00  5020.1 1968.50
  5052.7 1972.23  5165.9 1970.88  5173.0 1971.50  5180.0 1975.16  5187.1 1975.84
  5194.2 1979.32  5208.3 1980.44  5215.2 1979.08  5229.5 1979.32  5236.6 1981.41
  5243.6 1980.26  5250.7 1982.36  5264.9 1983.31  5302.0 1984.23  5459.0 1986.79
#Mann=8,-1,0
  4400.0   0.035       0  4469.7    0.07       0  4610.8    0.16       0
  4988.6    0.07       0  5014.7    0.07       0  5020.1    0.07       0
  5215.2    0.16       0  5302.0    0.07       0
Bank Sta=5014.7,5020.1
Exp/Cntr=0.3,0.1

Type RM Length L Ch R = 1,973,372,372,372
BEGIN DESCRIPTION:
Mapping XS 92a4899f
END DESCRIPTION:
XS GIS Cut Line= 3
      1478574.98      6825460.80      1478801.55      6825002.46
      1479124.46      6824598.81
#Sta/Elev= 30
  4476.0 1988.00  4710.4 1983.33  4746.8 1981.47  4755.3 1981.81  4760.8 1980.60
  4777.7 1981.34  4783.3 1979.71  4800.1 1980.21  4828.2 1977.75  4867.5 1978.65
  4889.9 1976.47  4902.5 1972.94  4917.9 1969.90  4979.7 1970.91  4987.3 1968.98
  4993.3 1968.98  5000.1 1965.89  5003.3 1965.50  5003.8 1965.00  5009.8 1965.50
  5014.5 1970.22  5020.9 1971.72  5057.0 1971.23  5078.5 1973.08  5127.7 1972.80
  5198.6 1973.22  5341.5 1978.02  5385.1 1981.10  5464.2 1984.40  5504.2 1985.13
#Mann=8,-1,0
  4476.0    0.07       0  4902.5    0.16       0  5003.3    0.07       0
  5009.8    0.16       0  5127.7    0.07       0  5341.5    0.16       0
  5385.1    0.07       0  5464.2   0.035       0
Bank Sta=5003.3,5009.8
Exp/Cntr=0.3,0.1

Type RM Length L Ch R = 1,601,296,296,296
BEGIN DESCRIPTION:
Mapping XS 0a28af21
END DESCRIPTION:
XS GIS Cut Line= 4
      1478671.35      6825695.14      1478942.17      6825286.31
      1479009.88      6825153.50      1479145.29      6824669.14
#Sta/Elev= 30
  4500.7 1989.10  4653.1 1984.30  4753.5 1979.91  4819.7 1974.75  4825.7 1975.54
  4861.8 1973.50  4891.9 1974.99  4949.0 1974.81  4964.1 1973.57  4985.1 1968.90
  5009.5 1968.53  5029.4 1969.01  5035.0 1970.15  5051.6 1969.21  5057.3 1970.28
  5067.8 1969.06  5076.2 1962.87  5076.7 1962.37  5082.7 1962.87  5090.2 1965.71
  5096.1 1969.88  5101.7 1970.37  5145.9 1969.23  5177.5 1970.08  5228.9 1971.38
  5384.7 1971.37  5453.7 1974.60  5547.4 1980.81  5581.2 1981.93  5643.1 1984.31
#Mann=8,-1,0
  4500.7   0.035       0  4653.1    0.07       0  5009.5    0.16       0
  5076.2    0.07       0  5082.7    0.16       0  5177.5    0.07       0
  5453.7    0.16       0  5581.2    0.07       0
Bank Sta=5076.2,5082.7
Exp/Cntr=0.3,0.1

Type RM Length L Ch R = 1,305,0,0,0
BEGIN DESCRIPTION:
MULBERRY CREEK TRIBUTARY 21 1.0
END DESCRIPTION:
XS GIS Cut Line= 3
      1478955.02      6825737.98      1479202.41      6825488.92
      1479205.00      6824687.97
#Sta/Elev= 30
  4544.6 1988.29  4547.3 1988.29  4587.0 1986.63  4601.1 1983.26  4608.2 1978.49
  4615.3 1975.77  4622.3 1977.94  4636.5 1978.10  4643.5 1976.67  4721.3 1978.04
  4728.4 1975.96  4735.5 1977.82  4784.6 1978.89  4806.2 1979.72  4968.2 1975.92
  4976.6 1975.27  4996.6 1967.69  5046.6 1968.85  5053.3 1962.67  5053.8 1962.17
  5059.8 1962.67  5066.6 1963.42  5078.2 1968.15  5086.6 1969.34  5164.1 1967.51
  5196.6 1970.09  5426.6 1971.51  5526.6 1979.76  5653.7 1983.32  5696.6 1984.50
#Mann=9,-1,0
  4544.6   0.035       0  4547.3    0.07       0  4784.6   0.035       0
  4968.2    0.07       0  5053.3    0.07       0  5059.8    0.07       0
  5078.2    0.16       0  5164.1    0.07       0  5653.7    0.16       0
Bank Sta=5053.3,5059.8
Exp/Cntr=0.3,0.1

Chan Stop Cuts=-1