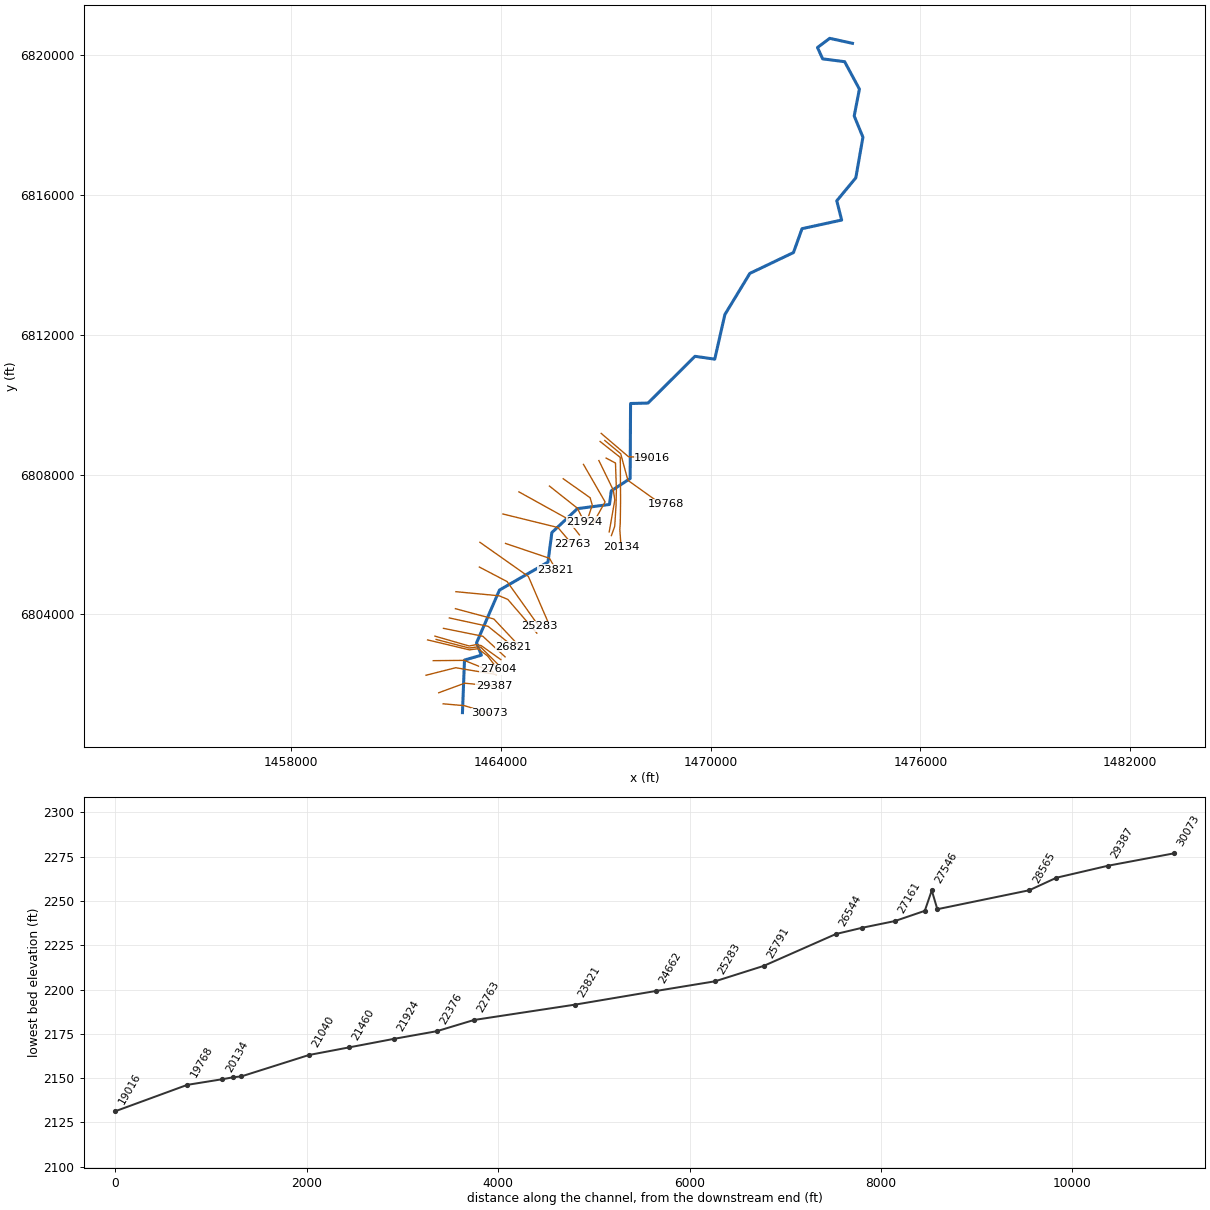
--- MULBERRY CREEK TRIBUTARY 21A.prj (project) ---

Proj Title=MULBERRY CREEK TRIBUTARY 21A Base Level Engineering
Current Plan=p01
Default Exp/Contr=0.3,0.1
English Units
Geom File=g01
Flow File=f01
Plan File=p01
Y Axis Title=Elevation
X Axis Title(PF)=Main Channel Distance
X Axis Title(XS)=Station
BEGIN DESCRIPTION:
MULBERRY CREEK TRIBUTARY 21A
END DESCRIPTION:
DSS File=dss
DSS Export Rating Curves= 0
DSS Export Rating Curve Sorted= 0
DSS Export Volume Flow Curves= 0
DXF OffsetX= 0
DXF OffsetY= 0
DXF ScaleX= 1
DXF ScaleY= 10

--- MULBERRY CREEK TRIBUTARY 21A.p01 (plan) ---

Plan Title=Multiple Run
Program Version=4.10
Short Identifier=Multiple Run
Geom File=g01
Flow File=f01
Subcritical Flow
K Sum by GR= 0
Std Step Tol= 0.01
Critical Tol= 0.01
Num of Std Step Trials= 20
Max Error Tol= 0.3
Flow Tol Ratio= 0.001
Split Flow NTrial= 30
Split Flow Tol= 0.02
Split Flow Ratio= 0.02
Log Output Level= 0
Friction Slope Method= 1
Unsteady Friction Slope Method= 2
Unsteady Bridges Friction Slope Method= 1
Parabolic Critical Depth
Global Vel Dist= 1 , 1 , 1
Global Log Level= 0
CheckData=True
Encroach Param=-1 ,0,0, 0
BEGIN DESCRIPTION:
Multiple Run
END DESCRIPTION:
Computation Interval=1HOUR
Output Interval=1HOUR
Run HTab= 0
Run UNet= 0
Run PostProcess= 0
Run WQNet= 0
UNET Theta= 1
UNET Theta Warmup= 1
UNET ZTol= 0.02
UNET ZSATol= 0.05
UNET MxIter= 20
UNET MaxInSteps= 0
UNET DtIC= 0
UNET DtMin= 0
UNET MaxCRTS= 20
UNET WFStab= 2
UNET SFStab= 1
UNET WFX= 1
UNET SFX= 1
UNET DSS MLevel= 4
UNET DZMax Abort= 100
UNET Convert EG Bridges= 0
UNET Use Existing IB Tables=-1
UNET Froude Reduction=False
UNET Froude Limit= 1
UNET Froude Power= 10
UNET Time Slicing=0,0, 5
UNET Junction Losses=0
Instantaneous Interval=1HOUR
DSS File=dss
Write IC File= 0
Write IC File at Sim End=0
Echo Input=False
Echo Parameters=False
Echo Output=False
Write Detailed= 0
WQ AD Non Conservative
WQ ULTIMATE=-1
WQ Max Comp Step=1HOUR
WQ Output Interval=15MIN
WQ Output Selected Increments= 0
WQ Output face flow=0
WQ Output face velocity=0
WQ Output face area=0
WQ Output face dispersion=0
WQ Output cell volume=0
WQ Output cell surface area=0
WQ Output cell continuity=0
WQ Output cumulative cell continuity=0
WQ Output face conc=0
WQ Output face dconc_dx=0
WQ Output face courant=0
WQ Output face peclet=0
WQ Output face adv mass=0
WQ Output face disp mass=0
WQ Output cell mass=0
WQ Output cell source sink temp=0
WQ Output cell source sink nsm=0
WQ Output MaxMinRange=-1
WQ Daily Max Min Mean=-1
WQ Daily Range=0
WQ Daily Time=0
WQ Create Restart=0
WQ Fixed Restart=0
WQ System Summary=0
WQ Use Fixed Temperature=0
Sorting and Armoring Iterations= 10
XS Update Threshold= 0.02
Hydraulics Update Threshold= 0.02
Energy Slope Method= 1
Volume Change Method= 0
XS Weighting Method= 0
Number of US Weighted Cross Sections= 1
Number of DS Weighted Cross Sections= 1
Upstream XS Weight=0.25
Main XS Weight=0.5
Downstream XS Weight=0.25
Number of DS XS's Weighted with US Boundary= 1
Upstream Boundary Weight= 1
Weight of XSs Associated with US Boundary= 0
Number of US XS's Weighted with DS Boundary= 1
Downstream Boundary Weight= 0.5
Weight of XSs Associated with DS Boundary= 0.5
Sediment Output Level= 4
Mass or Volume Output= 0
Output Increment Type= 1
Profile and TS Output Increment= 10
XS Output Flag= 0
XS Output Increment= 10
Disregard all LS=0
Disregard all Conn=0
Disregard all Breaches=0
Disregard all Pumps=0

--- MULBERRY CREEK TRIBUTARY 21A.f01 (steady flow) ---

Flow Title=Multiple
Program Version=4.10
Number of Profiles= 7
Profile Names=10-year,25-year,50-year,1pct_min,100-year,1pct_plu,500-year
River Rch & RM=MULBERRY CREEK T,Reach-1         ,30073
     315     454     573     361     720    1437    1150
River Rch & RM=MULBERRY CREEK T,Reach-1         ,28565
     538     798    1029     660    1317    2627    2183
River Rch & RM=MULBERRY CREEK T,Reach-1         ,25791
     681    1020    1321     851    1698    3388    2840
River Rch & RM=MULBERRY CREEK T,Reach-1         ,19768
    1078    1649    2168    1414    2822    5630    4843
River Rch & RM=MULBERRY CREEK T,Reach-1         ,16201
    1096    1672    2193    1427    2846    5679    4859
River Rch & RM=MULBERRY CREEK T,Reach-1         ,9089
    1138    1733    2269    1474    2941    5869    5005
River Rch & RM=MULBERRY CREEK T,Reach-1         ,1364
    1582    2443    3230    2117    4223    8426    7313
Boundary for River Rch & Prof#=MULBERRY CREEK T,Reach-1         , 1
Up Type= 0
Dn Type= 3
Dn Slope=0.00571
Boundary for River Rch & Prof#=MULBERRY CREEK T,Reach-1         , 2
Up Type= 0
Dn Type= 3
Dn Slope=0.00571
Boundary for River Rch & Prof#=MULBERRY CREEK T,Reach-1         , 3
Up Type= 0
Dn Type= 3
Dn Slope=0.00571
Boundary for River Rch & Prof#=MULBERRY CREEK T,Reach-1         , 4
Up Type= 0
Dn Type= 3
Dn Slope=0.00571
Boundary for River Rch & Prof#=MULBERRY CREEK T,Reach-1         , 5
Up Type= 0
Dn Type= 3
Dn Slope=0.00571
Boundary for River Rch & Prof#=MULBERRY CREEK T,Reach-1         , 6
Up Type= 0
Dn Type= 3
Dn Slope=0.00571
Boundary for River Rch & Prof#=MULBERRY CREEK T,Reach-1         , 7
Up Type= 0
Dn Type= 3
Dn Slope=0.00571
DSS Import GetInterval= 0
DSS Import GetPeak= 0
DSS Import FillOption= 0

--- MULBERRY CREEK TRIBUTARY 21A.g01 (geometry) ---

Geom Title=Existing Conditions
Program Version=4.10

River Reach=MULBERRY CREEK T,Reach-1
Reach XY= 30
        1462905.        6801188.      1462963.04      6802691.32
       1463445.9      6802831.29      1463306.96      6803182.11
       1463962.8      6804694.21      1465349.41      6805493.61
      1465460.83       6806340.3      1466191.44      6807024.51
      1467107.67      6807143.42      1467159.99        6807533.
      1467699.53      6807885.55      1467710.95      6810032.31
      1468211.34      6810045.36      1469552.57       6811382.6
      1470118.22      6811301.62      1470407.08      6812575.99
       1471121.2      6813754.71      1472368.35      6814351.36
      1472613.46       6815034.5      1473746.05      6815281.31
      1473607.06      6815832.15      1474151.25      6816489.55
      1474354.62      6817653.27      1474105.07      6818258.03
      1474253.95      6819027.56      1473831.88      6819811.83
      1473202.63      6819893.67      1473054.92      6820218.12
      1473404.99      6820480.47        1474055.        6820338.

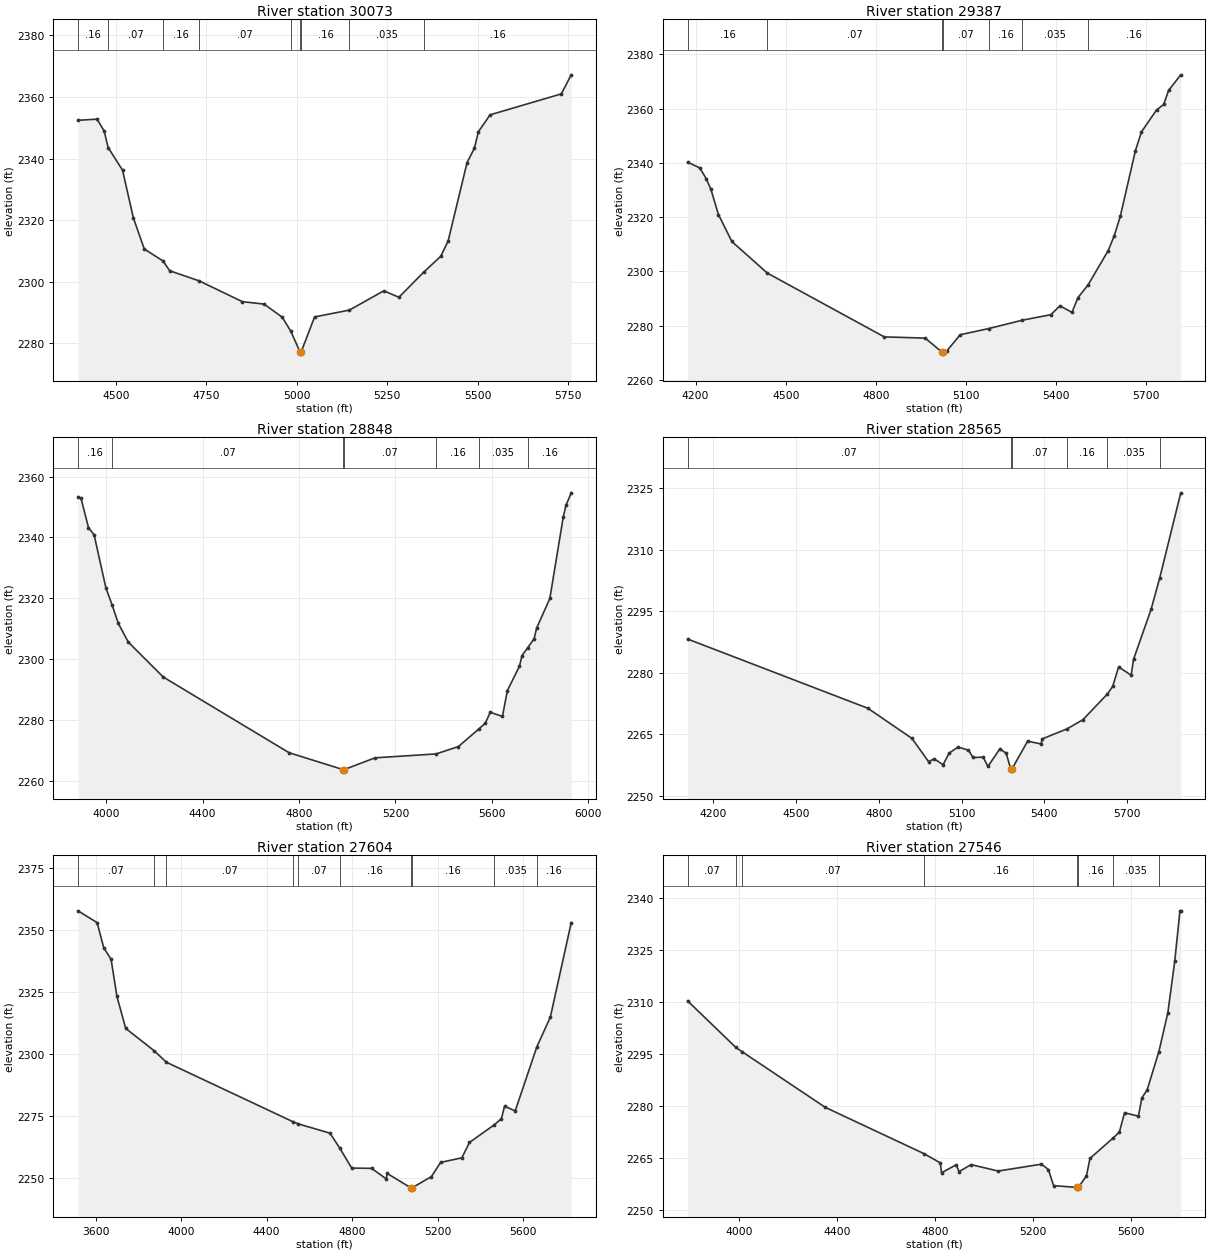
Type RM Length L Ch R = 1 ,30073   ,686,686,686
BEGIN DESCRIPTION:
MULBERRY CREEK TRIBUTARY 21A 57.0
END DESCRIPTION:
XS GIS Cut Line= 3
      1462352.68      6801439.53      1462955.08      6801387.97
      1463680.43      6801166.21
#Sta/Elev= 30
  4395.4 2352.46  4447.9 2352.83  4467.5 2348.97  4478.5  2343.6  4518.2 2336.29
  4548.3 2320.74  4578.4 2310.66  4630.3 2306.78  4648.6  2303.6  4729.9 2300.33
  4849.4 2293.57  4909.6 2292.78  4959.8 2288.51  4983.4 2283.96  5008.4 2277.36
  5008.6 2276.86  5012.4 2277.36  5049.1 2288.61  5145.5 2290.84  5240.4 2297.09
  5282.3    2295    5351 2303.19  5397.9 2308.31  5418.2 2313.25  5470.5 2338.72
    5491 2343.42  5501.9 2348.74  5534.2 2354.23    5731 2361.03  5758.5 2367.22
#Mann= 9 ,-1 , 0
  4395.4     .16       0  4478.5     .07       0  4630.3     .16       0
  4729.9     .07       0  4983.4     .16       0  5008.4     .07       0
  5012.4     .16       0  5145.5    .035       0    5351     .16       0
Bank Sta=5008.4,5012.4
XS Rating Curve= 0 ,0
Exp/Cntr=0.3,0.1

Type RM Length L Ch R = 1 ,29387   ,539,539,539
BEGIN DESCRIPTION:
Mapping XS e056810e
END DESCRIPTION:
XS GIS Cut Line= 3
       1462226.8      6801756.38      1462968.99      6802029.81
      1463815.32      6801947.35
#Sta/Elev= 30
  4173.3 2340.31    4214 2338.18  4235.3 2334.21  4250.8 2330.32  4275.9    2321
  4320.6 2311.06  4438.4 2299.42  4827.8 2275.89  4964.3 2275.43  5018.5  2270.4
  5018.8  2269.9  5022.5  2270.4  5035.1  2270.6  5080.8 2276.68    5176 2278.97
  5287.8 2282.05  5382.2 2284.07  5412.4 2287.32  5452.6 2284.93  5472.7 2290.39
  5505.5 2294.93  5573.1  2307.7  5593.2 2313.13  5613.3  2320.3  5663.6 2344.49
  5683.7 2351.44  5733.9 2359.52  5757.7 2361.56  5774.1 2366.74  5814.6 2372.49
#Mann= 7 ,-1 , 0
  4173.3     .16       0  4438.4     .07       0  5018.5     .07       0
  5022.5     .07       0    5176     .16       0  5287.8    .035       0
  5505.5     .16       0
Bank Sta=5018.5,5022.5
XS Rating Curve= 0 ,0
Exp/Cntr=0.3,0.1

Type RM Length L Ch R = 1 ,28848   ,283,283,283
BEGIN DESCRIPTION:
Mapping XS 936d4803
END DESCRIPTION:
XS GIS Cut Line= 3
      1461863.13      6802257.25      1462713.78      6802472.52
      1463866.53      6802278.08
#Sta/Elev= 30
    3883 2353.36  3895.2 2352.86  3926.2 2343.22  3949.6 2340.84  3998.4 2323.39
  4024.2 2317.78    4050 2311.71  4091.2 2305.57  4236.7 2294.06  4758.5 2269.18
  4982.8 2263.62  4983.1 2263.12  4986.8 2263.62    5115 2267.49  5368.9 2268.78
  5461.5 2271.21  5546.3 2277.01    5573 2278.87  5593.3 2282.47    5644 2281.11
  5664.4 2289.61  5714.7 2297.65  5725.1 2301.09  5748.6  2303.7  5775.2 2306.63
    5786 2310.17  5840.8 2319.94  5896.2 2346.64  5907.7 2350.55  5929.5 2354.66
#Mann= 7 ,-1 , 0
    3883     .16       0  4024.2     .07       0  4982.8     .07       0
  4986.8     .07       0  5368.9     .16       0  5546.3    .035       0
  5748.6     .16       0
Bank Sta=4982.8,4986.8
XS Rating Curve= 0 ,0
Exp/Cntr=0.3,0.1

Type RM Length L Ch R = 1 ,28565   ,961,961,961
BEGIN DESCRIPTION:
Mapping XS 4071cbf3
END DESCRIPTION:
XS GIS Cut Line= 4
      1462070.88      6802674.38      1462960.65      6802683.06
       1463073.5      6802635.32      1463793.98      6802344.52
#Sta/Elev= 30
  4106.1 2288.23  4760.3 2271.37  4920.3 2264.03  4980.3 2258.39  5001.1 2259.06
  5033.2 2257.63  5054.9 2260.45  5087.5 2261.93    5125 2261.18  5141.6 2259.39
  5178.7 2259.46  5195.6  2257.2  5238.7 2261.45  5261.9 2260.46  5278.7 2256.57
  5278.9 2256.07  5282.7 2256.57  5339.8 2263.36    5388 2262.69  5393.4 2263.93
  5482.5 2266.35  5540.6 2268.59  5629.6 2274.87  5648.5  2276.7    5670 2281.44
  5715.5 2279.41    5724 2283.27  5787.9 2295.47  5819.4 2303.17  5895.4 2323.82
#Mann= 6 ,-1 , 0
  4106.1     .07       0  5278.7     .07       0  5282.7     .07       0
  5482.5     .16       0  5629.6    .035       0  5819.4     .16       0
#XS Ineff= 2 , 0
       0  5087.5 2261.93               0
Permanent Ineff=
       F       F
Bank Sta=5278.7,5282.7
XS Rating Curve= 0 ,0
Exp/Cntr=0.3,0.1

Type RM Length L Ch R = 1 ,27604   ,58,58,58
BEGIN DESCRIPTION:
Mapping XS 883ea3ff
END DESCRIPTION:
XS GIS Cut Line= 5
       1461908.2      6803268.53      1463100.75      6802983.76
       1463354.7      6803017.75      1463625.06      6802806.67
      1463917.45       6802422.6
#Sta/Elev= 30
  3517.7 2357.87  3606.9  2353.1  3637.8 2342.95  3672.2 2338.27  3699.5  2323.3
  3740.6 2310.33  3872.4  2301.4  3931.1 2296.66  4522.7 2272.63  4547.3 2271.76
  4696.7 2267.99  4741.4 2262.06  4798.5 2253.87  4891.6 2253.76  4959.5 2249.51
  4964.6  2251.7  5075.5 2245.86  5075.8 2245.36  5080.1 2245.86  5170.9 2250.39
  5214.3 2256.16  5313.8 2258.02  5349.4 2264.22  5466.4 2271.42  5499.1 2273.88
  5513.6 2278.89  5563.5 2276.98  5665.2 2302.99  5727.8 2314.86  5825.7 2353.12
#Mann= 10 ,-1 , 0
  3517.7     .07       0  3872.4    .035       0  3931.1     .07       0
  4522.7     .16       0  4547.3     .07       0  4741.4     .16       0
  5075.5     .07       0  5080.1     .16       0  5466.4    .035       0
  5665.2     .16       0
Bank Sta=5075.5,5080.1
XS Rating Curve= 0 ,0
Exp/Cntr=0.3,0.1

Type RM Length L Ch R = 1 ,27546   ,73,73,73
BEGIN DESCRIPTION:
Mapping XS 1db99b90
END DESCRIPTION:
XS GIS Cut Line= 5
      1462150.52      6803282.11       1463098.4      6803035.59
      1463320.62      6803066.84      1463428.26       6803059.9
      1463924.81      6802563.35
#Sta/Elev= 30
  3790.2 2310.34  3987.5 2296.88  4012.4 2295.68  4352.8 2279.58  4755.1 2266.24
  4822.3 2263.55  4827.3 2260.69  4887.4 2263.03  4898.6 2261.03  4947.9 2263.06
  5058.6  2261.2  5235.3 2263.19  5263.6 2261.63  5284.8 2256.99  5381.5 2256.48
  5381.8 2255.98  5386.1 2256.48  5419.1 2259.82  5433.3 2264.84  5528.7 2270.79
  5553.5 2272.47  5574.7 2278.03  5631.2 2277.04  5645.4 2282.37  5666.6 2284.57
  5714.9 2295.72  5751.5 2306.96  5779.7 2321.88  5800.7 2336.34  5804.1 2336.34
#Mann= 8 ,-1 , 0
  3790.2     .07       0  3987.5    .035       0  4012.4     .07       0
  4755.1     .16       0  5381.5     .07       0  5386.1     .16       0
  5528.7    .035       0  5714.9     .16       0
Bank Sta=5381.5,5386.1
XS Rating Curve= 0 ,0
Exp/Cntr=0.3,0.1

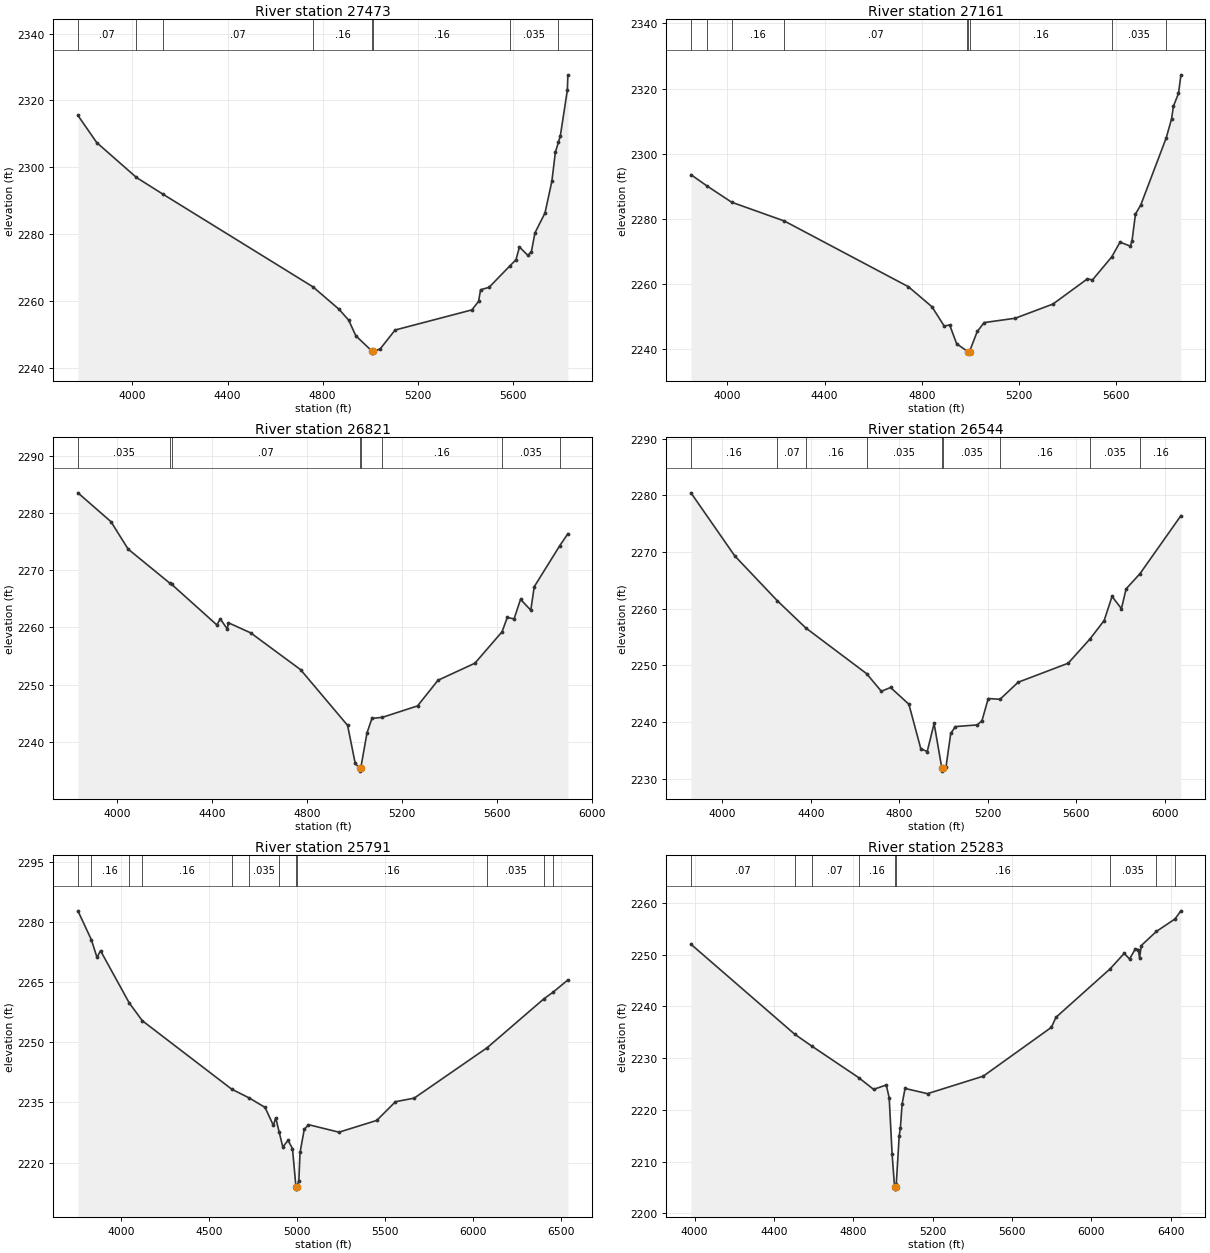
Type RM Length L Ch R = 1 ,27473   ,312,312,312
BEGIN DESCRIPTION:
Mapping XS f59f9656
END DESCRIPTION:
XS GIS Cut Line= 5
      1462118.12      6803376.12      1463093.81      6803094.87
      1463304.17      6803132.98      1463441.03      6803105.28
      1464003.15      6802702.78
#Sta/Elev= 30
  3770.8 2315.53  3849.9 2307.41    4017 2296.97  4127.6 2292.01  4759.5 2264.24
  4868.7 2257.56  4909.4  2254.3  4939.4 2249.62  5008.8 2244.94  5009.1 2244.44
  5013.4 2244.94  5041.7 2245.69  5104.4 2251.35  5427.4 2257.37  5455.4 2259.91
    5464 2263.39  5499.7 2264.12    5586 2270.45  5612.7 2272.36  5627.4 2276.18
    5663 2273.66  5677.8 2274.83  5692.5  2280.4  5734.9 2286.37  5763.8 2295.89
  5778.5 2304.56  5791.2 2307.47  5799.4 2309.49  5828.9 2323.12    5831 2327.67
#Mann= 8 ,-1 , 0
  3770.8     .07       0    4017    .035       0  4127.6     .07       0
  4759.5     .16       0  5008.8     .07       0  5013.4     .16       0
    5586    .035       0  5791.2     .16       0
Bank Sta=5008.8,5013.4
XS Rating Curve= 0 ,0
Exp/Cntr=0.3,0.1

Type RM Length L Ch R = 1 ,27161   ,340,340,340
BEGIN DESCRIPTION:
Mapping XS 39625050
END DESCRIPTION:
XS GIS Cut Line= 3
      1462361.74      6803598.85      1463485.82      6803373.17
      1464123.76      6802782.96
#Sta/Elev= 30
  3850.3 2293.52    3916 2290.07  4017.6 2285.06  4234.5 2279.28  4744.9 2259.08
  4841.6 2252.94  4892.5 2246.95  4914.4 2247.36  4943.4 2241.54  4987.4 2239.24
  4991.5 2239.17  4991.8 2238.67  4996.2 2239.17  5028.1 2245.32  5056.5 2248.06
  5184.1 2249.39  5339.4 2253.75  5481.2  2261.5  5502.1 2261.18  5581.3 2268.25
  5615.5 2272.78  5658.1 2271.55  5664.9 2273.28    5679 2281.43  5700.6 2284.18
  5805.5 2304.83  5827.6 2310.72    5835 2314.55  5855.9 2318.49  5865.9 2324.21
#Mann= 9 ,-1 , 0
  3850.3     .16       0    3916    .035       0  4017.6     .16       0
  4234.5     .07       0  4987.4     .16       0  4991.5     .07       0
  4996.2     .16       0  5581.3    .035       0  5805.5     .16       0
Bank Sta=4991.5,4996.2
XS Rating Curve= 0 ,0
Exp/Cntr=0.3,0.1

Type RM Length L Ch R = 1 ,26821   ,277,277,277
BEGIN DESCRIPTION:
Mapping XS 041c719e
END DESCRIPTION:
XS GIS Cut Line= 3
      1462528.98       6803896.7       1463636.6      6803657.12
      1464361.11      6803074.73
#Sta/Elev= 30
  3836.6 2283.51  3975.8 2278.47  4047.9 2273.69  4224.5  2267.7  4231.1 2267.54
  4421.3 2260.45  4436.2 2261.48  4465.4 2259.73  4470.5 2260.81  4563.8 2259.06
  4773.8 2252.64    4972  2242.9  5004.1 2236.26  5022.6 2235.41  5022.9 2234.91
  5027.3 2235.41  5053.7 2241.59  5074.5 2244.11  5118.8 2244.31  5266.5  2246.3
  5352.7 2250.78  5508.1 2253.76  5622.4 2259.25  5644.1 2261.74  5672.9  2261.5
  5700.1 2264.91  5743.3 2263.01  5757.7 2267.11  5864.7 2274.24  5899.4 2276.37
#Mann= 8 ,-1 , 0
  3836.6    .035       0  4224.5     .16       0  4231.1     .07       0
  5022.6     .07       0  5027.3     .07       0  5118.8     .16       0
  5622.4    .035       0  5864.7     .16       0
Bank Sta=5022.6,5027.3
XS Rating Curve= 0 ,0
Exp/Cntr=0.3,0.1

Type RM Length L Ch R = 1 ,26544   ,753,753,753
BEGIN DESCRIPTION:
Mapping XS e0448e5f
END DESCRIPTION:
XS GIS Cut Line= 3
      1462704.24      6804161.75      1463802.32      6803866.62
      1464539.13      6803082.13
#Sta/Elev= 30
  3858.7 2280.45  4056.2 2269.34  4248.5 2261.42  4377.7  2256.6  4651.8 2248.55
  4718.9 2245.43  4760.4  2246.1  4843.2 2243.14  4897.1 2235.28    4926  2234.8
  4957.1 2239.75  4992.1 2231.84  4992.4 2231.34    4997 2231.84  5010.7 2232.05
  5032.2 2237.99  5053.2  2239.2  5152.3  2239.5  5173.4 2240.26  5201.7 2244.15
    5255 2244.02  5336.4 2247.02  5562.6 2250.38  5661.4 2254.67  5725.3 2257.92
  5760.9 2262.17  5803.3 2260.01  5824.4  2263.5    5887 2266.18    6072 2276.42
#Mann= 9 ,-1 , 0
  3858.7     .16       0  4248.5     .07       0  4377.7     .16       0
  4651.8    .035       0  4992.1    .035       0    4997    .035       0
    5255     .16       0  5661.4    .035       0    5887     .16       0
Bank Sta=4992.1,4997
XS Rating Curve= 0 ,0
Exp/Cntr=0.3,0.1

Type RM Length L Ch R = 1 ,25791   ,508,508,508
BEGIN DESCRIPTION:
Mapping XS 39983ac3
END DESCRIPTION:
XS GIS Cut Line= 4
       1462717.2      6804647.87      1463954.23      6804530.68
      1464201.62      6804426.51      1465030.31      6803463.33
#Sta/Elev= 30
  3756.2 2282.72  3832.9 2275.48  3864.5 2271.11  3884.6 2272.78  4047.3 2259.79
  4121.7 2255.34    4629 2238.29  4728.7 2236.09  4818.7 2233.73    4866 2229.23
    4879 2231.15  4898.7  2227.6  4919.2 2223.87  4949.3 2225.52  4974.3 2223.47
  4994.2 2213.87  4994.5 2213.37  4999.1 2213.87  5010.5 2215.49  5017.2  2222.5
    5041 2228.23  5064.7 2229.44  5238.3 2227.56  5452.6 2230.49    5559 2235.15
  5665.5 2236.05  6080.2 2248.63  6400.4 2260.75  6453.7 2262.45  6537.8 2265.49
#Mann= 12 ,-1 , 0
  3756.2     .07       0  3832.9     .16       0  4047.3     .07       0
  4121.7     .16       0    4629     .07       0  4728.7    .035       0
  4898.7     .16       0  4994.2     .07       0  4999.1     .16       0
  6080.2    .035       0  6400.4     .07       0  6453.7     .16       0
Bank Sta=4994.2,4999.1
XS Rating Curve= 0 ,0
Exp/Cntr=0.3,0.1

Type RM Length L Ch R = 1 ,25283   ,621,621,621
BEGIN DESCRIPTION:
Mapping XS 81999447
END DESCRIPTION:
XS GIS Cut Line= 3
      1463387.36      6805353.61      1464181.66      6804936.93
       1465093.1      6803656.57
#Sta/Elev= 30
  3982.1    2252    4505 2234.61  4590.8 2232.32    4828  2226.2  4902.3 2223.95
  4966.1  2224.8  4980.9 2222.33  4995.6 2211.42  5007.8 2205.17  5008.2 2204.67
    5013 2205.17  5016.5  2205.6  5031.3 2214.97  5037.4 2216.54    5046 2221.13
  5060.8 2224.13  5173.9 2223.12  5454.7  2226.5  5798.4 2235.95  5820.7 2237.86
  6094.3 2247.26    6165 2250.24    6192 2249.15  6221.5 2251.13  6236.3 2250.96
  6242.4 2249.32    6251 2251.75  6326.9 2254.47  6420.6 2256.88  6450.7 2258.46
#Mann= 9 ,-1 , 0
  3982.1     .07       0    4505    .035       0  4590.8     .07       0
    4828     .16       0  5007.8     .07       0    5013     .16       0
  6094.3    .035       0  6326.9     .16       0  6420.6    .035       0
Bank Sta=5007.8,5013
XS Rating Curve= 0 ,0
Exp/Cntr=0.3,0.1

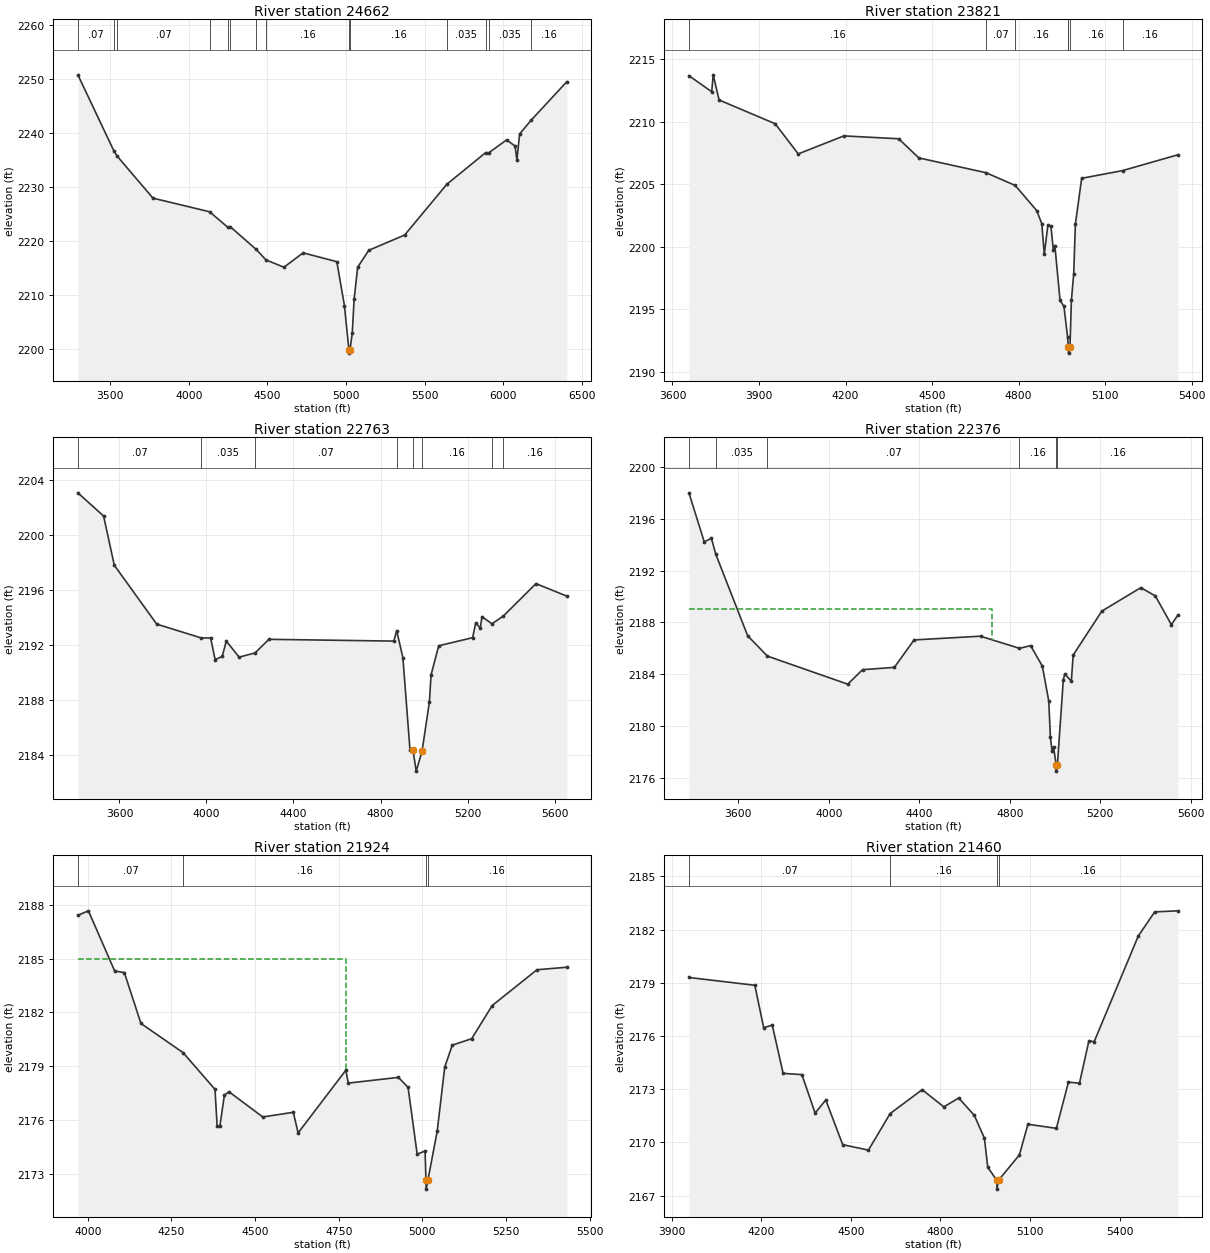
Type RM Length L Ch R = 1 ,24662   ,841,841,841
BEGIN DESCRIPTION:
Mapping XS 5982accd
END DESCRIPTION:
XS GIS Cut Line= 3
      1463403.88      6806061.06      1464788.43       6805084.5
      1465348.34      6803786.73
#Sta/Elev= 30
  3295.3 2250.73    3524 2236.65    3547  2235.6  3772.8 2227.88  4132.6 2225.36
  4246.8 2222.52  4264.7 2222.57  4428.4 2218.39  4491.1 2216.44  4605.2 2215.08
  4727.1 2217.75  4941.4 2216.11  4989.6 2207.98  5018.6 2199.67    5019 2199.17
  5024.2 2199.67  5039.4 2202.86  5051.1 2209.13  5073.8 2215.09  5144.4 2218.22
  5372.3 2221.05  5641.2 2230.47  5887.3 2236.32  5906.7 2236.28  6020.4 2238.67
  6074.2 2237.53  6085.8 2234.98  6103.2 2239.77    6175 2242.28    6403 2249.45
#Mann= 14 ,-1 , 0
  3295.3     .07       0    3524     .16       0    3547     .07       0
  4132.6     .16       0  4246.8     .07       0  4264.7     .16       0
  4428.4     .07       0  4491.1     .16       0  5018.6     .07       0
  5024.2     .16       0  5641.2    .035       0  5887.3     .16       0
  5906.7    .035       0    6175     .16       0
Bank Sta=5018.6,5024.2
XS Rating Curve= 0 ,0
Exp/Cntr=0.3,0.1

Type RM Length L Ch R = 1 ,23821   ,1058,1058,1058
BEGIN DESCRIPTION:
Mapping XS d8fb2305
END DESCRIPTION:
XS GIS Cut Line= 3
      1464135.99      6806028.55      1465394.68       6805603.2
      1465572.34      6805282.54
#Sta/Elev= 30
    3657 2213.67    3736 2212.39  3741.2 2213.74  3761.5 2211.73  3956.1 2209.83
    4036 2207.42  4194.3 2208.86  4384.3 2208.63  4454.1  2207.1  4686.8 2205.92
  4788.3  2204.9  4862.9 2202.89  4880.4 2201.85  4889.1  2199.4  4901.5 2201.72
  4912.1 2201.65  4920.6 2199.73  4925.8 2200.09  4943.7 2195.72  4957.3 2195.23
  4969.7 2192.82  4972.6    2192  4973.1  2191.5  4978.2    2192  4983.1 2195.73
  4991.2 2197.86  4996.9 2201.81  5018.7 2205.47  5161.1 2206.09  5352.2 2207.35
#Mann= 7 ,-1 , 0
    3657     .16       0  4686.8     .07       0  4788.3     .16       0
  4969.7     .16       0  4972.6     .07       0  4978.2     .16       0
  5161.1     .16       0
Bank Sta=4972.6,4978.2
XS Rating Curve= 0 ,0
Exp/Cntr=0.3,0.1

Type RM Length L Ch R = 1 ,22763   ,387,387,387
BEGIN DESCRIPTION:
Mapping XS 1d2f29e4
END DESCRIPTION:
XS GIS Cut Line= 3
      1464062.23      6806870.56      1465633.39      6806484.28
       1466040.5      6806003.54
#Sta/Elev= 30
  3408.6  2203.1  3526.9 2201.41  3576.2 2197.82    3771 2193.53  3975.8 2192.52
    4019 2192.52  4039.6 2190.94  4072.1 2191.17  4091.1 2192.29    4150 2191.12
  4223.5 2191.43  4286.8 2192.42  4861.3 2192.29  4874.3 2193.05  4902.9 2191.09
  4935.5 2184.37  4949.5 2184.34  4964.1 2182.81  4991.1 2184.27  5024.8 2187.85
  5032.5 2189.83  5067.6 2191.95  5223.6 2192.54  5237.9 2193.63  5258.8 2193.24
  5266.5 2194.07  5312.6 2193.55  5364.9 2194.12  5514.8 2196.48  5656.5 2195.57
#Mann= 8 ,-1 , 0
  3408.6     .07       0  3975.8    .035       0  4223.5     .07       0
  4874.3     .16       0  4949.5     .07       0  4991.1     .16       0
  5312.6     .07       0  5364.9     .16       0
#XS Ineff= 2 , 0
       0  4873.7    2193               0
Permanent Ineff=
       F       F
Bank Sta=4949.5,4991.1
XS Rating Curve= 0 ,0
Exp/Cntr=0.3,0.1

Type RM Length L Ch R = 1 ,22376   ,452,452,452
BEGIN DESCRIPTION:
Mapping XS ff691f20
END DESCRIPTION:
XS GIS Cut Line= 3
      1464517.96      6807504.23      1465880.79      6806749.03
       1466249.2      6806272.27
#Sta/Elev= 30
  3381.8 2198.01  3449.5 2194.22  3481.3 2194.49    3500 2193.29  3641.4 2186.96
  3728.6 2185.39  4083.7 2183.22  4148.9 2184.34  4289.7 2184.52  4376.7 2186.64
  4670.3 2186.93  4842.6 2185.99  4891.8  2186.2  4943.7 2184.61    4972 2181.91
  4979.1 2179.12  4986.5 2178.06  4992.9 2178.39  5004.5    2177    5005  2176.5
  5010.2    2177  5036.3 2183.57  5042.7 2184.01  5071.7 2183.45  5079.8 2185.47
  5206.6 2188.87  5378.7 2190.68    5443 2190.04  5513.6 2187.82  5542.4 2188.56
#Mann= 6 ,-1 , 0
  3381.8     .07       0    3500    .035       0  3728.6     .07       0
  4842.6     .16       0  5004.5     .07       0  5010.2     .16       0
#XS Ineff= 2 , 0
       0  4719.7    2189               0
Permanent Ineff=
       F       F
Bank Sta=5004.5,5010.2
XS Rating Curve= 0 ,0
Exp/Cntr=0.3,0.1

Type RM Length L Ch R = 1 ,21924   ,464,464,464
BEGIN DESCRIPTION:
Mapping XS 216ef0db
END DESCRIPTION:
XS GIS Cut Line= 3
       1465392.1      6807670.02      1466190.68      6807036.36
      1466389.75      6806642.56
#Sta/Elev= 30
  3970.6 2187.42  4002.1 2187.67  4080.6 2184.31  4109.5 2184.22  4159.1 2181.38
    4285 2179.75  4380.3  2177.7  4386.6 2175.68  4394.7 2175.63  4408.3 2177.37
  4421.9 2177.57  4522.9 2176.16  4614.2 2176.42  4628.6 2175.27  4771.2 2178.77
  4778.5 2178.05  4928.2 2178.37  4957.1 2177.81  4984.3 2174.08  5007.9 2174.26
  5010.6 2172.63  5011.1 2172.13  5016.3 2172.63  5044.2 2175.37  5066.6 2178.94
  5089.1 2180.17  5147.2 2180.53  5208.4 2182.38  5342.2 2184.38  5431.3 2184.52
#Mann= 4 ,-1 , 0
  3970.6     .07       0    4285     .16       0  5010.6     .07       0
  5016.3     .16       0
#XS Ineff= 2 , 0
       0  4771.2    2185               0
Permanent Ineff=
       F       F
Bank Sta=5010.6,5016.3
XS Rating Curve= 0 ,0
Exp/Cntr=0.3,0.1

Type RM Length L Ch R = 1 ,21460   ,420,420,420
BEGIN DESCRIPTION:
Mapping XS effe12d1
END DESCRIPTION:
XS GIS Cut Line= 4
      1465787.01      6807878.39      1466555.27      6807335.84
      1466616.03      6807123.17      1466464.33      6806672.41
#Sta/Elev= 30
    3958  2179.3  4178.7 2178.86  4208.3 2176.47  4237.1 2176.61  4273.5 2173.89
  4336.3 2173.82  4380.6 2171.65  4416.3 2172.39  4472.9 2169.87  4559.1 2169.56
  4631.7 2171.62    4739 2172.97  4811.6    2172  4861.5  2172.5  4913.8 2171.52
  4947.6 2170.23  4958.7 2168.59    4989 2167.86  4989.4 2167.36  4994.7 2167.86
  5064.6 2169.29  5093.2 2171.02  5188.5 2170.79    5229  2173.4  5265.8 2173.33
  5297.3 2175.72  5315.1 2175.68  5462.8 2181.64  5517.8    2183  5595.3 2183.06
#Mann= 4 ,-1 , 0
    3958     .07       0  4631.7     .16       0    4989     .07       0
  4994.7     .16       0
#XS Ineff= 2 , 0
       0    4739 2172.97               0
Permanent Ineff=
       F       F
Bank Sta=4989,4994.7
XS Rating Curve= 0 ,0
Exp/Cntr=0.3,0.1

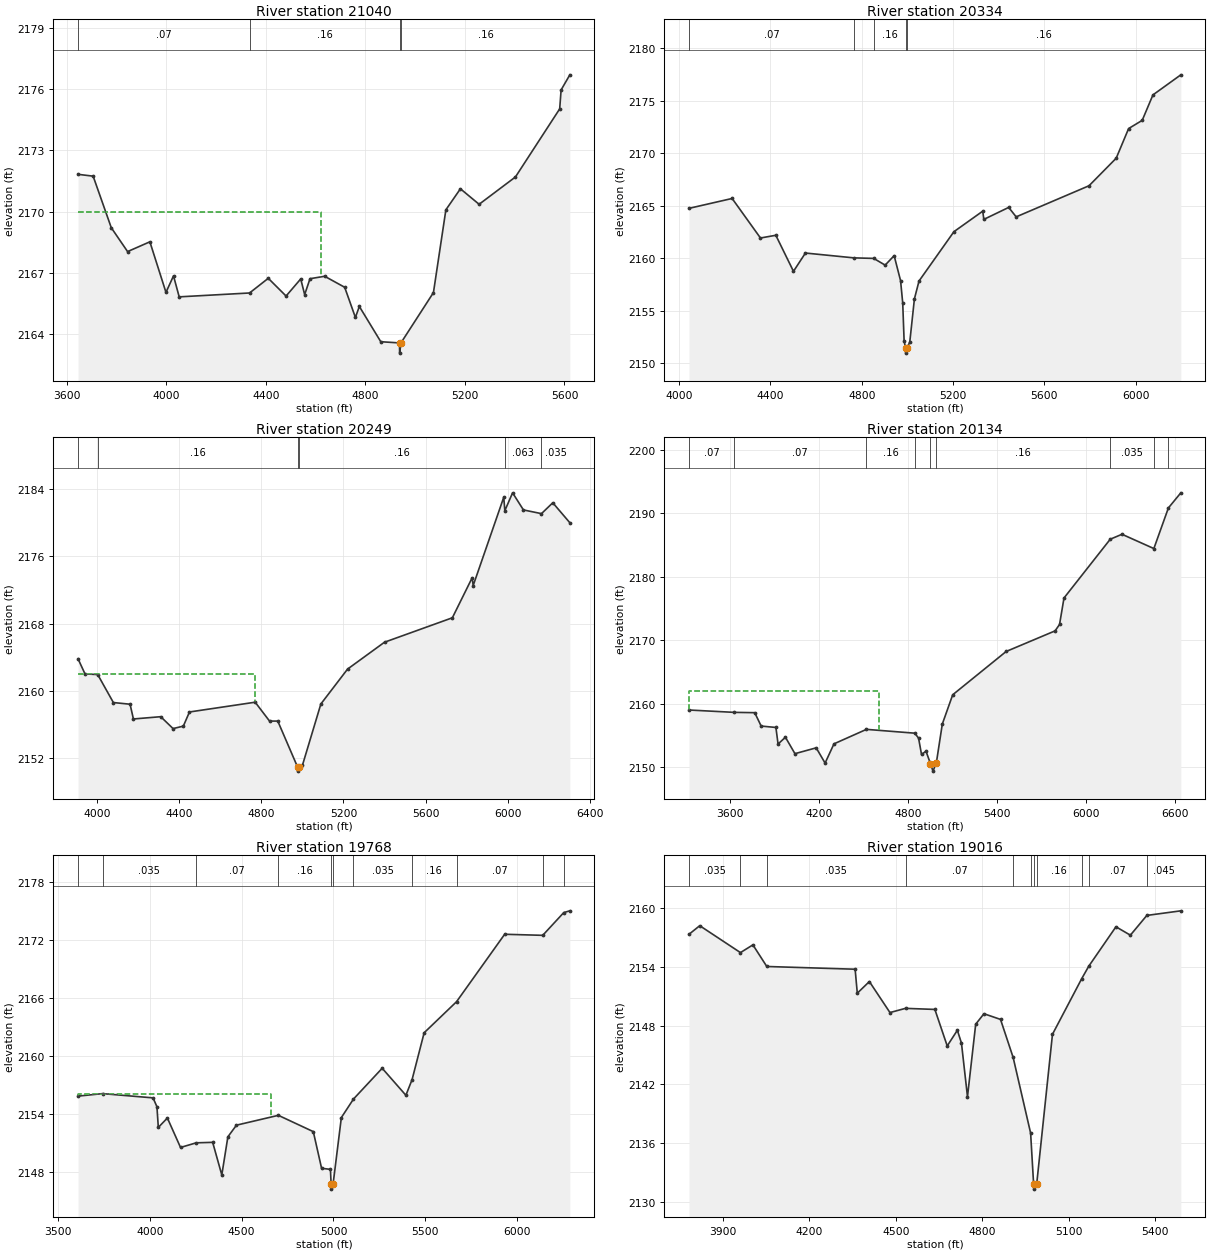
Type RM Length L Ch R = 1 ,21040   ,706,706,706
BEGIN DESCRIPTION:
Mapping XS 8ed41b4c
END DESCRIPTION:
XS GIS Cut Line= 3
      1466364.29      6808290.71      1466983.22      6807216.05
      1466622.09      6806573.65
#Sta/Elev= 30
  3644.4 2171.83  3705.2 2171.74  3778.2 2169.21  3843.7 2168.04  3933.3 2168.52
    3998 2166.04  4028.3 2166.85  4051.1 2165.82    4334 2166.01  4409.2 2166.73
  4480.8 2165.86  4539.7  2166.7  4555.5 2165.93    4577 2166.71  4635.9 2166.83
  4716.4 2166.29  4759.5 2164.81  4775.3 2165.35  4861.5 2163.62  4936.8 2163.56
  4937.3 2163.06  4942.5 2163.56  5073.2 2166.03  5123.2 2170.09  5181.6 2171.12
  5256.8 2170.36  5402.8  2171.7  5580.7 2175.04  5586.4 2175.97  5621.5 2176.71
#Mann= 4 ,-1 , 0
  3644.4     .07       0    4334     .16       0  4936.8     .07       0
  4942.5     .16       0
#XS Ineff= 2 , 0
       0  4620.1    2170               0
Permanent Ineff=
       F       F
Bank Sta=4936.8,4942.5
XS Rating Curve= 0 ,0
Exp/Cntr=0.3,0.1

Type RM Length L Ch R = 1 ,20334   ,85,85,85
BEGIN DESCRIPTION:
Mapping XS f301ed00
END DESCRIPTION:
XS GIS Cut Line= 4
      1466805.49       6808399.3      1467218.67      6807552.11
      1467260.34      6807270.86      1467100.62      6806357.72
#Sta/Elev= 30
  4043.6 2164.75  4232.5 2165.69  4356.6 2161.93  4423.9 2162.19  4501.2 2158.76
  4553.5  2160.5  4765.8 2160.04  4852.6 2159.99  4902.6 2159.35  4942.1 2160.25
  4970.2 2157.87  4979.6 2155.75  4985.7 2152.14  4992.1 2151.48  4992.6 2150.98
  4998.6 2151.48  5010.5 2152.03  5030.8 2156.14    5051 2157.84  5203.8 2162.53
  5329.9 2164.48  5334.9  2163.7  5443.7 2164.84  5476.4 2163.94  5795.5  2166.9
  5914.5 2169.52  5968.9 2172.34  6028.4 2173.12  6075.4 2175.54  6197.5 2177.45
#Mann= 5 ,-1 , 0
  4043.6     .07       0  4765.8     .16       0  4852.6     .16       0
  4992.1     .07       0  4998.6     .16       0
Bank Sta=4992.1,4998.6
XS Rating Curve= 0 ,0
Exp/Cntr=0.3,0.1

Type RM Length L Ch R = 1 ,20249   ,115,115,115
BEGIN DESCRIPTION:
Mapping XS 79df8c98
END DESCRIPTION:
XS GIS Cut Line= 6
      1467012.92      6808470.55       1467280.3      6808328.15
      1467305.84      6807554.12      1467295.93      6807118.08
      1467257.73      6806517.39      1467162.79      6806252.54
#Sta/Elev= 30
  3906.4 2163.82  3940.4 2162.02  4002.4 2161.94  4078.7 2158.62  4160.1 2158.42
  4176.4 2156.67  4309.5 2156.94  4369.6 2155.53  4419.6 2155.82  4449.6  2157.5
  4769.8 2158.66  4839.8 2156.42  4879.9 2156.42  4976.1 2150.98  4976.6 2150.48
  4982.6 2150.98  4999.9 2151.16  5089.9 2158.45    5220 2162.59    5400 2165.78
  5730.7 2168.68  5827.2 2173.43  5832.2 2172.51  5981.1 2182.98  5986.4 2181.39
  6024.2 2183.51    6077 2181.48  6164.9 2181.04  6220.1 2182.33  6303.2 2179.96
#Mann= 6 ,-1 , 0
  3906.4     .07       0  4002.4     .16       0  4976.1     .07       0
  4982.6     .16       0  5986.4    .063       0  6164.9    .035       0
#XS Ineff= 2 , 0
       0  4769.8    2162               0
Permanent Ineff=
       F       F
Bank Sta=4976.1,4982.6
XS Rating Curve= 0 ,0
Exp/Cntr=0.3,0.1

Type RM Length L Ch R = 1 ,20134   ,366,366,366
BEGIN DESCRIPTION:
Mapping XS 15935705
END DESCRIPTION:
XS GIS Cut Line= 6
      1466839.69      6808945.61      1467416.95      6808489.88
      1467425.63      6807248.56      1467416.95       6806627.9
      1467403.93      6806432.59      1467440.42      6805912.34
#Sta/Elev= 30
  3325.3    2159  3629.4 2158.63  3768.4 2158.58  3811.8 2156.47  3911.1 2156.25
  3925.6 2153.64  3975.3 2154.71  4039.4 2152.12  4182.6 2153.04  4242.6 2150.64
  4302.6 2153.67  4521.4 2155.95    4847 2155.35  4872.6 2154.57  4892.6 2151.99
  4922.6 2152.52  4952.6 2150.56  4969.9 2149.37  4992.7 2150.71  5032.7 2156.79
  5102.7  2161.4  5462.8 2168.22  5792.8 2171.47  5822.8 2172.48  5852.8 2176.65
  6164.5 2185.91  6243.6 2186.69  6458.5 2184.44  6556.5 2190.84  6640.2 2193.22
#Mann= 9 ,-1 , 0
  3325.3     .07       0  3629.4     .07       0  4521.4     .16       0
    4847     .16       0  4952.6     .07       0  4992.7     .16       0
  6164.5    .035       0  6458.5     .16       0  6556.5     .07       0
#XS Ineff= 2 , 0
       0  4602.6    2162               0
Permanent Ineff=
       F       F
Bank Sta=4952.6,4992.7
XS Rating Curve= 0 ,0
Exp/Cntr=0.3,0.1

Type RM Length L Ch R = 1 ,19768   ,752,752,752
BEGIN DESCRIPTION:
Mapping XS f8867216
END DESCRIPTION:
XS GIS Cut Line= 5
      1466974.56      6808973.36      1467429.39      6808594.92
      1467634.25       6807834.5       1468415.5      6807275.47
      1468730.75      6807150.76
#Sta/Elev= 30
  3608.6 2155.83  3742.3 2156.09  4017.3 2155.65  4038.5 2154.73    4046 2152.59
  4095.4 2153.56    4167 2150.51  4252.5 2150.99  4342.1 2151.04  4391.8 2147.66
  4424.9 2151.61  4471.6 2152.82  4699.9 2153.84  4890.2 2152.15  4935.3 2148.35
  4983.4 2148.24  4987.4 2146.69  4987.9 2146.19  4997.8 2146.69    5043 2153.61
  5109.1 2155.53  5265.4 2158.72  5394.5 2155.92  5428.2 2157.54  5493.9  2162.4
  5670.4 2165.62  5932.5 2172.61  6139.8  2172.5  6254.5 2174.86  6287.5 2175.04
#Mann= 11 ,-1 , 0
  3608.6     .07       0  3742.3    .035       0  4252.5     .07       0
  4699.9     .16       0  4987.4     .07       0  4997.8     .16       0
  5109.1    .035       0  5428.2     .16       0  5670.4     .07       0
  6139.8     .16       0  6254.5     .07       0
#XS Ineff= 2 , 0
       0    4661    2156               0
Permanent Ineff=
       F       F
Bank Sta=4987.4,4997.8
XS Rating Curve= 0 ,0
Exp/Cntr=0.3,0.1

Type RM Length L Ch R = 1 ,19016   ,467,467,467
BEGIN DESCRIPTION:
Mapping XS fc974419
END DESCRIPTION:
XS GIS Cut Line= 3
      1466871.38      6809177.05      1467652.67      6808508.62
      1468329.78      6808478.23
#Sta/Elev= 30
  3782.2 2157.35  3819.5 2158.23  3960.7 2155.48  4003.9 2156.27  4052.1 2154.06
  4358.5 2153.78    4366 2151.33  4407.9 2152.52  4479.3 2149.35  4533.2 2149.78
  4635.1 2149.67  4677.9 2145.94  4713.1 2147.54  4727.3 2146.23  4748.2 2140.75
  4776.7 2148.16  4805.3 2149.23  4862.8 2148.65  4906.6 2144.76  4967.2 2137.03
  4977.6  2131.8  4978.1  2131.3  4988.2  2131.8    5043 2147.13  5144.7 2152.83
  5168.9 2154.09  5263.2 2158.12  5313.2 2157.26  5370.3 2159.28  5488.2 2159.75
#Mann= 11 ,-1 , 0
  3782.2    .035       0  3960.7     .07       0  4052.1    .035       0
  4533.2     .07       0  4906.6     .16       0  4967.2     .16       0
  4977.6     .07       0  4988.2     .16       0  5144.7     .16       0
  5168.9     .07       0  5370.3    .045       0
#XS Ineff= 2 , 0
       0  4805.3 2149.23               0
Permanent Ineff=
       F       F
Bank Sta=4977.6,4988.2
XS Rating Curve= 0 ,0
Exp/Cntr=0.3,0.1