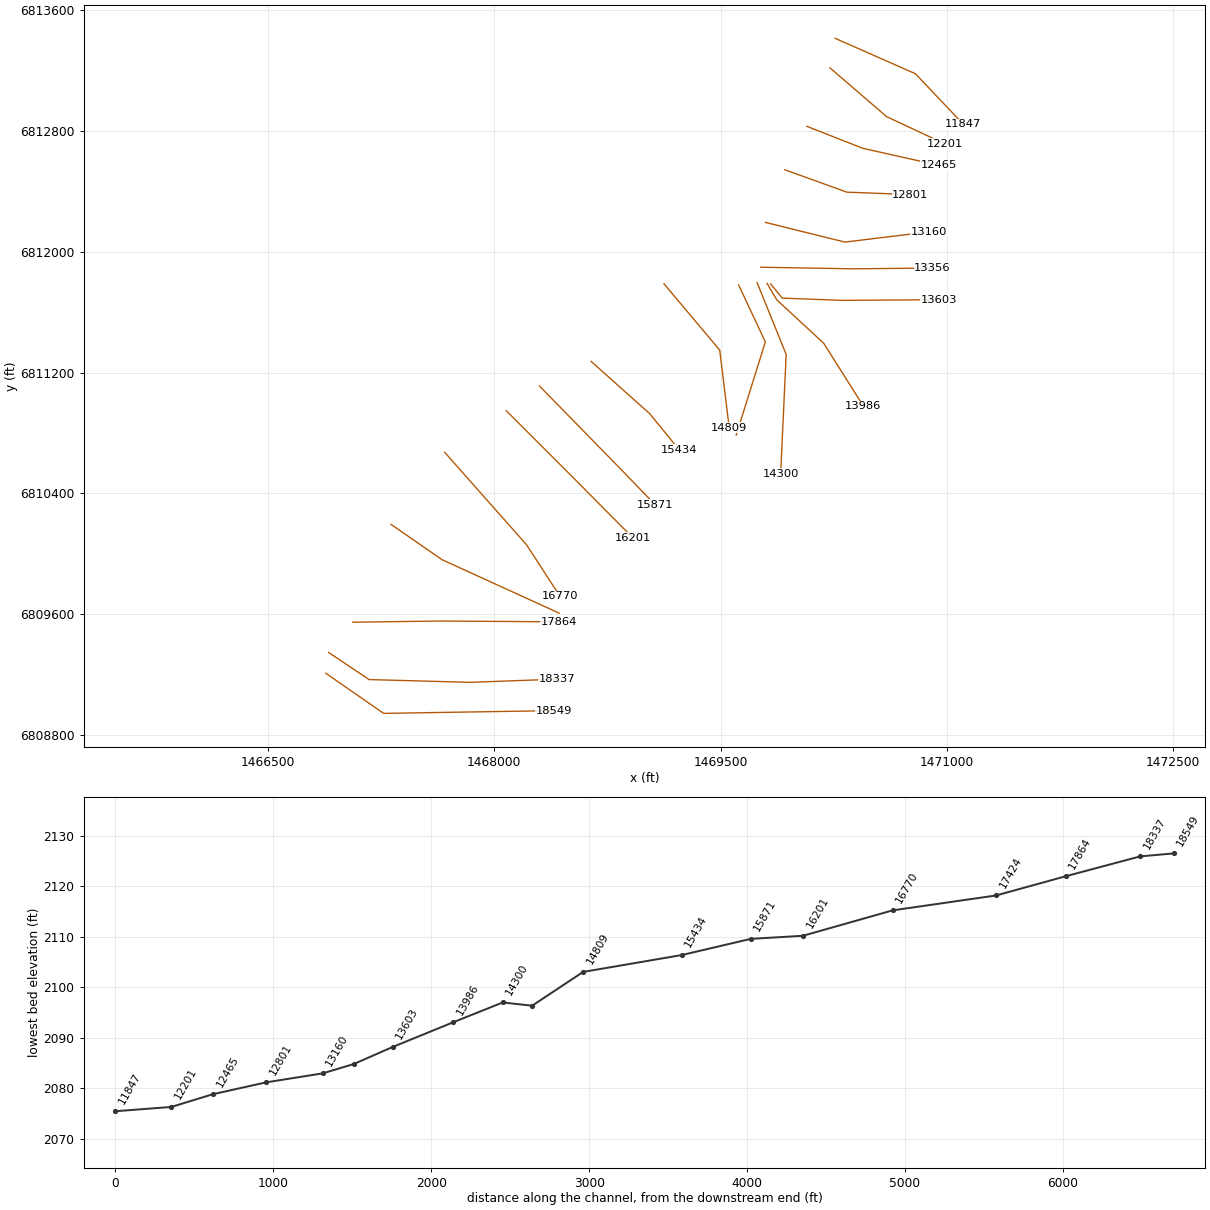
HEC-RAS study MULBERRY CREEK TRIBUTARY 21A.prj: MULBERRY CREEK TRIBUTARY 21A Base Level Engineering

--- MULBERRY CREEK TRIBUTARY 21A.g01 (geometry) --- (continued)

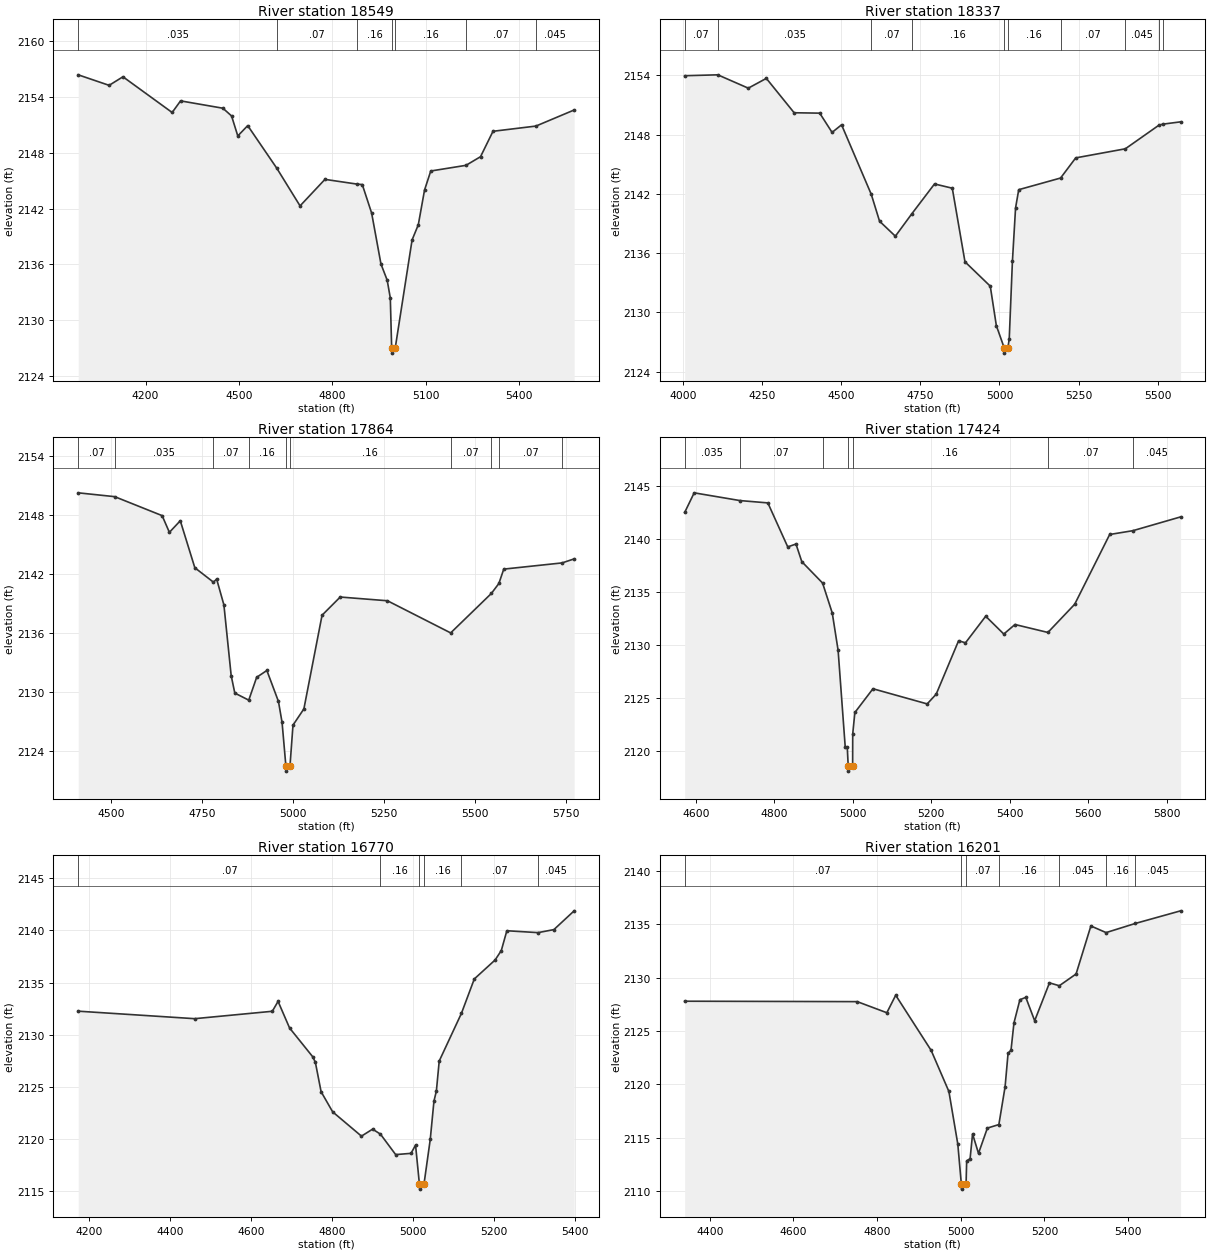
Type RM Length L Ch R = 1 ,18549   ,212,212,212
BEGIN DESCRIPTION:
Mapping XS cfa30e48
END DESCRIPTION:
XS GIS Cut Line= 3
       1466885.3      6809207.41      1467268.12      6808941.78
      1468395.72      6808960.01
#Sta/Elev= 30
  3983.7 2156.38    4083 2155.25  4127.5 2156.17  4285.6 2152.33  4312.6 2153.58
  4448.6 2152.79  4476.5 2151.96  4496.5 2149.81  4528.4 2150.92  4621.8 2146.34
  4696.6 2142.29  4776.6 2145.14  4880.2 2144.63  4896.6 2144.58  4926.6 2141.52
  4956.6 2136.04  4976.6  2134.3  4986.6 2132.39    4991 2126.96  4991.5 2126.46
  5002.2 2126.96  5056.6 2138.63  5076.6 2140.26  5096.6 2143.99  5116.6 2146.04
  5229.8 2146.65  5276.6 2147.58  5316.6 2150.31  5454.5 2150.87  5577.4  2152.6
#Mann= 7 ,-1 , 0
  3983.7    .035       0  4621.8     .07       0  4880.2     .16       0
    4991     .07       0  5002.2     .16       0  5229.8     .07       0
  5454.5    .045       0
Bank Sta=4991,5002.2
XS Rating Curve= 0 ,0
Exp/Cntr=0.3,0.1

Type RM Length L Ch R = 1 ,18337   ,473,473,473
BEGIN DESCRIPTION:
Mapping XS 4d6c8fa5
END DESCRIPTION:
XS GIS Cut Line= 4
      1466903.57       6809345.4      1467171.76      6809165.74
      1467838.43      6809147.51      1468416.53      6809168.34
#Sta/Elev= 30
  4004.6 2153.96  4109.3 2154.05  4205.7  2152.7  4262.8 2153.69  4350.7 2150.21
  4431.6 2150.17  4470.7 2148.22  4500.7 2148.99  4594.6 2141.95  4620.8 2139.23
  4670.8 2137.71  4722.4 2139.96  4794.6    2143  4850.8 2142.57  4890.9 2135.12
  4970.9 2132.65  4990.1 2128.66  5015.3 2126.37  5015.8 2125.87  5026.5 2126.37
  5030.9 2127.31  5040.9 2135.15  5050.9 2140.58  5060.9 2142.42  5193.2  2143.6
  5241.1 2145.64    5398 2146.56  5504.6 2148.96  5517.7 2149.06  5572.8 2149.29
#Mann= 10 ,-1 , 0
  4004.6     .07       0  4109.3    .035       0  4594.6     .07       0
  4722.4     .16       0  5015.3     .07       0  5026.5     .16       0
  5193.2     .07       0    5398    .045       0  5504.6     .07       0
  5517.7    .045       0
Bank Sta=5015.3,5026.5
XS Rating Curve= 0 ,0
Exp/Cntr=0.3,0.1

Type RM Length L Ch R = 1 ,17864   ,440,440,440
BEGIN DESCRIPTION:
Mapping XS f1eef065
END DESCRIPTION:
XS GIS Cut Line= 3
      1467064.09      6809545.94      1467642.25      6809553.76
      1468428.72      6809548.55
#Sta/Elev= 30
  4408.9 2150.24  4509.3 2149.85  4639.8 2147.92  4659.8 2146.22  4689.8  2147.4
  4729.8 2142.62  4781.1 2141.15  4789.8 2141.47  4809.8 2138.84  4829.8 2131.65
  4839.8 2129.87  4878.2 2129.15  4899.9 2131.47    4928 2132.17  4959.9 2129.02
  4969.9 2126.88  4980.4 2122.43  4980.9 2121.93  4991.6 2122.43  4999.9 2126.61
  5029.9 2128.26  5079.9 2137.79  5129.9 2139.64  5259.9 2139.26  5433.8 2135.99
  5545.7    2140  5566.5 2141.02  5579.9 2142.48  5740.3 2143.11  5773.6 2143.52
#Mann= 10 ,-1 , 0
  4408.9     .07       0  4509.3    .035       0  4781.1     .07       0
  4878.2     .16       0  4980.4     .07       0  4991.6     .16       0
  5433.8     .07       0  5545.7    .045       0  5566.5     .07       0
  5740.3    .045       0
Bank Sta=4980.4,4991.6
XS Rating Curve= 0 ,0
Exp/Cntr=0.3,0.1

Type RM Length L Ch R = 1 ,17424   ,654,654,654
BEGIN DESCRIPTION:
Mapping XS fb41d052
END DESCRIPTION:
XS GIS Cut Line= 3
      1467316.69      6810194.41      1467655.27      6809960.01
      1468430.64      6809606.15
#Sta/Elev= 30
  4571.6 2142.54  4595.8 2144.39  4712.4 2143.66  4783.6 2143.44  4834.3 2139.29
  4855.3 2139.56  4870.1  2137.9  4923.1 2135.88  4947.8 2133.05  4962.7 2129.53
  4980.8 2120.42    4986 2120.42  4988.4 2118.64  4988.9 2118.14  4999.7 2118.64
  4999.9 2121.64  5005.4 2123.67  5051.5 2125.91  5189.7 2124.48  5212.7  2125.4
  5269.8 2130.44  5287.3 2130.24  5338.9 2132.75    5385 2131.07  5413.5 2131.97
  5497.4 2131.22  5565.7 2133.88  5654.9 2140.46  5714.1 2140.82  5835.7 2142.12
#Mann= 7 ,-1 , 0
  4571.6    .035       0  4712.4     .07       0  4923.1     .16       0
  4988.4     .07       0  4999.7     .16       0  5497.4     .07       0
  5714.1    .045       0
Bank Sta=4988.4,4999.7
XS Rating Curve= 0 ,0
Exp/Cntr=0.3,0.1

Type RM Length L Ch R = 1 ,16770   ,569,569,569
BEGIN DESCRIPTION:
Mapping XS db3f54b0
END DESCRIPTION:
XS GIS Cut Line= 3
      1467672.65      6810671.79       1468214.3      6810059.83
      1468435.65      6809718.69
#Sta/Elev= 30
  4173.2 2132.26  4460.6 2131.54  4652.2 2132.25  4666.4  2133.2  4694.8 2130.65
  4751.7  2127.9  4758.4 2127.37  4772.6 2124.54  4801.1 2122.61  4872.2 2120.28
  4899.7 2120.95  4919.1 2120.47  4956.6 2118.51  4994.5 2118.63  5005.7 2119.42
  5015.2  2115.7  5015.7  2115.2  5026.6  2115.7    5042 2119.97  5051.1 2123.63
  5057.1 2124.61  5064.1 2127.48  5118.9 2132.05  5150.7 2135.35  5202.1 2137.17
  5217.3 2138.07    5231 2139.97    5308 2139.79  5347.1 2140.08  5397.1 2141.88
#Mann= 6 ,-1 , 0
  4173.2     .07       0  4919.1     .16       0  5015.2     .07       0
  5026.6     .16       0  5118.9     .07       0    5308    .045       0
Bank Sta=5015.2,5026.6
XS Rating Curve= 0 ,0
Exp/Cntr=0.3,0.1

Type RM Length L Ch R = 1 ,16201   ,330,330,330
BEGIN DESCRIPTION:
Mapping XS 25ed8b0d
END DESCRIPTION:
XS GIS Cut Line= 3
      1468080.63      6810947.19      1468563.26      6810464.56
      1468917.44       6810106.9
#Sta/Elev= 30
  4339.8 2127.78  4752.4 2127.74  4823.2  2126.7  4844.4 2128.34  4929.2 2123.17
  4971.6 2119.32  4992.9 2114.39  5001.3 2110.67  5001.8 2110.17  5012.7 2110.67
  5014.1 2112.82  5022.3 2113.02  5028.2 2115.34  5042.4 2113.52  5063.6 2115.89
  5091.1 2116.22    5106 2119.77  5113.1 2122.91  5120.1 2123.18  5127.2 2125.75
  5141.4 2127.92  5155.5 2128.14  5176.7 2125.95  5212.1  2129.5  5235.6 2129.23
  5275.7 2130.33  5311.1 2134.83  5347.5 2134.21  5417.6 2135.07  5525.7 2136.25
#Mann= 7 ,-1 , 0
  4339.8     .07       0  5001.3     .07       0  5012.7     .07       0
  5091.1     .16       0  5235.6    .045       0  5347.5     .16       0
  5417.6    .045       0
Bank Sta=5001.3,5012.7
XS Rating Curve= 0 ,0
Exp/Cntr=0.3,0.1

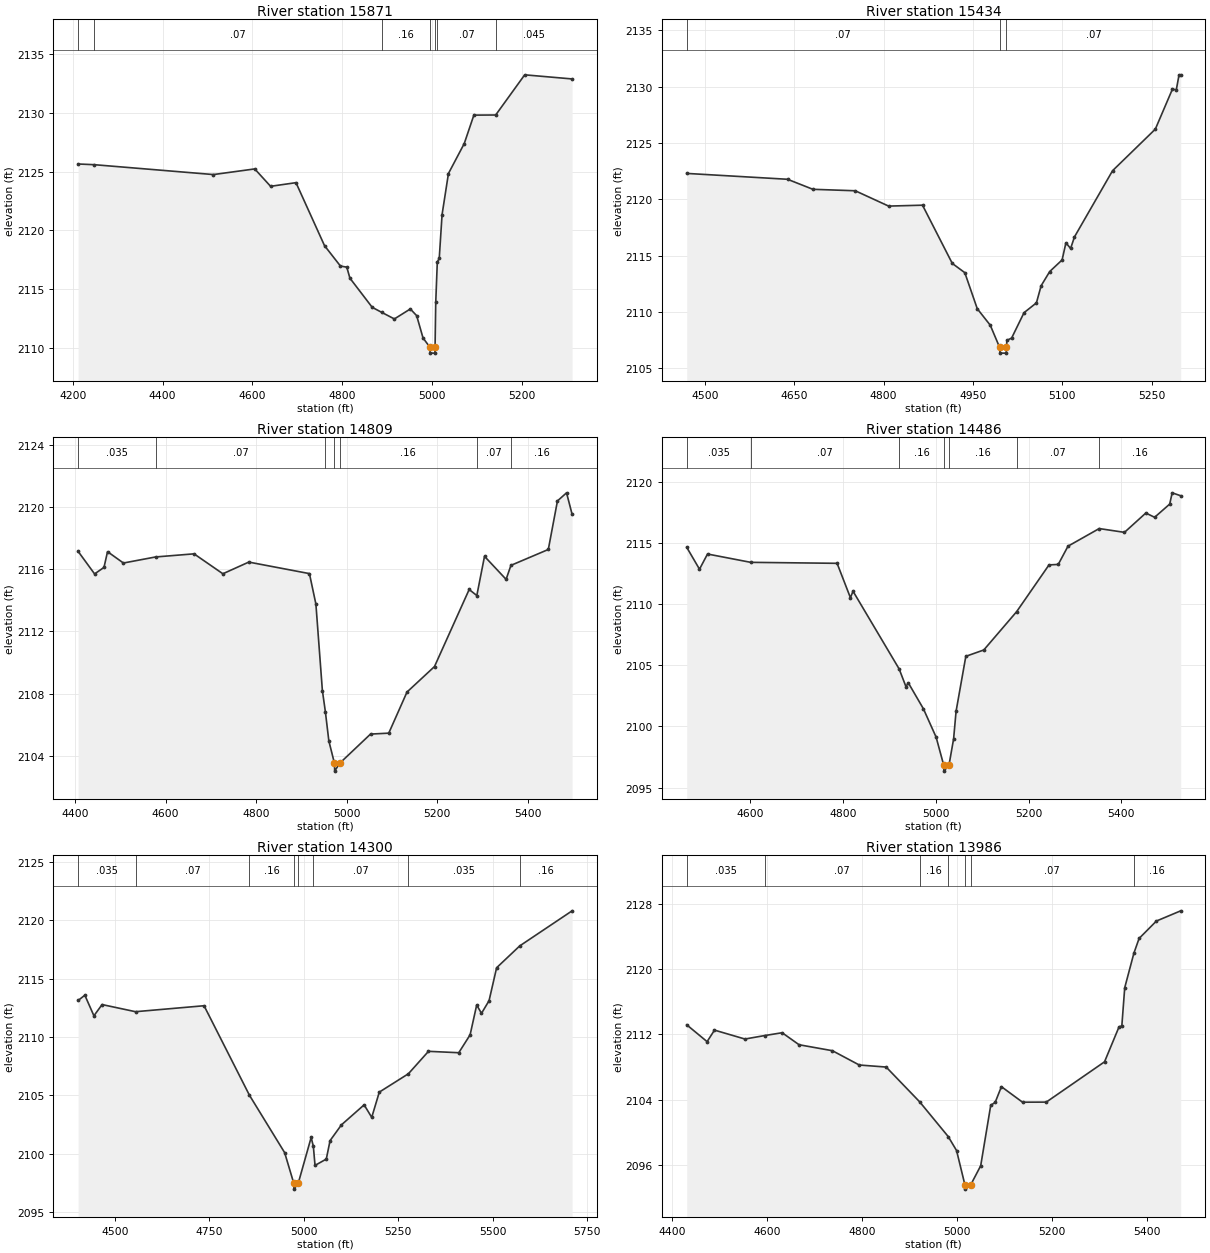
Type RM Length L Ch R = 1 ,15871   ,437,437,437
BEGIN DESCRIPTION:
Mapping XS 01d91fe5
END DESCRIPTION:
XS GIS Cut Line= 3
      1468301.29      6811110.39      1468861.17      6810537.48
       1469068.7      6810322.17
#Sta/Elev= 30
  4211.7 2125.66  4247.8  2125.6    4513 2124.76    4605 2125.24  4640.3 2123.76
  4696.9 2124.07  4760.4 2118.71  4795.9 2116.97    4810 2116.88    4817 2115.94
  4866.6 2113.46  4888.3 2113.02    4916 2112.47  4951.5 2113.32  4965.6 2112.75
  4979.8 2110.85  4995.2 2110.06  4995.7 2109.56  5006.1 2109.56  5006.6 2110.06
  5008.1 2113.87  5011.6 2117.32  5015.9 2117.62  5022.2 2121.35  5036.4 2124.85
  5071.6  2127.4    5093 2129.82  5141.6 2129.83  5206.2 2133.25  5311.8  2132.9
#Mann= 7 ,-1 , 0
  4211.7    .035       0  4247.8     .07       0  4888.3     .16       0
  4995.2     .07       0  5006.6     .16       0  5011.6     .07       0
  5141.6    .045       0
Bank Sta=4995.2,5006.6
XS Rating Curve= 0 ,0
Exp/Cntr=0.3,0.1

Type RM Length L Ch R = 1 ,15434   ,625,625,625
BEGIN DESCRIPTION:
Mapping XS 753c28c1
END DESCRIPTION:
XS GIS Cut Line= 3
      1468642.41      6811274.47      1469030.44      6810928.11
      1469225.73      6810688.56
#Sta/Elev= 30
  4469.5 2122.31  4638.7 2121.79  4681.3  2120.9  4752.4 2120.77  4808.4 2119.41
  4865.3 2119.49  4915.3 2114.32  4936.3  2113.5  4957.2  2110.3    4979 2108.84
  4994.8 2106.86  4995.3 2106.36  5005.7 2106.36  5006.2 2106.86  5006.9 2107.49
  5014.9  2107.7  5035.7 2109.95  5056.5 2110.82  5064.4 2112.34  5078.8  2113.6
  5099.6 2114.63    5106 2116.15  5113.9 2115.65  5120.4 2116.68  5184.3 2122.55
  5256.1 2126.24  5284.8 2129.79  5291.3 2129.73  5295.9 2131.06  5298.7 2131.06
#Mann= 3 ,-1 , 0
  4469.5     .07       0  4994.8     .07       0  5006.2     .07       0
Bank Sta=4994.8,5006.2
XS Rating Curve= 0 ,0
Exp/Cntr=0.3,0.1

Type RM Length L Ch R = 1 ,14809   ,323,323,323
BEGIN DESCRIPTION:
Mapping XS e7473531
END DESCRIPTION:
XS GIS Cut Line= 3
      1469125.03      6811788.96      1469494.85      6811348.82
      1469557.35       6810835.8
#Sta/Elev= 30
  4406.5 2117.14  4442.9 2115.69  4463.7 2116.11  4471.5 2117.12  4506.6 2116.39
  4577.8 2116.78  4662.7 2116.98  4726.4  2115.7  4783.7 2116.45  4917.7 2115.71
    4932 2113.75  4946.3  2108.2  4952.9 2106.84  4960.6 2104.96    4973 2103.52
  4973.5 2103.02  4984.4 2103.52  5052.7  2105.4    5093 2105.46  5133.3  2108.1
  5194.1 2109.74  5270.7 2114.69  5287.6  2114.3  5304.6 2116.82  5352.3 2115.34
    5363 2116.24  5445.6 2117.26  5465.8 2120.38  5485.9  2120.9  5498.2 2119.52
#Mann= 7 ,-1 , 0
  4406.5    .035       0  4577.8     .07       0  4952.9     .16       0
    4973     .07       0  4984.4     .16       0  5287.6     .07       0
    5363     .16       0
Bank Sta=4973,4984.4
XS Rating Curve= 0 ,0
Exp/Cntr=0.3,0.1

Type RM Length L Ch R = 1 ,14486   ,186,186,186
BEGIN DESCRIPTION:
Mapping XS 49ff7480
END DESCRIPTION:
XS GIS Cut Line= 3
      1469619.83      6811781.16      1469796.94      6811403.51
      1469604.23      6810786.31
#Sta/Elev= 30
    4464 2114.63  4491.5 2112.84  4508.8 2114.08  4601.8  2113.4  4787.8 2113.32
  4816.5 2110.51  4822.1 2111.04  4921.4 2104.69    4936 2103.25  4941.2 2103.55
  4973.7 2101.43    5001 2099.12  5017.3 2096.84  5017.8 2096.34  5028.8 2096.84
  5038.7 2098.98    5044 2101.23    5065 2105.72  5103.7 2106.24  5174.4 2109.37
  5244.1 2113.19    5264 2113.23    5285 2114.72  5352.2 2116.16  5406.6 2115.85
  5452.6 2117.43  5471.5 2117.08    5504 2118.16  5509.3 2119.08  5527.7 2118.84
#Mann= 7 ,-1 , 0
    4464    .035       0  4601.8     .07       0  4921.4     .16       0
  5017.3     .07       0  5028.8     .16       0  5174.4     .07       0
  5352.2     .16       0
Bank Sta=5017.3,5028.8
XS Rating Curve= 0 ,0
Exp/Cntr=0.3,0.1

Type RM Length L Ch R = 1 ,14300   ,314,314,314
BEGIN DESCRIPTION:
Mapping XS 2098289b
END DESCRIPTION:
XS GIS Cut Line= 3
      1469742.23      6811796.78      1469934.96      6811320.18
       1469898.5      6810528.51
#Sta/Elev= 30
  4403.2 2113.12    4421 2113.57    4445 2111.81  4466.6 2112.77    4555 2112.16
  4736.3 2112.67  4856.4 2105.01  4949.5  2100.1  4973.6 2097.48  4974.1 2096.98
  4985.4 2097.48  5019.6  2101.4  5025.4 2100.64  5029.8 2099.01  5059.6 2099.55
  5069.6 2101.13  5099.7 2102.48  5159.7 2104.19  5179.8 2103.12  5199.8 2105.28
  5276.8 2106.85  5329.9 2108.77    5410 2108.65    5440 2110.18  5457.4 2112.73
  5470.1 2112.02  5490.1  2113.1  5510.1 2115.92  5571.3 2117.79  5709.8 2120.79
#Mann= 8 ,-1 , 0
  4403.2    .035       0    4555     .07       0  4856.4     .16       0
  4973.6     .07       0  4985.4     .16       0  5025.4     .07       0
  5276.8    .035       0  5571.3     .16       0
Bank Sta=4973.6,4985.4
XS Rating Curve= 0 ,0
Exp/Cntr=0.3,0.1

Type RM Length L Ch R = 1 ,13986   ,383,383,383
BEGIN DESCRIPTION:
Mapping XS 34cd6b37
END DESCRIPTION:
XS GIS Cut Line= 4
      1469808.45      6811790.64      1469873.54      6811681.29
      1470183.44      6811394.83      1470446.46      6810978.17
#Sta/Elev= 30
  4430.1 2113.17  4473.1 2111.11  4488.7 2112.52  4552.9 2111.43  4595.1 2111.86
  4631.4  2112.2  4667.1 2110.73  4737.4    2110  4794.1 2108.25  4850.8    2108
  4921.5 2103.74  4981.6  2099.5  4999.3 2097.78    5017 2093.56  5017.5 2093.06
  5028.9 2093.56  5050.2 2095.92  5071.4 2103.33  5080.7 2103.67  5093.9  2105.6
  5138.4  2103.7  5188.5 2103.71  5311.4 2108.64    5342 2112.92  5347.9 2113.04
    5354 2117.71  5373.3 2121.93  5384.3 2123.74  5420.8 2125.87  5472.1 2127.12
#Mann= 7 ,-1 , 0
  4430.1    .035       0  4595.1     .07       0  4921.5     .16       0
  4981.6     .07       0    5017     .07       0  5028.9     .07       0
  5373.3     .16       0
Bank Sta=5017,5028.9
XS Rating Curve= 0 ,0
Exp/Cntr=0.3,0.1

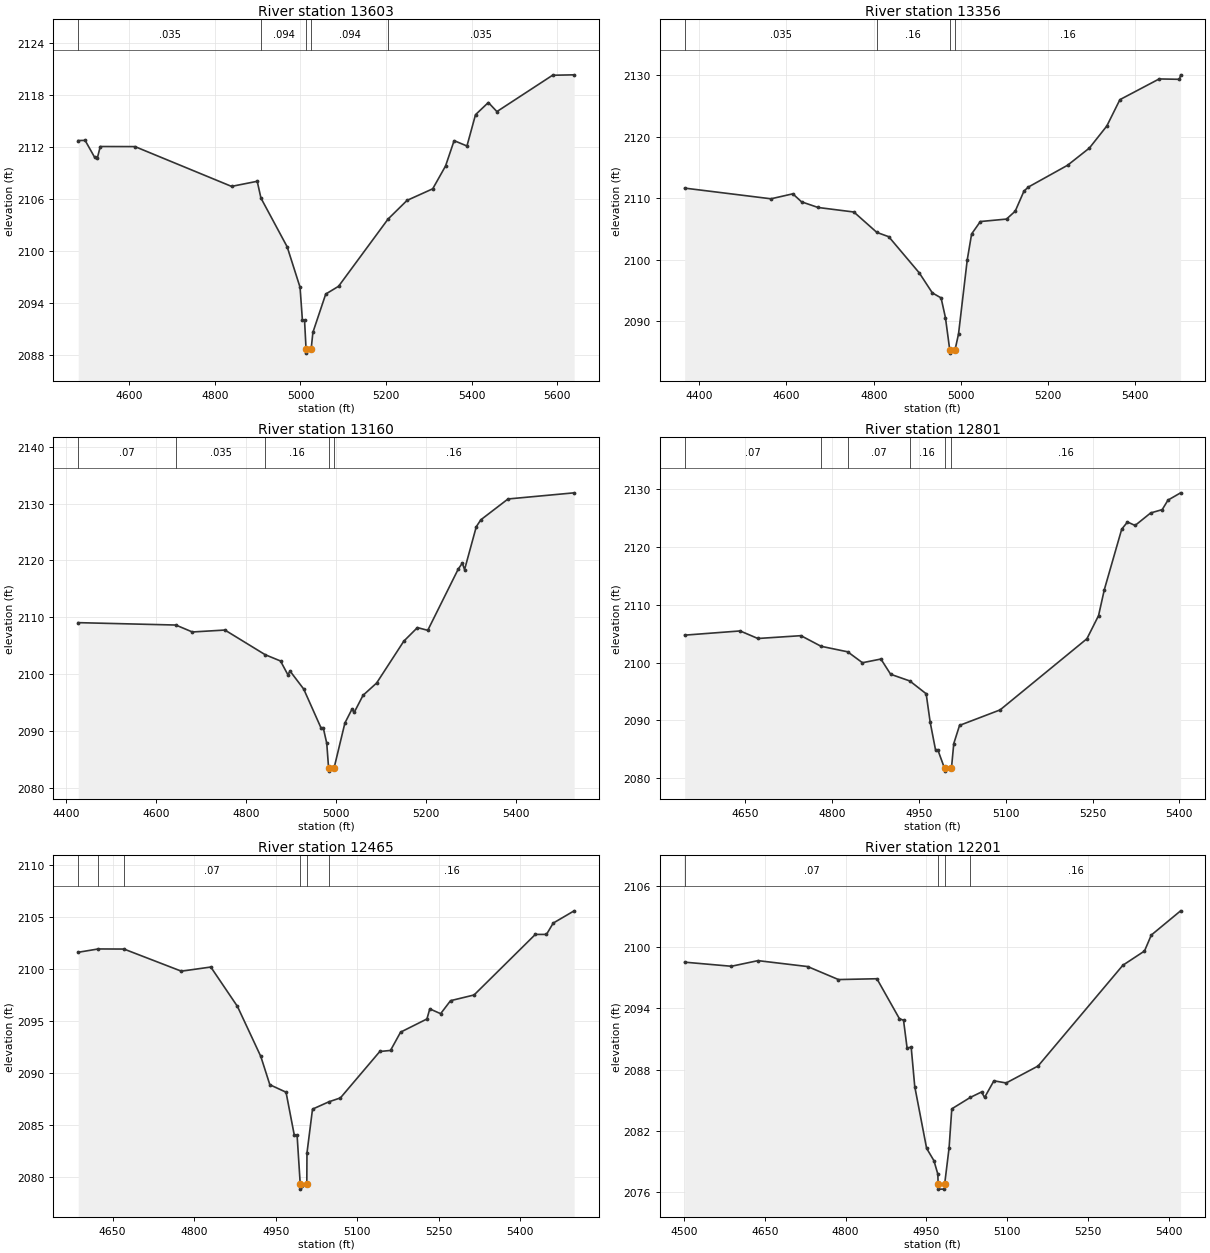
Type RM Length L Ch R = 1 ,13603   ,247,247,247
BEGIN DESCRIPTION:
Mapping XS 59fe925b
END DESCRIPTION:
XS GIS Cut Line= 4
      1469831.89      6811788.04      1469909.03      6811693.37
      1470311.04      6811678.68      1470945.52      6811682.95
#Sta/Elev= 30
  4480.7 2112.76  4496.8 2112.78  4519.1 2110.82  4525.6 2110.78  4532.3 2112.07
  4613.4 2112.06    4839 2107.46    4899 2108.05  4907.7 2106.11    4969 2100.47
  4999.1 2095.79  5004.6 2091.97  5009.6 2091.97  5013.1 2088.68  5013.6 2088.18
  5025.1 2088.68  5029.1 2090.58  5059.1 2095.01  5089.1 2095.91  5204.7 2103.68
  5249.1 2105.84  5309.1 2107.18  5339.1 2109.82  5359.1 2112.75  5389.1 2112.13
  5409.1 2115.75  5439.1 2117.16  5459.1 2116.11  5589.1 2120.31  5639.6 2120.36
#Mann= 5 ,-1 , 0
  4480.7    .035       0  4907.7    .094       0  5013.1     .07       0
  5025.1    .094       0  5204.7    .035       0
Bank Sta=5013.1,5025.1
XS Rating Curve= 0 ,0
Exp/Cntr=0.3,0.1

Type RM Length L Ch R = 1 ,13356   ,196,196,196
BEGIN DESCRIPTION:
Mapping XS 10b6ceb0
END DESCRIPTION:
XS GIS Cut Line= 3
      1469767.18      6811898.23      1470381.77      6811887.81
      1470904.16      6811893.01
#Sta/Elev= 30
  4366.6 2111.66  4564.5 2109.92  4614.5 2110.73  4634.5 2109.43  4672.3 2108.51
  4754.5 2107.77  4807.2 2104.45  4834.5 2103.75  4904.5 2097.86  4934.5  2094.6
  4954.5 2093.79  4964.5 2090.57  4974.4  2085.3  4974.9  2084.8  4986.4  2085.3
  4994.5 2087.93  5014.5 2099.99  5024.5  2104.2  5044.5 2106.22  5104.5 2106.62
  5124.5 2107.91  5144.5 2111.17  5154.5 2111.83  5244.5 2115.38  5294.5 2118.18
  5334.5 2121.77  5364.5 2126.06  5454.5 2129.43  5501.1 2129.37  5503.7  2130.1
#Mann= 4 ,-1 , 0
  4366.6    .035       0  4807.2     .16       0  4974.4     .07       0
  4986.4     .16       0
Bank Sta=4974.4,4986.4
XS Rating Curve= 0 ,0
Exp/Cntr=0.3,0.1

Type RM Length L Ch R = 1 ,13160   ,359,359,359
BEGIN DESCRIPTION:
Mapping XS 24375ab3
END DESCRIPTION:
XS GIS Cut Line= 3
      1469798.45       6812195.1      1470324.48       6812064.9
      1470880.88       6812132.5
#Sta/Elev= 30
  4427.1 2109.07  4644.1 2108.65  4680.8 2107.43  4753.2 2107.77  4842.8 2103.43
  4876.8 2102.33    4893 2099.93  4898.1 2100.54  4928.3  2097.4  4966.7 2090.58
  4971.8 2090.58  4979.6 2087.84  4983.7 2083.46  4984.2 2082.96  4995.7 2083.46
  5019.9 2091.42  5035.6 2093.85  5040.6 2093.29  5060.2 2096.29  5090.4 2098.45
  5150.9 2105.82  5181.1  2108.2  5204.1 2107.72  5271.7 2118.47  5280.9 2119.54
  5285.9  2118.4    5312 2125.95  5322.1 2127.16  5382.5 2130.82  5529.5  2131.9
#Mann= 5 ,-1 , 0
  4427.1     .07       0  4644.1    .035       0  4842.8     .16       0
  4983.7     .07       0  4995.7     .16       0
Bank Sta=4983.7,4995.7
XS Rating Curve= 0 ,0
Exp/Cntr=0.3,0.1

Type RM Length L Ch R = 1 ,12801   ,336,336,336
BEGIN DESCRIPTION:
Mapping XS 275bf89d
END DESCRIPTION:
XS GIS Cut Line= 3
        1469926.      6812544.08       1470337.5      6812395.63
      1470756.75        6812380.
#Sta/Elev= 30
  4545.1 2104.75  4640.9 2105.48  4671.6 2104.17    4746 2104.66  4780.8 2102.82
  4826.8 2101.86  4852.3 2099.97  4884.2 2100.61    4901 2097.97  4934.1 2096.81
  4962.4 2094.59  4969.3 2089.68  4978.6 2084.85  4982.6 2084.85  4994.1 2081.68
  4994.6 2081.18  5006.1 2081.68  5010.1 2085.96  5020.1 2089.11  5090.1 2091.79
  5240.2 2104.13  5260.3 2108.14  5270.3 2112.65  5300.3 2123.12  5310.3 2124.37
  5323.4 2123.76  5350.3 2125.93  5370.3 2126.51  5380.3 2128.16  5402.1 2129.42
#Mann= 6 ,-1 , 0
  4545.1     .07       0  4780.8    .035       0  4826.8     .07       0
  4934.1     .16       0  4994.1     .07       0  5006.1     .16       0
Bank Sta=4994.1,5006.1
XS Rating Curve= 0 ,0
Exp/Cntr=0.3,0.1

Type RM Length L Ch R = 1 ,12465   ,264,264,264
BEGIN DESCRIPTION:
Mapping XS cd60cbb6
END DESCRIPTION:
XS GIS Cut Line= 3
      1470072.27      6812831.73      1470444.62      6812685.91
      1470944.65      6812573.92
#Sta/Elev= 30
  4586.7 2101.64  4623.5 2101.96  4670.9 2101.95  4776.4 2099.82  4830.6 2100.22
  4879.6 2096.43  4922.6 2091.61  4939.2 2088.89    4969 2088.17  4984.1 2084.06
  4989.3 2084.06  4995.1 2079.34  4995.6 2078.84  5007.2 2079.34  5007.5 2082.31
  5017.7 2086.54    5048 2087.25    5069 2087.62  5141.5 2092.09  5161.2 2092.19
  5179.7 2093.95  5228.2 2095.22  5233.4 2096.19  5253.4 2095.73  5271.6 2096.98
  5314.9 2097.53  5427.6 2103.36  5448.1 2103.36  5460.5 2104.45    5499 2105.63
#Mann= 6 ,-1 , 0
  4586.7     .07       0  4623.5    .035       0  4670.9     .07       0
  4995.1     .07       0  5007.2     .07       0    5048     .16       0
Bank Sta=4995.1,5007.2
XS Rating Curve= 0 ,0
Exp/Cntr=0.3,0.1

Type RM Length L Ch R = 1 ,12201   ,354,354,354
BEGIN DESCRIPTION:
Mapping XS 078acb9c
END DESCRIPTION:
XS GIS Cut Line= 3
      1470224.68      6813219.79      1470600.14      6812896.41
      1470984.28      6812716.28
#Sta/Elev= 30
  4501.6 2098.51  4588.2 2098.11  4637.6 2098.66  4729.8 2098.08  4786.8 2096.81
  4858.1 2096.89  4899.8 2092.99  4907.5 2092.83  4914.1 2090.12  4921.7  2090.2
  4928.3 2086.35  4950.3 2080.31  4963.9  2079.1  4971.1 2077.79  4971.7 2076.82
  4972.2 2076.32  4983.3 2076.32  4983.8 2076.82    4992 2080.36    4997 2084.17
  5031.5 2085.29  5052.2 2085.82  5057.8 2085.28  5075.1 2086.91  5097.9  2086.7
  5157.1 2088.36  5314.3 2098.21  5354.4  2099.6    5367 2101.16  5421.4 2103.53
#Mann= 4 ,-1 , 0
  4501.6     .07       0  4971.7     .07       0  4983.8     .07       0
  5031.5     .16       0
Bank Sta=4971.7,4983.8
XS Rating Curve= 0 ,0
Exp/Cntr=0.3,0.1

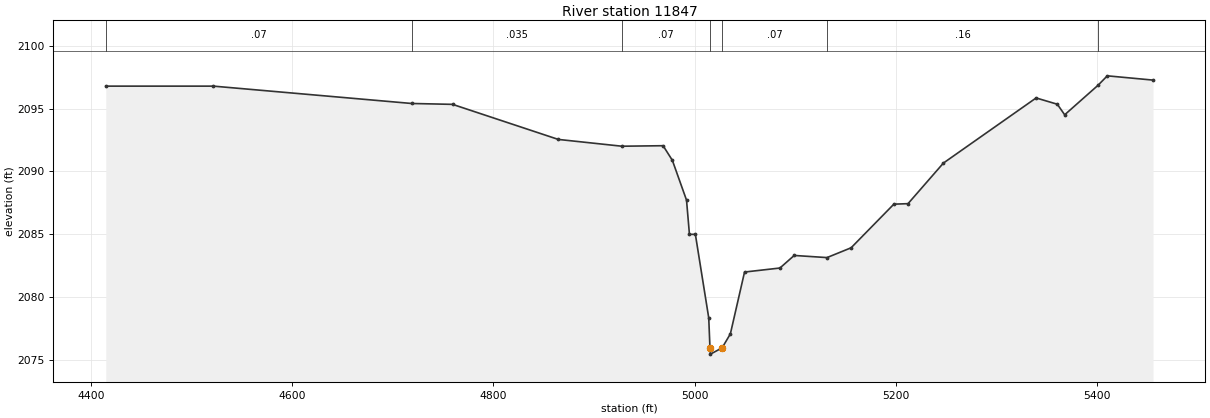
Type RM Length L Ch R = 1 ,11847   ,404,404,404
BEGIN DESCRIPTION:
Mapping XS 1809dde6
END DESCRIPTION:
XS GIS Cut Line= 3
       1470259.4      6813415.09      1470791.11       6813180.7
      1471107.96       6812846.5
#Sta/Elev= 30
  4414.4 2096.79  4521.5 2096.79  4718.6 2095.41  4759.3 2095.34  4864.5 2092.55
  4927.7 2092.01  4968.7 2092.05  4977.9 2090.89    4992 2087.72  4994.9    2085
  5000.8    2085  5014.1 2078.35  5015.3 2075.97  5015.8 2075.47  5027.4 2075.97
  5035.6 2077.08  5049.7    2082  5084.9 2082.32  5099.1 2083.32  5131.7 2083.15
  5155.7 2083.93  5198.2  2087.4  5212.3 2087.44  5247.5 2090.67  5339.7 2095.85
  5360.8 2095.35  5368.1 2094.51  5401.3 2096.86  5410.5 2097.61    5456 2097.27
#Mann= 7 ,-1 , 0
  4414.4     .07       0  4718.6    .035       0  4927.7     .07       0
  5015.3     .07       0  5027.4     .07       0  5131.7     .16       0
  5401.3    .035       0
Bank Sta=5015.3,5027.4
XS Rating Curve= 0 ,0
Exp/Cntr=0.3,0.1