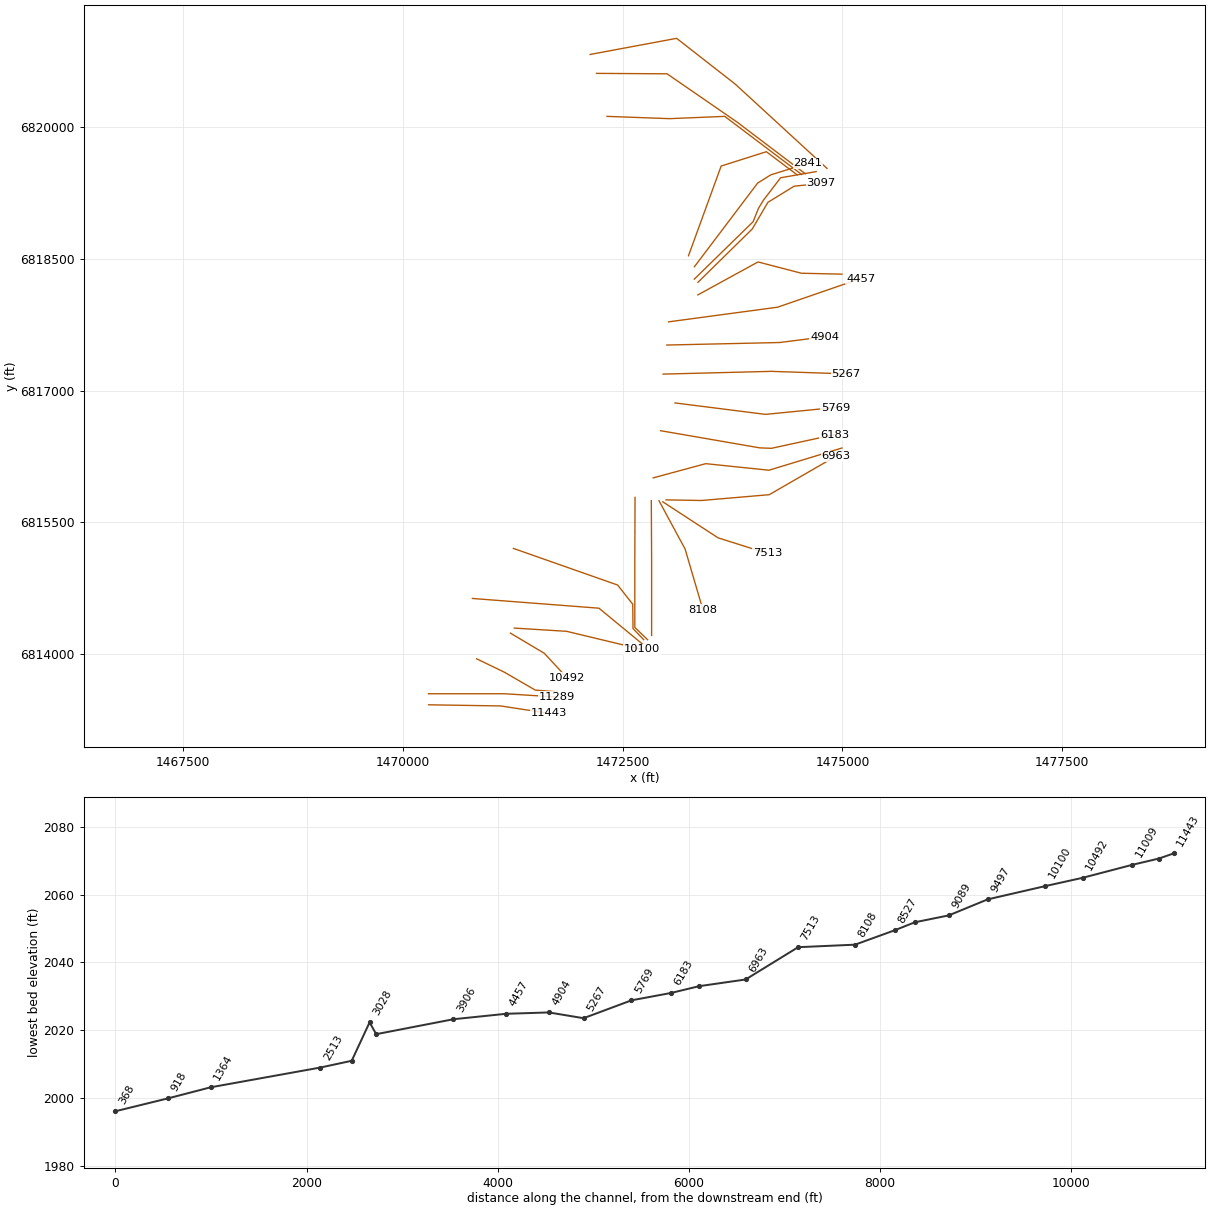
HEC-RAS study MULBERRY CREEK TRIBUTARY 21A.prj: MULBERRY CREEK TRIBUTARY 21A Base Level Engineering

--- MULBERRY CREEK TRIBUTARY 21A.g01 (geometry) --- (continued)

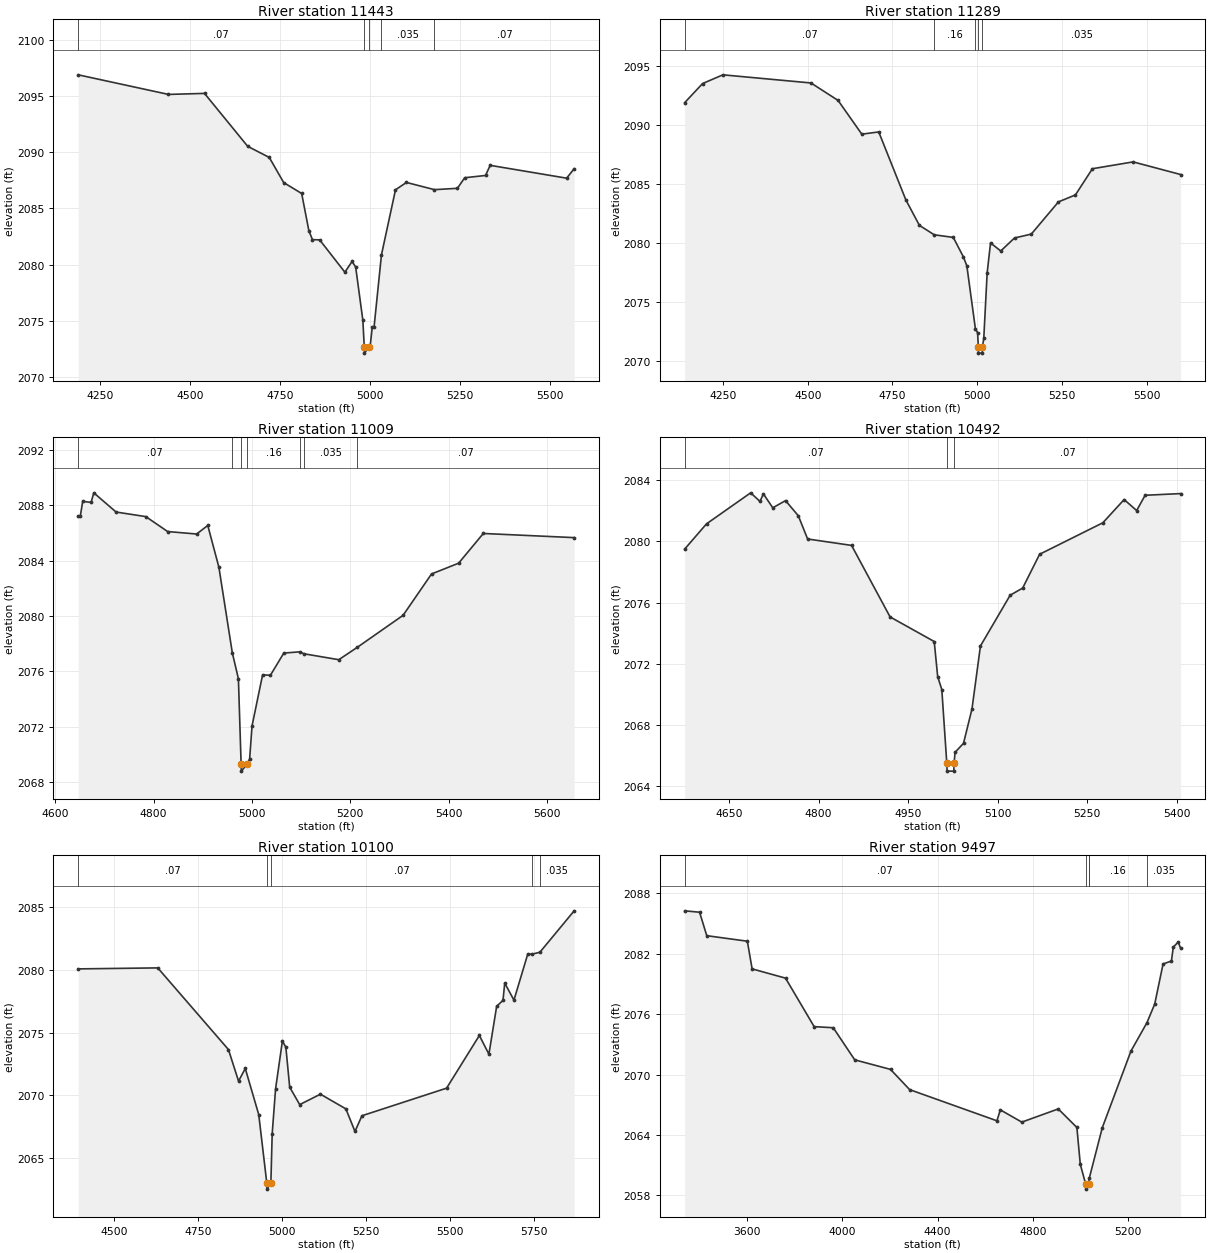
Type RM Length L Ch R = 1 ,11443   ,154,154,154
BEGIN DESCRIPTION:
Mapping XS ec12e0d7
END DESCRIPTION:
XS GIS Cut Line= 3
      1470294.18      6813423.76      1471112.29      6813410.74
      1471665.65      6813326.11
#Sta/Elev= 30
  4189.2 2096.87    4440 2095.13  4540.1 2095.22  4660.1 2090.52  4720.1 2089.53
  4760.1  2087.3  4810.1 2086.33  4830.1 2083.02  4840.1 2082.23  4860.1 2082.21
  4930.1 2079.34  4950.1 2080.29  4960.1  2079.8  4980.1 2075.07  4984.1 2072.65
  4984.6 2072.15  4996.2 2072.65  5000.1 2072.68  5006.3 2074.48  5011.3 2074.48
  5031.8 2080.88  5070.8 2086.66  5101.2 2087.31  5179.1 2086.67  5242.8 2086.79
  5263.1 2087.73  5320.9 2087.93  5333.9 2088.83  5546.3 2087.69  5567.2 2088.53
#Mann= 5 ,-1 , 0
  4189.2     .07       0  4984.1     .07       0  4996.2     .07       0
  5031.8    .035       0  5179.1     .07       0
Bank Sta=4984.1,4996.2
XS Rating Curve= 0 ,0
Exp/Cntr=0.3,0.1

Type RM Length L Ch R = 1 ,11289   ,280,280,280
BEGIN DESCRIPTION:
Mapping XS d95cd13c
END DESCRIPTION:
XS GIS Cut Line= 3
      1470292.25      6813549.59      1471153.74      6813549.59
      1471754.91      6813512.69
#Sta/Elev= 30
  4136.8 2091.87  4189.6 2093.49  4249.6 2094.23  4509.6 2093.54  4589.6 2092.06
  4659.6  2089.2  4709.6 2089.39  4789.6 2083.63  4829.6 2081.47  4873.4 2080.67
  4929.6 2080.45  4959.6 2078.79  4969.6 2078.04    4995 2072.68  5001.4 2072.37
  5003.5 2071.14    5004 2070.64  5015.1 2070.64  5015.6 2071.14  5019.6 2071.89
  5029.6 2077.45  5039.6 2079.98  5069.7  2079.3  5110.3  2080.4  5159.9 2080.73
    5240 2083.46  5290.1 2084.05  5340.2 2086.27  5460.4 2086.85  5600.6 2085.78
#Mann= 5 ,-1 , 0
  4136.8     .07       0  4873.4     .16       0    4995    .035       0
  5003.5    .035       0  5015.6    .035       0
Bank Sta=5003.5,5015.6
XS Rating Curve= 0 ,0
Exp/Cntr=0.3,0.1

Type RM Length L Ch R = 1 ,11009   ,517,517,517
BEGIN DESCRIPTION:
Mapping XS 90ed2d05
END DESCRIPTION:
XS GIS Cut Line= 4
      1470841.26      6813946.72      1471151.57      6813796.99
      1471507.48      6813590.82      1471759.17      6813571.29
#Sta/Elev= 30
  4646.9 2087.23  4651.2 2087.23    4656 2088.29  4673.1 2088.22  4678.6 2088.91
  4723.9 2087.52  4784.3 2087.19  4828.7 2086.11  4887.7 2085.93  4910.3 2086.55
  4932.9 2083.53  4960.2 2077.34  4972.6 2075.46  4978.1 2069.28  4978.6 2068.78
  4990.2 2069.28  4995.4 2069.65  5000.3 2072.05  5021.8 2075.75  5037.6 2075.71
  5064.9 2077.32  5098.2 2077.41  5105.5 2077.27  5176.7 2076.84  5214.5 2077.74
  5307.4 2080.05  5365.2 2083.04  5420.3 2083.82  5470.5 2085.97  5655.2 2085.67
#Mann= 7 ,-1 , 0
  4646.9     .07       0  4960.2     .16       0  4978.1     .07       0
  4990.2     .16       0  5098.2     .07       0  5105.5    .035       0
  5214.5     .07       0
Bank Sta=4978.1,4990.2
XS Rating Curve= 0 ,0
Exp/Cntr=0.3,0.1

Type RM Length L Ch R = 1 ,10492   ,392,392,392
BEGIN DESCRIPTION:
Mapping XS 576d512a
END DESCRIPTION:
XS GIS Cut Line= 3
      1471224.46      6814239.28      1471609.91      6814010.09
      1471870.17      6813729.01
#Sta/Elev= 30
  4575.4  2079.5    4612 2081.15    4686 2083.18  4701.6 2082.62  4707.4 2083.11
  4723.1  2082.2  4744.5 2082.67  4765.9 2081.68  4781.5 2080.16  4855.2 2079.74
  4919.8 2075.06  4993.8 2073.45  4999.6 2071.15  5006.5 2070.31  5014.9 2065.47
  5015.4 2064.97  5026.6 2064.97  5027.1 2065.47  5028.7  2066.2  5042.9 2066.79
  5057.1 2069.04  5071.3 2073.16  5121.1 2076.48  5142.1 2076.95  5170.5 2079.16
  5276.5 2081.22  5312.2 2082.74  5333.2 2082.02  5347.4 2083.02  5406.9 2083.13
#Mann= 3 ,-1 , 0
  4575.4     .07       0  5014.9     .07       0  5027.1     .07       0
Bank Sta=5014.9,5027.1
XS Rating Curve= 0 ,0
Exp/Cntr=0.3,0.1

Type RM Length L Ch R = 1 ,10100   ,603,603,603
BEGIN DESCRIPTION:
Mapping XS 643bf3bd
END DESCRIPTION:
XS GIS Cut Line= 3
      1471268.74      6814296.55      1471862.51      6814260.09
      1472719.27      6814054.37
#Sta/Elev= 30
  4393.1 2080.08  4629.8 2080.16  4840.2 2073.65  4870.3 2071.13  4890.3 2072.14
  4930.4 2068.46  4954.3 2063.02  4954.8 2062.52  4966.5 2063.02  4970.4 2066.93
  4980.5 2070.52  5000.8 2074.33  5011.1 2073.83  5022.5 2070.65  5052.3 2069.26
    5114 2070.09  5189.7 2068.92  5216.8 2067.12  5237.5 2068.37  5489.4 2070.57
    5587 2074.77  5615.4 2073.28  5638.5  2077.1  5657.3 2077.57  5662.5 2078.95
  5689.9 2077.59    5731 2081.26  5744.8 2081.26  5767.2 2081.41  5869.1 2084.71
#Mann= 5 ,-1 , 0
  4393.1     .07       0  4954.3     .07       0  4966.5     .07       0
  5744.8     .16       0  5767.2    .035       0
Bank Sta=4954.3,4966.5
XS Rating Curve= 0 ,0
Exp/Cntr=0.3,0.1

Type RM Length L Ch R = 1 ,9497    ,408,408,408
BEGIN DESCRIPTION:
Mapping XS c6e68925
END DESCRIPTION:
XS GIS Cut Line= 3
      1470792.48      6814633.72      1472231.25      6814523.04
      1472726.08      6814115.46
#Sta/Elev= 30
  3337.1 2086.27  3399.8 2086.13  3429.9  2083.8  3600.4 2083.25  3620.5  2080.5
  3760.9 2079.58  3881.2 2074.76  3961.5 2074.65  4051.7 2071.46  4202.2 2070.51
  4282.4  2068.5  4649.4  2065.4  4663.5 2066.49  4753.8 2065.27    4907 2066.58
  4985.2 2064.74  4999.6 2061.08  5022.2 2059.11  5022.7 2058.61  5034.4 2059.11
  5037.5 2059.71  5092.1 2064.72  5212.5 2072.33  5279.4 2075.14  5312.3    2077
  5347.5 2080.99  5382.6 2081.28  5390.5 2082.67  5411.3 2083.17  5421.2 2082.55
#Mann= 5 ,-1 , 0
  3337.1     .07       0  5022.2     .07       0  5034.4     .07       0
  5037.5     .16       0  5279.4    .035       0
Bank Sta=5022.2,5034.4
XS Rating Curve= 0 ,0
Exp/Cntr=0.3,0.1

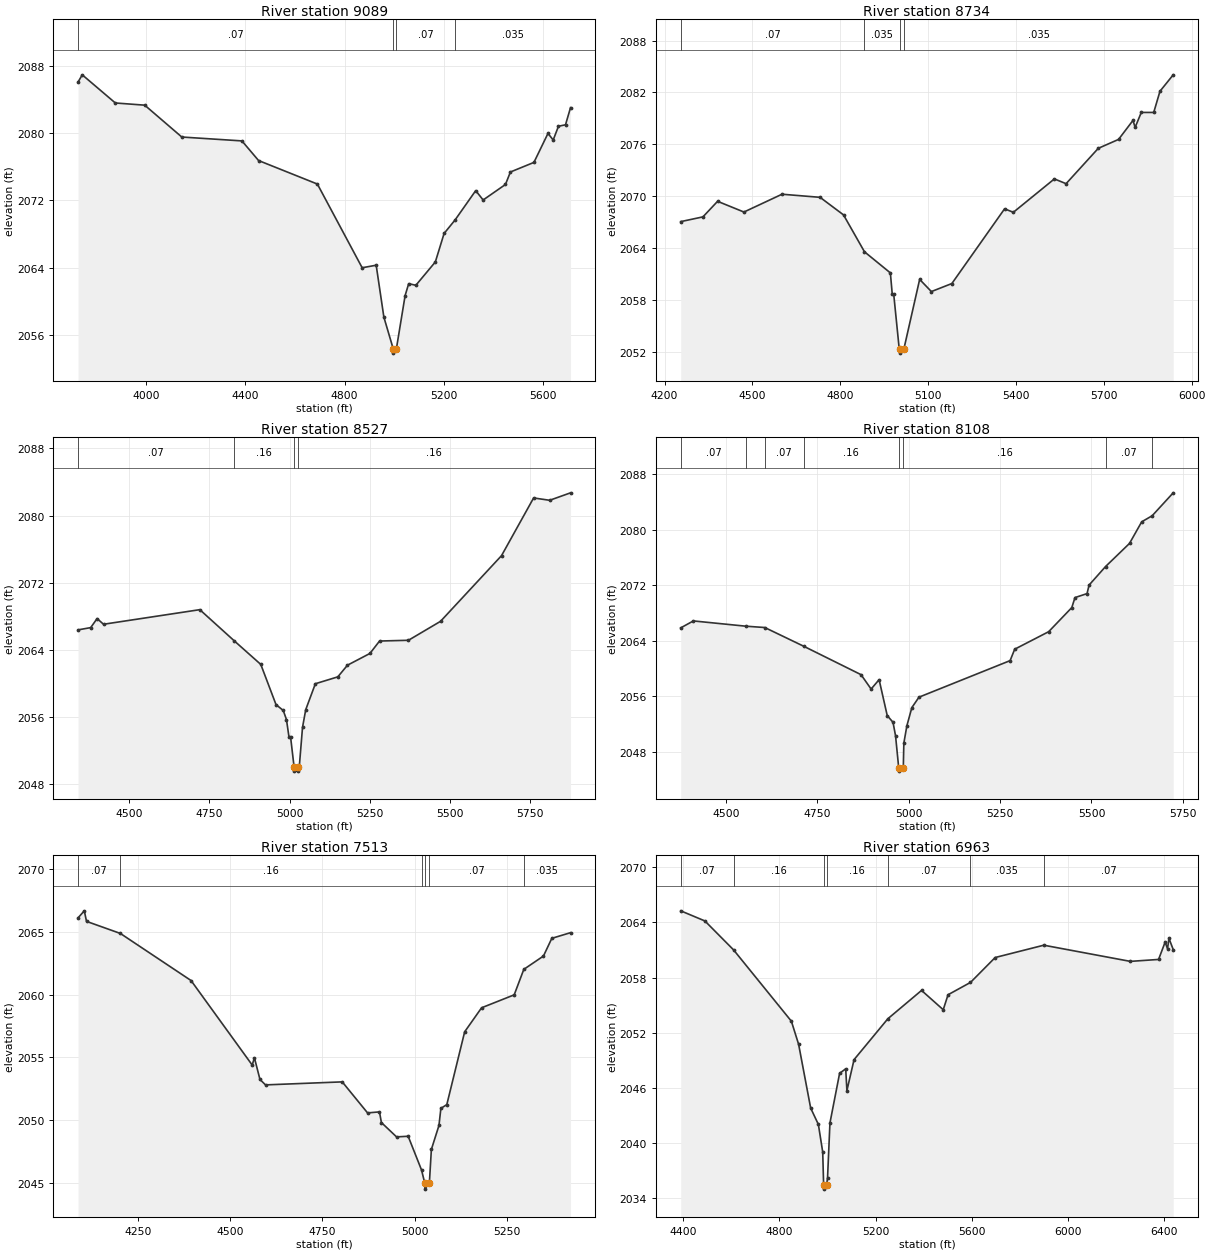
Type RM Length L Ch R = 1 ,9089    ,355,355,355
BEGIN DESCRIPTION:
Mapping XS 86daaf9d
END DESCRIPTION:
XS GIS Cut Line= 5
      1471258.99      6815203.18      1472443.93       6814786.5
       1472615.8      6814567.75      1472618.41       6814291.7
      1472740.37      6814164.55
#Sta/Elev= 30
  3724.7 2086.04  3741.7  2086.9  3875.1 2083.56  3993.7  2083.3  4143.2 2079.52
  4385.7 2079.06  4452.9 2076.73  4690.1 2073.94  4870.7 2064.01  4927.3 2064.31
  4958.3 2058.15  4996.1 2054.38  4996.6 2053.88  5008.7 2054.38    5044 2060.71
  5058.4 2062.12  5087.3 2061.93  5165.9  2064.7  5201.2 2068.08  5245.5 2069.68
  5328.7 2073.16  5358.7 2072.05  5448.7 2073.89  5468.7 2075.37  5563.6 2076.51
  5620.2 2079.95  5641.3 2079.17  5662.6  2080.8  5690.9 2080.97  5711.2 2083.01
#Mann= 4 ,-1 , 0
  3724.7     .07       0  4996.1     .07       0  5008.7     .07       0
  5245.5    .035       0
Bank Sta=4996.1,5008.7
XS Rating Curve= 0 ,0
Exp/Cntr=0.3,0.1

Type RM Length L Ch R = 1 ,8734    ,207,207,207
BEGIN DESCRIPTION:
Mapping XS 997f5040
END DESCRIPTION:
XS GIS Cut Line= 4
      1472641.84      6815783.86      1472639.24      6815059.93
      1472639.24      6814304.73      1472785.06      6814164.12
#Sta/Elev= 30
  4255.3 2067.06  4331.2 2067.61  4381.2 2069.41  4471.2 2068.17  4601.2 2070.23
  4731.2 2069.87  4811.2 2067.84  4882.8 2063.57  4971.2 2061.13  4977.7 2058.64
  4982.7 2058.64  5001.2 2052.42  5004.9 2052.35  5005.4 2051.85  5017.5 2052.35
  5071.2 2060.38  5111.2 2058.97  5181.2  2059.9  5361.2 2068.54  5391.2 2068.14
  5531.2    2072  5571.2 2071.45  5681.2 2075.54  5750.4 2076.57  5799.7 2078.77
    5807 2077.96    5828 2079.69  5870.5 2079.69  5891.8 2082.14    5937 2084.04
#Mann= 4 ,-1 , 0
  4255.3     .07       0  4882.8    .035       0  5004.9    .035       0
  5017.5    .035       0
Bank Sta=5004.9,5017.5
XS Rating Curve= 0 ,0
Exp/Cntr=0.3,0.1

Type RM Length L Ch R = 1 ,8527    ,419,419,419
BEGIN DESCRIPTION:
Mapping XS e9592817
END DESCRIPTION:
XS GIS Cut Line= 3
      1472826.74      6815747.43      1472830.21      6815087.71
      1472830.21      6814213.03
#Sta/Elev= 30
  4340.6 2066.37    4380 2066.64    4400 2067.72    4420 2067.04    4720 2068.78
  4827.4 2065.06    4910 2062.25  4957.4 2057.46    4980 2056.76    4990 2055.67
  4997.7 2053.63  5002.7 2053.63  5013.7 2050.03  5014.2 2049.53  5025.8 2049.53
  5026.3 2050.03    5030 2050.09    5040 2054.75    5050 2056.86    5080 2059.95
    5150 2060.77    5180 2062.16    5250 2063.56    5280 2065.04    5370 2065.13
    5470 2067.39    5660 2075.22    5760  2082.1    5810 2081.82    5875 2082.71
#Mann= 4 ,-1 , 0
  4340.6     .07       0  4827.4     .16       0  5013.7     .07       0
  5026.3     .16       0
Bank Sta=5013.7,5026.3
XS Rating Curve= 0 ,0
Exp/Cntr=0.3,0.1

Type RM Length L Ch R = 1 ,8108    ,595,595,595
BEGIN DESCRIPTION:
Mapping XS ca24ecc4
END DESCRIPTION:
XS GIS Cut Line= 3
      1472914.55      6815745.26      1473211.03      6815196.19
      1473414.69      6814501.74
#Sta/Elev= 30
    4376 2065.86  4410.6 2066.86  4554.6  2066.1  4606.1 2065.91  4712.1 2063.23
  4869.4 2059.13    4897 2057.06  4918.9 2058.41  4941.1 2053.25    4957 2052.27
  4963.9 2050.33  4972.5 2045.75    4973 2045.25  4985.1 2045.75  4986.6 2049.28
    4995  2051.8  5008.5 2054.39    5028 2055.89  5277.4 2061.15  5289.9 2062.79
  5382.9 2065.31  5446.2 2068.78  5454.9 2070.22  5487.9 2070.79  5493.5 2072.02
  5538.7 2074.69  5604.1 2078.01  5637.5 2081.12  5666.1 2081.99  5723.7 2085.29
#Mann= 8 ,-1 , 0
    4376     .07       0  4554.6     .16       0  4606.1     .07       0
  4712.1     .16       0  4972.5     .07       0  4985.1     .16       0
  5538.7     .07       0  5666.1     .16       0
Bank Sta=4972.5,4985.1
XS Rating Curve= 0 ,0
Exp/Cntr=0.3,0.1

Type RM Length L Ch R = 1 ,7513    ,550,550,550
BEGIN DESCRIPTION:
Mapping XS a11bb551
END DESCRIPTION:
XS GIS Cut Line= 3
      1472957.56      6815733.46      1473586.07      6815323.71
      1474145.11      6815146.63
#Sta/Elev= 30
  4086.7 2066.11  4103.7 2066.67  4109.7 2065.83  4201.5 2064.87  4393.4 2061.12
  4559.4 2054.39  4565.4 2054.97  4580.5 2053.24  4595.6 2052.81  4803.8 2053.05
  4872.5 2050.58  4904.8 2050.66  4910.1 2049.81  4951.2 2048.67  4982.7 2048.72
  5018.9 2046.04  5027.6 2045.01  5028.1 2044.51  5040.3 2045.01  5045.7 2047.67
  5066.3 2049.58  5071.5 2050.94  5087.6 2051.24  5136.1 2057.04    5182 2058.95
  5270.5 2059.98  5296.6 2062.01  5349.9 2063.07  5372.6 2064.48  5423.4 2064.93
#Mann= 6 ,-1 , 0
  4086.7     .07       0  4201.5     .16       0  5018.9     .07       0
  5027.6     .07       0  5040.3     .07       0  5296.6    .035       0
Bank Sta=5027.6,5040.3
XS Rating Curve= 0 ,0
Exp/Cntr=0.3,0.1

Type RM Length L Ch R = 1 ,6963    ,486,486,486
BEGIN DESCRIPTION:
Mapping XS 3084e588
END DESCRIPTION:
XS GIS Cut Line= 4
      1472994.45      6815755.68      1473397.18      6815748.74
      1474168.02      6815814.71      1474924.94      6816252.19
#Sta/Elev= 30
  4388.9 2065.27  4489.5 2064.17    4609 2061.02  4849.7 2053.26  4879.8 2050.75
    4930 2043.81  4962.1 2042.03  4980.2 2039.02  4983.9 2035.49  4984.4 2034.99
  4996.6 2035.49  5000.3 2036.23  5010.3 2042.19  5050.5 2047.59  5075.9 2048.08
  5080.9 2045.71  5110.7 2049.08  5251.5 2053.53  5391.7 2056.61    5482 2054.51
  5502.1 2056.14  5595.5 2057.48  5698.3 2060.19  5900.7 2061.53    6261 2059.77
  6378.7 2059.98    6406 2061.87    6416 2061.14  6421.8 2062.28  6439.6 2061.06
#Mann= 7 ,-1 , 0
  4388.9     .07       0    4609     .16       0  4983.9     .07       0
  4996.6     .16       0  5251.5     .07       0  5595.5    .035       0
  5900.7     .07       0
Bank Sta=4983.9,4996.6
XS Rating Curve= 0 ,0
Exp/Cntr=0.3,0.1

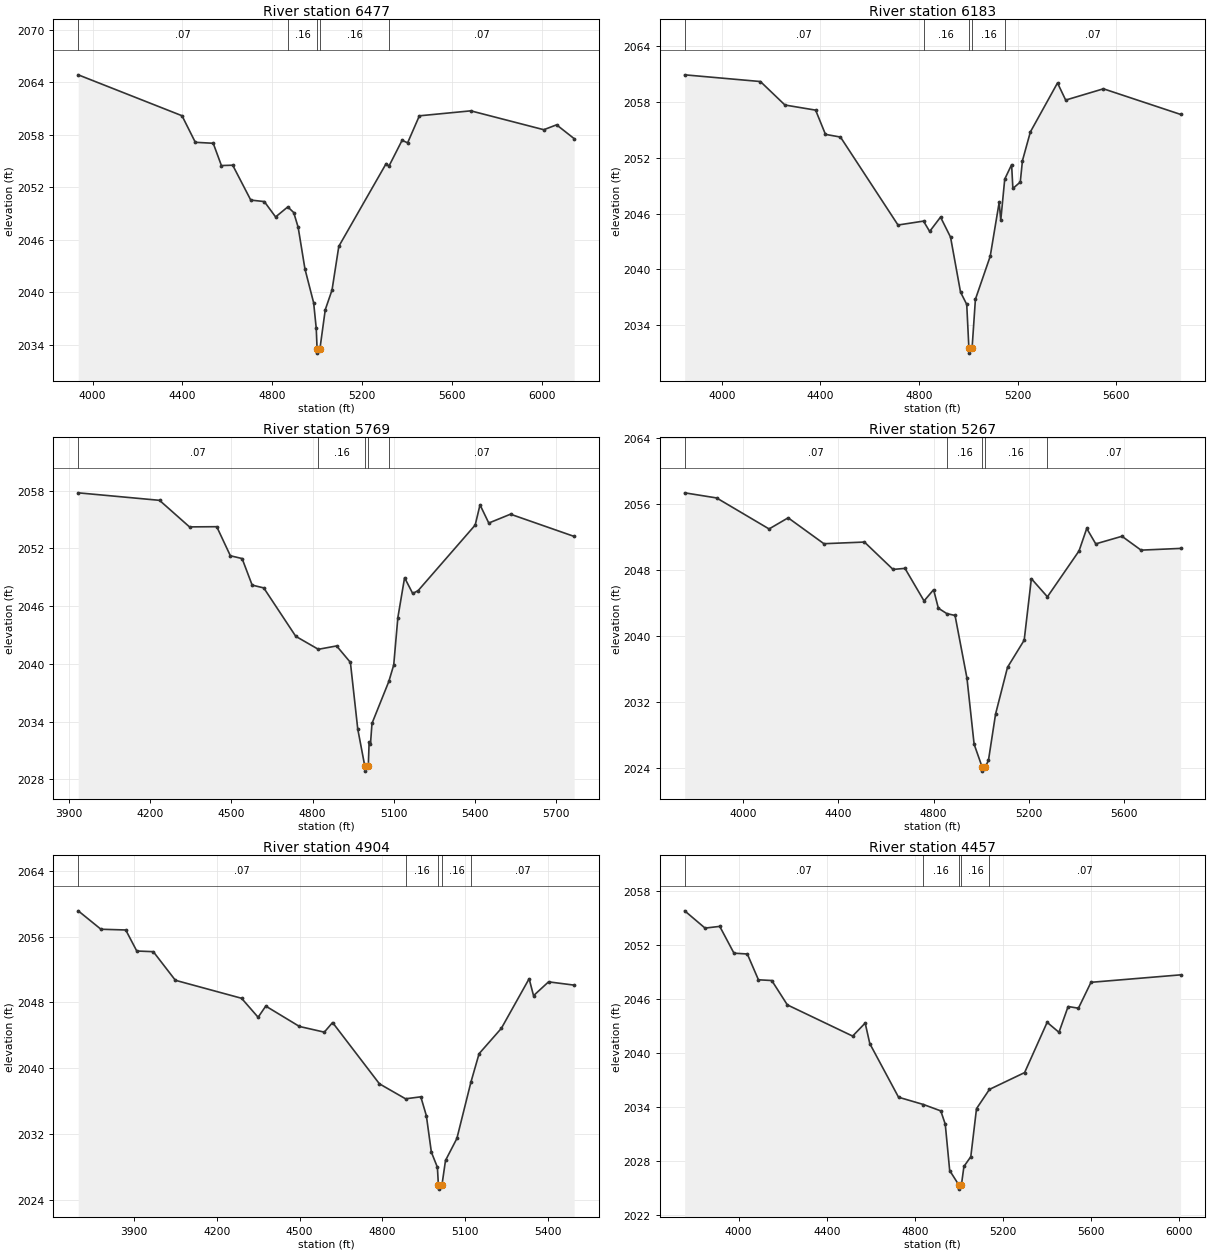
Type RM Length L Ch R = 1 ,6477    ,294,294,294
BEGIN DESCRIPTION:
Mapping XS ad407f56
END DESCRIPTION:
XS GIS Cut Line= 4
      1472848.84      6816006.31      1473446.05      6816167.76
       1474164.8      6816093.11      1474994.36      6816345.95
#Sta/Elev= 30
  3936.2 2064.86  4398.4 2060.18  4457.7 2057.14  4537.4 2057.03  4573.9 2054.48
  4624.2 2054.52  4704.6 2050.53  4764.9 2050.36  4815.2  2048.6  4869.5 2049.75
    4896  2049.1  4915.7 2047.41  4945.9 2042.65  4984.6 2038.78  4996.2 2035.85
  4999.9 2033.52  5000.4 2033.02  5012.6 2033.52  5036.4 2037.99  5066.5 2040.24
  5096.7 2045.24  5307.6 2054.71  5319.7  2054.4  5378.5 2057.37  5403.1 2057.08
  5455.4 2060.17  5684.4 2060.74  6009.5 2058.58  6066.5 2059.14  6144.7 2057.56
#Mann= 5 ,-1 , 0
  3936.2     .07       0  4869.5     .16       0  4999.9     .07       0
  5012.6     .16       0  5319.7     .07       0
Bank Sta=4999.9,5012.6
XS Rating Curve= 0 ,0
Exp/Cntr=0.3,0.1

Type RM Length L Ch R = 1 ,6183    ,414,414,414
BEGIN DESCRIPTION:
Mapping XS e26243fb
END DESCRIPTION:
XS GIS Cut Line= 4
      1472932.17      6816542.93      1474059.77      6816347.62
      1474192.58      6816342.41      1474910.71      6816498.53
#Sta/Elev= 30
  3849.4 2060.89  4156.7 2060.17  4256.2 2057.65  4380.7  2057.1  4420.6  2054.5
  4481.5 2054.21  4714.9 2044.77  4818.4 2045.19  4843.4 2044.08  4887.5 2045.62
  4928.1 2043.47  4968.6 2037.57  4993.8 2036.25  5002.6 2031.52  5003.1 2031.02
  5015.4 2031.52    5029  2036.8  5089.1 2041.42  5125.4  2047.2  5131.9 2045.29
    5148  2049.7  5175.9 2051.25    5181 2048.69    5211 2049.38  5219.9 2051.68
    5252 2054.76  5362.1 2060.02  5395.2 2058.18  5548.4 2059.39  5861.6 2056.64
#Mann= 5 ,-1 , 0
  3849.4     .07       0  4818.4     .16       0  5002.6     .07       0
  5015.4     .16       0    5148     .07       0
Bank Sta=5002.6,5015.4
XS Rating Curve= 0 ,0
Exp/Cntr=0.3,0.1

Type RM Length L Ch R = 1 ,5769    ,502,502,502
BEGIN DESCRIPTION:
Mapping XS 96ae719f
END DESCRIPTION:
XS GIS Cut Line= 3
      1473096.45      6816858.91      1474125.09       6816728.7
      1474919.41      6816806.83
#Sta/Elev= 30
  3933.1 2057.77    4234 2056.99  4344.9 2054.23  4445.7 2054.25  4496.1 2051.23
  4539.5 2050.94  4576.7 2048.18  4619.6 2047.89    4738 2042.86  4821.6 2041.51
  4889.2 2041.86  4940.2 2040.15  4967.4 2033.23  4993.6 2029.35  4994.1 2028.85
  5006.4 2029.35  5009.5 2031.85  5014.5 2031.67  5020.1 2033.81  5082.4 2038.17
  5100.5 2039.88  5115.8  2044.8  5140.7 2048.95  5170.8 2047.31  5190.9 2047.61
  5401.9 2054.42  5419.8 2056.52  5452.2 2054.63  5532.6 2055.55  5768.1 2053.24
#Mann= 5 ,-1 , 0
  3933.1     .07       0  4821.6     .16       0  4993.6     .07       0
  5006.4     .16       0  5082.4     .07       0
Bank Sta=4993.6,5006.4
XS Rating Curve= 0 ,0
Exp/Cntr=0.3,0.1

Type RM Length L Ch R = 1 ,5267    ,363,363,363
BEGIN DESCRIPTION:
Mapping XS 28603cd6
END DESCRIPTION:
XS GIS Cut Line= 3
      1472961.06      6817187.03       1474190.2      6817218.28
      1475040.88      6817189.67
#Sta/Elev= 30
  3755.9 2057.33  3889.9 2056.71    4110 2052.95    4190  2054.3    4340 2051.16
  4510.1 2051.36  4630.1 2048.04  4680.1 2048.17  4760.2 2044.22  4800.2 2045.58
  4820.2 2043.34  4855.9 2042.68  4890.2 2042.46  4940.2 2034.86  4970.2 2026.85
  5003.8 2024.08  5004.3 2023.58  5016.7 2024.08  5030.3 2024.87  5060.3 2030.51
  5110.3 2036.17  5180.3 2039.46  5210.4 2046.92  5277.7 2044.72  5410.5 2050.29
  5442.7 2053.01  5480.5 2051.14  5590.6 2052.06  5670.6 2050.38  5836.6 2050.59
#Mann= 5 ,-1 , 0
  3755.9     .07       0  4855.9     .16       0  5003.8     .07       0
  5016.7     .16       0  5277.7     .07       0
Bank Sta=5003.8,5016.7
XS Rating Curve= 0 ,0
Exp/Cntr=0.3,0.1

Type RM Length L Ch R = 1 ,4904    ,447,447,447
BEGIN DESCRIPTION:
Mapping XS 3ee19e8f
END DESCRIPTION:
XS GIS Cut Line= 3
      1473002.66      6817517.76      1474286.55      6817546.41
      1474797.01      6817611.52
#Sta/Elev= 30
  3697.3 2059.14  3779.7  2056.9  3869.7 2056.81  3909.7 2054.25  3969.7 2054.17
  4049.7 2050.69  4289.8  2048.5  4349.8 2046.19  4377.6 2047.55  4499.8 2045.07
  4589.9 2044.38  4619.9 2045.55  4789.9 2038.09  4884.6 2036.27  4939.9 2036.51
    4960 2034.22  4978.2 2029.78  5000.1 2027.94  5003.7 2025.78  5004.2 2025.28
  5016.6 2025.78  5029.5 2028.77  5070.7 2031.44  5121.7  2038.3  5151.3 2041.76
    5232 2044.84  5332.8 2050.88  5348.8 2048.82  5403.3  2050.5  5496.1  2050.1
#Mann= 5 ,-1 , 0
  3697.3     .07       0  4884.6     .16       0  5003.7     .07       0
  5016.6     .16       0  5121.7     .07       0
Bank Sta=5003.7,5016.6
XS Rating Curve= 0 ,0
Exp/Cntr=0.3,0.1

Type RM Length L Ch R = 1 ,4457    ,551,551,551
BEGIN DESCRIPTION:
Mapping XS ede45042
END DESCRIPTION:
XS GIS Cut Line= 3
      1473023.38      6817781.65      1474262.94      6817948.32
      1475207.42      6818274.72
#Sta/Elev= 30
  3755.3 2055.83  3847.7 2053.91  3914.4  2054.1  3978.9 2051.12  4039.5 2051.03
  4089.9 2048.16  4150.4 2048.08  4221.1 2045.37  4517.3  2041.9  4574.2 2043.35
  4595.2 2041.06  4725.6  2035.1  4838.6 2034.29  4917.3 2033.58  4937.5  2032.1
  4957.6 2026.95  4998.1 2025.38  4998.6 2024.88    5011 2025.38  5022.2  2027.4
  5053.4 2028.49  5079.3 2033.83  5137.9 2035.97  5297.5 2037.84  5399.7 2043.43
  5453.4 2042.32  5494.9 2045.19  5541.7    2045  5598.7 2047.88  6005.3 2048.71
#Mann= 5 ,-1 , 0
  3755.3     .07       0  4838.6     .16       0  4998.1     .07       0
    5011     .16       0  5137.9     .07       0
Bank Sta=4998.1,5011
XS Rating Curve= 0 ,0
Exp/Cntr=0.3,0.1

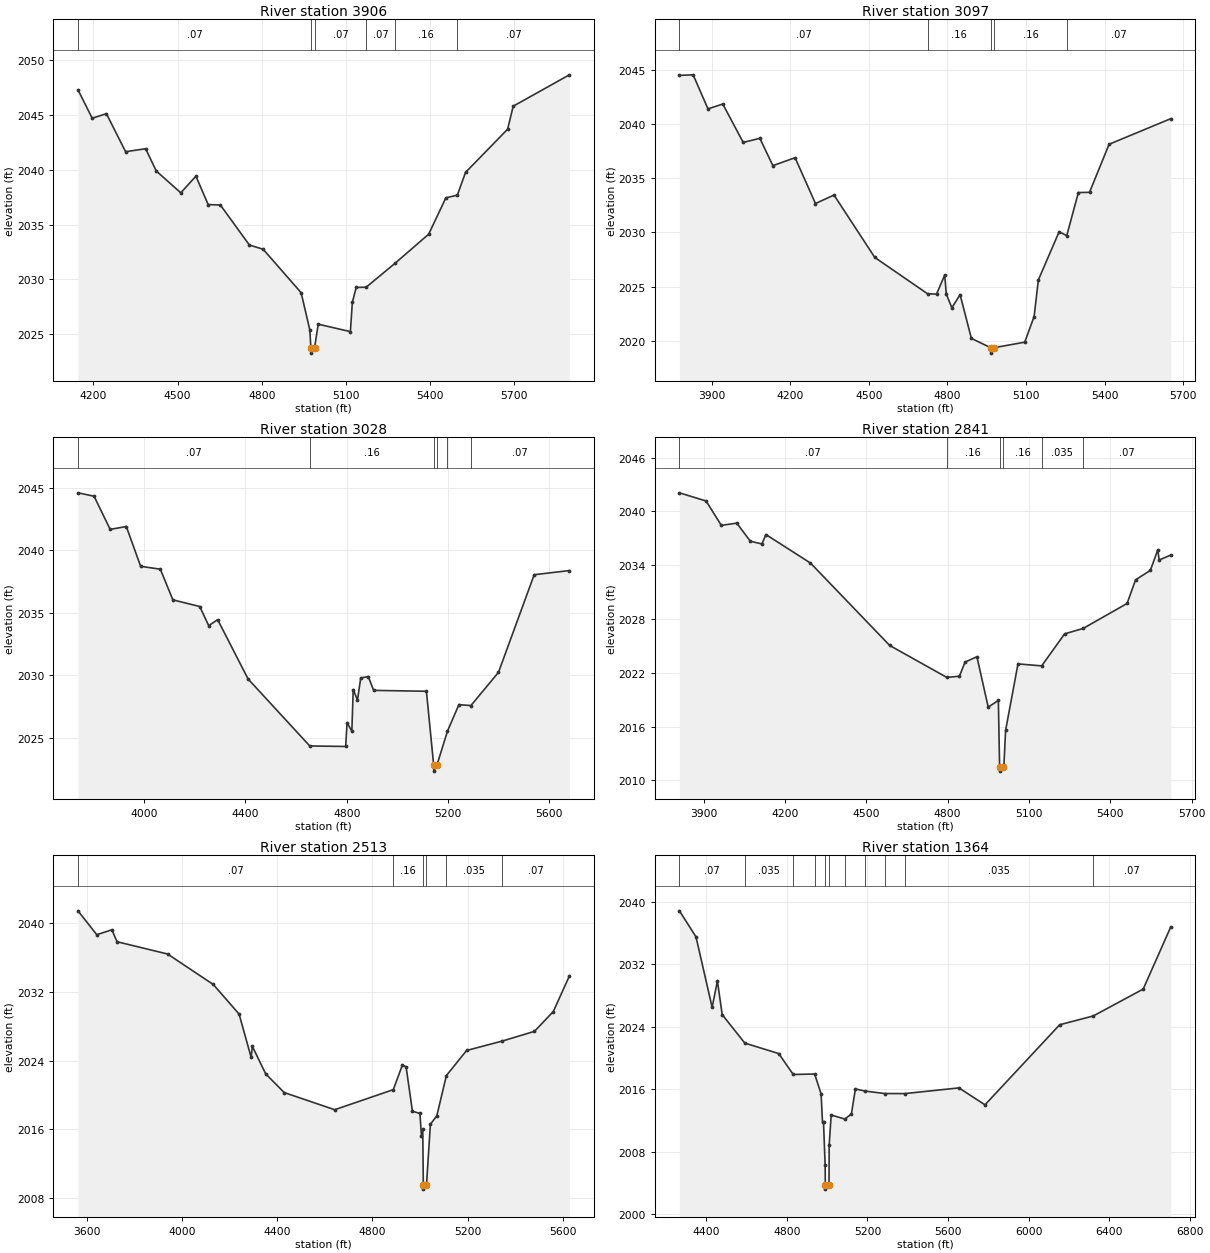
Type RM Length L Ch R = 1 ,3906    ,809,809,809
BEGIN DESCRIPTION:
Mapping XS 89cd97c9
END DESCRIPTION:
XS GIS Cut Line= 4
      1473356.18      6818088.28      1474040.24       6818463.3
      1474533.29      6818334.83      1474995.05      6818324.41
#Sta/Elev= 30
    4145 2047.29  4195.7  2044.7  4246.3 2045.12  4314.7 2041.65  4386.2 2041.92
  4424.1 2039.89  4511.4  2037.9  4565.4 2039.42    4609 2036.83  4652.6 2036.79
  4755.9 2033.14  4805.2 2032.75  4940.4 2028.79  4971.4  2025.4  4975.1 2023.78
  4975.6 2023.28  4988.3 2023.78  5001.4 2025.92    5116 2025.24  5122.9  2027.9
  5136.7 2029.27  5172.1 2029.29  5275.1 2031.47  5395.1 2034.13  5456.3 2037.44
  5497.3 2037.69  5526.4 2039.76  5676.4  2043.7  5696.4  2045.8  5896.5 2048.66
#Mann= 6 ,-1 , 0
    4145     .07       0  4975.1     .07       0  4988.3     .07       0
  5172.1     .07       0  5275.1     .16       0  5497.3     .07       0
Bank Sta=4975.1,4988.3
XS Rating Curve= 0 ,0
Exp/Cntr=0.3,0.1

Type RM Length L Ch R = 1 ,3097    ,69,69,69
BEGIN DESCRIPTION:
Mapping XS dde23d51
END DESCRIPTION:
XS GIS Cut Line= 5
      1473357.24      6818231.69       1473975.3      6818839.34
      1474152.39      6819141.42        1474451.      6819325.45
      1474756.54       6819356.7
#Sta/Elev= 30
  3777.2 2044.47  3829.6 2044.52  3886.2 2041.38  3942.7 2041.83  4020.5 2038.29
  4084.1 2038.67  4133.7 2036.15  4218.5 2036.88  4296.3 2032.66    4367 2033.44
  4522.6 2027.69    4724 2024.34  4758.3 2024.31  4789.5 2026.07  4795.3 2024.32
  4816.7 2023.05  4848.1 2024.26  4891.1 2020.23  4964.6 2019.37  4965.1 2018.87
  4977.8 2019.37  5094.7 2019.88  5130.5 2022.24  5146.8 2025.62    5226 2030.06
    5255  2029.7  5299.4 2033.67  5341.9 2033.69  5416.6 2038.12    5652 2040.48
#Mann= 5 ,-1 , 0
  3777.2     .07       0    4724     .16       0  4964.6     .07       0
  4977.8     .16       0    5255     .07       0
Bank Sta=4964.6,4977.8
XS Rating Curve= 0 ,0
Exp/Cntr=0.3,0.1

Type RM Length L Ch R = 1 ,3028    ,187,187,187
BEGIN DESCRIPTION:
Mapping XS b1ead1da
END DESCRIPTION:
XS GIS Cut Line= 6
      1473315.48      6818267.74      1473984.77       6818921.4
      1474044.66      6819072.44      1474101.96      6819166.19
      1474297.27       6819421.4      1474701.77      6819491.41
#Sta/Elev= 30
    3739 2044.59  3802.5 2044.32  3866.1 2041.67  3929.8  2041.9  3986.4 2038.72
  4064.1 2038.49  4113.7 2036.04  4219.7 2035.51  4255.1 2033.98  4290.4 2034.46
  4410.6 2029.72  4654.1 2024.37  4795.9 2024.33  4801.3 2026.23  4820.2 2025.55
  4825.6 2028.88  4842.5 2028.04  4855.2  2029.8  4885.1 2029.91  4906.4 2028.81
  5114.6 2028.74  5143.2 2022.86  5143.7 2022.36  5156.4 2022.86  5197.7 2025.55
  5242.8 2027.67  5290.3  2027.6  5399.1 2030.25  5540.1 2038.05  5678.9 2038.38
#Mann= 6 ,-1 , 0
    3739     .07       0  4654.1     .16       0  5143.2     .07       0
  5156.4     .16       0  5197.7    .035       0  5290.3     .07       0
Bank Sta=5143.2,5156.4
XS Rating Curve= 0 ,0
Exp/Cntr=0.3,0.1

Type RM Length L Ch R = 1 ,2841    ,328,328,328
BEGIN DESCRIPTION:
Mapping XS 7d9a31fa
END DESCRIPTION:
XS GIS Cut Line= 4
      1473317.21      6818409.22      1474035.98      6819360.64
      1474185.29      6819454.39      1474608.91      6819586.34
#Sta/Elev= 30
  3810.6 2042.07  3908.9 2041.16  3965.1 2038.44  4022.1 2038.69  4072.3 2036.67
    4115 2036.37  4129.5 2037.42    4294 2034.24  4586.1 2025.05    4797 2021.48
  4843.4 2021.62  4864.2 2023.19  4907.9 2023.79  4949.6 2018.17    4987 2018.91
  4991.6 2011.53  4992.1 2011.03  5004.9 2011.53  5007.6 2011.75  5013.7 2015.57
  5059.4 2022.99  5146.8 2022.77  5231.4 2026.34  5299.5 2026.94  5461.8 2029.73
  5493.2 2032.37  5547.7 2033.42    5575 2035.71  5580.2 2034.58    5623 2035.13
#Mann= 6 ,-1 , 0
  3810.6     .07       0    4797     .16       0  4991.6     .07       0
  5004.9     .16       0  5146.8    .035       0  5299.5     .07       0
Bank Sta=4991.6,5004.9
XS Rating Curve= 0 ,0
Exp/Cntr=0.3,0.1

Type RM Length L Ch R = 1 ,2513    ,1149,1149,1149
BEGIN DESCRIPTION:
Mapping XS f6958120
END DESCRIPTION:
XS GIS Cut Line= 4
      1473249.62      6818533.82      1473621.14      6819554.62
      1474135.03      6819717.81      1474485.75       6819453.9
#Sta/Elev= 30
  3563.1 2041.46    3642 2038.68  3705.5 2039.25  3727.2 2037.86  3939.5 2036.43
  4131.6 2032.88    4240 2029.43  4290.5  2024.4  4295.9 2025.66  4351.7 2022.47
  4429.5 2020.29  4641.6 2018.29  4887.9 2020.63  4926.2 2023.51  4941.7 2023.28
  4968.2 2018.11  4999.7 2017.86  5006.2 2015.25  5011.5 2016.03    5014 2009.54
  5014.5 2009.04  5027.3 2009.54  5043.7  2016.6  5070.7 2017.58  5110.9 2022.27
  5195.7 2025.19  5345.8 2026.29    5481 2027.42  5560.1 2029.73  5627.5 2033.86
#Mann= 6 ,-1 , 0
  3563.1     .07       0  4887.9     .16       0    5014     .07       0
  5027.3     .16       0  5110.9    .035       0  5345.8     .07       0
Bank Sta=5014,5027.3
XS Rating Curve= 0 ,0
Exp/Cntr=0.3,0.1

Type RM Length L Ch R = 1 ,1364    ,446,446,446
BEGIN DESCRIPTION:
Mapping XS ee1d1a58
END DESCRIPTION:
XS GIS Cut Line= 4
      1472322.92      6820119.94       1473033.9       6820093.9
       1473661.5      6820119.94      1474536.52      6819458.47
#Sta/Elev= 30
  4267.8 2038.87  4349.9 2035.54    4430 2026.51  4456.2 2029.88    4480 2025.57
  4592.1 2021.92  4760.2 2020.58  4832.2  2017.9  4938.4 2017.96  4970.3 2015.41
  4977.3 2011.81  4982.3 2011.81  4990.4 2006.27  4991.3 2003.71  4991.8 2003.21
  5009.5 2003.71  5010.4 2008.88  5020.4 2012.71  5087.7 2012.19  5120.5 2012.83
  5140.5 2016.05  5186.6 2015.78  5285.6 2015.46  5384.5 2015.45  5653.9 2016.18
  5782.9 2014.01  6153.3 2024.27  6320.1  2025.4  6567.4 2028.84  6704.3 2036.82
#Mann= 11 ,-1 , 0
  4267.8     .07       0  4592.1    .035       0  4832.2     .07       0
  4938.4    .035       0  4991.3    .035       0  5009.5    .035       0
  5087.7     .07       0  5186.6    .035       0  5285.6     .07       0
  5384.5    .035       0  6320.1     .07       0
Bank Sta=4991.3,5009.5
XS Rating Curve= 0 ,0
Exp/Cntr=0.3,0.1

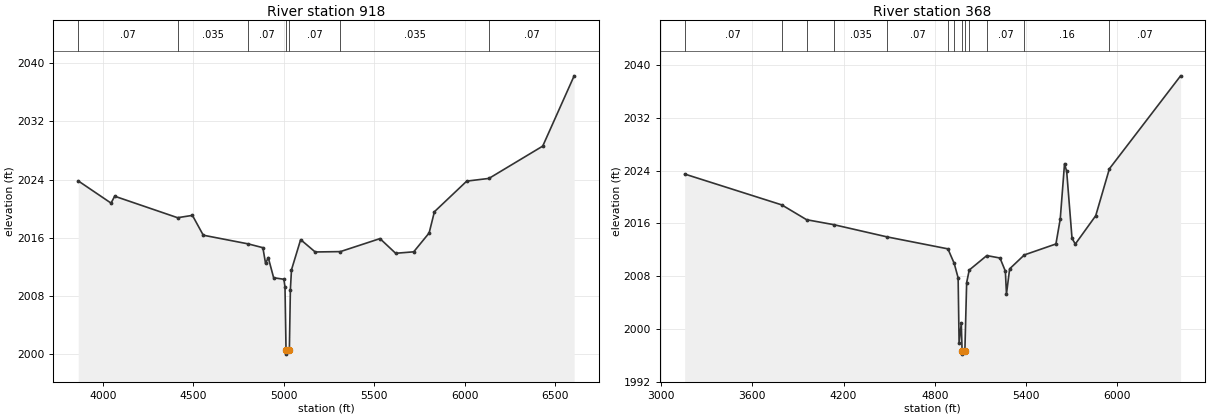
Type RM Length L Ch R = 1 ,918     ,550,550,550
BEGIN DESCRIPTION:
Mapping XS e3809746
END DESCRIPTION:
XS GIS Cut Line= 4
      1472203.36      6820609.11      1473006.12      6820604.31
      1473802.13      6820054.83      1474577.33      6819467.14
#Sta/Elev= 30
  3863.1 2023.81  4044.7 2020.75  4064.7  2021.7  4412.6 2018.74  4494.7 2019.06
  4554.7 2016.33  4803.7 2015.13  4884.4 2014.61  4899.2 2012.45  4914.1 2013.25
  4943.9 2010.47  5000.7 2010.26  5006.7 2009.18  5012.5 2000.45    5013 1999.95
  5030.8 2000.45  5036.5 2008.83  5042.6 2011.56  5093.3 2015.72  5173.7 2014.02
    5313 2014.07    5532 2015.86  5618.6 2013.84  5718.6 2014.04  5803.9 2016.64
    5833 2019.56  6011.9 2023.78  6134.6 2024.15  6432.1  2028.6  6605.9 2038.28
#Mann= 7 ,-1 , 0
  3863.1     .07       0  4412.6    .035       0  4803.7     .07       0
  5012.5     .07       0  5030.8     .07       0    5313    .035       0
  6134.6     .07       0
Bank Sta=5012.5,5030.8
XS Rating Curve= 0 ,0
Exp/Cntr=0.3,0.1

Type RM Length L Ch R = 1 ,368     ,0,0,0
BEGIN DESCRIPTION:
MULBERRY CREEK TRIBUTARY 21A 1.0
END DESCRIPTION:
XS GIS Cut Line= 4
       1472130.4      6820824.39      1473114.63      6821007.96
      1473780.12       6820487.9       1474824.7      6819527.92
#Sta/Elev= 30
  3154.2 2023.48  3793.3  2018.8  3956.9 2016.55  4135.7  2015.8  4487.6 2013.94
    4887 2012.13  4928.5 2009.92  4954.2 2007.72  4960.5 1997.88    4975 2000.85
  4980.3 1996.66  4980.8 1996.16  4998.6 1996.66  5010.3 2007.02  5027.4 2008.92
  5142.9 2011.11  5229.8 2010.74    5265 2008.75  5272.4 2005.29  5293.3  2009.1
    5390 2011.21  5597.9 2012.87  5626.3 2016.65  5654.6 2025.06  5668.8 2023.87
  5703.9 2013.72  5725.5 2012.86  5859.9 2017.16  5949.9 2024.28  6418.7 2038.38
#Mann= 13 ,-1 , 0
  3154.2     .07       0  3793.3    .035       0  3956.9     .07       0
  4135.7    .035       0  4487.6     .07       0    4887     .16       0
  4928.5     .07       0  4980.3     .07       0  4998.6     .07       0
  5027.4     .16       0  5142.9     .07       0    5390     .16       0
  5949.9     .07       0
Bank Sta=4980.3,4998.6
XS Rating Curve= 0 ,0
Exp/Cntr=0.3,0.1

Chan Stop Cuts=-1
Use User Specified Reach Order=0
Composite Channel Slope=5