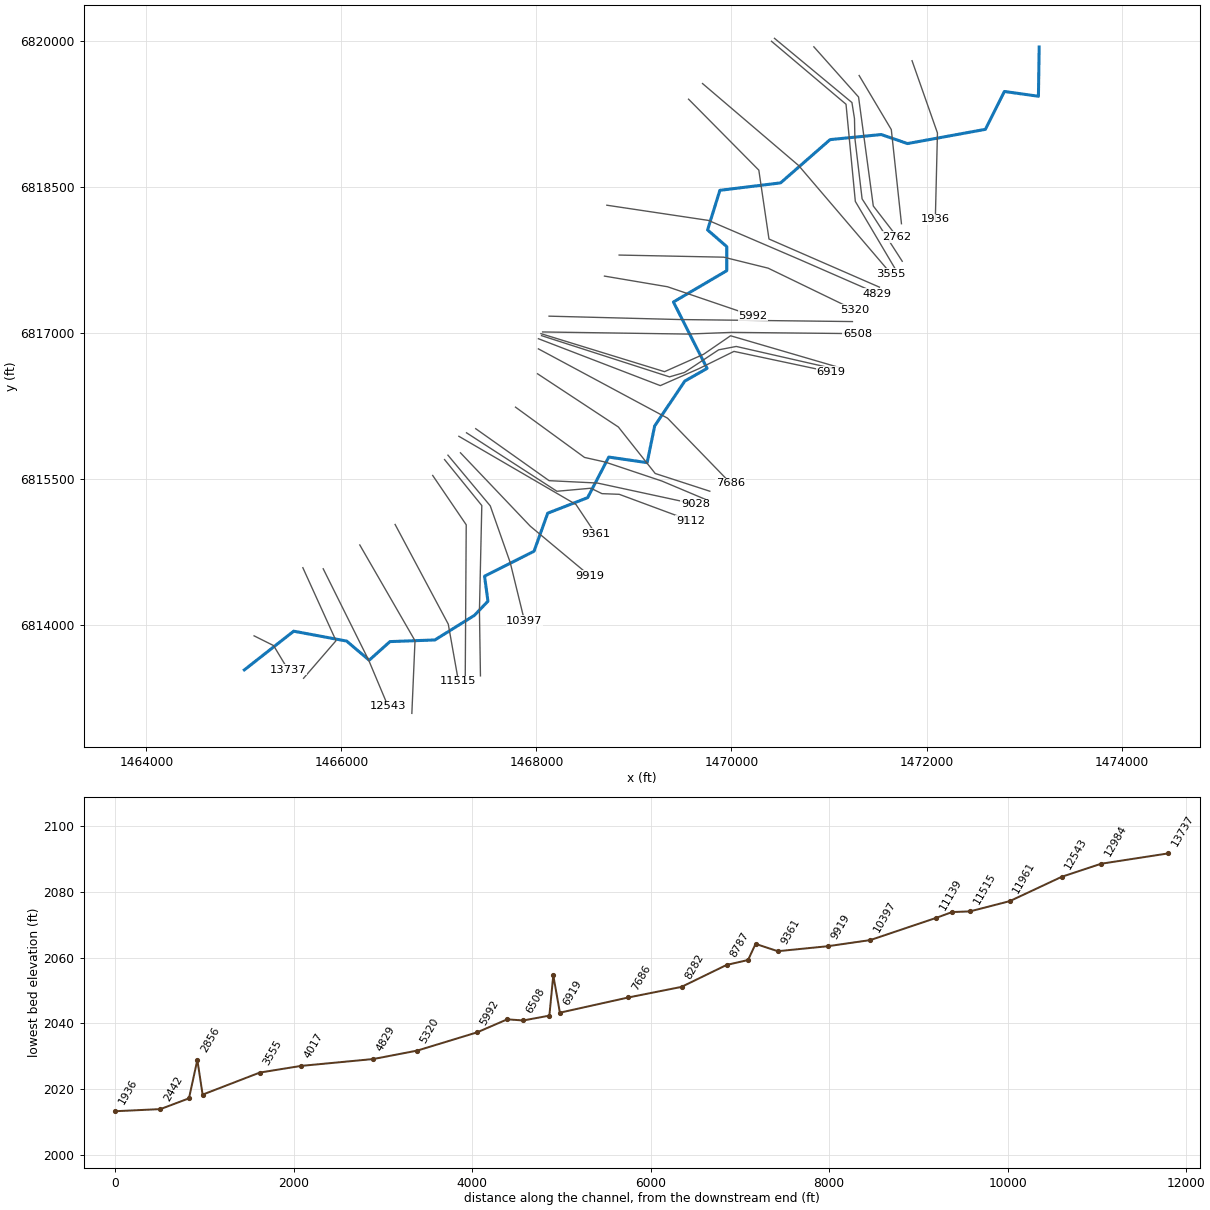
--- MULBERRY CREEK TRIBUTARY 21A_1.prj (project) ---

Proj Title=MULBERRY CREEK TRIBUTARY 21A_1 Base Level Engineering
Current Plan=p01
Default Exp/Contr=0.3,0.1
English Units
Geom File=g01
Flow File=f01
Plan File=p01
BEGIN DESCRIPTION:
MULBERRY CREEK TRIBUTARY 21A_1
END DESCRIPTION:

--- MULBERRY CREEK TRIBUTARY 21A_1.p01 (plan) ---

Plan Title=Multiple Run
Short Identifier=Multiple
Geom File=g01
Flow File=f01
Subcritical Flow
K Sum by GR= 0
Std Step Tol= 0.01
Critical Tol= 0.01
Num of Std Step Trials= 20
Max Error Tol= 0.3
Flow Tol Ratio= 0.001
Split Flow NTrial= 30
Split Flow Tol= 0.02
Split Flow Ratio= 0.02
Log Output Level= 0
Friction Slope Method= 1
Unsteady Friction Slope Method= 2
Unsteady Bridges Friction Slope Method= 1
Parabolic Critical Depth
Global Vel Dist=  1 , 1 , 1
Global Log Level= 0
CheckData=True
Encroach Param= -1, 0, 0, 0
BEGIN DESCRIPTION:
Multiple Run
END DESCRIPTION:

--- MULBERRY CREEK TRIBUTARY 21A_1.f01 (steady flow) ---

Flow Title=Multiple
Number of Profiles=7
Profile Names=10-year,25-year,50-year,1pct_min,100-year,1pct_plu,500-year
River Rch & RM= MULBERRY CREEK T,Reach-1,13737
     424     623     798     509    1016    2026    1665
River Rch & RM= MULBERRY CREEK T,Reach-1,12543
     679    1022    1329     860    1716    3424    2895
River Rch & RM= MULBERRY CREEK T,Reach-1,9361
     720    1084    1409     910    1817    3625    3059
River Rch & RM= MULBERRY CREEK T,Reach-1,5992
     785    1181    1534     990    1976    3943    3320
Boundary for River Rch & Prof#=MULBERRY CREEK T,Reach-1,1
Up Type=0
Dn Type=3
Dn Slope=0.005
Boundary for River Rch & Prof#=MULBERRY CREEK T,Reach-1,2
Up Type=0
Dn Type=3
Dn Slope=0.005
Boundary for River Rch & Prof#=MULBERRY CREEK T,Reach-1,3
Up Type=0
Dn Type=3
Dn Slope=0.005
Boundary for River Rch & Prof#=MULBERRY CREEK T,Reach-1,4
Up Type=0
Dn Type=3
Dn Slope=0.005
Boundary for River Rch & Prof#=MULBERRY CREEK T,Reach-1,5
Up Type=0
Dn Type=3
Dn Slope=0.005
Boundary for River Rch & Prof#=MULBERRY CREEK T,Reach-1,6
Up Type=0
Dn Type=3
Dn Slope=0.005
Boundary for River Rch & Prof#=MULBERRY CREEK T,Reach-1,7
Up Type=0
Dn Type=3
Dn Slope=0.005

--- MULBERRY CREEK TRIBUTARY 21A_1.g01 (geometry) ---

Geom Title=Existing Conditions

River Reach=MULBERRY CREEK T,Reach-1
Reach XY= 30
      1465005.00      6813538.00      1465510.94      6813935.78
      1466053.55      6813834.47      1466285.14      6813637.67
      1466498.27      6813828.85      1466958.64      6813845.75
      1467364.68      6814098.78      1467502.95      6814243.85
      1467468.05      6814501.00      1467975.64      6814757.43
      1468115.63      6815148.00      1468525.13      6815307.77
      1468741.67      6815724.68      1469135.38      6815667.31
      1469212.37      6816044.34      1469521.27      6816505.21
      1469749.61      6816635.56      1469404.79      6817317.95
      1469951.47      6817639.45      1469951.55      6817886.75
      1469754.95      6818057.98      1469880.99      6818465.34
      1470503.54      6818541.54      1471010.85      6818985.94
      1471534.82      6819038.28      1471805.01      6818945.53
      1472603.48      6819091.74      1472798.62      6819480.68
      1473147.33      6819431.48      1473155.00      6819938.00

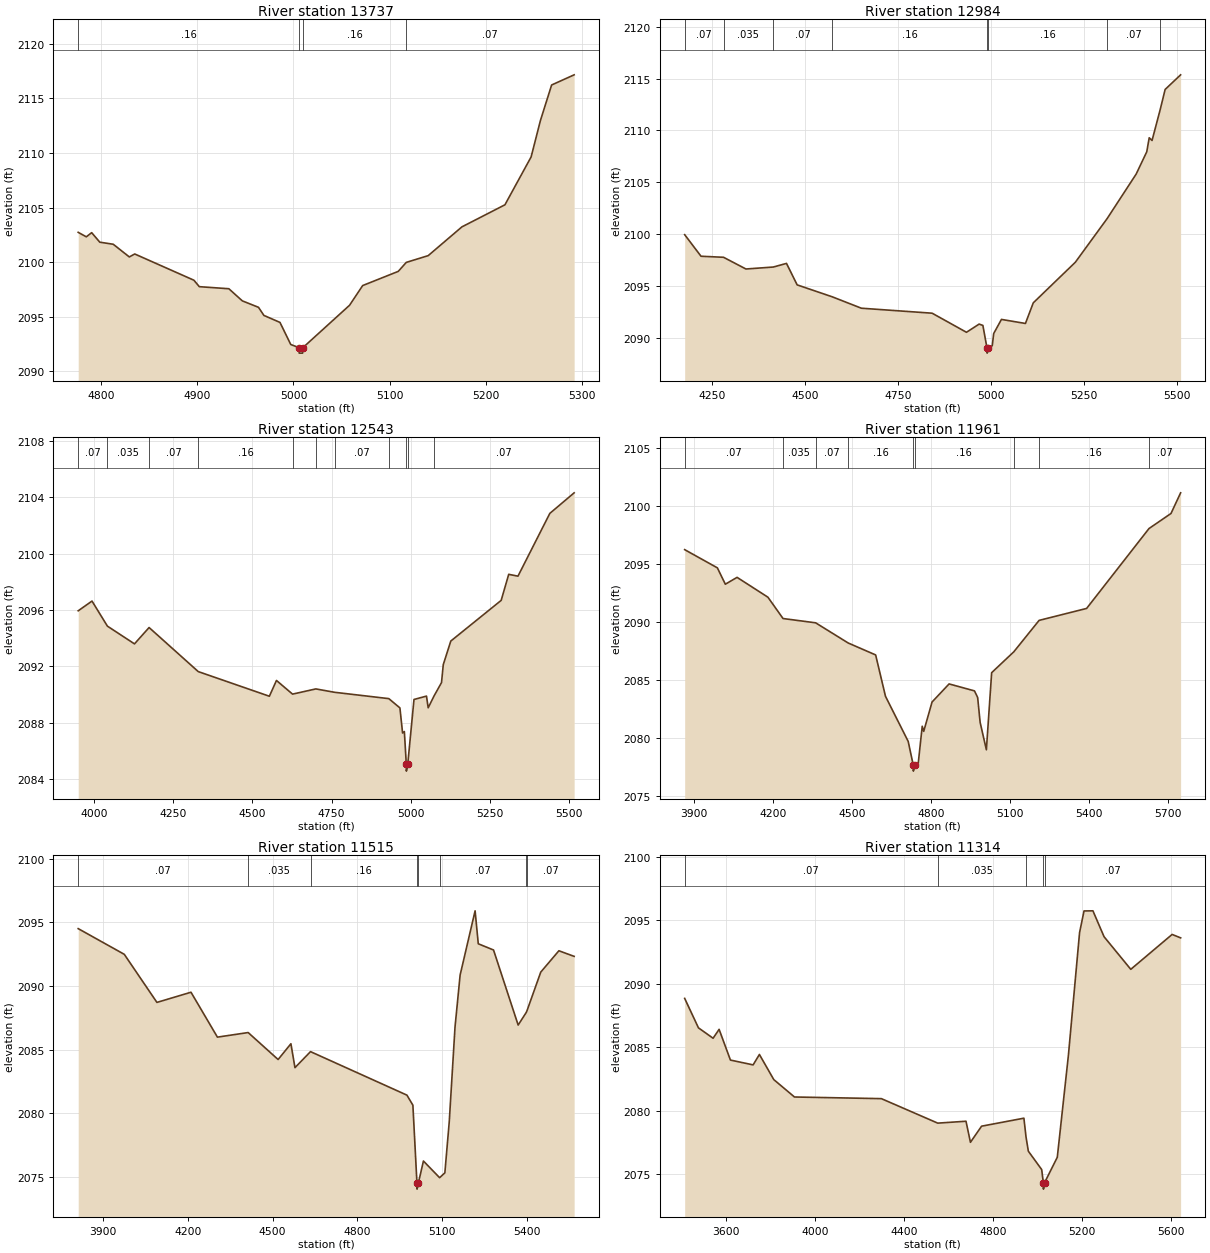
Type RM Length L Ch R = 1,13737,753,753,753
BEGIN DESCRIPTION:
MULBERRY CREEK TRIBUTARY 21A_1 28.0
END DESCRIPTION:
XS GIS Cut Line= 3
      1465104.98      6813888.01      1465305.00      6813788.00
      1465455.01      6813537.98
#Sta/Elev= 30
  4776.4 2102.73  4784.8 2102.32  4790.4 2102.70  4798.8 2101.83  4812.8 2101.64
  4829.5 2100.48  4835.1 2100.75  4896.6 2098.35  4902.2 2097.76  4932.9 2097.57
  4946.9 2096.46  4963.7 2095.87  4969.3 2095.13  4986.0 2094.49  4997.2 2092.47
  5005.8 2092.18  5006.0 2091.68  5009.5 2091.68  5009.8 2092.18  5058.3 2096.06
  5071.9 2097.86  5108.9 2099.16  5117.2 2099.98  5140.0 2100.60  5175.0 2103.23
  5219.7 2105.25  5246.9 2109.63  5256.6 2112.97  5268.2 2116.21  5291.6 2117.14
#Mann=4,-1,0
  4776.4    0.16       0  5005.8    0.07       0  5009.8    0.16       0
  5117.2    0.07       0
Bank Sta=5005.8,5009.8
Exp/Cntr=0.3,0.1

Type RM Length L Ch R = 1,12984,441,441,441
BEGIN DESCRIPTION:
MULBERRY CREEK TRIBUTARY 21A_1 27.0
END DESCRIPTION:
XS GIS Cut Line= 3
      1465605.01      6814587.97      1465945.02      6813838.05
      1465612.27      6813452.08
#Sta/Elev= 30
  4176.6 2099.95  4220.5 2097.87  4281.0 2097.77  4341.3 2096.64  4414.9 2096.83
  4450.3 2097.18  4478.9 2095.11  4573.2 2093.96  4651.5 2092.86  4841.7 2092.38
  4934.0 2090.54  4968.1 2091.33  4978.1 2091.20  4989.2 2089.03  4989.5 2088.53
  4993.2 2089.03  5003.3 2089.24  5007.2 2090.42  5028.0 2091.78  5092.5 2091.39
  5113.6 2093.38  5226.6 2097.29  5311.9 2101.49  5390.1 2105.79  5418.6 2107.94
  5425.2 2109.29  5432.8 2109.03  5454.8 2112.02  5468.0 2113.95  5509.6 2115.36
#Mann=8,-1,0
  4176.6    0.07       0  4281.0   0.035       0  4414.9    0.07       0
  4573.2    0.16       0  4989.2    0.07       0  4993.2    0.16       0
  5311.9    0.07       0  5454.8    0.16       0
Bank Sta=4989.2,4993.2
Exp/Cntr=0.3,0.1

Type RM Length L Ch R = 1,12543,582,582,582
BEGIN DESCRIPTION:
MULBERRY CREEK TRIBUTARY 21A_1 26.0
END DESCRIPTION:
XS GIS Cut Line= 3
      1465813.73      6814576.96      1466280.25      6813637.41
      1466479.63      6813162.13
#Sta/Elev= 30
  3951.0 2095.95  3994.5 2096.64  4043.1 2094.86  4128.5 2093.60  4174.6 2094.76
  4329.7 2091.63  4554.0 2089.88  4576.4 2091.00  4627.1 2090.03  4700.5 2090.40
  4759.8 2090.16  4930.8 2089.71  4965.8 2089.05  4974.2 2087.27  4979.8 2087.37
  4985.9 2085.06  4986.2 2084.56  4990.5 2085.06  5010.2 2089.65  5049.6 2089.89
  5055.0 2089.06  5073.7 2089.91  5097.0 2090.85  5102.6 2092.13  5126.3 2093.80
  5285.2 2096.69  5309.0 2098.54  5338.2 2098.41  5438.7 2102.87  5515.4 2104.33
#Mann=11,-1,0
  3951.0    0.07       0  4043.1   0.035       0  4174.6    0.07       0
  4329.7    0.16       0  4627.1    0.07       0  4700.5    0.16       0
  4759.8    0.07       0  4930.8    0.16       0  4985.9    0.07       0
  4990.5    0.16       0  5073.7    0.07       0
Bank Sta=4985.9,4990.5
Exp/Cntr=0.3,0.1

Type RM Length L Ch R = 1,11961,446,446,446
BEGIN DESCRIPTION:
MULBERRY CREEK TRIBUTARY 21A_1 25.0
END DESCRIPTION:
XS GIS Cut Line= 3
      1466188.74      6814821.76      1466755.00      6813838.00
      1466722.63      6813091.49
#Sta/Elev= 30
  3864.6 2096.26  3988.7 2094.69  4018.9 2093.28  4063.5 2093.87  4180.5 2092.16
  4237.9 2090.32  4361.6 2089.95  4485.2 2088.21  4589.4 2087.18  4626.8 2083.61
  4713.0 2079.72  4732.3 2077.66  4732.6 2077.16  4736.9 2077.66  4750.4 2077.70
  4766.2 2081.03  4771.9 2080.59  4803.5 2083.12  4868.2 2084.68  4964.5 2084.08
  4976.6 2083.51  4986.0 2081.36  5009.7 2079.00  5029.7 2085.65  5113.8 2087.45
  5209.8 2090.16  5390.1 2091.19  5626.9 2098.08  5710.4 2099.38  5746.9 2101.16
#Mann=9,-1,0
  3864.6    0.07       0  4237.9   0.035       0  4361.6    0.07       0
  4485.2    0.16       0  4732.3    0.07       0  4736.9    0.16       0
  5113.8    0.07       0  5209.8    0.16       0  5626.9    0.07       0
Bank Sta=4732.3,4736.9
Exp/Cntr=0.3,0.1

Type RM Length L Ch R = 1,11515,201,201,201
BEGIN DESCRIPTION:
Mapping XS 2b23009a
END DESCRIPTION:
XS GIS Cut Line= 3
      1466551.01      6815032.30      1467096.15      6814008.00
      1467200.00      6813422.97
#Sta/Elev= 30
  3812.4 2094.51  3975.4 2092.49  4090.9 2088.71  4211.4 2089.51  4304.9 2085.98
  4413.6 2086.34  4519.6 2084.22  4564.9 2085.46  4579.2 2083.58  4634.2 2084.84
  4975.3 2081.42  4996.4 2080.63  5010.7 2074.53  5011.1 2074.03  5016.0 2074.53
  5033.7 2076.24  5090.9 2074.93  5109.5 2075.31  5125.1 2079.34  5145.4 2086.76
  5163.5 2090.86  5216.5 2095.91  5227.7 2093.32  5281.7 2092.83  5368.8 2086.93
  5397.7 2087.93  5400.8 2088.10  5448.7 2091.09  5512.9 2092.77  5566.9 2092.33
#Mann=8,-1,0
  3812.4    0.07       0  4413.6   0.035       0  4634.2    0.16       0
  5010.7    0.07       0  5016.0    0.16       0  5090.9    0.07       0
  5397.7    0.16       0  5400.8    0.07       0
Bank Sta=5010.7,5016
Exp/Cntr=0.3,0.1

Type RM Length L Ch R = 1,11314,175,175,175
BEGIN DESCRIPTION:
Mapping XS bf3e24a4
END DESCRIPTION:
XS GIS Cut Line= 3
      1466936.44      6815535.75      1467280.18      6815028.83
      1467269.76      6813414.24
#Sta/Elev= 30
  3416.0 2088.86  3477.8 2086.54  3543.6 2085.72  3570.6 2086.42  3621.5 2084.00
  3723.3 2083.62  3751.6 2084.44  3816.2 2082.46  3909.1 2081.09  4299.3 2080.96
  4552.5 2079.03  4679.3 2079.18  4699.3 2077.52  4749.3 2078.79  4939.3 2079.42
  4948.9 2077.94  4959.3 2076.82  5019.3 2075.37  5026.7 2074.33  5027.1 2073.83
  5032.0 2074.33  5089.3 2076.34  5139.3 2084.39  5189.3 2094.04  5209.3 2095.75
  5249.3 2095.76  5299.3 2093.72  5419.3 2091.15  5605.0 2093.90  5643.1 2093.63
#Mann=5,-1,0
  3416.0    0.07       0  4552.5   0.035       0  4948.9    0.07       0
  5026.7    0.07       0  5032.0    0.07       0
Bank Sta=5026.7,5032
Exp/Cntr=0.3,0.1

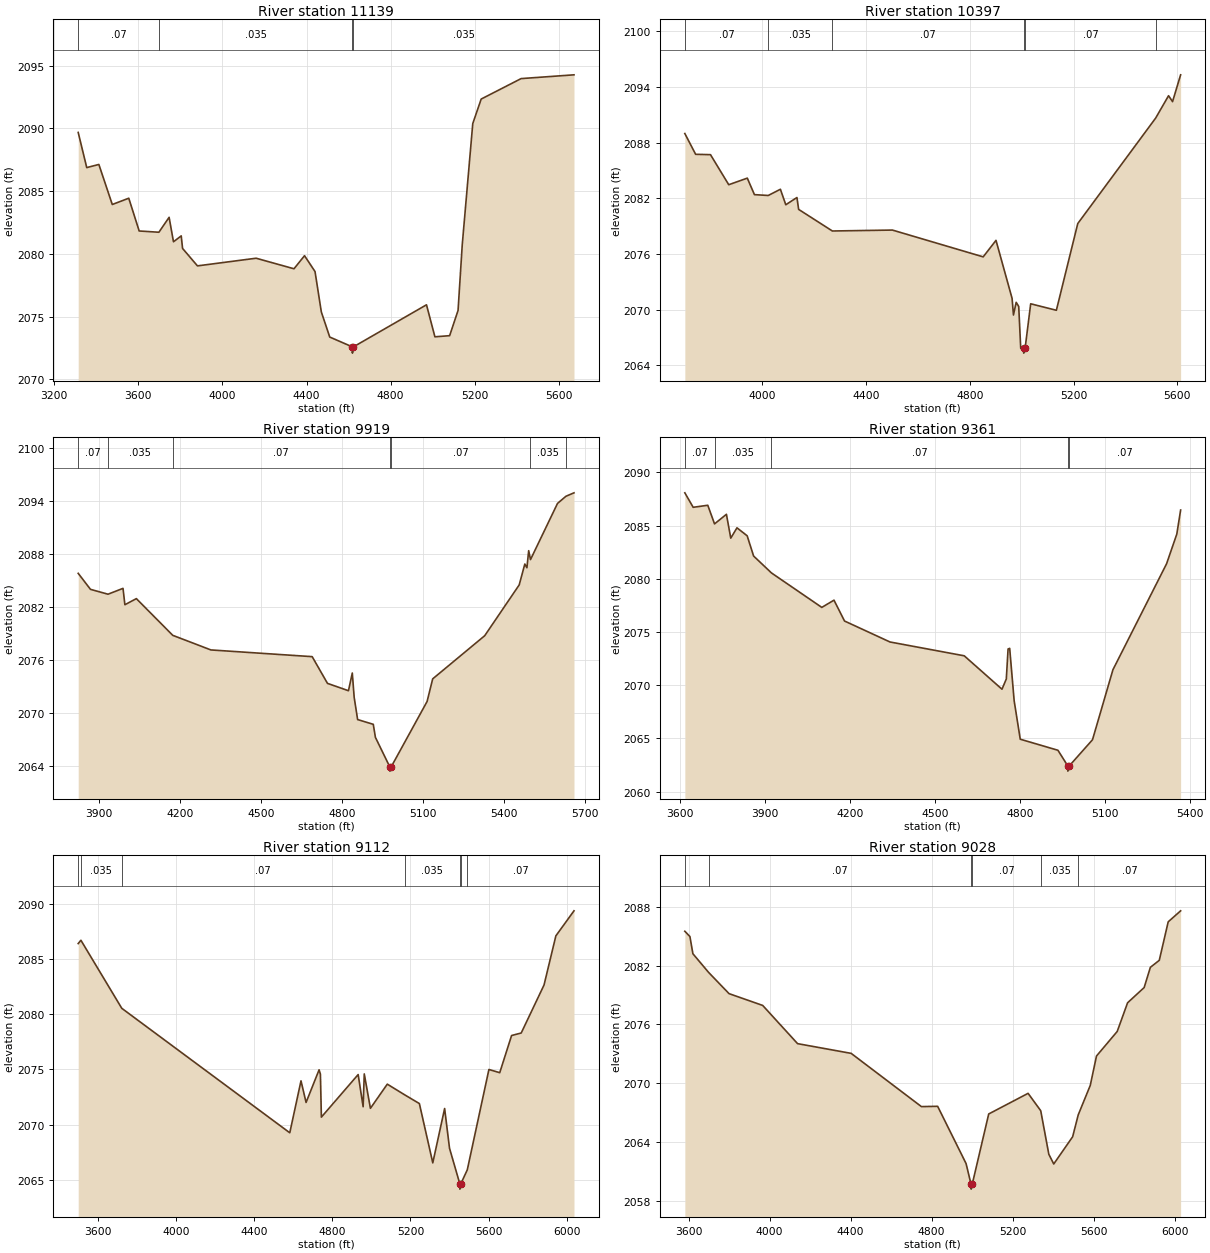
Type RM Length L Ch R = 1,11139,742,742,742
BEGIN DESCRIPTION:
Mapping XS 1e20d21c
END DESCRIPTION:
XS GIS Cut Line= 4
      1467057.97      6815698.95      1467439.90      6815226.75
      1467415.59      6814143.42      1467426.01      6813476.73
#Sta/Elev= 30
  3314.1 2089.67  3354.7 2086.87  3412.3 2087.12  3476.2 2083.93  3554.6 2084.43
  3604.1 2081.82  3697.8 2081.72  3746.4 2082.91  3767.2 2080.96  3804.0 2081.43
  3810.4 2080.43  3881.2 2079.04  4160.2 2079.65  4340.3 2078.81  4390.3 2079.85
  4440.3 2078.59  4470.3 2075.37  4510.3 2073.37  4617.7 2072.59  4618.1 2072.09
  4623.0 2072.59  4970.4 2075.94  5010.4 2073.39  5080.5 2073.48  5120.5 2075.49
  5140.5 2080.74  5190.5 2090.38  5230.5 2092.33  5420.5 2093.96  5671.8 2094.26
#Mann=4,-1,0
  3314.1    0.07       0  3697.8   0.035       0  4617.7   0.035       0
  4623.0   0.035       0
Bank Sta=4617.7,4623
Exp/Cntr=0.3,0.1

Type RM Length L Ch R = 1,10397,478,478,478
BEGIN DESCRIPTION:
Mapping XS 4f924c6b
END DESCRIPTION:
XS GIS Cut Line= 4
      1467092.68      6815744.11      1467526.70      6815223.28
      1467731.56      6814639.94      1467877.38      6814042.82
#Sta/Elev= 30
  3701.6 2088.98  3743.2 2086.74  3800.5 2086.70  3870.8 2083.46  3942.3 2084.17
  3969.9 2082.39  4023.1 2082.30  4069.9 2082.97  4090.7 2081.30  4133.7 2082.08
  4140.2 2080.80  4270.2 2078.47  4501.7 2078.57  4851.5 2075.68  4900.9 2077.46
  4962.9 2071.20  4968.2 2069.41  4978.7 2070.78  4988.5 2070.33  4996.2 2065.81
  5007.3 2065.80  5007.7 2065.30  5013.0 2065.80  5034.6 2070.62  5133.6 2069.92
  5216.0 2079.27  5516.4 2090.65  5566.0 2093.06  5581.4 2092.42  5612.5 2095.31
#Mann=6,-1,0
  3701.6    0.07       0  4023.1   0.035       0  4270.2    0.07       0
  5007.3    0.07       0  5013.0    0.07       0  5516.4   0.035       0
Bank Sta=5007.3,5013
Exp/Cntr=0.3,0.1

Type RM Length L Ch R = 1,9919,558,558,558
BEGIN DESCRIPTION:
Mapping XS 59003f2d
END DESCRIPTION:
XS GIS Cut Line= 3
      1467221.12      6815768.45      1467936.43      6815014.94
      1468547.55      6814504.52
#Sta/Elev= 30
  3822.9 2085.79  3868.3 2083.98  3933.2 2083.43  3988.8 2084.09  3995.7 2082.24
  4038.2 2082.93  4172.9 2078.78  4314.1 2077.13  4689.0 2076.37  4745.6 2073.35
  4823.3 2072.52  4837.5 2074.52  4844.4 2071.78  4857.2 2069.26  4915.2 2068.72
  4923.0 2067.25  4976.0 2063.93  4976.5 2063.43  4981.8 2063.93  5114.3 2071.30
  5135.1 2073.86  5327.7 2078.74  5455.3 2084.48  5476.1 2086.84  5483.9 2086.42
  5490.4 2088.35  5497.1 2087.34  5597.1 2093.69  5628.3 2094.50  5658.1 2094.89
#Mann=7,-1,0
  3822.9    0.07       0  3933.2   0.035       0  4172.9    0.07       0
  4976.0    0.07       0  4981.8    0.07       0  5497.1   0.035       0
  5628.3    0.07       0
Bank Sta=4976,4981.8
Exp/Cntr=0.3,0.1

Type RM Length L Ch R = 1,9361,249,249,249
BEGIN DESCRIPTION:
MULBERRY CREEK TRIBUTARY 21A_1 19.0
END DESCRIPTION:
XS GIS Cut Line= 3
      1467204.99      6815938.00      1468405.00      6815238.00
      1468605.00      6814938.01
#Sta/Elev= 30
  3616.1 2088.08  3645.5 2086.72  3697.1 2086.91  3720.9 2085.16  3762.9 2086.06
  3778.2 2083.82  3800.1 2084.79  3836.1 2084.04  3858.8 2082.14  3921.8 2080.55
  4099.5 2077.31  4142.5 2077.99  4179.7 2076.03  4340.1 2074.06  4602.2 2072.76
  4735.4 2069.62  4750.7 2070.58  4756.9 2073.40  4762.6 2073.46  4778.4 2068.53
  4799.9 2064.92  4933.0 2063.88  4967.3 2062.42  4967.8 2061.92  4973.2 2062.42
  5054.9 2064.87  5127.0 2071.45  5316.3 2081.41  5352.4 2084.20  5365.9 2086.46
#Mann=5,-1,0
  3616.1    0.07       0  3720.9   0.035       0  3921.8    0.07       0
  4967.3    0.07       0  4973.2    0.07       0
Bank Sta=4967.3,4973.2
Exp/Cntr=0.3,0.1

Type RM Length L Ch R = 1,9112,84,84,84
BEGIN DESCRIPTION:
Mapping XS 18ca9091
END DESCRIPTION:
XS GIS Cut Line= 6
      1467283.16      6815974.01      1468210.27      6815373.30
      1468557.50      6815404.55      1468672.08      6815348.99
      1468849.16      6815342.05      1469578.36      6815071.20
#Sta/Elev= 30
  3497.9 2086.42  3511.8 2086.72  3721.1 2080.55  4581.8 2069.26  4639.3 2073.97
  4665.3 2072.01  4731.9 2074.97  4738.7 2074.58  4743.7 2070.68  4932.1 2074.54
  4957.6 2071.62  4963.4 2074.60  4994.9 2071.48  5081.4 2073.67  5169.7 2072.71
  5245.7 2071.91  5314.4 2066.53  5375.1 2071.46  5400.1 2067.86  5452.6 2064.65
  5453.1 2064.15  5458.5 2064.65  5491.2 2065.90  5602.0 2075.00  5657.4 2074.71
  5718.1 2078.08  5767.5 2078.31  5884.3 2082.66  5945.0 2087.12  6037.8 2089.39
#Mann=7,-1,0
  3497.9    0.07       0  3511.8   0.035       0  3721.1    0.07       0
  5169.7   0.035       0  5452.6    0.07       0  5458.5   0.035       0
  5491.2    0.07       0
Bank Sta=5452.6,5458.5
Exp/Cntr=0.3,0.1

Type RM Length L Ch R = 1,9028,241,241,241
BEGIN DESCRIPTION:
MULBERRY CREEK TRIBUTARY 21A_1 18.0
END DESCRIPTION:
XS GIS Cut Line= 4
      1467377.66      6816016.15      1468129.94      6815482.30
      1468625.28      6815457.88      1469630.91      6815240.26
#Sta/Elev= 30
  3581.6 2085.49  3606.7 2084.95  3621.4 2083.20  3699.0 2081.30  3799.8 2079.14
  3965.9 2077.94  4138.1 2074.05  4402.6 2073.06  4749.4 2067.64  4829.5 2067.67
  4969.7 2061.85  4994.4 2059.74  4994.9 2059.24  5000.3 2059.74  5081.6 2066.89
  5276.0 2068.99  5338.4 2067.22  5378.3 2062.79  5402.6 2061.80  5495.9 2064.57
  5523.5 2066.80  5582.9 2069.80  5613.6 2072.79  5715.9 2075.29  5767.1 2078.21
  5848.9 2079.76  5879.6 2081.82  5923.5 2082.53  5967.6 2086.45  6028.9 2087.57
#Mann=6,-1,0
  3581.6   0.035       0  3699.0    0.07       0  4994.4    0.07       0
  5000.3    0.07       0  5338.4   0.035       0  5523.5    0.07       0
Bank Sta=4994.4,5000.3
Exp/Cntr=0.3,0.1

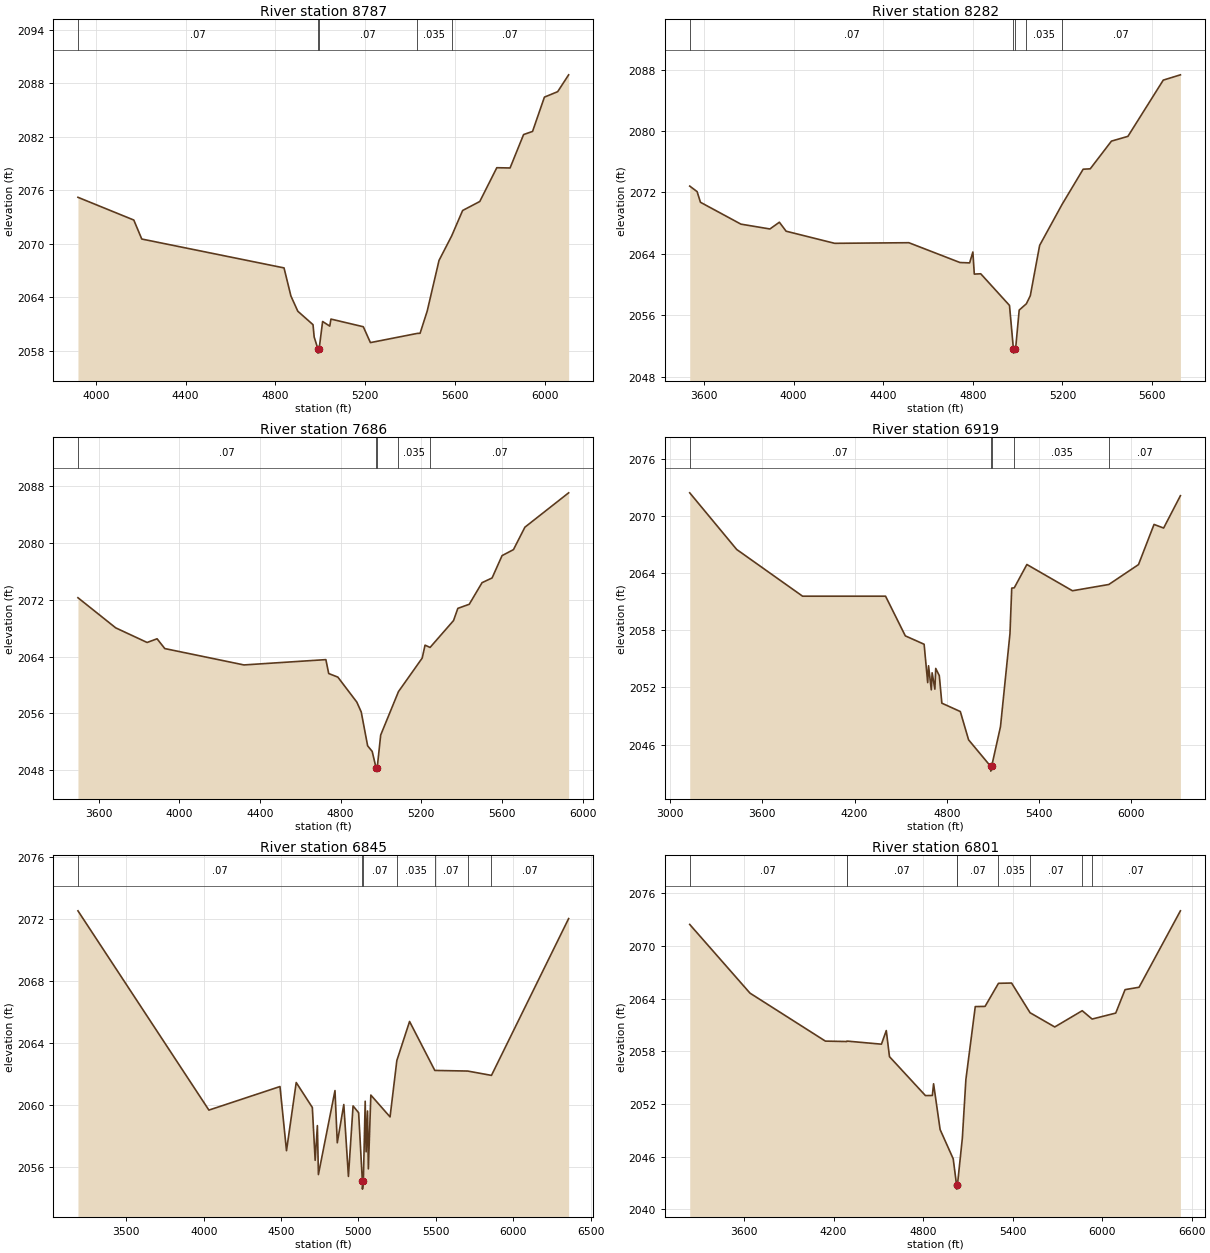
Type RM Length L Ch R = 1,8787,505,505,505
BEGIN DESCRIPTION:
Mapping XS d2eaa687
END DESCRIPTION:
XS GIS Cut Line= 5
      1467785.71      6816237.45      1468493.14      6815720.99
      1468705.81      6815673.24      1469287.41      6815477.93
      1469730.10      6815291.30
#Sta/Elev= 30
  3919.8 2075.21  4168.8 2072.66  4204.3 2070.53  4838.6 2067.29  4869.3 2064.14
  4900.1 2062.43  4967.9 2060.92  4973.0 2059.54  4989.4 2058.23  4989.9 2057.73
  4995.3 2058.23  5010.7 2061.28  5042.5 2060.76  5047.8 2061.55  5192.1 2060.69
  5223.8 2058.91  5432.3 2059.94  5445.3 2059.96  5477.0 2062.45  5529.7 2068.13
  5585.9 2070.87  5634.9 2073.73  5711.4 2074.74  5787.3 2078.53  5846.4 2078.50
  5906.7 2082.25  5946.7 2082.60  5999.6 2086.45  6058.7 2087.06  6107.6 2088.95
#Mann=5,-1,0
  3919.8    0.07       0  4989.4    0.07       0  4995.3    0.07       0
  5432.3   0.035       0  5585.9    0.07       0
Bank Sta=4989.4,4995.3
Exp/Cntr=0.3,0.1

Type RM Length L Ch R = 1,8282,596,596,596
BEGIN DESCRIPTION:
Mapping XS a97f3f80
END DESCRIPTION:
XS GIS Cut Line= 4
      1468011.41      6816580.33      1468840.36      6816033.49
      1469217.97      6815556.06      1469777.85      6815373.77
#Sta/Elev= 30
  3536.1 2072.83  3569.0 2072.11  3584.0 2070.72  3764.7 2067.87  3894.1 2067.24
  3936.3 2068.12  3966.4 2066.95  4183.2 2065.37  4514.3 2065.45  4742.4 2062.87
  4785.7 2062.82  4800.1 2064.24  4806.5 2061.36  4835.3 2061.40  4963.6 2057.28
  4981.3 2051.56  4981.8 2051.06  4987.4 2051.56  4992.4 2052.09  5006.9 2056.67
  5038.9 2057.49  5056.5 2058.54  5098.2 2065.10  5197.9 2070.42  5292.5 2075.03
  5324.1 2075.08  5418.7 2078.69  5492.3 2079.31  5650.1 2086.64  5726.7 2087.33
#Mann=5,-1,0
  3536.1    0.07       0  4981.3    0.07       0  4987.4    0.07       0
  5038.9   0.035       0  5197.9    0.07       0
Bank Sta=4981.3,4987.4
Exp/Cntr=0.3,0.1

Type RM Length L Ch R = 1,7686,767,767,767
BEGIN DESCRIPTION:
Mapping XS 0cee0535
END DESCRIPTION:
XS GIS Cut Line= 3
      1468020.04      6816836.44      1469343.83      6816124.63
      1469990.28      6815456.50
#Sta/Elev= 30
  3498.1 2072.30  3685.4 2068.05  3840.9 2065.99  3890.4 2066.51  3928.6 2065.13
  4321.2 2062.82  4727.2 2063.57  4741.3 2061.61  4786.7 2061.10  4880.6 2057.58
  4902.5 2056.19  4934.3 2051.41  4956.9 2050.62  4975.7 2048.34  4976.2 2047.84
  4981.8 2048.34  4999.0 2052.93  5087.2 2059.06  5204.8 2063.79  5218.9 2065.61
  5243.9 2065.29  5360.2 2069.08  5381.5 2070.80  5438.1 2071.38  5501.6 2074.43
  5551.3 2075.09  5600.7 2078.24  5657.3 2079.09  5713.9 2082.25  5930.8 2087.10
#Mann=5,-1,0
  3498.1    0.07       0  4975.7    0.07       0  4981.8    0.07       0
  5087.2   0.035       0  5243.9    0.07       0
Bank Sta=4975.7,4981.8
Exp/Cntr=0.3,0.1

Type RM Length L Ch R = 1,6919,74,74,74
BEGIN DESCRIPTION:
Mapping XS 2c7ee84a
END DESCRIPTION:
XS GIS Cut Line= 5
      1468020.07      6816940.60      1469270.05      6816458.83
      1469665.01      6816632.44      1470025.26      6816810.40
      1471021.76      6816598.10
#Sta/Elev= 30
  3127.7 2072.45  3433.1 2066.50  3861.7 2061.59  4401.5 2061.59  4530.1 2057.42
  4652.3 2056.54  4675.6 2052.51  4681.1 2054.28  4699.0 2051.75  4704.4 2053.54
  4722.3 2051.82  4727.8 2054.00  4751.1 2053.24  4767.6 2050.35  4887.8 2049.47
  4941.5 2046.50  5085.2 2043.71  5085.7 2043.21  5091.5 2043.71  5149.0 2047.88
  5210.8 2057.67  5222.2 2062.44  5238.7 2062.47  5320.7 2064.92  5617.2 2062.16
  5853.7 2062.82  6046.7 2064.91  6147.8 2069.13  6210.2 2068.75  6319.4 2072.15
#Mann=5,-1,0
  3127.7    0.07       0  5085.2    0.07       0  5091.5    0.07       0
  5238.7   0.035       0  5853.7    0.07       0
Bank Sta=5085.2,5091.5
Exp/Cntr=0.3,0.1

Type RM Length L Ch R = 1,6845,44,44,44
BEGIN DESCRIPTION:
Mapping XS 0641d046
END DESCRIPTION:
XS GIS Cut Line= 6
      1468052.30      6816972.25      1469364.79      6816548.65
      1469517.57      6816593.79      1469868.26      6816826.42
      1470048.82      6816861.15      1471051.11      6816632.25
#Sta/Elev= 30
  3187.3 2072.52  4033.7 2059.66  4493.1 2061.18  4535.2 2057.04  4598.0 2061.44
  4702.2 2059.83  4720.4 2056.42  4734.8 2058.66  4741.4 2055.50  4848.6 2060.92
  4863.4 2057.55  4905.5 2060.02  4935.4 2055.38  4965.4 2059.93  5001.3 2059.49
  5025.6 2055.06  5026.1 2054.56  5031.9 2055.06  5043.8 2060.23  5049.8 2056.97
  5058.9 2059.60  5064.2 2055.87  5080.3 2060.63  5204.5 2059.22  5248.4 2062.86
  5330.6 2065.38  5493.7 2062.22  5706.1 2062.18  5859.9 2061.90  6358.7 2072.02
#Mann=7,-1,0
  3187.3    0.07       0  5025.6    0.07       0  5031.9    0.07       0
  5248.4   0.035       0  5493.7    0.07       0  5706.1   0.035       0
  5859.9    0.07       0
Bank Sta=5025.6,5031.9
Exp/Cntr=0.3,0.1

Type RM Length L Ch R = 1,6801,293,293,293
BEGIN DESCRIPTION:
Mapping XS 7bba1752
END DESCRIPTION:
XS GIS Cut Line= 5
      1468046.09      6816992.69      1469313.45      6816602.06
      1469712.76      6816780.01      1469990.54      6816970.99
      1471131.01      6816637.08
#Sta/Elev= 30
  3236.1 2072.44  3640.1 2064.62  4145.3 2059.16  4288.9 2059.11  4290.6 2059.16
  4521.0 2058.81  4553.5 2060.36  4574.9 2057.39  4815.8 2052.96  4862.2 2052.97
  4870.5 2054.30  4914.3 2049.09  5002.1 2045.76  5024.3 2042.81  5024.8 2042.31
  5030.6 2042.81  5063.3 2048.11  5087.0 2054.78  5149.9 2063.09  5215.5 2063.11
  5305.5 2065.74  5393.3 2065.77  5517.2 2062.39  5682.6 2060.77  5866.7 2062.62
  5933.2 2061.67  6091.4 2062.35  6153.9 2065.02  6247.7 2065.29  6524.9 2073.99
#Mann=9,-1,0
  3236.1    0.07       0  4288.9   0.035       0  4290.6    0.07       0
  5024.3    0.07       0  5030.6    0.07       0  5305.5   0.035       0
  5517.2    0.07       0  5866.7   0.035       0  5933.2    0.07       0
Bank Sta=5024.3,5030.6
Exp/Cntr=0.3,0.1

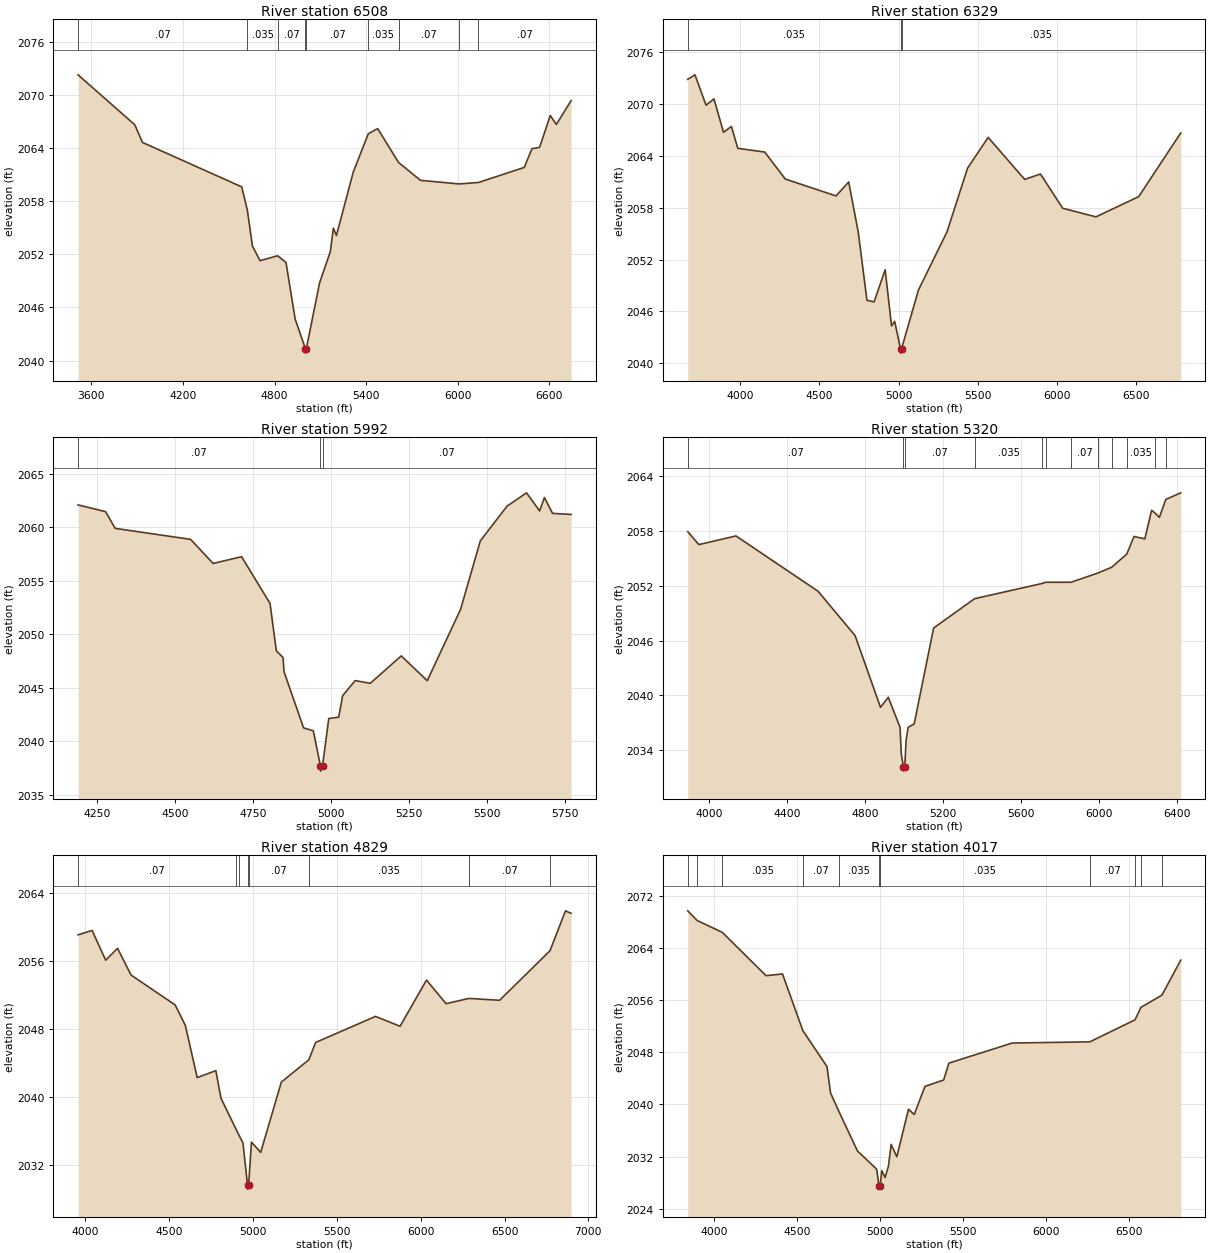
Type RM Length L Ch R = 1,6508,179,179,179
BEGIN DESCRIPTION:
Mapping XS 8e3b543f
END DESCRIPTION:
XS GIS Cut Line= 4
      1468063.47      6817010.05      1469547.83      6816988.35
      1470003.56      6817005.71      1471291.31      6816992.70
#Sta/Elev= 30
  3513.2 2072.29  3884.8 2066.64  3934.8 2064.65  4584.8 2059.63  4621.8 2057.00
  4654.9 2052.94  4704.9 2051.29  4819.9 2051.84  4874.9 2051.08  4934.9 2044.68
  5001.7 2041.34  5002.2 2040.84  5008.0 2041.34  5095.0 2048.80  5165.0 2052.30
  5185.0 2054.97  5205.0 2054.13  5315.1 2061.29  5413.7 2065.63  5475.2 2066.21
  5611.7 2062.39  5755.2 2060.37  6007.8 2059.96  6134.6 2060.12  6435.3 2061.83
  6485.3 2063.94  6535.3 2064.09  6605.3 2067.69  6645.3 2066.68  6741.6 2069.37
#Mann=9,-1,0
  3513.2    0.07       0  4621.8   0.035       0  4819.9    0.07       0
  5001.7    0.07       0  5008.0    0.07       0  5413.7   0.035       0
  5611.7    0.07       0  6007.8   0.035       0  6134.6    0.07       0
Bank Sta=5001.7,5008
Exp/Cntr=0.3,0.1

Type RM Length L Ch R = 1,6329,337,337,337
BEGIN DESCRIPTION:
Mapping XS 9343fa30
END DESCRIPTION:
XS GIS Cut Line= 3
      1468129.44      6817172.37      1469466.23      6817137.65
      1471240.27      6817116.82
#Sta/Elev= 30
  3668.9 2072.82  3714.5 2073.34  3784.5 2069.83  3834.5 2070.56  3894.5 2066.70
  3944.5 2067.38  3984.6 2064.85  4154.6 2064.42  4284.7 2061.30  4604.8 2059.35
  4684.8 2060.96  4744.8 2055.18  4800.0 2047.29  4844.9 2047.11  4914.9 2050.82
  4954.9 2044.33  4974.9 2044.86  5011.8 2041.69  5012.3 2041.19  5018.1 2041.69
  5124.9 2048.48  5304.9 2055.19  5434.9 2062.56  5564.9 2066.11  5795.0 2061.26
  5895.0 2061.88  6035.0 2057.93  6245.0 2056.93  6515.0 2059.27  6780.3 2066.63
#Mann=3,-1,0
  3668.9   0.035       0  5011.8   0.035       0  5018.1   0.035       0
Bank Sta=5011.8,5018.1
Exp/Cntr=0.3,0.1

Type RM Length L Ch R = 1,5992,672,672,672
BEGIN DESCRIPTION:
Mapping XS e2c09809
END DESCRIPTION:
XS GIS Cut Line= 3
      1468697.78      6817583.93      1469343.66      6817474.55
      1470220.63      6817175.28
#Sta/Elev= 30
  4189.2 2062.11  4277.7 2061.48  4308.1 2059.92  4550.3 2058.89  4622.5 2056.64
  4713.8 2057.27  4805.1 2052.90  4825.3 2048.47  4846.7 2047.85  4850.0 2046.52
  4912.7 2041.27  4944.0 2041.00  4966.7 2037.73  4967.2 2037.23  4973.5 2037.73
  4993.6 2042.15  5025.3 2042.27  5038.0 2044.28  5078.1 2045.69  5126.7 2045.44
  5226.1 2048.00  5309.4 2045.68  5416.3 2052.34  5479.7 2058.75  5565.3 2061.99
  5628.0 2063.24  5669.9 2061.55  5685.4 2062.80  5711.4 2061.32  5770.9 2061.22
#Mann=3,-1,0
  4189.2    0.07       0  4966.7    0.07       0  4973.5    0.07       0
Bank Sta=4966.7,4973.5
Exp/Cntr=0.3,0.1

Type RM Length L Ch R = 1,5320,491,491,491
BEGIN DESCRIPTION:
Mapping XS 4d4a0f8a
END DESCRIPTION:
XS GIS Cut Line= 4
      1468848.05      6817800.06      1469920.05      6817778.36
      1470375.78      6817665.52      1471260.58      6817236.13
#Sta/Elev= 30
  3891.7 2057.94  3948.7 2056.52  4138.7 2057.47  4558.8 2051.41  4748.8 2046.54
  4878.9 2038.67  4918.9 2039.77  4979.3 2036.46  4985.4 2033.55  4996.5 2032.17
  4997.0 2031.67  5003.3 2032.17  5010.2 2035.08  5020.5 2036.48  5051.4 2036.84
  5151.0 2047.37  5361.3 2050.59  5707.8 2052.26  5725.9 2052.39  5854.9 2052.39
  5993.8 2053.41  6063.3 2054.04  6140.4 2055.48  6177.5 2057.41  6232.9 2057.15
  6267.7 2060.29  6286.4 2059.95  6307.3 2059.51  6340.5 2061.48  6416.9 2062.20
#Mann=12,-1,0
  3891.7    0.07       0  4996.5    0.07       0  5003.3    0.07       0
  5361.3   0.035       0  5707.8    0.07       0  5725.9   0.035       0
  5854.9    0.07       0  5993.8   0.035       0  6063.3    0.07       0
  6140.4   0.035       0  6286.4    0.07       0  6340.5   0.035       0
Bank Sta=4996.5,5003.3
Exp/Cntr=0.3,0.1

Type RM Length L Ch R = 1,4829,812,812,812
BEGIN DESCRIPTION:
Mapping XS bfb6d1fe
END DESCRIPTION:
XS GIS Cut Line= 4
      1468722.15      6818312.22      1469763.80      6818155.97
      1470692.62      6817756.66      1471495.60      6817405.09
#Sta/Elev= 30
  3955.8 2059.07  4039.6 2059.59  4120.5 2056.08  4191.3 2057.48  4272.2 2054.33
  4535.1 2050.81  4595.7 2048.40  4666.5 2042.25  4777.7 2043.07  4808.1 2039.83
  4896.7 2036.23  4914.0 2035.53  4939.5 2034.55  4966.5 2029.61  4967.0 2029.11
  4973.3 2029.61  4990.1 2034.65  5045.2 2033.44  5168.4 2041.72  5332.3 2044.35
  5373.1 2046.39  5729.9 2049.46  5876.6 2048.30  6034.2 2053.74  6151.1 2050.96
  6287.3 2051.58  6470.3 2051.36  6771.1 2057.20  6863.3 2061.90  6896.7 2061.61
#Mann=8,-1,0
  3955.8    0.07       0  4896.7   0.035       0  4914.0    0.07       0
  4966.5    0.07       0  4973.3    0.07       0  5332.3   0.035       0
  6287.3    0.07       0  6771.1   0.035       0
Bank Sta=4966.5,4973.3
Exp/Cntr=0.3,0.1

Type RM Length L Ch R = 1,4017,462,462,462
BEGIN DESCRIPTION:
Mapping XS e8669ff0
END DESCRIPTION:
XS GIS Cut Line= 4
      1469559.80      6819401.64      1470280.29      6818672.46
      1470384.46      6817965.00      1471517.24      6817470.22
#Sta/Elev= 30
  3839.0 2069.70  3895.7 2068.22  4047.4 2066.40  4311.9 2059.75  4410.9 2060.02
  4533.9 2051.32  4679.6 2045.80  4700.9 2041.78  4750.8 2038.96  4863.5 2032.87
  4979.8 2030.06  4993.6 2027.51  4994.1 2027.01  5000.8 2027.51  5010.1 2029.85
  5030.3 2028.80  5050.5 2030.51  5066.9 2033.87  5101.1 2031.97  5171.8 2039.27
  5206.3 2038.45  5270.9 2042.77  5384.1 2043.75  5415.4 2046.34  5798.0 2049.42
  6266.2 2049.60  6539.3 2052.98  6575.0 2054.89  6701.8 2056.77  6815.3 2062.14
#Mann=11,-1,0
  3839.0   0.035       0  3895.7    0.07       0  4047.4   0.035       0
  4533.9    0.07       0  4750.8   0.035       0  4993.6   0.035       0
  5000.8   0.035       0  6266.2    0.07       0  6539.3   0.035       0
  6575.0    0.07       0  6701.8   0.035       0
Bank Sta=4993.6,5000.8
Exp/Cntr=0.3,0.1

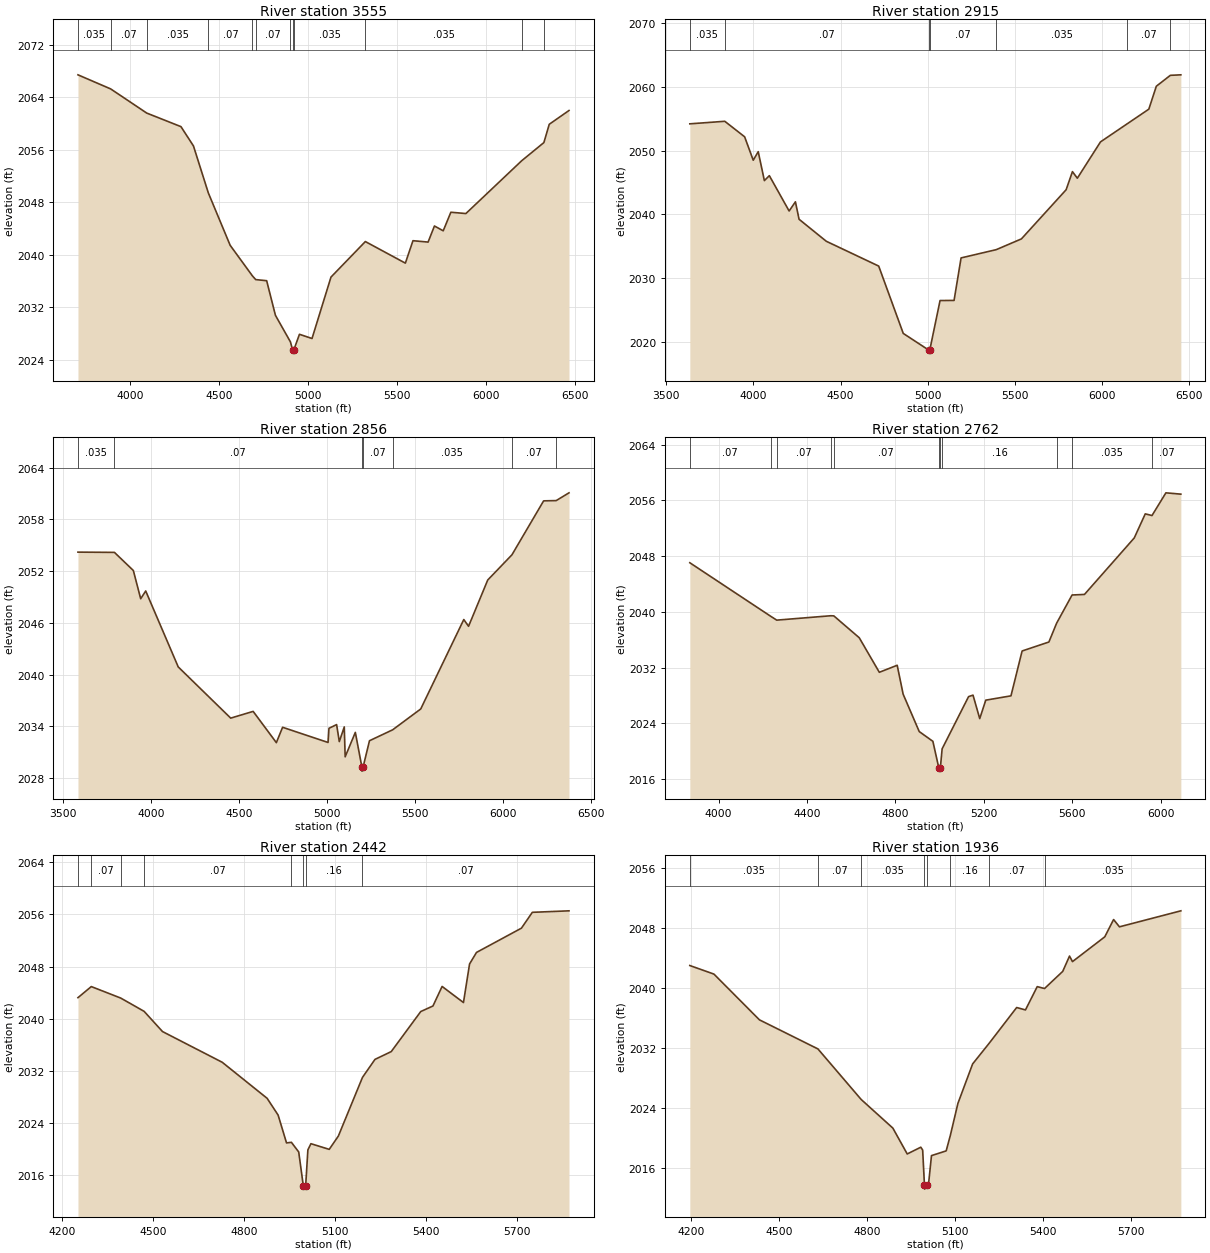
Type RM Length L Ch R = 1,3555,640,640,640
BEGIN DESCRIPTION:
Mapping XS a2986796
END DESCRIPTION:
XS GIS Cut Line= 3
      1469703.05      6819562.20      1470688.28      6818720.20
      1471638.79      6817604.77
#Sta/Elev= 30
  3704.8 2067.41  3888.9 2065.26  4091.5 2061.58  4284.0 2059.51  4354.3 2056.57
  4437.8 2049.42  4560.7 2041.42  4686.1 2036.75  4704.5 2036.19  4766.0 2036.02
  4815.4 2030.74  4899.8 2026.69  4911.7 2025.48  4912.2 2024.98  4918.9 2025.48
  4950.4 2027.85  5021.1 2027.21  5127.7 2036.57  5321.0 2041.99  5546.0 2038.70
  5588.8 2042.12  5673.8 2041.91  5709.6 2044.36  5759.0 2043.63  5801.9 2046.46
  5886.4 2046.26  6200.2 2054.31  6325.0 2057.08  6355.3 2059.87  6466.3 2061.97
#Mann=12,-1,0
  3704.8   0.035       0  3888.9    0.07       0  4091.5   0.035       0
  4437.8    0.07       0  4686.1   0.035       0  4704.5    0.07       0
  4899.8   0.035       0  4911.7    0.07       0  4918.9   0.035       0
  5321.0   0.035       0  6200.2    0.07       0  6325.0   0.035       0
Bank Sta=4911.7,4918.9
Exp/Cntr=0.3,0.1

Type RM Length L Ch R = 1,2915,59,59,59
BEGIN DESCRIPTION:
Mapping XS b9500f3e
END DESCRIPTION:
XS GIS Cut Line= 4
      1470410.54      6819996.21      1471174.39      6819349.55
      1471269.88      6818351.28      1471682.05      6817652.76
#Sta/Elev= 30
  3636.0 2054.20  3836.4 2054.60  3950.1 2052.17  3999.5 2048.50  4028.1 2049.84
  4063.3 2045.30  4091.8 2046.08  4205.2 2040.54  4241.3 2041.98  4262.1 2039.25
  4418.1 2035.80  4718.7 2031.91  4859.4 2021.36  5004.2 2018.77  5004.7 2018.27
  5011.6 2018.77  5070.3 2026.51  5150.7 2026.53  5190.9 2033.19  5393.1 2034.49
  5536.7 2036.17  5793.0 2043.87  5829.2 2046.71  5857.3 2045.68  5990.0 2051.37
  6143.4 2054.21  6267.1 2056.50  6310.0 2060.09  6390.4 2061.80  6450.7 2061.88
#Mann=7,-1,0
  3636.0   0.035       0  3836.4    0.07       0  5004.2    0.07       0
  5011.6    0.07       0  5393.1   0.035       0  6143.4    0.07       0
  6390.4   0.035       0
Bank Sta=5004.2,5011.6
Exp/Cntr=0.3,0.1

Type RM Length L Ch R = 1,2856,94,94,94
BEGIN DESCRIPTION:
Mapping XS cdca1b33
END DESCRIPTION:
XS GIS Cut Line= 6
      1470440.86      6820026.65      1471235.15      6819366.91
      1471261.20      6819201.98      1471265.54      6818997.98
      1471339.32      6818377.32      1471750.81      6817736.27
#Sta/Elev= 30
  3586.2 2054.20  3793.5 2054.17  3901.0 2052.07  3942.7 2048.80  3971.3 2049.70
  4156.2 2040.90  4454.4 2034.97  4582.0 2035.75  4713.9 2032.13  4749.3 2033.91
  5007.7 2032.15  5012.9 2033.79  5056.4 2034.22  5071.7 2032.25  5099.9 2033.95
  5105.0 2030.49  5162.8 2033.32  5199.8 2029.33  5200.3 2028.83  5207.2 2029.33
  5243.2 2032.35  5375.2 2033.62  5534.5 2036.03  5779.3 2046.39  5806.4 2045.61
  5915.4 2050.97  6053.0 2053.89  6233.1 2060.14  6304.6 2060.17  6377.3 2061.07
#Mann=7,-1,0
  3586.2   0.035       0  3793.5    0.07       0  5199.8    0.07       0
  5207.2    0.07       0  5375.2   0.035       0  6053.0    0.07       0
  6304.6   0.035       0
Bank Sta=5199.8,5207.2
Exp/Cntr=0.3,0.1

Type RM Length L Ch R = 1,2762,320,320,320
BEGIN DESCRIPTION:
Mapping XS bd2e0448
END DESCRIPTION:
XS GIS Cut Line= 4
      1470844.70      6819939.39      1471303.01      6819423.79
      1471454.05      6818304.00      1471698.87      6817986.26
#Sta/Elev= 30
  3870.3 2047.06  4236.3 2039.37  4263.4 2038.82  4507.5 2039.45  4521.6 2039.43
  4636.6 2036.29  4727.4 2031.33  4808.2 2032.34  4835.1 2028.19  4907.9 2022.82
  4969.6 2021.42  4996.2 2017.64  4996.7 2017.14  5003.6 2017.64  5011.4 2020.34
  5131.1 2027.84  5151.2 2028.05  5181.5 2024.68  5208.8 2027.33  5322.8 2027.95
  5373.2 2034.39  5494.3 2035.68  5529.4 2038.39  5599.2 2042.43  5655.2 2042.51
  5880.4 2050.62  5930.2 2054.08  5960.7 2053.84  6023.5 2057.10  6091.2 2056.91
#Mann=11,-1,0
  3870.3    0.07       0  4236.3   0.035       0  4263.4    0.07       0
  4507.5   0.035       0  4521.6    0.07       0  4996.2    0.07       0
  5003.6    0.07       0  5011.4    0.16       0  5529.4    0.07       0
  5599.2   0.035       0  5960.7    0.07       0
Bank Sta=4996.2,5003.6
Exp/Cntr=0.3,0.1

Type RM Length L Ch R = 1,2442,506,506,506
BEGIN DESCRIPTION:
Mapping XS 4123efa1
END DESCRIPTION:
XS GIS Cut Line= 3
      1471308.94      6819644.69      1471638.80      6819089.13
      1471742.87      6818122.12
#Sta/Elev= 30
  4251.8 2043.24  4295.7 2044.94  4392.7 2043.18  4469.9 2041.14  4530.5 2038.04
  4727.3 2033.33  4875.4 2027.80  4911.6 2025.23  4939.3 2020.96  4955.4 2021.05
  4979.5 2019.57  4994.7 2014.37  4995.2 2013.87  5002.4 2014.37  5009.7 2019.88
  5019.7 2020.84  5080.1 2019.97  5110.3 2022.02  5189.7 2031.01  5230.9 2033.77
  5284.6 2034.97  5381.8 2041.11  5422.0 2041.96  5452.2 2044.96  5522.6 2042.49
  5542.7 2048.41  5565.6 2050.18  5713.7 2053.90  5749.6 2056.33  5870.5 2056.56
#Mann=8,-1,0
  4251.8   0.035       0  4295.7    0.07       0  4392.7   0.035       0
  4469.9    0.07       0  4955.4    0.16       0  4994.7    0.07       0
  5002.4    0.16       0  5189.7    0.07       0
Bank Sta=4994.7,5002.4
Exp/Cntr=0.3,0.1

Type RM Length L Ch R = 1,1936,441,441,441
BEGIN DESCRIPTION:
Mapping XS bee6e237
END DESCRIPTION:
XS GIS Cut Line= 3
      1471851.46      6819796.63      1472111.89      6819054.41
      1472090.19      6818168.96
#Sta/Elev= 30
  4196.9 2042.98  4279.0 2041.84  4434.0 2035.75  4633.2 2031.88  4780.5 2025.15
  4888.4 2021.34  4937.3 2017.90  4983.5 2018.80  4989.9 2018.42  4996.0 2013.72
  4996.5 2013.22  5003.8 2013.72  5009.9 2013.89  5019.9 2017.68  5069.9 2018.31
  5084.0 2020.35  5109.9 2024.63  5160.0 2029.88  5216.3 2032.63  5310.0 2037.39
  5340.0 2037.07  5380.0 2040.17  5404.9 2039.92  5466.9 2042.20  5490.0 2044.24
  5500.1 2043.50  5610.1 2046.80  5640.1 2049.10  5660.1 2048.13  5869.2 2050.26
#Mann=8,-1,0
  4196.9   0.035       0  4633.2    0.07       0  4780.5   0.035       0
  4996.0   0.035       0  5003.8   0.035       0  5084.0    0.16       0
  5216.3    0.07       0  5404.9   0.035       0
Bank Sta=4996,5003.8
Exp/Cntr=0.3,0.1