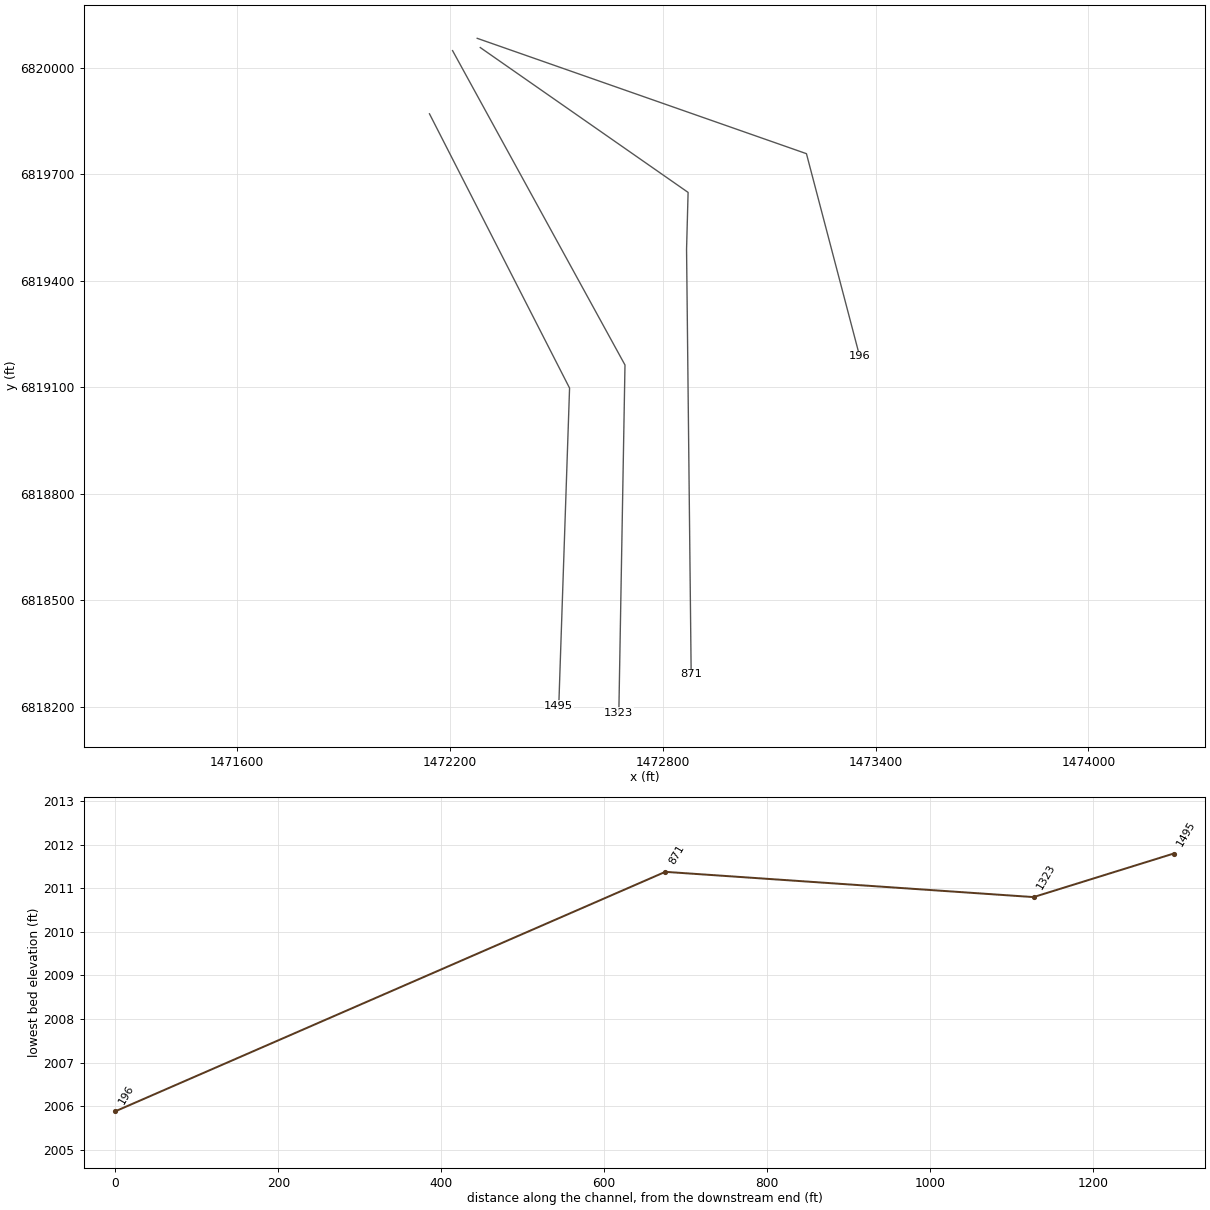
HEC-RAS study MULBERRY CREEK TRIBUTARY 21A_1.prj: MULBERRY CREEK TRIBUTARY 21A_1 Base Level Engineering

--- MULBERRY CREEK TRIBUTARY 21A_1.g01 (geometry) --- (continued)

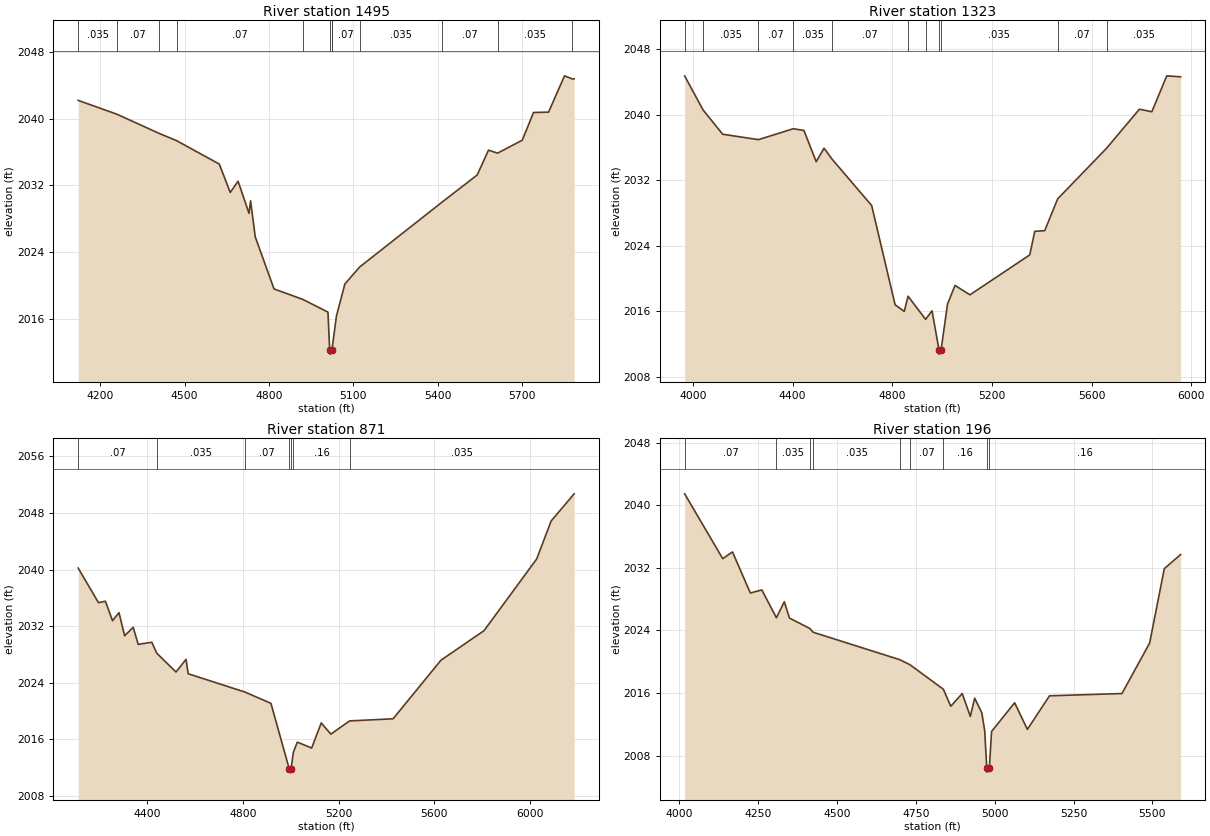
Type RM Length L Ch R = 1,1495,172,172,172
BEGIN DESCRIPTION:
Mapping XS b9b4fbbc
END DESCRIPTION:
XS GIS Cut Line= 3
      1472142.25      6819870.42      1472537.24      6819097.81
      1472506.86      6818203.75
#Sta/Elev= 30
  4122.2 2042.19  4259.1 2040.54  4410.8 2038.22  4471.6 2037.37  4623.6 2034.56
  4662.4 2031.16  4690.3 2032.51  4729.1 2028.66  4734.7 2030.16  4751.3 2025.85
  4817.9 2019.61  4919.3 2018.37  5009.7 2016.83  5015.8 2012.30  5016.3 2011.80
  5023.6 2012.30  5024.1 2012.39  5039.8 2016.36  5069.8 2020.20  5122.2 2022.23
  5416.5 2030.04  5540.1 2033.26  5580.1 2036.23  5612.6 2035.87  5700.1 2037.42
  5740.2 2040.74  5793.6 2040.78  5850.2 2045.13  5878.1 2044.76  5884.5 2044.77
#Mann=12,-1,0
  4122.2   0.035       0  4259.1    0.07       0  4410.8   0.035       0
  4471.6    0.07       0  4919.3    0.16       0  5015.8    0.07       0
  5023.6    0.16       0  5024.1    0.07       0  5122.2   0.035       0
  5416.5    0.07       0  5612.6   0.035       0  5878.1    0.07       0
Bank Sta=5015.8,5023.6
Exp/Cntr=0.3,0.1

Type RM Length L Ch R = 1,1323,452,452,452
BEGIN DESCRIPTION:
Mapping XS b97dcb85
END DESCRIPTION:
XS GIS Cut Line= 3
      1472207.38      6820048.33      1472693.49      6819162.91
      1472676.14      6818182.55
#Sta/Elev= 30
  3967.1 2044.71  4041.2 2040.56  4119.7 2037.61  4263.2 2036.95  4402.9 2038.28
  4445.7 2038.07  4495.0 2034.26  4526.5 2035.91  4558.7 2034.57  4717.6 2028.92
  4811.7 2016.82  4848.4 2016.01  4863.8 2017.86  4934.1 2015.04  4960.0 2016.08
  4988.1 2011.30  4988.6 2010.80  4996.1 2011.30  5022.1 2016.90  5052.1 2019.18
  5112.1 2018.03  5352.2 2022.90  5372.2 2025.77  5412.2 2025.85  5464.2 2029.73
  5660.2 2035.89  5792.2 2040.66  5842.2 2040.35  5902.2 2044.73  5957.7 2044.61
#Mann=11,-1,0
  3967.1    0.07       0  4041.2   0.035       0  4263.2    0.07       0
  4402.9   0.035       0  4558.7    0.07       0  4863.8    0.16       0
  4934.1   0.035       0  4988.1   0.035       0  4996.1   0.035       0
  5464.2    0.07       0  5660.2   0.035       0
Bank Sta=4988.1,4996.1
Exp/Cntr=0.3,0.1

Type RM Length L Ch R = 1,871,675,675,675
BEGIN DESCRIPTION:
Mapping XS 7e6792ec
END DESCRIPTION:
XS GIS Cut Line= 4
      1472285.51      6820057.00      1472871.44      6819649.02
      1472867.10      6819488.43      1472880.11      6818291.73
#Sta/Elev= 30
  4112.6 2040.22  4197.3 2035.33  4226.2 2035.54  4255.9 2032.78  4282.9 2033.92
  4306.5 2030.66  4342.3 2031.85  4363.2 2029.44  4419.9 2029.74  4440.7 2028.19
  4521.1 2025.53  4563.0 2027.33  4571.8 2025.29  4809.9 2022.69  4917.6 2021.10
  4993.7 2011.88  4994.2 2011.38  5001.7 2011.88  5011.2 2014.19  5027.7 2015.62
  5087.7 2014.79  5127.7 2018.33  5167.7 2016.75  5246.1 2018.62  5427.7 2018.92
  5627.7 2027.20  5807.7 2031.38  6027.7 2041.52  6087.7 2046.87  6184.0 2050.72
#Mann=7,-1,0
  4112.6    0.07       0  4440.7   0.035       0  4809.9    0.07       0
  4993.7    0.07       0  5001.7    0.07       0  5011.2    0.16       0
  5246.1   0.035       0
Bank Sta=4993.7,5001.7
Exp/Cntr=0.3,0.1

Type RM Length L Ch R = 1,196,0,0,0
BEGIN DESCRIPTION:
MULBERRY CREEK TRIBUTARY 21A_1 1.0
END DESCRIPTION:
XS GIS Cut Line= 3
      1472276.83      6820083.05      1473205.10      6819758.10
      1473355.01      6819187.98
#Sta/Elev= 30
  4016.5 2041.47  4137.1 2033.18  4168.1 2034.04  4224.8 2028.79  4261.2 2029.18
  4307.5 2025.62  4332.4 2027.67  4348.9 2025.58  4413.4 2024.25  4423.9 2023.77
  4698.7 2020.26  4731.2 2019.61  4837.0 2016.48  4860.5 2014.30  4896.8 2015.93
  4922.5 2013.01  4936.3 2015.34  4958.9 2013.48  4968.1 2011.17  4974.7 2006.38
  4975.2 2005.88  4982.8 2006.38  4989.9 2011.08  5063.0 2014.75  5103.5 2011.35
  5173.6 2015.64  5403.4 2015.93  5491.2 2022.38  5537.8 2031.90  5589.5 2033.71
#Mann=9,-1,0
  4016.5    0.07       0  4307.5   0.035       0  4413.4    0.07       0
  4423.9   0.035       0  4698.7    0.16       0  4731.2    0.07       0
  4837.0    0.16       0  4974.7    0.07       0  4982.8    0.16       0
Bank Sta=4974.7,4982.8
Exp/Cntr=0.3,0.1

Chan Stop Cuts=-1