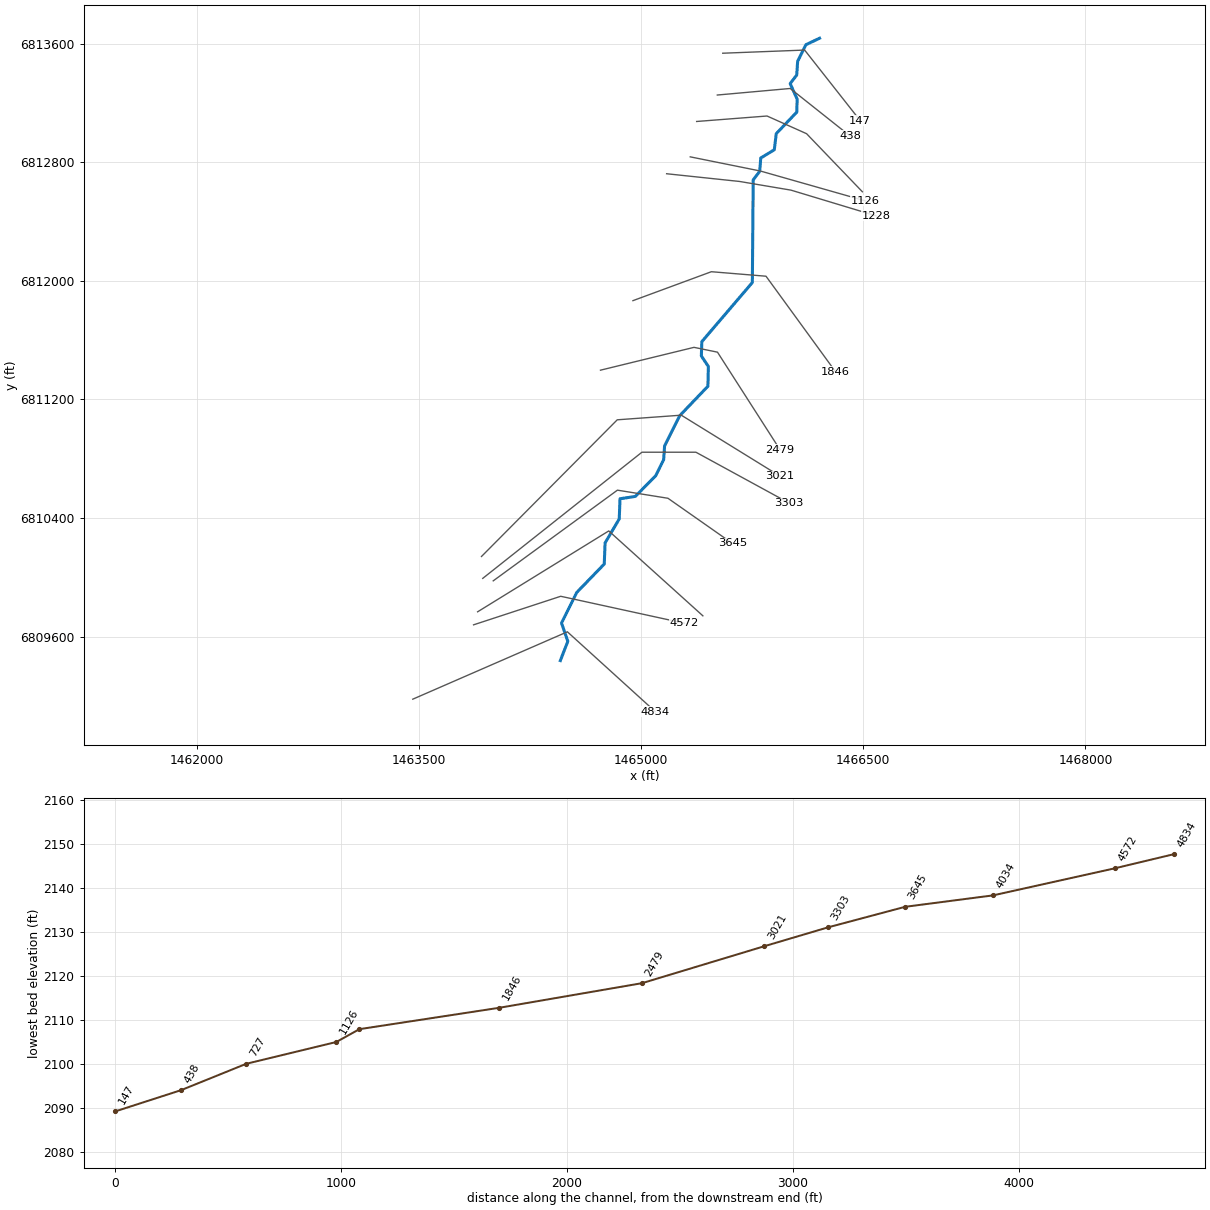
--- MULBERRY CREEK TRIBUTARY 21A_1_1.prj (project) ---

Proj Title=MULBERRY CREEK TRIBUTARY 21A_1_1 Base Level Engineering
Current Plan=p01
Default Exp/Contr=0.3,0.1
English Units
Geom File=g01
Flow File=f01
Plan File=p01
Y Axis Title=Elevation
X Axis Title(PF)=Main Channel Distance
X Axis Title(XS)=Station
BEGIN DESCRIPTION:
MULBERRY CREEK TRIBUTARY 21A_1_1
END DESCRIPTION:
DSS Export Rating Curves= 0
DSS Export Rating Curve Sorted= 0
DSS Export Volume Flow Curves= 0
DXF OffsetX= 0
DXF OffsetY= 0
DXF ScaleX= 1
DXF ScaleY= 10

--- MULBERRY CREEK TRIBUTARY 21A_1_1.p01 (plan) ---

Plan Title=Multiple Run
Short Identifier=Multiple
Geom File=g01
Flow File=f01
Subcritical Flow
K Sum by GR= 0
Std Step Tol= 0.01
Critical Tol= 0.01
Num of Std Step Trials= 20
Max Error Tol= 0.3
Flow Tol Ratio= 0.001
Split Flow NTrial= 30
Split Flow Tol= 0.02
Split Flow Ratio= 0.02
Log Output Level= 0
Friction Slope Method= 1
Unsteady Friction Slope Method= 2
Unsteady Bridges Friction Slope Method= 1
Parabolic Critical Depth
Global Vel Dist=  1 , 1 , 1
Global Log Level= 0
CheckData=True
Encroach Param= -1, 0, 0, 0
BEGIN DESCRIPTION:
Multiple Run
END DESCRIPTION:

--- MULBERRY CREEK TRIBUTARY 21A_1_1.f01 (steady flow) ---

Flow Title=Multiple
Number of Profiles=7
Profile Names=10-year,25-year,50-year,1pct_min,100-year,1pct_plu,500-year
River Rch & RM= MULBERRY CREEK T,Reach-1,4834
     180     250     308     190     379     755     578
Boundary for River Rch & Prof#=MULBERRY CREEK T,Reach-1,1
Up Type=0
Dn Type=3
Dn Slope=0.005
Boundary for River Rch & Prof#=MULBERRY CREEK T,Reach-1,2
Up Type=0
Dn Type=3
Dn Slope=0.005
Boundary for River Rch & Prof#=MULBERRY CREEK T,Reach-1,3
Up Type=0
Dn Type=3
Dn Slope=0.005
Boundary for River Rch & Prof#=MULBERRY CREEK T,Reach-1,4
Up Type=0
Dn Type=3
Dn Slope=0.005
Boundary for River Rch & Prof#=MULBERRY CREEK T,Reach-1,5
Up Type=0
Dn Type=3
Dn Slope=0.005
Boundary for River Rch & Prof#=MULBERRY CREEK T,Reach-1,6
Up Type=0
Dn Type=3
Dn Slope=0.005
Boundary for River Rch & Prof#=MULBERRY CREEK T,Reach-1,7
Up Type=0
Dn Type=3
Dn Slope=0.005

--- MULBERRY CREEK TRIBUTARY 21A_1_1.g01 (geometry) ---

Geom Title=Existing Conditions
Program Version=4.10

River Reach=MULBERRY CREEK T,Reach-1
Reach XY= 30
        1464455.        6809438.      1464505.61      6809567.95
      1464463.05      6809691.32      1464565.76      6809897.68
      1464751.46      6810089.47      1464757.25      6810232.07
      1464852.75      6810393.94      1464857.94      6810530.02
      1464961.12      6810545.88      1465099.17       6810685.7
      1465152.67      6810793.97      1465158.83      6810886.42
      1465260.83       6811090.3      1465451.47      6811289.47
      1465454.49      6811422.78      1465407.16      6811493.98
       1465410.4      6811590.43      1465751.46      6811989.46
      1465757.26      6812682.07      1465801.11      6812739.67
      1465808.19      6812829.65      1465899.54      6812885.34
      1465912.86      6812994.17      1466051.54       6813139.5
      1466053.88      6813227.45      1466006.82      6813331.88
      1466051.11      6813389.58      1466057.33      6813482.04
      1466112.95      6813594.31        1466205.        6813638.

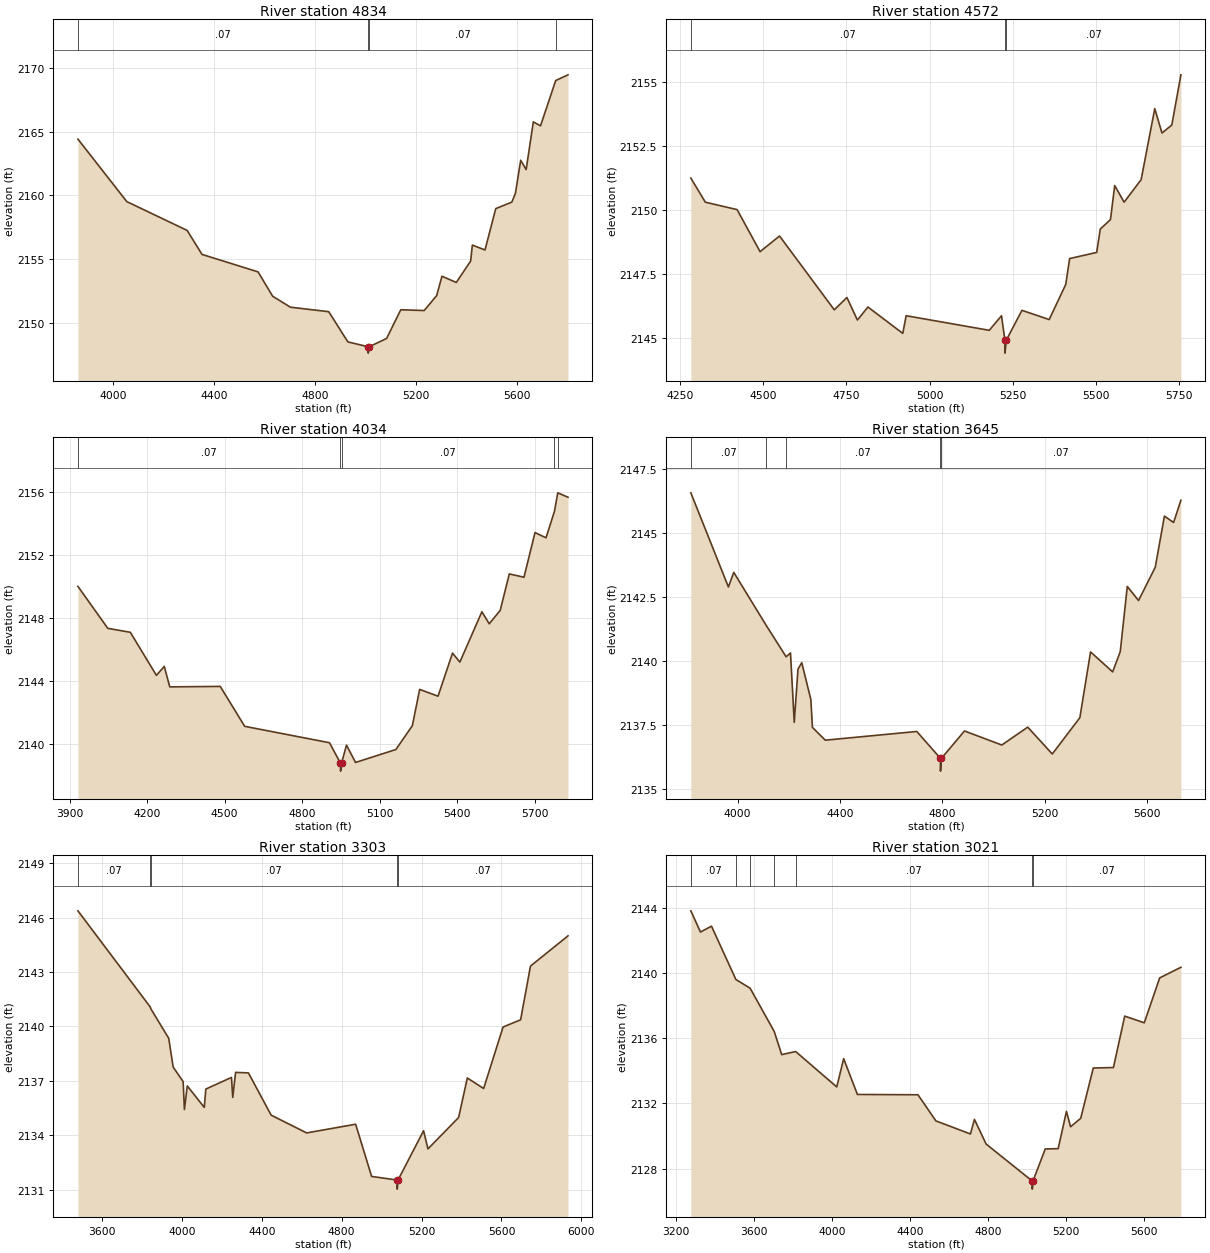
Type RM Length L Ch R = 1 ,4834    ,262,262,262
BEGIN DESCRIPTION:
MULBERRY CREEK TRIBUTARY 21A_1_1 9.0
END DESCRIPTION:
XS GIS Cut Line= 3
      1463458.74      6809177.47      1464502.64      6809632.11
      1465095.26      6809094.26
#Sta/Elev= 30
  3861.4 2164.41  4054.8 2159.51  4293.6 2157.25  4352.3 2155.37  4574.1    2154
  4631.9 2152.09  4702.2 2151.23  4853.7 2150.88  4929.4 2148.51  5009.7 2148.13
    5010 2147.63  5013.7 2148.13  5082.7 2148.78  5138.8 2151.03  5231.4 2150.97
  5280.7 2152.14  5301.7 2153.66  5358.4 2153.17  5415.2 2154.85  5421.9  2156.1
    5472 2155.72  5514.5 2158.96  5578.1 2159.47  5592.2 2160.15  5613.2 2162.75
  5634.8 2162.02  5663.2 2165.76  5691.6 2165.45  5751.6    2169  5800.3 2169.45
#Mann= 4 ,-1 , 0
  3861.4     .07       0  5009.7     .07       0  5013.7     .07       0
  5751.6    .035       0
Bank Sta=5009.7,5013.7
XS Rating Curve= 0 ,0
Exp/Cntr=0.3,0.1

Type RM Length L Ch R = 1 ,4572    ,538,538,538
BEGIN DESCRIPTION:
Mapping XS 06029bd6
END DESCRIPTION:
XS GIS Cut Line= 3
      1463869.14      6809679.25      1464457.66      6809871.95
       1465291.8      6809690.05
#Sta/Elev= 30
  4282.5 2151.25  4326.1 2150.31  4421.6 2150.02  4490.6 2148.38  4549.1 2148.99
  4713.6 2146.11  4751.6 2146.59  4783.2 2145.71  4814.8 2146.22  4919.5 2145.19
  4929.7 2145.88  5179.5 2145.31  5216.3 2145.88  5226.5 2144.92  5226.8 2144.42
  5230.5 2144.92  5277.7 2146.09  5359.6 2145.73  5409.4  2147.1    5421 2148.11
  5502.4 2148.35  5513.1 2149.26  5543.8 2149.63  5556.5 2150.96  5584.8 2150.31
    5636 2151.19  5676.9 2153.96  5698.6 2153.01  5728.1 2153.32  5755.5 2155.28
#Mann= 3 ,-1 , 0
  4282.5     .07       0  5226.5     .07       0  5230.5     .07       0
Bank Sta=5226.5,5230.5
XS Rating Curve= 0 ,0
Exp/Cntr=0.3,0.1

Type RM Length L Ch R = 1 ,4034    ,389,389,389
BEGIN DESCRIPTION:
Mapping XS 7578ddc1
END DESCRIPTION:
XS GIS Cut Line= 3
      1463896.58      6809767.12      1464781.96      6810312.93
      1465417.41      6809739.99
#Sta/Elev= 30
  3932.4    2150    4048 2147.34  4135.1 2147.09    4236 2144.36  4266.4 2144.93
  4287.7 2143.63  4482.9 2143.66  4577.5 2141.13  4905.6 2140.09  4948.1 2138.79
  4948.4 2138.29  4952.1 2138.79  4971.3 2139.94  5006.3 2138.84  5162.4 2139.66
    5226 2141.17  5254.4 2143.47  5325.4 2143.04  5381.4 2145.77  5409.8  2145.2
    5495 2148.39  5523.4 2147.63    5566 2148.48  5601.1 2150.79  5657.9 2150.58
  5700.5 2153.41  5743.1 2153.08  5775.6 2154.75  5788.6 2155.93  5828.1 2155.65
#Mann= 5 ,-1 , 0
  3932.4     .07       0  4948.1     .07       0  4952.1     .07       0
  5775.6    .035       0  5788.6     .07       0
Bank Sta=4948.1,4952.1
XS Rating Curve= 0 ,0
Exp/Cntr=0.3,0.1

Type RM Length L Ch R = 1 ,3645    ,342,342,342
BEGIN DESCRIPTION:
Mapping XS c7d27871
END DESCRIPTION:
XS GIS Cut Line= 4
       1464001.9      6809976.09      1464840.47      6810588.09
      1465181.62       6810533.4      1465616.55      6810228.69
#Sta/Elev= 30
  3817.6 2146.58  3964.4  2142.9  3985.3 2143.47  4110.7 2141.42  4189.9 2140.17
    4207 2140.32  4221.6 2137.61  4236.3 2139.69    4251 2139.94  4286.5  2138.5
  4292.7 2137.41  4342.9 2136.91  4700.5 2137.25  4792.7  2136.2    4793  2135.7
  4796.7  2136.2  4886.8 2137.27  5032.5 2136.72  5133.8 2137.42  5229.8 2136.37
  5337.5 2137.79  5379.3 2140.36  5465.6 2139.58  5495.3 2140.37  5522.8 2142.92
  5566.8 2142.37  5632.1 2143.67  5667.9 2145.67  5703.6 2145.42  5732.3 2146.29
#Mann= 5 ,-1 , 0
  3817.6     .07       0  4110.7    .035       0  4189.9     .07       0
  4792.7     .07       0  4796.7     .07       0
Bank Sta=4792.7,4796.7
XS Rating Curve= 0 ,0
Exp/Cntr=0.3,0.1

Type RM Length L Ch R = 1 ,3303    ,282,282,282
BEGIN DESCRIPTION:
Mapping XS 71941b10
END DESCRIPTION:
XS GIS Cut Line= 4
      1463931.23      6809992.76      1465005.92      6810844.18
      1465370.51      6810844.18      1466000.34      6810500.64
#Sta/Elev= 30
  3479.9 2146.38  3842.5 2141.07  3844.8 2140.98  3934.4 2139.35  3956.8 2137.76
  4006.6 2136.96  4012.9 2135.42  4027.4 2136.72  4112.3 2135.54  4120.3 2136.55
  4248.5 2137.19  4254.9 2136.09  4269.3 2137.47  4333.4 2137.44  4447.2 2135.11
  4625.1 2134.13  4870.1 2134.61  4950.1 2131.73  5078.1 2131.53  5078.3 2131.03
  5082.1 2131.53  5210.1 2134.25  5232.1 2133.25  5385.5 2134.98  5429.1 2137.16
  5510.8 2136.58    5608 2139.97  5695.9 2140.37  5745.2 2143.33    5933    2145
#Mann= 5 ,-1 , 0
  3479.9     .07       0  3842.5    .035       0  3844.8     .07       0
  5078.1     .07       0  5082.1     .07       0
Bank Sta=5078.1,5082.1
XS Rating Curve= 0 ,0
Exp/Cntr=0.3,0.1

Type RM Length L Ch R = 1 ,3021    ,542,542,542
BEGIN DESCRIPTION:
Mapping XS 7af46bc9
END DESCRIPTION:
XS GIS Cut Line= 4
      1463922.61      6810140.38      1464839.26      6811062.93
      1465271.55      6811094.18        1465938.      6810682.86
#Sta/Elev= 30
  3274.8  2143.8  3324.3  2142.5  3380.9 2142.86  3506.3 2139.59  3579.3 2139.06
  3703.1 2136.41  3741.5 2134.99  3813.2 2135.18  4024.3 2133.01  4059.7 2134.74
  4130.4 2132.55  4441.5 2132.53  4533.5 2130.93  4710.7 2130.13  4731.5 2131.02
  4791.6 2129.51  5028.2 2127.25  5028.5 2126.75  5032.2 2127.25  5095.1 2129.21
  5161.5 2129.23    5204 2131.51  5225.3 2130.57  5277.4 2131.09  5341.8 2134.17
  5445.3  2134.2  5503.3 2137.35  5603.7 2136.94  5682.9 2139.69  5791.9 2140.34
#Mann= 7 ,-1 , 0
  3274.8     .07       0  3506.3    .035       0  3579.3     .07       0
  3703.1    .035       0  3813.2     .07       0  5028.2     .07       0
  5032.2     .07       0
Bank Sta=5028.2,5032.2
XS Rating Curve= 0 ,0
Exp/Cntr=0.3,0.1

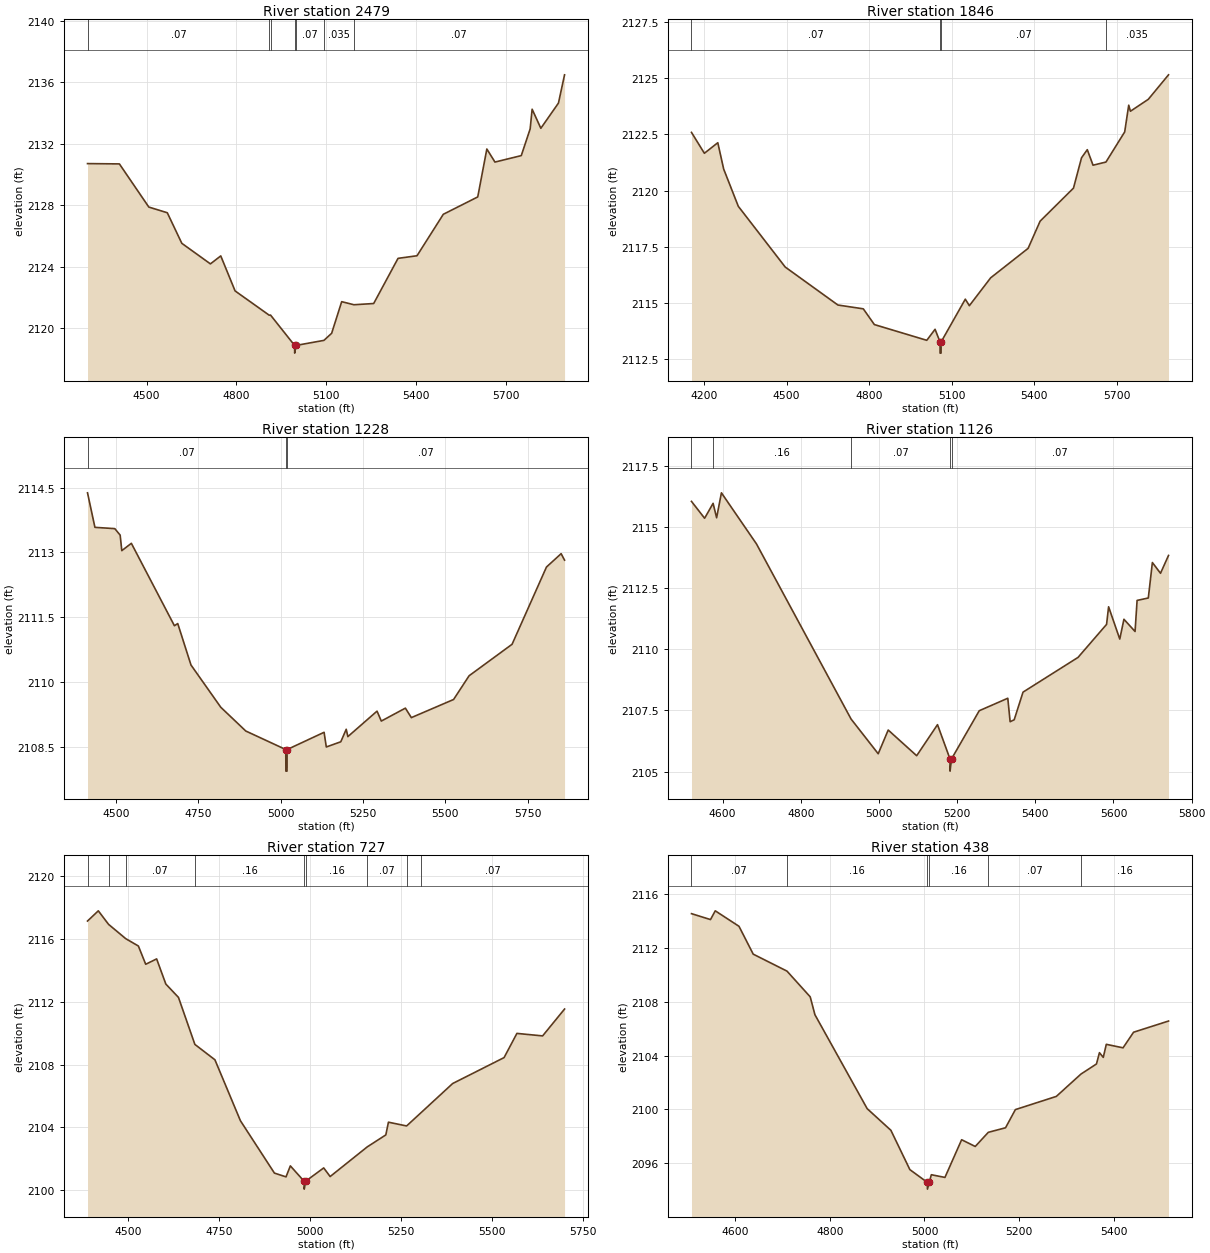
Type RM Length L Ch R = 1 ,2479    ,633,633,633
BEGIN DESCRIPTION:
Mapping XS 6ac5f90b
END DESCRIPTION:
XS GIS Cut Line= 4
      1464726.07      6811397.85       1465357.6      6811551.93
      1465516.02      6811519.38      1465938.14      6810861.31
#Sta/Elev= 30
  4302.4  2130.7  4408.9 2130.68  4507.2 2127.87  4568.9  2127.5  4617.4 2125.51
    4713 2124.17  4747.5 2124.69  4795.4 2122.41  4909.3 2120.83  4913.7 2120.84
  4994.3 2118.86  4994.5 2118.36  4998.3 2118.86  5092.2 2119.19  5117.9 2119.65
  5151.5 2121.71  5192.3 2121.51  5258.4 2121.59  5339.7 2124.53  5403.1  2124.7
    5491  2127.4    5606 2128.53  5636.4 2131.65  5663.5  2130.8  5751.4 2131.22
  5781.1 2132.96  5787.7 2134.24  5816.8    2133  5875.6 2134.64    5896 2136.48
#Mann= 7 ,-1 , 0
  4302.4     .07       0  4909.3    .035       0  4913.7     .07       0
  4994.3     .07       0  4998.3     .07       0  5092.2    .035       0
  5192.3     .07       0
Bank Sta=4994.3,4998.3
XS Rating Curve= 0 ,0
Exp/Cntr=0.3,0.1

Type RM Length L Ch R = 1 ,1846    ,618,618,618
BEGIN DESCRIPTION:
Mapping XS 9e9365b6
END DESCRIPTION:
XS GIS Cut Line= 4
      1464945.25      6811867.03      1465474.79      6812062.35
      1465843.71      6812031.97      1466314.64      6811385.25
#Sta/Elev= 30
    4154 2122.59  4200.9 2121.66  4249.7 2122.13    4271 2120.96  4324.3  2119.3
  4494.8  2116.6  4686.4 2114.91  4778.8 2114.74    4819 2114.04  5009.6 2113.34
  5039.7 2113.83  5057.8 2113.27    5058 2112.77  5061.5 2112.77  5061.8 2113.27
  5149.7 2115.17  5164.4 2114.88  5241.9 2116.12    5378 2117.43  5421.7 2118.64
    5543 2120.11  5572.3 2121.46  5593.2 2121.82  5614.1 2121.13  5661.1 2121.27
  5729.2 2122.61  5743.9  2123.8  5750.1 2123.53    5815 2124.06  5888.6 2125.15
#Mann= 4 ,-1 , 0
    4154     .07       0  5057.8     .07       0  5061.8     .07       0
  5661.1    .035       0
Bank Sta=5057.8,5061.8
XS Rating Curve= 0 ,0
Exp/Cntr=0.3,0.1

Type RM Length L Ch R = 1 ,1228    ,102,102,102
BEGIN DESCRIPTION:
Mapping XS 26eb5295
END DESCRIPTION:
XS GIS Cut Line= 4
      1465172.64      6812723.55      1465665.21      6812671.47
      1466012.43      6812612.87      1466587.55      6812439.26
#Sta/Elev= 30
    4414 2114.38  4436.5 2113.58  4496.8 2113.55  4513.1  2113.4  4518.1 2113.04
  4547.1 2113.21  4677.8  2111.3  4687.9 2111.35  4728.1 2110.39  4818.6 2109.41
  4894.4 2108.86  5015.9 2108.43  5016.2 2107.93  5019.7 2107.93  5019.9 2108.43
  5132.2 2108.83  5138.9 2108.49  5182.9 2108.61  5199.4  2108.9  5204.4 2108.73
  5292.9 2109.32  5305.9 2109.09    5379 2109.39  5397.1 2109.17  5525.3 2109.59
  5572.4 2110.14  5702.9 2110.87  5807.3 2112.66  5851.8 2112.97  5862.2 2112.82
#Mann= 3 ,-1 , 0
    4414     .07       0  5015.9     .07       0  5019.9     .07       0
Bank Sta=5015.9,5019.9
XS Rating Curve= 0 ,0
Exp/Cntr=0.3,0.1

Type RM Length L Ch R = 1 ,1126    ,399,399,399
BEGIN DESCRIPTION:
Mapping XS dad029bf
END DESCRIPTION:
XS GIS Cut Line= 3
      1465332.02      6812837.58      1465805.11      6812742.09
      1466514.74      6812540.27
#Sta/Elev= 30
  4520.4 2116.05    4554 2115.36  4575.7 2115.97  4584.7 2115.38    4597  2116.4
  4686.7 2114.31  4928.7 2107.15  4998.1 2105.73  5023.7  2106.7  5096.5 2105.65
  5149.8 2106.92  5181.7 2105.52  5181.9 2105.02  5185.7 2105.52  5256.6 2107.49
  5329.6    2108  5335.6 2107.04    5346 2107.12  5368.6 2108.25  5509.3 2109.67
  5582.3 2111.02  5587.5 2111.74  5616.1 2110.42  5626.7 2111.23  5655.2 2110.73
  5660.4    2112  5689.1  2112.1  5699.5 2113.55  5720.3 2113.11  5740.8 2113.84
#Mann= 5 ,-1 , 0
  4520.4     .07       0  4575.7     .16       0  4928.7     .07       0
  5181.7     .07       0  5185.7     .07       0
Bank Sta=5181.7,5185.7
XS Rating Curve= 0 ,0
Exp/Cntr=0.3,0.1

Type RM Length L Ch R = 1 ,727     ,289,289,289
BEGIN DESCRIPTION:
Mapping XS 65b0596a
END DESCRIPTION:
XS GIS Cut Line= 4
      1465375.41      6813076.29      1465850.68      6813113.19
      1466117.61      6812993.83      1466494.27      6812602.01
#Sta/Elev= 30
  4387.5 2117.13  4417.2 2117.78  4445.4 2116.92  4492.6 2116.01  4527.5 2115.54
  4547.6 2114.38  4577.7 2114.72    4603 2113.12  4637.8 2112.27  4682.9 2109.28
  4738.1  2108.3  4808.3 2104.42  4901.8 2101.09  4933.7 2100.85  4945.6 2101.55
  4983.5 2100.57  4983.8 2100.07  4987.5 2100.57  5037.4 2101.42  5055.1 2100.87
  5157.3 2102.76  5208.3 2103.52  5215.5 2104.33  5265.5 2104.09  5304.5 2104.92
  5392.2 2106.79  5533.7 2108.44    5569 2109.98  5639.7 2109.82  5700.1 2111.53
#Mann= 9 ,-1 , 0
  4387.5     .07       0  4445.4     .16       0  4492.6     .07       0
  4682.9     .16       0  4983.5     .07       0  4987.5     .16       0
  5157.3     .07       0  5265.5     .16       0  5304.5     .07       0
Bank Sta=4983.5,4987.5
XS Rating Curve= 0 ,0
Exp/Cntr=0.3,0.1

Type RM Length L Ch R = 1 ,438     ,291,291,291
BEGIN DESCRIPTION:
Mapping XS ae134c8d
END DESCRIPTION:
XS GIS Cut Line= 3
      1465514.92      6813254.76      1466007.14      6813299.03
      1466410.39      6812979.03
#Sta/Elev= 30
  4507.2 2114.55  4547.4 2114.11  4557.5 2114.76  4607.7 2113.61  4637.8 2111.54
  4709.2 2110.28  4758.3 2108.37  4768.3 2107.04  4878.8 2100.06    4929 2098.45
  4969.1 2095.53  5006.1 2094.58  5006.3 2094.08  5010.1 2094.58  5014.5 2095.15
  5043.3 2094.95  5078.6 2097.75  5107.4 2097.25    5135  2098.3  5171.5 2098.64
  5192.3 2099.99  5278.9 2100.97    5331 2102.63  5363.8 2103.38  5370.1 2104.22
  5378.2 2103.87  5384.6 2104.84    5420 2104.58  5442.3 2105.74  5516.2 2106.57
#Mann= 6 ,-1 , 0
  4507.2     .07       0  4709.2     .16       0  5006.1     .07       0
  5010.1     .16       0    5135     .07       0    5331     .16       0
Bank Sta=5006.1,5010.1
XS Rating Curve= 0 ,0
Exp/Cntr=0.3,0.1

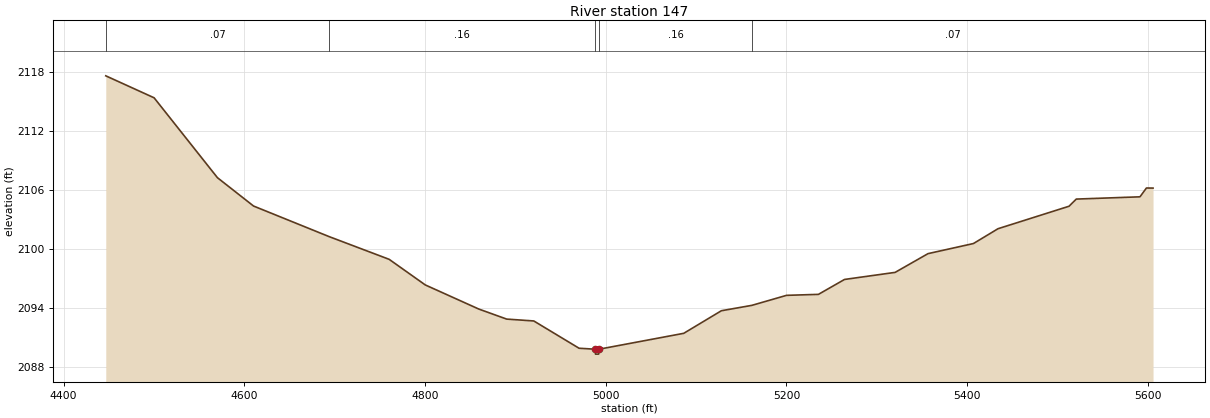
Type RM Length L Ch R = 1 ,147     ,0,0,0
BEGIN DESCRIPTION:
MULBERRY CREEK TRIBUTARY 21A_1_1 1.0
END DESCRIPTION:
XS GIS Cut Line= 3
      1465551.52      6813536.94      1466104.51      6813558.25
      1466479.46       6813082.3
#Sta/Elev= 30
  4446.6 2117.63  4500.1 2115.39  4570.2 2107.25  4610.2 2104.36  4693.7 2101.25
  4760.3 2098.93  4800.3 2096.32  4859.6 2093.86  4890.4 2092.84  4920.4 2092.65
  4970.5 2089.87  4988.5 2089.77  4988.7 2089.27  4992.2 2089.27  4992.5 2089.77
  5086.4 2091.39    5128 2093.69  5161.8 2094.24  5200.2 2095.26  5235.5 2095.36
  5264.4 2096.88  5320.4  2097.6  5356.8 2099.51  5407.1 2100.54  5434.3 2102.05
  5512.9 2104.34  5520.9 2105.07  5591.4  2105.3  5598.6  2106.2  5605.9 2106.19
#Mann= 5 ,-1 , 0
  4446.6     .07       0  4693.7     .16       0  4988.5     .07       0
  4992.5     .16       0  5161.8     .07       0
Bank Sta=4988.5,4992.5
XS Rating Curve= 0 ,0
Exp/Cntr=0.3,0.1

Chan Stop Cuts=-1
Use User Specified Reach Order=0
Composite Channel Slope=5