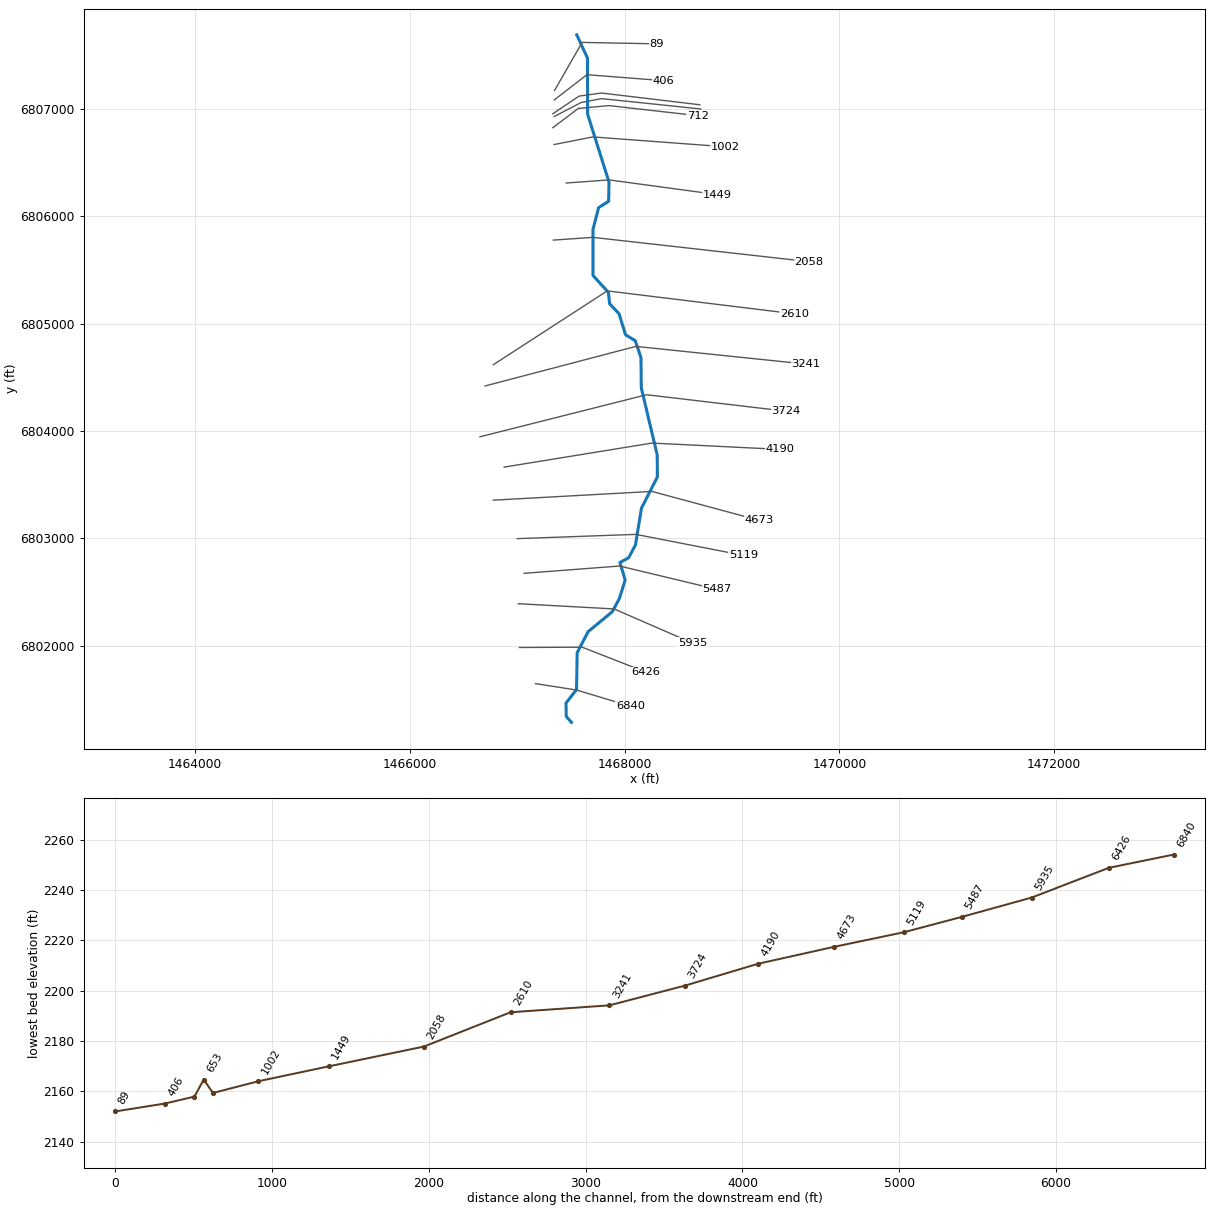
--- MULBERRY CREEK TRIBUTARY 21A_2.prj (project) ---

Proj Title=MULBERRY CREEK TRIBUTARY 21A_2 Base Level Engineering
Current Plan=p01
Default Exp/Contr=0.3,0.1
English Units
Geom File=g01
Flow File=f01
Plan File=p01
Y Axis Title=Elevation
X Axis Title(PF)=Main Channel Distance
X Axis Title(XS)=Station
BEGIN DESCRIPTION:
MULBERRY CREEK TRIBUTARY 21A_2
END DESCRIPTION:
DSS Export Rating Curves= 0
DSS Export Rating Curve Sorted= 0
DSS Export Volume Flow Curves= 0
DXF OffsetX= 0
DXF OffsetY= 0
DXF ScaleX= 1
DXF ScaleY= 10

--- MULBERRY CREEK TRIBUTARY 21A_2.p01 (plan) ---

Plan Title=Multiple Run
Short Identifier=Multiple
Geom File=g01
Flow File=f01
Subcritical Flow
K Sum by GR= 0
Std Step Tol= 0.01
Critical Tol= 0.01
Num of Std Step Trials= 20
Max Error Tol= 0.3
Flow Tol Ratio= 0.001
Split Flow NTrial= 30
Split Flow Tol= 0.02
Split Flow Ratio= 0.02
Log Output Level= 0
Friction Slope Method= 1
Unsteady Friction Slope Method= 2
Unsteady Bridges Friction Slope Method= 1
Parabolic Critical Depth
Global Vel Dist=  1 , 1 , 1
Global Log Level= 0
CheckData=True
Encroach Param= -1, 0, 0, 0
BEGIN DESCRIPTION:
Multiple Run
END DESCRIPTION:

--- MULBERRY CREEK TRIBUTARY 21A_2.f01 (steady flow) ---

Flow Title=Multiple
Program Version=4.10
Number of Profiles= 7
Profile Names=10-year,25-year,50-year,1pct_min,100-year,1pct_plu,500-year
River Rch & RM=MULBERRY CREEK T,Reach-1         ,6840
     525     776     996     637    1270    2534    2090
Boundary for River Rch & Prof#=MULBERRY CREEK T,Reach-1         , 1
Up Type= 0
Dn Type= 3
Dn Slope=0.011
Boundary for River Rch & Prof#=MULBERRY CREEK T,Reach-1         , 2
Up Type= 0
Dn Type= 3
Dn Slope=0.011
Boundary for River Rch & Prof#=MULBERRY CREEK T,Reach-1         , 3
Up Type= 0
Dn Type= 3
Dn Slope=0.011
Boundary for River Rch & Prof#=MULBERRY CREEK T,Reach-1         , 4
Up Type= 0
Dn Type= 3
Dn Slope=0.011
Boundary for River Rch & Prof#=MULBERRY CREEK T,Reach-1         , 5
Up Type= 0
Dn Type= 3
Dn Slope=0.011
Boundary for River Rch & Prof#=MULBERRY CREEK T,Reach-1         , 6
Up Type= 0
Dn Type= 3
Dn Slope=0.011
Boundary for River Rch & Prof#=MULBERRY CREEK T,Reach-1         , 7
Up Type= 0
Dn Type= 3
Dn Slope=0.011
DSS Import GetInterval= 0
DSS Import GetPeak= 0
DSS Import FillOption= 0

--- MULBERRY CREEK TRIBUTARY 21A_2.g01 (geometry) ---

Geom Title=Existing Conditions
Program Version=4.10

River Reach=MULBERRY CREEK T,Reach-1
Reach XY= 30
        1467505.        6801288.      1467456.88      6801343.79
      1467454.94      6801468.01      1467552.93      6801593.86
      1467558.75      6801936.45      1467660.59      6802132.39
      1467885.22      6802317.91      1467951.18      6802439.58
       1468005.4        6802613.      1467956.53      6802776.12
      1468038.42      6802820.98      1468101.24      6802939.56
      1468157.25      6803282.07      1468305.44      6803572.82
      1468303.78       6803777.5      1468155.52      6804403.22
      1468152.74      6804682.06      1468099.54      6804840.66
      1468008.53      6804896.49      1467949.46      6805090.42
      1467860.54      6805185.58      1467849.48      6805290.43
      1467706.05      6805448.43      1467706.22       6805877.5
      1467758.11      6806079.68      1467851.52      6806139.26
      1467854.93      6806317.97      1467656.22       6806948.5
      1467654.48      6807472.78        1467555.        6807688.

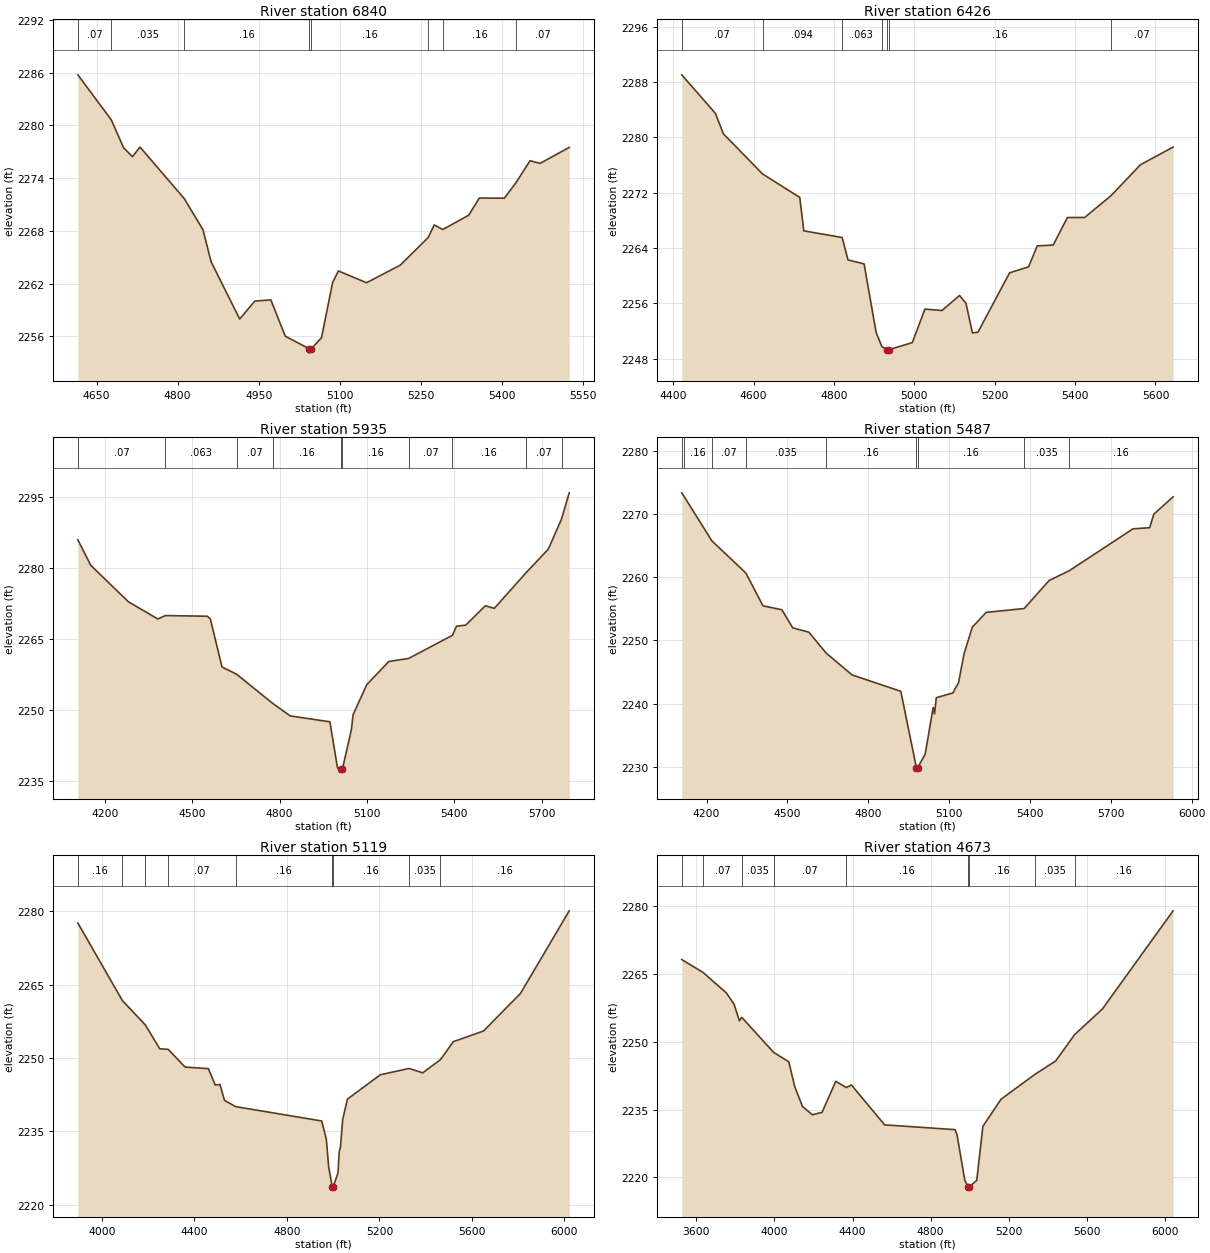
Type RM Length L Ch R = 1 ,6840    ,414,414,414
BEGIN DESCRIPTION:
MULBERRY CREEK TRIBUTARY 21A_2 14.0
END DESCRIPTION:
XS GIS Cut Line= 3
      1467171.24      6801648.74      1467551.45      6801589.47
      1468054.41      6801438.25
#Sta/Elev= 30
  4615.2 2285.75  4677.2 2280.62    4700 2277.44  4716.3 2276.44  4730.3 2277.53
  4812.3 2271.66    4847 2268.11  4861.9 2264.49  4914.9 2257.96  4942.9    2260
  4972.6 2260.14  4999.3 2256.01  5043.5 2254.58  5043.7 2254.08  5047.5 2254.58
  5066.4 2255.83    5087  2262.1  5097.7 2263.43  5149.9 2262.09  5212.5  2264.1
  5264.1 2267.24  5275.2 2268.67    5291 2268.15  5339.1 2269.77  5358.7 2271.73
  5405.1 2271.71  5426.8 2273.49  5452.7 2275.98  5471.2 2275.67  5525.2 2277.49
#Mann= 8 ,-1 , 0
  4615.2     .07       0  4677.2    .035       0  4812.3     .16       0
  5043.5     .07       0  5047.5     .16       0  5264.1     .07       0
    5291     .16       0  5426.8     .07       0
Bank Sta=5043.5,5047.5
XS Rating Curve= 0 ,0
Exp/Cntr=0.3,0.1

Type RM Length L Ch R = 1 ,6426    ,491,491,491
BEGIN DESCRIPTION:
MULBERRY CREEK TRIBUTARY 21A_2 13.0
END DESCRIPTION:
XS GIS Cut Line= 3
      1467021.45      6801985.12        1467605.        6801988.
      1468199.86      6801755.08
#Sta/Elev= 30
  4421.5 2289.02  4505.1 2283.46  4525.1  2280.5  4622.7 2274.69  4715.1 2271.31
  4725.1 2266.48  4820.6 2265.51  4835.1 2262.28  4875.1  2261.7  4905.1 2251.79
  4919.6 2249.72  4933.1 2249.31  4933.3 2248.81  4937.1 2249.31  4995.1 2250.33
  5026.5 2255.17  5068.9 2254.97  5112.5 2257.14  5128.5 2256.03  5144.7 2251.74
  5158.3 2251.82  5237.1 2260.41  5284.3 2261.28  5305.8  2264.3  5345.6 2264.43
  5380.9  2268.4  5423.9 2268.41  5489.8 2271.58  5562.7 2276.03  5643.9 2278.58
#Mann= 7 ,-1 , 0
  4421.5     .07       0  4622.7    .094       0  4820.6    .063       0
  4919.6     .16       0  4933.1     .07       0  4937.1     .16       0
  5489.8     .07       0
Bank Sta=4933.1,4937.1
XS Rating Curve= 0 ,0
Exp/Cntr=0.3,0.1

Type RM Length L Ch R = 1 ,5935    ,448,448,448
BEGIN DESCRIPTION:
MULBERRY CREEK TRIBUTARY 21A_2 12.0
END DESCRIPTION:
XS GIS Cut Line= 3
      1467010.63      6802392.67       1467902.5      6802344.03
      1468630.88      6802026.71
#Sta/Elev= 30
  4106.8 2285.93  4151.2 2280.53  4280.4 2272.83  4381.6 2269.19  4407.2 2269.91
  4551.8 2269.77  4561.8 2269.21  4601.9 2259.04  4652.6 2257.48  4776.3 2251.33
  4836.3 2248.69  4972.5 2247.44  4998.7 2237.68  5011.6 2237.51  5011.8 2237.01
  5015.7 2237.51  5046.4  2245.8  5052.2 2248.93  5099.1  2255.3  5174.8 2260.19
  5242.9 2260.84  5393.5 2265.74  5407.5 2267.67    5439 2267.88  5506.6 2271.99
  5537.2 2271.44  5646.9 2279.01  5722.6 2283.94  5768.4 2290.37  5794.5 2295.87
#Mann= 10 ,-1 , 0
  4106.8     .07       0  4407.2    .063       0  4652.6     .07       0
  4776.3     .16       0  5011.6     .07       0  5015.7     .16       0
  5242.9     .07       0  5393.5     .16       0  5646.9     .07       0
  5768.4     .16       0
Bank Sta=5011.6,5015.7
XS Rating Curve= 0 ,0
Exp/Cntr=0.3,0.1

Type RM Length L Ch R = 1 ,5487    ,368,368,368
BEGIN DESCRIPTION:
MULBERRY CREEK TRIBUTARY 21A_2 11.0
END DESCRIPTION:
XS GIS Cut Line= 3
      1467064.48      6802675.66        1467954.      6802743.43
      1468859.55      6802526.35
#Sta/Elev= 30
  4107.9  2273.4    4116 2272.87  4219.5 2265.79  4345.6  2260.7  4409.3 2255.49
  4479.5 2254.87  4519.6    2252  4579.8 2251.31  4642.8 2248.04  4740.2 2244.53
  4920.8 2241.94  4978.8 2229.79  4979.1 2229.29    4983 2229.79  5011.3 2231.99
  5040.9 2239.38    5046 2238.36  5052.4 2240.93  5114.1 2241.68  5135.2 2243.34
  5155.3 2247.87  5186.1 2252.11  5237.5 2254.45  5378.5 2255.06  5471.3 2259.51
  5546.1 2261.06  5782.6  2267.7  5844.3 2267.87  5859.7 2270.02  5931.2 2272.77
#Mann= 9 ,-1 , 0
  4107.9     .07       0    4116     .16       0  4219.5     .07       0
  4345.6    .035       0  4642.8     .16       0  4978.8     .07       0
    4983     .16       0  5378.5    .035       0  5546.1     .16       0
Bank Sta=4978.8,4983
XS Rating Curve= 0 ,0
Exp/Cntr=0.3,0.1

Type RM Length L Ch R = 1 ,5119    ,446,446,446
BEGIN DESCRIPTION:
MULBERRY CREEK TRIBUTARY 21A_2 10.0
END DESCRIPTION:
XS GIS Cut Line= 3
      1467001.07      6802998.57        1468105.        6803038.
       1469106.5      6802842.67
#Sta/Elev= 30
  3895.7 2277.61  4088.4 2261.75  4187.4 2256.79  4249.9  2251.9  4286.3 2251.79
  4359.9 2248.16    4460 2247.85    4490 2244.49    4510 2244.62    4530 2241.35
  4578.5 2240.08  4950.3 2237.15  4970.3 2233.42  4980.3 2227.84  4995.7 2223.72
    4996 2223.22  4999.9 2223.72  5020.7 2226.51  5026.1 2230.91  5031.2  2231.7
  5041.1 2237.46  5061.5 2241.62  5204.1  2246.6  5328.2 2247.88  5387.3 2246.99
  5463.7 2249.68  5519.9 2253.37  5650.3 2255.54  5810.2 2263.23  6020.7  2280.1
#Mann= 9 ,-1 , 0
  3895.7     .16       0  4088.4     .07       0  4187.4    .063       0
  4286.3     .07       0  4578.5     .16       0  4995.7     .07       0
  4999.9     .16       0  5328.2    .035       0  5463.7     .16       0
Bank Sta=4995.7,4999.9
XS Rating Curve= 0 ,0
Exp/Cntr=0.3,0.1

Type RM Length L Ch R = 1 ,4673    ,483,483,483
BEGIN DESCRIPTION:
MULBERRY CREEK TRIBUTARY 21A_2 9.0
END DESCRIPTION:
XS GIS Cut Line= 3
      1466777.49      6803356.64        1468255.        6803438.
      1469255.83      6803167.84
#Sta/Elev= 30
  3525.4 2268.14  3634.7 2265.29  3753.3 2260.79  3793.3 2258.27  3820.6 2254.61
  3832.6 2255.38  3995.8 2247.64  4073.7 2245.54  4103.8 2240.09  4143.8 2235.67
  4193.9 2233.85    4244 2234.37  4314.1 2241.23    4368 2239.86  4394.2 2240.43
  4564.5 2231.61    4925 2230.56    4935 2229.46  4975.1 2219.33  4992.9 2217.91
  4993.2 2217.41  4997.3 2217.91  5036.2 2219.34  5067.6 2231.29  5160.5 2237.27
  5336.2 2242.84  5440.2 2245.72  5537.6 2251.56  5680.1 2257.24  6041.8 2278.91
#Mann= 9 ,-1 , 0
  3525.4     .16       0  3634.7     .07       0  3832.6    .035       0
  3995.8     .07       0    4368     .16       0  4992.9     .07       0
  4997.3     .16       0  5336.2    .035       0  5537.6     .16       0
Bank Sta=4992.9,4997.3
XS Rating Curve= 0 ,0
Exp/Cntr=0.3,0.1

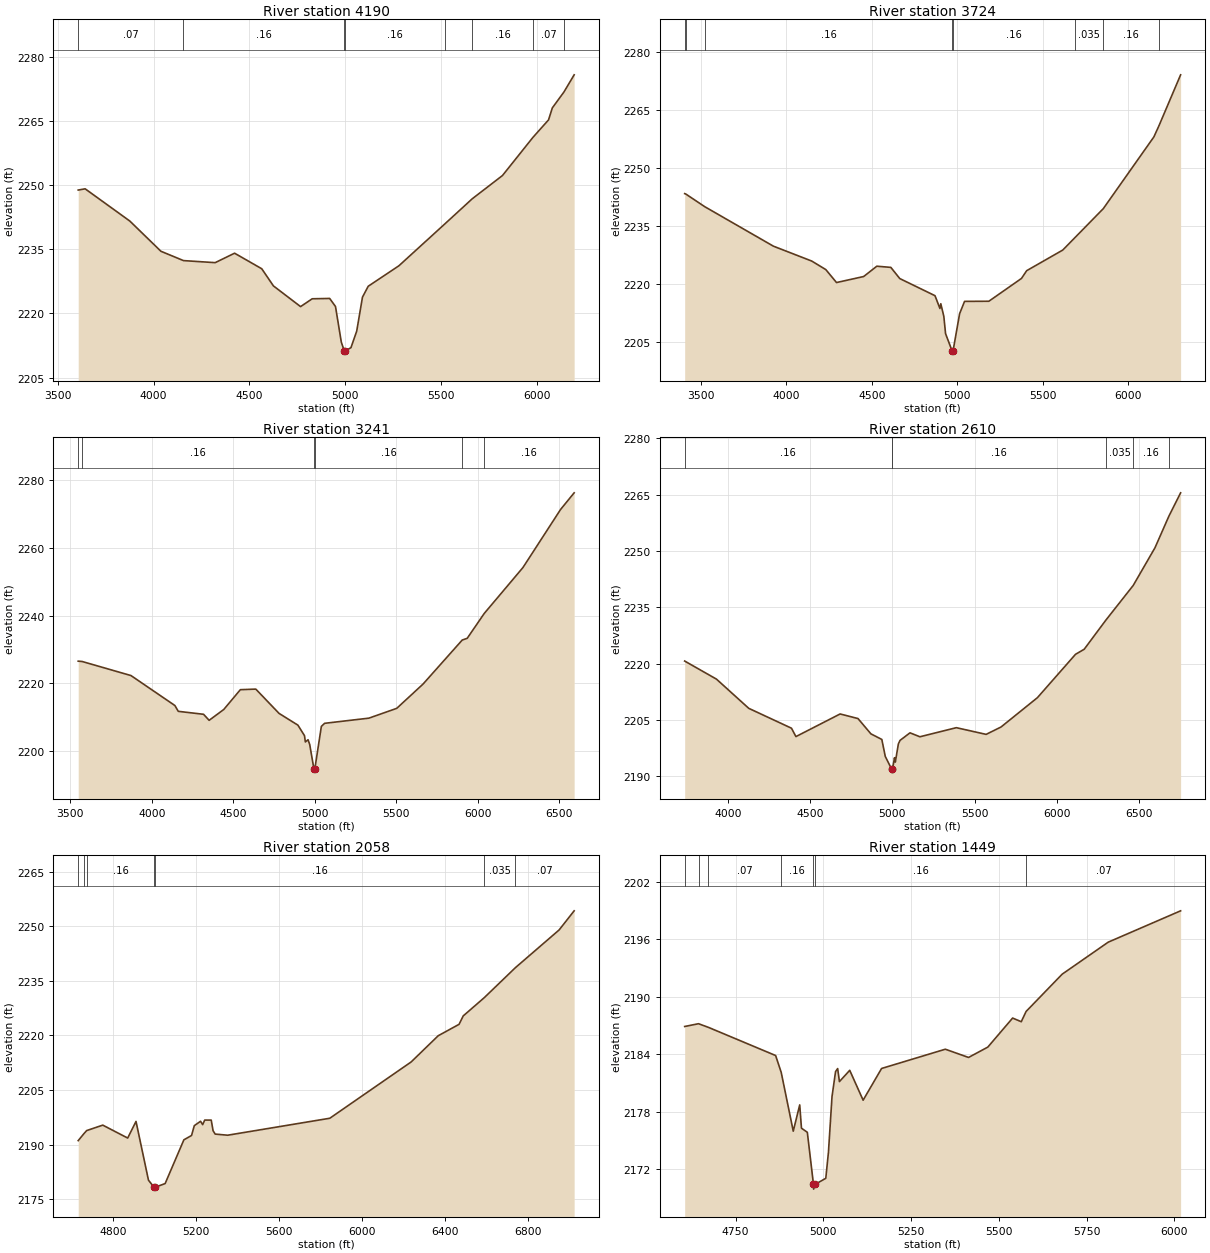
Type RM Length L Ch R = 1 ,4190    ,466,466,466
BEGIN DESCRIPTION:
MULBERRY CREEK TRIBUTARY 21A_2 8.0
END DESCRIPTION:
XS GIS Cut Line= 3
      1466879.25      6803664.44        1468255.        6803888.
      1469448.66      6803829.37
#Sta/Elev= 30
  3606.6 2248.85  3642.8 2249.14  3875.8 2241.61  4038.5 2234.53  4156.1 2232.35
  4321.6 2231.87  4422.9 2234.08  4564.8 2230.44  4625.5 2226.44  4767.4 2221.59
  4828.2 2223.42  4919.3  2223.5  4949.7 2221.61  4980.1 2213.27  4995.6 2211.21
  4995.9 2210.71  5000.1 2211.21  5030.4 2211.99  5060.5 2215.87  5090.5  2223.8
  5120.5 2226.35  5280.7 2231.14  5521.2 2240.96  5663.3  2246.8  5821.4 2252.25
  5981.1 2261.21  6061.7 2265.25  6081.7 2268.07  6142.6 2271.81  6195.5  2275.8
#Mann= 8 ,-1 , 0
  3606.6     .07       0  4156.1     .16       0  4995.6     .07       0
  5000.1     .16       0  5521.2    .035       0  5663.3     .16       0
  5981.1     .07       0  6142.6     .16       0
Bank Sta=4995.6,5000.1
XS Rating Curve= 0 ,0
Exp/Cntr=0.3,0.1

Type RM Length L Ch R = 1 ,3724    ,483,483,483
BEGIN DESCRIPTION:
MULBERRY CREEK TRIBUTARY 21A_2 7.0
END DESCRIPTION:
XS GIS Cut Line= 3
      1466653.54      6803946.56        1468205.        6804338.
      1469500.35      6804185.33
#Sta/Elev= 30
  3404.1  2243.3  3410.8 2243.19  3520.7 2239.94  3923.7  2229.7  4148.2 2225.85
  4230.7 2223.64  4293.3 2220.29  4452.4 2221.85  4529.4 2224.52  4611.5 2224.21
  4663.8 2221.32  4870.1 2216.89  4898.9 2213.58  4904.1 2214.81  4921.7 2211.57
    4932 2207.06  4970.9 2202.53  4971.3 2202.03  4975.5 2202.53  5014.3 2212.24
  5043.2 2215.42  5185.4 2215.45  5376.7 2221.36    5407 2223.36  5618.4  2228.7
  5689.1 2231.89  5855.7 2239.41  6152.1 2257.98  6182.3 2260.92  6308.5 2274.03
#Mann= 8 ,-1 , 0
  3404.1     .16       0  3410.8     .07       0  3520.7     .16       0
  4970.9     .07       0  4975.5     .16       0  5689.1    .035       0
  5855.7     .16       0  6182.3     .07       0
Bank Sta=4970.9,4975.5
XS Rating Curve= 0 ,0
Exp/Cntr=0.3,0.1

Type RM Length L Ch R = 1 ,3241    ,631,631,631
BEGIN DESCRIPTION:
MULBERRY CREEK TRIBUTARY 21A_2 6.0
END DESCRIPTION:
XS GIS Cut Line= 3
      1466701.29      6804419.65        1468105.        6804788.
      1469687.45      6804623.64
#Sta/Elev= 30
  3548.7 2226.57  3571.8 2226.49  3872.5 2222.33  4141.8  2213.5  4162.5 2211.79
  4317.6 2210.92  4351.8 2209.14  4441.7 2212.34  4543.4 2218.17  4638.1 2218.34
  4780.5 2211.19  4896.4 2207.72  4936.8 2204.62    4942 2202.77  4958.6 2203.42
  4968.9    2202  4995.1 2194.67  4995.4 2194.17  4999.7 2194.67  5040.2 2207.35
  5060.3 2208.26  5331.7 2209.78  5502.6 2212.67  5663.5  2219.8  5904.4  2232.8
  5934.9 2233.31  6039.5 2240.64  6276.8 2254.16    6508  2271.3  6590.9 2276.18
#Mann= 6 ,-1 , 0
  3548.7     .07       0  3571.8     .16       0  4995.1     .07       0
  4999.7     .16       0  5904.4    .035       0  6039.5     .16       0
Bank Sta=4995.1,4999.7
XS Rating Curve= 0 ,0
Exp/Cntr=0.3,0.1

Type RM Length L Ch R = 1 ,2610    ,552,552,552
BEGIN DESCRIPTION:
MULBERRY CREEK TRIBUTARY 21A_2 5.0
END DESCRIPTION:
XS GIS Cut Line= 3
      1466777.81      6804617.34      1467838.54      6805304.75
      1469579.91      6805091.29
#Sta/Elev= 30
    3736  2220.7  3929.8 2215.88  4125.9 2208.12    4386 2202.83  4413.1  2200.6
  4682.1 2206.62  4790.9  2205.4  4869.4 2201.33  4935.9 2199.84    4957 2195.31
    4996 2191.91  4996.3 2191.41  5000.8 2191.91    5013 2194.98    5018 2193.81
  5036.7 2198.67  5046.8 2199.59  5107.3  2201.6  5167.7 2200.55  5389.4 2202.97
  5570.7 2201.19  5661.4 2203.15    5883 2210.96  6114.7 2222.49  6167.6 2223.84
  6299.5 2231.59  6465.8 2240.81  6598.3 2250.84  6683.7 2259.31  6754.4 2265.46
#Mann= 6 ,-1 , 0
    3736     .16       0    4996     .07       0  5000.8     .16       0
  6299.5    .035       0  6465.8     .16       0  6683.7     .07       0
Bank Sta=4996,5000.8
XS Rating Curve= 0 ,0
Exp/Cntr=0.3,0.1

Type RM Length L Ch R = 1 ,2058    ,609,609,609
BEGIN DESCRIPTION:
MULBERRY CREEK TRIBUTARY 21A_2 4.0
END DESCRIPTION:
XS GIS Cut Line= 3
      1467336.64      6805777.56      1467704.86      6805803.06
        1469717.      6805576.98
#Sta/Elev= 30
  4630.9 2191.11  4658.2 2193.01    4672 2193.88  4749.5 2195.37  4869.8 2191.82
  4909.9 2196.39  4970.1 2180.24  4997.2 2178.29  4997.5 2177.79    5002 2178.29
  5050.5 2179.32    5141 2191.34  5177.9 2192.52  5191.3 2195.23  5221.5 2196.43
  5231.6  2195.5  5241.7 2196.76    5273 2196.75  5281.9 2193.84    5292 2192.91
  5352.3  2192.6  5845.4 2197.26  6237.9 2212.72  6368.7 2219.93  6469.3 2223.06
  6489.5 2225.38    6591 2230.39  6741.3 2238.63  6952.3 2248.99  7024.8 2254.24
#Mann= 7 ,-1 , 0
  4630.9     .16       0  4658.2     .07       0    4672     .16       0
  4997.2     .07       0    5002     .16       0    6591    .035       0
  6741.3     .07       0
Bank Sta=4997.2,5002
XS Rating Curve= 0 ,0
Exp/Cntr=0.3,0.1

Type RM Length L Ch R = 1 ,1449    ,447,447,447
BEGIN DESCRIPTION:
MULBERRY CREEK TRIBUTARY 21A_2 3.0
END DESCRIPTION:
XS GIS Cut Line= 3
      1467456.45      6806308.82        1467855.        6806338.
      1468859.41      6806201.97
#Sta/Elev= 30
  4604.8 2186.87  4644.2 2187.16  4672.5 2186.78    4864 2183.84  4879.9 2182.08
  4914.2 2175.95  4932.6 2178.69  4937.6 2176.26  4954.3 2175.83  4971.8  2170.4
  4972.2  2169.9  4976.8  2170.4  5006.9 2171.03  5014.5 2173.76  5024.6 2179.54
  5034.7 2182.16  5040.7 2182.48  5045.8 2181.12  5075.1  2182.3  5113.3 2179.18
  5165.9 2182.49  5347.5  2184.5  5413.7 2183.64  5468.6 2184.72  5539.3 2187.75
  5563.9 2187.37  5577.7 2188.44  5680.5 2192.33  5811.7 2195.67    6018 2198.94
#Mann= 7 ,-1 , 0
  4604.8    .035       0  4644.2     .16       0  4672.5     .07       0
  4879.9     .16       0  4971.8     .07       0  4976.8     .16       0
  5577.7     .07       0
Bank Sta=4971.8,4976.8
XS Rating Curve= 0 ,0
Exp/Cntr=0.3,0.1

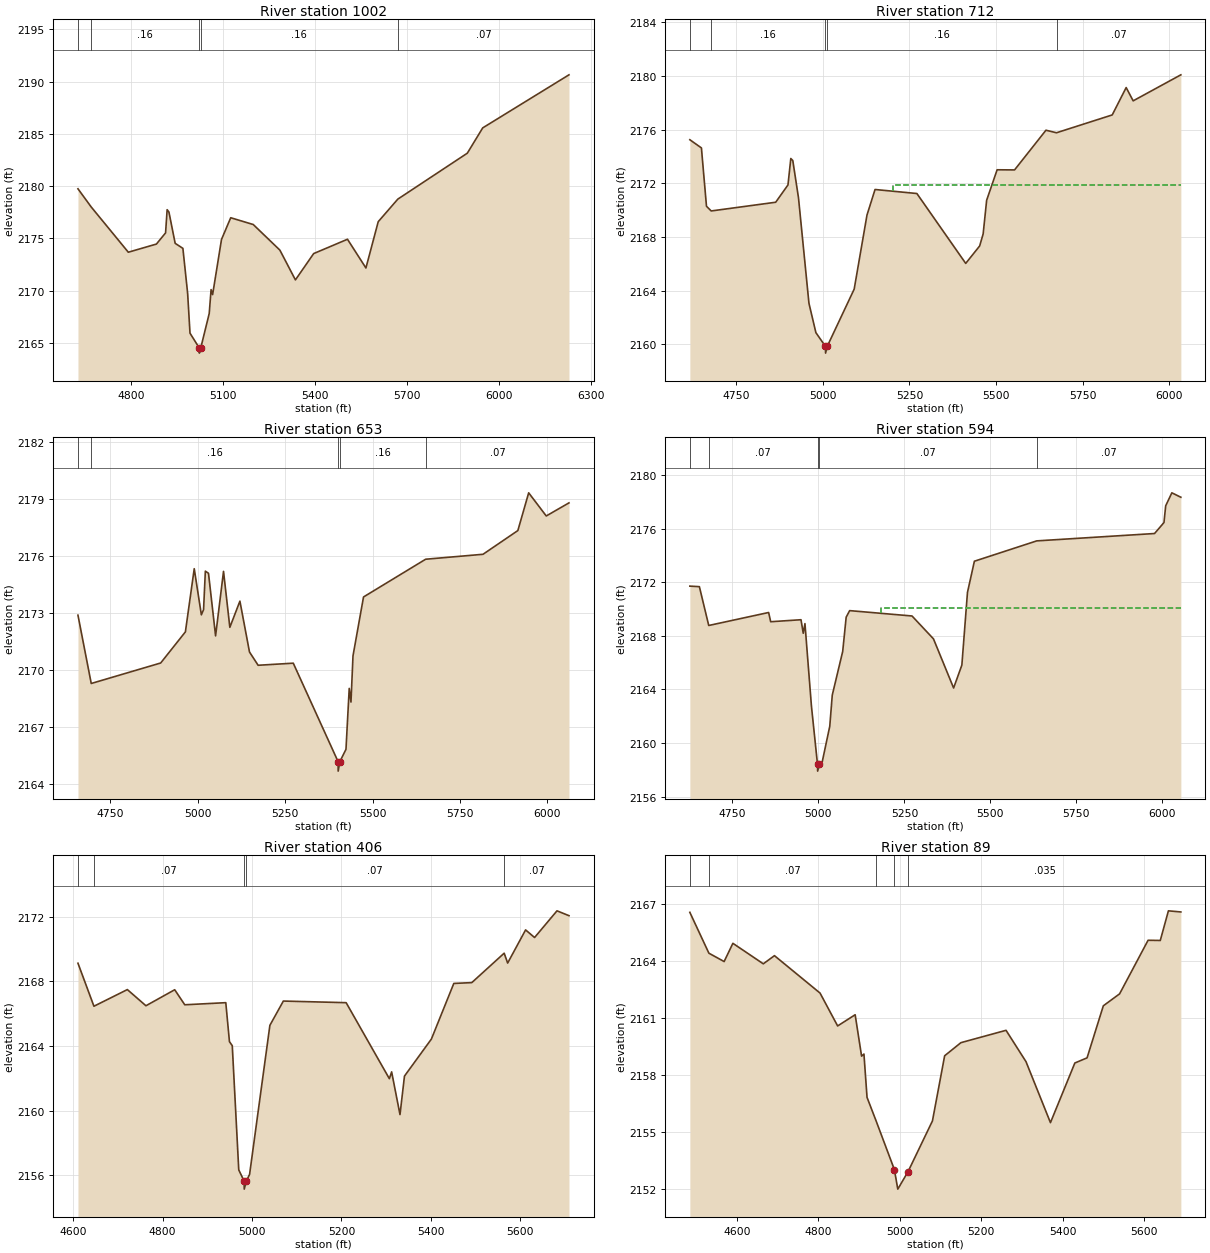
Type RM Length L Ch R = 1 ,1002    ,290,290,290
BEGIN DESCRIPTION:
MULBERRY CREEK TRIBUTARY 21A_2 2.0
END DESCRIPTION:
XS GIS Cut Line= 3
      1467343.76       6806667.1        1467705.        6806738.
      1468935.76      6806646.42
#Sta/Elev= 30
  4627.1 2179.74  4670.6 2177.99  4791.4 2173.67  4883.1 2174.45    4913 2175.52
  4918.1 2177.74  4923.9 2177.52  4944.3 2174.52  4969.5 2174.04    4985 2169.73
  4992.7 2165.92  5022.8 2164.51  5023.2 2164.01  5027.8 2164.51  5055.4  2167.8
  5061.5 2170.09  5066.5 2169.61  5095.5 2174.89  5125.6 2176.97  5199.1 2176.32
    5286 2173.87  5336.7 2171.02  5396.3 2173.54  5506.6 2174.91  5566.8 2172.16
  5606.9 2176.59  5670.8 2178.75  5897.7 2183.15  5947.9 2185.57  6229.4 2190.65
#Mann= 5 ,-1 , 0
  4627.1    .035       0  4670.6     .16       0  5022.8     .07       0
  5027.8     .16       0  5670.8     .07       0
Bank Sta=5022.8,5027.8
XS Rating Curve= 0 ,0
Exp/Cntr=0.3,0.1

Type RM Length L Ch R = 1 ,712     ,59,59,59
BEGIN DESCRIPTION:
Mapping XS 47213d1e
END DESCRIPTION:
XS GIS Cut Line= 4
      1467332.05      6806823.79      1467569.03      6807003.48
      1467855.49      6807029.52      1468681.77      6806935.98
#Sta/Elev= 30
  4616.5 2175.25  4649.9 2174.64  4664.5 2170.29  4678.1 2169.94  4864.2 2170.59
  4899.6 2171.88  4907.8 2173.85  4913.5  2173.7  4929.9 2170.93  4960.1 2163.06
  4980.1 2160.87  5007.8 2159.84  5008.1 2159.34  5012.8 2159.84  5090.6 2164.11
  5127.6 2169.64  5150.8 2171.54  5271.5 2171.24  5412.4 2166.03  5452.6 2167.33
  5462.7 2168.23  5472.8 2170.74    5503 2173.01  5553.3    2173  5643.9 2175.96
  5674.3 2175.77  5835.1  2177.1  5875.3 2179.14  5895.5 2178.15  6033.1 2180.09
#Mann= 5 ,-1 , 0
  4616.5    .035       0  4678.1     .16       0  5007.8     .07       0
  5012.8     .16       0  5674.3     .07       0
#XS Ineff= 2 , 0
       0                  5201.5       0 2171.84
Permanent Ineff=
       F       F
Bank Sta=5007.8,5012.8
XS Rating Curve= 0 ,0
Exp/Cntr=0.3,0.1

Type RM Length L Ch R = 1 ,653     ,59,59,59
BEGIN DESCRIPTION:
Mapping XS 2ad94ec4
END DESCRIPTION:
XS GIS Cut Line= 4
      1467345.05      6806927.94      1467595.07      6807058.16
      1467785.18      6807094.62       1468709.7      6806998.26
#Sta/Elev= 30
  4657.1 2172.89  4695.1 2169.29  4893.8 2170.37  4964.5 2172.01  4989.8 2175.34
  5010.2 2172.91  5016.5 2173.18  5021.6 2175.21  5030.6  2175.1  5050.9  2171.8
  5073.6  2175.2  5091.7 2172.25  5120.5 2173.63  5147.9 2170.95  5172.6 2170.25
  5273.2 2170.36  5401.4 2165.17  5401.7 2164.67  5406.4 2165.17    5424 2165.82
  5433.3 2169.03  5438.3 2168.31  5444.1 2170.75  5474.2 2173.85    5652 2175.84
  5816.1  2176.1  5915.8 2177.35  5946.8 2179.34  5997.1 2178.12  6062.1 2178.81
#Mann= 5 ,-1 , 0
  4657.1    .035       0  4695.1     .16       0  5401.4     .07       0
  5406.4     .16       0    5652     .07       0
Bank Sta=5401.4,5406.4
XS Rating Curve= 0 ,0
Exp/Cntr=0.3,0.1

Type RM Length L Ch R = 1 ,594     ,188,188,188
BEGIN DESCRIPTION:
Mapping XS dfceab59
END DESCRIPTION:
XS GIS Cut Line= 4
      1467332.02      6806953.98      1467576.84      6807118.06
      1467785.18      6807146.71      1468700.97      6807037.44
#Sta/Elev= 30
  4626.4 2171.72  4654.1 2171.68  4681.3 2168.78  4855.4 2169.75  4861.4 2169.06
  4949.5 2169.21    4956  2168.2    4961 2168.92  4979.8 2162.77  4997.5  2158.4
  4997.9  2157.9  5002.5  2158.4  5010.1 2158.46  5033.1 2161.25  5040.4 2163.58
  5070.7 2166.84  5080.8  2169.4  5090.9 2169.89  5272.2 2169.49  5334.6 2167.78
  5393.1 2164.11  5417.1 2165.82  5433.4 2171.25  5453.5 2173.58  5634.8  2175.1
  5977.2 2175.65  6004.6 2176.47  6009.6 2177.72  6027.5 2178.69  6053.7 2178.36
#Mann= 5 ,-1 , 0
  4626.4    .035       0  4681.3     .07       0  4997.5    .035       0
  5002.5     .07       0  5634.8     .07       0
#XS Ineff= 2 , 0
       0                  5181.6       0  2170.1
Permanent Ineff=
       F       F
Bank Sta=4997.5,5002.5
XS Rating Curve= 0 ,0
Exp/Cntr=0.3,0.1

Type RM Length L Ch R = 1 ,406     ,317,317,317
BEGIN DESCRIPTION:
Mapping XS e767c6d8
END DESCRIPTION:
XS GIS Cut Line= 3
      1467345.94      6807082.99      1467649.76      6807317.36
      1468361.69      6807261.93
#Sta/Elev= 30
    4611 2169.12  4646.7 2166.46  4721.4 2167.49    4763 2166.49  4827.3 2167.48
  4849.8 2166.55  4941.5 2166.68  4949.7 2164.27    4956 2164.02  4970.5 2156.34
  4982.4 2155.65  4982.8 2155.15  4987.5 2155.65  4994.7 2156.06  5040.1 2165.28
  5070.2 2166.78  5210.6 2166.68  5307.2 2161.98  5312.3  2162.4    5331 2159.76
    5341 2162.14  5401.2 2164.43  5451.3 2167.87  5491.5 2167.92  5563.9 2169.74
  5571.7 2169.13  5611.8 2171.18  5631.9 2170.71    5682 2172.36  5708.8 2172.06
#Mann= 5 ,-1 , 0
    4611    .035       0  4646.7     .07       0  4982.4    .035       0
  4987.5     .07       0  5563.9     .07       0
#XS Ineff= 2 , 0
       0                  5210.6       0 2166.68
Permanent Ineff=
       F       F
Bank Sta=4982.4,4987.5
XS Rating Curve= 0 ,0
Exp/Cntr=0.3,0.1

Type RM Length L Ch R = 1 ,89      ,0,0,0
BEGIN DESCRIPTION:
MULBERRY CREEK TRIBUTARY 21A_2 1.0
END DESCRIPTION:
XS GIS Cut Line= 3
       1467347.9       6807170.2      1467604.81      6807617.92
      1468295.59      6807604.69
#Sta/Elev= 30
  4483.8 2166.57  4530.6 2164.42  4568.1 2163.98  4589.6 2164.94  4664.4 2163.86
  4691.8 2164.29  4803.9 2162.32  4847.1 2160.59  4890.2 2161.18    4906    2159
  4911.8 2159.11  4919.4 2156.83    4941 2155.63  4986.6 2153.03    4995    2152
  5020.2 2152.92  5080.2 2155.59  5110.2 2159.02  5150.2 2159.71  5261.1 2160.36
  5310.2 2158.71  5370.3  2155.5  5430.3 2158.64  5460.3 2158.91  5500.3 2161.65
  5540.3 2162.28  5610.3  2165.1  5640.3 2165.09  5660.3 2166.65  5690.9 2166.59
#Mann= 5 ,-1 , 0
  4483.8    .035       0  4530.6     .07       0    4941    .035       0
  4986.6    .035       0  5020.2    .035       0
#XS Ineff= 2 , 0
       0                  5261.1       0 2160.36
Permanent Ineff=
       F       F
Bank Sta=4986.6,5020.2
XS Rating Curve= 0 ,0
Exp/Cntr=0.3,0.1

Chan Stop Cuts=-1
Use User Specified Reach Order=0
Composite Channel Slope=5