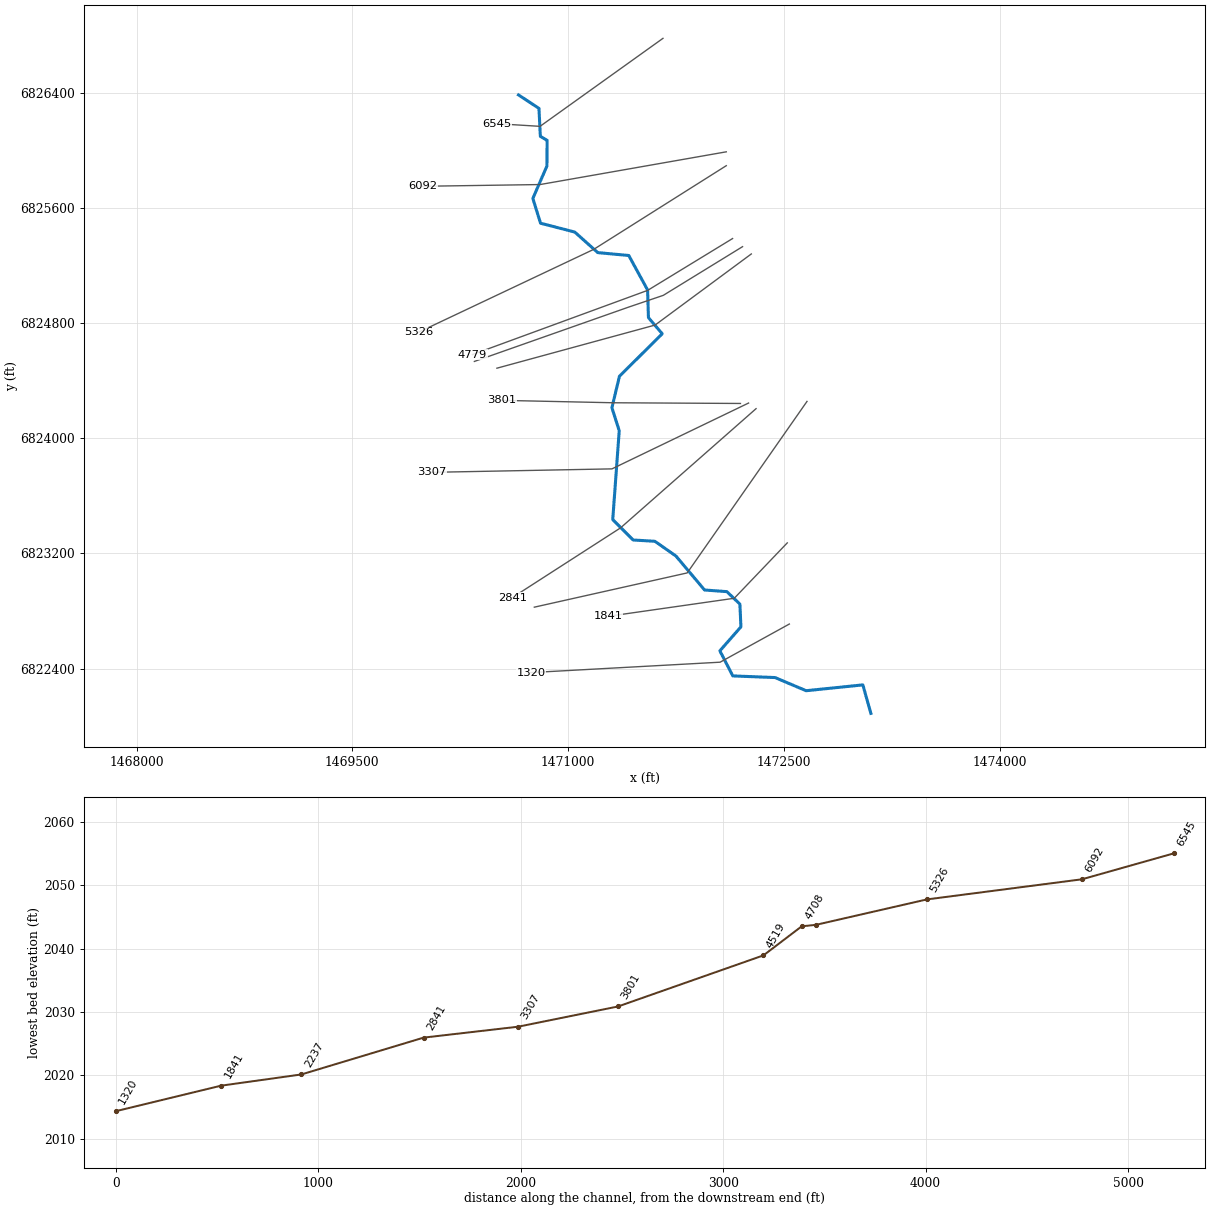
--- MULBERRY CREEK TRIBUTARY 22.prj (project) ---

Proj Title=MULBERRY CREEK TRIBUTARY 22 Base Level Engineering
Current Plan=p01
Default Exp/Contr=0.3,0.1
English Units
Geom File=g01
Flow File=f01
Plan File=p01
Y Axis Title=Elevation
X Axis Title(PF)=Main Channel Distance
X Axis Title(XS)=Station
BEGIN DESCRIPTION:
MULBERRY CREEK TRIBUTARY 22
END DESCRIPTION:
DSS Export Rating Curves= 0
DSS Export Rating Curve Sorted= 0
DSS Export Volume Flow Curves= 0
DXF OffsetX= 0
DXF OffsetY= 0
DXF ScaleX= 1
DXF ScaleY= 10

--- MULBERRY CREEK TRIBUTARY 22.p01 (plan) ---

Plan Title=Multiple Run
Short Identifier=Multiple
Geom File=g01
Flow File=f01
Subcritical Flow
K Sum by GR= 0
Std Step Tol= 0.01
Critical Tol= 0.01
Num of Std Step Trials= 20
Max Error Tol= 0.3
Flow Tol Ratio= 0.001
Split Flow NTrial= 30
Split Flow Tol= 0.02
Split Flow Ratio= 0.02
Log Output Level= 0
Friction Slope Method= 1
Unsteady Friction Slope Method= 2
Unsteady Bridges Friction Slope Method= 1
Parabolic Critical Depth
Global Vel Dist=  1 , 1 , 1
Global Log Level= 0
CheckData=True
Encroach Param= -1, 0, 0, 0
BEGIN DESCRIPTION:
Multiple Run
END DESCRIPTION:

--- MULBERRY CREEK TRIBUTARY 22.f01 (steady flow) ---

Flow Title=Multiple
Program Version=4.10
Number of Profiles= 7
Profile Names=10-year,25-year,50-year,1pct_min,100-year,1pct_plu,500-year
River Rch & RM=MULBERRY CREEK T,Reach-1         ,6545
     401     586     748     476     949    1894    1547
River Rch & RM=MULBERRY CREEK T,Reach-1         ,5326
     605     905    1172     755    1506    3005    2520
River Rch & RM=MULBERRY CREEK T,Reach-1         ,2841
     713    1074    1397     904    1803    3597    3039
Boundary for River Rch & Prof#=MULBERRY CREEK T,Reach-1         , 1
Up Type= 0
Dn Type= 3
Dn Slope=0.00775
Boundary for River Rch & Prof#=MULBERRY CREEK T,Reach-1         , 2
Up Type= 0
Dn Type= 3
Dn Slope=0.00775
Boundary for River Rch & Prof#=MULBERRY CREEK T,Reach-1         , 3
Up Type= 0
Dn Type= 3
Dn Slope=0.00775
Boundary for River Rch & Prof#=MULBERRY CREEK T,Reach-1         , 4
Up Type= 0
Dn Type= 3
Dn Slope=0.00775
Boundary for River Rch & Prof#=MULBERRY CREEK T,Reach-1         , 5
Up Type= 0
Dn Type= 3
Dn Slope=0.00775
Boundary for River Rch & Prof#=MULBERRY CREEK T,Reach-1         , 6
Up Type= 0
Dn Type= 3
Dn Slope=0.00775
Boundary for River Rch & Prof#=MULBERRY CREEK T,Reach-1         , 7
Up Type= 0
Dn Type= 3
Dn Slope=0.00775
DSS Import GetInterval= 0
DSS Import GetPeak= 0
DSS Import FillOption= 0

--- MULBERRY CREEK TRIBUTARY 22.g01 (geometry) ---

Geom Title=Existing Conditions

River Reach=MULBERRY CREEK T,Reach-1
Reach XY= 30
      1470655.00      6826388.00      1470797.32      6826294.48
      1470806.97      6826099.97      1470854.04      6826072.04
      1470852.74      6825893.94      1470754.90      6825667.90
      1470808.35      6825496.10      1471046.44      6825434.48
      1471206.47      6825291.55      1471421.80      6825271.59
      1471552.74      6825032.06      1471558.55      6824839.47
      1471654.46      6824727.31      1471357.07      6824432.14
      1471304.60      6824213.00      1471355.47      6824053.16
      1471310.40      6823435.57      1471452.55      6823293.47
      1471603.53      6823284.45      1471749.38      6823182.38
      1471948.81      6822945.82      1472103.54      6822934.46
      1472194.54      6822847.82      1472201.47      6822689.47
      1472055.24      6822522.78      1472145.17      6822348.47
      1472439.04      6822337.04      1472655.00      6822245.56
      1473049.35      6822286.03      1473105.00      6822088.00

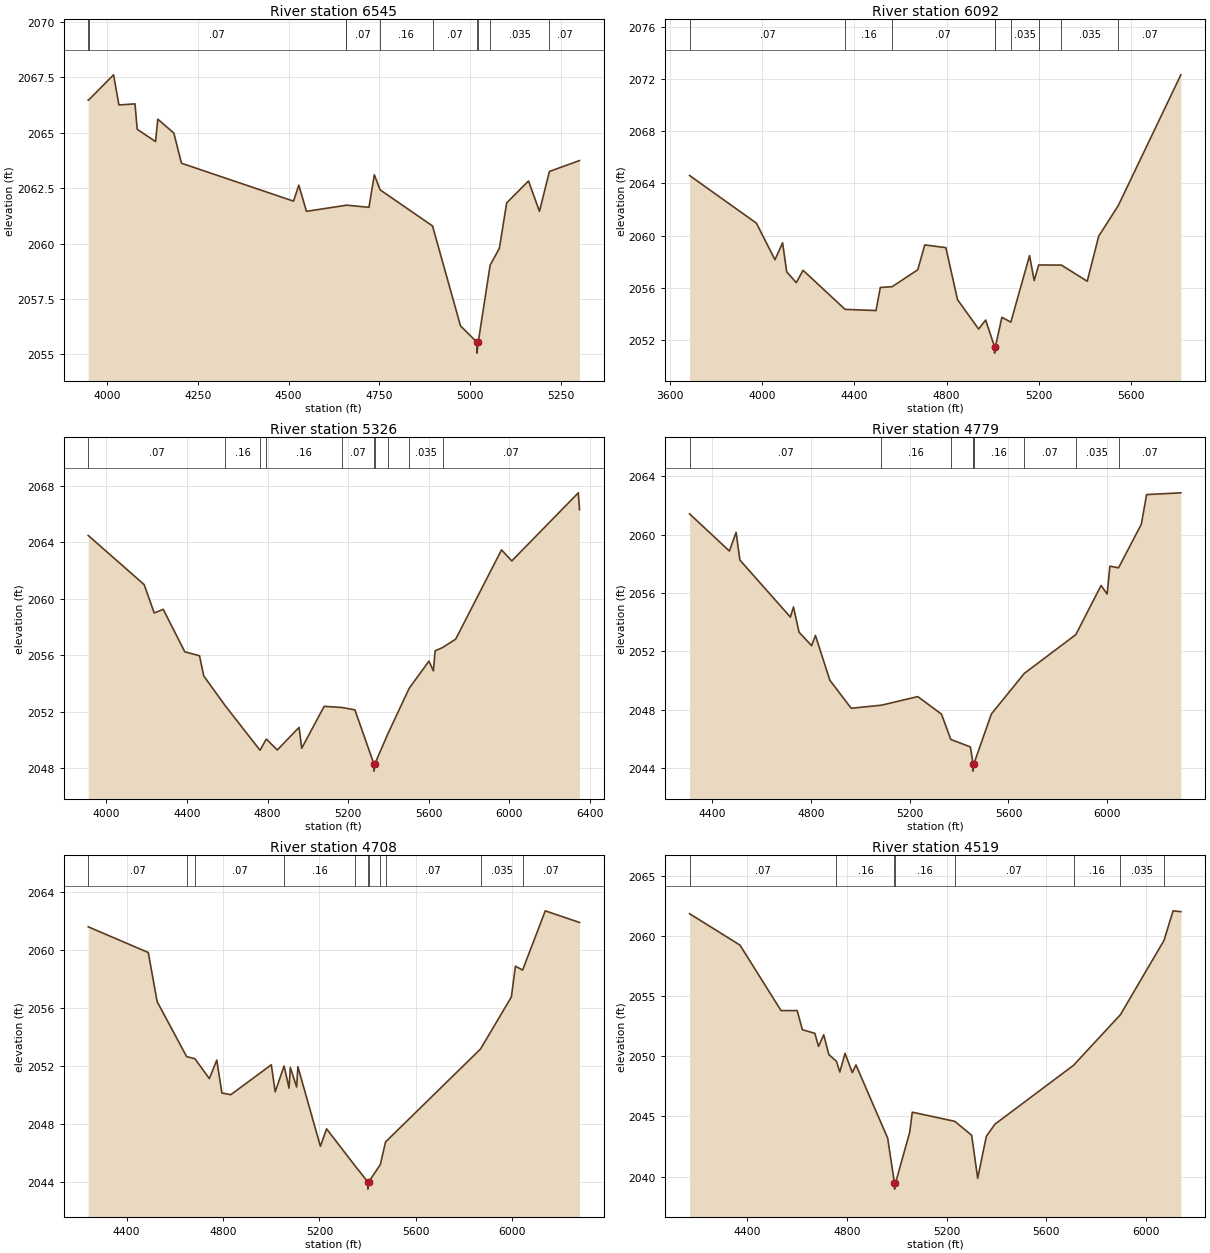
Type RM Length L Ch R = 1,6545,453,453,453
BEGIN DESCRIPTION:
MULBERRY CREEK TRIBUTARY 22 10.0
END DESCRIPTION:
XS GIS Cut Line= 3
      1471659.66      6826781.47      1470804.80      6826169.56
      1470504.96      6826188.00
#Sta/Elev= 30
  3948.7 2066.48  3949.7 2066.48  4018.4 2067.62  4033.2 2066.26  4077.4 2066.31
  4083.5 2065.16  4133.9 2064.61  4140.1 2065.62  4184.3 2064.99  4205.2 2063.63
  4513.5 2061.92  4528.2 2062.64  4549.1 2061.46  4657.4 2061.73  4658.1 2061.74
  4721.1 2061.64  4735.9 2063.11  4751.8 2062.43  4896.0 2060.80  4973.0 2056.29
  5017.8 2055.56  5018.1 2055.06  5021.8 2055.56  5054.5 2059.03  5079.9 2059.79
  5100.0 2061.84  5160.1 2062.83  5190.2 2061.46  5217.6 2063.26  5300.4 2063.75
#Mann=10,-1,0
  3948.7   0.035       0  3949.7    0.07       0  4657.4    0.16       0
  4658.1    0.07       0  4751.8    0.16       0  4896.0    0.07       0
  5017.8    0.07       0  5021.8    0.07       0  5054.5   0.035       0
  5217.6    0.07       0
Bank Sta=5017.8,5021.8
Exp/Cntr=0.3,0.1

Type RM Length L Ch R = 1,6092,766,766,766
BEGIN DESCRIPTION:
MULBERRY CREEK TRIBUTARY 22 9.0
END DESCRIPTION:
XS GIS Cut Line= 3
      1472099.78      6825992.42      1470805.15      6825764.87
      1469988.92      6825752.85
#Sta/Elev= 30
  3685.4 2064.61  3975.3 2060.95  4055.8 2058.14  4088.9 2059.45  4106.5 2057.22
  4148.2 2056.38  4177.6 2057.33  4360.0 2054.33  4494.1 2054.24  4512.7 2056.01
  4563.8 2056.07  4675.1 2057.37  4705.6 2059.28  4797.0 2059.07  4847.7 2055.07
  4939.1 2052.82  4969.6 2053.51  5008.0 2051.47  5008.3 2050.97  5012.0 2051.47
  5040.0 2053.72  5078.8 2053.35  5160.0 2058.46  5180.0 2056.54  5199.8 2057.74
  5298.3 2057.73  5410.1 2056.49  5460.1 2059.96  5544.8 2062.30  5816.2 2072.34
#Mann=9,-1,0
  3685.4    0.07       0  4360.0    0.16       0  4563.8    0.07       0
  5008.0    0.07       0  5012.0    0.07       0  5078.8   0.035       0
  5199.8    0.07       0  5298.3   0.035       0  5544.8    0.07       0
Bank Sta=5008,5012
Exp/Cntr=0.3,0.1

Type RM Length L Ch R = 1,5326,547,547,547
BEGIN DESCRIPTION:
MULBERRY CREEK TRIBUTARY 22 8.0
END DESCRIPTION:
XS GIS Cut Line= 3
      1472099.75      6825896.05      1471178.14      6825314.22
      1469959.65      6824737.71
#Sta/Elev= 30
  3910.1 2064.48  4187.7 2061.00  4237.6 2058.99  4282.3 2059.25  4389.4 2056.24
  4462.3 2055.96  4483.5 2054.53  4589.1 2052.44  4762.5 2049.27  4793.9 2050.06
  4848.3 2049.29  4956.4 2050.89  4969.5 2049.41  5080.9 2052.38  5167.2 2052.30
  5233.5 2052.13  5328.0 2048.29  5328.3 2047.79  5332.0 2048.29  5396.6 2050.42
  5502.9 2053.66  5600.9 2055.58  5623.0 2054.89  5631.4 2056.31  5668.3 2056.54
  5733.6 2057.14  5961.0 2063.46  6012.0 2062.68  6342.1 2067.50  6348.0 2066.30
#Mann=10,-1,0
  3910.1    0.07       0  4589.1    0.16       0  4762.5    0.07       0
  4793.9    0.16       0  5167.2    0.07       0  5328.0    0.07       0
  5332.0    0.07       0  5396.6    0.16       0  5502.9   0.035       0
  5668.3    0.07       0
Bank Sta=5328,5332
Exp/Cntr=0.3,0.1

Type RM Length L Ch R = 1,4779,71,71,71
BEGIN DESCRIPTION:
Mapping XS 81bc2a14
END DESCRIPTION:
XS GIS Cut Line= 3
      1472143.55      6825389.44      1471553.27      6825029.19
      1470334.78      6824582.56
#Sta/Elev= 30
  4308.6 2061.42  4469.8 2058.87  4497.0 2060.15  4512.4 2058.25  4716.9 2054.34
  4729.3 2055.03  4752.1 2053.30  4802.8 2052.38  4818.3 2053.08  4876.4 2050.02
  4963.0 2048.09  5085.6 2048.30  5232.6 2048.89  5328.5 2047.69  5366.6 2045.95
  5445.6 2045.44  5455.3 2044.43  5455.8 2044.28  5456.0 2043.78  5459.8 2044.28
  5530.8 2047.70  5664.0 2050.48  5872.7 2053.14  5974.9 2056.51  5999.4 2055.92
  6010.7 2057.83  6045.7 2057.72  6137.9 2060.71  6159.2 2062.74  6297.9 2062.86
#Mann=9,-1,0
  4308.6    0.07       0  5085.6    0.16       0  5366.6    0.07       0
  5455.3    0.16       0  5455.8    0.07       0  5459.8    0.16       0
  5664.0    0.07       0  5872.7   0.035       0  6045.7    0.07       0
Bank Sta=5455.8,5459.8
Exp/Cntr=0.3,0.1

Type RM Length L Ch R = 1,4708,189,189,189
BEGIN DESCRIPTION:
Mapping XS 21ebc595
END DESCRIPTION:
XS GIS Cut Line= 4
      1472213.02      6825333.03      1471661.78      6824994.47
      1471418.72      6824912.01      1470348.35      6824534.99
#Sta/Elev= 30
  4240.5 2061.60  4489.7 2059.83  4526.4 2056.45  4648.9 2052.66  4683.0 2052.52
  4743.0 2051.15  4773.9 2052.42  4795.1 2050.16  4831.9 2050.04  5000.2 2052.10
  5016.2 2050.24  5053.2 2052.02  5073.8 2050.49  5079.0 2051.92  5105.2 2050.57
  5110.4 2051.97  5203.8 2046.49  5229.5 2047.69  5348.7 2045.12  5400.5 2044.04
  5400.7 2043.54  5404.5 2044.04  5452.6 2045.24  5474.2 2046.79  5868.3 2053.19
  5996.2 2056.77  6013.0 2058.89  6042.7 2058.62  6136.9 2062.70  6278.9 2061.90
#Mann=11,-1,0
  4240.5    0.07       0  4648.9    0.16       0  4683.0    0.07       0
  5053.2    0.16       0  5348.7    0.07       0  5400.5    0.07       0
  5404.5    0.07       0  5452.6    0.16       0  5474.2    0.07       0
  5868.3   0.035       0  6042.7    0.07       0
Bank Sta=5400.5,5404.5
Exp/Cntr=0.3,0.1

Type RM Length L Ch R = 1,4519,718,718,718
BEGIN DESCRIPTION:
MULBERRY CREEK TRIBUTARY 22 7.0
END DESCRIPTION:
XS GIS Cut Line= 3
      1472273.85      6825282.37      1471605.00      6824788.00
      1470505.00      6824488.00
#Sta/Elev= 30
  4168.3 2061.86  4370.6 2059.25  4535.5 2053.80  4600.3 2053.80  4621.1 2052.21
  4671.2 2051.91  4685.9 2050.82  4706.7 2051.79  4727.5 2050.14  4757.9 2049.58
  4771.4 2048.69  4792.3 2050.25  4821.5 2048.64  4836.2 2049.28  4963.5 2043.19
  4990.7 2039.45  4991.0 2038.95  4994.8 2039.45  5051.9 2043.68  5062.2 2045.35
  5232.9 2044.59  5300.6 2043.43  5324.8 2039.85  5359.4 2043.34  5393.9 2044.35
  5709.4 2049.25  5897.6 2053.46  6072.4 2059.63  6109.1 2062.10  6140.2 2062.03
#Mann=8,-1,0
  4168.3    0.07       0  4757.9    0.16       0  4990.7    0.07       0
  4994.8    0.16       0  5232.9    0.07       0  5709.4    0.16       0
  5897.6   0.035       0  6072.4    0.07       0
Bank Sta=4990.7,4994.8
Exp/Cntr=0.3,0.1

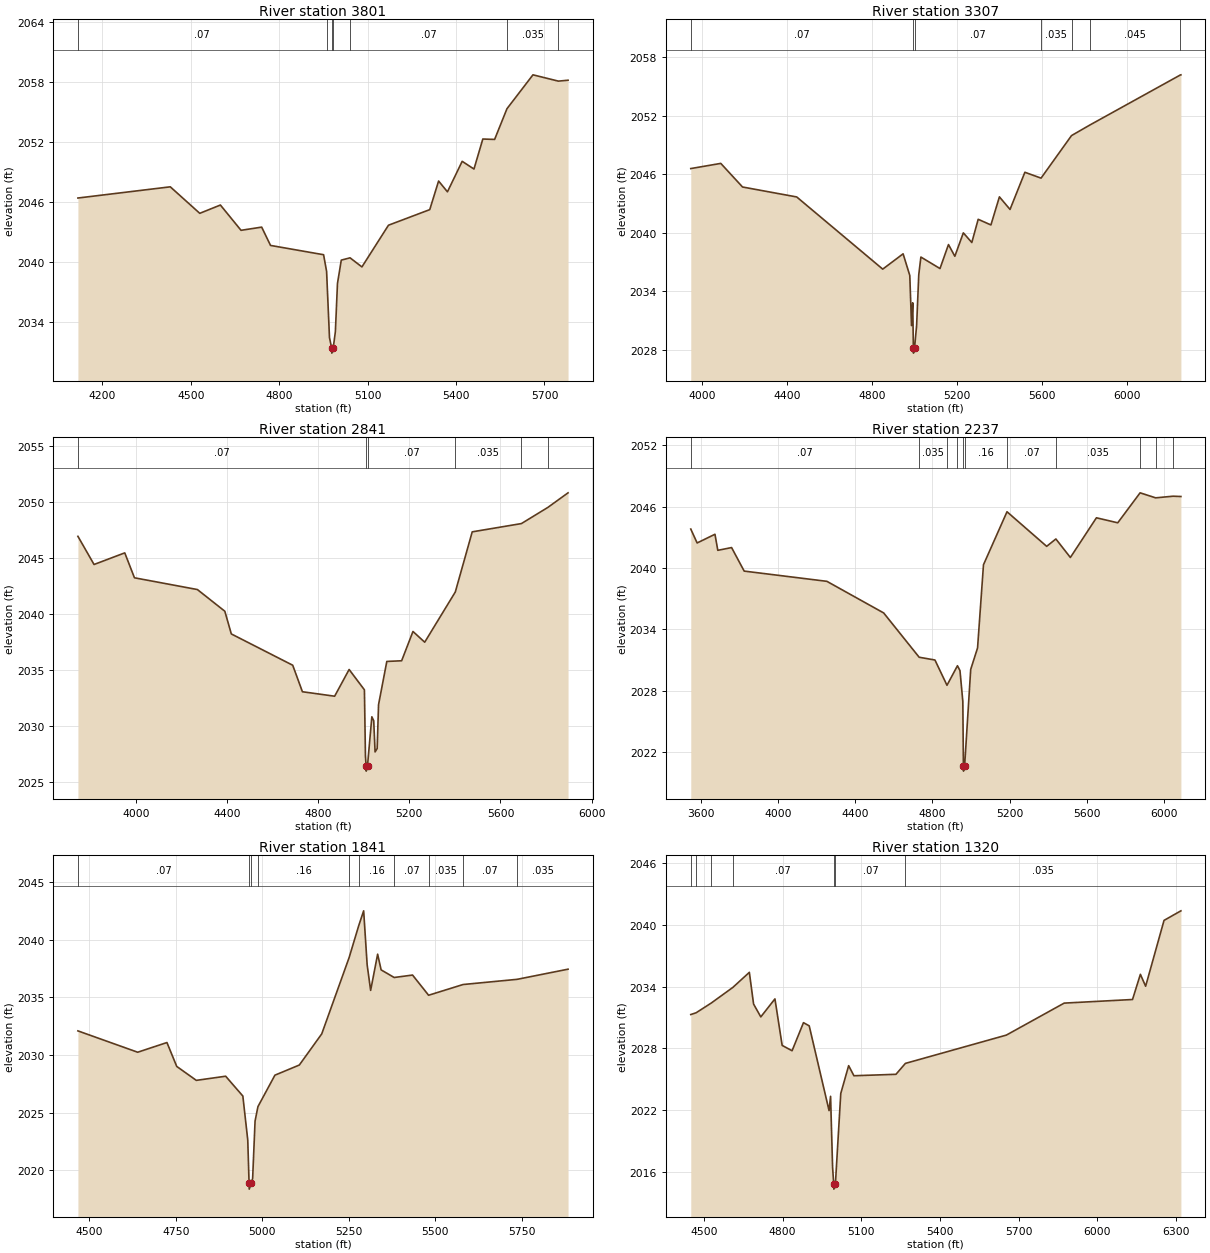
Type RM Length L Ch R = 1,3801,494,494,494
BEGIN DESCRIPTION:
MULBERRY CREEK TRIBUTARY 22 5.0
END DESCRIPTION:
XS GIS Cut Line= 3
      1472198.30      6824242.78      1471315.81      6824247.63
      1470535.99      6824264.48
#Sta/Elev= 30
  4117.5 2046.39  4430.8 2047.51  4530.8 2044.86  4600.8 2045.69  4670.8 2043.16
  4740.8 2043.48  4770.8 2041.65  4950.8 2040.72  4961.0 2039.05  4970.8 2032.43
  4978.2 2031.38  4978.6 2030.88  4983.4 2031.38  4990.8 2033.03  4997.9 2037.85
  5010.8 2040.18  5040.6 2040.41  5080.8 2039.50  5170.9 2043.67  5310.9 2045.23
  5340.9 2048.09  5370.9 2047.01  5420.9 2050.06  5460.9 2049.29  5490.9 2052.29
  5530.9 2052.25  5572.8 2055.32  5661.0 2058.71  5747.2 2058.08  5780.0 2058.17
#Mann=7,-1,0
  4117.5    0.07       0  4961.0    0.16       0  4978.2    0.07       0
  4983.4    0.16       0  5040.6    0.07       0  5572.8   0.035       0
  5747.2    0.07       0
Bank Sta=4978.2,4983.4
Exp/Cntr=0.3,0.1

Type RM Length L Ch R = 1,3307,466,466,466
BEGIN DESCRIPTION:
MULBERRY CREEK TRIBUTARY 22 4.0
END DESCRIPTION:
XS GIS Cut Line= 3
      1472254.74      6824245.68      1471304.85      6823788.00
      1470049.98      6823763.91
#Sta/Elev= 30
  3945.6 2046.60  4087.0 2047.13  4189.5 2044.71  4444.8 2043.69  4850.1 2036.29
  4946.1 2037.86  4977.6 2035.64  4985.8 2030.50  4991.4 2032.84  4994.5 2028.18
  4994.9 2027.68  4999.8 2028.18  5009.8 2030.52  5019.9 2035.72  5029.9 2037.53
  5119.9 2036.35  5159.9 2038.81  5189.9 2037.61  5229.9 2040.01  5269.9 2039.02
  5299.9 2041.40  5359.9 2040.82  5399.9 2043.70  5449.9 2042.41  5519.9 2046.22
  5596.1 2045.62  5739.6 2049.98  5824.9 2051.05  6252.9 2056.20  6255.1 2056.21
#Mann=7,-1,0
  3945.6    0.07       0  4994.5    0.07       0  4999.8    0.07       0
  5596.1   0.035       0  5739.6    0.07       0  5824.9   0.045       0
  6252.9    0.07       0
Bank Sta=4994.5,4999.8
Exp/Cntr=0.3,0.1

Type RM Length L Ch R = 1,2841,604,604,604
BEGIN DESCRIPTION:
MULBERRY CREEK TRIBUTARY 22 3.0
END DESCRIPTION:
XS GIS Cut Line= 3
      1472306.81      6824206.60      1471364.84      6823377.92
      1470611.01      6822892.31
#Sta/Elev= 30
  3745.4 2046.96  3816.2 2044.44  3951.0 2045.48  3993.6 2043.25  4269.8 2042.20
  4390.2 2040.26  4418.7 2038.23  4688.2 2035.43  4730.8 2033.06  4872.2 2032.66
  4935.8 2035.05  5002.9 2033.23  5007.4 2027.32  5010.2 2026.46  5010.7 2025.96
  5016.5 2026.46  5035.5 2030.82  5043.7 2030.47  5049.7 2027.68  5058.9 2027.98
  5064.9 2031.90  5101.2 2035.77  5166.3 2035.83  5216.0 2038.45  5267.5 2037.49
  5401.8 2041.98  5476.1 2047.36  5692.1 2048.10  5807.7 2049.54  5896.7 2050.85
#Mann=6,-1,0
  3745.4    0.07       0  5010.2    0.07       0  5016.5    0.07       0
  5401.8   0.035       0  5692.1    0.07       0  5807.7   0.035       0
Bank Sta=5010.2,5016.5
Exp/Cntr=0.3,0.1

Type RM Length L Ch R = 1,2237,396,396,396
BEGIN DESCRIPTION:
MULBERRY CREEK TRIBUTARY 22 2.0
END DESCRIPTION:
XS GIS Cut Line= 3
      1472661.01      6824257.05      1471828.27      6823064.65
      1470765.13      6822826.46
#Sta/Elev= 30
  3545.6 2043.80  3578.6 2042.44  3671.1 2043.29  3685.9 2041.72  3757.4 2041.99
  3822.8 2039.69  4252.0 2038.69  4546.8 2035.60  4731.0 2031.27  4813.0 2031.00
  4875.4 2028.53  4929.7 2030.44  4942.8 2029.97  4957.6 2026.96  4960.6 2020.64
  4961.1 2020.14  4966.9 2020.64  4998.5 2030.08  5034.1 2032.18  5064.8 2040.31
  5186.9 2045.49  5392.8 2042.11  5440.6 2042.83  5515.8 2041.02  5651.0 2044.90
  5761.7 2044.41  5877.7 2047.34  5958.4 2046.85  6048.5 2047.01  6089.5 2046.98
#Mann=11,-1,0
  3545.6    0.07       0  4731.0   0.035       0  4875.4    0.07       0
  4929.7    0.16       0  4960.6    0.07       0  4966.9    0.16       0
  5186.9    0.07       0  5440.6   0.035       0  5877.7    0.07       0
  5958.4   0.035       0  6048.5    0.07       0
Bank Sta=4960.6,4966.9
Exp/Cntr=0.3,0.1

Type RM Length L Ch R = 1,1841,521,521,521
BEGIN DESCRIPTION:
Mapping XS ed51c103
END DESCRIPTION:
XS GIS Cut Line= 3
      1472523.75      6823273.40      1472155.35      6822888.35
      1471279.98      6822763.00
#Sta/Elev= 30
  4467.1 2032.09  4639.9 2030.24  4724.5 2031.08  4752.8 2029.01  4809.4 2027.80
  4894.3 2028.16  4944.0 2026.44  4958.2 2022.62  4962.0 2018.87  4962.5 2018.37
  4968.3 2018.87  4972.3 2019.30  4979.3 2024.27  4987.6 2025.52  5036.7 2028.25
  5107.3 2029.13  5172.1 2031.83  5251.2 2038.44  5279.0 2041.21  5293.3 2042.50
  5303.4 2037.82  5313.5 2035.60  5333.7 2038.74  5343.8 2037.38  5381.5 2036.72
  5434.7 2036.93  5481.1 2035.18  5580.7 2036.11  5737.0 2036.56  5884.3 2037.44
#Mann=10,-1,0
  4467.1    0.07       0  4962.0    0.07       0  4968.3    0.07       0
  4987.6    0.16       0  5251.2    0.07       0  5279.0    0.16       0
  5381.5    0.07       0  5481.1   0.035       0  5580.7    0.07       0
  5737.0   0.035       0
Bank Sta=4962,4968.3
Exp/Cntr=0.3,0.1

Type RM Length L Ch R = 1,1320,0,0,0
BEGIN DESCRIPTION:
MULBERRY CREEK TRIBUTARY 22 1.0
END DESCRIPTION:
XS GIS Cut Line= 3
      1472538.24      6822709.25      1472056.95      6822443.88
      1470740.84      6822371.60
#Sta/Elev= 30
  4450.4 2031.30  4470.7 2031.47  4528.6 2032.42  4610.9 2033.94  4673.6 2035.40
  4689.7 2032.32  4717.2 2031.07  4771.1 2032.82  4798.6 2028.30  4836.4 2027.78
  4879.9 2030.51  4901.7 2030.20  4977.4 2021.96  4983.1 2023.35  4990.8 2016.45
  4995.1 2014.83  4995.6 2014.33  5001.5 2014.83  5022.0 2023.63  5052.0 2026.33
  5072.1 2025.35  5232.3 2025.49  5268.2 2026.55  5652.9 2029.30  5873.3 2032.41
  6133.7 2032.76  6163.7 2035.21  6183.7 2034.05  6253.8 2040.45  6318.1 2041.38
#Mann=7,-1,0
  4450.4    0.16       0  4470.7    0.07       0  4528.6    0.16       0
  4610.9    0.07       0  4995.1    0.07       0  5001.5    0.07       0
  5268.2   0.035       0
Bank Sta=4995.1,5001.5
Exp/Cntr=0.3,0.1

Chan Stop Cuts=-1