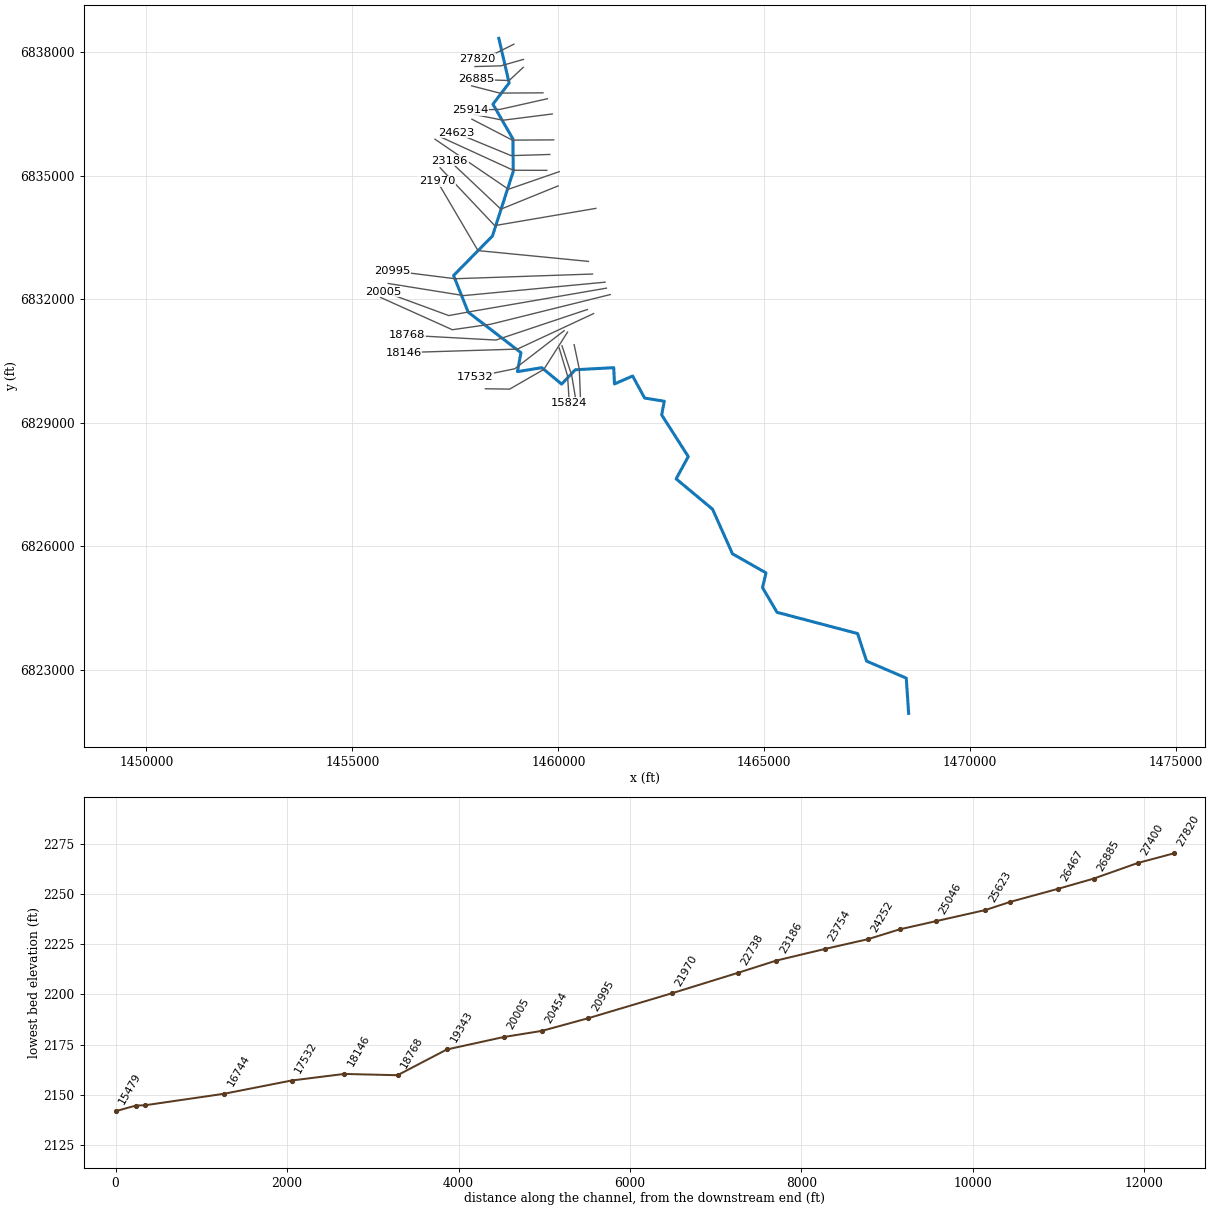
--- MULBERRY CREEK TRIBUTARY 23.prj (project) ---

Proj Title=MULBERRY CREEK TRIBUTARY 23 Base Level Engineering
Current Plan=p01
Default Exp/Contr=0.3,0.1
English Units
Geom File=g01
Flow File=f01
Plan File=p01
Y Axis Title=Elevation
X Axis Title(PF)=Main Channel Distance
X Axis Title(XS)=Station
BEGIN DESCRIPTION:
MULBERRY CREEK TRIBUTARY 23
END DESCRIPTION:
DSS Export Rating Curves= 0
DSS Export Rating Curve Sorted= 0
DSS Export Volume Flow Curves= 0
DXF OffsetX= 0
DXF OffsetY= 0
DXF ScaleX= 1
DXF ScaleY= 10

--- MULBERRY CREEK TRIBUTARY 23.p01 (plan) ---

Plan Title=Multiple Run
Short Identifier=Multiple
Geom File=g01
Flow File=f01
Subcritical Flow
K Sum by GR= 0
Std Step Tol= 0.01
Critical Tol= 0.01
Num of Std Step Trials= 20
Max Error Tol= 0.3
Flow Tol Ratio= 0.001
Split Flow NTrial= 30
Split Flow Tol= 0.02
Split Flow Ratio= 0.02
Log Output Level= 0
Friction Slope Method= 1
Unsteady Friction Slope Method= 2
Unsteady Bridges Friction Slope Method= 1
Parabolic Critical Depth
Global Vel Dist=  1 , 1 , 1
Global Log Level= 0
CheckData=True
Encroach Param= -1, 0, 0, 0
BEGIN DESCRIPTION:
Multiple Run
END DESCRIPTION:

--- MULBERRY CREEK TRIBUTARY 23.f01 (steady flow) ---

Flow Title=Multiple
Program Version=4.10
Number of Profiles= 7
Profile Names=10-year,25-year,50-year,1pct_min,100-year,1pct_plu,500-year
River Rch & RM=MULBERRY CREEK T,Reach-1         ,27820
     419     614     785     500     997    1990    1628
River Rch & RM=MULBERRY CREEK T,Reach-1         ,26885
     593     883    1140     732    1460    2913    2424
River Rch & RM=MULBERRY CREEK T,Reach-1         ,20995
     803    1212    1580    1022    2040    4071    3446
River Rch & RM=MULBERRY CREEK T,Reach-1         ,18146
     881    1331    1734    1121    2237    4464    3773
River Rch & RM=MULBERRY CREEK T,Reach-1         ,12314
    1044    1587    2077    1349    2691    5369    4575
River Rch & RM=MULBERRY CREEK T,Reach-1         ,7770
    1068    1621    2119    1373    2740    5467    4642
Boundary for River Rch & Prof#=MULBERRY CREEK T,Reach-1         , 1
Up Type= 0
Dn Type= 3
Dn Slope=0.005
Boundary for River Rch & Prof#=MULBERRY CREEK T,Reach-1         , 2
Up Type= 0
Dn Type= 3
Dn Slope=0.005
Boundary for River Rch & Prof#=MULBERRY CREEK T,Reach-1         , 3
Up Type= 0
Dn Type= 3
Dn Slope=0.005
Boundary for River Rch & Prof#=MULBERRY CREEK T,Reach-1         , 4
Up Type= 0
Dn Type= 3
Dn Slope=0.005
Boundary for River Rch & Prof#=MULBERRY CREEK T,Reach-1         , 5
Up Type= 0
Dn Type= 3
Dn Slope=0.005
Boundary for River Rch & Prof#=MULBERRY CREEK T,Reach-1         , 6
Up Type= 0
Dn Type= 3
Dn Slope=0.005
Boundary for River Rch & Prof#=MULBERRY CREEK T,Reach-1         , 7
Up Type= 0
Dn Type= 3
Dn Slope=0.005
DSS Import GetInterval= 0
DSS Import GetPeak= 0
DSS Import FillOption= 0

--- MULBERRY CREEK TRIBUTARY 23.g01 (geometry) ---

Geom Title=Existing Conditions
Program Version=4.10

River Reach=MULBERRY CREEK T,Reach-1
Reach XY= 30
        1458555.        6838338.      1458804.69      6837253.06
      1458412.22      6836737.69       1458897.4      6835891.34
      1458904.49      6835103.21      1458399.53      6833535.55
      1457456.46      6832575.86      1457810.83       6831685.7
      1459091.88      6830701.22      1459006.45      6830241.53
      1459599.15      6830335.96      1460080.13       6829937.7
      1460410.89      6830286.04      1461344.72      6830337.11
      1461363.09      6829941.35      1461803.68      6830134.67
      1462095.25      6829598.53      1462572.24      6829521.75
      1462508.74      6829189.56      1463154.13      6828177.67
      1462859.95      6827635.42      1463744.48      6826897.79
      1464227.99      6825814.48      1465041.73      6825351.69
      1464957.05      6824993.84        1465310.        6824393.
      1467264.79      6823877.48      1467484.52      6823207.61
      1468447.24      6822794.17        1468505.        6821938.

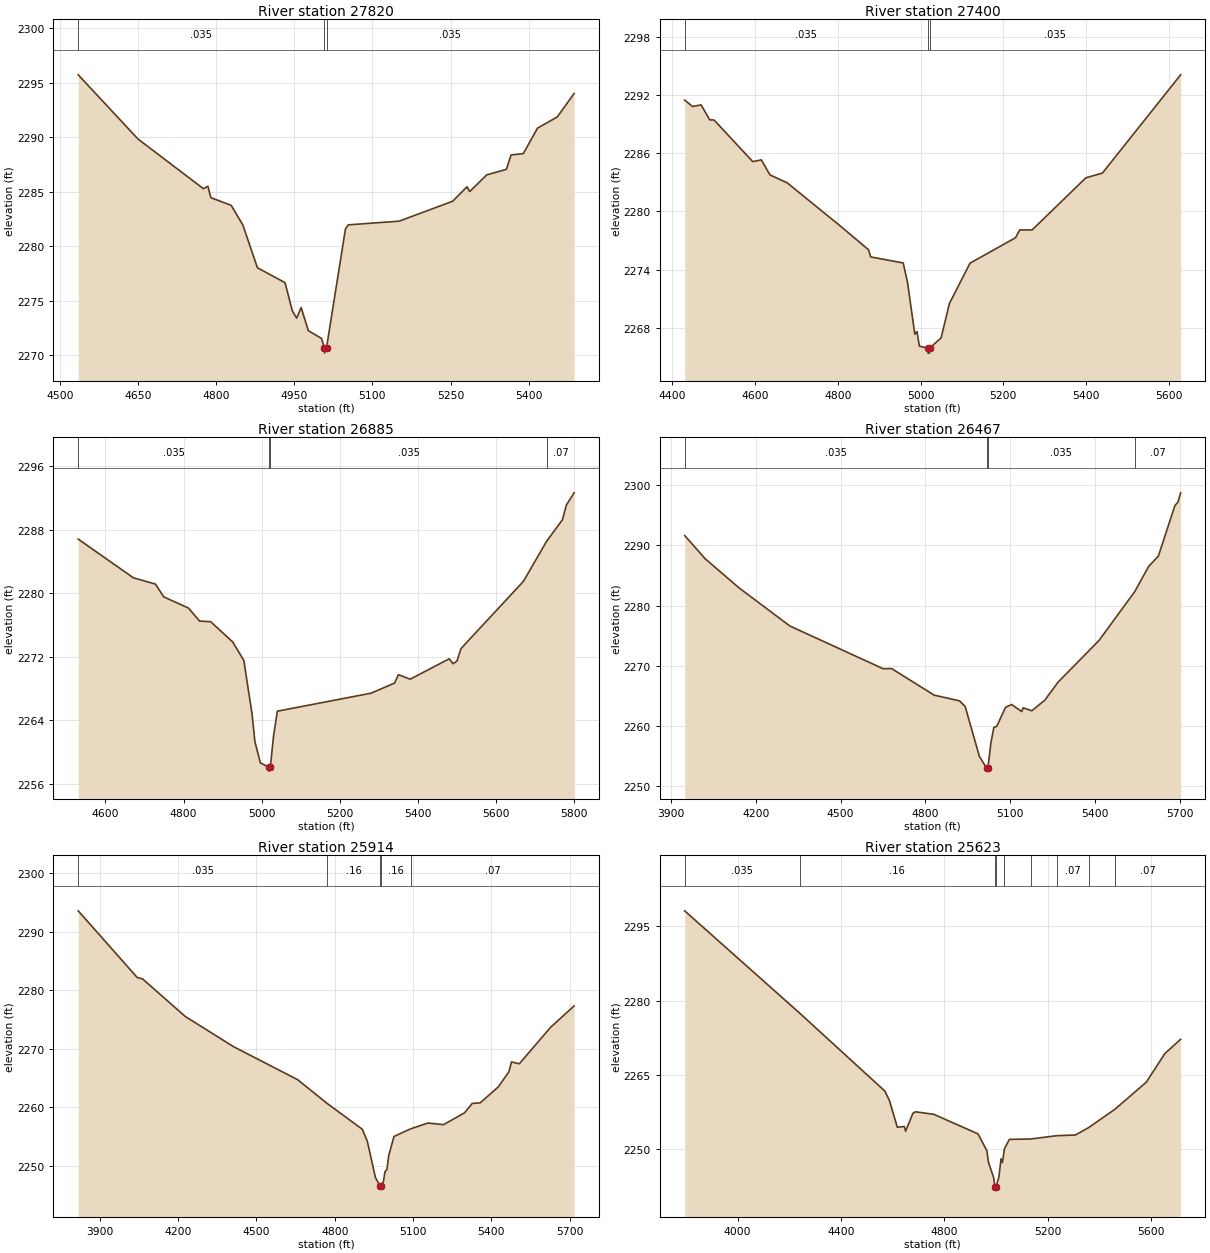
Type RM Length L Ch R = 1 ,27820   ,420,420,420
BEGIN DESCRIPTION:
MULBERRY CREEK TRIBUTARY 23 52.0
END DESCRIPTION:
XS GIS Cut Line= 3
      1458919.85      6838195.79        1458505.        6837988.
      1458039.34      6837843.32
#Sta/Elev= 30
  4535.5 2295.74  4650.3 2289.84  4775.8 2285.28  4784.4 2285.51    4790 2284.46
  4829.1 2283.75  4851.4 2281.95  4879.4 2278.02  4932.4 2276.65  4946.4 2274.05
  4954.7  2273.4  4963.2 2274.37  4977.1 2272.24  5002.1 2271.54    5008 2270.68
  5008.2 2270.18    5012 2270.68  5048.3 2281.59  5053.6 2281.96  5151.2  2282.3
  5254.1 2284.13  5281.5 2285.46  5286.7 2285.02  5319.3 2286.55  5357.1 2287.06
    5366 2288.38  5389.6 2288.51  5416.9 2290.85  5454.7 2291.87  5487.1 2294.03
#Mann= 3 ,-1 , 0
  4535.5    .035       0    5008    .035       0    5012    .035       0
Bank Sta=5008,5012
XS Rating Curve= 0 ,0
Exp/Cntr=0.3,0.1

Type RM Length L Ch R = 1 ,27400   ,515,515,515
BEGIN DESCRIPTION:
MULBERRY CREEK TRIBUTARY 23 51.0
END DESCRIPTION:
XS GIS Cut Line= 3
      1459153.31      6837826.04      1458604.73      6837669.78
      1457975.97      6837652.42
#Sta/Elev= 30
  4429.6 2291.46  4448.6  2290.8  4469.4 2290.96  4490.2 2289.42  4500.6 2289.41
  4594.2 2285.12    4615  2285.3  4635.8 2283.75  4677.4 2282.94  4806.5 2278.47
  4874.2 2276.04  4879.4  2275.3  4958.1 2274.68  4968.5 2272.68  4986.2 2267.34
  4991.4 2267.61  4997.3 2266.11  5017.7 2265.89    5018 2265.39  5021.5 2265.39
  5021.7 2265.89  5049.8 2266.96  5069.8  2270.5  5119.8 2274.66  5229.8 2277.28
  5239.8 2278.08  5269.8 2278.08  5399.9 2283.45  5439.9 2283.94    5629 2294.06
#Mann= 3 ,-1 , 0
  4429.6    .035       0  5017.7    .035       0  5021.7    .035       0
Bank Sta=5017.7,5021.7
XS Rating Curve= 0 ,0
Exp/Cntr=0.3,0.1

Type RM Length L Ch R = 1 ,26885   ,418,418,418
BEGIN DESCRIPTION:
MULBERRY CREEK TRIBUTARY 23 50.0
END DESCRIPTION:
XS GIS Cut Line= 3
      1459148.89      6837633.83      1458805.51       6837313.2
        1458005.        6837338.
#Sta/Elev= 30
  4530.2 2286.84  4671.7 2281.96  4727.9 2281.18  4749.4 2279.56  4812.9 2278.15
  4841.2 2276.51  4869.6 2276.44  4926.2 2273.87  4954.6 2271.55  4975.6 2264.81
  4982.9 2261.33  4996.9 2258.65  5018.5 2258.11  5018.8 2257.61  5022.5 2258.11
  5030.5 2261.96  5040.5 2265.16  5280.6 2267.43  5340.7  2268.7  5350.7 2269.76
  5380.7 2269.19  5480.7 2271.76  5490.7 2271.14  5500.8 2271.48  5510.8 2273.04
  5670.8 2281.51  5730.4 2286.57  5770.9 2289.28  5780.9 2291.13  5800.9 2292.67
#Mann= 4 ,-1 , 0
  4530.2    .035       0  5018.5    .035       0  5022.5    .035       0
  5730.4     .07       0
Bank Sta=5018.5,5022.5
XS Rating Curve= 0 ,0
Exp/Cntr=0.3,0.1

Type RM Length L Ch R = 1 ,26467   ,553,553,553
BEGIN DESCRIPTION:
MULBERRY CREEK TRIBUTARY 23 49.0
END DESCRIPTION:
XS GIS Cut Line= 3
      1459626.86      6837013.94      1458575.38      6837007.84
      1457895.51       6837183.1
#Sta/Elev= 30
  3948.5 2291.62  4020.4 2287.79  4140.4 2282.94  4320.4  2276.6  4650.4  2269.5
  4680.4 2269.53  4830.4 2265.12  4920.4 2264.17  4940.4 2263.23  4990.4 2254.97
    5016    2253  5016.3  2252.5  5020.6    2253  5031.4 2257.22  5041.7 2259.75
    5052 2259.94    5083  2263.1  5104.8 2263.56  5140.3 2262.39  5145.5 2263.02
  5175.8 2262.52  5221.7 2264.27  5268.9 2267.28  5413.5 2274.19  5540.2 2282.33
    5589 2286.48  5623.4  2288.2    5682 2296.61  5692.3 2297.14  5702.1 2298.71
#Mann= 4 ,-1 , 0
  3948.5    .035       0    5016    .035       0  5020.6    .035       0
  5540.2     .07       0
Bank Sta=5016,5020.6
XS Rating Curve= 0 ,0
Exp/Cntr=0.3,0.1

Type RM Length L Ch R = 1 ,25914   ,291,291,291
BEGIN DESCRIPTION:
MULBERRY CREEK TRIBUTARY 23 48.0
END DESCRIPTION:
XS GIS Cut Line= 3
      1459735.37      6836870.72      1458581.75      6836611.41
       1457865.1      6836596.83
#Sta/Elev= 30
  3817.6 2293.57  4043.5 2282.19    4064 2281.95    4228 2275.52  4412.5 2270.38
  4658.4 2264.73  4770.5  2260.7  4905.6 2256.28  4924.9 2254.21  4955.7 2248.06
  4973.8 2246.56  4974.2 2246.06  4978.5 2246.56  4986.4 2247.33  4992.2 2249.01
    5000 2249.43  5006.8  2251.8  5026.8 2255.05  5090.6 2256.35  5156.8 2257.34
  5216.8 2257.07  5296.8 2259.08  5326.8  2260.7  5356.8 2260.78  5426.8 2263.53
  5466.9  2266.1  5476.9 2267.77  5506.9 2267.46  5626.9  2273.7  5716.8 2277.34
#Mann= 5 ,-1 , 0
  3817.6    .035       0  4770.5     .16       0  4973.8     .07       0
  4978.5     .16       0  5090.6     .07       0
Bank Sta=4973.8,4978.5
XS Rating Curve= 0 ,0
Exp/Cntr=0.3,0.1

Type RM Length L Ch R = 1 ,25623   ,577,577,577
BEGIN DESCRIPTION:
MULBERRY CREEK TRIBUTARY 23 47.0
END DESCRIPTION:
XS GIS Cut Line= 3
      1459851.71       6836500.4      1458656.22      6836348.51
      1457954.96      6836488.01
#Sta/Elev= 30
  3794.9  2298.1  4240.3 2277.46  4570.2 2261.74  4587.9  2259.8  4618.2 2254.46
  4645.2 2254.61  4650.2 2253.66  4678.7 2257.29  4688.7 2257.57  4759.3 2257.07
  4930.7 2253.12  4965.1 2249.69    4971 2247.42  4991.1 2244.31  4995.7 2242.48
  4996.1 2241.98  5000.4 2242.48  5011.4 2244.41  5019.8 2248.11  5024.9 2247.34
    5033 2250.14  5052.2 2252.01  5134.6 2252.09  5236.1 2252.76  5307.1 2252.89
  5358.8 2254.38  5461.2 2258.11  5582.1 2263.55  5653.8  2269.3    5715 2272.19
#Mann= 9 ,-1 , 0
  3794.9    .035       0  4240.3     .16       0  4995.7     .07       0
  5000.4     .16       0    5033     .07       0  5134.6     .16       0
  5236.1     .07       0  5358.8     .16       0  5461.2     .07       0
Bank Sta=4995.7,5000.4
XS Rating Curve= 0 ,0
Exp/Cntr=0.3,0.1

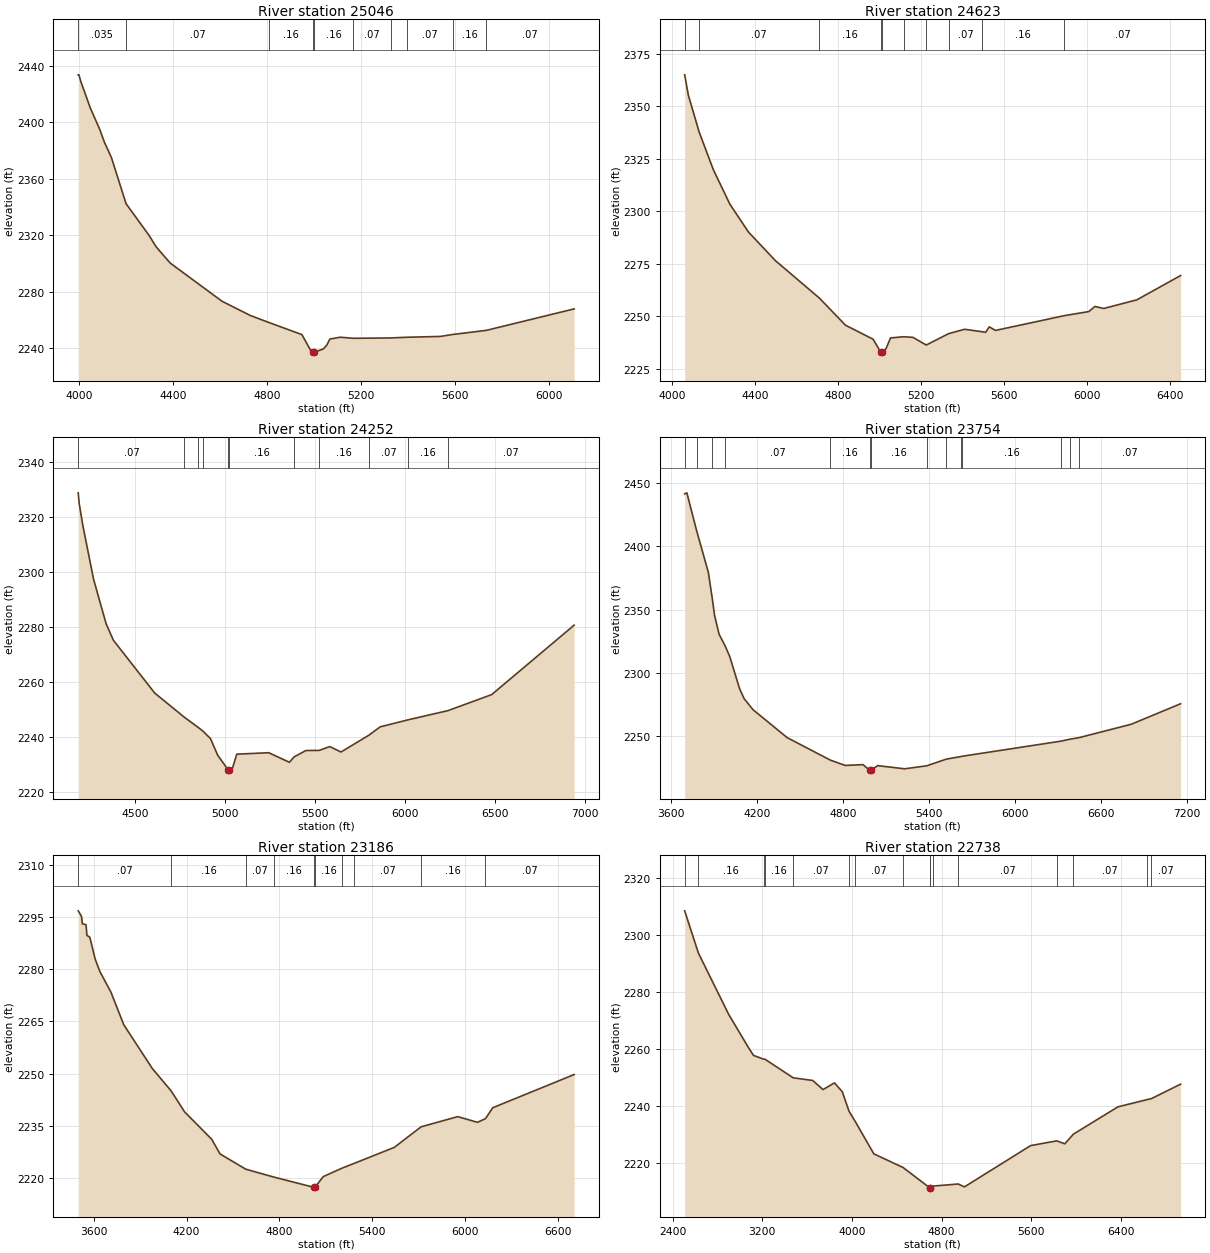
Type RM Length L Ch R = 1 ,25046   ,423,423,423
BEGIN DESCRIPTION:
MULBERRY CREEK TRIBUTARY 23 46.0
END DESCRIPTION:
XS GIS Cut Line= 3
      1459886.34      6835871.14      1458882.56      6835864.69
       1457901.6      6836373.35
#Sta/Elev= 30
  3996.2 2433.49  3999.3 2433.49  4007.5 2428.67  4047.5 2410.08  4087.5 2394.97
  4107.5 2385.82  4137.5 2374.89  4199.5 2342.29  4297.5  2319.8  4327.5  2311.7
  4387.5 2300.19  4607.6 2273.19  4727.6 2263.12  4807.2 2258.12  4947.6 2249.54
  4987.6 2237.43  4993.8 2236.94  4994.1 2236.44  4998.8 2236.94  5038.2 2239.39
  5053.6 2242.17    5066 2246.39  5110.2 2247.71  5166.7 2246.94  5324.2 2247.19
  5393.1 2247.67  5535.9 2248.26  5589.9 2249.67  5731.6 2252.56    6105 2267.76
#Mann= 10 ,-1 , 0
  3996.2    .035       0  4199.5     .07       0  4807.2     .16       0
  4993.8     .07       0  4998.8     .16       0  5166.7     .07       0
  5324.2     .16       0  5393.1     .07       0  5589.9     .16       0
  5731.6     .07       0
Bank Sta=4993.8,4998.8
XS Rating Curve= 0 ,0
Exp/Cntr=0.3,0.1

Type RM Length L Ch R = 1 ,24623   ,371,371,371
BEGIN DESCRIPTION:
MULBERRY CREEK TRIBUTARY 23 45.0
END DESCRIPTION:
XS GIS Cut Line= 3
      1459792.62      6835516.98        1458855.        6835488.
      1457512.72      6836042.57
#Sta/Elev= 30
    4062    2365  4079.6 2355.34  4131.4 2337.87  4199.7 2319.88  4279.7 2303.39
  4369.8 2290.03  4499.8  2276.4  4711.8 2258.55  4836.6  2245.7  4970.1 2238.99
  5006.8 2232.86  5007.2 2232.36  5011.9 2232.86  5032.5 2234.49  5054.2  2239.6
  5117.8 2240.17  5162.4 2239.87  5226.2 2236.22  5334.6 2241.66  5411.3 2243.72
  5495.3 2242.57  5512.4 2242.26  5530.2 2244.89  5560.2 2243.18  5892.5 2250.23
    6010 2252.17  6039.4  2254.6  6081.8 2253.64  6241.5 2257.76  6452.4 2269.34
#Mann= 10 ,-1 , 0
    4062     .16       0  4131.4     .07       0  4711.8     .16       0
  5006.8     .07       0  5011.9     .16       0  5117.8     .07       0
  5226.2     .16       0  5334.6     .07       0  5495.3     .16       0
  5892.5     .07       0
Bank Sta=5006.8,5011.9
XS Rating Curve= 0 ,0
Exp/Cntr=0.3,0.1

Type RM Length L Ch R = 1 ,24252   ,498,498,498
BEGIN DESCRIPTION:
MULBERRY CREEK TRIBUTARY 23 44.0
END DESCRIPTION:
XS GIS Cut Line= 3
      1459720.35      6835130.96      1458905.45      6835132.82
       1457140.1      6835942.57
#Sta/Elev= 30
  4185.1 2328.91  4190.4 2325.09  4210.4 2317.17  4270.4 2297.43  4340.4 2281.16
  4380.4  2275.2  4610.4 2255.92  4775.8 2247.08  4853.2 2243.34  4879.1 2242.01
  4920.4 2239.33  4960.4 2233.28  5018.2 2227.96  5018.6 2227.46  5023.3 2227.96
  5043.7 2228.73  5066.5 2233.64  5244.2 2234.17  5359.1 2230.69  5385.5 2232.66
  5451.1 2234.98  5524.4 2235.01  5583.6 2236.41  5646.1 2234.43  5800.2 2240.52
    5864  2243.6  6020.9 2246.19  6241.1 2249.52  6483.9 2255.36  6942.2 2280.67
#Mann= 11 ,-1 , 0
  4185.1     .07       0  4775.8     .16       0  4853.2     .07       0
  4879.1     .16       0  5018.2     .07       0  5023.3     .16       0
  5385.5     .07       0  5524.4     .16       0  5800.2     .07       0
  6020.9     .16       0  6241.1     .07       0
Bank Sta=5018.2,5023.3
XS Rating Curve= 0 ,0
Exp/Cntr=0.3,0.1

Type RM Length L Ch R = 1 ,23754   ,568,568,568
BEGIN DESCRIPTION:
MULBERRY CREEK TRIBUTARY 23 43.0
END DESCRIPTION:
XS GIS Cut Line= 3
      1460022.05      6835098.85      1458788.19      6834671.39
      1457004.67      6835887.02
#Sta/Elev= 30
  3694.2  2441.4  3709.5 2442.24  3776.9 2412.68    3860 2379.28  3887.1 2358.69
  3902.7 2345.75  3934.5 2330.64  3975.7 2321.71  4008.6 2313.18    4078 2287.63
  4109.1  2279.9  4171.4 2271.12  4410.1 2249.07  4712.1  2231.3    4815 2227.13
  4939.9 2227.73  4988.7 2223.13  4989.1 2222.63  4993.8 2223.13  5042.3 2226.96
  5230.7 2224.46  5384.6 2226.82  5521.3 2232.08  5625.2 2234.17  5631.5 2234.34
  6325.1 2246.33    6383 2247.78    6447 2248.99  6813.5 2259.62  7158.4 2275.81
#Mann= 14 ,-1 , 0
  3694.2     .16       0  3776.9     .07       0  3887.1     .16       0
  3975.7     .07       0  4712.1     .16       0  4988.7     .07       0
  4993.8     .16       0  5384.6     .07       0  5521.3     .16       0
  5625.2     .07       0  5631.5     .16       0  6325.1     .07       0
    6383     .16       0    6447     .07       0
Bank Sta=4988.7,4993.8
XS Rating Curve= 0 ,0
Exp/Cntr=0.3,0.1

Type RM Length L Ch R = 1 ,23186   ,448,448,448
BEGIN DESCRIPTION:
MULBERRY CREEK TRIBUTARY 23 42.0
END DESCRIPTION:
XS GIS Cut Line= 3
      1459995.14      6834752.93        1458605.        6834188.
      1457363.14      6835360.57
#Sta/Elev= 30
    3499 2296.71  3520.4 2295.11  3525.8 2292.99  3549.8 2292.74  3555.2 2289.66
  3573.9 2289.15  3608.8 2282.85  3639.5 2279.27  3710.5  2273.4  3793.5 2264.04
  3978.2 2251.47  4100.9 2244.99    4187 2239.03  4362.7 2231.14  4416.7 2226.94
  4583.1 2222.56  4765.3 2220.29    5025 2217.34  5025.4 2216.84  5030.3 2217.34
  5084.3 2220.43    5207 2222.88    5285 2224.24  5544.3 2228.83  5717.1 2234.72
  5954.5 2237.65  6081.9 2236.01  6133.8 2237.07  6181.1  2240.2  6707.5 2249.73
#Mann= 10 ,-1 , 0
    3499     .07       0  4100.9     .16       0  4583.1     .07       0
  4765.3     .16       0    5025     .07       0  5030.3     .16       0
    5207     .16       0    5285     .07       0  5717.1     .16       0
  6133.8     .07       0
Bank Sta=5025,5030.3
XS Rating Curve= 0 ,0
Exp/Cntr=0.3,0.1

Type RM Length L Ch R = 1 ,22738   ,768,768,768
BEGIN DESCRIPTION:
MULBERRY CREEK TRIBUTARY 23 41.0
END DESCRIPTION:
XS GIS Cut Line= 3
      1460910.92      6834206.91        1458455.        6833788.
      1457129.84      6835192.82
#Sta/Elev= 30
  2508.6 2308.56  2631.4 2293.68  2900.1 2272.23  3072.6  2260.8  3122.4 2257.73
  3212.4 2256.42    3225 2256.39  3476.5 2249.86  3650.8 2248.92  3742.1 2245.72
  3844.4 2248.08  3914.5 2244.95  3974.1 2238.12  4031.7 2234.37  4195.3 2223.13
    4456 2218.33    4693 2211.23  4693.4 2210.73  4698.4 2211.23  4720.5 2211.79
    4948 2212.53  5003.4 2211.52  5594.1 2226.04  5826.6  2227.7  5898.3 2226.65
  5975.4 2230.06  6372.5 2239.66  6627.5 2242.15  6669.4 2242.52  6931.2 2247.63
#Mann= 16 ,-1 , 0
  2508.6     .07       0  2631.4     .16       0  3212.4     .07       0
    3225     .16       0  3476.5     .07       0  3974.1     .16       0
  4031.7     .07       0    4456     .16       0    4693     .07       0
  4698.4     .16       0  4720.5    .045       0    4948     .07       0
  5826.6     .16       0  5975.4     .07       0  6627.5     .16       0
  6669.4     .07       0
Bank Sta=4693,4698.4
XS Rating Curve= 0 ,0
Exp/Cntr=0.3,0.1

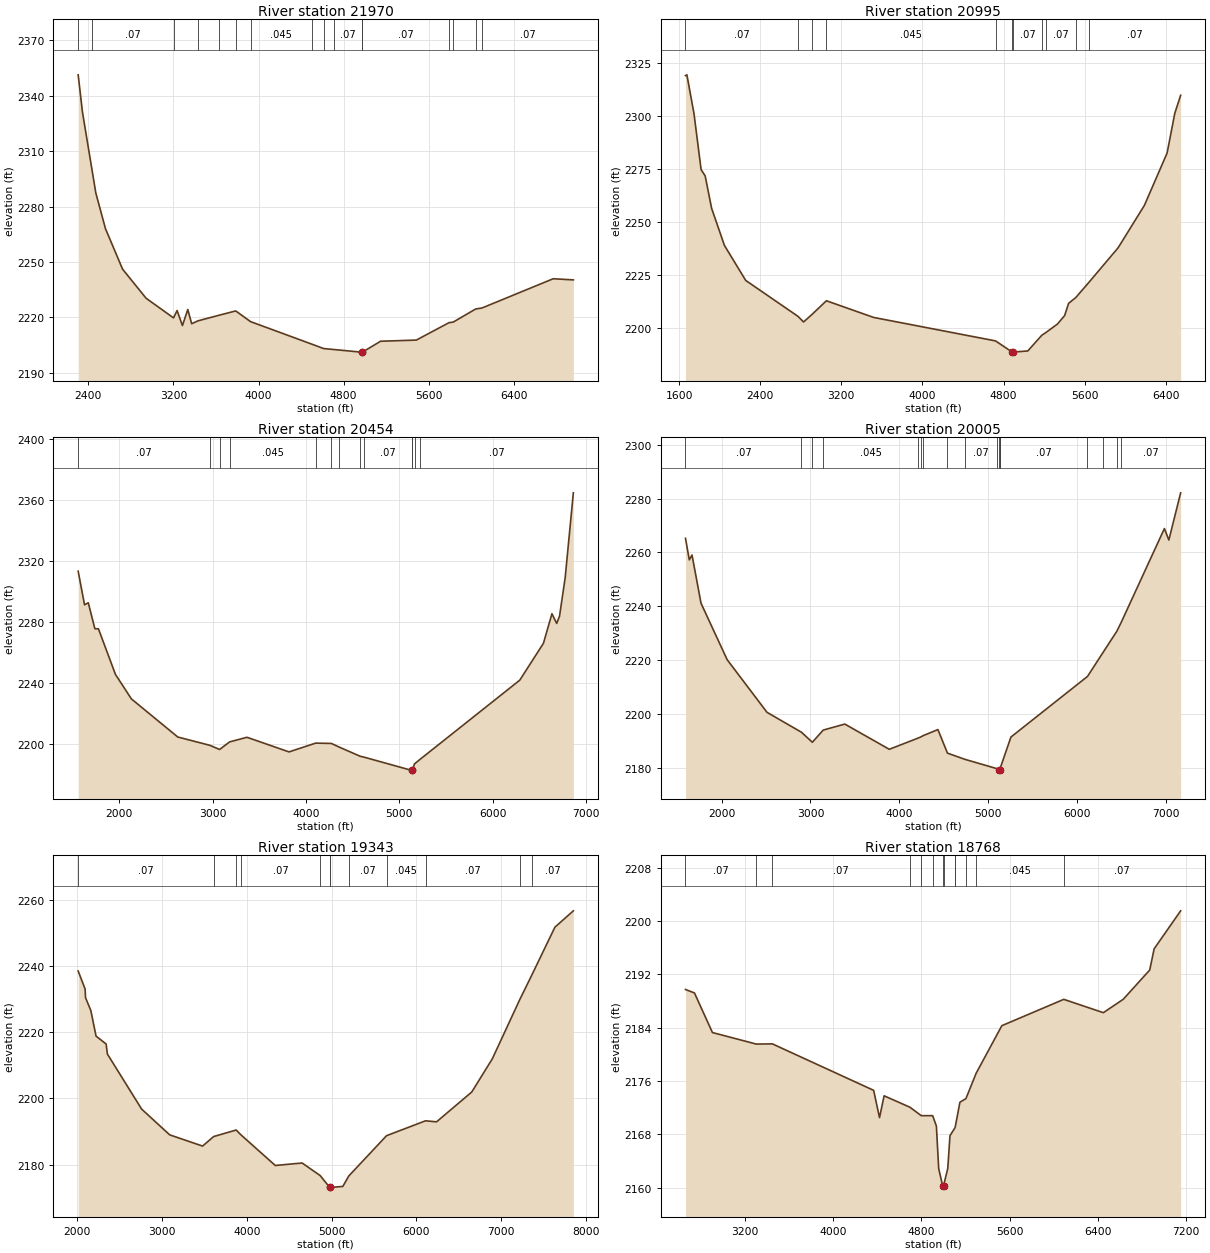
Type RM Length L Ch R = 1 ,21970   ,975,975,975
BEGIN DESCRIPTION:
MULBERRY CREEK TRIBUTARY 23 40.0
END DESCRIPTION:
XS GIS Cut Line= 3
      1460730.12      6832919.06      1458048.32      6833181.34
      1457056.71      6834870.14
#Sta/Elev= 30
  2305.4 2351.37  2345.8 2331.13  2437.9 2299.01  2471.3 2287.35  2561.7 2268.06
  2722.5  2246.1  2943.6 2230.33  3201.4 2219.68  3234.9 2223.66  3285.2 2215.52
  3335.4 2224.23  3371.9 2216.52  3431.5 2218.09    3631 2221.15    3786 2223.45
  3925.4 2217.65  4504.5 2205.38  4612.3 2203.06  4712.9 2202.52  4970.5 2201.09
  4970.9 2200.59  4975.9 2201.09  5146.9 2207.03  5483.2 2207.66  5790.9 2217.12
    5829 2217.38  6040.6  2224.5  6099.9 2225.04  6769.4 2240.89  6958.4 2240.27
#Mann= 16 ,-1 , 0
  2305.4     .16       0  2437.9     .07       0  3201.4     .16       0
  3431.5     .07       0    3631    .045       0    3786     .07       0
  3925.4    .045       0  4504.5     .07       0  4612.3     .16       0
  4712.9     .07       0  4970.5     .07       0  4975.9     .07       0
  5790.9     .16       0    5829     .07       0  6040.6     .16       0
  6099.9     .07       0
Bank Sta=4970.5,4975.9
XS Rating Curve= 0 ,0
Exp/Cntr=0.3,0.1

Type RM Length L Ch R = 1 ,20995   ,541,541,541
BEGIN DESCRIPTION:
MULBERRY CREEK TRIBUTARY 23 39.0
END DESCRIPTION:
XS GIS Cut Line= 3
      1460829.01      6832611.77      1457493.77       6832497.6
      1455959.67      6832689.84
#Sta/Elev= 30
  1662.8 2319.16  1676.8 2319.53  1746.9 2301.16  1816.9  2274.8  1856.9 2271.83
  1920.6 2256.52    2047 2239.01  2257.2 2222.48  2771.2 2205.58  2827.5 2202.88
    2913 2206.55  3052.6 2212.89  3517.9 2205.03  4720.3 2193.95  4884.9 2188.68
  4885.4 2188.18  4892.5 2188.68  5038.7  2189.2  5177.3 2196.64    5216 2197.86
  5331.3 2201.91  5401.9  2205.9  5441.4 2211.69  5512.1 2214.43  5645.6 2221.82
  5929.5 2237.91    6188 2257.86  6412.7 2282.65  6488.2 2301.35  6546.1 2309.88
#Mann= 11 ,-1 , 0
  1662.8     .07       0  2771.2     .16       0    2913     .07       0
  3052.6    .045       0  4720.3     .07       0  4884.9     .07       0
  4892.5     .07       0  5177.3     .16       0    5216     .07       0
  5512.1     .16       0  5645.6     .07       0
Bank Sta=4884.9,4892.5
XS Rating Curve= 0 ,0
Exp/Cntr=0.3,0.1

Type RM Length L Ch R = 1 ,20454   ,449,449,449
BEGIN DESCRIPTION:
MULBERRY CREEK TRIBUTARY 23 38.0
END DESCRIPTION:
XS GIS Cut Line= 3
      1461132.85      6832413.85        1457705.        6832088.
      1455868.64      6832382.38
#Sta/Elev= 30
  1561.3 2313.31  1629.5 2291.22  1669.6 2292.56  1739.9 2275.51  1778.4 2275.43
  1960.9 2245.41  2131.7 2229.33    2628 2204.29  2970.9 2198.85  3075.9  2196.1
  3183.4 2201.09  3369.5 2204.11  3819.3  2194.5  4105.1 2200.28  4273.2 2200.06
  4359.2  2197.6  4581.3 2191.64  4619.5 2191.11  5132.4 2182.36  5132.9 2181.86
  5140.1 2182.36  5163.5 2186.65  5226.7  2189.8  6290.8 2241.68    6544 2265.91
  6635.2 2285.35  6685.8 2278.97  6716.2 2283.71  6776.9 2309.06  6864.4 2364.85
#Mann= 13 ,-1 , 0
  1561.3     .07       0  2970.9     .16       0  3075.9     .07       0
  3183.4    .045       0  4105.1     .07       0  4273.2    .045       0
  4359.2     .07       0  4581.3    .045       0  4619.5     .07       0
  5132.4     .07       0  5140.1     .07       0  5163.5     .16       0
  5226.7     .07       0
Bank Sta=5132.4,5140.1
XS Rating Curve= 0 ,0
Exp/Cntr=0.3,0.1

Type RM Length L Ch R = 1 ,20005   ,662,662,662
BEGIN DESCRIPTION:
MULBERRY CREEK TRIBUTARY 23 37.0
END DESCRIPTION:
XS GIS Cut Line= 4
      1461167.62       6832268.9        1457805.        6831688.
      1457339.46      6831602.22      1455750.89       6832187.3
#Sta/Elev= 30
    1592 2265.25  1635.3 2257.24  1665.7 2259.05  1767.2 2241.12  2061.5 2220.17
  2510.4 2200.61    2899 2193.21  3021.2 2189.49  3143.8 2194.02  3387.4 2196.24
  3888.1 2186.88  4211.3 2191.02  4246.1 2191.51  4271.1 2191.97  4436.1 2194.21
  4543.3 2185.46  4738.1 2183.17    5104 2179.66  5122.6 2179.27  5123.1 2178.77
  5130.4 2179.27  5138.7 2179.94  5258.6 2191.43  6121.1 2213.94  6294.4 2222.75
    6453  2230.8  6503.7 2234.21  6987.6 2268.87  7037.8 2264.61  7170.7 2282.14
#Mann= 17 ,-1 , 0
    1592     .07       0    2899     .16       0  3021.2     .07       0
  3143.8    .045       0  4211.3     .07       0  4246.1    .045       0
  4271.1     .07       0  4543.3     .16       0  4738.1     .07       0
    5104     .16       0  5122.6     .07       0  5130.4     .16       0
  5138.7     .07       0  6121.1     .16       0  6294.4     .07       0
    6453    .035       0  6503.7     .07       0
Bank Sta=5122.6,5130.4
XS Rating Curve= 0 ,0
Exp/Cntr=0.3,0.1

Type RM Length L Ch R = 1 ,19343   ,575,575,575
BEGIN DESCRIPTION:
MULBERRY CREEK TRIBUTARY 23 35.0
END DESCRIPTION:
XS GIS Cut Line= 4
      1461259.57      6832112.63      1458356.74      6831392.19
      1457426.27      6831258.47      1455683.47      6832043.08
#Sta/Elev= 30
  2009.1 2238.44  2090.8 2233.01  2096.2 2230.36  2158.1 2226.54  2220.1 2218.78
    2339  2216.4  2353.8 2213.37  2757.8 2196.75  3088.7 2188.97  3476.9 2185.58
  3608.1 2188.46  3873.4 2190.43  3924.8 2189.08  4334.8 2179.72  4651.5 2180.47
  4864.2 2176.68  4977.2 2173.08  4977.7 2172.58  4985.1 2173.08  5131.5  2173.4
  5202.3 2176.56  5647.2 2188.71  6107.2 2193.21  6237.5  2192.9  6653.1 2201.91
  6895.5 2211.94  7218.8 2229.79  7359.7 2237.13  7633.8 2251.67  7851.3 2256.61
#Mann= 12 ,-1 , 0
  2009.1     .07       0  3608.1    .035       0  3873.4    .045       0
  3924.8     .07       0  4864.2     .16       0  4977.2     .07       0
  4985.1     .16       0  5202.3     .07       0  5647.2    .045       0
  6107.2     .07       0  7218.8    .035       0  7359.7     .07       0
Bank Sta=4977.2,4985.1
XS Rating Curve= 0 ,0
Exp/Cntr=0.3,0.1

Type RM Length L Ch R = 1 ,18768   ,622,622,622
BEGIN DESCRIPTION:
MULBERRY CREEK TRIBUTARY 23 34.0
END DESCRIPTION:
XS GIS Cut Line= 3
      1460704.48      6831749.79      1458484.64       6831007.7
      1456334.72      6831124.79
#Sta/Elev= 30
  2659.4 2189.72  2740.9  2189.2  2904.1 2183.26  3301.9 2181.53  3447.9 2181.56
    4367 2174.59  4420.3  2170.5  4461.9 2173.77  4695.8 2172.06  4799.2 2170.79
  4902.5 2170.79  4936.4 2169.23  4957.4 2162.85  4993.2 2160.27  4993.7 2159.77
  5001.1 2160.27  5039.7 2162.88  5059.7 2167.79    5105 2168.97  5109.3 2169.25
  5149.9 2172.81  5204.3 2173.34  5297.2 2177.15  5530.4 2184.29  6092.6 2188.24
  6451.8 2186.24  6632.1 2188.25  6872.4 2192.64  6912.5 2195.82  7153.1 2201.52
#Mann= 13 ,-1 , 0
  2659.4     .07       0  3301.9    .035       0  3447.9     .07       0
  4695.8     .16       0  4799.2     .07       0  4902.5     .16       0
  4993.2     .07       0  5001.1     .16       0    5105     .07       0
  5109.3    .045       0  5204.3     .07       0  5297.2    .045       0
  6092.6     .07       0
Bank Sta=4993.2,5001.1
XS Rating Curve= 0 ,0
Exp/Cntr=0.3,0.1

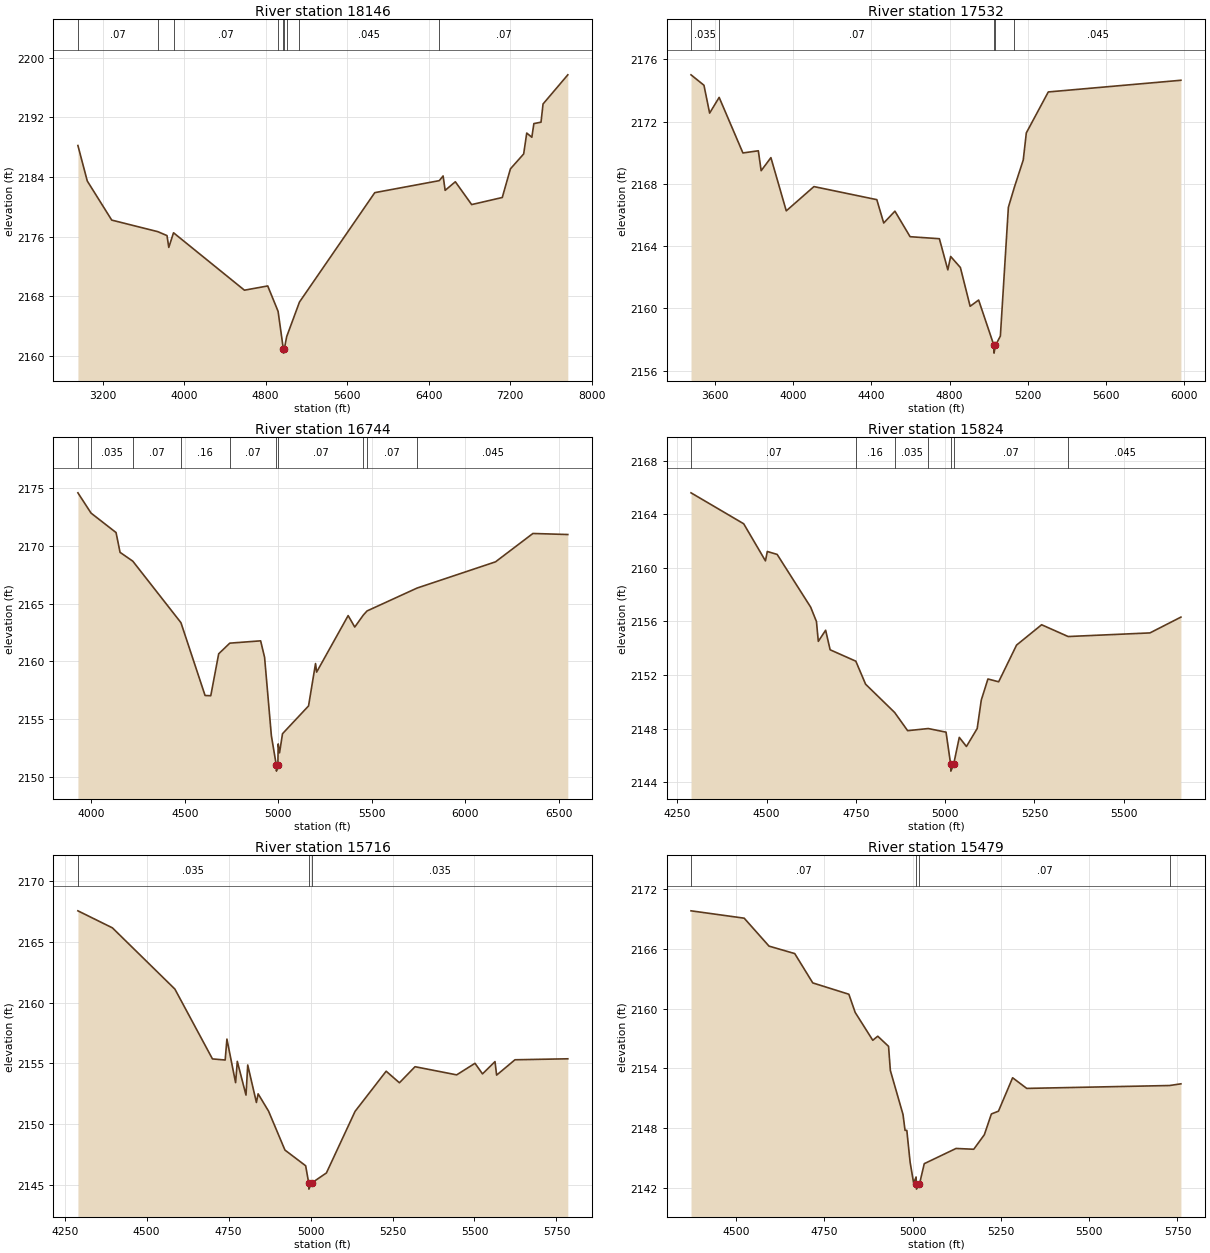
Type RM Length L Ch R = 1 ,18146   ,614,614,614
BEGIN DESCRIPTION:
MULBERRY CREEK TRIBUTARY 23 33.0
END DESCRIPTION:
XS GIS Cut Line= 3
      1460855.56      6831650.85        1459005.        6830788.
      1456242.24      6830702.96
#Sta/Elev= 30
  2958.4 2188.24  3050.4 2183.48  3290.1 2178.24  3741.8 2176.69  3832.5 2176.16
  3849.9 2174.58  3896.4 2176.54    4592 2168.84  4820.5 2169.41  4922.2    2166
  4974.2  2160.9  4974.7  2160.4  4982.2  2160.9  5006.4 2162.61  5131.9 2167.25
  5870.6 2181.92  6503.5 2183.53    6541 2184.16    6561 2182.23    6661 2183.38
  6821.1 2180.32  7121.2 2181.27  7201.3 2185.11  7331.3 2187.11  7361.4 2189.91
  7411.4 2189.35  7431.4 2191.18  7501.4 2191.37  7521.4 2193.81  7764.3 2197.72
#Mann= 9 ,-1 , 0
  2958.4     .07       0  3741.8    .035       0  3896.4     .07       0
  4922.2     .16       0  4974.2     .07       0  4982.2     .16       0
  5006.4     .07       0  5131.9    .045       0  6503.5     .07       0
Bank Sta=4974.2,4982.2
XS Rating Curve= 0 ,0
Exp/Cntr=0.3,0.1

Type RM Length L Ch R = 1 ,17532   ,788,788,788
BEGIN DESCRIPTION:
Mapping XS 89d53312
END DESCRIPTION:
XS GIS Cut Line= 3
      1460140.66      6831234.85      1458942.72      6830310.35
      1457970.51       6830110.7
#Sta/Elev= 30
  3477.6 2175.01  3543.8 2174.34  3572.8 2172.55  3621.5 2173.56  3743.1 2169.99
  3821.9 2170.13  3836.4 2168.85  3886.2 2169.69  3964.8 2166.27  4106.3 2167.83
  4427.9 2166.99  4463.2 2165.49  4520.5 2166.25  4598.1 2164.61  4747.9 2164.48
  4791.1 2162.48  4805.6 2163.34  4855.4 2162.63  4905.2 2160.14  4948.7 2160.54
  5026.8 2157.63  5027.3 2157.13  5034.9 2157.63  5059.9 2158.23  5100.8  2166.5
  5131.8  2167.8  5176.9 2169.54  5192.6 2171.28  5304.9 2173.91  5983.3 2174.66
#Mann= 5 ,-1 , 0
  3477.6    .035       0  3621.5     .07       0  5026.8     .07       0
  5034.9     .07       0  5131.8    .045       0
Bank Sta=5026.8,5034.9
XS Rating Curve= 0 ,0
Exp/Cntr=0.3,0.1

Type RM Length L Ch R = 1 ,16744   ,920,920,920
BEGIN DESCRIPTION:
Mapping XS 11cb8d87
END DESCRIPTION:
XS GIS Cut Line= 4
      1460223.11      6831200.11      1459645.85      6830292.99
      1458816.86      6829815.56      1458228.28      6829824.22
#Sta/Elev= 30
  3928.3 2174.56  3998.6 2172.81  4132.3 2171.13  4153.8 2169.42  4221.9 2168.66
  4479.4 2163.35  4608.5 2157.06    4639 2157.04  4681.3 2160.66  4740.7 2161.58
  4905.7 2161.78  4926.8 2160.36  4963.2 2153.58  4989.7 2151.03  4990.2 2150.53
  4997.8 2151.03  4999.6 2152.88  5006.9 2152.11  5022.7 2153.76    5162 2156.16
  5199.4 2159.82  5205.2 2159.08  5373.8 2163.96  5409.2 2162.97  5454.3 2163.99
  5474.8 2164.36  5742.9 2166.34    6162  2168.6  6362.1 2171.05  6548.8 2170.96
#Mann= 10 ,-1 , 0
  3928.3     .07       0  3998.6    .035       0  4221.9     .07       0
  4479.4     .16       0  4740.7     .07       0  4989.7     .07       0
  4997.8     .07       0  5454.3    .045       0  5474.8     .07       0
  5742.9    .045       0
Bank Sta=4989.7,4997.8
XS Rating Curve= 0 ,0
Exp/Cntr=0.3,0.1

Type RM Length L Ch R = 1 ,15824   ,108,108,108
BEGIN DESCRIPTION:
Mapping XS f9cfd11b
END DESCRIPTION:
XS GIS Cut Line= 3
      1460019.12      6830819.02      1460223.97      6830135.01
      1460265.64      6829478.75
#Sta/Elev= 30
  4288.4  2165.6  4435.9 2163.29  4496.8 2160.52    4502 2161.22  4529.6    2161
  4623.5 2157.06  4639.6 2155.99  4644.8 2154.51  4665.3 2155.34  4677.9 2153.88
  4749.8 2153.03  4777.2 2151.31  4858.5  2149.2  4894.9 2147.84  4952.6    2148
  5002.4 2147.73  5015.4 2145.32  5015.9 2144.82  5023.6 2145.32  5039.5 2147.34
  5059.5 2146.66  5089.6    2148  5101.1 2150.13  5119.7  2151.7  5149.7 2151.49
  5199.8 2154.23    5270 2155.75  5344.3 2154.87  5573.3 2155.14    5660 2156.32
#Mann= 7 ,-1 , 0
  4288.4     .07       0  4749.8     .16       0  4858.5    .035       0
  4952.6     .07       0  5015.4     .07       0  5023.6     .07       0
  5344.3    .045       0
Bank Sta=5015.4,5023.6
XS Rating Curve= 0 ,0
Exp/Cntr=0.3,0.1

Type RM Length L Ch R = 1 ,15716   ,237,237,237
BEGIN DESCRIPTION:
Mapping XS 16c45985
END DESCRIPTION:
XS GIS Cut Line= 3
      1460088.55      6830867.67      1460324.67      6830152.37
      1460445.93      6829421.32
#Sta/Elev= 30
  4290.4 2167.54  4395.7 2166.14  4586.2 2161.11  4700.8 2155.37  4739.6 2155.28
  4744.9    2157  4771.4 2153.42  4776.6 2155.17  4803.1  2152.4  4808.4 2154.87
  4834.9 2151.79  4840.1  2152.5  4871.9 2151.08  4921.9 2147.88  4985.1 2146.59
  4994.4 2145.17  4994.9 2144.67  5003.3 2145.17  5048.4    2146  5135.8 2151.06
  5230.6 2154.36  5271.1 2153.41  5318.7 2154.73  5445.7 2154.06  5501.6 2155.01
  5524.5 2154.14  5562.6 2155.15  5567.6 2154.04  5623.5  2155.3  5784.7 2155.38
#Mann= 3 ,-1 , 0
  4290.4    .035       0  4994.4    .035       0  5003.3    .035       0
Bank Sta=4994.4,5003.3
XS Rating Curve= 0 ,0
Exp/Cntr=0.3,0.1

Type RM Length L Ch R = 1 ,15479   ,657,657,657
BEGIN DESCRIPTION:
Mapping XS 4fda39c2
END DESCRIPTION:
XS GIS Cut Line= 3
       1460383.7      6830895.41       1460508.7      6830301.67
      1460539.89      6829521.75
#Sta/Elev= 30
  4372.5 2169.83  4523.1 2169.09  4593.4 2166.28  4666.2 2165.53  4717.3 2162.58
  4819.5 2161.44  4837.4 2159.61  4887.2 2156.81  4901.3 2157.22  4931.9  2156.2
    4937 2153.77  4972.8 2149.35  4978.6 2147.75  4983.6 2147.75  4992.9 2144.56
  5002.9 2142.45  5009.9 2143.06  5010.5 2142.34    5011 2141.84  5019.4 2142.34
    5033  2144.4    5123 2145.93  5173.1 2145.85  5203.1 2147.31  5223.1  2149.4
  5243.1 2149.68  5283.2 2153.04  5323.2 2151.97  5727.6 2152.26  5759.8 2152.43
#Mann= 4 ,-1 , 0
  4372.5     .07       0  5010.5     .07       0  5019.4     .07       0
  5727.6    .035       0
Bank Sta=5010.5,5019.4
XS Rating Curve= 0 ,0
Exp/Cntr=0.3,0.1