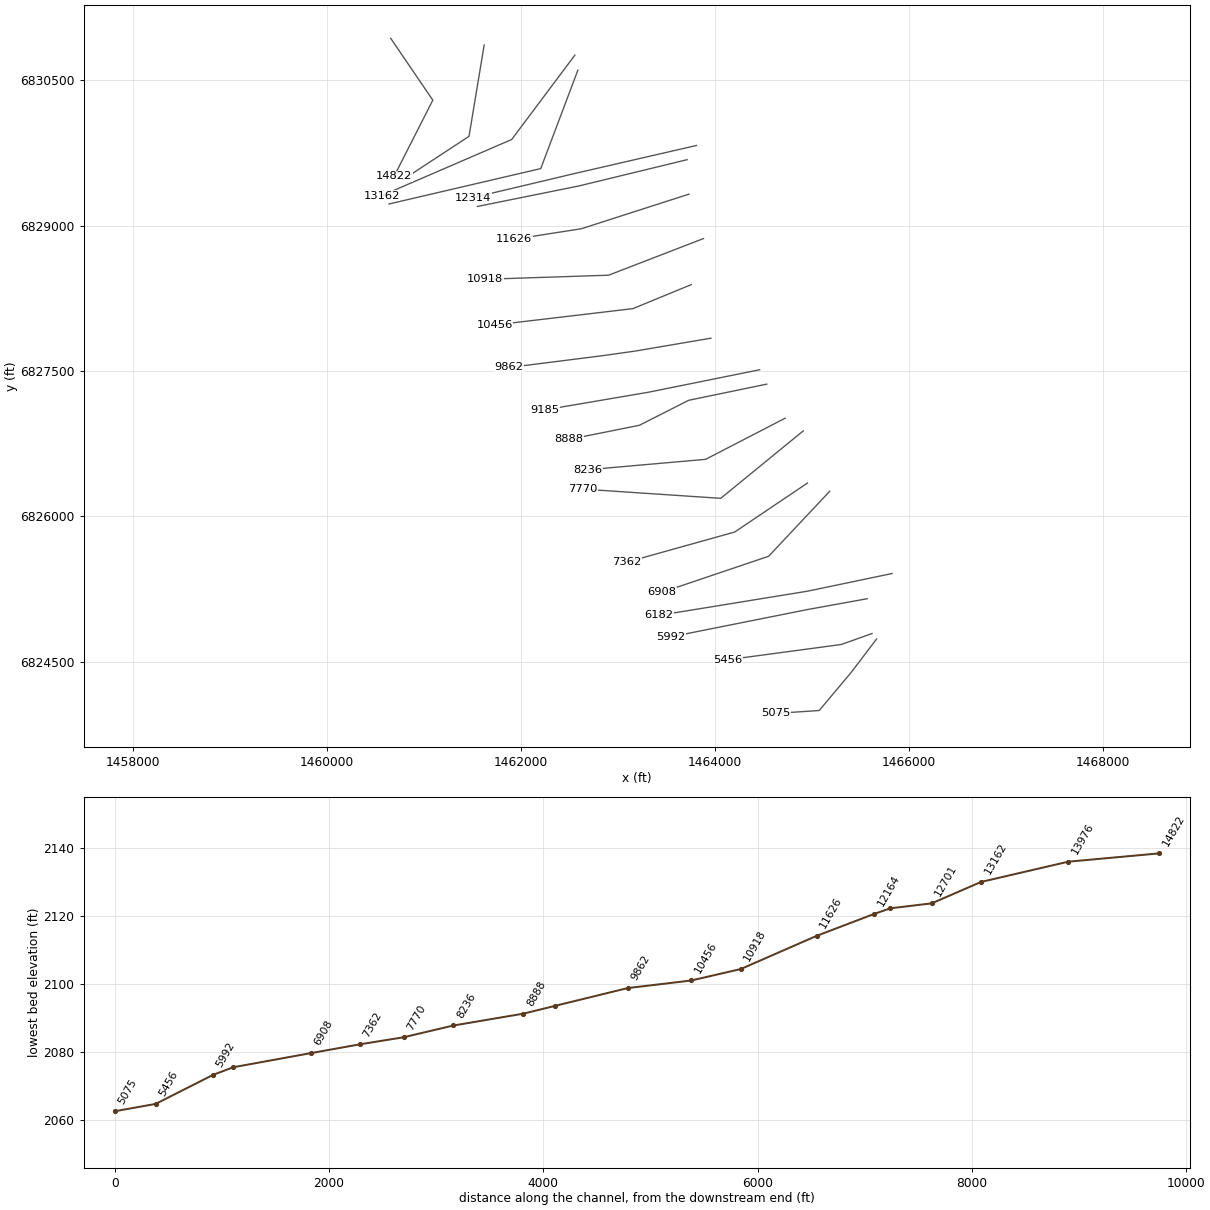
HEC-RAS study MULBERRY CREEK TRIBUTARY 23.prj: MULBERRY CREEK TRIBUTARY 23 Base Level Engineering

--- MULBERRY CREEK TRIBUTARY 23.g01 (geometry) --- (continued)

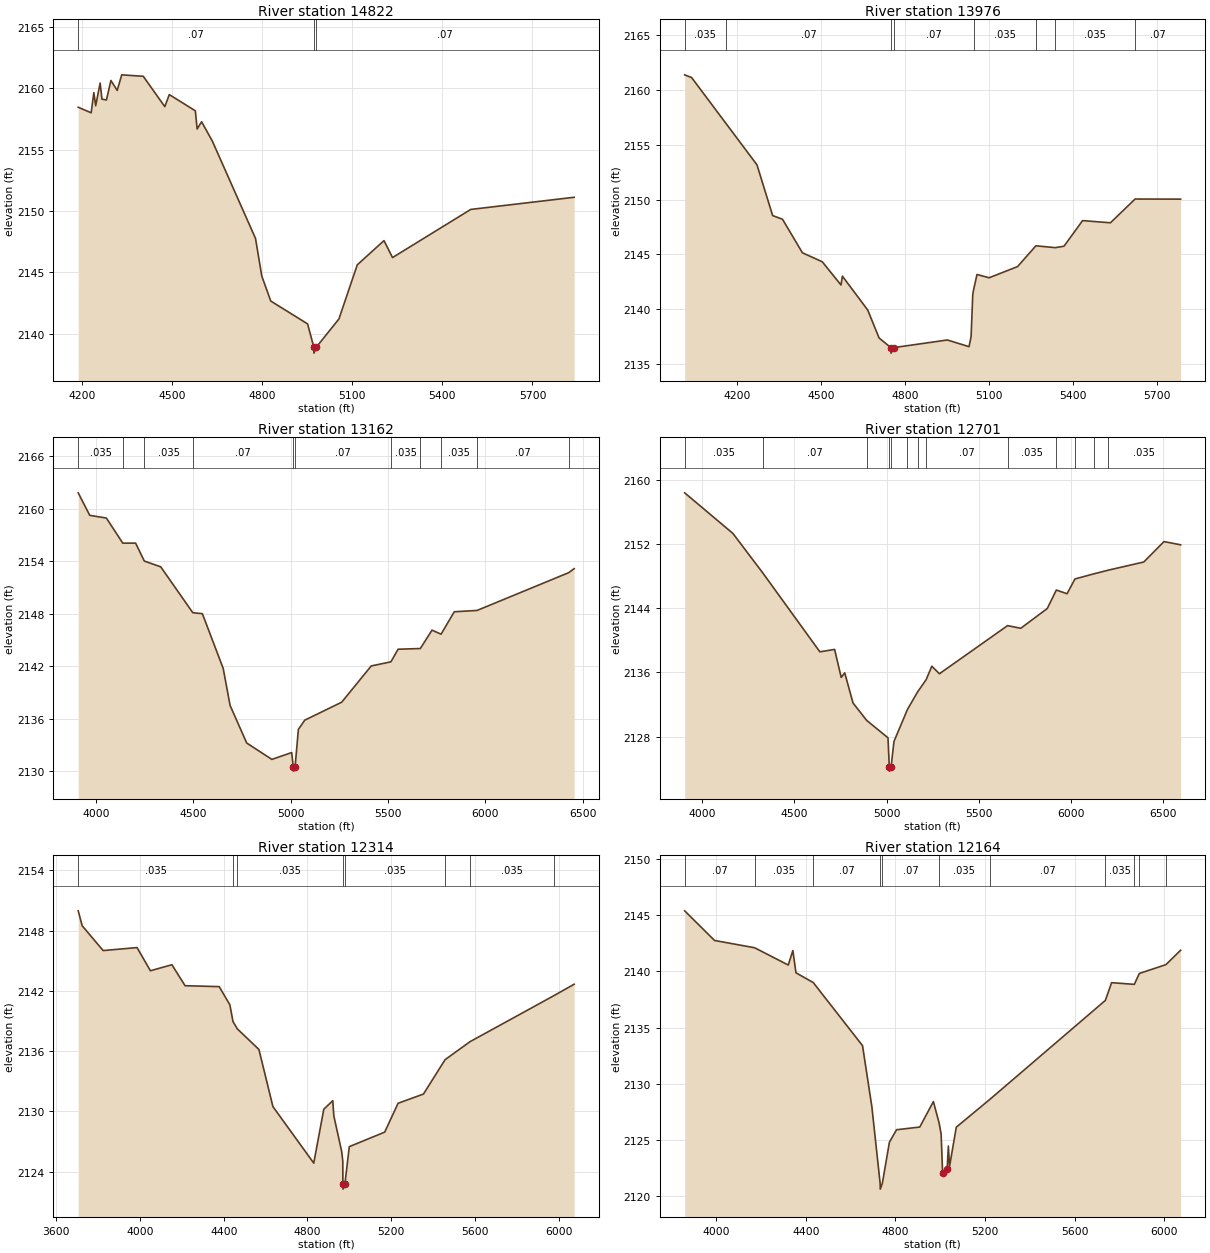
Type RM Length L Ch R = 1 ,14822   ,846,846,846
BEGIN DESCRIPTION:
Mapping XS f560ce6b
END DESCRIPTION:
XS GIS Cut Line= 3
      1460657.87      6830931.97       1461091.9      6830293.95
       1460692.6      6829508.36
#Sta/Elev= 30
  4186.1 2158.45  4229.3    2158  4238.2 2159.64  4244.3 2158.57  4259.2 2160.42
  4265.3 2159.11  4280.2 2159.04  4295.1 2160.63  4316.1 2159.82  4331.1 2161.09
  4402.9 2160.97  4474.7  2158.5  4489.7 2159.48  4576.5 2158.16  4582.5 2156.68
  4597.4 2157.27  4633.4 2155.68    4777 2147.77    4798  2144.7  4827.9 2142.67
  4950.6 2140.81  4971.2 2138.93  4971.7 2138.43  4980.1 2138.93    5055 2141.21
  5116.2 2145.62  5205.2 2147.59  5233.7 2146.21  5494.4 2150.13    5839 2151.12
#Mann= 3 ,-1 , 0
  4186.1     .07       0  4971.2     .07       0  4980.1     .07       0
Bank Sta=4971.2,4980.1
XS Rating Curve= 0 ,0
Exp/Cntr=0.3,0.1

Type RM Length L Ch R = 1 ,13976   ,814,814,814
BEGIN DESCRIPTION:
Mapping XS 09835238
END DESCRIPTION:
XS GIS Cut Line= 3
      1461621.41      6830862.49      1461465.16      6829920.68
       1460783.7      6829473.61
#Sta/Elev= 30
  4014.5  2161.4  4039.3 2161.15  4162.5 2156.94  4272.5 2153.18  4328.4 2148.55
  4363.7 2148.21  4434.7 2145.15  4505.6 2144.33  4572.3 2142.21  4577.3 2143.02
  4667.8 2139.92  4708.3 2137.37  4750.5 2136.49    4751 2135.99  4759.7 2136.49
  4951.6 2137.19  5029.2 2136.58  5036.5 2137.49  5042.5 2141.34  5045.4 2141.76
  5057.6 2143.17  5100.9 2142.87  5202.3 2143.89  5267.9 2145.79  5336.6 2145.62
    5368 2145.75  5434.4 2148.09  5533.8 2147.89  5621.8 2150.06  5784.2 2150.05
#Mann= 8 ,-1 , 0
  4014.5    .035       0  4162.5     .07       0  4750.5     .07       0
  4759.7     .07       0  5045.4    .035       0  5267.9     .07       0
  5336.6    .035       0  5621.8     .07       0
Bank Sta=4750.5,4759.7
XS Rating Curve= 0 ,0
Exp/Cntr=0.3,0.1

Type RM Length L Ch R = 1 ,13162   ,461,461,461
BEGIN DESCRIPTION:
MULBERRY CREEK TRIBUTARY 23 28.0
END DESCRIPTION:
XS GIS Cut Line= 3
      1462556.93       6830758.5        1461905.        6829888.
      1460564.74      6829308.83
#Sta/Elev= 30
  3907.9 2161.81  3967.1 2159.24  4052.6 2158.93  4136.9 2156.06  4202.6 2156.07
  4247.5 2154.02  4331.8 2153.36  4496.5 2148.12  4545.7 2148.01  4652.7 2141.76
  4688.1 2137.53  4773.5 2133.24  4902.7 2131.37  5004.5 2132.15  5012.5 2130.53
    5013 2130.03  5021.9 2130.53    5039  2134.8  5071.7 2135.85  5261.3  2137.9
  5413.1 2142.04  5514.3 2142.51    5551 2143.95  5665.4 2144.03  5725.3 2146.13
  5771.9 2145.67  5839.8 2148.23    5957 2148.38  6427.3 2152.69  6455.5 2153.15
#Mann= 11 ,-1 , 0
  3907.9    .035       0  4136.9     .07       0  4247.5    .035       0
  4496.5     .07       0  5012.5     .07       0  5021.9     .07       0
  5514.3    .035       0  5665.4     .07       0  5771.9    .035       0
    5957     .07       0  6427.3    .035       0
Bank Sta=5012.5,5021.9
XS Rating Curve= 0 ,0
Exp/Cntr=0.3,0.1

Type RM Length L Ch R = 1 ,12701   ,387,387,387
BEGIN DESCRIPTION:
MULBERRY CREEK TRIBUTARY 23 27.0
END DESCRIPTION:
XS GIS Cut Line= 3
      1462587.57      6830602.77        1462205.        6829588.
      1460640.31      6829222.95
#Sta/Elev= 30
  3904.3 2158.36  4165.9 2153.31  4328.2 2148.39  4637.9 2138.57  4717.9 2138.87
  4753.7 2135.39  4772.9 2135.95  4817.8  2132.2    4892 2130.03  5007.5 2127.87
  5014.8 2124.22  5015.3 2123.72  5024.3 2124.22  5040.1 2127.42  5113.3  2131.4
  5167.9 2133.57  5214.3 2135.09  5245.5 2136.78  5286.6 2135.84  5656.5 2141.83
  5728.1  2141.5  5871.9 2143.96  5921.1 2146.26  5979.4  2145.8  6022.1 2147.64
  6123.9 2148.27  6202.3 2148.73  6395.6 2149.75  6505.3 2152.29  6595.5 2151.89
#Mann= 13 ,-1 , 0
  3904.3    .035       0  4328.2     .07       0    4892     .16       0
  5014.8     .07       0  5024.3     .16       0  5113.3     .07       0
  5167.9    .035       0  5214.3     .07       0  5656.5    .035       0
  5921.1     .07       0  6022.1    .035       0  6123.9     .07       0
  6202.3    .035       0
Bank Sta=5014.8,5024.3
XS Rating Curve= 0 ,0
Exp/Cntr=0.3,0.1

Type RM Length L Ch R = 1 ,12314   ,150,150,150
BEGIN DESCRIPTION:
MULBERRY CREEK TRIBUTARY 23 26.0
END DESCRIPTION:
XS GIS Cut Line= 3
      1463811.01      6829826.67      1462549.36      6829536.03
      1461505.01        6829288.
#Sta/Elev= 30
  3705.3 2149.97  3724.3 2148.48  3824.4 2146.01  3986.2 2146.31  4050.1    2144
  4152.7  2144.6  4215.5 2142.51  4378.5 2142.42  4429.5 2140.61  4444.4 2138.94
  4464.8 2138.22  4568.2 2136.16    4635 2130.47    4830 2124.84    4878 2130.21
  4920.8 2131.06  4925.9 2129.54  4963.4    2126  4968.7 2125.02  4969.1 2122.75
  4969.6 2122.25  4978.7 2122.75  4999.7 2126.48  5168.9 2127.93  5232.6  2130.8
  5353.9 2131.72    5457 2135.14  5575.7 2136.93  5975.8 2141.51  6073.4 2142.66
#Mann= 8 ,-1 , 0
  3705.3    .035       0  4444.4     .07       0  4464.8    .035       0
  4969.1    .035       0  4978.7    .035       0    5457     .07       0
  5575.7    .035       0  5975.8     .07       0
#XS Ineff= 2 , 0
       0  4920.8 2131.06               0
Permanent Ineff=
       F       F
Bank Sta=4969.1,4978.7
XS Rating Curve= 0 ,0
Exp/Cntr=0.3,0.1

Type RM Length L Ch R = 1 ,12164   ,538,538,538
BEGIN DESCRIPTION:
MULBERRY CREEK TRIBUTARY 23 25.0
END DESCRIPTION:
XS GIS Cut Line= 3
      1463714.63      6829679.98       1462601.4      6829409.46
      1461552.85      6829197.43
#Sta/Elev= 30
  3858.4  2145.4  3991.8 2142.76    4171 2142.11  4321.1 2140.57  4341.7 2141.86
  4355.5 2139.88  4432.8 2139.01  4652.9 2133.39  4694.7 2127.93  4731.6 2121.11
  4732.1 2120.61  4741.2 2121.11    4773 2124.79  4804.8  2125.9  4908.6 2126.14
  4969.4 2128.41  4995.2 2126.48    5004 2125.52  5010.6 2122.04    5031 2122.44
  5036.3 2124.45  5041.4 2122.62  5071.8 2126.13  5220.8 2128.59  5737.6 2137.42
  5765.5    2139    5867 2138.85  5889.3 2139.82  6008.3 2140.61  6073.8 2141.89
#Mann= 11 ,-1 , 0
  3858.4     .07       0    4171    .035       0  4432.8     .07       0
  4731.6    .035       0  4741.2     .07       0  4995.2    .035       0
  5220.8     .07       0  5737.6    .035       0    5867     .07       0
  5889.3    .035       0  6008.3     .07       0
#XS Ineff= 2 , 0
       0  4969.4 2128.41               0
Permanent Ineff=
       F       F
Bank Sta=5010.6,5031
XS Rating Curve= 0 ,0
Exp/Cntr=0.3,0.1

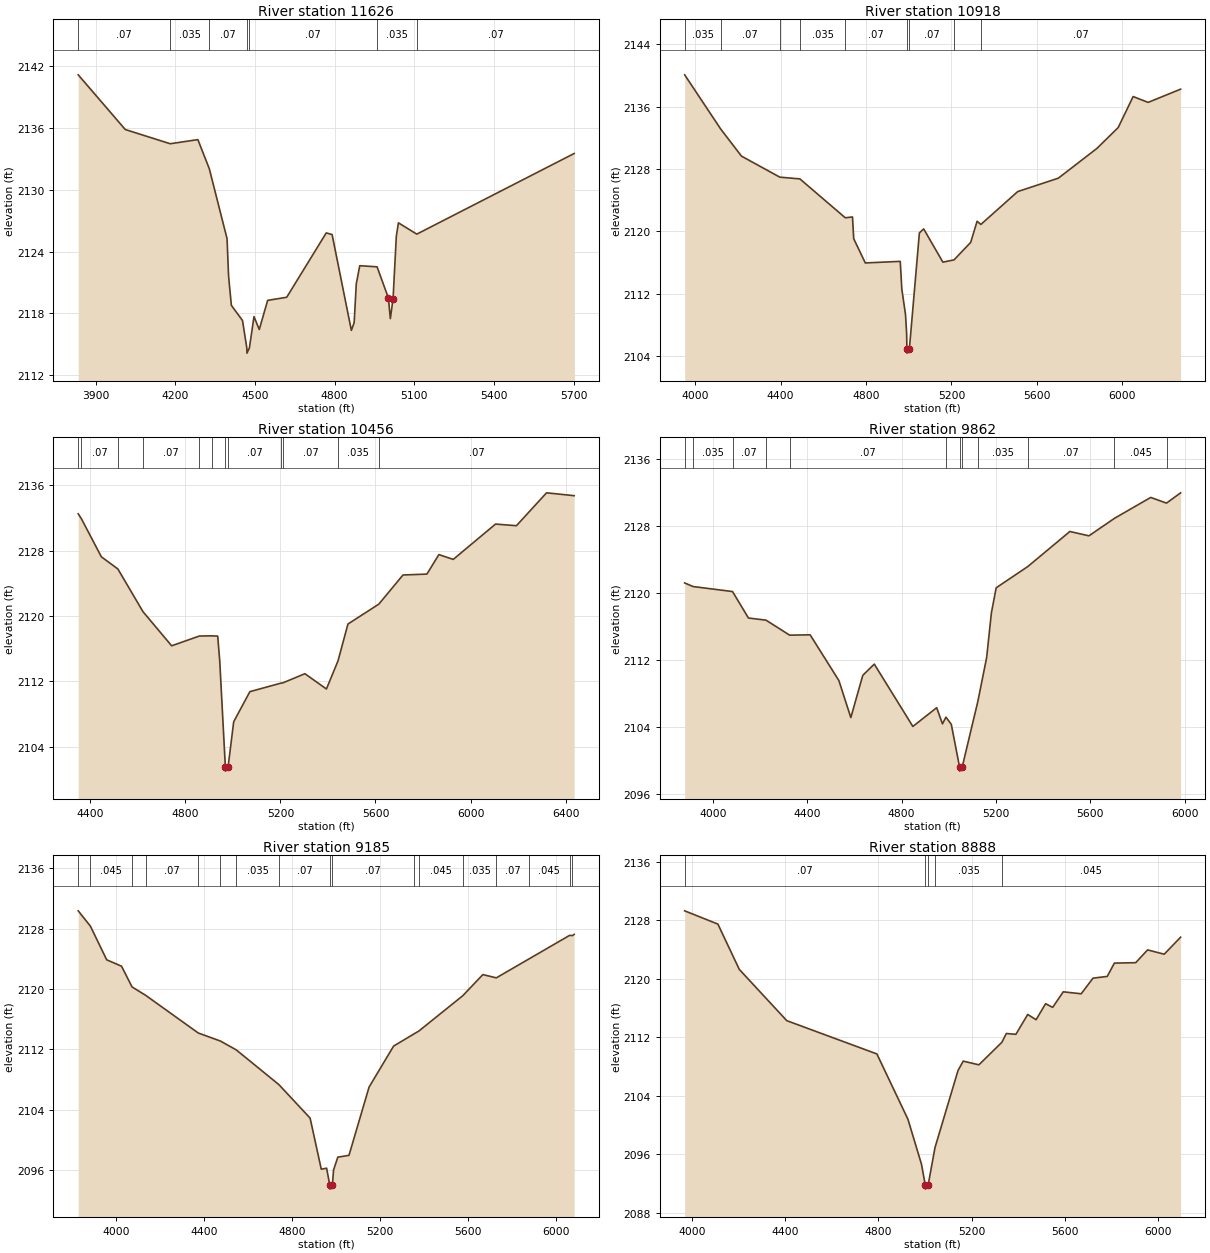
Type RM Length L Ch R = 1 ,11626   ,708,708,708
BEGIN DESCRIPTION:
MULBERRY CREEK TRIBUTARY 23 24.0
END DESCRIPTION:
XS GIS Cut Line= 3
      1463733.71      6829324.44      1462624.62      6828967.52
      1461931.54      6828859.15
#Sta/Elev= 30
  3834.9 2141.19  4012.1 2135.87  4181.2 2134.49  4285.3 2134.89  4328.3 2132.06
  4395.1 2125.26  4400.8 2121.64  4411.3 2118.78  4453.3  2117.3  4469.5 2114.63
    4470 2114.13  4479.2 2114.63  4496.5 2117.68  4516.4 2116.43  4547.9 2119.26
  4619.6 2119.56  4768.5 2125.82  4790.5 2125.66    4863 2116.34  4873.5 2117.09
  4881.5 2120.86  4894.6 2122.63  4959.8 2122.52  5002.3  2119.5  5009.7 2117.49
  5019.9 2119.41  5032.2 2125.49  5040.1  2126.8  5109.2  2125.7  5701.5 2133.54
#Mann= 7 ,-1 , 0
  3834.9     .07       0  4181.2    .035       0  4328.3     .07       0
  4469.5    .035       0  4479.2     .07       0  4959.8    .035       0
  5109.2     .07       0
#XS Ineff= 2 , 0
       0  4768.5 2125.82               0
Permanent Ineff=
       F       F
Bank Sta=5002.3,5019.9
XS Rating Curve= 0 ,0
Exp/Cntr=0.3,0.1

Type RM Length L Ch R = 1 ,10918   ,462,462,462
BEGIN DESCRIPTION:
MULBERRY CREEK TRIBUTARY 23 23.0
END DESCRIPTION:
XS GIS Cut Line= 3
      1463883.01      6828866.11        1462905.        6828488.
      1461632.96      6828445.96
#Sta/Elev= 30
  3951.4 2140.09  4119.8 2133.14  4217.3 2129.65    4397 2126.95  4490.6 2126.73
    4703 2121.74  4736.9 2121.84  4742.6 2119.05  4796.8 2115.94  4960.4 2116.14
  4967.8 2112.57    4985 2109.33  4990.3 2106.88  4991.6 2104.86  4992.1 2104.36
    5003 2104.86    5050 2119.79    5070 2120.31    5160 2116.04  5212.1 2116.33
  5290.1 2118.58  5320.1 2121.29  5337.8 2120.88  5510.2  2125.1  5700.3 2126.82
  5880.4 2130.63  5980.5 2133.32  6050.5  2137.3  6120.6 2136.55  6272.7 2138.25
#Mann= 9 ,-1 , 0
  3951.4    .035       0  4119.8     .07       0    4397    .045       0
  4490.6    .035       0    4703     .07       0  4991.6     .07       0
    5003     .07       0  5212.1    .035       0  5337.8     .07       0
Bank Sta=4991.6,5003
XS Rating Curve= 0 ,0
Exp/Cntr=0.3,0.1

Type RM Length L Ch R = 1 ,10456   ,594,594,594
BEGIN DESCRIPTION:
MULBERRY CREEK TRIBUTARY 23 22.0
END DESCRIPTION:
XS GIS Cut Line= 3
      1463757.92      6828390.99      1463155.86      6828143.08
      1461729.61      6827974.37
#Sta/Elev= 30
  4348.9 2132.53  4362.4 2131.92  4446.3 2127.26  4515.8 2125.77  4621.6 2120.53
  4742.2 2116.35    4859 2117.55  4910.5 2117.57    4936 2117.54  4944.6 2114.48
  4968.2 2101.49  4968.7 2100.99  4979.6 2101.49  5003.3 2107.04  5071.4 2110.73
  5202.9 2111.78  5209.6  2111.8    5303 2112.93  5393.6 2111.06  5442.4 2114.51
  5484.2 2119.02  5614.2 2121.46  5715.8 2125.03  5816.5 2125.14  5866.9 2127.53
  5927.3 2126.94  6105.4 2131.27  6193.3 2131.07    6320  2135.1  6436.2 2134.75
#Mann= 12 ,-1 , 0
  4348.9    .045       0  4362.4     .07       0  4515.8    .045       0
  4621.6     .07       0    4859    .035       0  4910.5     .07       0
  4968.2     .07       0  4979.6     .07       0  5202.9     .16       0
  5209.6     .07       0  5442.4    .035       0  5614.2     .07       0
Bank Sta=4968.2,4979.6
XS Rating Curve= 0 ,0
Exp/Cntr=0.3,0.1

Type RM Length L Ch R = 1 ,9862    ,677,677,677
BEGIN DESCRIPTION:
Mapping XS 41ab7e86
END DESCRIPTION:
XS GIS Cut Line= 4
      1463959.31      6827837.83      1463178.07      6827705.01
      1462847.34      6827658.14      1461879.32      6827535.84
#Sta/Elev= 30
  3880.7 2121.24  3916.2 2120.81  4083.6 2120.21    4151 2117.05  4225.7 2116.79
  4325.6    2115  4412.5 2115.04  4534.3 2109.58    4585 2105.15  4635.7  2110.2
  4684.4 2111.54  4847.9 2104.09  4948.9 2106.33  4973.4  2104.4  4988.2  2105.2
  5010.9 2104.34  5045.8 2099.25  5046.3 2098.75  5057.2 2099.25  5123.3 2107.07
  5160.7 2112.32  5180.9 2117.68  5201.1 2120.66  5335.1  2123.2  5513.5 2127.39
  5594.2 2126.87  5702.4 2128.96  5856.2 2131.46  5923.1 2130.78  5982.9 2132.01
#Mann= 12 ,-1 , 0
  3880.7     .07       0  3916.2    .035       0  4083.6     .07       0
  4225.7    .045       0  4325.6     .07       0  4988.2     .16       0
  5045.8     .07       0  5057.2     .16       0  5123.3    .035       0
  5335.1     .07       0  5702.4    .045       0  5923.1     .07       0
Bank Sta=5045.8,5057.2
XS Rating Curve= 0 ,0
Exp/Cntr=0.3,0.1

Type RM Length L Ch R = 1 ,9185    ,297,297,297
BEGIN DESCRIPTION:
Mapping XS 4366f92a
END DESCRIPTION:
XS GIS Cut Line= 3
      1464461.91       6827512.3      1463316.09      6827280.54
      1462245.83      6827098.25
#Sta/Elev= 30
  3828.9 2130.35  3884.2 2128.33  3958.4 2123.87  4025.9 2123.02  4073.6 2120.28
  4135.9 2119.16  4374.8 2114.18  4475.2 2113.12  4547.3 2111.95  4741.3 2107.35
  4883.2 2102.92  4933.9 2096.16  4958.2 2096.29  4972.8 2094.02  4973.3 2093.52
  4984.5 2094.02  4989.7 2096.05  5009.2 2097.75  5059.9 2097.99  5151.2 2107.02
  5262.8 2112.45  5354.9 2114.05  5377.1 2114.43    5577 2119.11  5668.5 2121.91
  5729.8 2121.48  5876.8 2123.96  6062.8  2127.1    6075 2127.07  6083.6 2127.23
#Mann= 17 ,-1 , 0
  3828.9     .07       0  3884.2    .045       0  4073.6    .035       0
  4135.9     .07       0  4374.8    .035       0  4475.2    .045       0
  4547.3    .035       0  4741.3     .07       0  4972.8     .07       0
  4984.5     .07       0  5354.9    .035       0  5377.1    .045       0
    5577    .035       0  5729.8     .07       0  5876.8    .045       0
  6062.8     .07       0    6075    .045       0
Bank Sta=4972.8,4984.5
XS Rating Curve= 0 ,0
Exp/Cntr=0.3,0.1

Type RM Length L Ch R = 1 ,8888    ,652,652,652
BEGIN DESCRIPTION:
Mapping XS 77eb04ee
END DESCRIPTION:
XS GIS Cut Line= 4
      1464534.89      6827363.88      1463730.16       6827197.2
      1463222.34      6826939.39      1462495.76      6826793.55
#Sta/Elev= 30
  3966.7 2129.32  4109.6  2127.5  4201.5  2121.3  4405.7 2114.28  4793.2 2109.72
  4926.8 2100.77    4985 2094.61  5001.5 2091.71    5002 2091.21  5013.2 2091.71
  5043.1 2096.91    5142 2107.45  5164.4 2108.74  5231.7 2108.23  5330.6 2111.32
  5349.7 2112.52  5390.8 2112.41  5441.7 2115.13  5477.7 2114.41  5518.5  2116.6
  5549.1  2116.1  5594.4 2118.23  5671.5 2117.96  5722.5  2120.1  5783.7 2120.34
  5814.3 2122.16  5906.1 2122.22  5957.1 2123.97  6028.5 2123.38  6099.1 2125.71
#Mann= 5 ,-1 , 0
  3966.7     .07       0  5001.5     .07       0  5013.2     .07       0
  5043.1    .035       0  5330.6    .045       0
Bank Sta=5001.5,5013.2
XS Rating Curve= 0 ,0
Exp/Cntr=0.3,0.1

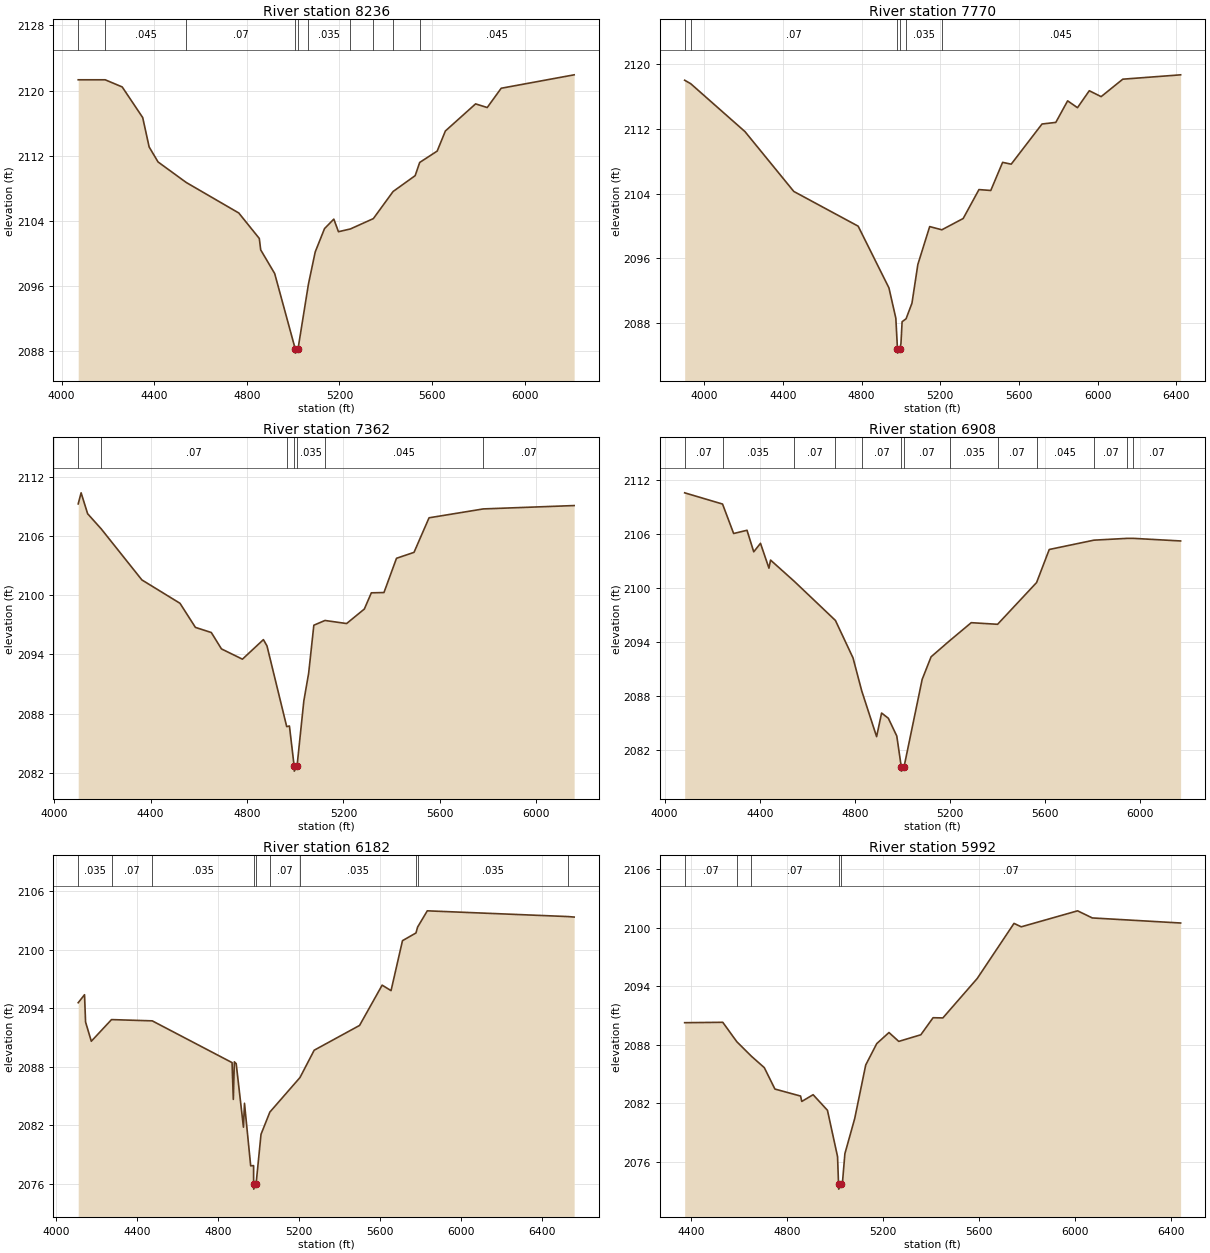
Type RM Length L Ch R = 1 ,8236    ,466,466,466
BEGIN DESCRIPTION:
MULBERRY CREEK TRIBUTARY 23 17.0
END DESCRIPTION:
XS GIS Cut Line= 3
      1464724.91      6827012.28        1463905.        6826588.
      1462691.08      6826481.06
#Sta/Elev= 30
    4072 2121.32  4188.5 2121.32    4262 2120.44  4350.5 2116.68  4378.3 2113.07
  4416.9 2111.22  4538.6  2108.7  4765.5 2104.95  4854.1 2101.82  4860.1 2100.42
  4920.5 2097.51  5009.4 2088.23  5009.9 2087.73  5021.2 2088.23  5066.4 2096.23
  5095.6 2100.17  5135.7 2103.03  5175.9  2104.2    5196 2102.65  5247.5 2102.99
  5346.6 2104.26  5431.8 2107.59  5527.2 2109.54  5546.7 2111.16  5622.3 2112.56
  5657.7 2115.03  5788.2 2118.36  5838.4 2117.91  5898.7 2120.28  6213.8 2121.93
#Mann= 10 ,-1 , 0
    4072     .07       0  4188.5    .045       0  4538.6     .07       0
  5009.4     .07       0  5021.2     .07       0  5066.4    .035       0
  5247.5     .07       0  5346.6    .045       0  5431.8     .07       0
  5546.7    .045       0
Bank Sta=5009.4,5021.2
XS Rating Curve= 0 ,0
Exp/Cntr=0.3,0.1

Type RM Length L Ch R = 1 ,7770    ,408,408,408
BEGIN DESCRIPTION:
MULBERRY CREEK TRIBUTARY 23 16.0
END DESCRIPTION:
XS GIS Cut Line= 3
      1464912.43      6826882.08      1464060.81      6826185.69
      1462641.57      6826280.54
#Sta/Elev= 30
  3899.9 2118.05  3930.7 2117.62  4206.6 2111.69  4454.9 2104.28  4782.3 2099.98
  4938.8 2092.34  4973.9 2088.59  4982.3 2084.76  4982.8 2084.26  4994.2 2084.76
    5000 2085.46  5005.8 2088.15  5025.9 2088.51  5055.9 2090.44    5086 2095.25
  5146.1 2099.93  5207.9 2099.53  5316.5 2100.93  5396.7 2104.51  5456.8  2104.4
    5517 2107.88  5560.8 2107.66  5717.4 2112.63  5787.6 2112.83  5847.7  2115.5
  5897.8 2114.65  5957.9 2116.75  6018.1 2116.02  6128.3 2118.18  6422.4 2118.72
#Mann= 6 ,-1 , 0
  3899.9    .035       0  3930.7     .07       0  4982.3     .07       0
  4994.2     .07       0  5025.9    .035       0  5207.9    .045       0
Bank Sta=4982.3,4994.2
XS Rating Curve= 0 ,0
Exp/Cntr=0.3,0.1

Type RM Length L Ch R = 1 ,7362    ,454,454,454
BEGIN DESCRIPTION:
MULBERRY CREEK TRIBUTARY 23 15.0
END DESCRIPTION:
XS GIS Cut Line= 3
      1464955.02      6826343.06        1464205.        6825838.
      1463095.64      6825527.94
#Sta/Elev= 30
  4100.2 2109.25  4112.2 2110.37  4139.3 2108.25  4195.8 2106.71  4364.1 2101.55
  4522.2 2099.18  4586.1 2096.74    4652 2096.22  4694.1 2094.56    4781 2093.52
    4868  2095.5  4882.9 2094.86  4964.6 2086.69  4975.9 2086.75  4995.5 2082.68
    4996 2082.18  5007.4 2082.68  5035.6 2089.29  5055.6  2092.1  5077.1 2096.96
  5123.2 2097.44    5213 2097.13  5286.5  2098.6  5315.5 2100.24  5367.8 2100.27
  5419.8 2103.74  5492.4 2104.34  5554.7 2107.84  5779.9 2108.74  6156.3 2109.08
#Mann= 7 ,-1 , 0
  4100.2    .035       0  4195.8     .07       0  4964.6    .035       0
  4995.5    .035       0  5007.4    .035       0  5123.2    .045       0
  5779.9     .07       0
Bank Sta=4995.5,5007.4
XS Rating Curve= 0 ,0
Exp/Cntr=0.3,0.1

Type RM Length L Ch R = 1 ,6908    ,726,726,726
BEGIN DESCRIPTION:
MULBERRY CREEK TRIBUTARY 23 14.0
END DESCRIPTION:
XS GIS Cut Line= 3
      1465185.05      6826258.87        1464555.        6825588.
      1463450.67      6825214.57
#Sta/Elev= 30
  4084.2  2110.6  4243.5 2109.35  4290.2 2106.07  4346.4 2106.43  4374.7 2104.03
  4403.1 2104.98  4438.7 2102.21  4445.5 2103.11    4545 2100.75  4718.3 2096.39
  4792.3 2092.22  4828.9 2088.55  4891.5 2083.45  4912.5 2086.08  4940.8  2085.5
  4976.4 2083.52  4995.2 2080.11  4995.7 2079.61  5007.1 2080.11  5083.1 2089.82
  5120.7 2092.34  5198.3 2094.12  5289.6 2096.14  5400.4 2095.96  5564.5 2100.61
  5617.7 2104.29  5805.9 2105.33    5946 2105.53  5971.4 2105.53  6170.3 2105.24
#Mann= 13 ,-1 , 0
  4084.2     .07       0  4243.5    .035       0    4545     .07       0
  4718.3     .16       0  4828.9     .07       0  4995.2     .07       0
  5007.1     .07       0  5198.3    .035       0  5400.4     .07       0
  5564.5    .045       0  5805.9     .07       0    5946    .045       0
  5971.4     .07       0
Bank Sta=4995.2,5007.1
XS Rating Curve= 0 ,0
Exp/Cntr=0.3,0.1

Type RM Length L Ch R = 1 ,6182    ,190,190,190
BEGIN DESCRIPTION:
MULBERRY CREEK TRIBUTARY 23 13.0
END DESCRIPTION:
XS GIS Cut Line= 3
      1465828.21      6825409.87      1464956.06      6825227.57
      1463419.66      6824977.63
#Sta/Elev= 30
    4109 2094.55  4140.2 2095.37  4145.3 2092.57  4173.6  2090.6  4273.4 2092.82
  4474.5 2092.69  4868.3 2088.41  4874.5 2084.64  4879.6 2088.49  4888.7  2088.3
  4924.5 2081.79  4929.6 2084.24  4960.2 2077.83  4974.5 2077.85  4974.7 2075.94
  4975.2 2075.44  4986.7 2075.94  5011.2 2081.06  5054.9 2083.34  5203.5 2086.88
  5273.6 2089.68  5497.5 2092.22    5609 2096.35  5652.9 2095.79  5709.4 2100.91
  5775.9  2101.7  5783.9  2102.3  5831.9 2103.97  6527.2 2103.38  6556.6 2103.33
#Mann= 10 ,-1 , 0
    4109    .035       0  4273.4     .07       0  4474.5    .035       0
  4974.7    .035       0  4986.7    .035       0  5054.9     .07       0
  5203.5    .035       0  5775.9    .045       0  5783.9    .035       0
  6527.2     .07       0
Bank Sta=4974.7,4986.7
XS Rating Curve= 0 ,0
Exp/Cntr=0.3,0.1

Type RM Length L Ch R = 1 ,5992    ,536,536,536
BEGIN DESCRIPTION:
MULBERRY CREEK TRIBUTARY 23 12.0
END DESCRIPTION:
XS GIS Cut Line= 3
      1465571.09      6825149.85        1464955.        6825038.
      1463544.43      6824756.24
#Sta/Elev= 30
  4373.4 2090.27    4532 2090.31  4590.4 2088.32  4651.1 2086.83  4704.8 2085.66
  4749.1 2083.46  4855.9 2082.74    4861 2082.19  4908.1 2082.88  4967.8 2081.28
  5009.8 2076.53    5014 2073.69  5014.5 2073.19    5026 2073.69  5030.2 2073.85
  5040.4 2076.83  5081.2 2080.43  5127.1 2085.93  5172.9 2088.12  5223.9 2089.26
  5264.7 2088.35  5356.5 2089.03  5407.5 2090.78  5448.3 2090.76  5591.4 2094.81
  5744.4 2100.46  5774.6 2100.11  6009.1 2101.75  6070.3 2101.02    6438  2100.5
#Mann= 5 ,-1 , 0
  4373.4     .07       0  4590.4     .16       0  4651.1     .07       0
    5014     .07       0    5026     .07       0
Bank Sta=5014,5026
XS Rating Curve= 0 ,0
Exp/Cntr=0.3,0.1

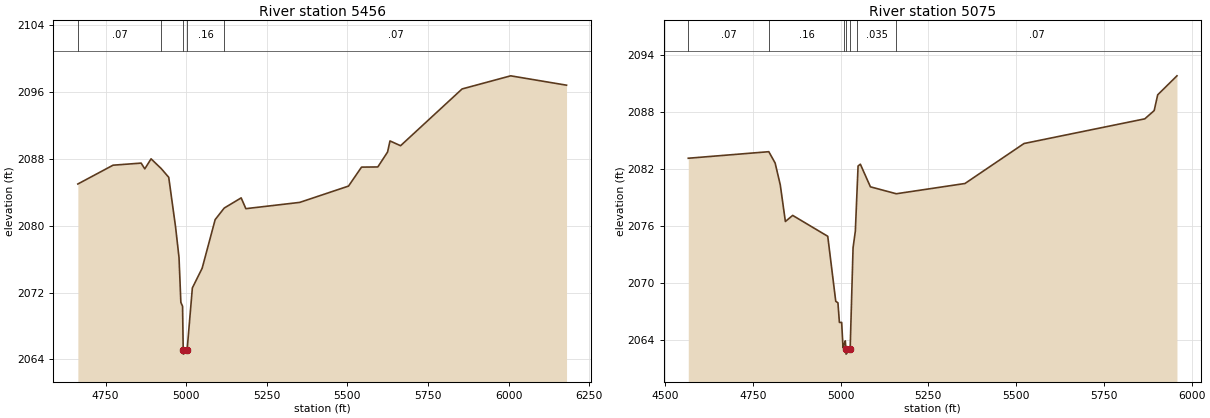
Type RM Length L Ch R = 1 ,5456    ,381,381,381
BEGIN DESCRIPTION:
MULBERRY CREEK TRIBUTARY 23 11.0
END DESCRIPTION:
XS GIS Cut Line= 3
      1465620.52      6824790.47      1465303.95      6824677.57
      1464134.77      6824520.38
#Sta/Elev= 30
  4663.9 2084.98    4773 2087.23  4860.2 2087.48  4871.5 2086.79    4891 2087.99
  4922.6 2086.82  4945.8 2085.78    4967 2079.84  4977.7 2076.19  4983.4 2070.83
  4988.7 2070.35  4990.7 2065.13  4991.2 2064.63  5002.8 2065.13  5019.1 2072.55
  5049.4  2074.9  5089.8 2080.72  5117.8  2082.1  5170.5 2083.32    5185 2082.03
  5352.1 2082.78  5503.4 2084.73  5543.8    2087  5594.3 2087.02  5624.5  2088.8
  5632.1 2090.13  5664.9 2089.56  5855.7 2096.35  6006.4 2097.92  6179.7  2096.8
#Mann= 5 ,-1 , 0
  4663.9     .07       0  4922.6     .16       0  4990.7     .07       0
  5002.8     .16       0  5117.8     .07       0
Bank Sta=4990.7,5002.8
XS Rating Curve= 0 ,0
Exp/Cntr=0.3,0.1

Type RM Length L Ch R = 1 ,5075    ,541,541,541
BEGIN DESCRIPTION:
MULBERRY CREEK TRIBUTARY 23 10.0
END DESCRIPTION:
XS GIS Cut Line= 4
      1465667.42      6824733.18        1465405.        6824388.
      1465076.44      6823996.36      1464630.23      6823966.84
#Sta/Elev= 30
  4566.2  2083.1  4795.6 2083.79  4813.7 2082.59  4828.3 2080.29  4842.8 2076.44
  4863.6 2077.08  4963.5 2074.88  4986.3 2068.03  4992.5 2067.88  4996.7 2065.81
  5003.1 2065.81    5007 2063.16  5009.8 2063.47  5013.5 2063.87  5015.2 2062.97
  5015.7 2062.47  5027.3 2062.97  5035.6 2073.67  5042.1 2075.43  5048.1 2080.71
  5049.9 2082.29  5056.4 2082.47    5085 2080.09  5158.7 2079.36  5354.3 2080.44
  5522.5 2084.65  5866.6 2087.25  5893.3 2088.12  5903.3 2089.78  5958.2 2091.78
#Mann= 7 ,-1 , 0
  4566.2     .07       0  4795.6     .16       0  5009.8     .07       0
  5015.2     .07       0  5027.3     .07       0  5048.1    .035       0
  5158.7     .07       0
Bank Sta=5015.2,5027.3
XS Rating Curve= 0 ,0
Exp/Cntr=0.3,0.1