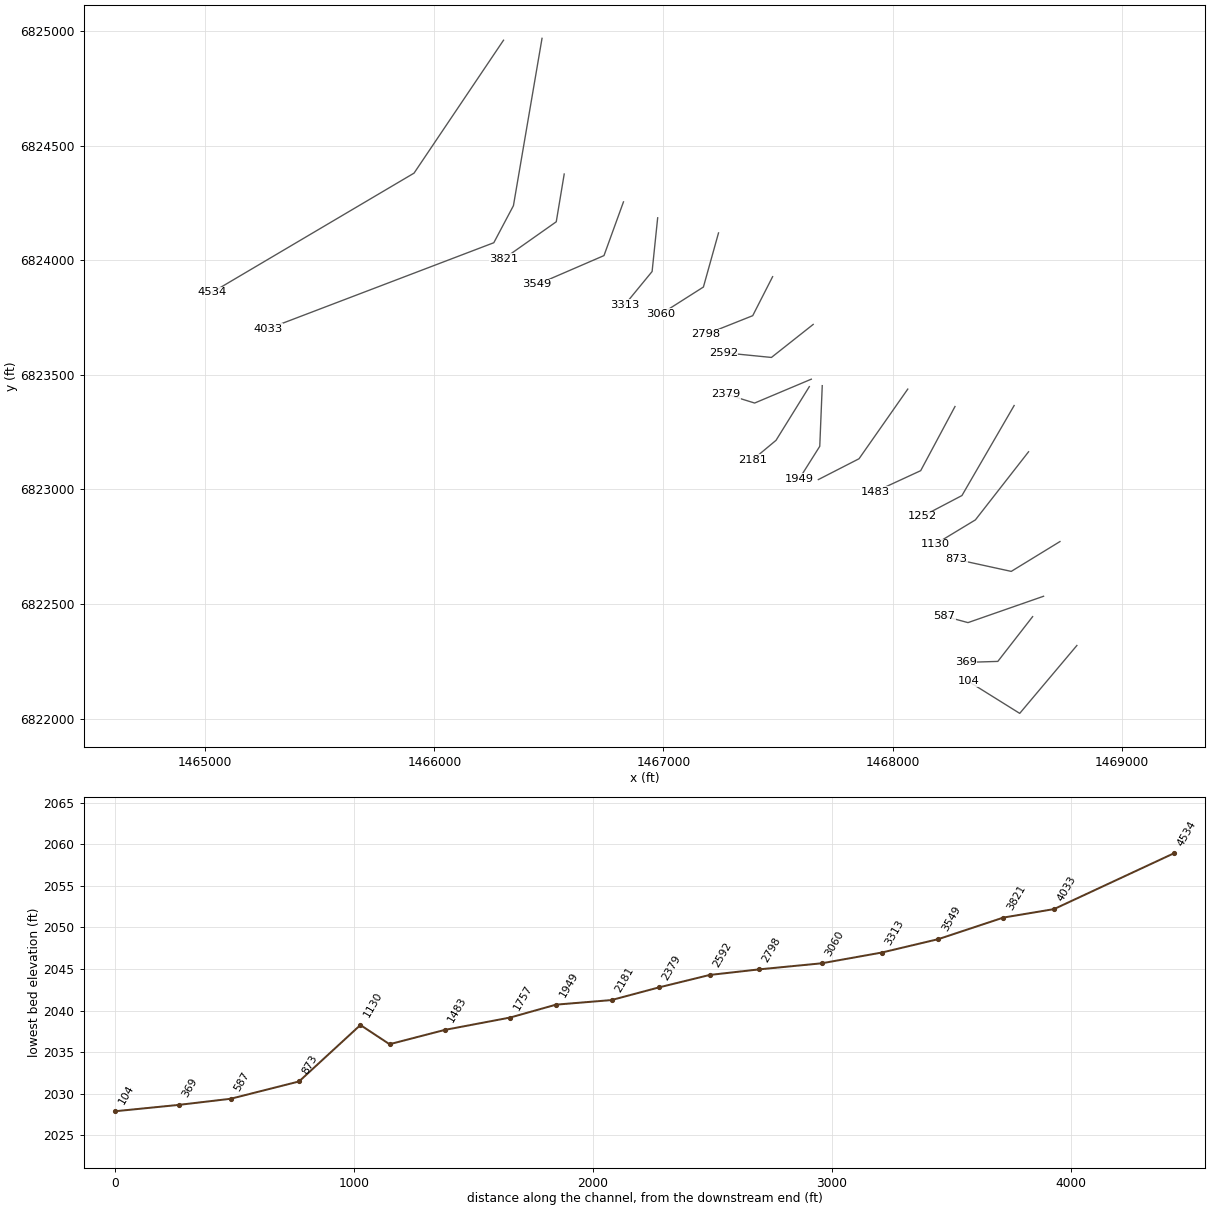
HEC-RAS study MULBERRY CREEK TRIBUTARY 23.prj: MULBERRY CREEK TRIBUTARY 23 Base Level Engineering

--- MULBERRY CREEK TRIBUTARY 23.g01 (geometry) --- (continued)

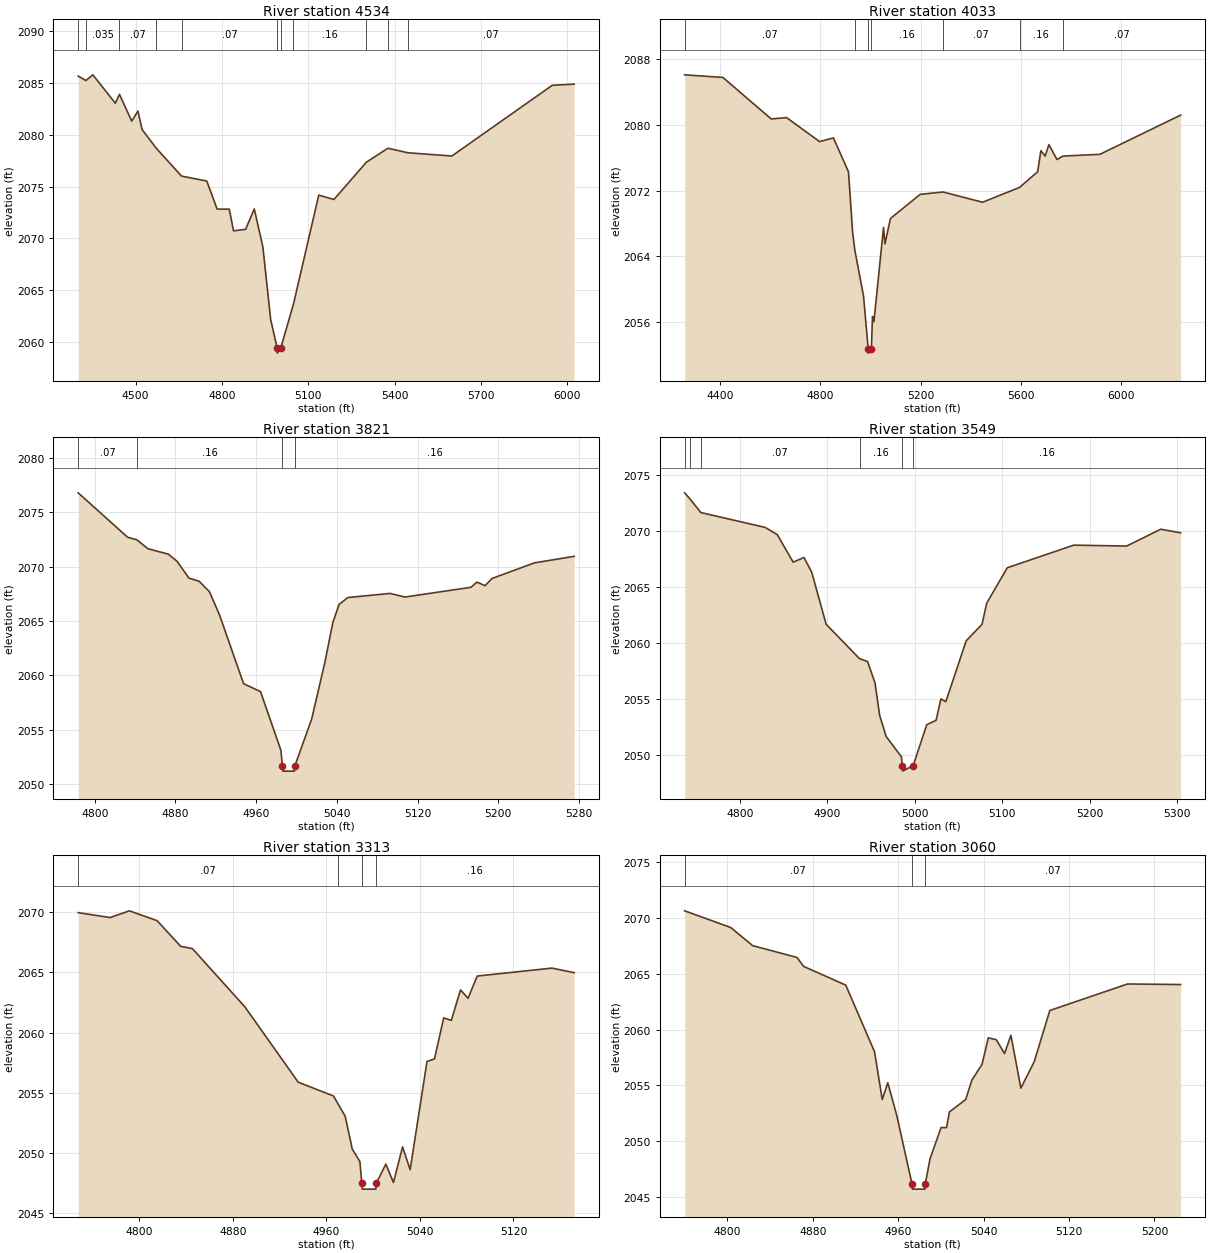
Type RM Length L Ch R = 1 ,4534    ,501,501,501
BEGIN DESCRIPTION:
MULBERRY CREEK TRIBUTARY 23 9.0
END DESCRIPTION:
XS GIS Cut Line= 3
       1466301.8      6824960.21      1465911.19      6824380.17
      1465029.63      6823859.76
#Sta/Elev= 30
  4300.7 2085.67  4327.5 2085.24  4351.6 2085.79  4429.6 2083.05    4444 2083.91
  4486.6 2081.32  4508.3 2082.29  4522.6 2080.51  4572.2 2078.69  4659.6 2076.01
  4747.4 2075.53  4783.4 2072.82  4825.4 2072.82  4840.4 2070.72  4882.4 2070.87
  4912.4 2072.84  4942.3 2069.16  4969.4 2062.14    4992 2059.41  4992.5 2058.91
  5004.5 2059.41  5048.5 2063.64  5136.4 2074.17  5189.2 2073.75  5302.2 2077.36
  5376.7  2078.7  5446.5 2078.26  5598.9 2077.95  5947.8 2084.78  6023.7 2084.89
#Mann= 11 ,-1 , 0
  4300.7     .07       0  4327.5    .035       0    4444     .07       0
  4572.2    .035       0  4659.6     .07       0    4992     .07       0
  5004.5     .07       0  5048.5     .16       0  5302.2     .07       0
  5376.7    .035       0  5446.5     .07       0
Bank Sta=4992,5004.5
XS Rating Curve= 0 ,0
Exp/Cntr=0.3,0.1

Type RM Length L Ch R = 1 ,4033    ,212,212,212
BEGIN DESCRIPTION:
MULBERRY CREEK TRIBUTARY 23 8.0
END DESCRIPTION:
XS GIS Cut Line= 4
      1466469.86      6824968.36      1466345.02      6824238.05
      1466259.36      6824076.46      1465274.16      6823701.04
#Sta/Elev= 30
  4259.1 2086.13  4411.6 2085.81  4604.4 2080.75  4665.3 2080.92  4797.3 2077.99
  4852.4 2078.44  4912.5  2074.3    4929 2066.91  4937.9 2064.74  4972.6 2059.14
  4991.2 2052.71  4991.7 2052.21  5003.7 2052.71  5008.2 2056.67  5013.9 2056.04
  5052.2 2067.53  5057.9 2065.53  5079.9 2068.62  5198.3 2071.56  5289.4 2071.85
  5447.5  2070.6  5594.8 2072.41  5666.9 2074.31  5679.8 2076.89    5697 2076.23
  5711.9 2077.63    5744 2075.81  5768.6 2076.23  5915.3 2076.44  6237.2 2081.22
#Mann= 7 ,-1 , 0
  4259.1     .07       0  4937.9     .16       0  4991.2     .07       0
  5003.7     .16       0  5289.4     .07       0  5594.8     .16       0
  5768.6     .07       0
Bank Sta=4991.2,5003.7
XS Rating Curve= 0 ,0
Exp/Cntr=0.3,0.1

Type RM Length L Ch R = 1 ,3821    ,272,272,272
BEGIN DESCRIPTION:
Mapping XS 72ad9e98
END DESCRIPTION:
XS GIS Cut Line= 3
      1466566.69      6824376.19      1466531.97      6824167.86
      1466302.83      6824006.43
#Sta/Elev= 30
  4783.6 2076.78  4832.5  2072.7  4841.8 2072.46  4852.7 2071.64    4873 2071.14
  4881.6 2070.48  4893.3 2068.94  4903.4 2068.65  4913.6  2067.7  4923.7 2065.54
  4947.5 2059.23  4964.3  2058.5  4984.5  2053.1  4985.9 2051.69  4986.4 2051.19
  4997.9 2051.19  4998.4 2051.69    5015 2055.99  5027.8 2061.08  5035.9 2064.83
  5042.1 2066.51  5050.7 2067.15  5092.6 2067.53  5107.4  2067.2  5172.7 2068.09
  5178.8 2068.57  5186.8 2068.24  5193.6  2068.9  5235.7 2070.34  5275.1 2070.94
#Mann= 4 ,-1 , 0
  4783.6     .07       0  4841.8     .16       0  4985.9     .07       0
  4998.4     .16       0
Bank Sta=4985.9,4998.4
XS Rating Curve= 0 ,0
Exp/Cntr=0.3,0.1

Type RM Length L Ch R = 1 ,3549    ,236,236,236
BEGIN DESCRIPTION:
Mapping XS 5e87ae48
END DESCRIPTION:
XS GIS Cut Line= 3
      1466825.37      6824254.67       1466740.3      6824020.29
       1466448.4      6823894.21
#Sta/Elev= 30
  4736.7 2073.44  4742.3 2072.94  4755.2 2071.68  4828.9 2070.35  4842.6 2069.71
  4860.8 2067.25  4873.2 2067.67  4882.1 2066.34  4898.5 2061.71  4936.7 2058.64
  4945.9 2058.38  4954.4 2056.48  4959.7 2053.59  4967.2 2051.69  4984.6 2049.88
  4985.6  2049.1  4986.1  2048.6  4998.1  2049.1  5013.6 2052.74  5024.3 2053.14
  5029.8 2055.05  5035.4 2054.79  5058.7 2060.23  5076.8  2061.7  5082.2 2063.59
  5105.7 2066.75  5181.7 2068.77  5242.3 2068.69  5281.2 2070.19    5304 2069.87
#Mann= 6 ,-1 , 0
  4736.7     .07       0  4742.3    .045       0  4755.2     .07       0
  4936.7     .16       0  4985.6     .07       0  4998.1     .16       0
Bank Sta=4985.6,4998.1
XS Rating Curve= 0 ,0
Exp/Cntr=0.3,0.1

Type RM Length L Ch R = 1 ,3313    ,253,253,253
BEGIN DESCRIPTION:
Mapping XS 8277fc7c
END DESCRIPTION:
XS GIS Cut Line= 3
      1466974.67      6824185.19      1466950.37      6823950.85
      1466830.59      6823805.03
#Sta/Elev= 30
  4747.6 2069.97  4774.9 2069.56  4791.4 2070.12  4815.1  2069.3  4835.3 2067.17
  4845.3 2066.98  4890.2 2062.14  4935.8 2055.88    4966 2054.73  4970.1 2054.04
    4976 2053.05  4982.1 2050.31  4988.6 2049.28  4990.2 2047.49  4990.7 2046.99
  5002.2 2046.99  5002.7 2047.49  5010.8 2049.07  5017.3 2047.54  5025.1  2050.5
  5031.6 2048.61    5046  2057.6  5052.4 2057.81  5060.3 2061.22  5066.8 2061.01
  5074.7 2063.55  5081.1 2062.85    5089  2064.7  5152.9 2065.36  5171.9 2064.98
#Mann= 4 ,-1 , 0
  4747.6     .07       0  4970.1     .16       0  4990.2     .07       0
  5002.7     .16       0
Bank Sta=4990.2,5002.7
XS Rating Curve= 0 ,0
Exp/Cntr=0.3,0.1

Type RM Length L Ch R = 1 ,3060    ,262,262,262
BEGIN DESCRIPTION:
Mapping XS 1f63b076
END DESCRIPTION:
XS GIS Cut Line= 3
       1467240.3      6824119.27      1467174.33      6823883.14
       1466989.3      6823765.55
#Sta/Elev= 30
  4760.1 2070.65  4803.3 2069.15  4823.7 2067.53  4865.2 2066.47  4871.6 2065.66
  4910.9 2063.99  4937.9 2058.01  4945.1 2053.73  4950.3 2055.23  4958.7  2052.3
  4972.9 2046.19  4973.4 2045.69    4985 2045.69  4985.5 2046.19  4989.8  2048.4
  5000.2 2051.21  5005.3 2051.21    5008 2052.61  5023.2 2053.72  5029.1 2055.48
  5038.5 2056.87  5044.4 2059.26  5051.9 2059.09  5059.6 2057.85  5065.6 2059.49
  5074.9 2054.75  5087.4 2057.11    5102 2061.71  5174.8 2064.09  5224.5 2064.04
#Mann= 3 ,-1 , 0
  4760.1     .07       0  4972.9     .07       0  4985.5     .07       0
Bank Sta=4972.9,4985.5
XS Rating Curve= 0 ,0
Exp/Cntr=0.3,0.1

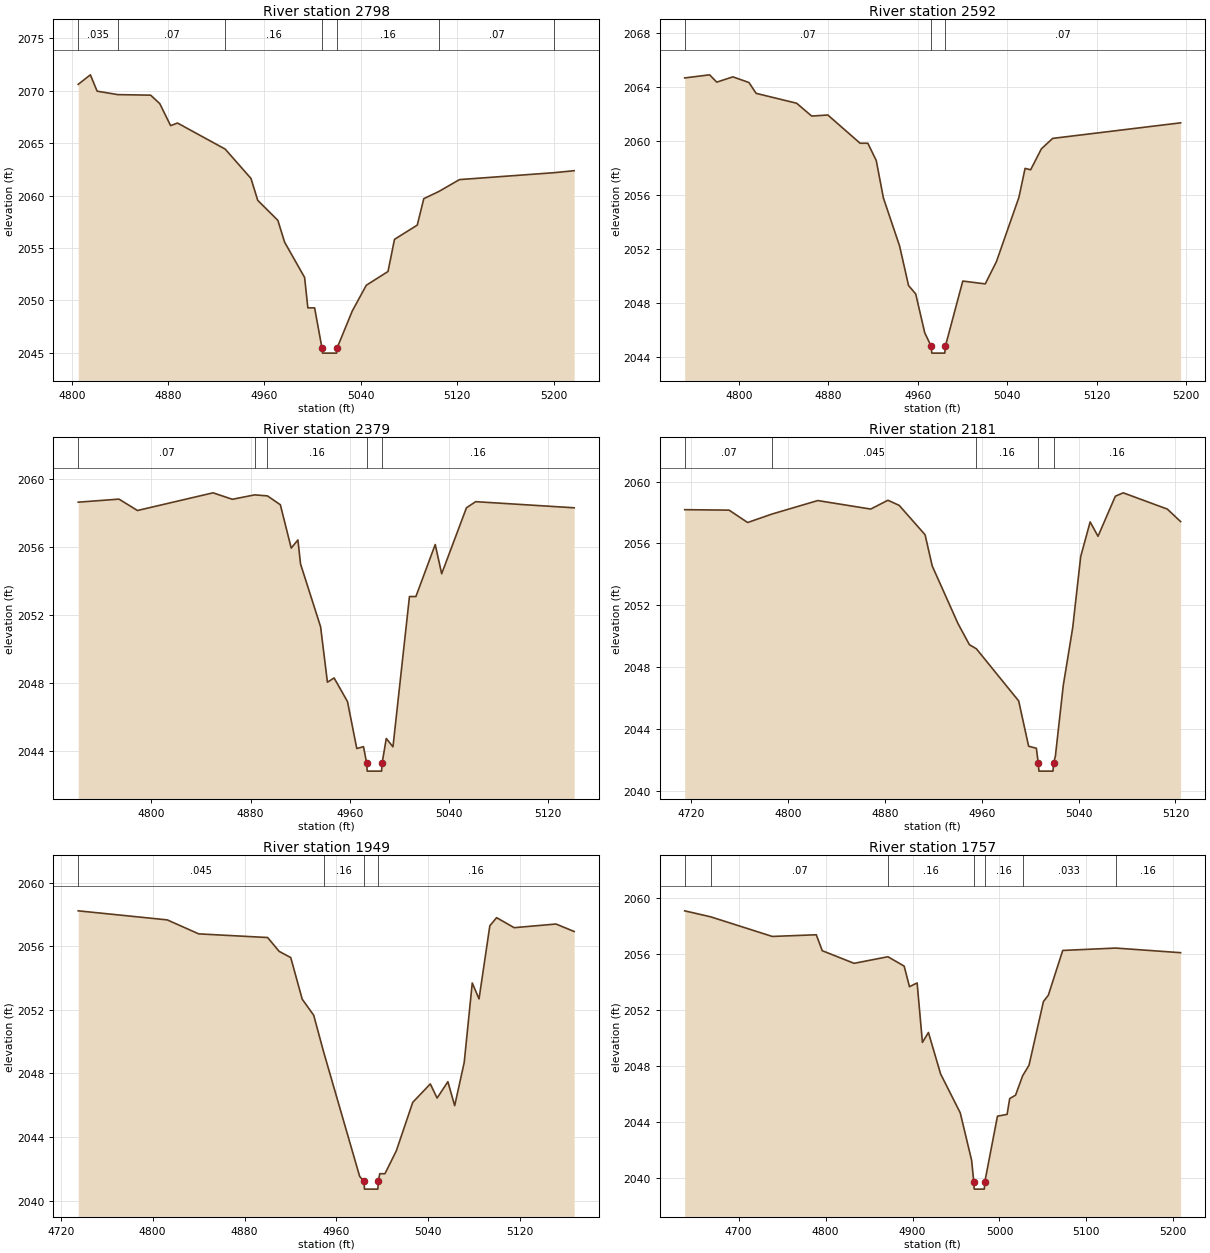
Type RM Length L Ch R = 1 ,2798    ,206,206,206
BEGIN DESCRIPTION:
Mapping XS bba81f17
END DESCRIPTION:
XS GIS Cut Line= 3
      1467476.43      6823928.32      1467389.61      6823758.14
      1467184.71      6823676.53
#Sta/Elev= 30
  4805.4 2070.61  4815.5 2071.52  4821.1 2069.96  4838.3 2069.63  4865.5 2069.58
  4873.1 2068.77  4882.1 2066.67  4887.8 2066.92  4927.4 2064.43  4948.8 2061.63
  4954.4 2059.54  4971.1 2057.63  4976.7 2055.55  4993.3 2052.18    4996 2049.28
  5001.6 2049.28  5007.7 2045.46  5008.2 2044.96  5019.8 2044.96  5020.3 2045.46
  5032.8 2048.97  5044.5 2051.44  5062.5 2052.75  5067.9 2055.82  5086.8 2057.18
  5092.2  2059.7  5104.6 2060.38  5121.8 2061.52  5200.3 2062.18    5217 2062.37
#Mann= 7 ,-1 , 0
  4805.4    .035       0  4838.3     .07       0  4927.4     .16       0
  5007.7     .07       0  5020.3     .16       0  5104.6     .07       0
  5200.3     .16       0
Bank Sta=5007.7,5020.3
XS Rating Curve= 0 ,0
Exp/Cntr=0.3,0.1

Type RM Length L Ch R = 1 ,2592    ,213,213,213
BEGIN DESCRIPTION:
Mapping XS 045a741c
END DESCRIPTION:
XS GIS Cut Line= 3
      1467653.52      6823719.97       1467471.2      6823575.85
      1467261.13      6823596.68
#Sta/Elev= 30
  4751.4 2064.64  4773.7 2064.87  4780.1 2064.33  4794.5 2064.72  4808.9  2064.3
  4815.3  2063.5  4851.5 2062.77    4865 2061.82  4879.4  2061.9  4908.3 2059.81
  4915.2 2059.81  4922.7 2058.54  4929.1 2055.77  4943.6 2052.21  4951.6 2049.29
    4958 2048.67  4966.1 2045.79  4971.9 2044.79  4972.4 2044.29    4984 2044.29
  4984.5 2044.79  5000.1 2049.62  5020.2 2049.41  5030.2 2051.06  5050.3 2055.81
  5055.8 2057.95  5060.8 2057.85  5070.4  2059.4  5080.5 2060.17  5194.9 2061.32
#Mann= 3 ,-1 , 0
  4751.4     .07       0  4971.9     .07       0  4984.5     .07       0
Bank Sta=4971.9,4984.5
XS Rating Curve= 0 ,0
Exp/Cntr=0.3,0.1

Type RM Length L Ch R = 1 ,2379    ,198,198,198
BEGIN DESCRIPTION:
Mapping XS 3991abb4
END DESCRIPTION:
XS GIS Cut Line= 3
       1467645.3      6823481.04      1467397.94      6823376.89
      1467272.05      6823415.96
#Sta/Elev= 30
  4740.9 2058.61  4773.8 2058.79  4788.7 2058.12  4849.7 2059.16  4865.3 2058.78
  4883.3 2059.04  4893.6 2058.98    4904 2058.46  4912.8 2055.91  4918.2 2056.39
  4920.3 2054.98  4936.5 2051.28    4942 2048.02  4947.4 2048.27  4958.2 2046.88
  4965.7 2044.12  4971.1 2044.23  4973.6 2043.29  4974.1 2042.79  4985.7 2042.79
  4986.2 2043.29  4989.5 2044.71  4994.9 2044.22  5008.2 2053.06  5013.4 2053.06
    5029 2056.12  5034.2  2054.4  5054.2 2058.28  5061.6 2058.64  5141.1 2058.28
#Mann= 5 ,-1 , 0
  4740.9     .07       0  4883.3    .045       0  4893.6     .16       0
  4973.6     .07       0  4986.2     .16       0
Bank Sta=4973.6,4986.2
XS Rating Curve= 0 ,0
Exp/Cntr=0.3,0.1

Type RM Length L Ch R = 1 ,2181    ,232,232,232
BEGIN DESCRIPTION:
Mapping XS 9b3094a1
END DESCRIPTION:
XS GIS Cut Line= 3
      1467636.64      6823448.48      1467491.26      6823214.13
      1467388.53      6823128.53
#Sta/Elev= 30
  4714.8 2058.18  4751.5 2058.15  4766.8 2057.35    4787  2057.9  4824.7 2058.77
  4868.4 2058.22  4882.6 2058.79  4891.9 2058.46  4913.3 2056.56  4919.2 2054.54
  4940.5 2050.81  4949.9 2049.45  4955.7 2049.18  4990.6 2045.81  4998.8 2042.88
  5005.2 2042.75  5006.8 2041.77  5007.3 2041.27  5018.9 2041.27  5019.4 2041.77
  5020.9 2042.24  5027.4 2046.81  5035.2 2050.55  5041.8 2055.15  5049.6 2057.39
  5056.1 2056.46  5070.4 2059.05  5076.9 2059.27  5113.3 2058.22  5124.3 2057.41
#Mann= 5 ,-1 , 0
  4714.8     .07       0    4787    .045       0  4955.7     .16       0
  5006.8     .07       0  5019.4     .16       0
Bank Sta=5006.8,5019.4
XS Rating Curve= 0 ,0
Exp/Cntr=0.3,0.1

Type RM Length L Ch R = 1 ,1949    ,192,192,192
BEGIN DESCRIPTION:
Mapping XS 2099703e
END DESCRIPTION:
XS GIS Cut Line= 3
      1467693.08       6823452.8      1467682.23      6823188.09
      1467593.26      6823047.04
#Sta/Elev= 30
  4735.2 2058.23  4812.7 2057.66  4840.1 2056.78  4900.1 2056.55  4910.1 2055.68
  4920.2 2055.29  4930.2 2052.67  4940.2 2051.66  4948.8 2049.36  4980.2 2041.52
  4983.9 2041.22  4984.4 2040.72    4996 2040.72  4996.5 2041.22  4997.7 2041.69
  5002.2 2041.69  5012.1 2043.13  5026.4 2046.18  5041.7 2047.34  5047.6 2046.45
    5057 2047.48  5062.9 2045.97  5071.2 2048.69  5078.2 2053.69  5084.1 2052.69
  5093.5 2057.29  5099.4  2057.8  5114.7 2057.17  5151.1  2057.4  5166.9 2056.93
#Mann= 4 ,-1 , 0
  4735.2    .045       0  4948.8     .16       0  4983.9     .07       0
  4996.5     .16       0
Bank Sta=4983.9,4996.5
XS Rating Curve= 0 ,0
Exp/Cntr=0.3,0.1

Type RM Length L Ch R = 1 ,1757    ,274,274,274
BEGIN DESCRIPTION:
Mapping XS 3667b894
END DESCRIPTION:
XS GIS Cut Line= 3
      1468066.36      6823437.69      1467853.67      6823133.84
      1467676.01      6823042.84
#Sta/Elev= 30
  4637.9 2059.05  4667.9 2058.62  4738.7 2057.22  4789.3 2057.34  4796.2  2056.2
  4832.8  2055.3  4871.7 2055.77  4890.4  2055.1  4896.5 2053.63  4905.3  2053.9
  4911.4 2049.65  4918.3 2050.36  4932.3  2047.4  4954.9 2044.62    4968 2041.22
  4970.5 2039.67    4971 2039.17  4982.6 2039.17  4983.1 2039.67  4997.7 2044.38
  5008.8 2044.51  5011.8 2045.64  5018.5 2045.88  5026.7 2047.27    5034 2048.02
  5050.6 2052.57  5056.2 2053.02  5072.8 2056.22  5133.8 2056.39  5208.4 2056.06
#Mann= 7 ,-1 , 0
  4637.9    .045       0  4667.9     .07       0  4871.7     .16       0
  4970.5     .07       0  4983.1     .16       0  5026.7    .033       0
  5133.8     .16       0
Bank Sta=4970.5,4983.1
XS Rating Curve= 0 ,0
Exp/Cntr=0.3,0.1

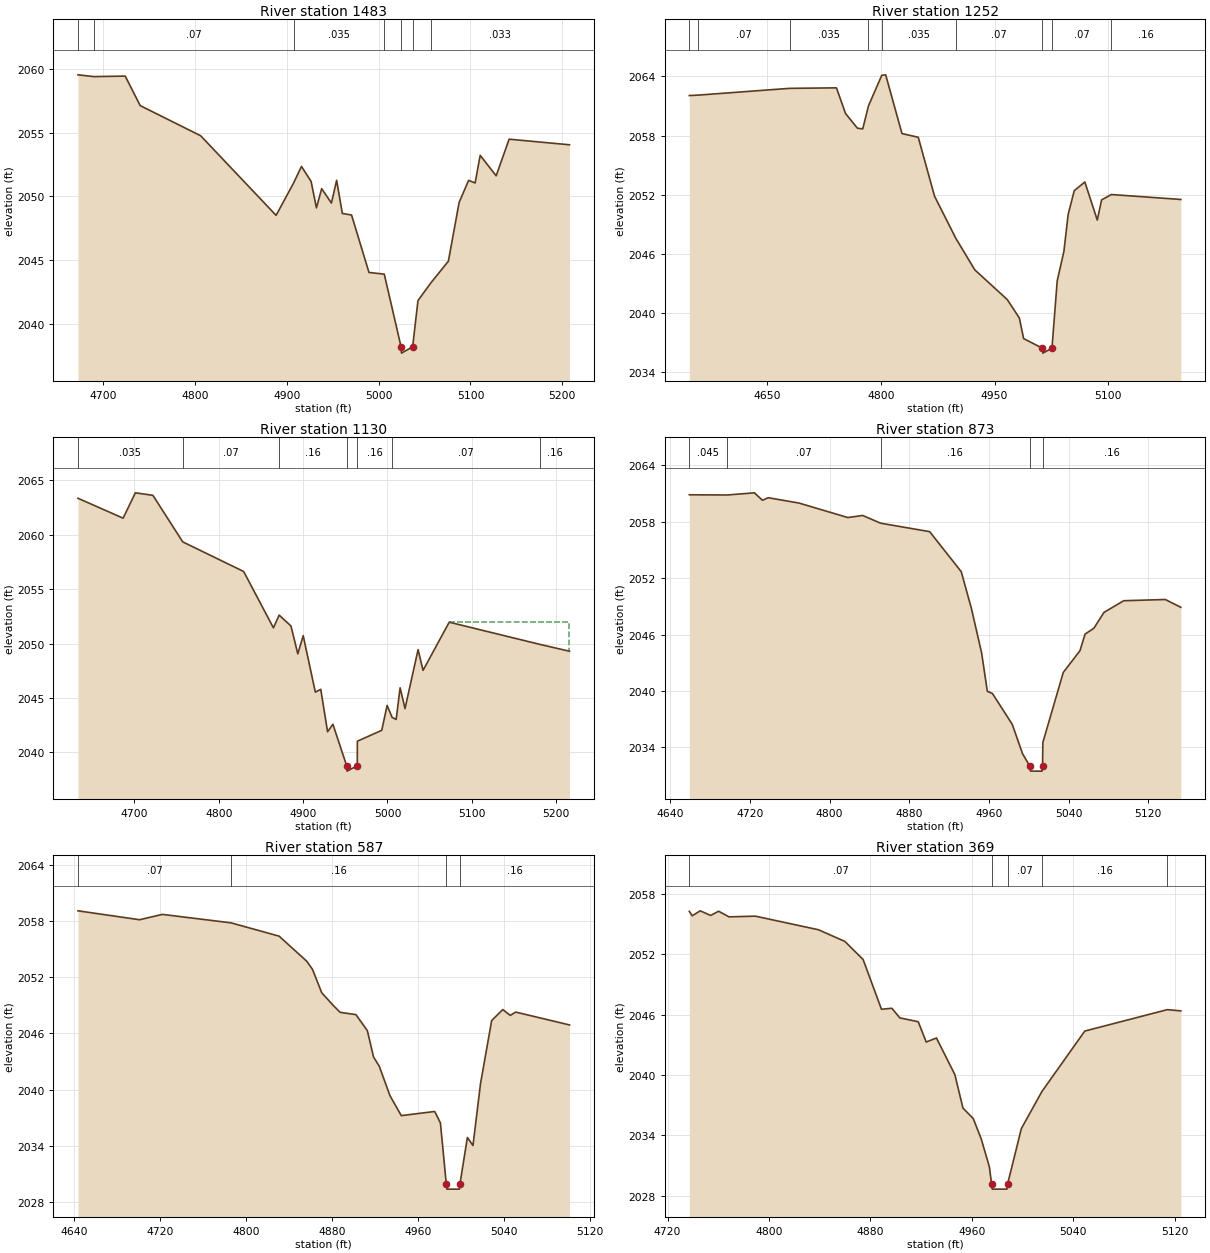
Type RM Length L Ch R = 1 ,1483    ,231,231,231
BEGIN DESCRIPTION:
Mapping XS 2929bc15
END DESCRIPTION:
XS GIS Cut Line= 3
      1468272.49      6823361.67      1468122.77      6823081.75
      1467925.32      6822990.63
#Sta/Elev= 30
  4672.9 2059.56  4690.1 2059.42  4724.3 2059.46  4740.6 2057.14  4806.4 2054.77
  4888.5 2048.51  4907.8 2051.09  4916.1 2052.36  4926.6 2051.18  4932.4  2049.1
  4938.1 2050.61  4948.7 2049.48  4954.4 2051.27  4960.6 2048.66  4970.6 2048.54
  4989.6 2044.02  5006.2 2043.89  5024.5 2038.18    5025 2037.68  5037.1 2038.18
  5042.9 2041.81  5056.9  2043.2    5076 2044.91  5087.7 2049.53    5098 2051.26
  5105.1 2051.06  5110.6 2053.23    5128 2051.62  5142.1  2054.5  5207.8 2054.06
#Mann= 7 ,-1 , 0
  4672.9    .045       0  4690.1     .07       0  4907.8    .035       0
  5006.2     .16       0  5024.5    .035       0  5037.1     .16       0
  5056.9    .033       0
Bank Sta=5024.5,5037.1
XS Rating Curve= 0 ,0
Exp/Cntr=0.3,0.1

Type RM Length L Ch R = 1 ,1252    ,122,122,122
BEGIN DESCRIPTION:
Mapping XS fbb49a38
END DESCRIPTION:
XS GIS Cut Line= 3
      1468530.73      6823366.01      1468302.89      6822973.25
      1468130.47      6822882.73
#Sta/Elev= 30
  4547.1 2062.06  4558.1  2062.1  4679.5 2062.79  4741.3 2062.84  4753.3 2060.24
    4769 2058.75    4776 2058.68  4783.6 2061.02  4801.1 2064.11  4806.3 2064.16
  4827.8 2058.21  4849.3 2057.83  4870.8 2051.86  4898.7 2047.62  4923.9  2044.4
  4966.9 2041.38  4982.7 2039.52  4988.4 2037.43  5013.2 2036.46  5013.7 2035.96
  5025.8 2036.46  5032.7 2043.28  5041.5 2046.25  5047.2 2050.02  5055.2 2052.42
  5069.2  2053.3  5085.6 2049.44  5091.3 2051.49  5104.3 2052.03  5195.9 2051.53
#Mann= 9 ,-1 , 0
  4547.1    .045       0  4558.1     .07       0  4679.5    .035       0
  4783.6     .07       0  4801.1    .035       0  4898.7     .07       0
  5013.2     .07       0  5025.8     .07       0  5104.3     .16       0
Bank Sta=5013.2,5025.8
XS Rating Curve= 0 ,0
Exp/Cntr=0.3,0.1

Type RM Length L Ch R = 1 ,1130    ,257,257,257
BEGIN DESCRIPTION:
Mapping XS 70ab8c94
END DESCRIPTION:
XS GIS Cut Line= 3
      1468593.69      6823164.22      1468361.48      6822866.91
      1468185.69      6822760.57
#Sta/Elev= 30
  4633.1 2063.35  4686.6 2061.52  4701.1 2063.85  4721.9 2063.62  4757.3 2059.34
  4829.5 2056.62  4864.8 2051.44  4871.6 2052.61  4885.6 2051.61  4893.7 2049.05
  4900.1 2050.72  4914.5 2045.53  4920.9 2045.79    4929 2041.89  4935.3 2042.58
  4951.6 2038.77  4952.1 2038.27  4964.2 2038.77  4964.3 2041.02  4993.2 2042.02
  4999.6 2044.31  5005.5 2043.21  5010.3 2043.02    5015 2045.93  5020.8 2044.02
  5036.3 2049.44  5042.2 2047.53  5073.2 2051.96  5180.7 2049.92  5215.8 2049.29
#Mann= 7 ,-1 , 0
  4633.1    .035       0  4757.3     .07       0  4871.6     .16       0
  4951.6     .07       0  4964.2     .16       0  5005.5     .07       0
  5180.7     .16       0
#XS Ineff= 2 , 0
       0                  5073.2       0 2051.96
Permanent Ineff=
       F       F
Bank Sta=4951.6,4964.2
XS Rating Curve= 0 ,0
Exp/Cntr=0.3,0.1

Type RM Length L Ch R = 1 ,873     ,286,286,286
BEGIN DESCRIPTION:
Mapping XS 34882892
END DESCRIPTION:
XS GIS Cut Line= 3
      1468730.72      6822772.44      1468518.08      6822642.26
      1468279.71      6822694.26
#Sta/Elev= 30
  4659.3 2060.88  4697.6 2060.86  4724.6 2061.09  4732.7  2060.3  4738.5 2060.57
  4769.4    2060  4818.4 2058.46  4833.3 2058.68  4851.2 2057.86  4900.5 2056.96
  4932.2  2052.7  4942.5 2048.75  4952.7 2044.03  4958.4 2039.97  4963.5 2039.74
  4983.4 2036.46  4993.7 2033.34  5001.2 2031.98  5001.7 2031.48  5013.3 2031.48
  5013.8 2031.98  5014.1 2034.52  5034.6 2041.98  5051.4  2044.3  5056.5 2046.06
  5065.3 2046.68  5075.5 2048.37  5095.3 2049.61    5137 2049.74  5152.6 2048.91
#Mann= 5 ,-1 , 0
  4659.3    .045       0  4697.6     .07       0  4851.2     .16       0
  5001.2     .07       0  5013.8     .16       0
Bank Sta=5001.2,5013.8
XS Rating Curve= 0 ,0
Exp/Cntr=0.3,0.1

Type RM Length L Ch R = 1 ,587     ,218,218,218
BEGIN DESCRIPTION:
Mapping XS 9a7b8929
END DESCRIPTION:
XS GIS Cut Line= 3
      1468659.15      6822533.75      1468329.28      6822418.73
      1468225.08      6822446.95
#Sta/Elev= 30
  4643.5 2059.08  4700.8 2058.13    4722  2058.7  4785.8  2057.8  4830.6 2056.38
  4856.4  2053.7  4861.7 2052.83  4870.3 2050.34  4880.9    2049  4887.5 2048.25
  4902.1 2048.01  4912.7 2046.31  4918.5 2043.49  4923.8 2042.51  4933.8 2039.36
  4944.3 2037.24  4975.4 2037.68  4980.7 2036.46  4986.2  2029.9  4986.7  2029.4
  4998.3  2029.4  4998.8  2029.9  5005.8 2034.91    5011 2034.05    5018 2040.64
  5028.4 2047.38  5038.7 2048.55  5045.7 2047.93  5050.8 2048.28  5100.8 2046.91
#Mann= 4 ,-1 , 0
  4643.5     .07       0  4785.8     .16       0  4986.2     .07       0
  4998.8     .16       0
Bank Sta=4986.2,4998.8
XS Rating Curve= 0 ,0
Exp/Cntr=0.3,0.1

Type RM Length L Ch R = 1 ,369     ,265,265,265
BEGIN DESCRIPTION:
Mapping XS 0de7f952
END DESCRIPTION:
XS GIS Cut Line= 3
      1468611.42      6822444.81      1468459.48      6822249.46
      1468319.23      6822245.15
#Sta/Elev= 30
  4737.2 2056.28  4739.5 2055.85  4745.8 2056.34    4754 2055.88  4760.3  2056.3
  4768.5 2055.74  4789.3 2055.81    4839 2054.46  4859.9  2053.3  4874.3  2051.5
  4888.8 2046.55    4897 2046.65  4903.3 2045.69  4917.8 2045.31  4924.1 2043.29
  4932.2 2043.69  4946.7 2040.05  4953.1 2036.72  4961.2 2035.68  4967.5 2033.66
  4973.9 2030.89  4975.7 2029.16  4976.2 2028.66  4987.8 2028.66  4988.3 2029.16
  4999.2 2034.69  5015.4 2038.37  5049.2 2044.38  5114.3 2046.51    5125 2046.39
#Mann= 5 ,-1 , 0
  4737.2     .07       0  4975.7     .07       0  4988.3     .07       0
  5015.4     .16       0  5114.3     .07       0
Bank Sta=4975.7,4988.3
XS Rating Curve= 0 ,0
Exp/Cntr=0.3,0.1

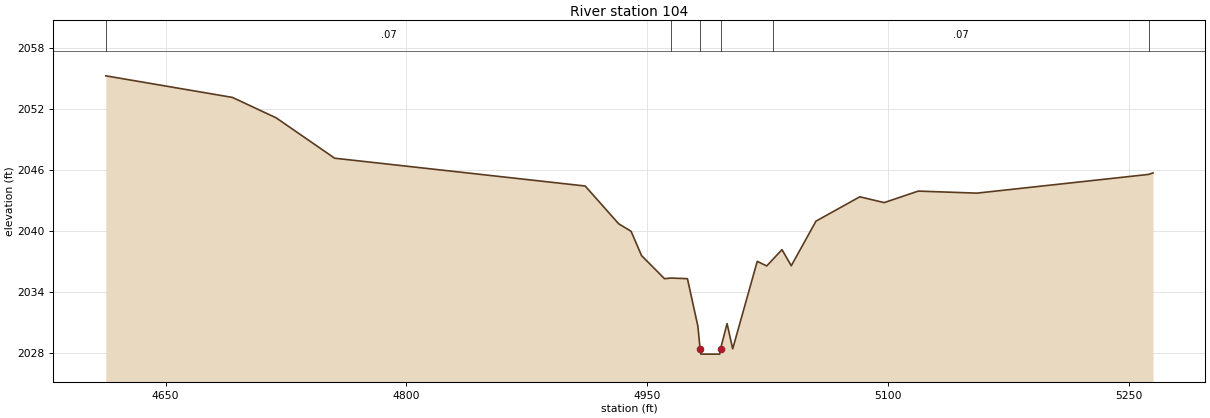
Type RM Length L Ch R = 1 ,104     ,0,0,0
BEGIN DESCRIPTION:
MULBERRY CREEK TRIBUTARY 23 1.0
END DESCRIPTION:
XS GIS Cut Line= 3
      1468804.53       6822318.9      1468555.03      6822022.67
        1468330.        6822163.
#Sta/Elev= 30
  4612.7 2055.23  4691.6 2053.11  4718.9  2051.1  4755.3 2047.14  4911.4 2044.41
  4932.2 2040.71    4940 2039.96  4946.5 2037.58  4960.8 2035.31  4964.9 2035.37
  4975.1 2035.31  4981.6 2030.65    4983  2028.4  4983.5  2027.9  4995.2  2027.9
  4995.7  2028.4  4999.8  2030.9  5003.3 2028.42  5018.6 2037.01  5024.5 2036.56
  5028.6 2037.25    5034 2038.16  5039.8 2036.58  5055.2 2040.96  5082.5 2043.35
  5097.7 2042.78  5118.9 2043.91  5155.5 2043.71  5262.5 2045.55  5265.2  2045.7
#Mann= 6 ,-1 , 0
  4612.7     .07       0  4964.9     .16       0    4983     .07       0
  4995.7     .16       0  5028.6     .07       0  5262.5     .16       0
Bank Sta=4983,4995.7
XS Rating Curve= 0 ,0
Exp/Cntr=0.3,0.1

Chan Stop Cuts=-1
Use User Specified Reach Order=0
Composite Channel Slope=5