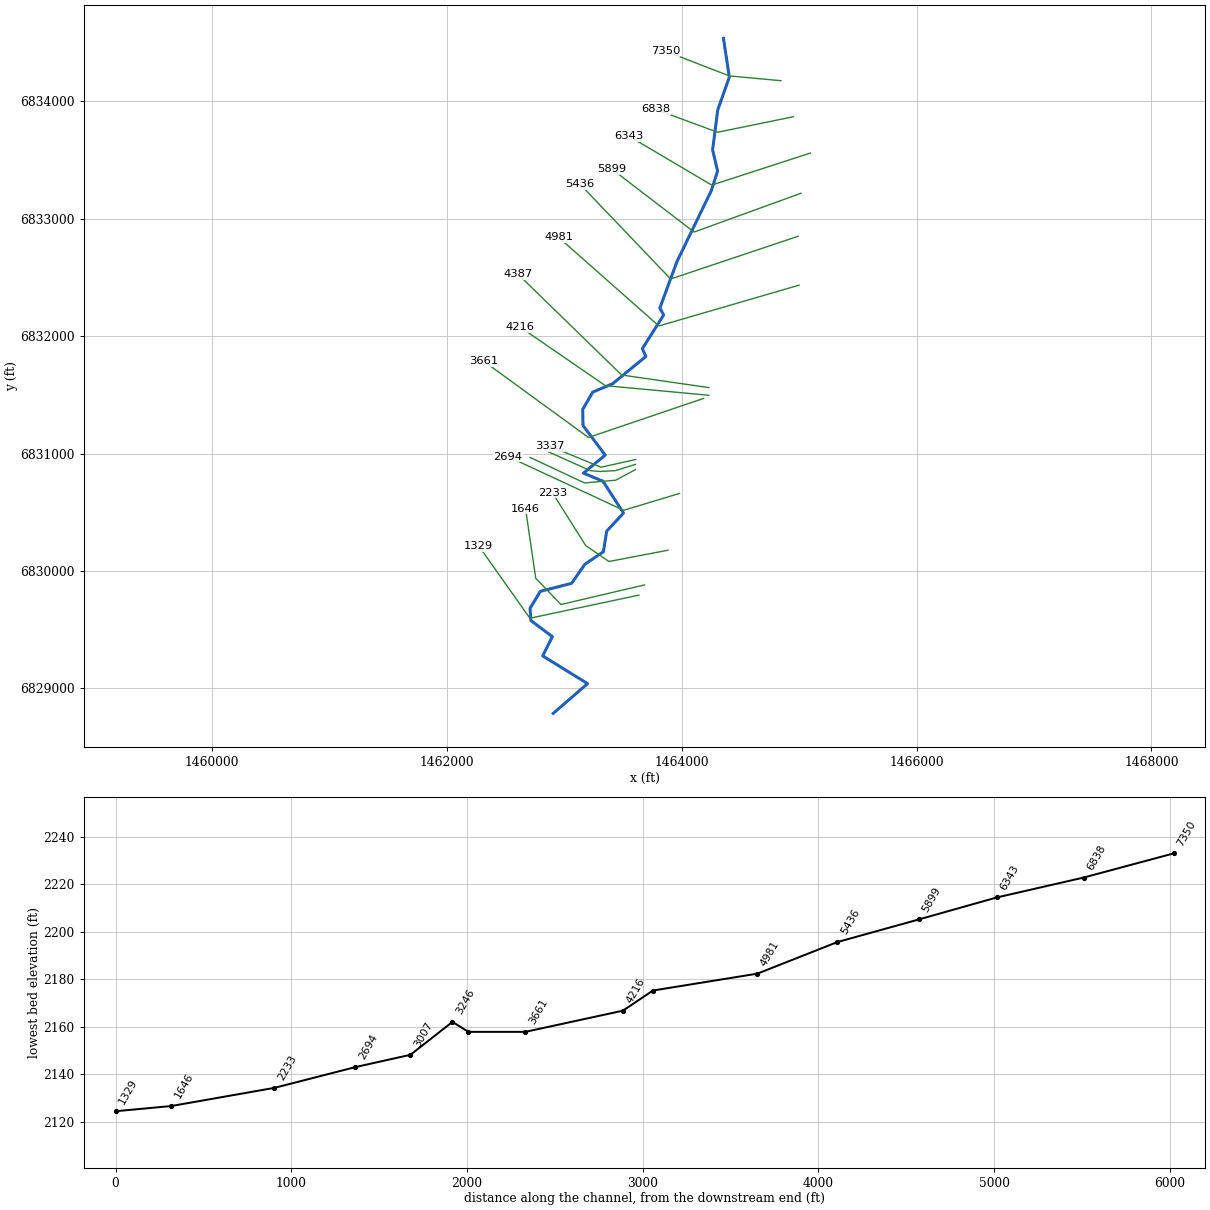
--- MULBERRY CREEK TRIBUTARY 23_1.prj (project) ---

Proj Title=MULBERRY CREEK TRIBUTARY 23_1 Base Level Engineering
Current Plan=p01
Default Exp/Contr=0.3,0.1
English Units
Geom File=g01
Flow File=f01
Plan File=p01
BEGIN DESCRIPTION:
MULBERRY CREEK TRIBUTARY 23_1
END DESCRIPTION:

--- MULBERRY CREEK TRIBUTARY 23_1.p01 (plan) ---

Plan Title=Multiple Run
Short Identifier=Multiple
Geom File=g01
Flow File=f01
Subcritical Flow
K Sum by GR= 0
Std Step Tol= 0.01
Critical Tol= 0.01
Num of Std Step Trials= 20
Max Error Tol= 0.3
Flow Tol Ratio= 0.001
Split Flow NTrial= 30
Split Flow Tol= 0.02
Split Flow Ratio= 0.02
Log Output Level= 0
Friction Slope Method= 1
Unsteady Friction Slope Method= 2
Unsteady Bridges Friction Slope Method= 1
Parabolic Critical Depth
Global Vel Dist=  1 , 1 , 1
Global Log Level= 0
CheckData=True
Encroach Param= -1, 0, 0, 0
BEGIN DESCRIPTION:
Multiple Run
END DESCRIPTION:

--- MULBERRY CREEK TRIBUTARY 23_1.f01 (steady flow) ---

Flow Title=Multiple
Number of Profiles=7
Profile Names=10-year,25-year,50-year,1pct_min,100-year,1pct_plu,500-year
River Rch & RM= MULBERRY CREEK T,Reach-1,7350
     297     429     543     343     684    1365    1098
River Rch & RM= MULBERRY CREEK T,Reach-1,4387
     334     484     613     387     773    1542    1242
Boundary for River Rch & Prof#=MULBERRY CREEK T,Reach-1,1
Up Type=0
Dn Type=3
Dn Slope=0.005
Boundary for River Rch & Prof#=MULBERRY CREEK T,Reach-1,2
Up Type=0
Dn Type=3
Dn Slope=0.005
Boundary for River Rch & Prof#=MULBERRY CREEK T,Reach-1,3
Up Type=0
Dn Type=3
Dn Slope=0.005
Boundary for River Rch & Prof#=MULBERRY CREEK T,Reach-1,4
Up Type=0
Dn Type=3
Dn Slope=0.005
Boundary for River Rch & Prof#=MULBERRY CREEK T,Reach-1,5
Up Type=0
Dn Type=3
Dn Slope=0.005
Boundary for River Rch & Prof#=MULBERRY CREEK T,Reach-1,6
Up Type=0
Dn Type=3
Dn Slope=0.005
Boundary for River Rch & Prof#=MULBERRY CREEK T,Reach-1,7
Up Type=0
Dn Type=3
Dn Slope=0.005

--- MULBERRY CREEK TRIBUTARY 23_1.g01 (geometry) ---

Geom Title=Existing Conditions

River Reach=MULBERRY CREEK T,Reach-1
Reach XY= 30
      1464355.00      6834538.00      1464404.95      6834208.04
      1464306.22      6833927.50      1464262.56      6833588.00
      1464304.95      6833408.04      1464251.17      6833239.58
      1463958.83      6832636.42      1463813.24      6832241.23
      1463845.42      6832181.45      1463664.32      6831894.66
      1463693.77      6831827.98      1463411.06      6831596.14
      1463241.43      6831524.53      1463156.19      6831377.50
      1463158.74      6831239.56      1463347.93      6830987.99
      1463162.39      6830834.57      1463328.89      6830765.28
      1463503.42      6830494.05      1463360.47      6830340.45
      1463332.16      6830164.42      1463174.77      6830058.42
      1463061.47      6829895.70      1462795.00      6829827.37
      1462707.14      6829682.03      1462715.43      6829578.19
      1462897.51      6829441.58      1462815.04      6829278.00
      1463197.42      6829041.35      1462905.00      6828788.00

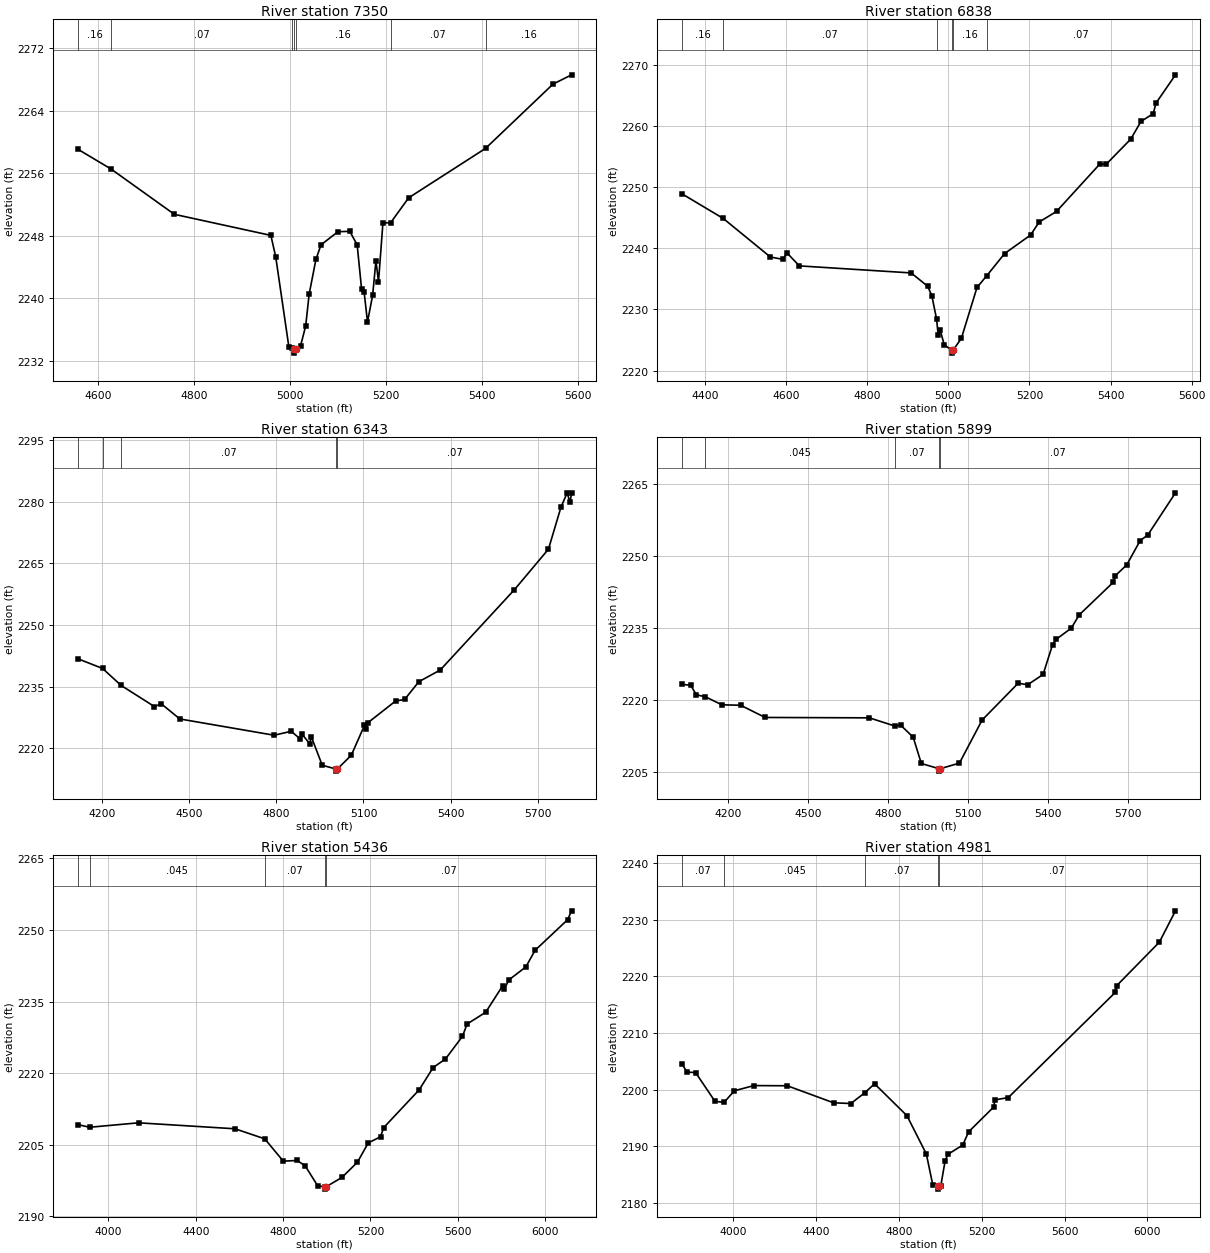
Type RM Length L Ch R = 1,7350,512,512,512
BEGIN DESCRIPTION:
MULBERRY CREEK TRIBUTARY 23_1 14.0
END DESCRIPTION:
XS GIS Cut Line= 3
      1464844.71      6834177.25      1464405.39      6834217.87
      1463858.91      6834429.42
#Sta/Elev= 30
  4558.8 2259.06  4627.8 2256.53  4759.4 2250.75  4960.2 2248.06  4970.3 2245.33
  4997.7 2233.81  5005.2 2233.68  5008.0 2233.52  5008.2 2233.02  5012.0 2233.52
  5021.9 2233.92  5032.6 2236.47  5039.9 2240.56  5054.0 2244.99  5064.5 2246.85
  5099.8 2248.53  5124.4 2248.58  5139.8 2246.86  5148.9 2241.26  5154.3 2240.81
  5161.3 2237.00  5172.0 2240.40  5178.9 2244.83  5184.2 2242.13  5193.4 2249.64
  5209.6 2249.69  5247.0 2252.86  5406.9 2259.17  5547.3 2267.38  5586.0 2268.57
#Mann=7,-1,0
  4558.8    0.16       0  4627.8    0.07       0  5005.2    0.16       0
  5008.0    0.07       0  5012.0    0.16       0  5209.6    0.07       0
  5406.9    0.16       0
Bank Sta=5008,5012
Exp/Cntr=0.3,0.1

Type RM Length L Ch R = 1,6838,495,495,495
BEGIN DESCRIPTION:
MULBERRY CREEK TRIBUTARY 23_1 13.0
END DESCRIPTION:
XS GIS Cut Line= 3
      1464948.88      6833869.95      1464305.07      6833737.97
      1463779.80      6833932.40
#Sta/Elev= 30
  4342.8 2248.91  4444.9 2244.87  4561.1 2238.57  4591.8 2238.19  4602.0 2239.24
  4632.6 2237.12  4908.2 2235.97  4949.0 2233.79  4959.2 2232.26  4971.1 2228.38
  4974.7 2225.90  4979.9 2226.60  4989.9 2224.22  5008.0 2223.36  5008.2 2222.86
  5012.0 2223.36  5032.1 2225.28  5070.7 2233.61  5094.1 2235.46  5138.7 2239.13
  5202.7 2242.16  5224.0 2244.29  5266.7 2246.02  5373.3 2253.75  5389.1 2253.72
  5449.9 2257.85  5475.0 2260.73  5505.4 2262.01  5511.9 2263.71  5560.1 2268.35
#Mann=6,-1,0
  4342.8    0.16       0  4444.9    0.07       0  4971.1    0.16       0
  5008.0    0.07       0  5012.0    0.16       0  5094.1    0.07       0
Bank Sta=5008,5012
Exp/Cntr=0.3,0.1

Type RM Length L Ch R = 1,6343,444,444,444
BEGIN DESCRIPTION:
MULBERRY CREEK TRIBUTARY 23_1 12.0
END DESCRIPTION:
XS GIS Cut Line= 3
      1465095.67      6833560.73      1464255.00      6833288.00
      1463551.30      6833703.47
#Sta/Elev= 30
  4116.2 2241.80  4201.0 2239.44  4265.0 2235.31  4379.7 2230.17  4403.3 2230.85
  4467.2 2227.16  4792.2 2223.20  4850.9 2224.16  4882.8 2222.27  4888.1 2223.45
  4914.8 2221.16  4920.1 2222.86  4958.0 2215.90  5005.8 2214.97  5006.1 2214.47
  5009.8 2214.97  5058.1 2218.33  5103.4 2225.58  5109.3 2224.72  5116.1 2226.29
  5210.7 2231.52  5242.0 2231.91  5290.7 2236.21  5364.8 2239.08  5620.4 2258.62
  5737.5 2268.46  5780.4 2278.62  5801.9 2282.17  5811.7 2279.86  5817.2 2282.06
#Mann=5,-1,0
  4116.2    0.07       0  4201.0    0.16       0  4265.0    0.07       0
  5005.8    0.07       0  5009.8    0.07       0
Bank Sta=5005.8,5009.8
Exp/Cntr=0.3,0.1

Type RM Length L Ch R = 1,5899,463,463,463
BEGIN DESCRIPTION:
MULBERRY CREEK TRIBUTARY 23_1 11.0
END DESCRIPTION:
XS GIS Cut Line= 3
      1465016.04      6833218.55      1464105.00      6832888.00
      1463404.77      6833423.86
#Sta/Elev= 30
  4026.1 2223.25  4059.1 2223.07  4080.4 2221.09  4114.7 2220.66  4176.1 2219.00
  4246.4 2218.91  4338.3 2216.37  4729.3 2216.29  4823.5 2214.61  4846.3 2214.78
  4893.4 2212.28  4924.0 2206.80  4990.6 2205.71  4990.8 2205.21  4994.6 2205.71
  5066.9 2206.88  5152.1 2215.84  5287.2 2223.49  5322.7 2223.17  5380.6 2225.31
  5416.0 2231.49  5430.5 2232.65  5486.7 2234.96  5515.7 2237.68  5644.5 2244.52
  5650.8 2245.82  5694.4 2248.10  5744.2 2253.11  5773.3 2254.32  5877.0 2263.08
#Mann=5,-1,0
  4026.1    0.07       0  4114.7   0.045       0  4823.5    0.07       0
  4990.6    0.07       0  4994.6    0.07       0
Bank Sta=4990.6,4994.6
Exp/Cntr=0.3,0.1

Type RM Length L Ch R = 1,5436,455,455,455
BEGIN DESCRIPTION:
MULBERRY CREEK TRIBUTARY 23_1 10.0
END DESCRIPTION:
XS GIS Cut Line= 3
      1464990.61      6832851.95      1463905.00      6832488.00
      1463134.63      6833293.81
#Sta/Elev= 30
  3860.9 2209.21  3913.9 2208.66  4138.3 2209.59  4580.0 2208.34  4716.1 2206.23
  4800.8 2201.56  4863.9 2201.70  4900.7 2200.60  4958.6 2196.38  4993.4 2196.20
  4993.6 2195.70  4997.4 2196.20  5069.6 2198.16  5140.3 2201.34  5189.7 2205.37
  5246.3 2206.68  5260.5 2208.58  5423.1 2216.51  5486.9 2221.17  5543.5 2222.97
  5621.2 2227.71  5642.3 2230.29  5727.2 2232.74  5805.2 2238.29  5812.1 2237.54
  5833.5 2239.53  5911.2 2242.24  5953.7 2245.73  6102.1 2252.12  6120.7 2254.00
#Mann=5,-1,0
  3860.9    0.07       0  3913.9   0.045       0  4716.1    0.07       0
  4993.4    0.07       0  4997.4    0.07       0
Bank Sta=4993.4,4997.4
Exp/Cntr=0.3,0.1

Type RM Length L Ch R = 1,4981,594,594,594
BEGIN DESCRIPTION:
MULBERRY CREEK TRIBUTARY 23_1 9.0
END DESCRIPTION:
XS GIS Cut Line= 3
      1464998.45      6832435.29      1463805.00      6832088.00
      1462950.09      6832843.11
#Sta/Elev= 30
  3752.2 2204.60  3776.6 2203.09  3818.3 2203.02  3912.0 2197.93  3956.1 2197.75
  4005.7 2199.79  4099.5 2200.71  4261.2 2200.68  4484.8 2197.67  4568.2 2197.54
  4636.1 2199.46  4682.7 2201.03  4839.1 2195.39  4932.7 2188.63  4963.9 2183.15
  4990.6 2182.91  4990.8 2182.41  4994.6 2182.91  5002.3 2182.94  5023.2 2187.37
  5037.4 2188.57  5108.5 2190.20  5137.0 2192.54  5257.4 2196.90  5264.1 2198.19
  5328.5 2198.59  5845.5 2217.19  5852.2 2218.38  6058.0 2226.06  6135.8 2231.60
#Mann=5,-1,0
  3752.2    0.07       0  3956.1   0.045       0  4636.1    0.07       0
  4990.6    0.07       0  4994.6    0.07       0
Bank Sta=4990.6,4994.6
Exp/Cntr=0.3,0.1

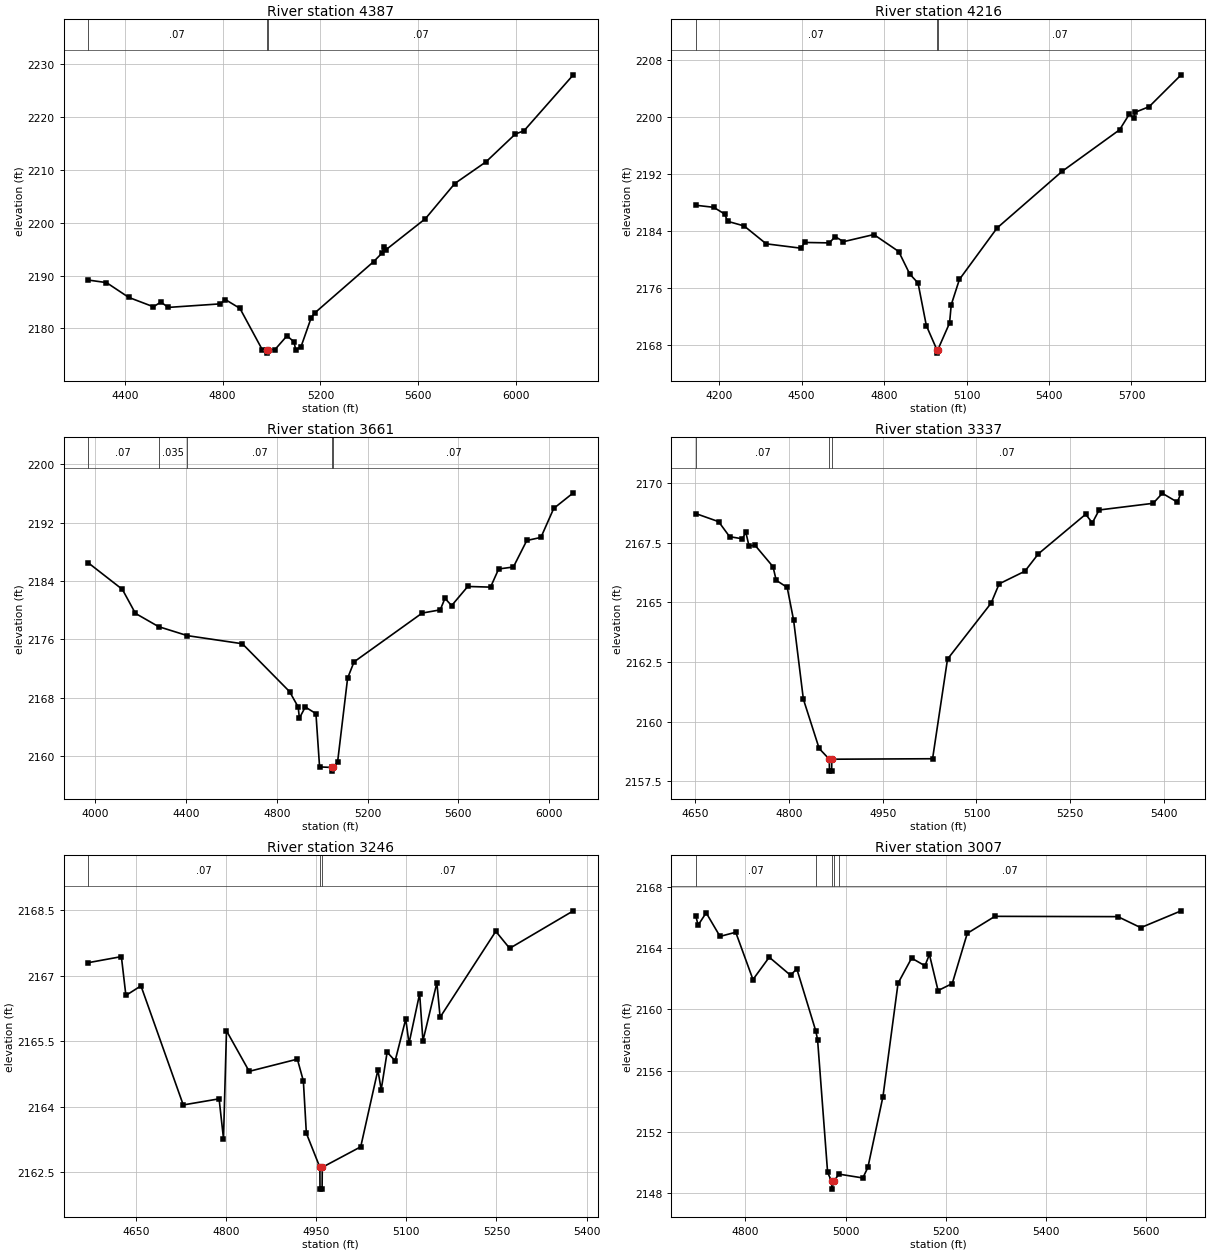
Type RM Length L Ch R = 1,4387,171,171,171
BEGIN DESCRIPTION:
MULBERRY CREEK TRIBUTARY 23_1 8.0
END DESCRIPTION:
XS GIS Cut Line= 3
      1464230.02      6831563.00      1463487.35      6831670.42
      1462602.79      6832530.98
#Sta/Elev= 30
  4249.6 2189.16  4325.4 2188.67  4416.3 2185.87  4517.4 2184.09  4547.7 2184.98
  4578.0 2183.97  4790.2 2184.64  4812.0 2185.44  4871.0 2183.79  4962.0 2175.99
  4980.2 2175.81  4980.4 2175.31  4984.2 2175.81  5014.1 2175.98  5063.6 2178.59
  5091.9 2177.45  5099.0 2175.98  5120.1 2176.43  5162.6 2182.04  5176.7 2182.91
  5417.2 2192.62  5452.5 2194.29  5459.7 2195.48  5466.6 2194.84  5629.4 2200.78
  5749.6 2207.44  5876.9 2211.54  5997.0 2216.81  6032.5 2217.43  6234.1 2228.03
#Mann=3,-1,0
  4249.6    0.07       0  4980.2    0.07       0  4984.2    0.07       0
Bank Sta=4980.2,4984.2
Exp/Cntr=0.3,0.1

Type RM Length L Ch R = 1,4216,555,555,555
BEGIN DESCRIPTION:
MULBERRY CREEK TRIBUTARY 23_1 7.0
END DESCRIPTION:
XS GIS Cut Line= 3
      1464229.97      6831497.66      1463349.07      6831579.56
      1462623.44      6832078.48
#Sta/Elev= 30
  4115.3 2187.57  4180.5 2187.28  4220.7 2186.33  4230.8 2185.32  4291.0 2184.67
  4371.4 2182.16  4497.0 2181.55  4512.0 2182.35  4601.2 2182.29  4622.4 2183.17
  4652.6 2182.46  4763.0 2183.46  4853.4 2181.08  4893.6 2177.92  4923.7 2176.66
  4953.9 2170.69  4992.0 2167.33  4992.3 2166.83  4996.0 2167.33  5038.3 2171.04
  5044.4 2173.60  5074.2 2177.17  5211.2 2184.38  5447.6 2192.32  5656.7 2198.15
  5692.5 2200.37  5707.4 2199.75  5713.5 2200.61  5764.2 2201.39  5880.6 2205.86
#Mann=3,-1,0
  4115.3    0.07       0  4992.0    0.07       0  4996.0    0.07       0
Bank Sta=4992,4996
Exp/Cntr=0.3,0.1

Type RM Length L Ch R = 1,3661,324,324,324
BEGIN DESCRIPTION:
MULBERRY CREEK TRIBUTARY 23_1 6.0
END DESCRIPTION:
XS GIS Cut Line= 3
      1464185.95      6831470.89      1463205.00      6831138.00
      1462314.38      6831786.84
#Sta/Elev= 30
  3968.4 2186.54  4120.0 2182.86  4177.5 2179.57  4279.4 2177.75  4406.6 2176.51
  4648.5 2175.40  4856.5 2168.83  4894.4 2166.72  4899.7 2165.19  4925.8 2166.72
  4972.6 2165.81  4988.6 2158.50  5045.2 2158.42  5045.4 2157.92  5049.2 2158.42
  5068.0 2159.18  5112.1 2170.68  5140.4 2172.91  5440.4 2179.61  5520.0 2180.05
  5540.9 2181.63  5570.2 2180.63  5641.3 2183.26  5741.7 2183.17  5777.3 2185.66
  5842.2 2185.93  5901.3 2189.57  5963.5 2189.99  6019.9 2193.97  6106.2 2196.11
#Mann=5,-1,0
  3968.4    0.07       0  4279.4   0.035       0  4406.6    0.07       0
  5045.2    0.07       0  5049.2    0.07       0
Bank Sta=5045.2,5049.2
Exp/Cntr=0.3,0.1

Type RM Length L Ch R = 1,3337,91,91,91
BEGIN DESCRIPTION:
MULBERRY CREEK TRIBUTARY 23_1 5.0
END DESCRIPTION:
XS GIS Cut Line= 3
      1463607.93      6830950.44      1463312.21      6830884.72
      1462873.55      6831065.00
#Sta/Elev= 30
  4650.5 2168.73  4687.1 2168.39  4704.7 2167.76  4725.2 2167.67  4730.6 2167.95
  4735.7 2167.38  4745.7 2167.39  4774.2 2166.50  4779.3 2165.93  4796.9 2165.63
  4807.2 2164.25  4822.8 2160.94  4848.1 2158.87  4864.3 2158.42  4864.6 2157.92
  4868.1 2157.92  4868.3 2158.42  5029.7 2158.44  5053.6 2162.62  5123.4 2164.97
  5136.3 2165.78  5177.5 2166.31  5199.1 2167.04  5274.8 2168.70  5285.5 2168.34
  5296.4 2168.88  5382.9 2169.16  5397.6 2169.58  5421.6 2169.21  5427.7 2169.60
#Mann=3,-1,0
  4650.5    0.07       0  4864.3    0.07       0  4868.3    0.07       0
Bank Sta=4864.3,4868.3
Exp/Cntr=0.3,0.1

Type RM Length L Ch R = 1,3246,239,239,239
BEGIN DESCRIPTION:
Mapping XS 3dc739f9
END DESCRIPTION:
XS GIS Cut Line= 5
      1463605.33      6830908.78      1463433.12      6830855.51
      1463301.17      6830848.56      1463221.31      6830855.51
      1462842.23      6831025.97
#Sta/Elev= 30
  4569.8 2167.30  4625.5 2167.44  4633.0 2166.55  4658.1 2166.77  4728.5 2164.04
  4788.2 2164.18  4795.5 2163.27  4800.5 2165.74  4838.3 2164.81  4918.5 2165.09
  4928.5 2164.59  4933.5 2163.39  4956.0 2162.61  4956.2 2162.11  4959.7 2162.11
  4960.0 2162.61  5024.0 2163.08  5052.6 2164.84  5058.1 2164.39  5068.0 2165.25
  5081.3 2165.05  5099.0 2166.01  5104.4 2165.45  5122.1 2166.59  5127.6 2165.51
  5150.8 2166.84  5156.2 2166.05  5248.9 2168.02  5272.0 2167.63  5378.0 2168.49
#Mann=3,-1,0
  4569.8    0.07       0  4956.0    0.07       0  4960.0    0.07       0
Bank Sta=4956,4960
Exp/Cntr=0.3,0.1

Type RM Length L Ch R = 1,3007,313,313,313
BEGIN DESCRIPTION:
MULBERRY CREEK TRIBUTARY 23_1 4.0
END DESCRIPTION:
XS GIS Cut Line= 4
      1463605.29      6830864.50      1463437.17      6830774.28
      1463171.54      6830750.85      1462708.44      6830967.91
#Sta/Elev= 30
  4701.0 2166.13  4705.6 2165.50  4721.8 2166.31  4749.4 2164.77  4780.8 2165.04
  4815.2 2161.95  4847.7 2163.41  4890.2 2162.23  4902.7 2162.65  4940.7 2158.58
  4944.2 2158.01  4964.2 2149.35  4972.3 2148.76  4972.5 2148.26  4976.3 2148.76
  4986.8 2149.24  5034.5 2148.99  5044.6 2149.68  5074.7 2154.31  5104.8 2161.71
  5131.9 2163.35  5158.5 2162.85  5167.4 2163.59  5184.7 2161.23  5213.0 2161.69
  5243.0 2164.97  5298.2 2166.08  5543.6 2166.06  5589.3 2165.34  5669.9 2166.44
#Mann=5,-1,0
  4701.0    0.07       0  4940.7    0.16       0  4972.3    0.07       0
  4976.3    0.16       0  4986.8    0.07       0
Bank Sta=4972.3,4976.3
Exp/Cntr=0.3,0.1

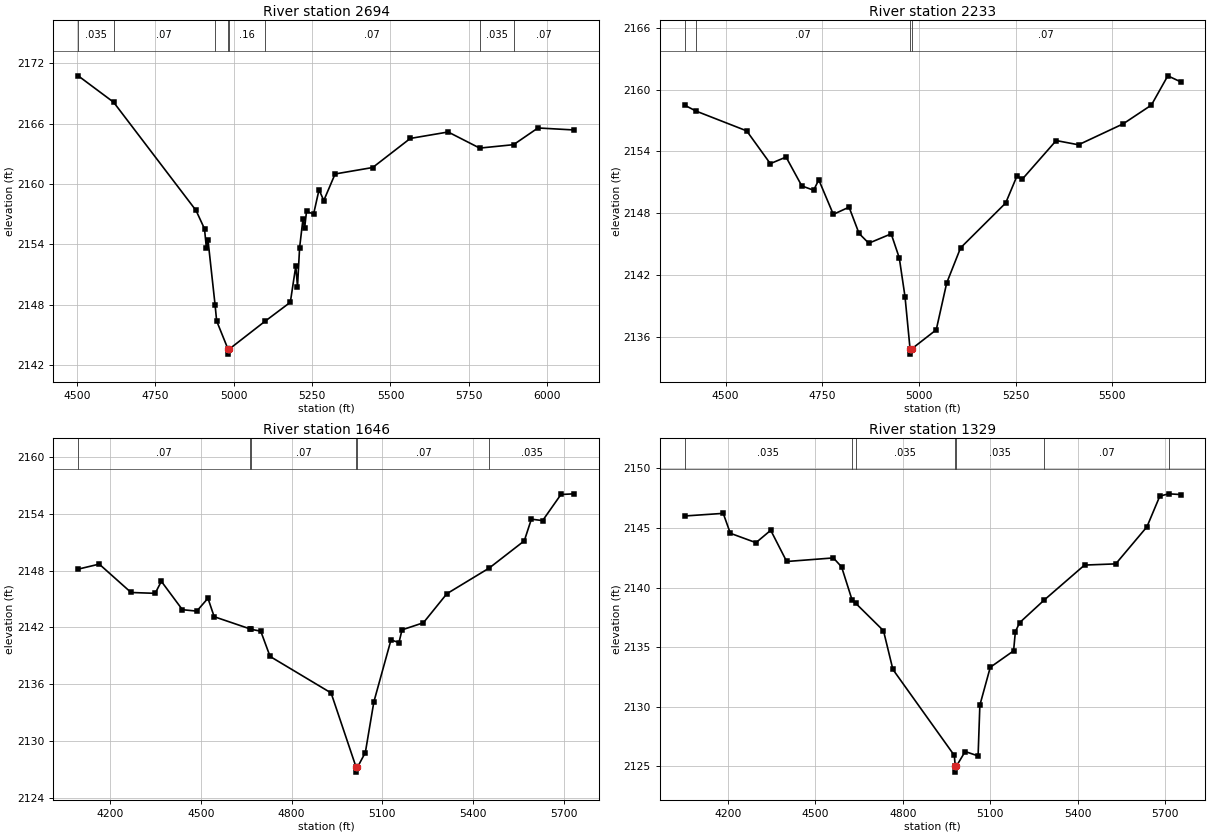
Type RM Length L Ch R = 1,2694,461,461,461
BEGIN DESCRIPTION:
MULBERRY CREEK TRIBUTARY 23_1 3.0
END DESCRIPTION:
XS GIS Cut Line= 3
      1463980.80      6830661.63      1463505.47      6830517.84
      1462520.23      6830975.37
#Sta/Elev= 30
  4503.4 2170.74  4616.3 2168.12  4879.5 2157.36  4906.5 2155.54  4912.4 2153.66
  4917.6 2154.42  4940.1 2148.02  4945.3 2146.38  4981.5 2143.59  4981.7 2143.09
  4985.5 2143.59  5099.1 2146.34  5180.4 2148.24  5197.8 2151.83  5203.3 2149.79
  5210.0 2153.66  5220.7 2156.50  5226.2 2155.65  5232.1 2157.27  5254.7 2157.01
  5272.0 2159.42  5287.2 2158.35  5323.3 2160.99  5443.3 2161.63  5563.3 2164.52
  5684.1 2165.16  5784.8 2163.56  5892.9 2163.90  5970.8 2165.56  6086.3 2165.36
#Mann=8,-1,0
  4503.4   0.035       0  4616.3    0.07       0  4940.1    0.16       0
  4981.5    0.07       0  4985.5    0.16       0  5099.1    0.07       0
  5784.8   0.035       0  5892.9    0.07       0
Bank Sta=4981.5,4985.5
Exp/Cntr=0.3,0.1

Type RM Length L Ch R = 1,2233,587,587,587
BEGIN DESCRIPTION:
Mapping XS ef8362da
END DESCRIPTION:
XS GIS Cut Line= 4
      1463882.43      6830177.92      1463379.87      6830081.58
      1463181.96      6830216.99      1462899.07      6830665.99
#Sta/Elev= 30
  4394.3 2158.49  4423.7 2157.92  4554.6 2156.00  4615.7 2152.82  4656.4 2153.46
  4697.1 2150.66  4727.7 2150.24  4741.0 2151.25  4778.6 2147.90  4819.3 2148.60
  4845.1 2146.05  4870.2 2145.10  4928.2 2146.01  4949.1 2143.68  4964.0 2139.90
  4977.0 2134.84  4977.2 2134.34  4981.0 2134.84  5044.7 2136.70  5071.7 2141.24
  5107.6 2144.65  5224.2 2149.00  5253.4 2151.62  5266.6 2151.29  5354.8 2155.06
  5412.5 2154.65  5527.9 2156.68  5600.9 2158.50  5643.4 2161.34  5676.5 2160.76
#Mann=4,-1,0
  4394.3   0.035       0  4423.7    0.07       0  4977.0    0.07       0
  4981.0    0.07       0
Bank Sta=4977,4981
Exp/Cntr=0.3,0.1

Type RM Length L Ch R = 1,1646,317,317,317
BEGIN DESCRIPTION:
MULBERRY CREEK TRIBUTARY 23_1 2.0
END DESCRIPTION:
XS GIS Cut Line= 4
      1463682.65      6829882.35      1462970.88      6829715.26
      1462756.03      6829938.78      1462669.23      6830531.19
#Sta/Elev= 30
  4094.3 2148.16  4163.8 2148.69  4269.1 2145.69  4348.7 2145.60  4369.2 2146.87
  4438.8 2143.87  4486.3 2143.72  4523.3 2145.08  4543.9 2143.13  4660.8 2141.86
  4664.0 2141.81  4697.9 2141.60  4728.7 2138.93  4930.5 2135.07  5013.4 2127.20
  5013.6 2126.70  5017.4 2127.20  5043.7 2128.77  5072.0 2134.14  5128.6 2140.68
  5154.9 2140.39  5165.0 2141.74  5235.7 2142.49  5313.3 2145.56  5453.6 2148.28
  5569.3 2151.15  5592.7 2153.44  5629.9 2153.29  5690.5 2156.05  5734.2 2156.12
#Mann=6,-1,0
  4094.3    0.07       0  4660.8   0.035       0  4664.0    0.07       0
  5013.4    0.07       0  5017.4    0.07       0  5453.6   0.035       0
Bank Sta=5013.4,5017.4
Exp/Cntr=0.3,0.1

Type RM Length L Ch R = 1,1329,0,0,0
BEGIN DESCRIPTION:
MULBERRY CREEK TRIBUTARY 23_1 1.0
END DESCRIPTION:
XS GIS Cut Line= 3
      1463634.52      6829795.20      1462705.93      6829598.47
      1462270.83      6830214.14
#Sta/Elev= 30
  4050.8 2146.01  4183.2 2146.23  4207.5 2144.56  4295.6 2143.77  4346.3 2144.81
  4401.1 2142.19  4561.4 2142.49  4589.6 2141.74  4625.8 2138.95  4637.8 2138.69
  4733.5 2136.38  4765.8 2133.13  4976.8 2125.91  4979.9 2125.01  4980.1 2124.51
  4983.9 2125.01  5014.0 2126.24  5058.4 2125.87  5064.5 2130.13  5100.2 2133.31
  5180.3 2134.69  5186.4 2136.30  5201.2 2137.06  5285.7 2138.96  5424.0 2141.89
  5531.1 2141.99  5638.2 2145.10  5682.5 2147.68  5713.3 2147.87  5753.9 2147.81
#Mann=7,-1,0
  4050.8   0.035       0  4625.8    0.07       0  4637.8   0.035       0
  4979.9   0.035       0  4983.9   0.035       0  5285.7    0.07       0
  5713.3   0.035       0
Bank Sta=4979.9,4983.9
Exp/Cntr=0.3,0.1

Chan Stop Cuts=-1