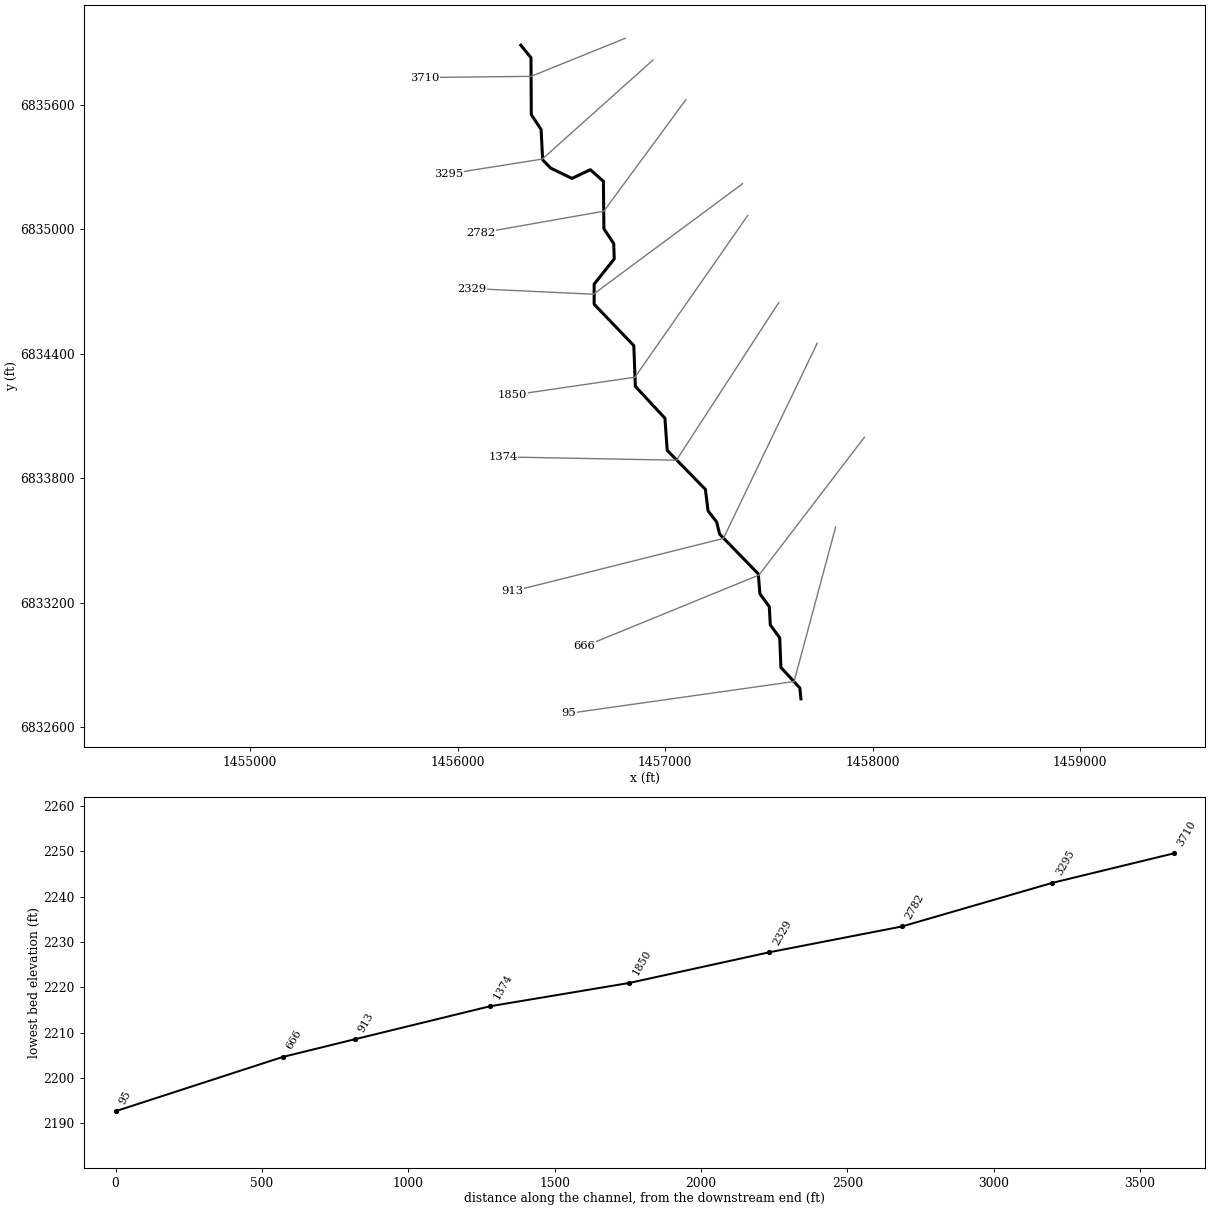
--- MULBERRY CREEK TRIBUTARY 23_2.prj (project) ---

Proj Title=MULBERRY CREEK TRIBUTARY 23_2 Base Level Engineering
Current Plan=p01
Default Exp/Contr=0.3,0.1
English Units
Geom File=g01
Flow File=f01
Plan File=p01
BEGIN DESCRIPTION:
MULBERRY CREEK TRIBUTARY 23_2
END DESCRIPTION:

--- MULBERRY CREEK TRIBUTARY 23_2.p01 (plan) ---

Plan Title=Multiple Run
Short Identifier=Multiple
Geom File=g01
Flow File=f01
Subcritical Flow
K Sum by GR= 0
Std Step Tol= 0.01
Critical Tol= 0.01
Num of Std Step Trials= 20
Max Error Tol= 0.3
Flow Tol Ratio= 0.001
Split Flow NTrial= 30
Split Flow Tol= 0.02
Split Flow Ratio= 0.02
Log Output Level= 0
Friction Slope Method= 1
Unsteady Friction Slope Method= 2
Unsteady Bridges Friction Slope Method= 1
Parabolic Critical Depth
Global Vel Dist=  1 , 1 , 1
Global Log Level= 0
CheckData=True
Encroach Param= -1, 0, 0, 0
BEGIN DESCRIPTION:
Multiple Run
END DESCRIPTION:

--- MULBERRY CREEK TRIBUTARY 23_2.f01 (steady flow) ---

Flow Title=Multiple
Number of Profiles=7
Profile Names=10-year,25-year,50-year,1pct_min,100-year,1pct_plu,500-year
River Rch & RM= MULBERRY CREEK T,Reach-1,3710
     276     395     495     310     619    1236     978
River Rch & RM= MULBERRY CREEK T,Reach-1,1850
     355     515     653     413     823    1643    1325
Boundary for River Rch & Prof#=MULBERRY CREEK T,Reach-1,1
Up Type=0
Dn Type=3
Dn Slope=0.005
Boundary for River Rch & Prof#=MULBERRY CREEK T,Reach-1,2
Up Type=0
Dn Type=3
Dn Slope=0.005
Boundary for River Rch & Prof#=MULBERRY CREEK T,Reach-1,3
Up Type=0
Dn Type=3
Dn Slope=0.005
Boundary for River Rch & Prof#=MULBERRY CREEK T,Reach-1,4
Up Type=0
Dn Type=3
Dn Slope=0.005
Boundary for River Rch & Prof#=MULBERRY CREEK T,Reach-1,5
Up Type=0
Dn Type=3
Dn Slope=0.005
Boundary for River Rch & Prof#=MULBERRY CREEK T,Reach-1,6
Up Type=0
Dn Type=3
Dn Slope=0.005
Boundary for River Rch & Prof#=MULBERRY CREEK T,Reach-1,7
Up Type=0
Dn Type=3
Dn Slope=0.005

--- MULBERRY CREEK TRIBUTARY 23_2.g01 (geometry) ---

Geom Title=Existing Conditions

River Reach=MULBERRY CREEK T,Reach-1
Reach XY= 30
      1456305.00      6835888.00      1456354.04      6835827.60
      1456355.52      6835553.22      1456402.73      6835482.06
      1456410.36      6835335.30      1456448.62      6835295.98
      1456551.69      6835246.07      1456639.78      6835288.05
      1456703.02      6835232.38      1456705.52      6835003.22
      1456752.84      6834932.02      1456755.21      6834858.05
      1456658.47      6834736.50      1456658.46      6834639.50
      1456849.54      6834440.45      1456857.06      6834243.85
      1456999.53      6834090.45      1457010.47      6833935.55
      1457194.48      6833747.79      1457207.33      6833643.97
      1457248.86      6833590.17      1457263.14      6833531.94
      1457449.48      6833340.43      1457457.36      6833243.98
      1457502.65      6833182.03      1457507.36      6833093.98
      1457552.73      6833032.06      1457558.54      6832889.47
      1457649.67      6832790.51      1457655.00      6832738.00

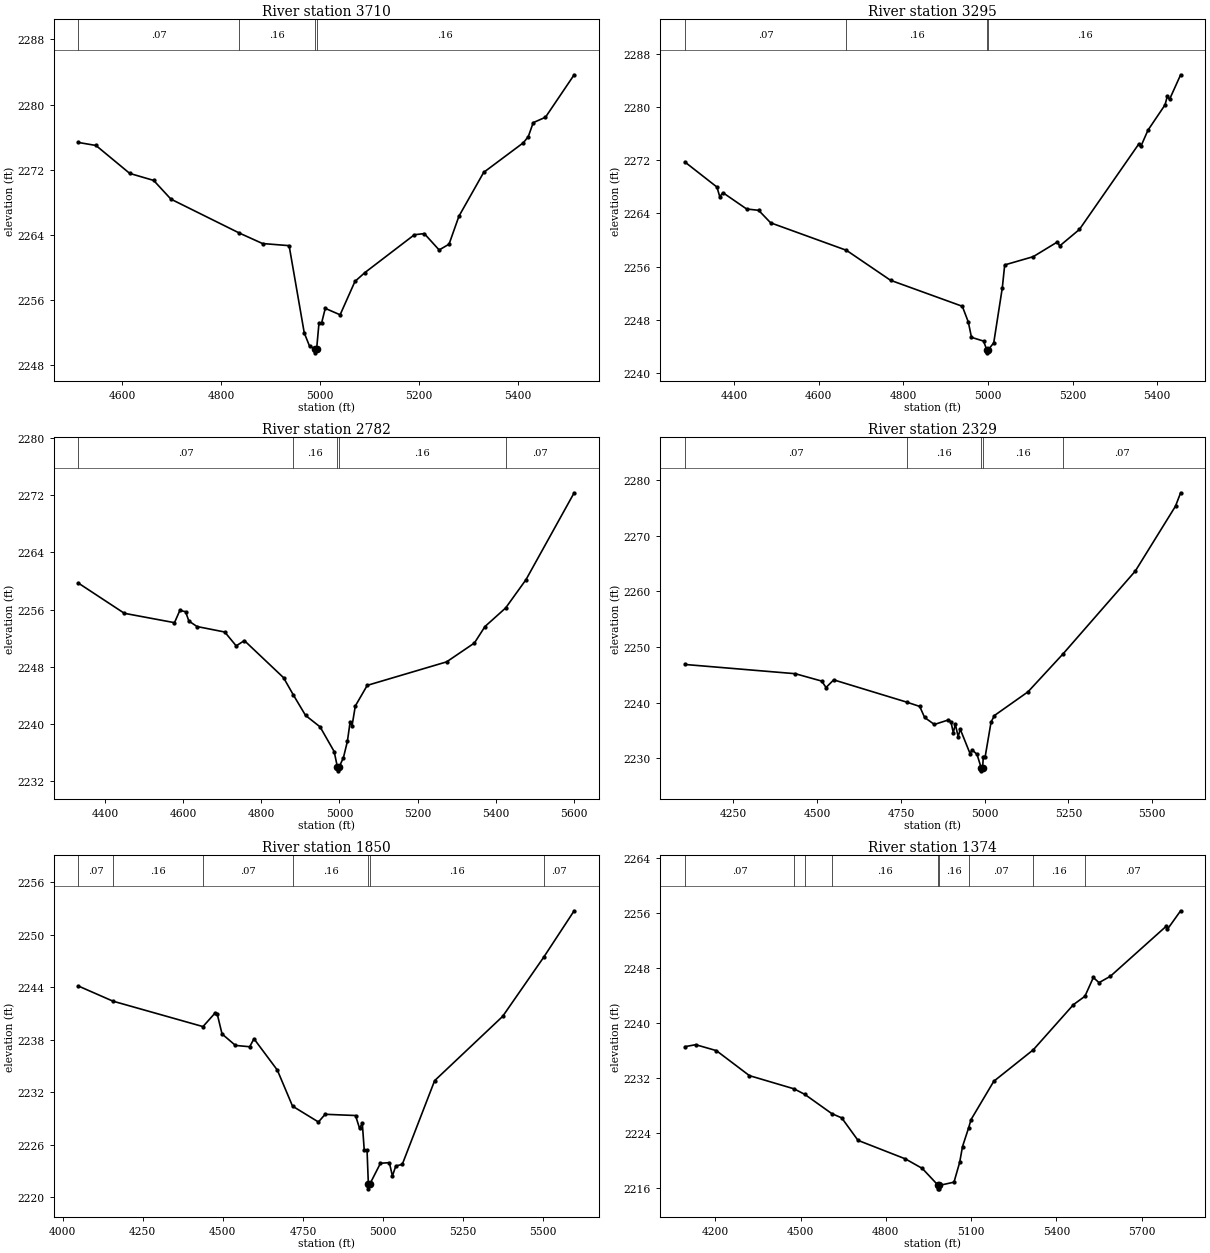
Type RM Length L Ch R = 1,3710,415,415,415
BEGIN DESCRIPTION:
MULBERRY CREEK TRIBUTARY 23_2 8.0
END DESCRIPTION:
XS GIS Cut Line= 3
      1456807.95      6835921.15      1456355.00      6835738.00
      1455842.30      6835732.36
#Sta/Elev= 30
  4511.5 2275.35  4547.0 2274.98  4615.2 2271.55  4663.5 2270.69  4698.4 2268.39
  4836.8 2264.22  4883.4 2262.94  4937.1 2262.68  4967.7 2251.96  4978.5 2250.32
  4988.7 2250.02  4989.0 2249.52  4992.7 2250.02  4997.4 2253.16  5002.6 2253.16
  5010.1 2254.98  5040.1 2254.19  5070.1 2258.29  5090.1 2259.37  5190.1 2264.02
  5210.1 2264.16  5240.1 2262.15  5260.1 2262.86  5280.1 2266.30  5330.1 2271.68
  5410.1 2275.31  5420.1 2276.06  5430.1 2277.78  5454.9 2278.45  5512.8 2283.66
#Mann=4,-1,0
  4511.5    0.07       0  4836.8    0.16       0  4988.7    0.07       0
  4992.7    0.16       0
Bank Sta=4988.7,4992.7
Exp/Cntr=0.3,0.1

Type RM Length L Ch R = 1,3295,513,513,513
BEGIN DESCRIPTION:
MULBERRY CREEK TRIBUTARY 23_2 7.0
END DESCRIPTION:
XS GIS Cut Line= 3
      1456942.55      6835817.01      1456408.45      6835339.25
      1455958.64      6835268.16
#Sta/Elev= 30
  4283.4 2271.72  4359.2 2267.95  4365.9 2266.50  4373.4 2267.10  4429.4 2264.65
  4457.8 2264.45  4486.2 2262.57  4665.3 2258.44  4769.6 2253.93  4939.3 2250.02
  4953.5 2247.65  4961.0 2245.35  4989.4 2244.79  4997.0 2243.52  4997.2 2243.02
  5001.0 2243.52  5013.6 2244.52  5033.9 2252.82  5039.5 2256.24  5107.0 2257.48
  5164.3 2259.70  5169.4 2259.09  5216.1 2261.57  5356.6 2274.43  5361.6 2274.09
  5378.1 2276.49  5418.6 2280.31  5424.0 2281.63  5429.1 2281.12  5455.4 2284.83
#Mann=4,-1,0
  4283.4    0.07       0  4665.3    0.16       0  4997.0    0.07       0
  5001.0    0.16       0
Bank Sta=4997,5001
Exp/Cntr=0.3,0.1

Type RM Length L Ch R = 1,2782,453,453,453
BEGIN DESCRIPTION:
MULBERRY CREEK TRIBUTARY 23_2 6.0
END DESCRIPTION:
XS GIS Cut Line= 3
      1457100.96      6835626.03      1456705.00      6835088.00
      1456113.56      6834983.67
#Sta/Elev= 30
  4331.9 2259.71  4449.5 2255.48  4577.8 2254.17  4591.5 2255.88  4606.1 2255.71
  4614.6 2254.40  4635.4 2253.63  4706.4 2252.86  4735.7 2250.92  4756.6 2251.66
  4856.8 2246.47  4881.6 2244.08  4913.2 2241.18  4950.3 2239.58  4986.4 2236.12
  4994.8 2233.92  4995.1 2233.42  4998.8 2233.92  5010.1 2235.27  5020.2 2237.54
  5027.0 2240.19  5032.1 2239.71  5040.5 2242.50  5071.0 2245.39  5274.1 2248.68
  5345.2 2251.32  5372.3 2253.63  5425.2 2256.23  5477.2 2260.19  5600.5 2272.36
#Mann=5,-1,0
  4331.9    0.07       0  4881.6    0.16       0  4994.8    0.07       0
  4998.8    0.16       0  5425.2    0.07       0
Bank Sta=4994.8,4998.8
Exp/Cntr=0.3,0.1

Type RM Length L Ch R = 1,2329,479,479,479
BEGIN DESCRIPTION:
MULBERRY CREEK TRIBUTARY 23_2 5.0
END DESCRIPTION:
XS GIS Cut Line= 3
      1457373.42      6835220.28      1456655.00      6834688.00
      1456069.76      6834715.42
#Sta/Elev= 30
  4105.0 2246.85  4434.6 2245.19  4513.7 2243.86  4526.4 2242.71  4549.4 2244.08
  4766.9 2240.09  4806.1 2239.31  4820.7 2237.33  4849.8 2236.07  4891.6 2236.88
  4899.6 2236.48  4906.3 2234.60  4912.5 2236.09  4920.9 2233.87  4927.1 2235.22
  4956.3 2230.85  4962.6 2231.52  4977.2 2230.69  4989.8 2228.24  4990.1 2227.74
  4993.8 2228.24  4996.0 2230.31  5001.6 2230.31  5019.1 2236.50  5029.2 2237.68
  5129.3 2241.93  5234.9 2248.81  5449.6 2263.62  5569.7 2275.29  5585.0 2277.69
#Mann=5,-1,0
  4105.0    0.07       0  4766.9    0.16       0  4989.8    0.07       0
  4993.8    0.16       0  5234.9    0.07       0
Bank Sta=4989.8,4993.8
Exp/Cntr=0.3,0.1

Type RM Length L Ch R = 1,1850,476,476,476
BEGIN DESCRIPTION:
MULBERRY CREEK TRIBUTARY 23_2 4.0
END DESCRIPTION:
XS GIS Cut Line= 3
      1457398.88      6835067.60      1456855.00      6834288.00
      1456263.93      6834201.75
#Sta/Elev= 30
  4049.0 2244.12  4157.1 2242.39  4438.0 2239.49  4475.3 2241.02  4482.7 2240.89
  4497.5 2238.65  4539.4 2237.34  4583.9 2237.19  4597.2 2238.10  4670.2 2234.52
  4717.6 2230.41  4798.5 2228.60  4819.4 2229.48  4914.2 2229.34  4926.7 2227.90
  4935.5 2228.43  4941.5 2225.38  4950.3 2225.35  4954.4 2221.47  4954.6 2220.97
  4958.4 2221.47  4992.1 2223.89  5019.8 2223.96  5029.5 2222.44  5040.0 2223.58
  5060.2 2223.76  5161.3 2233.32  5373.5 2240.65  5501.8 2247.41  5596.9 2252.71
#Mann=7,-1,0
  4049.0    0.07       0  4157.1    0.16       0  4438.0    0.07       0
  4717.6    0.16       0  4954.4    0.07       0  4958.4    0.16       0
  5501.8    0.07       0
Bank Sta=4954.4,4958.4
Exp/Cntr=0.3,0.1

Type RM Length L Ch R = 1,1374,461,461,461
BEGIN DESCRIPTION:
MULBERRY CREEK TRIBUTARY 23_2 3.0
END DESCRIPTION:
XS GIS Cut Line= 3
      1457548.51      6834648.37      1457055.00      6833888.00
      1456218.04      6833903.97
#Sta/Elev= 30
  4093.1 2236.50  4131.2 2236.79  4203.7 2235.93  4320.1 2232.29  4477.1 2230.37
  4515.1 2229.56  4610.1 2226.76  4644.7 2226.15  4702.0 2222.88  4868.4 2220.19
  4928.1 2218.80  4984.1 2216.33  4984.3 2215.83  4987.8 2215.83  4988.1 2216.33
  5039.6 2216.80  5059.6 2219.68  5069.6 2221.98  5091.2 2224.71  5099.6 2225.90
  5179.6 2231.47  5318.6 2236.05  5459.7 2242.61  5500.1 2243.83  5529.7 2246.56
  5549.7 2245.81  5589.7 2246.74  5785.4 2253.99  5790.4 2253.58  5836.7 2256.26
#Mann=9,-1,0
  4093.1    0.07       0  4477.1    0.16       0  4515.1    0.07       0
  4610.1    0.16       0  4984.1    0.07       0  4988.1    0.16       0
  5091.2    0.07       0  5318.6    0.16       0  5500.1    0.07       0
Bank Sta=4984.1,4988.1
Exp/Cntr=0.3,0.1

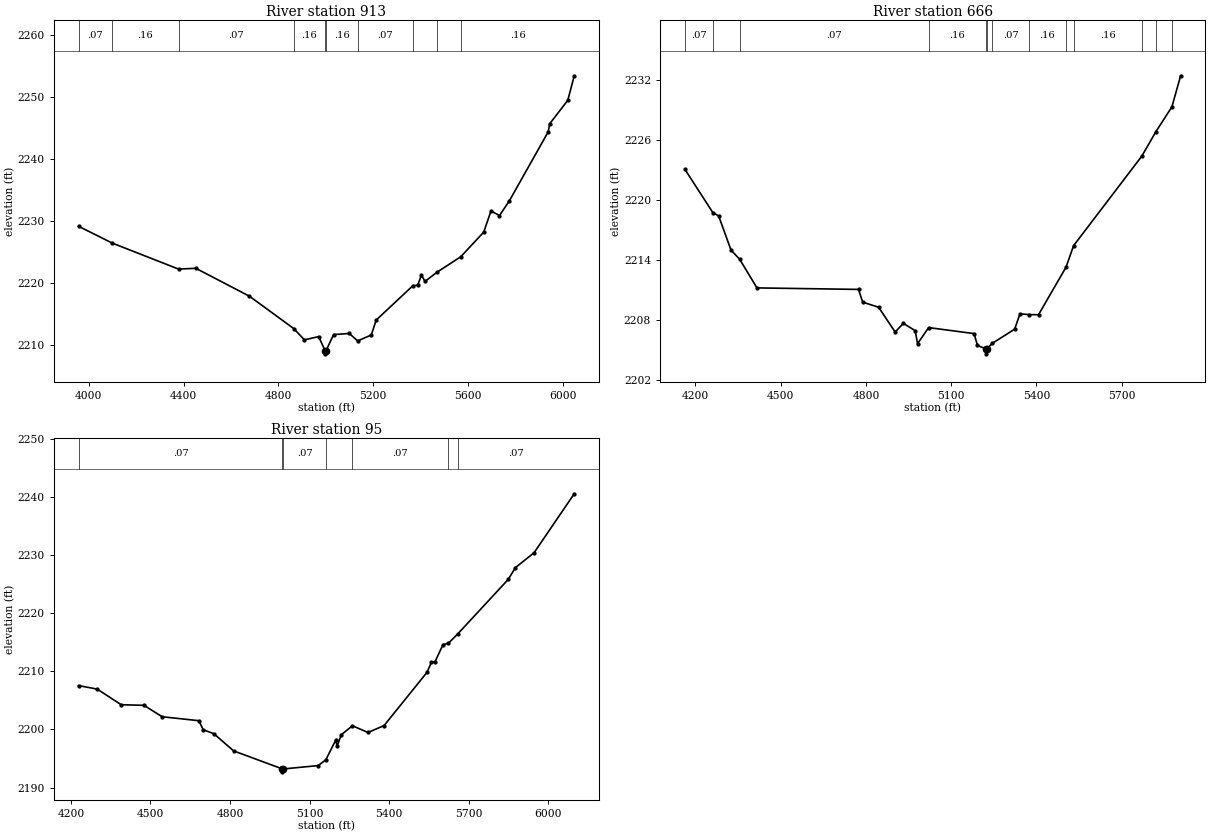
Type RM Length L Ch R = 1,913,247,247,247
BEGIN DESCRIPTION:
MULBERRY CREEK TRIBUTARY 23_2 2.0
END DESCRIPTION:
XS GIS Cut Line= 3
      1457733.27      6834451.49      1457281.29      6833511.18
      1456264.49      6833256.14
#Sta/Elev= 30
  3956.7 2229.12  4098.4 2226.42  4379.0 2222.22  4451.7 2222.35  4678.0 2217.85
  4864.9 2212.64  4909.9 2210.82  4970.2 2211.35  4997.0 2209.07  4997.2 2208.57
  5001.0 2209.07  5032.9 2211.67  5099.3 2211.85  5134.5 2210.65  5192.1 2211.61
  5212.7 2214.01  5366.9 2219.52  5387.9 2219.63  5403.5 2221.23  5418.9 2220.24
  5468.2 2221.69  5569.6 2224.21  5666.3 2228.17  5697.2 2231.59  5732.9 2230.84
  5774.0 2233.18  5938.7 2244.34  5944.7 2245.63  6021.1 2249.40  6048.3 2253.36
#Mann=10,-1,0
  3956.7    0.07       0  4098.4    0.16       0  4379.0    0.07       0
  4864.9    0.16       0  4997.0    0.07       0  5001.0    0.16       0
  5134.5    0.07       0  5366.9    0.16       0  5468.2    0.07       0
  5569.6    0.16       0
Bank Sta=4997,5001
Exp/Cntr=0.3,0.1

Type RM Length L Ch R = 1,666,571,571,571
BEGIN DESCRIPTION:
Mapping XS 147d9936
END DESCRIPTION:
XS GIS Cut Line= 3
      1457960.90      6833998.74      1457453.11      6833334.71
      1456611.97      6832990.96
#Sta/Elev= 30
  4163.0 2223.07  4261.4 2218.75  4281.6 2218.43  4325.2 2215.02  4355.5 2214.10
  4416.7 2211.24  4774.0 2211.09  4788.6 2209.82  4844.7 2209.31  4902.8 2206.84
  4931.8 2207.70  4973.5 2206.97  4981.7 2205.67  5020.7 2207.28  5180.5 2206.68
  5192.6 2205.50  5221.7 2205.16  5222.0 2204.66  5225.7 2205.16  5244.7 2205.71
  5323.5 2207.12  5342.1 2208.65  5373.2 2208.58  5407.4 2208.56  5504.1 2213.30
  5531.0 2215.46  5771.2 2224.40  5820.7 2226.84  5876.9 2229.31  5907.6 2232.41
#Mann=13,-1,0
  4163.0    0.07       0  4261.4    0.16       0  4355.5    0.07       0
  5020.7    0.16       0  5221.7    0.07       0  5225.7    0.16       0
  5244.7    0.07       0  5373.2    0.16       0  5504.1    0.07       0
  5531.0    0.16       0  5771.2    0.07       0  5820.7    0.16       0
  5876.9    0.07       0
Bank Sta=5221.7,5225.7
Exp/Cntr=0.3,0.1

Type RM Length L Ch R = 1,95,0,0,0
BEGIN DESCRIPTION:
MULBERRY CREEK TRIBUTARY 23_2 1.0
END DESCRIPTION:
XS GIS Cut Line= 3
      1457822.33      6833566.20      1457621.85      6832821.41
      1456535.23      6832667.96
#Sta/Elev= 30
  4228.7 2207.56  4299.3 2206.95  4389.5 2204.26  4475.4 2204.16  4544.1 2202.19
  4682.5 2201.51  4698.7 2199.95  4738.6 2199.28  4813.4 2196.31  4997.2 2193.20
  4997.4 2192.70  5001.2 2193.20  5132.4 2193.78  5161.0 2194.77  5198.5 2198.18
  5203.5 2197.10  5219.0 2199.07  5261.1 2200.64  5320.0 2199.48  5380.6 2200.67
  5542.2 2209.83  5559.0 2211.55  5572.5 2211.65  5602.8 2214.62  5623.0 2214.84
  5657.7 2216.43  5848.5 2225.84  5875.5 2227.87  5946.1 2230.45  6097.4 2240.60
#Mann=7,-1,0
  4228.7    0.07       0  4997.2    0.07       0  5001.2    0.07       0
  5161.0    0.16       0  5261.1    0.07       0  5623.0    0.16       0
  5657.7    0.07       0
Bank Sta=4997.2,5001.2
Exp/Cntr=0.3,0.1

Chan Stop Cuts=-1