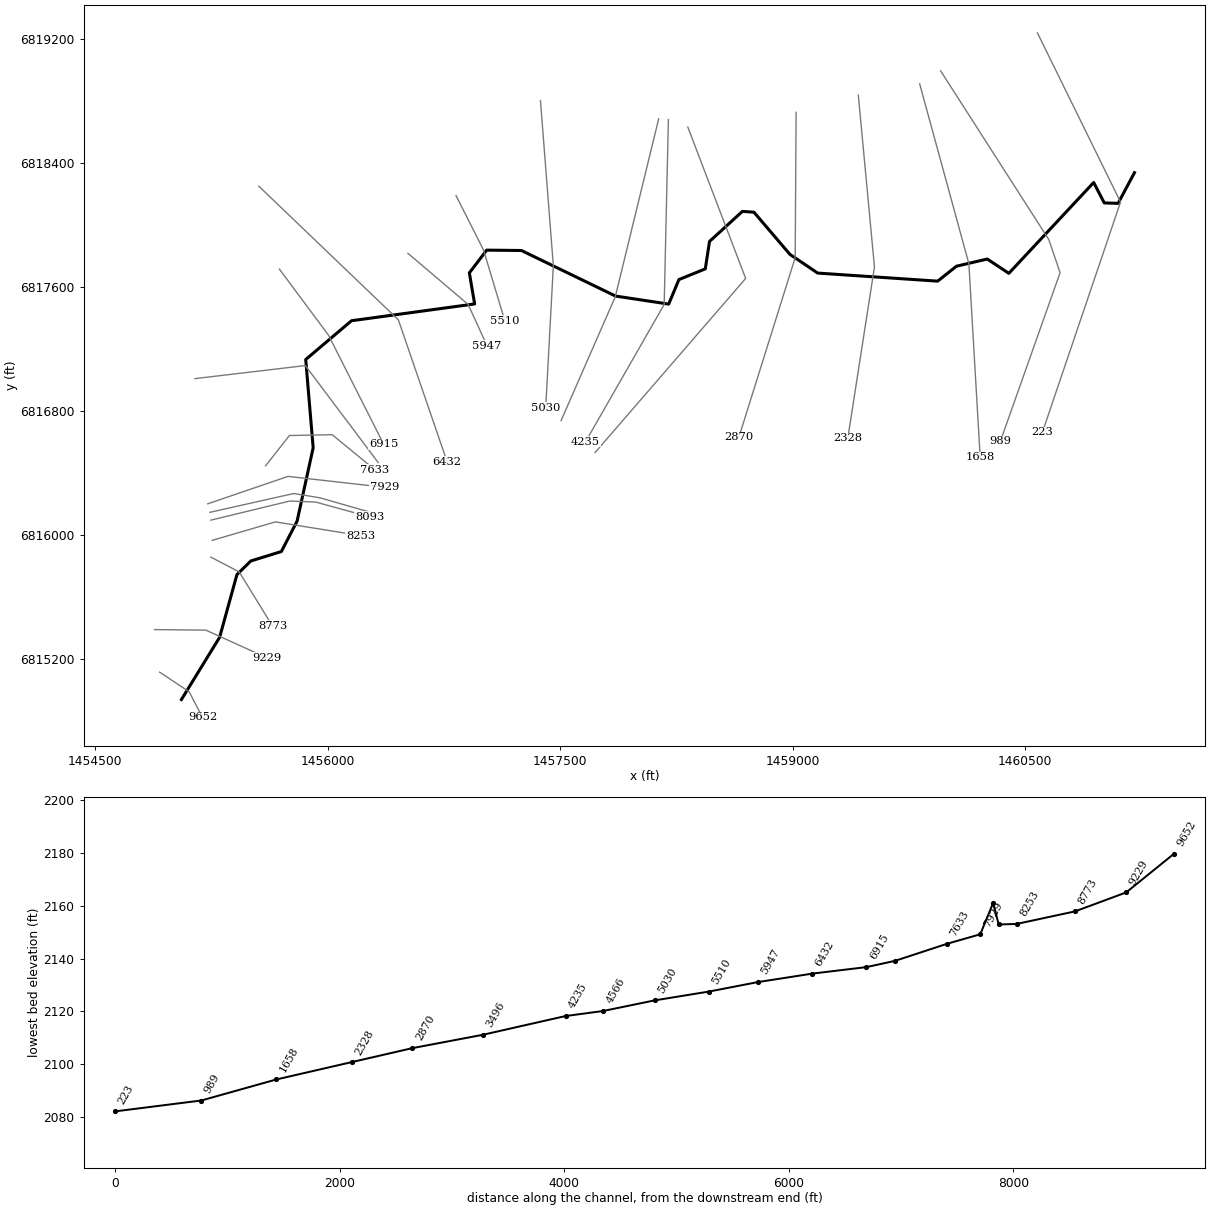
--- MULBERRY CREEK TRIBUTARY 24.prj (project) ---

Proj Title=MULBERRY CREEK TRIBUTARY 24 Base Level Engineering
Current Plan=p01
Default Exp/Contr=0.3,0.1
English Units
Geom File=g01
Flow File=f01
Plan File=p01
Y Axis Title=Elevation
X Axis Title(PF)=Main Channel Distance
X Axis Title(XS)=Station
BEGIN DESCRIPTION:
MULBERRY CREEK TRIBUTARY 24
END DESCRIPTION:
DSS Export Rating Curves= 0
DSS Export Rating Curve Sorted= 0
DSS Export Volume Flow Curves= 0
DXF OffsetX= 0
DXF OffsetY= 0
DXF ScaleX= 1
DXF ScaleY= 10

--- MULBERRY CREEK TRIBUTARY 24.p01 (plan) ---

Plan Title=Multiple Run
Short Identifier=Multiple
Geom File=g01
Flow File=f01
Subcritical Flow
K Sum by GR= 0
Std Step Tol= 0.01
Critical Tol= 0.01
Num of Std Step Trials= 20
Max Error Tol= 0.3
Flow Tol Ratio= 0.001
Split Flow NTrial= 30
Split Flow Tol= 0.02
Split Flow Ratio= 0.02
Log Output Level= 0
Friction Slope Method= 1
Unsteady Friction Slope Method= 2
Unsteady Bridges Friction Slope Method= 1
Parabolic Critical Depth
Global Vel Dist=  1 , 1 , 1
Global Log Level= 0
CheckData=True
Encroach Param= -1, 0, 0, 0
BEGIN DESCRIPTION:
Multiple Run
END DESCRIPTION:

--- MULBERRY CREEK TRIBUTARY 24.f01 (steady flow) ---

Flow Title=Multiple
Number of Profiles=7
Profile Names=10-year,25-year,50-year,1pct_min,100-year,1pct_plu,500-year
River Rch & RM= MULBERRY CREEK T,Reach-1,9652
     436     643     826     528    1054    2103    1738
River Rch & RM= MULBERRY CREEK T,Reach-1,9229
     649     978    1272     824    1644    3280    2779
River Rch & RM= MULBERRY CREEK T,Reach-1,6915
     711    1069    1389     897    1790    3572    3010
Boundary for River Rch & Prof#=MULBERRY CREEK T,Reach-1,1
Up Type=0
Dn Type=3
Dn Slope=0.005
Boundary for River Rch & Prof#=MULBERRY CREEK T,Reach-1,2
Up Type=0
Dn Type=3
Dn Slope=0.005
Boundary for River Rch & Prof#=MULBERRY CREEK T,Reach-1,3
Up Type=0
Dn Type=3
Dn Slope=0.005
Boundary for River Rch & Prof#=MULBERRY CREEK T,Reach-1,4
Up Type=0
Dn Type=3
Dn Slope=0.005
Boundary for River Rch & Prof#=MULBERRY CREEK T,Reach-1,5
Up Type=0
Dn Type=3
Dn Slope=0.005
Boundary for River Rch & Prof#=MULBERRY CREEK T,Reach-1,6
Up Type=0
Dn Type=3
Dn Slope=0.005
Boundary for River Rch & Prof#=MULBERRY CREEK T,Reach-1,7
Up Type=0
Dn Type=3
Dn Slope=0.005

--- MULBERRY CREEK TRIBUTARY 24.g01 (geometry) ---

Geom Title=Existing Conditions
Program Version=4.10

River Reach=MULBERRY CREEK T,Reach-1
Reach XY= 30
        1455055.        6814938.      1455301.45      6815339.47
      1455413.13      6815744.07      1455502.69      6815832.18
      1455699.89      6815893.11      1455801.44      6816089.47
       1455905.2      6816562.92      1455857.06      6817132.15
      1456152.55      6817382.53       1456947.1      6817490.91
      1456913.04      6817691.32      1457024.88      6817838.09
      1457249.06      6817835.74      1457856.56      6817541.76
      1458199.35      6817489.96      1458265.37      6817648.16
      1458435.59      6817717.36      1458462.82      6817894.19
      1458675.21      6818088.28      1458749.53       6818082.9
      1458981.53      6817811.01      1459160.86      6817690.06
      1459935.02      6817637.96      1460056.47      6817734.44
       1460255.1      6817780.67      1460394.51      6817688.49
      1460941.79      6818274.64      1461010.11      6818142.96
      1461099.22      6818139.83        1461205.        6818338.

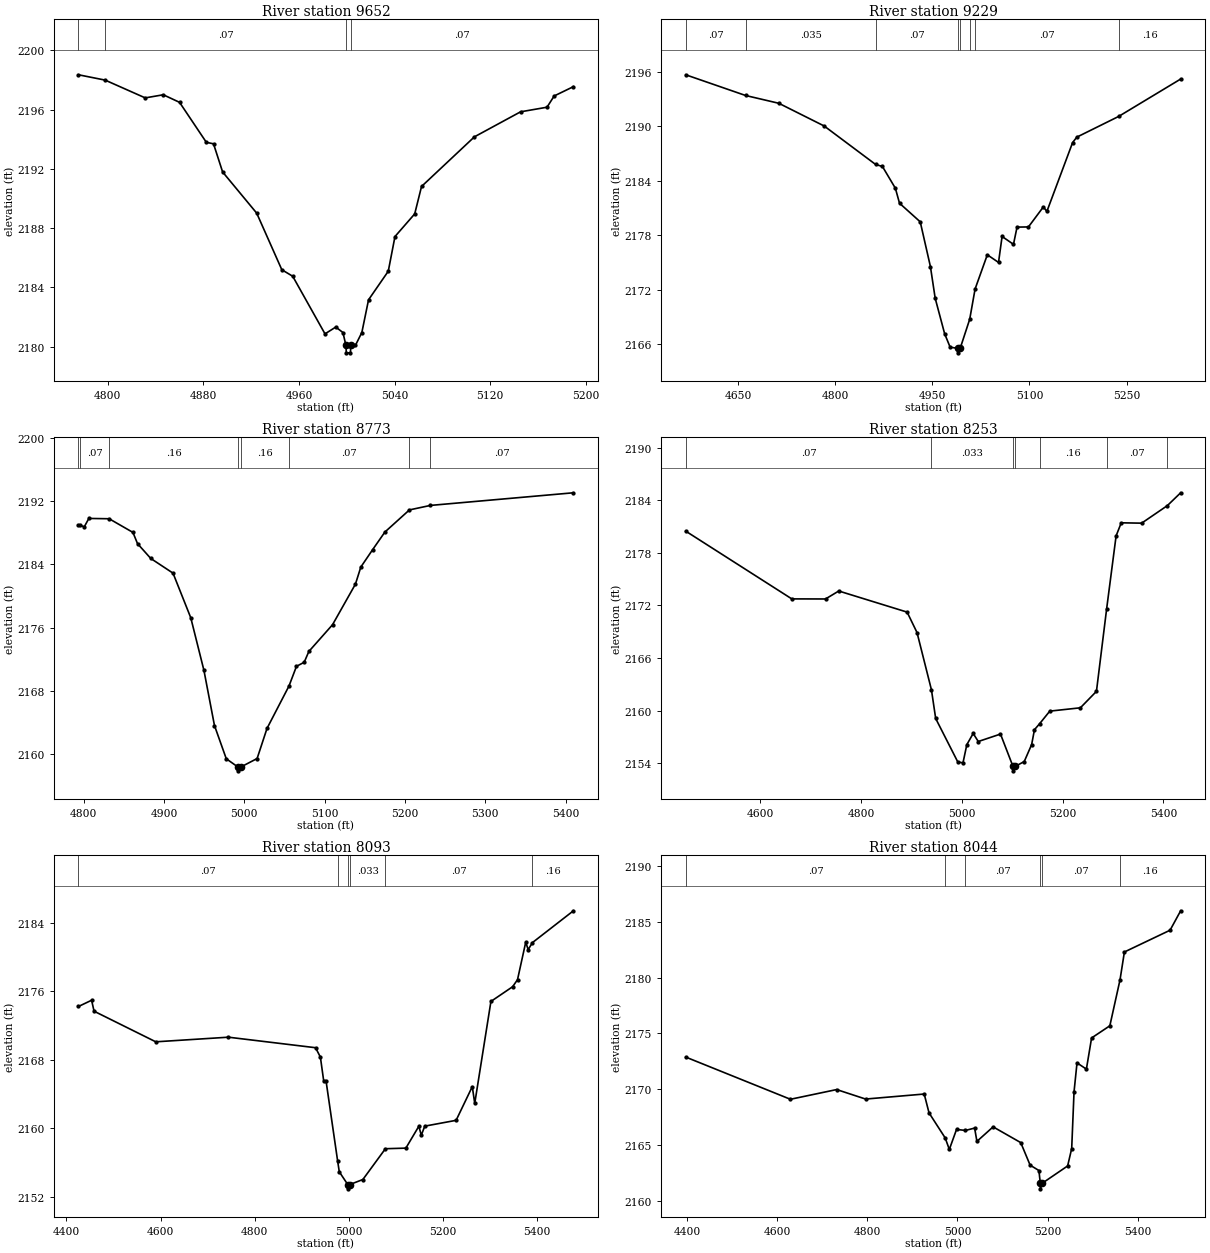
Type RM Length L Ch R = 1 ,9652    ,423,423,423
BEGIN DESCRIPTION:
MULBERRY CREEK TRIBUTARY 24 20.0
END DESCRIPTION:
XS GIS Cut Line= 3
      1454914.66      6815114.69        1455105.        6814988.
      1455190.37      6814823.71
#Sta/Elev= 30
  4775.7 2198.35    4798 2197.99  4831.5 2196.79  4846.6    2197  4860.2 2196.49
  4882.6 2193.79  4888.6 2193.69  4896.2 2191.79  4924.7 2189.01  4945.7 2185.19
  4954.8 2184.75  4981.8 2180.86  4990.8 2181.32  4996.8 2180.95  4999.3 2180.08
  4999.6 2179.58  5003.1 2179.58  5003.3 2180.08  5007.2 2180.08  5012.6 2180.95
  5018.2 2183.16  5034.7 2185.09  5040.3 2187.43  5056.8 2188.96  5062.5 2190.81
  5106.7 2194.16  5145.3 2195.85  5167.4 2196.16  5173.4 2196.92  5189.5 2197.55
#Mann= 4 ,-1 , 0
  4775.7     .16       0    4798     .07       0  4999.3     .07       0
  5003.3     .07       0
Bank Sta=4999.3,5003.3
XS Rating Curve= 0 ,0
Exp/Cntr=0.3,0.1

Type RM Length L Ch R = 1 ,9229    ,456,456,456
BEGIN DESCRIPTION:
Mapping XS 56c378e1
END DESCRIPTION:
XS GIS Cut Line= 3
      1454881.25       6815389.4      1455212.87      6815385.93
      1455606.96      6815207.12
#Sta/Elev= 30
  4569.2 2195.68  4661.6  2193.4    4713 2192.54    4783 2190.04  4862.5  2185.8
    4873 2185.58    4893 2183.18  4899.4 2181.53  4931.4 2179.48  4947.1 2174.56
  4954.5 2171.06  4969.1 2167.15  4977.6 2165.67    4989 2165.55  4989.2 2165.05
  4993.1 2165.55  5007.8 2168.75  5016.1 2172.08    5035 2175.85  5052.3 2175.01
  5057.8 2177.87  5075.4    2177  5080.9  2178.9  5098.5 2178.92  5121.5 2181.12
    5127 2180.63  5166.7 2188.21  5173.2 2188.81  5237.8 2191.09  5333.6 2195.21
#Mann= 8 ,-1 , 0
  4569.2     .07       0  4661.6    .035       0  4862.5     .07       0
    4989     .07       0  4993.1     .07       0  5007.8     .16       0
  5016.1     .07       0  5237.8     .16       0
Bank Sta=4989,4993.1
XS Rating Curve= 0 ,0
Exp/Cntr=0.3,0.1

Type RM Length L Ch R = 1 ,8773    ,520,520,520
BEGIN DESCRIPTION:
Mapping XS 7114c76b
END DESCRIPTION:
XS GIS Cut Line= 3
      1455244.94      6815857.09      1455427.99      6815761.52
      1455642.51      6815412.47
#Sta/Elev= 30
  4793.5 2188.94  4795.3 2188.94  4800.8 2188.78  4806.4 2189.83  4831.7 2189.79
  4861.3 2188.06    4867 2186.64  4883.5 2184.76  4911.2  2182.9  4933.3 2177.25
  4949.7 2170.58  4962.8  2163.6  4977.5 2159.39  4991.8 2158.36  4992.1 2157.86
  4995.9 2158.36  5015.9 2159.42  5028.2 2163.23  5055.6 2168.61  5064.9  2171.1
  5074.5 2171.61  5080.3 2172.98  5109.8 2176.37  5138.3 2181.51    5145 2183.67
  5159.6 2185.86    5175 2188.11  5205.5 2190.91  5231.7 2191.48  5409.7 2193.08
#Mann= 8 ,-1 , 0
  4793.5    .035       0  4795.3     .07       0  4831.7     .16       0
  4991.8     .07       0  4995.9     .16       0  5055.6     .07       0
  5205.5     .16       0  5231.7     .07       0
Bank Sta=4991.8,4995.9
XS Rating Curve= 0 ,0
Exp/Cntr=0.3,0.1

Type RM Length L Ch R = 1 ,8253    ,160,160,160
BEGIN DESCRIPTION:
Mapping XS 780da76e
END DESCRIPTION:
XS GIS Cut Line= 3
      1455253.55      6815965.17      1455661.57      6816084.54
      1456211.43      6815995.79
#Sta/Elev= 30
  4452.3 2180.49  4662.8 2172.75  4729.7 2172.74    4756 2173.65  4891.6 2171.24
  4911.3  2168.9  4939.9 2162.36  4948.3 2159.09  4992.3 2154.11  5002.5 2154.03
  5010.1  2156.1  5022.7 2157.38  5032.8 2156.46  5076.9 2157.31  5101.7 2153.61
  5101.9 2153.11  5105.8 2153.61    5124 2154.17  5138.7 2156.11  5144.3 2157.81
  5154.5 2158.49  5174.7 2159.93  5235.4 2160.31  5267.3 2162.19  5287.5 2171.61
  5306.3 2179.95  5316.5 2181.44    5357  2181.4  5407.9  2183.4  5434.4 2184.87
#Mann= 7 ,-1 , 0
  4452.3     .07       0  4939.9    .033       0  5101.7    .033       0
  5105.8    .033       0  5154.5     .16       0  5287.5     .07       0
  5407.9     .16       0
Bank Sta=5101.7,5105.8
XS Rating Curve= 0 ,0
Exp/Cntr=0.3,0.1

Type RM Length L Ch R = 1 ,8093    ,49,49,49
BEGIN DESCRIPTION:
Mapping XS de3cd8e8
END DESCRIPTION:
XS GIS Cut Line= 4
       1455245.3      6816095.82      1455753.98      6816219.08
      1455922.39      6816212.14      1456269.65      6816116.64
#Sta/Elev= 30
  4425.5 2174.22  4453.4 2174.95  4458.6 2173.67  4589.8 2170.09  4744.2 2170.63
  4929.4  2169.4  4939.7 2168.31  4946.9 2165.46  4951.9 2165.46  4976.3 2156.18
  4979.9 2154.89  4997.9  2153.4  4998.1  2152.9  5002.1  2153.4    5030 2153.99
  5077.9 2157.59  5121.4 2157.66    5149 2160.22  5154.2 2159.17  5161.6 2160.23
  5228.2 2160.91  5262.6 2164.85  5267.8 2162.89  5302.2 2174.81  5348.3 2176.53
  5358.7 2177.35  5376.2 2181.74  5381.4 2180.87  5390.5 2181.69  5477.6 2185.41
#Mann= 6 ,-1 , 0
  4425.5     .07       0  4976.3    .033       0  4997.9    .033       0
  5002.1    .033       0  5077.9     .07       0  5390.5     .16       0
Bank Sta=4997.9,5002.1
XS Rating Curve= 0 ,0
Exp/Cntr=0.3,0.1

Type RM Length L Ch R = 1 ,8044    ,115,115,115
BEGIN DESCRIPTION:
Mapping XS aa8bc90f
END DESCRIPTION:
XS GIS Cut Line= 4
      1455238.36      6816146.17      1455780.02      6816267.69
      1455948.43      6816239.92      1456306.04      6816137.49
#Sta/Elev= 30
  4397.2 2172.88  4629.5  2169.1    4732 2169.97  4796.2 2169.12  4926.2 2169.57
  4936.9 2167.88  4972.7 2165.64  4981.9 2164.61  4997.9  2166.4  5017.6 2166.31
    5038 2166.52  5043.1 2165.33    5079 2166.63  5140.3 2165.22  5161.1  2163.2
  5180.6 2162.72  5183.7 2161.58  5183.9 2161.08  5187.9 2161.58  5244.3 2163.13
  5253.3 2164.69  5258.5 2169.77  5265.1 2172.36  5285.9  2171.8  5297.4 2174.59
  5337.9 2175.68  5360.5  2179.8  5370.2 2182.29  5471.5 2184.24    5495 2185.98
#Mann= 6 ,-1 , 0
  4397.2     .07       0  4972.7    .033       0  5017.6     .07       0
  5183.7    .033       0  5187.9     .07       0  5360.5     .16       0
Bank Sta=5183.7,5187.9
XS Rating Curve= 0 ,0
Exp/Cntr=0.3,0.1

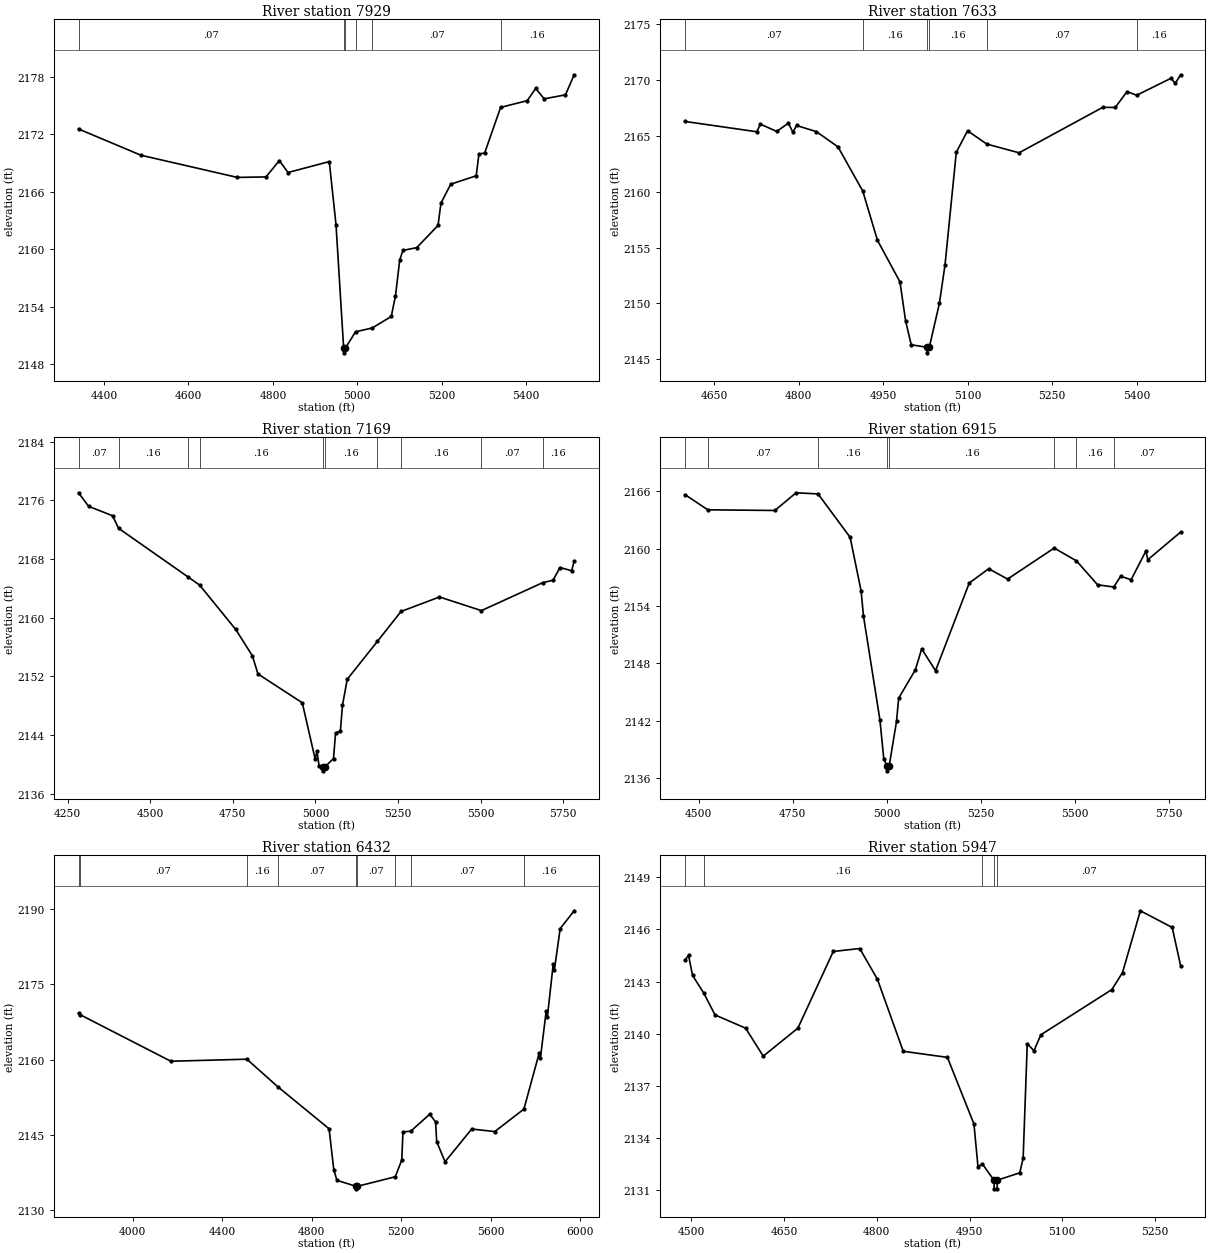
Type RM Length L Ch R = 1 ,7929    ,296,296,296
BEGIN DESCRIPTION:
Mapping XS 90f01267
END DESCRIPTION:
XS GIS Cut Line= 3
      1455224.89      6816201.05      1455743.08      6816378.12
      1456365.51       6816307.8
#Sta/Elev= 30
  4339.6 2172.54  4487.7  2169.8  4715.8 2167.49  4783.7 2167.54  4815.3 2169.25
  4835.8    2168  4933.6 2169.14  4949.5 2162.56  4967.6  2149.7  4967.8  2149.2
  4971.8  2149.7  4995.7 2151.39  5035.7  2151.8  5080.4 2152.99  5090.4 2155.15
  5100.5 2158.91  5108.2 2159.88  5140.7 2160.17  5191.1 2162.48  5198.1 2164.81
  5221.2 2166.78  5281.6 2167.66  5287.9  2169.9  5301.7 2170.05  5339.4 2174.79
  5402.4 2175.49  5422.5 2176.77  5442.6 2175.68    5493  2176.1  5513.6 2178.19
#Mann= 6 ,-1 , 0
  4339.6     .07       0  4967.6     .07       0  4971.8     .07       0
  4995.7     .16       0  5035.7     .07       0  5339.4     .16       0
Bank Sta=4967.6,4971.8
XS Rating Curve= 0 ,0
Exp/Cntr=0.3,0.1

Type RM Length L Ch R = 1 ,7633    ,464,464,464
BEGIN DESCRIPTION:
Mapping XS 9e38181a
END DESCRIPTION:
XS GIS Cut Line= 4
      1455598.27      6816446.49      1455751.94      6816641.83
      1456027.98      6816647.04      1456302.52      6816421.71
#Sta/Elev= 30
  4598.2 2166.26  4725.7 2165.34  4732.1 2166.02    4761 2165.37  4781.8 2166.11
  4789.8 2165.29  4796.2  2165.9  4831.5 2165.35  4869.8 2163.99  4913.8 2160.04
  4939.8 2155.65  4979.8 2151.93  4989.8 2148.45  4999.8 2146.31  5027.7 2146.09
    5028 2145.59  5031.9 2146.09  5049.8 2150.01  5059.8 2153.46  5079.8 2163.51
  5099.8 2165.43  5133.9 2164.24  5191.2 2163.46  5339.7 2167.52    5362 2167.51
  5382.8 2168.93  5399.9  2168.6    5461 2170.12  5468.3 2169.66    5478 2170.43
#Mann= 6 ,-1 , 0
  4598.2     .07       0  4913.8     .16       0  5027.7     .07       0
  5031.9     .16       0  5133.9     .07       0  5399.9     .16       0
Bank Sta=5027.7,5031.9
XS Rating Curve= 0 ,0
Exp/Cntr=0.3,0.1

Type RM Length L Ch R = 1 ,7169    ,254,254,254
BEGIN DESCRIPTION:
MULBERRY CREEK TRIBUTARY 24 15.0
END DESCRIPTION:
XS GIS Cut Line= 3
      1455142.58      6817009.02      1455854.52       6817093.2
      1456324.87      6816467.33
#Sta/Elev= 30
  4283.1 2177.04  4313.8 2175.19  4386.2 2173.91  4404.2  2172.2  4614.9 2165.55
  4649.4 2164.46  4758.8  2158.4  4809.2 2154.81  4826.1 2152.33  4960.2  2148.4
  4999.2 2140.72  5004.7 2141.79  5010.9 2139.81  5023.2 2139.62  5023.6 2139.12
  5027.8 2139.62  5054.7  2140.8  5060.9  2144.3  5075.5 2144.52  5081.8 2148.05
  5096.3 2151.61  5187.6 2156.78  5258.9 2160.85  5375.4 2162.83  5502.3 2160.97
  5687.1 2164.77  5719.1 2165.12  5739.9 2166.85  5775.3 2166.41  5782.9 2167.71
#Mann= 10 ,-1 , 0
  4283.1     .07       0  4404.2     .16       0  4614.9     .07       0
  4649.4     .16       0  5023.2     .07       0  5027.8     .16       0
  5187.6     .07       0  5258.9     .16       0  5502.3     .07       0
  5687.1     .16       0
Bank Sta=5023.2,5027.8
XS Rating Curve= 0 ,0
Exp/Cntr=0.3,0.1

Type RM Length L Ch R = 1 ,6915    ,483,483,483
BEGIN DESCRIPTION:
MULBERRY CREEK TRIBUTARY 24 14.0
END DESCRIPTION:
XS GIS Cut Line= 3
      1455687.68      6817715.21        1456005.        6817288.
      1456359.73      6816586.11
#Sta/Elev= 30
  4463.5 2165.64  4524.2 2164.05  4702.6 2163.98    4759 2165.83  4817.5 2165.71
  4902.8 2161.18  4932.1 2155.56  4938.3 2152.96  4982.1 2142.09  4992.5 2137.97
  5001.3 2137.26  5001.8 2136.76  5006.7 2137.26  5026.3 2141.94  5031.9 2144.35
  5076.5 2147.33  5093.2 2149.51  5130.1 2147.23  5219.8  2156.4  5271.5 2157.89
  5321.7 2156.81  5445.8 2160.05    5505 2158.71  5561.2 2156.21  5604.3 2155.98
  5622.5  2157.1  5650.4 2156.74  5689.4 2159.72    5695 2158.84  5782.1 2161.72
#Mann= 8 ,-1 , 0
  4463.5     .16       0  4524.2     .07       0  4817.5     .16       0
  5001.3     .07       0  5006.7     .16       0  5445.8     .07       0
    5505     .16       0  5604.3     .07       0
Bank Sta=5001.3,5006.7
XS Rating Curve= 0 ,0
Exp/Cntr=0.3,0.1

Type RM Length L Ch R = 1 ,6432    ,485,485,485
BEGIN DESCRIPTION:
MULBERRY CREEK TRIBUTARY 24 13.0
END DESCRIPTION:
XS GIS Cut Line= 3
      1455554.42       6818250.8        1456455.        6817388.
       1456769.7      6816472.14
#Sta/Elev= 30
  3757.4  2169.2  3763.8 2168.95  4170.1 2159.67  4509.8 2160.08  4647.4 2154.63
  4877.4 2146.24  4898.4 2138.13  4912.6 2135.98  4998.4 2134.79  4998.9 2134.29
  5003.8 2134.79  5173.2 2136.69  5202.4 2140.02  5207.7  2145.6  5242.9 2145.77
  5327.4 2149.14  5353.4  2147.6  5358.6 2143.68  5395.8 2139.67  5514.9 2146.19
  5617.9 2145.68  5748.3 2150.15  5816.8 2161.31  5822.1 2160.28    5848 2169.69
  5853.3 2168.49  5879.3 2178.96  5884.6 2177.84  5910.5 2186.06    5973  2189.6
#Mann= 9 ,-1 , 0
  3757.4     .16       0  3763.8     .07       0  4509.8     .16       0
  4647.4     .07       0  4998.4     .07       0  5003.8     .07       0
  5173.2     .16       0  5242.9     .07       0  5748.3     .16       0
Bank Sta=4998.4,5003.8
XS Rating Curve= 0 ,0
Exp/Cntr=0.3,0.1

Type RM Length L Ch R = 1 ,5947    ,437,437,437
BEGIN DESCRIPTION:
MULBERRY CREEK TRIBUTARY 24 12.0
END DESCRIPTION:
XS GIS Cut Line= 3
       1456516.6      6817817.49        1456905.        6817488.
      1457026.57      6817222.65
#Sta/Elev= 30
    4490 2144.23  4495.7 2144.51  4502.3 2143.35  4520.3 2142.34  4538.6 2141.08
    4588 2140.32  4616.5 2138.71  4672.5 2140.32  4729.7 2144.73  4772.5  2144.9
  4801.1 2143.13  4842.8 2138.99  4914.2 2138.64  4957.1 2134.81  4963.6 2132.36
  4970.8 2132.51  4989.4 2131.58  4989.9 2131.08  4994.5 2131.08  4994.9 2131.58
  5031.1    2132  5036.6 2132.83  5043.3 2139.43  5054.1 2139.02  5065.3 2139.94
  5180.1 2142.54  5197.3 2143.52  5226.1 2147.07  5277.6 2146.11  5291.2  2143.9
#Mann= 5 ,-1 , 0
    4490     .07       0  4520.3     .16       0  4970.8     .07       0
  4989.4     .07       0  4994.9     .07       0
Bank Sta=4989.4,4994.9
XS Rating Curve= 0 ,0
Exp/Cntr=0.3,0.1

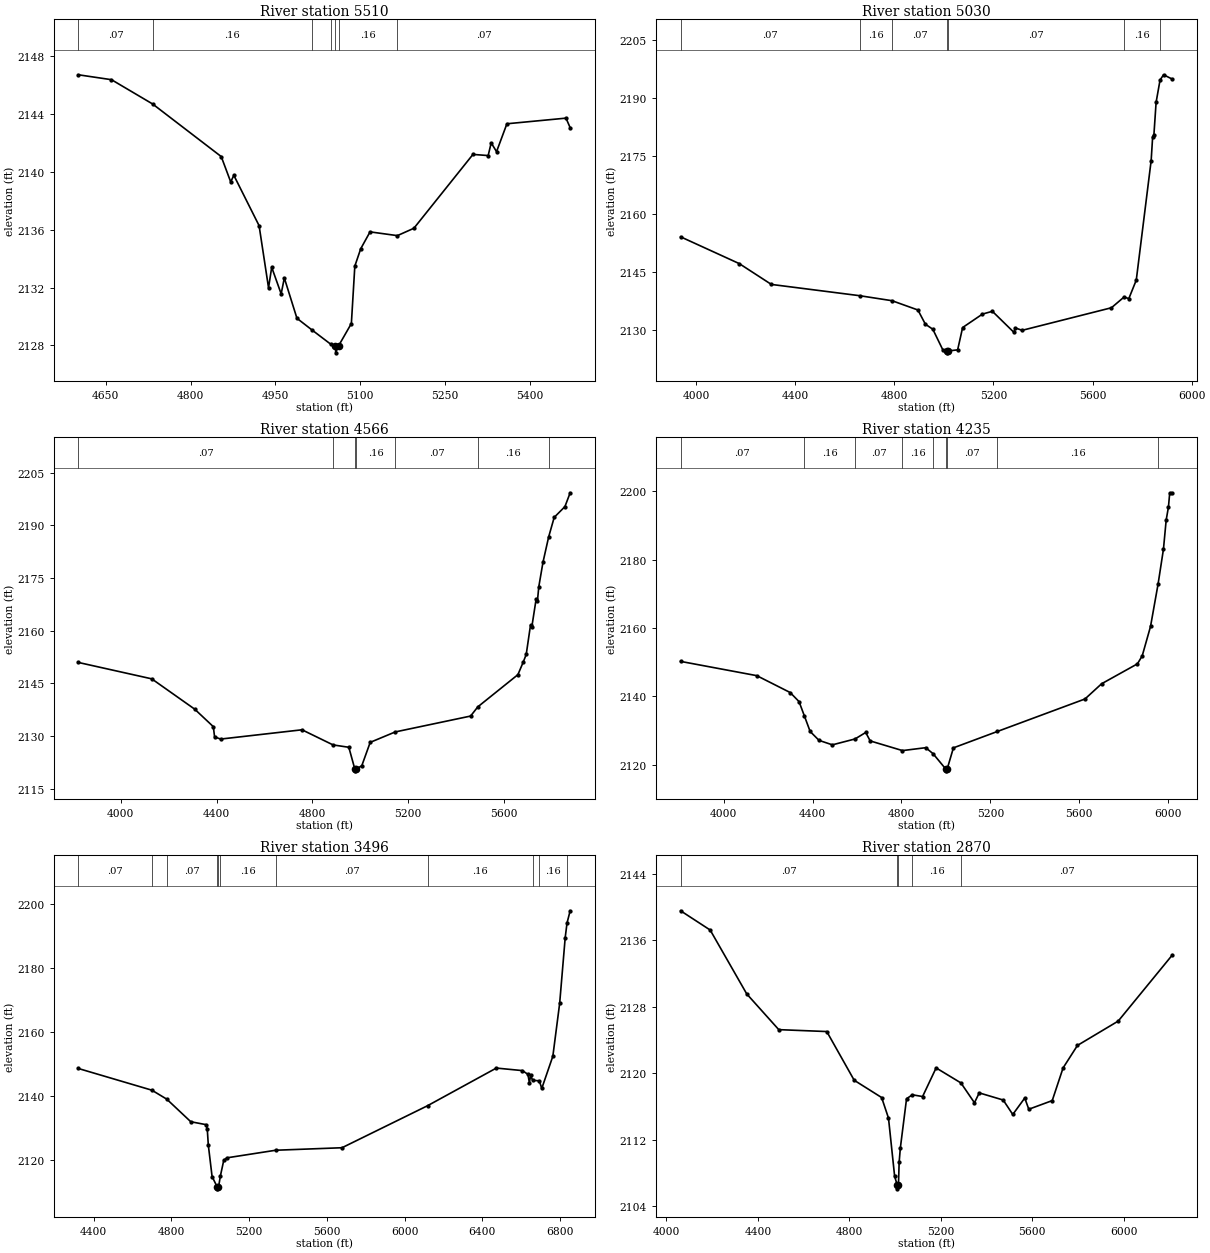
Type RM Length L Ch R = 1 ,5510    ,480,480,480
BEGIN DESCRIPTION:
MULBERRY CREEK TRIBUTARY 24 11.0
END DESCRIPTION:
XS GIS Cut Line= 3
      1456826.99      6818190.29        1457005.        6817838.
      1457141.37      6817383.42
#Sta/Elev= 30
  4601.6 2146.72  4660.2 2146.38  4732.9  2144.7  4854.2 2141.06  4870.9 2139.31
  4876.5 2139.76  4921.1 2136.28  4937.8 2131.98  4943.4  2133.4  4960.1 2131.56
  4965.7 2132.66    4988 2129.87    5015 2129.05  5048.3 2128.06  5056.1 2127.98
  5056.5 2127.48  5061.8 2127.98  5084.2 2129.51  5090.3 2133.48  5100.7 2134.68
  5117.2 2135.85  5165.5 2135.59  5194.7  2136.1  5299.1 2141.21    5326 2141.13
  5331.3 2142.01  5340.8  2141.4  5359.1 2143.33  5463.5 2143.72  5470.9 2143.06
#Mann= 7 ,-1 , 0
  4601.6     .07       0  4732.9     .16       0    5015     .07       0
  5048.3     .16       0  5056.1     .07       0  5061.8     .16       0
  5165.5     .07       0
Bank Sta=5056.1,5061.8
XS Rating Curve= 0 ,0
Exp/Cntr=0.3,0.1

Type RM Length L Ch R = 1 ,5030    ,464,464,464
BEGIN DESCRIPTION:
MULBERRY CREEK TRIBUTARY 24 10.0
END DESCRIPTION:
XS GIS Cut Line= 3
      1457371.87      6818803.12        1457455.        6817738.
      1457405.77      6816822.18
#Sta/Elev= 30
  3936.9 2154.17  4173.8 2147.24  4303.3 2141.86  4659.2 2138.95  4790.4 2137.65
  4894.9 2135.25    4925 2131.58  4955.1 2130.27  4995.2 2124.98  5012.4 2124.67
  5012.9 2124.17  5018.1 2124.67  5055.3 2124.94  5075.4 2130.71  5155.5 2134.19
  5195.5 2134.91  5282.7 2129.45  5287.7 2130.62  5315.7 2129.99  5676.2 2135.83
  5727.3 2138.61  5746.3 2138.19  5776.4 2142.97  5836.5  2173.9  5842.5 2180.02
  5847.5 2180.45  5856.5 2188.97  5872.4 2194.71  5886.5 2196.07  5922.4 2194.93
#Mann= 7 ,-1 , 0
  3936.9     .07       0  4659.2     .16       0  4790.4     .07       0
  5012.4     .07       0  5018.1     .07       0  5727.3     .16       0
  5872.4     .07       0
#XS Ineff= 2 , 0
       0                  5195.5       0 2134.91
Permanent Ineff=
       F       F
Bank Sta=5012.4,5018.1
XS Rating Curve= 0 ,0
Exp/Cntr=0.3,0.1

Type RM Length L Ch R = 1 ,4566    ,331,331,331
BEGIN DESCRIPTION:
MULBERRY CREEK TRIBUTARY 24 9.0
END DESCRIPTION:
XS GIS Cut Line= 3
      1458134.89      6818685.93        1457855.        6817538.
      1457504.99      6816737.98
#Sta/Elev= 30
  3822.6 2150.98  4129.3 2146.31  4308.5 2137.69  4386.6 2132.69  4391.9 2129.76
  4417.5 2129.16  4757.1  2131.8  4886.9 2127.49  4952.7 2126.82  4977.8 2120.61
  4978.3 2120.11  4983.6 2120.61  5006.9 2121.57    5042 2128.22  5146.6 2131.19
  5461.4 2135.71  5491.7 2138.34  5659.1  2147.5  5680.9 2151.01  5693.8 2153.25
  5711.7  2161.6  5717.2 2161.09  5735.1 2168.97  5740.5 2168.41  5746.4 2172.56
  5763.9 2179.54  5787.4 2186.69  5810.7  2192.3  5855.5 2195.36  5877.4  2199.3
#Mann= 7 ,-1 , 0
  3822.6     .07       0  4886.9     .16       0  4977.8     .07       0
  4983.6     .16       0  5146.6     .07       0  5491.7     .16       0
  5787.4     .07       0
Bank Sta=4977.8,4983.6
XS Rating Curve= 0 ,0
Exp/Cntr=0.3,0.1

Type RM Length L Ch R = 1 ,4235    ,739,739,739
BEGIN DESCRIPTION:
MULBERRY CREEK TRIBUTARY 24 8.0
END DESCRIPTION:
XS GIS Cut Line= 3
      1458197.39      6818680.73      1458170.25      6817487.44
      1457663.65      6816602.83
#Sta/Elev= 30
  3806.4 2150.23  4149.2 2146.06  4299.3 2141.13  4339.3 2138.48  4362.7  2134.4
  4389.3 2129.74  4429.3 2127.14  4489.3 2125.83  4591.2 2127.55  4639.4 2129.45
  4659.4 2126.98  4804.8 2124.15  4909.4    2125  4942.3 2123.25  4999.9 2118.73
  5000.4 2118.23  5005.7 2118.73  5033.9 2124.95  5231.7 2129.74  5625.9 2139.24
  5700.7 2143.69  5861.8 2149.51  5883.4 2151.84  5920.8 2160.44  5954.7  2172.8
  5978.9    2183  5991.3 2191.59  6001.4 2195.34  6007.2 2199.53  6019.4 2199.38
#Mann= 9 ,-1 , 0
  3806.4     .07       0  4362.7     .16       0  4591.2     .07       0
  4804.8     .16       0  4942.3     .07       0  4999.9     .07       0
  5005.7     .07       0  5231.7     .16       0  5954.7     .07       0
Bank Sta=4999.9,5005.7
XS Rating Curve= 0 ,0
Exp/Cntr=0.3,0.1

Type RM Length L Ch R = 1 ,3496    ,626,626,626
BEGIN DESCRIPTION:
MULBERRY CREEK TRIBUTARY 24 7.0
END DESCRIPTION:
XS GIS Cut Line= 3
      1458322.82      6818631.94      1458696.09      6817655.36
      1457724.67      6816532.15
#Sta/Elev= 30
  4321.5 2148.65  4699.9 2141.88  4776.6 2139.08  4900.1 2132.04  4978.8 2131.13
    4985  2129.7  4990.3 2124.77  5009.7 2114.94  5036.8 2111.61  5037.3 2111.11
  5042.7 2111.61  5052.6 2115.18  5069.8 2120.02  5085.8 2120.78  5337.2 2123.15
  5678.1 2123.93  6118.1 2137.03  6472.2 2148.78  6606.3 2147.99  6634.6 2146.83
  6642.2 2144.23  6648.8 2146.51  6658.7 2144.95  6693.2 2144.81  6705.9 2142.42
  6762.9 2152.47    6798 2168.98  6826.5 2189.49  6835.9 2194.04    6852 2197.84
#Mann= 11 ,-1 , 0
  4321.5     .07       0  4699.9     .16       0  4776.6     .07       0
  5036.8     .07       0  5042.7     .07       0  5052.6     .16       0
  5337.2     .07       0  6118.1     .16       0  6658.7     .07       0
  6693.2     .16       0  6835.9     .07       0
Bank Sta=5036.8,5042.7
XS Rating Curve= 0 ,0
Exp/Cntr=0.3,0.1

Type RM Length L Ch R = 1 ,2870    ,542,542,542
BEGIN DESCRIPTION:
MULBERRY CREEK TRIBUTARY 24 6.0
END DESCRIPTION:
XS GIS Cut Line= 3
      1459021.61      6818727.43      1459015.64      6817789.55
      1458652.59      6816631.63
#Sta/Elev= 30
  4062.1 2139.57  4191.5 2137.25  4351.5 2129.55  4491.5 2125.25  4701.5 2125.02
  4821.5 2119.15  4941.5 2117.07  4971.5 2114.59  4998.3 2107.59  5009.2 2106.57
  5009.6 2106.07  5015.1 2106.57  5018.1 2109.28  5023.3 2110.99  5050.5 2116.93
  5075.9  2117.4  5120.6 2117.19  5179.8 2120.64  5288.3 2118.83  5347.5 2116.44
  5368.4 2117.63  5473.2 2116.77  5515.1 2115.03  5567.5 2117.01  5585.2 2115.66
  5687.7  2116.7  5735.2 2120.64  5798.1 2123.35  5976.3 2126.28  6213.5 2134.26
#Mann= 5 ,-1 , 0
  4062.1     .07       0  5009.2     .07       0  5015.1     .07       0
  5075.9     .16       0  5288.3     .07       0
Bank Sta=5009.2,5015.1
XS Rating Curve= 0 ,0
Exp/Cntr=0.3,0.1

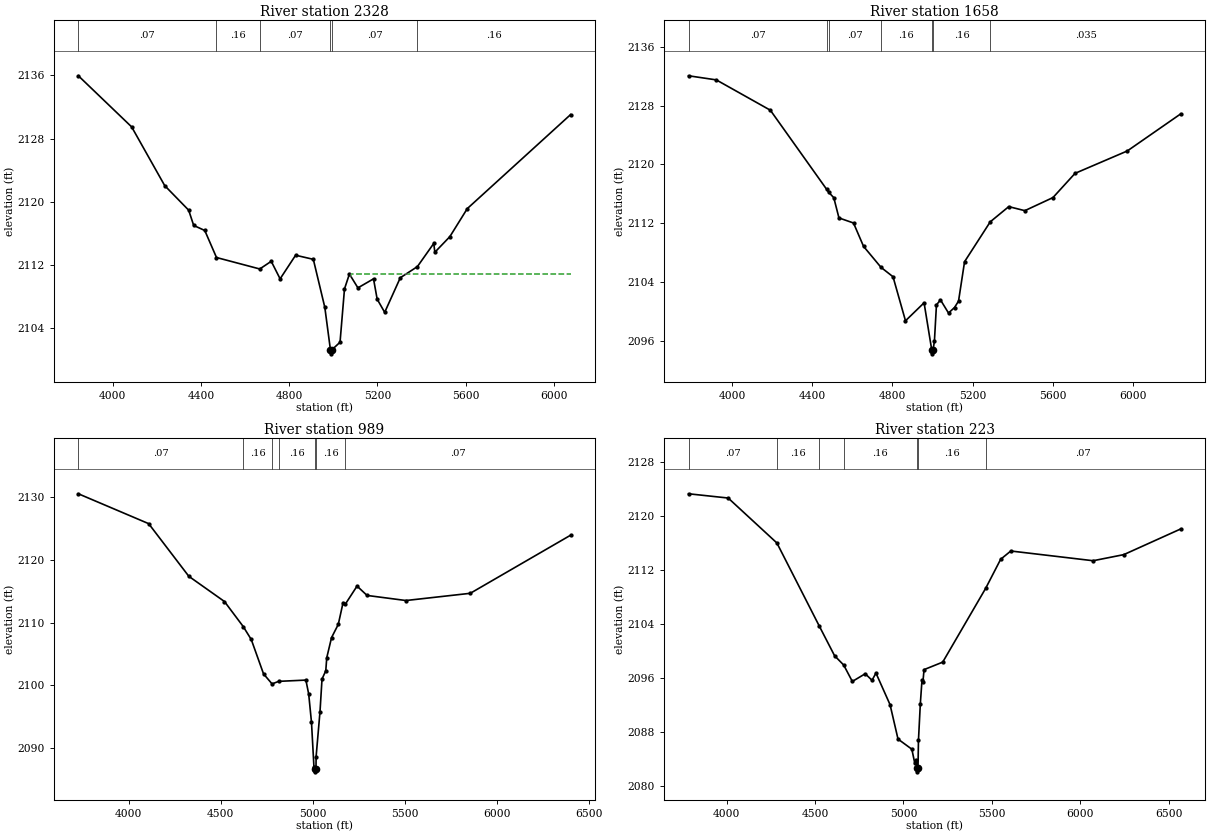
Type RM Length L Ch R = 1 ,2328    ,670,670,670
BEGIN DESCRIPTION:
Mapping XS 0f6d6f67
END DESCRIPTION:
XS GIS Cut Line= 3
      1459423.02      6818838.65      1459527.18      6817729.29
      1459355.31      6816625.13
#Sta/Elev= 30
    3844 2135.95  4085.7 2129.48  4235.5 2122.05  4344.2 2118.94  4366.9 2117.01
  4417.2 2116.37  4470.3 2112.95  4666.5  2111.5  4718.5 2112.47  4758.7 2110.25
    4829 2113.24  4909.3 2112.72  4961.4 2106.64  4986.9 2101.26  4987.4 2100.76
  4992.9 2101.26  5030.4 2102.23  5050.6 2108.98  5072.9 2110.86  5111.4 2109.11
  5182.2 2110.25  5198.7 2107.68  5232.8 2106.01  5303.6 2110.39  5381.1  2111.8
  5455.2 2114.73  5460.3 2113.62  5528.2 2115.59  5607.3 2119.14  6075.7 2131.04
#Mann= 6 ,-1 , 0
    3844     .07       0  4470.3     .16       0  4666.5     .07       0
  4986.9     .07       0  4992.9     .07       0  5381.1     .16       0
#XS Ineff= 2 , 0
       0                    5081       0 2110.91
Permanent Ineff=
       F       F
Bank Sta=4986.9,4992.9
XS Rating Curve= 0 ,0
Exp/Cntr=0.3,0.1

Type RM Length L Ch R = 1 ,1658    ,669,669,669
BEGIN DESCRIPTION:
Mapping XS a9721b5a
END DESCRIPTION:
XS GIS Cut Line= 3
      1459818.86      6818911.54      1460136.56      6817750.12
      1460209.39      6816501.53
#Sta/Elev= 30
  3783.7 2132.07  3922.1 2131.51  4191.7 2127.38  4472.6  2116.6  4482.5 2116.21
    4508 2115.47  4533.8 2112.71  4606.4 2112.02  4656.4 2108.84  4743.5 2105.98
  4803.4  2104.7  4865.6  2098.7  4958.3 2101.15  4996.7  2094.7  4997.2  2094.2
  5003.1  2094.7  5009.9 2095.94    5020 2100.86    5040 2101.55  5080.1 2099.76
  5110.1 2100.51  5130.1 2101.38  5160.2 2106.75  5288.3 2112.18  5380.6 2114.25
  5460.7  2113.7  5600.9 2115.48  5711.1 2118.78  5971.6 2121.83  6238.5 2126.89
#Mann= 7 ,-1 , 0
  3783.7     .07       0  4472.6     .16       0  4482.5     .07       0
  4743.5     .16       0  4996.7     .07       0  5003.1     .16       0
  5288.3    .035       0
Bank Sta=4996.7,5003.1
XS Rating Curve= 0 ,0
Exp/Cntr=0.3,0.1

Type RM Length L Ch R = 1 ,989     ,766,766,766
BEGIN DESCRIPTION:
Mapping XS 654a1381
END DESCRIPTION:
XS GIS Cut Line= 4
      1459954.25      6818994.93      1460652.18      6817906.37
       1460725.1      6817692.83      1460339.84      6816604.75
#Sta/Elev= 30
  3727.6 2130.54  4109.4 2125.78  4327.5 2117.39  4521.1 2113.37  4622.7 2109.39
  4666.5 2107.32  4733.2 2101.84  4779.6 2100.24  4815.4 2100.65  4963.2 2100.85
  4978.4 2098.63  4993.6 2094.11  5006.9 2087.01  5011.5 2086.73    5012 2086.23
    5018 2086.73  5018.7 2088.67  5039.8 2095.82  5050.7 2101.01  5071.2 2102.34
  5076.5 2104.42  5102.5 2107.62  5139.1 2109.73  5165.1  2113.2  5176.4 2112.91
  5240.9 2115.83  5295.4 2114.34  5506.3 2113.53  5855.8 2114.68  6400.6 2123.94
#Mann= 7 ,-1 , 0
  3727.6     .07       0  4622.7     .16       0  4779.6     .07       0
  4815.4     .16       0  5011.5     .07       0    5018     .16       0
  5176.4     .07       0
Bank Sta=5011.5,5018
XS Rating Curve= 0 ,0
Exp/Cntr=0.3,0.1

Type RM Length L Ch R = 1 ,223     ,0,0,0
BEGIN DESCRIPTION:
MULBERRY CREEK TRIBUTARY 24 1.0
END DESCRIPTION:
XS GIS Cut Line= 3
       1460578.9      6819239.87      1461115.12      6818148.26
      1460610.76      6816662.32
#Sta/Elev= 30
  3783.8 2123.28  4008.1 2122.65  4283.7    2116  4522.4 2103.76  4610.3  2099.3
  4661.8 2097.93  4710.6  2095.5  4783.6 2096.64    4822 2095.67  4844.3 2096.74
  4924.1 2092.06  4969.1 2086.97  5047.4 2085.47  5063.6 2083.43  5073.5  2083.9
  5075.5 2082.62    5076 2082.12  5082.1 2082.62  5084.8 2086.78  5095.3 2092.17
  5104.9 2095.74  5110.2 2095.48  5116.4 2097.25    5222 2098.36  5465.2 2109.29
  5549.8 2113.58  5607.3 2114.81    6073 2113.37  6246.4 2114.27  6569.2 2118.08
#Mann= 7 ,-1 , 0
  3783.8     .07       0  4283.7     .16       0  4522.4     .07       0
  4661.8     .16       0  5075.5     .07       0  5082.1     .16       0
  5465.2     .07       0
Bank Sta=5075.5,5082.1
XS Rating Curve= 0 ,0
Exp/Cntr=0.3,0.1

Chan Stop Cuts=-1
Use User Specified Reach Order=0
Composite Channel Slope=5