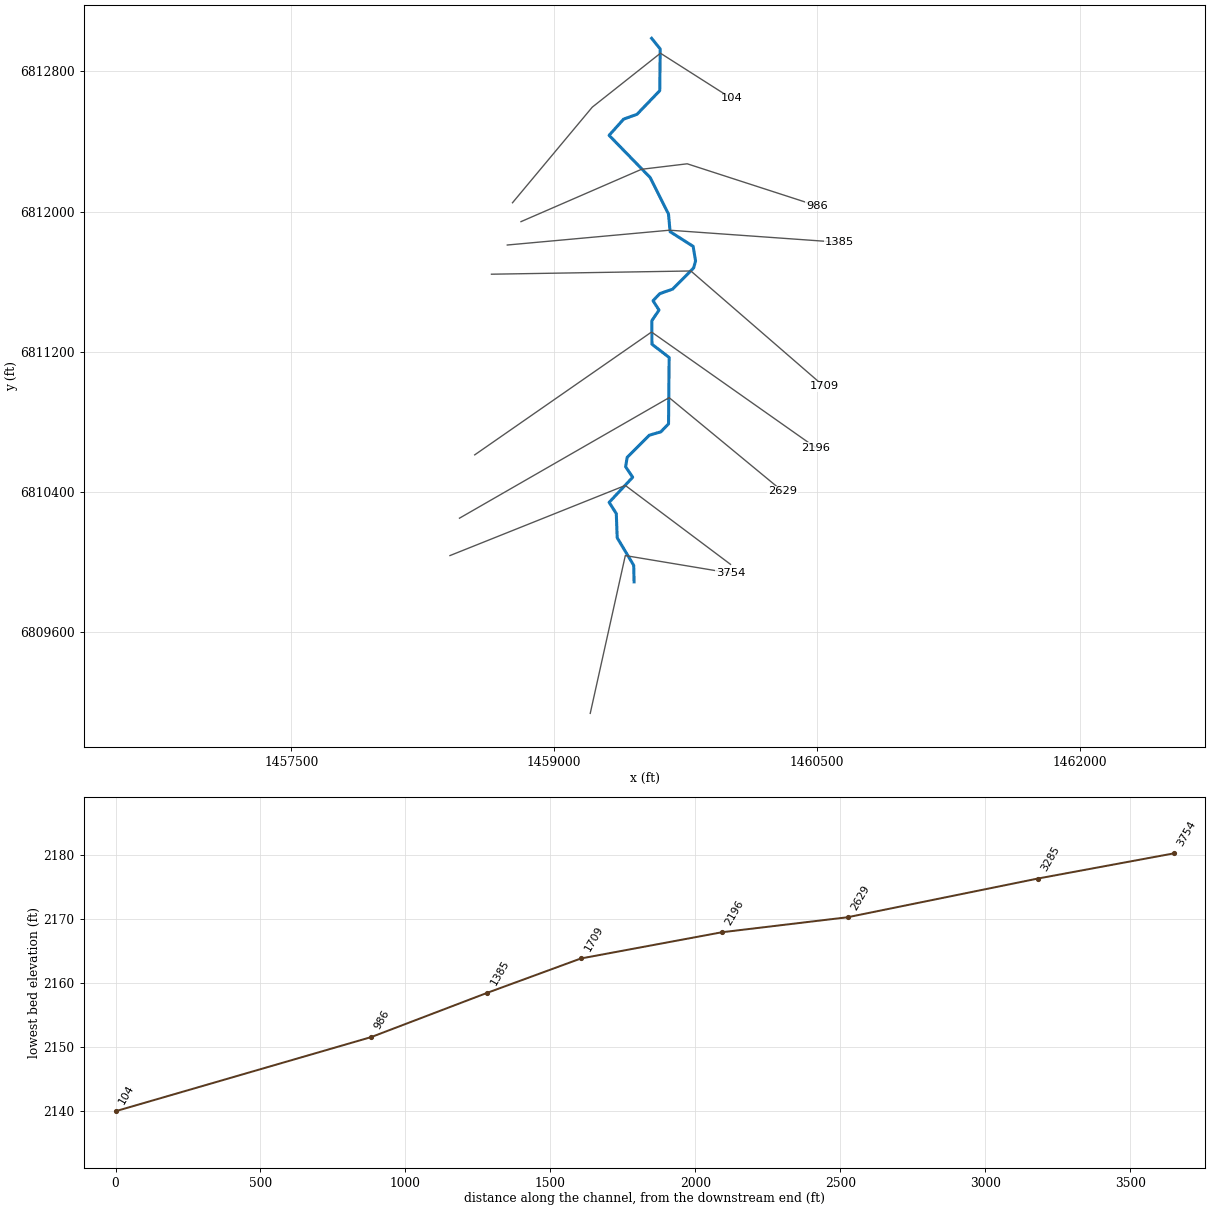
--- MULBERRY CREEK TRIBUTARY 25.prj (project) ---

Proj Title=MULBERRY CREEK TRIBUTARY 25 Base Level Engineering
Current Plan=p01
Default Exp/Contr=0.3,0.1
English Units
Geom File=g01
Flow File=f01
Plan File=p01
Y Axis Title=Elevation
X Axis Title(PF)=Main Channel Distance
X Axis Title(XS)=Station
BEGIN DESCRIPTION:
MULBERRY CREEK TRIBUTARY 25
END DESCRIPTION:
DSS Export Rating Curves= 0
DSS Export Rating Curve Sorted= 0
DSS Export Volume Flow Curves= 0
DXF OffsetX= 0
DXF OffsetY= 0
DXF ScaleX= 1
DXF ScaleY= 10

--- MULBERRY CREEK TRIBUTARY 25.p01 (plan) ---

Plan Title=Multiple Run
Short Identifier=Multiple
Geom File=g01
Flow File=f01
Subcritical Flow
K Sum by GR= 0
Std Step Tol= 0.01
Critical Tol= 0.01
Num of Std Step Trials= 20
Max Error Tol= 0.3
Flow Tol Ratio= 0.001
Split Flow NTrial= 30
Split Flow Tol= 0.02
Split Flow Ratio= 0.02
Log Output Level= 0
Friction Slope Method= 1
Unsteady Friction Slope Method= 2
Unsteady Bridges Friction Slope Method= 1
Parabolic Critical Depth
Global Vel Dist=  1 , 1 , 1
Global Log Level= 0
CheckData=True
Encroach Param= -1, 0, 0, 0
BEGIN DESCRIPTION:
Multiple Run
END DESCRIPTION:

--- MULBERRY CREEK TRIBUTARY 25.f01 (steady flow) ---

Flow Title=Multiple
Program Version=4.10
Number of Profiles= 7
Profile Names=10-year,25-year,50-year,1pct_min,100-year,1pct_plu,500-year
River Rch & RM=MULBERRY CREEK T,Reach-1         ,3754
     322     466     590     373     743    1483    1193
Boundary for River Rch & Prof#=MULBERRY CREEK T,Reach-1         , 1
Up Type= 0
Dn Type= 3
Dn Slope=0.013
Boundary for River Rch & Prof#=MULBERRY CREEK T,Reach-1         , 2
Up Type= 0
Dn Type= 3
Dn Slope=0.013
Boundary for River Rch & Prof#=MULBERRY CREEK T,Reach-1         , 3
Up Type= 0
Dn Type= 3
Dn Slope=0.013
Boundary for River Rch & Prof#=MULBERRY CREEK T,Reach-1         , 4
Up Type= 0
Dn Type= 3
Dn Slope=0.013
Boundary for River Rch & Prof#=MULBERRY CREEK T,Reach-1         , 5
Up Type= 0
Dn Type= 3
Dn Slope=0.013
Boundary for River Rch & Prof#=MULBERRY CREEK T,Reach-1         , 6
Up Type= 0
Dn Type= 3
Dn Slope=0.013
Boundary for River Rch & Prof#=MULBERRY CREEK T,Reach-1         , 7
Up Type= 0
Dn Type= 3
Dn Slope=0.013
DSS Import GetInterval= 0
DSS Import GetPeak= 0
DSS Import FillOption= 0

--- MULBERRY CREEK TRIBUTARY 25.g01 (geometry) ---

Geom Title=Existing Conditions
Program Version=4.10

River Reach=MULBERRY CREEK T,Reach-1
Reach XY= 30
        1459455.        6809888.      1459452.93      6809982.14
      1459358.76      6810139.56       1459353.6      6810277.56
       1459312.8      6810341.42      1459447.18      6810484.59
      1459406.99      6810544.05       1459415.2      6810597.68
       1459541.8      6810724.36      1459607.58      6810743.74
      1459651.55      6810789.25      1459654.94       6811167.8
        1459557.      6811243.69      1459556.36      6811377.56
      1459597.19      6811438.11      1459562.89      6811491.58
      1459602.17      6811532.14      1459675.07      6811557.79
      1459794.57      6811678.22      1459805.69      6811717.94
      1459791.81      6811801.65      1459660.42      6811885.33
      1459651.17      6811986.41      1459546.86      6812194.06
      1459312.58      6812434.68      1459395.28      6812527.22
      1459471.67      6812554.65      1459601.46      6812689.46
      1459604.04       6812927.6        1459555.        6812988.

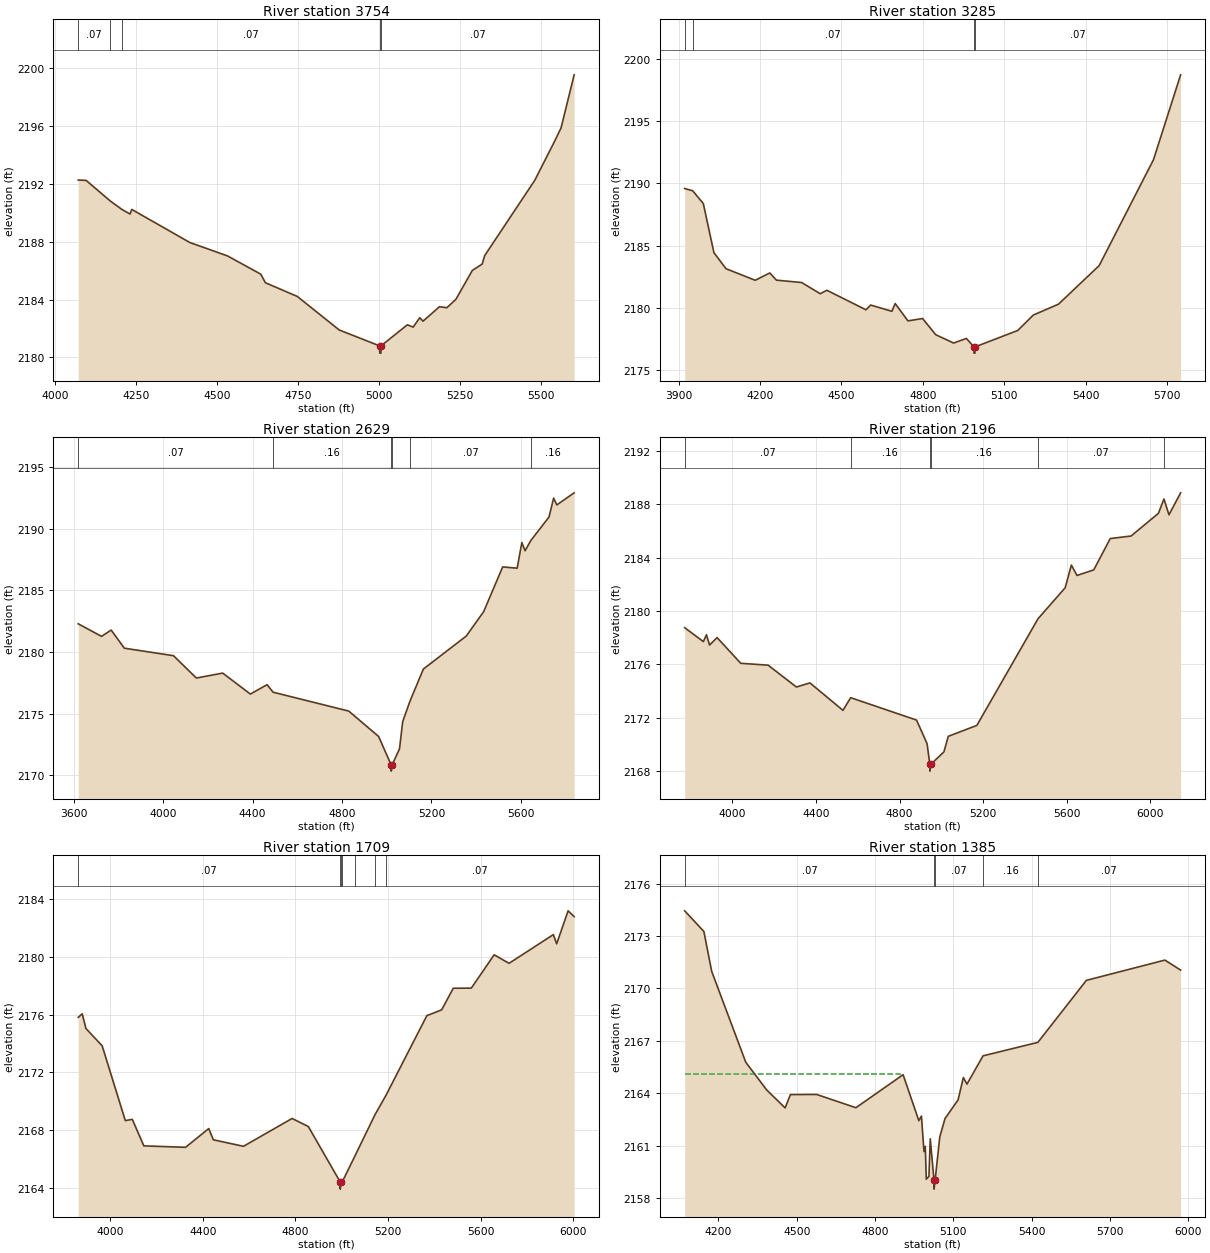
Type RM Length L Ch R = 1 ,3754    ,469,469,469
BEGIN DESCRIPTION:
MULBERRY CREEK TRIBUTARY 25 7.0
END DESCRIPTION:
XS GIS Cut Line= 3
        1459205.      6809137.99        1459405.        6810038.
      1460004.96      6809938.01
#Sta/Elev= 30
  4072.5 2192.27  4096.8 2192.25  4171.1 2190.83  4207.9 2190.23  4232.6 2189.92
  4237.7 2190.24    4417 2187.95  4533.5 2187.02  4635.9 2185.76    4650 2185.17
  4748.6 2184.22  4877.9  2181.9  5002.6  2180.8  5002.9  2180.3  5006.4  2180.3
  5006.6  2180.8  5088.2 2182.26    5106  2182.1  5126.3 2182.75  5136.4 2182.51
  5187.1 2183.51  5209.9 2183.44  5237.8 2184.02  5288.5 2186.02  5318.9 2186.46
  5326.5 2187.04  5481.1 2192.25  5541.9 2194.93  5562.2 2195.87  5602.7 2199.55
#Mann= 5 ,-1 , 0
  4072.5     .07       0  4171.1     .16       0  4207.9     .07       0
  5002.6     .07       0  5006.6     .07       0
Bank Sta=5002.6,5006.6
XS Rating Curve= 0 ,0
Exp/Cntr=0.3,0.1

Type RM Length L Ch R = 1 ,3285    ,656,656,656
BEGIN DESCRIPTION:
MULBERRY CREEK TRIBUTARY 25 6.0
END DESCRIPTION:
XS GIS Cut Line= 3
      1458404.97      6810037.99        1459405.        6810438.
      1460005.02      6809987.98
#Sta/Elev= 30
  3922.6 2189.59  3952.1 2189.41  3991.3 2188.38  4030.3 2184.44  4074.8 2183.15
  4182.5 2182.22  4236.3 2182.81  4260.6 2182.23  4353.5 2182.04  4422.1 2181.14
  4446.3 2181.42  4590.4 2179.85  4607.9 2180.23    4686 2179.73  4698.1 2180.35
  4745.2 2178.96  4799.1 2179.15  4847.5 2177.85  4913.5 2177.18  4960.6 2177.55
  4988.2 2176.87  4988.5 2176.37    4992 2176.37  4992.2 2176.87  5149.7 2178.19
    5207 2179.43  5299.7  2180.3  5449.7  2183.4  5649.7  2191.9  5749.7 2198.72
#Mann= 4 ,-1 , 0
  3922.6     .16       0  3952.1     .07       0  4988.2     .07       0
  4992.2     .07       0
Bank Sta=4988.2,4992.2
XS Rating Curve= 0 ,0
Exp/Cntr=0.3,0.1

Type RM Length L Ch R = 1 ,2629    ,433,433,433
BEGIN DESCRIPTION:
MULBERRY CREEK TRIBUTARY 25 5.0
END DESCRIPTION:
XS GIS Cut Line= 3
      1458459.29      6810251.25      1459655.04      6810938.75
      1460301.54      6810405.26
#Sta/Elev= 30
  3620.7 2182.28  3724.9 2181.26  3768.1 2181.77    3827  2180.3  4046.9 2179.69
    4149 2177.88  4266.8 2178.28  4390.5 2176.58  4465.2 2177.34  4492.1 2176.73
  4830.3  2175.2    4964 2173.14  5020.1 2170.83  5020.3 2170.33  5024.1 2170.83
  5057.2 2172.13  5071.6 2174.34  5104.2 2176.01  5164.1 2178.61  5355.6 2181.28
  5433.8 2183.27  5518.6 2186.89  5583.4 2186.79  5604.4 2188.87  5618.8  2188.2
  5644.7 2189.04  5725.6 2190.93  5746.5 2192.47  5760.8 2191.92  5838.2  2192.9
#Mann= 6 ,-1 , 0
  3620.7     .07       0  4492.1     .16       0  5020.1     .07       0
  5024.1     .16       0  5104.2     .07       0  5644.7     .16       0
Bank Sta=5020.1,5024.1
XS Rating Curve= 0 ,0
Exp/Cntr=0.3,0.1

Type RM Length L Ch R = 1 ,2196    ,487,487,487
BEGIN DESCRIPTION:
MULBERRY CREEK TRIBUTARY 25 4.0
END DESCRIPTION:
XS GIS Cut Line= 3
      1458546.09      6810612.35      1459554.59      6811312.99
      1460490.25      6810654.23
#Sta/Elev= 30
    3772 2178.75  3861.4 2177.71  3876.2 2178.22  3891.1 2177.45  3926.9 2178.01
  4040.3 2176.08  4171.3 2175.94  4306.4  2174.3  4371.2 2174.61  4529.2 2172.55
  4566.1  2173.5  4881.1 2171.82  4931.7 2170.04  4944.6 2168.49  4944.8 2167.99
  4948.6 2168.49    5012 2169.43  5032.9  2170.6  5169.6 2171.42  5462.1 2179.42
  5592.1 2181.75  5621.7 2183.45  5648.7 2182.67  5728.9 2183.09  5807.7 2185.44
  5907.4 2185.63  6038.1 2187.33  6064.7 2188.41  6088.6 2187.22  6144.3 2188.87
#Mann= 6 ,-1 , 0
    3772     .07       0  4566.1     .16       0  4944.6     .07       0
  4948.6     .16       0  5462.1     .07       0  6064.7     .16       0
Bank Sta=4944.6,4948.6
XS Rating Curve= 0 ,0
Exp/Cntr=0.3,0.1

Type RM Length L Ch R = 1 ,1709    ,324,324,324
BEGIN DESCRIPTION:
MULBERRY CREEK TRIBUTARY 25 3.0
END DESCRIPTION:
XS GIS Cut Line= 3
       1458641.6      6811642.74      1459778.85      6811661.13
      1460537.41      6811003.86
#Sta/Elev= 30
  3862.6  2175.8  3879.9 2176.05    3896 2175.03    3966 2173.83    4066 2168.64
    4096 2168.73    4146 2166.89  4326.1 2166.79  4426.1 2168.09  4446.1 2167.31
  4576.1 2166.86  4786.1 2168.79  4856.1 2168.23  4993.6 2164.39  4993.8 2163.89
  4997.6 2164.39  5002.7  2164.4  5057.3 2166.19  5144.2 2169.06  5191.5  2170.4
  5367.8 2175.92  5431.6 2176.32  5481.8 2177.82  5559.7 2177.83  5658.4 2180.14
  5722.7 2179.55  5913.9 2181.54  5928.2  2180.9  5977.6 2183.19  6003.7 2182.79
#Mann= 7 ,-1 , 0
  3862.6     .07       0  4993.6     .07       0  4997.6     .07       0
  5002.7     .16       0  5057.3     .07       0  5144.2     .16       0
  5191.5     .07       0
#XS Ineff= 2 , 0
       0  4786.1 2168.79               0
Permanent Ineff=
       F       F
Bank Sta=4993.6,4997.6
XS Rating Curve= 0 ,0
Exp/Cntr=0.3,0.1

Type RM Length L Ch R = 1 ,1385    ,399,399,399
BEGIN DESCRIPTION:
MULBERRY CREEK TRIBUTARY 25 2.0
END DESCRIPTION:
XS GIS Cut Line= 3
      1458731.82      6811809.23      1459657.08      6811893.71
      1460625.13      6811824.85
#Sta/Elev= 30
  4070.9 2174.44  4144.4 2173.26  4174.5 2170.97    4305 2165.77  4385.4 2164.18
  4455.7 2163.16  4475.8 2163.92  4576.2 2163.93  4726.8 2163.17  4907.5 2165.06
  4967.8 2162.43  4977.8 2162.69  4987.5 2160.66  4992.5 2160.96  4996.4 2159.08
  5006.5 2159.24  5011.5 2161.39    5026 2159.01  5026.2 2158.51    5030 2159.01
    5048  2161.5  5068.1 2162.55  5118.2 2163.62  5138.3  2164.9  5152.1 2164.52
  5213.8 2166.14  5423.7 2166.91  5609.5 2170.46  5910.2 2171.62  5970.5 2171.05
#Mann= 5 ,-1 , 0
  4070.9     .07       0    5026     .07       0    5030     .07       0
  5213.8     .16       0  5423.7     .07       0
#XS Ineff= 2 , 0
       0  4897.5 2165.11               0
Permanent Ineff=
       F       F
Bank Sta=5026,5030
XS Rating Curve= 0 ,0
Exp/Cntr=0.3,0.1

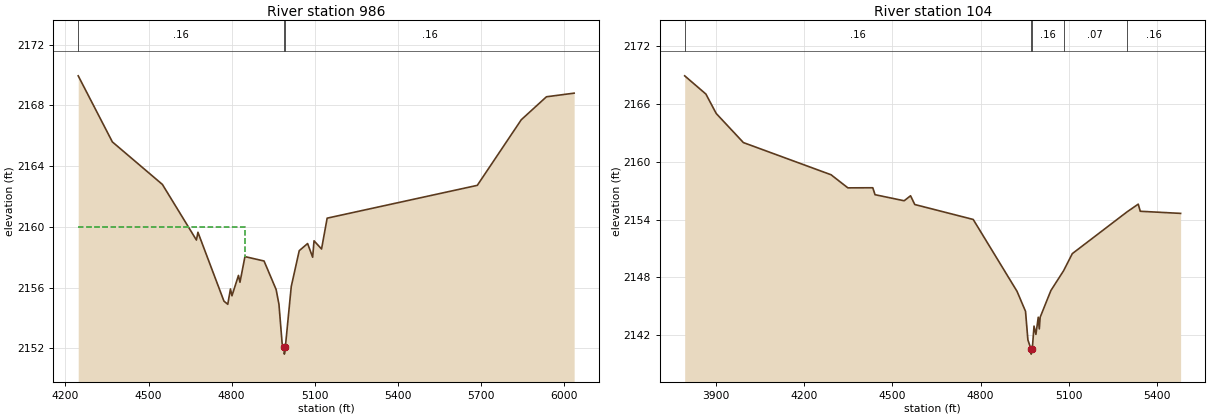
Type RM Length L Ch R = 1 ,986     ,882,882,882
BEGIN DESCRIPTION:
Mapping XS da447158
END DESCRIPTION:
XS GIS Cut Line= 4
      1458810.13      6811942.55      1459497.66      6812241.18
      1459758.08      6812272.43      1460497.39      6812032.93
#Sta/Elev= 30
  4246.4 2169.94  4369.6 2165.59  4550.1 2162.79  4672.8 2159.13  4678.3 2159.64
  4772.1 2155.11  4785.9  2154.9  4795.6 2155.91    4801 2155.46  4824.5  2156.8
  4829.9 2156.35  4847.9 2158.04  4916.8 2157.75  4960.4 2155.87  4970.6 2154.89
  4982.2 2152.28  4989.8 2152.12  4990.1 2151.62  4993.8 2152.12  5014.9 2156.07
  5043.7 2158.43  5073.9  2158.9  5092.1    2158  5097.1 2159.08  5124.2 2158.54
  5144.4 2160.57    5686 2162.73  5844.7 2167.05  5935.4 2168.56  6035.4  2168.8
#Mann= 3 ,-1 , 0
  4246.4     .16       0  4989.8     .07       0  4993.8     .16       0
#XS Ineff= 2 , 0
       0  4847.9    2160               0
Permanent Ineff=
       F       F
Bank Sta=4989.8,4993.8
XS Rating Curve= 0 ,0
Exp/Cntr=0.3,0.1

Type RM Length L Ch R = 1 ,104     ,0,0,0
BEGIN DESCRIPTION:
MULBERRY CREEK TRIBUTARY 25 1.0
END DESCRIPTION:
XS GIS Cut Line= 4
      1458761.58      6812050.24      1459216.41      6812595.34
      1459605.41      6812903.17      1460010.75      6812645.13
#Sta/Elev= 30
    3794 2168.93  3866.1 2167.04  3901.3 2165.02  3993.7    2162  4291.8 2158.66
    4349  2157.3  4433.6 2157.31  4441.4 2156.59  4540.4 2155.96  4562.1 2156.48
  4576.5 2155.57  4775.2 2154.02  4924.2 2146.56  4953.1 2144.48  4961.2 2141.51
    4972 2140.54  4972.2 2140.04    4976 2140.54    4982 2142.95  4988.4 2142.09
  4996.4 2143.87  4999.9 2142.66  5002.9 2143.87  5039.3 2146.64  5082.4 2148.69
  5112.1 2150.47    5298  2154.8  5336.4 2155.61  5343.3 2154.87  5480.5 2154.65
#Mann= 5 ,-1 , 0
    3794     .16       0    4972     .07       0    4976     .16       0
  5082.4     .07       0    5298     .16       0
Bank Sta=4972,4976
XS Rating Curve= 0 ,0
Exp/Cntr=0.3,0.1

Chan Stop Cuts=-1
Use User Specified Reach Order=0
Composite Channel Slope=5