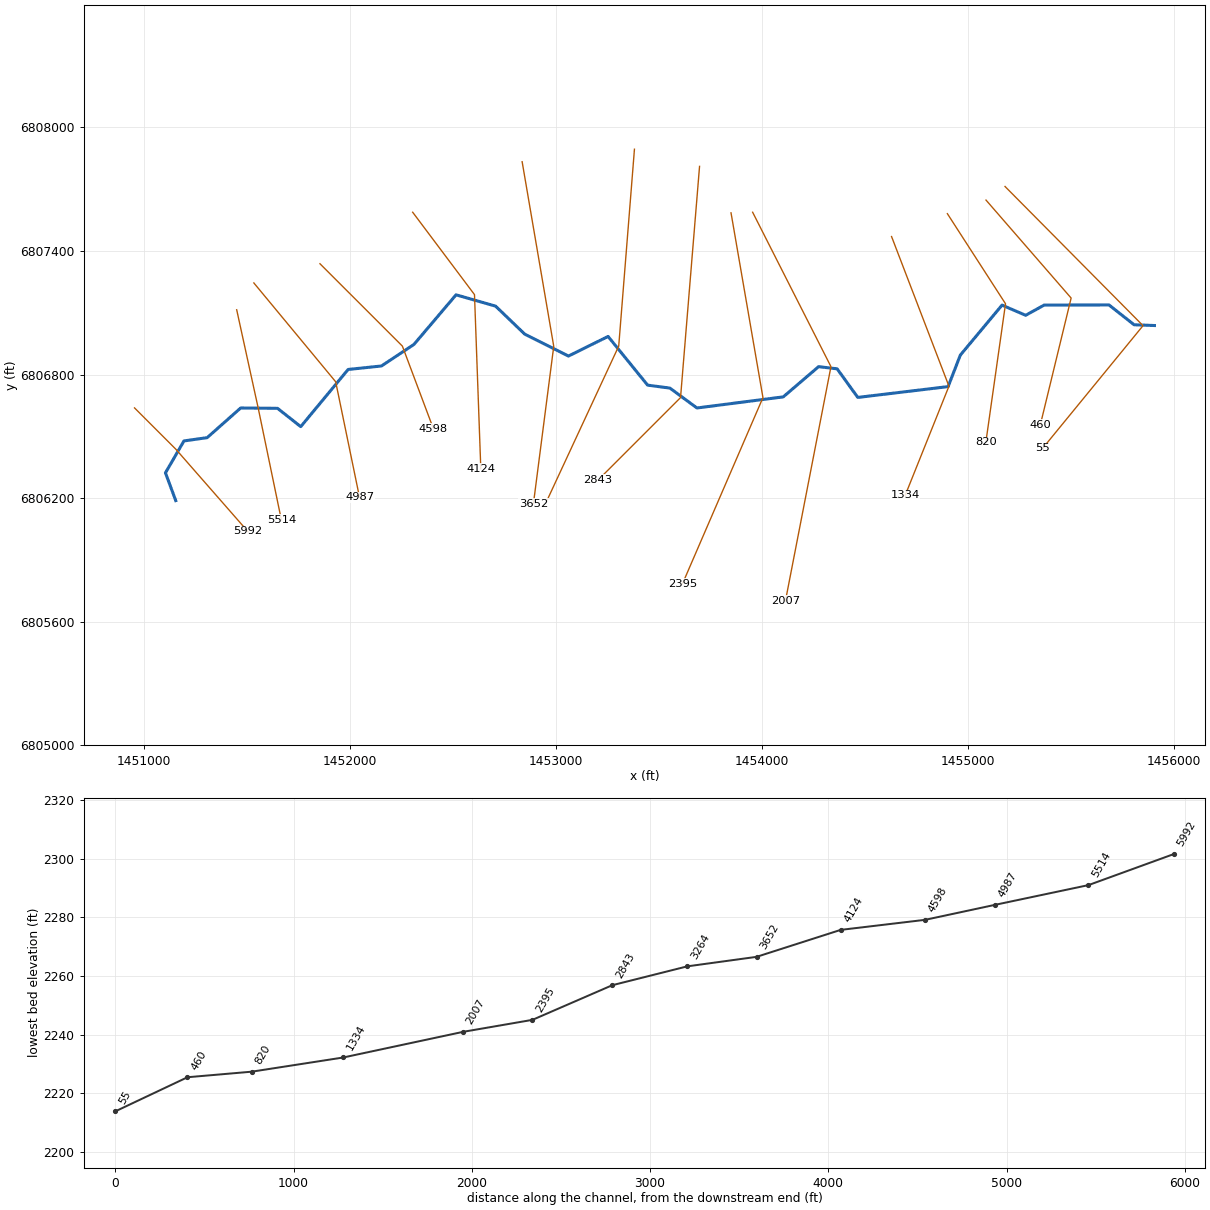
--- MULBERRY CREEK TRIBUTARY 26.prj (project) ---

Proj Title=MULBERRY CREEK TRIBUTARY 26 Base Level Engineering
Current Plan=p01
Default Exp/Contr=0.3,0.1
English Units
Geom File=g01
Flow File=f01
Plan File=p01
Y Axis Title=Elevation
X Axis Title(PF)=Main Channel Distance
X Axis Title(XS)=Station
BEGIN DESCRIPTION:
MULBERRY CREEK TRIBUTARY 26
END DESCRIPTION:
DSS Export Rating Curves= 0
DSS Export Rating Curve Sorted= 0
DSS Export Volume Flow Curves= 0
DXF OffsetX= 0
DXF OffsetY= 0
DXF ScaleX= 1
DXF ScaleY= 10

--- MULBERRY CREEK TRIBUTARY 26.p01 (plan) ---

Plan Title=Multiple Run
Short Identifier=Multiple
Geom File=g01
Flow File=f01
Subcritical Flow
K Sum by GR= 0
Std Step Tol= 0.01
Critical Tol= 0.01
Num of Std Step Trials= 20
Max Error Tol= 0.3
Flow Tol Ratio= 0.001
Split Flow NTrial= 30
Split Flow Tol= 0.02
Split Flow Ratio= 0.02
Log Output Level= 0
Friction Slope Method= 1
Unsteady Friction Slope Method= 2
Unsteady Bridges Friction Slope Method= 1
Parabolic Critical Depth
Global Vel Dist=  1 , 1 , 1
Global Log Level= 0
CheckData=True
Encroach Param= -1, 0, 0, 0
BEGIN DESCRIPTION:
Multiple Run
END DESCRIPTION:

--- MULBERRY CREEK TRIBUTARY 26.f01 (steady flow) ---

Flow Title=Multiple
Number of Profiles=7
Profile Names=10-year,25-year,50-year,1pct_min,100-year,1pct_plu,500-year
River Rch & RM= MULBERRY CREEK T,Reach-1,5992
     493     725     927     590    1178    2350    1924
River Rch & RM= MULBERRY CREEK T,Reach-1,2395
     588     871    1121     717    1432    2856    2363
Boundary for River Rch & Prof#=MULBERRY CREEK T,Reach-1,1
Up Type=0
Dn Type=3
Dn Slope=0.005
Boundary for River Rch & Prof#=MULBERRY CREEK T,Reach-1,2
Up Type=0
Dn Type=3
Dn Slope=0.005
Boundary for River Rch & Prof#=MULBERRY CREEK T,Reach-1,3
Up Type=0
Dn Type=3
Dn Slope=0.005
Boundary for River Rch & Prof#=MULBERRY CREEK T,Reach-1,4
Up Type=0
Dn Type=3
Dn Slope=0.005
Boundary for River Rch & Prof#=MULBERRY CREEK T,Reach-1,5
Up Type=0
Dn Type=3
Dn Slope=0.005
Boundary for River Rch & Prof#=MULBERRY CREEK T,Reach-1,6
Up Type=0
Dn Type=3
Dn Slope=0.005
Boundary for River Rch & Prof#=MULBERRY CREEK T,Reach-1,7
Up Type=0
Dn Type=3
Dn Slope=0.005

--- MULBERRY CREEK TRIBUTARY 26.g01 (geometry) ---

Geom Title=Existing Conditions
Program Version=4.10

River Reach=MULBERRY CREEK T,Reach-1
Reach XY= 30
        1451155.        6806188.      1451105.03      6806322.62
      1451194.89      6806477.61      1451307.42      6806493.53
      1451470.16      6806637.62      1451649.15      6806635.93
      1451761.67      6806546.96      1451991.66      6806824.64
      1452153.53      6806841.55      1452311.07      6806946.15
      1452515.47      6807187.07       1452707.3      6807132.17
      1452848.94      6806996.14      1453061.12      6806889.76
      1453253.36      6806984.91      1453445.19      6806748.51
      1453553.44      6806734.18      1453684.63      6806637.61
      1454103.54      6806691.54      1454275.06      6806838.22
       1454365.1       6806827.7      1454465.33      6806688.87
      1454903.78      6806741.44      1454962.86      6806894.17
      1455165.43      6807137.16      1455279.96      6807087.68
       1455370.2      6807137.46      1455684.72      6807137.74
      1455806.47      6807041.62        1455905.        6807038.

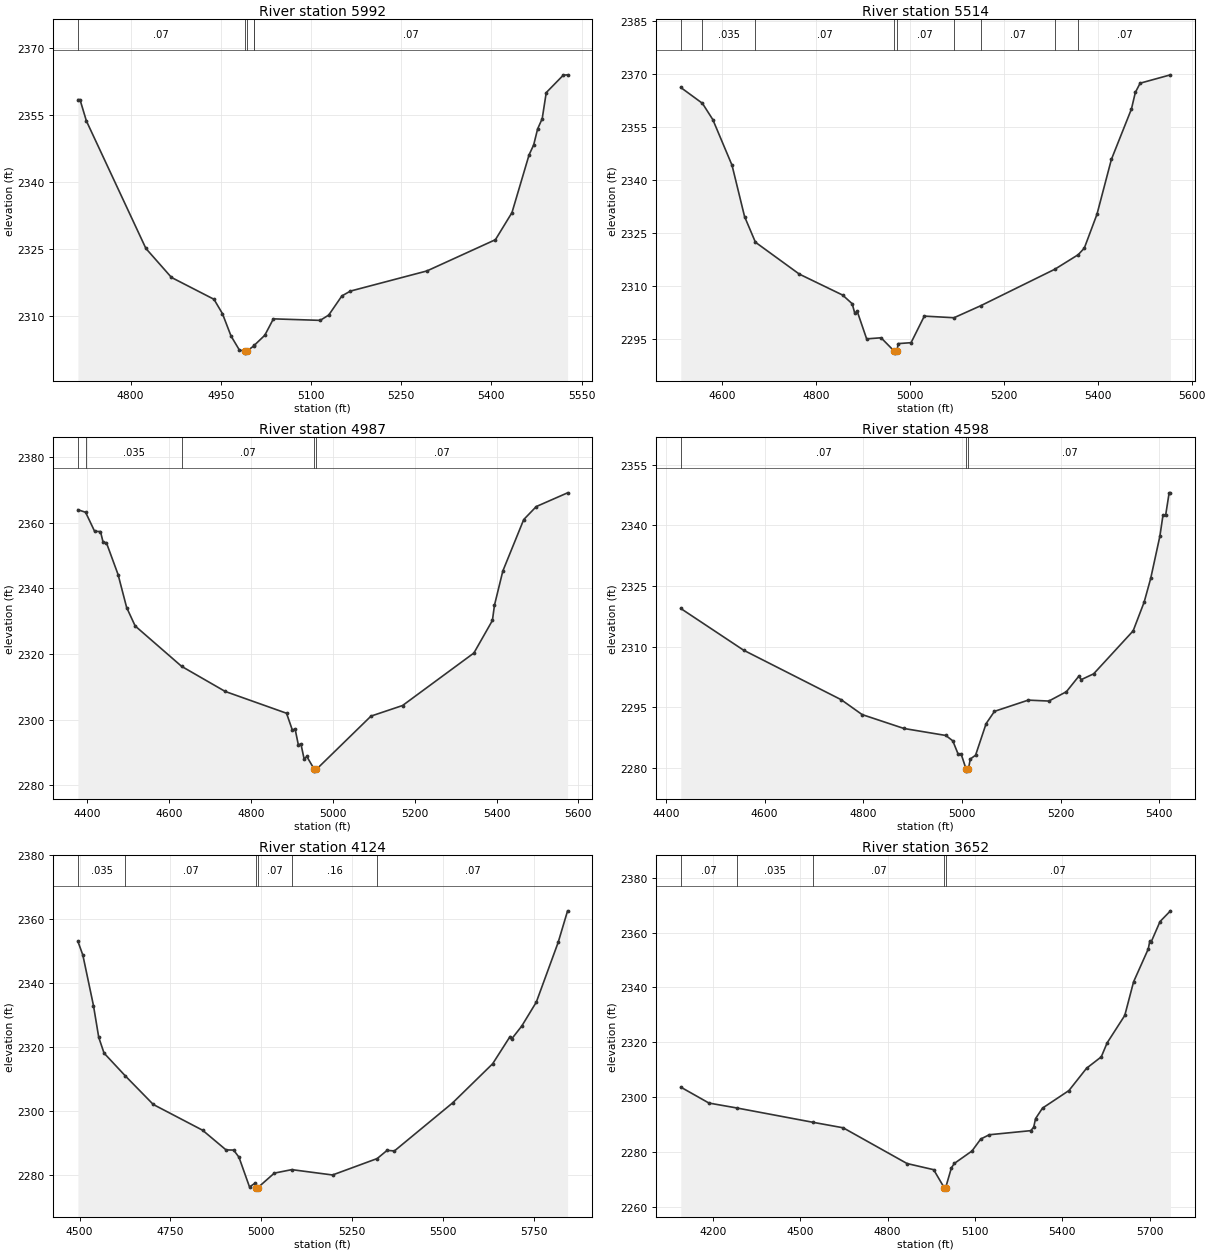
Type RM Length L Ch R = 1 ,5992    ,478,478,478
BEGIN DESCRIPTION:
MULBERRY CREEK TRIBUTARY 26 12.0
END DESCRIPTION:
XS GIS Cut Line= 3
        1450955.        6806638.        1451155.        6806438.
      1451504.97      6806038.04
#Sta/Elev= 30
  4712.4 2358.43  4715.9 2358.43  4726.5 2353.66  4825.5 2325.04    4868 2318.54
  4938.7 2313.64  4952.8 2310.41    4967 2305.41  4981.1 2302.22  4989.5 2302.06
  4989.8 2301.56    4994 2302.06  5004.5 2303.14  5005.9 2303.34  5023.2 2305.57
  5037.5 2309.25  5115.3 2308.91  5129.5  2310.1  5151.4  2314.4  5165.6 2315.48
  5292.8    2320  5406.7 2327.01  5434.2 2333.08  5462.7 2346.06  5470.3 2348.27
  5476.9 2351.87  5484.5 2354.17  5491.2 2360.01  5519.6 2363.93  5526.7    2364
#Mann= 5 ,-1 , 0
  4712.4     .07       0  4989.5     .07       0    4994     .07       0
  5004.5     .16       0  5005.9     .07       0
Bank Sta=4989.5,4994
XS Rating Curve= 0 ,0
Exp/Cntr=0.3,0.1

Type RM Length L Ch R = 1 ,5514    ,527,527,527
BEGIN DESCRIPTION:
MULBERRY CREEK TRIBUTARY 26 11.0
END DESCRIPTION:
XS GIS Cut Line= 3
      1451450.76      6807114.59        1451555.      6806638.16
       1451667.5      6806094.78
#Sta/Elev= 30
  4512.3 2366.28  4558.3  2361.8  4580.5 2357.18  4621.4 2344.24  4648.1 2329.69
  4671.2 2322.43  4764.7 2313.39  4856.8 2307.46  4877.3 2304.99  4882.7  2302.3
  4887.9 2302.86    4908 2295.04  4938.7 2295.35  4967.2  2291.5  4967.5    2291
  4971.8  2291.5  4975.6  2293.7  5002.6 2293.96  5030.8 2301.49    5094 2301.03
  5150.5 2304.41  5308.9 2314.79  5358.4 2318.89  5371.4 2320.75  5398.4 2330.35
  5429.1  2345.9  5471.8 2360.19  5480.1 2364.89  5490.3  2367.5  5554.9 2369.87
#Mann= 9 ,-1 , 0
  4512.3     .07       0  4558.3    .035       0  4671.2     .07       0
  4967.2     .07       0  4971.8     .07       0    5094     .16       0
  5150.5     .07       0  5308.9     .16       0  5358.4     .07       0
Bank Sta=4967.2,4971.8
XS Rating Curve= 0 ,0
Exp/Cntr=0.3,0.1

Type RM Length L Ch R = 1 ,4987    ,389,389,389
BEGIN DESCRIPTION:
MULBERRY CREEK TRIBUTARY 26 10.0
END DESCRIPTION:
XS GIS Cut Line= 3
      1451534.11      6807244.76      1451931.27      6806764.89
      1452047.12      6806203.11
#Sta/Elev= 30
  4377.1 2364.04  4395.9 2363.26    4418 2357.44  4432.3 2357.38  4438.8 2354.05
  4446.7 2353.99  4475.3 2344.24  4496.2 2334.19    4517 2328.56  4630.6 2316.22
  4737.1 2308.56  4886.9 2301.91  4901.3  2296.7  4907.7 2297.18  4915.6 2292.34
  4922.1  2292.5  4929.9 2287.93  4936.4 2288.72  4954.9 2284.74  4955.2 2284.24
  4959.5 2284.74  5093.3 2301.04  5170.4 2304.27  5344.7  2320.3  5389.9 2330.23
    5395 2334.93  5415.4 2345.34  5466.5 2361.05  5497.1 2365.01  5573.6  2369.2
#Mann= 5 ,-1 , 0
  4377.1     .07       0  4395.9    .035       0  4630.6     .07       0
  4954.9     .07       0  4959.5     .07       0
Bank Sta=4954.9,4959.5
XS Rating Curve= 0 ,0
Exp/Cntr=0.3,0.1

Type RM Length L Ch R = 1 ,4598    ,474,474,474
BEGIN DESCRIPTION:
MULBERRY CREEK TRIBUTARY 26 9.0
END DESCRIPTION:
XS GIS Cut Line= 3
      1451855.01      6807337.99        1452255.        6806938.
      1452405.01      6806537.97
#Sta/Elev= 30
    4430 2319.44  4557.3 2309.12  4755.3 2296.85  4797.7 2293.17  4882.5 2289.73
  4967.4    2288  4981.5 2286.67  4992.1 2283.46  4998.3 2283.46  5008.5 2279.67
  5008.8 2279.17  5013.2 2279.67    5017 2282.17  5027.7 2283.11  5049.1 2290.94
    5066 2293.97  5134.5 2296.75  5176.3 2296.52  5211.9 2298.84  5236.9 2302.65
  5242.2 2301.84  5267.1 2303.26  5347.2  2313.9  5369.5 2321.01  5382.8 2326.89
  5401.5 2337.39  5407.7 2342.55  5413.1 2342.53  5420.2 2348.08  5422.9 2348.08
#Mann= 3 ,-1 , 0
    4430     .07       0  5008.5     .07       0  5013.2     .07       0
Bank Sta=5008.5,5013.2
XS Rating Curve= 0 ,0
Exp/Cntr=0.3,0.1

Type RM Length L Ch R = 1 ,4124    ,472,472,472
BEGIN DESCRIPTION:
MULBERRY CREEK TRIBUTARY 26 8.0
END DESCRIPTION:
XS GIS Cut Line= 3
      1452304.97      6807588.03        1452605.        6807188.
      1452635.62       6806342.1
#Sta/Elev= 30
  4495.4 2353.16    4509 2348.87  4538.2  2333.1  4552.7 2323.17  4567.3 2318.24
  4625.7 2311.13  4702.7 2302.19  4838.2 2294.15  4902.7    2288  4923.6 2287.94
  4938.2 2285.74  4967.3 2276.42  4981.9 2277.55  4985.8 2276.24  4986.2 2275.74
  4990.5 2276.24  5035.5 2280.74  5083.5 2281.83  5195.6 2280.16  5318.5  2285.3
  5345.7 2287.86  5365.7 2287.67  5525.8 2302.69  5635.9 2314.92  5683.7 2323.42
  5688.7 2322.75  5715.9  2326.7  5755.9 2334.17    5816 2352.84  5841.9  2362.7
#Mann= 6 ,-1 , 0
  4495.4    .035       0  4625.7     .07       0  4985.8     .07       0
  4990.5     .07       0  5083.5     .16       0  5318.5     .07       0
Bank Sta=4985.8,4990.5
XS Rating Curve= 0 ,0
Exp/Cntr=0.3,0.1

Type RM Length L Ch R = 1 ,3652    ,388,388,388
BEGIN DESCRIPTION:
MULBERRY CREEK TRIBUTARY 26 7.0
END DESCRIPTION:
XS GIS Cut Line= 3
      1452836.19      6807833.29      1452989.61      6806937.03
      1452890.95      6806172.47
#Sta/Elev= 30
  4090.7  2303.7  4187.4  2297.9  4282.7 2296.12    4546 2290.86  4647.9 2288.89
  4867.1 2275.87  4958.4 2273.63  4994.6 2267.05  4994.9 2266.55  4999.4 2267.05
  5019.2  2274.3  5029.3 2275.91  5089.8 2280.44    5120 2284.81  5149.2 2286.36
  5291.4 2287.85  5301.5 2289.06    5308 2292.24  5331.8 2296.06  5422.5 2302.46
    5483 2310.59  5533.4 2314.73  5553.6 2319.83  5614.1 2329.82  5644.3 2342.07
  5694.7 2354.04    5700 2356.95    5705 2356.68  5735.1 2364.03  5770.9 2367.93
#Mann= 5 ,-1 , 0
  4090.7     .07       0  4282.7    .035       0    4546     .07       0
  4994.6     .07       0  4999.4     .07       0
Bank Sta=4994.6,4999.4
XS Rating Curve= 0 ,0
Exp/Cntr=0.3,0.1

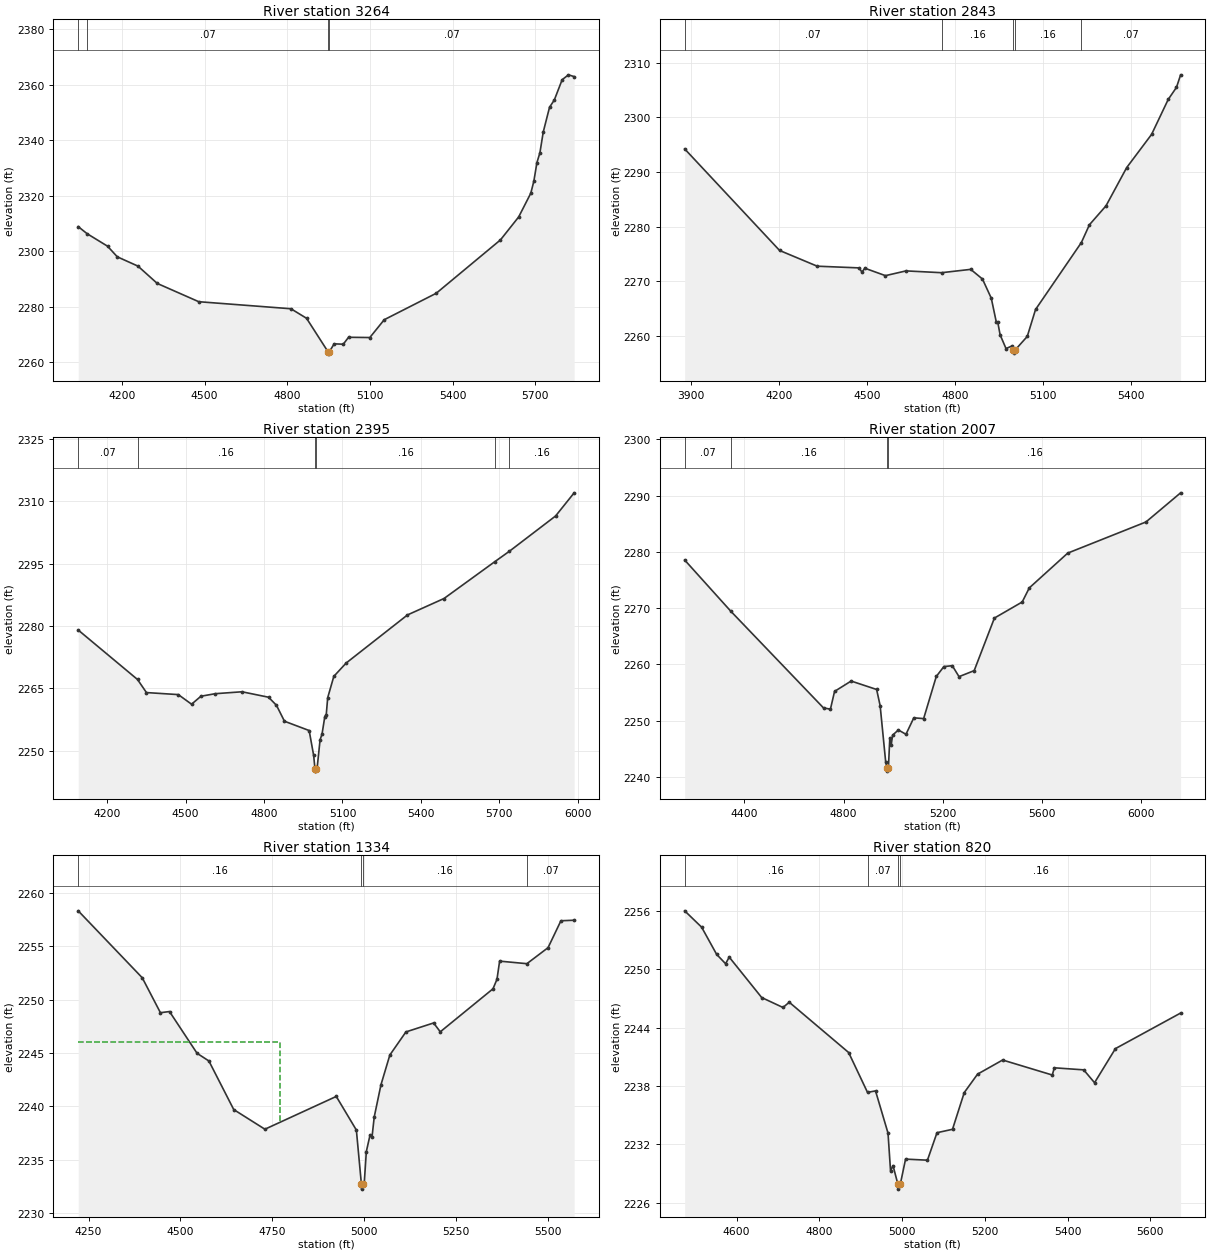
Type RM Length L Ch R = 1 ,3264    ,421,421,421
BEGIN DESCRIPTION:
MULBERRY CREEK TRIBUTARY 26 6.0
END DESCRIPTION:
XS GIS Cut Line= 3
      1453381.32      6807894.08        1453305.        6806938.
      1452950.78      6806175.37
#Sta/Elev= 30
  4041.5 2308.91  4073.8 2306.36  4147.9 2301.86  4183.4 2298.02  4258.3 2294.68
  4328.5 2288.43    4479 2281.85  4813.6 2279.31  4870.2 2275.88  4948.1 2263.82
  4948.4 2263.32  4952.9 2263.82  4970.5 2266.67  5003.4 2266.53  5022.7 2269.03
  5099.9 2268.94  5152.2 2275.36  5340.9 2284.89    5574 2304.12  5640.1 2312.39
  5684.2 2320.96  5695.3 2325.32  5706.4 2331.99  5717.3 2335.55  5729.3    2343
  5752.2 2351.93  5769.5 2354.54  5797.9 2361.84  5820.8 2363.61  5841.5 2362.97
#Mann= 4 ,-1 , 0
  4041.5    .035       0  4073.8     .07       0  4948.1     .07       0
  4952.9     .07       0
Bank Sta=4948.1,4952.9
XS Rating Curve= 0 ,0
Exp/Cntr=0.3,0.1

Type RM Length L Ch R = 1 ,2843    ,448,448,448
BEGIN DESCRIPTION:
MULBERRY CREEK TRIBUTARY 26 5.0
END DESCRIPTION:
XS GIS Cut Line= 3
      1453697.29      6807810.73        1453605.        6806688.
        1453205.        6806288.
#Sta/Elev= 30
  3878.6 2294.24  4202.4 2275.67  4330.8 2272.79  4473.3 2272.48  4483.4 2271.72
  4493.4 2272.42  4563.6 2271.06  4633.9 2271.93  4755.1  2271.6  4854.6 2272.21
  4894.7 2270.44  4924.8 2266.93    4942 2262.54    4947  2262.5  4954.9 2260.24
    4975 2257.73  4995.1 2258.19  5000.2 2257.39  5000.6 2256.89    5005 2257.39
  5047.5 2259.94  5075.8 2264.87  5232.1 2277.11  5259.7 2280.37  5316.2 2283.83
    5387 2290.84  5471.8  2296.9  5528.4 2303.28  5556.7  2305.5  5570.8 2307.79
#Mann= 5 ,-1 , 0
  3878.6     .07       0  4755.1     .16       0  5000.2     .07       0
    5005     .16       0  5232.1     .07       0
Bank Sta=5000.2,5005
XS Rating Curve= 0 ,0
Exp/Cntr=0.3,0.1

Type RM Length L Ch R = 1 ,2395    ,388,388,388
BEGIN DESCRIPTION:
MULBERRY CREEK TRIBUTARY 26 4.0
END DESCRIPTION:
XS GIS Cut Line= 3
      1453850.06      6807585.08        1454005.        6806688.
      1453613.98      6805783.03
#Sta/Elev= 30
  4089.6 2279.04  4316.3 2267.14  4350.5 2263.99  4472.3  2263.5    4523 2261.19
  4558.9 2263.11  4613.7 2263.72  4715.8 2264.18  4817.3 2262.87  4847.7 2260.92
  4878.2 2257.09  4972.6 2254.85  4989.8 2248.86  4994.9 2245.58  4995.3 2245.08
  4999.9 2245.58  5002.7 2245.58  5014.4 2252.64  5021.8 2253.98  5032.5 2258.22
  5037.9 2258.63  5043.5 2262.75  5066.9 2267.89  5113.9 2271.09  5348.6 2282.68
  5488.2 2286.63  5682.7 2295.51  5738.3 2298.01  5914.9  2306.5  5985.8 2312.07
#Mann= 6 ,-1 , 0
  4089.6     .07       0  4316.3     .16       0  4994.9     .07       0
  4999.9     .16       0  5682.7     .07       0  5738.3     .16       0
Bank Sta=4994.9,4999.9
XS Rating Curve= 0 ,0
Exp/Cntr=0.3,0.1

Type RM Length L Ch R = 1 ,2007    ,673,673,673
BEGIN DESCRIPTION:
MULBERRY CREEK TRIBUTARY 26 3.0
END DESCRIPTION:
XS GIS Cut Line= 3
      1453954.98      6807588.03      1454335.05      6806838.26
      1454114.28       6805701.3
#Sta/Elev= 30
  4159.4 2278.55  4345.4 2269.44  4718.9 2252.25  4746.8 2252.03  4763.5 2255.19
  4830.3 2257.03    4933 2255.53  4947.2 2252.65  4969.5 2242.66  4975.4 2241.51
  4975.8 2241.01  4980.4 2241.51  4986.2 2246.95  4991.8 2245.67  4997.3  2247.4
  5020.6 2248.33  5051.2 2247.56  5082.9 2250.49  5122.5 2250.35  5173.4 2257.84
    5204  2259.6    5238 2259.76  5265.1 2257.81  5326.2 2258.88  5407.7 2268.23
  5519.8 2271.09  5548.2 2273.59  5703.2 2279.78  6018.6 2285.32  6158.2  2290.5
#Mann= 4 ,-1 , 0
  4159.4     .07       0  4345.4     .16       0  4975.4     .07       0
  4980.4     .16       0
Bank Sta=4975.4,4980.4
XS Rating Curve= 0 ,0
Exp/Cntr=0.3,0.1

Type RM Length L Ch R = 1 ,1334    ,514,514,514
BEGIN DESCRIPTION:
MULBERRY CREEK TRIBUTARY 26 2.0
END DESCRIPTION:
XS GIS Cut Line= 3
      1454629.24        6807470.      1454907.74      6806743.34
      1454695.21      6806213.04
#Sta/Elev= 30
  4221.8 2258.32  4396.1 2252.05  4445.5 2248.78  4470.2 2248.89  4545.2 2244.98
  4577.4 2244.26    4645 2239.71  4729.8 2237.87    4924 2240.94  4978.7 2237.79
  4992.3 2232.76  4992.7 2232.26  4997.3 2232.76    5000 2232.76  5005.8 2235.78
    5016 2237.34  5021.4 2237.17  5027.3 2239.02  5045.6 2242.03  5069.8 2244.82
  5113.5 2246.98  5188.9 2247.82    5207 2246.99  5350.5 2251.02  5361.3 2251.91
  5368.5 2253.61  5442.7 2253.37  5500.3 2254.87  5535.3 2257.39  5571.3 2257.44
#Mann= 4 ,-1 , 0
  4221.8     .16       0  4992.3     .07       0  4997.3     .16       0
  5442.7     .07       0
#XS Ineff= 2 , 0
       0  4770.1    2246               0
Permanent Ineff=
       F       F
Bank Sta=4992.3,4997.3
XS Rating Curve= 0 ,0
Exp/Cntr=0.3,0.1

Type RM Length L Ch R = 1 ,820     ,360,360,360
BEGIN DESCRIPTION:
Mapping XS 54cc1ef5
END DESCRIPTION:
XS GIS Cut Line= 3
       1454900.1      6807581.08      1455182.28      6807143.65
      1455086.94      6806471.93
#Sta/Elev= 30
  4474.4 2255.98  4515.4  2254.3  4551.7 2251.51  4573.3 2250.55  4582.1 2251.23
  4660.6 2247.08  4712.1 2246.06  4727.2  2246.6  4870.8 2241.44  4916.4 2237.35
  4935.8  2237.5    4966 2233.17  4972.1 2229.29  4978.1 2229.83  4989.9 2227.92
  4990.4 2227.42  4995.7 2227.92  5008.4  2230.5  5061.3 2230.39  5084.4 2233.21
  5121.9 2233.56  5150.3 2237.33  5182.5 2239.22  5243.1 2240.67  5363.1 2239.13
  5368.1 2239.87  5439.1 2239.66  5465.3 2238.34  5515.8 2241.84  5673.4 2245.49
#Mann= 4 ,-1 , 0
  4474.4     .16       0  4916.4     .07       0  4989.9     .07       0
  4995.7     .16       0
Bank Sta=4989.9,4995.7
XS Rating Curve= 0 ,0
Exp/Cntr=0.3,0.1

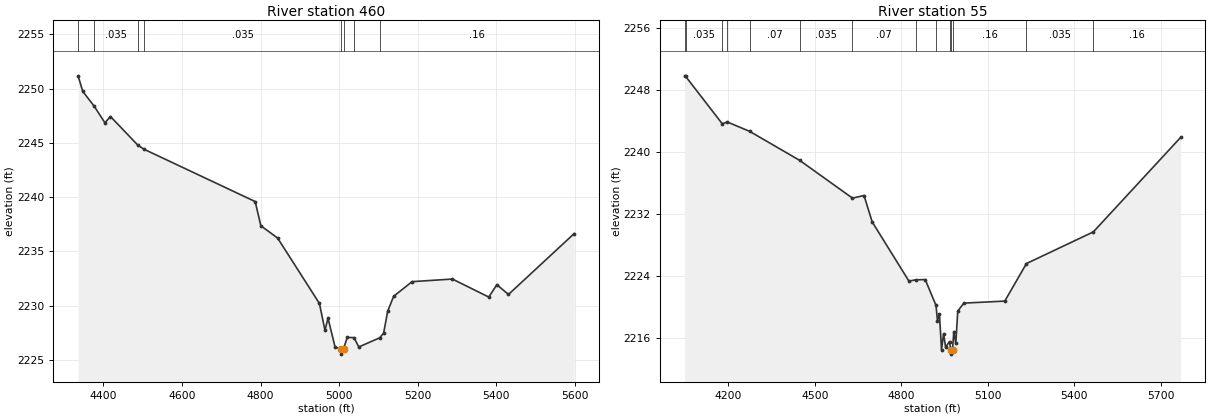
Type RM Length L Ch R = 1 ,460     ,405,405,405
BEGIN DESCRIPTION:
Mapping XS e5ffa6e3
END DESCRIPTION:
XS GIS Cut Line= 3
      1455087.59      6807647.08      1455500.77      6807171.39
      1455351.48      6806556.85
#Sta/Elev= 30
  4335.6 2251.18  4347.6 2249.74    4377 2248.36  4403.8 2246.85    4418 2247.43
  4487.7 2244.79  4503.7 2244.41  4786.4 2239.59  4800.7 2237.36  4843.4 2236.23
  4949.8  2230.2    4964 2227.71  4971.6 2228.86  4989.8 2226.16  5005.4 2226.03
  5005.9 2225.53  5011.2 2226.03  5020.6 2227.07  5037.9 2227.05    5050 2226.19
    5103 2227.03  5113.2 2227.46  5123.5 2229.48  5138.7 2230.86  5185.6 2232.21
  5288.2 2232.45  5380.8 2230.79  5401.4 2231.93    5431 2231.03  5598.1 2236.64
#Mann= 8 ,-1 , 0
  4335.6     .07       0    4377    .035       0  4487.7     .07       0
  4503.7    .035       0  5005.4     .07       0  5011.2    .035       0
  5037.9     .07       0    5103     .16       0
Bank Sta=5005.4,5011.2
XS Rating Curve= 0 ,0
Exp/Cntr=0.3,0.1

Type RM Length L Ch R = 1 ,55      ,0,0,0
BEGIN DESCRIPTION:
MULBERRY CREEK TRIBUTARY 26 1.0
END DESCRIPTION:
XS GIS Cut Line= 3
      1455179.97      6807713.03       1455849.7      6807037.29
      1455362.96      6806442.33
#Sta/Elev= 30
  4048.6 2249.85  4051.9  2249.8  4179.4 2243.65  4196.6 2243.89  4274.2 2242.68
  4447.8 2238.93  4630.9 2234.05  4670.9 2234.39  4699.2 2230.98  4826.5 2223.34
  4850.5  2223.5  4883.1 2223.53  4920.5  2220.2  4925.5 2218.24  4932.5 2219.04
  4939.6 2214.45  4946.7 2216.54  4953.8  2214.8  4967.3 2215.53    4972  2214.4
  4972.5  2213.9  4977.8  2214.4  4982.1 2216.81  4989.1  2215.3    4996 2219.46
  5016.9 2220.49    5159 2220.75  5234.1  2225.6  5466.1 2229.69  5768.7 2241.89
#Mann= 14 ,-1 , 0
  4048.6     .07       0  4051.9    .035       0  4179.4     .07       0
  4196.6    .035       0  4274.2     .07       0  4447.8    .035       0
  4630.9     .07       0  4850.5     .16       0  4920.5     .07       0
  4967.3     .16       0    4972     .07       0  4977.8     .16       0
  5234.1    .035       0  5466.1     .16       0
Bank Sta=4972,4977.8
XS Rating Curve= 0 ,0
Exp/Cntr=0.3,0.1

Chan Stop Cuts=-1
Use User Specified Reach Order=0
Composite Channel Slope=5