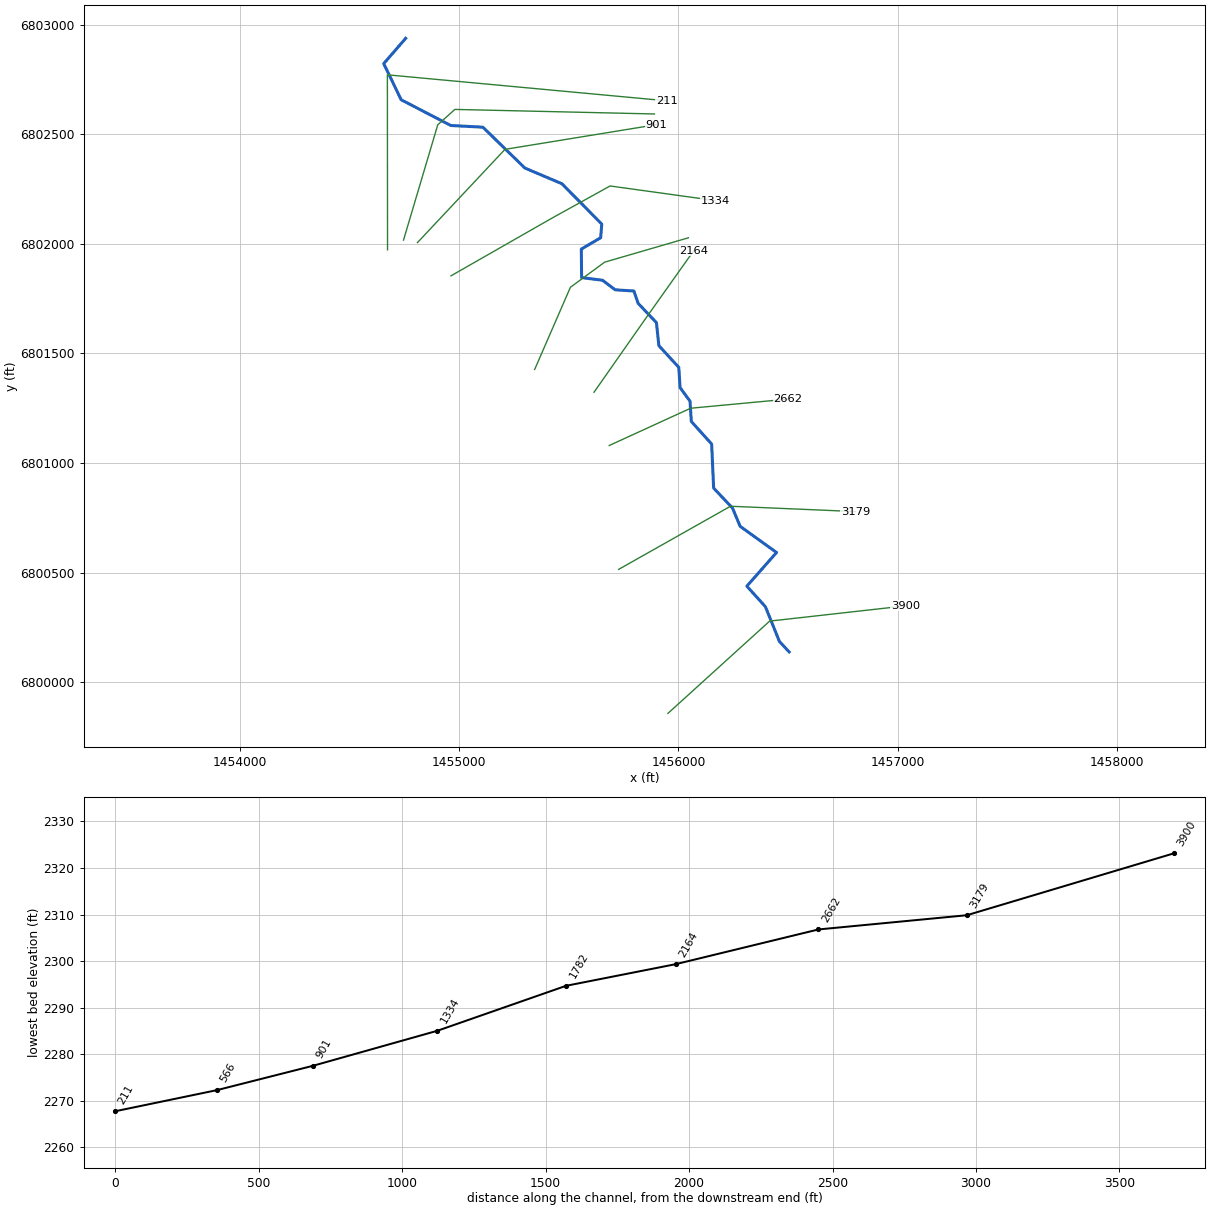
--- MULBERRY CREEK TRIBUTARY 27.prj (project) ---

Proj Title=MULBERRY CREEK TRIBUTARY 27 Base Level Engineering
Current Plan=p01
Default Exp/Contr=0.3,0.1
English Units
Geom File=g01
Flow File=f01
Plan File=p01
BEGIN DESCRIPTION:
MULBERRY CREEK TRIBUTARY 27
END DESCRIPTION:

--- MULBERRY CREEK TRIBUTARY 27.p01 (plan) ---

Plan Title=Multiple Run
Short Identifier=Multiple
Geom File=g01
Flow File=f01
Subcritical Flow
K Sum by GR= 0
Std Step Tol= 0.01
Critical Tol= 0.01
Num of Std Step Trials= 20
Max Error Tol= 0.3
Flow Tol Ratio= 0.001
Split Flow NTrial= 30
Split Flow Tol= 0.02
Split Flow Ratio= 0.02
Log Output Level= 0
Friction Slope Method= 1
Unsteady Friction Slope Method= 2
Unsteady Bridges Friction Slope Method= 1
Parabolic Critical Depth
Global Vel Dist=  1 , 1 , 1
Global Log Level= 0
CheckData=True
Encroach Param= -1, 0, 0, 0
BEGIN DESCRIPTION:
Multiple Run
END DESCRIPTION:

--- MULBERRY CREEK TRIBUTARY 27.f01 (steady flow) ---

Flow Title=Multiple
Number of Profiles=7
Profile Names=10-year,25-year,50-year,1pct_min,100-year,1pct_plu,500-year
River Rch & RM= MULBERRY CREEK T,Reach-1,3900
     289     413     519     325     648    1294    1023
River Rch & RM= MULBERRY CREEK T,Reach-1,3179
     372     538     682     430     859    1713    1377
Boundary for River Rch & Prof#=MULBERRY CREEK T,Reach-1,1
Up Type=0
Dn Type=3
Dn Slope=0.005
Boundary for River Rch & Prof#=MULBERRY CREEK T,Reach-1,2
Up Type=0
Dn Type=3
Dn Slope=0.005
Boundary for River Rch & Prof#=MULBERRY CREEK T,Reach-1,3
Up Type=0
Dn Type=3
Dn Slope=0.005
Boundary for River Rch & Prof#=MULBERRY CREEK T,Reach-1,4
Up Type=0
Dn Type=3
Dn Slope=0.005
Boundary for River Rch & Prof#=MULBERRY CREEK T,Reach-1,5
Up Type=0
Dn Type=3
Dn Slope=0.005
Boundary for River Rch & Prof#=MULBERRY CREEK T,Reach-1,6
Up Type=0
Dn Type=3
Dn Slope=0.005
Boundary for River Rch & Prof#=MULBERRY CREEK T,Reach-1,7
Up Type=0
Dn Type=3
Dn Slope=0.005

--- MULBERRY CREEK TRIBUTARY 27.g01 (geometry) ---

Geom Title=Existing Conditions

River Reach=MULBERRY CREEK T,Reach-1
Reach XY= 30
      1456505.00      6800138.00      1456460.67      6800185.64
      1456396.82      6800344.06      1456312.08      6800438.00
      1456447.52      6800591.58      1456281.27      6800711.12
      1456246.82      6800794.04      1456160.47      6800885.55
      1456151.45      6801086.53      1456058.62      6801189.50
      1456052.64      6801282.02      1456007.36      6801343.98
      1456001.38      6801436.50      1455910.54      6801535.58
      1455899.46      6801640.42      1455815.93      6801728.63
      1455796.66      6801784.84      1455711.06      6801790.39
      1455653.33      6801834.11      1455557.92      6801845.98
      1455556.63      6801976.15      1455644.90      6802028.03
      1455649.94      6802090.27      1455468.21      6802274.38
      1455298.94      6802346.14      1455107.45      6802532.53
      1454960.93      6802540.25      1454734.52      6802657.62
      1454654.91      6802822.66      1454755.00      6802938.00

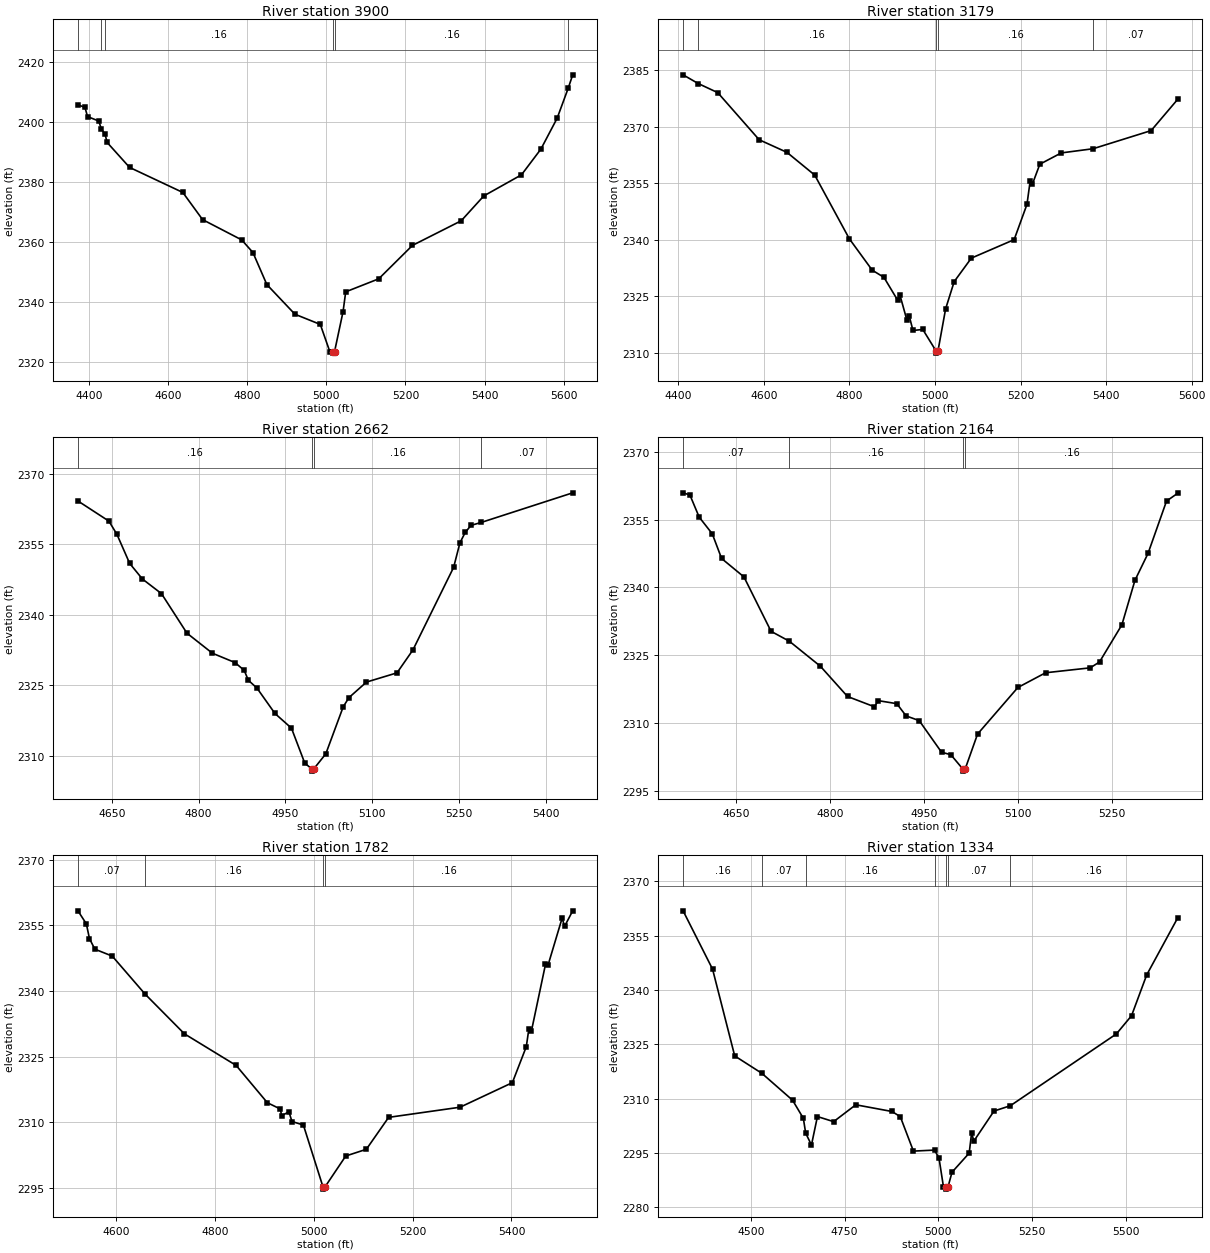
Type RM Length L Ch R = 1,3900,721,721,721
BEGIN DESCRIPTION:
MULBERRY CREEK TRIBUTARY 27 8.0
END DESCRIPTION:
XS GIS Cut Line= 3
      1455951.90      6799857.40      1456416.09      6800278.45
      1457034.81      6800347.85
#Sta/Elev= 30
  4373.3 2405.84  4390.4 2405.07  4397.1 2401.96  4425.5 2400.49  4432.1 2397.70
  4441.1 2396.18  4446.5 2393.35  4503.2 2385.03  4637.7 2376.68  4687.7 2367.62
  4786.4 2360.87  4814.8 2356.66  4850.0 2345.97  4920.9 2336.09  4985.0 2332.69
  5009.0 2323.64  5017.0 2323.62  5017.3 2323.12  5021.0 2323.62  5042.5 2336.96
  5049.2 2343.55  5132.6 2347.89  5217.8 2359.03  5341.0 2367.24  5398.0 2375.52
  5493.2 2382.56  5542.3 2391.14  5583.3 2401.43  5611.5 2411.53  5622.6 2415.89
#Mann=6,-1,0
  4373.3    0.16       0  4432.1    0.07       0  4441.1    0.16       0
  5017.0    0.07       0  5021.0    0.16       0  5611.5    0.07       0
Bank Sta=5017,5021
Exp/Cntr=0.3,0.1

Type RM Length L Ch R = 1,3179,517,517,517
BEGIN DESCRIPTION:
Mapping XS 2d386e97
END DESCRIPTION:
XS GIS Cut Line= 3
      1455727.06      6800514.51      1456237.48      6800802.71
      1456806.90      6800778.40
#Sta/Elev= 30
  4411.2 2383.76  4446.5 2381.45  4492.2 2379.03  4589.0 2366.52  4654.0 2363.17
  4718.9 2357.13  4799.8 2340.22  4853.3 2331.88  4880.7 2329.98  4912.5 2323.95
  4918.2 2325.22  4934.1 2318.73  4939.9 2319.66  4948.6 2315.86  4971.5 2316.14
  5002.9 2310.35  5003.1 2309.85  5006.9 2310.35  5024.9 2321.61  5044.9 2328.84
  5085.0 2335.08  5185.1 2339.99  5215.1 2349.38  5222.5 2355.55  5227.5 2354.66
  5245.1 2360.02  5295.2 2363.02  5369.5 2364.13  5505.3 2368.95  5567.3 2377.24
#Mann=5,-1,0
  4411.2    0.07       0  4446.5    0.16       0  5002.9    0.07       0
  5006.9    0.16       0  5369.5    0.07       0
Bank Sta=5002.9,5006.9
Exp/Cntr=0.3,0.1

Type RM Length L Ch R = 1,2662,498,498,498
BEGIN DESCRIPTION:
Mapping XS e2eac797
END DESCRIPTION:
XS GIS Cut Line= 3
      1455683.96      6801079.77      1456055.53      6801249.93
      1456500.00      6801291.60
#Sta/Elev= 30
  4591.8 2364.14  4645.0 2359.89  4658.9 2357.07  4680.9 2350.91  4702.9 2347.60
  4735.9 2344.49  4779.9 2336.10  4823.9 2331.84  4863.1 2329.85  4878.9 2328.20
  4886.1 2326.09  4900.9 2324.45  4932.1 2319.04  4960.6 2315.93  4983.6 2308.51
  4995.4 2307.30  4995.7 2306.80  4999.4 2307.30  5020.0 2310.47  5050.2 2320.49
  5060.2 2322.43  5090.3 2325.71  5143.1 2327.67  5170.7 2332.55  5241.0 2350.07
  5251.9 2355.28  5261.1 2357.50  5271.1 2358.99  5289.2 2359.63  5446.9 2365.90
#Mann=4,-1,0
  4591.8    0.16       0  4995.4    0.07       0  4999.4    0.16       0
  5289.2    0.07       0
Bank Sta=4995.4,4999.4
Exp/Cntr=0.3,0.1

Type RM Length L Ch R = 1,2164,382,382,382
BEGIN DESCRIPTION:
Mapping XS c6dda600
END DESCRIPTION:
XS GIS Cut Line= 3
      1455614.59      6801322.88      1455857.62      6801670.07
      1456069.43      6801968.68
#Sta/Elev= 30
  4565.0 2360.93  4575.9 2360.45  4590.7 2355.55  4611.6 2351.86  4626.5 2346.40
  4662.2 2342.32  4705.5 2330.28  4734.8 2328.08  4784.3 2322.55  4827.6 2315.86
  4870.6 2313.58  4876.7 2314.94  4906.3 2314.27  4921.2 2311.56  4942.1 2310.52
  4977.8 2303.52  4992.6 2302.98  5011.6 2299.84  5011.8 2299.34  5015.6 2299.84
  5035.3 2307.54  5099.7 2317.85  5144.0 2321.11  5215.3 2322.20  5230.1 2323.50
  5265.8 2331.71  5286.7 2341.57  5307.6 2347.53  5337.1 2359.10  5354.9 2360.83
#Mann=4,-1,0
  4565.0    0.07       0  4734.8    0.16       0  5011.6    0.07       0
  5015.6    0.16       0
Bank Sta=5011.6,5015.6
Exp/Cntr=0.3,0.1

Type RM Length L Ch R = 1,1782,448,448,448
BEGIN DESCRIPTION:
Mapping XS b28ae326
END DESCRIPTION:
XS GIS Cut Line= 4
      1455343.71      6801426.97      1455506.92      6801802.01
      1455663.17      6801916.59      1456045.15      6802027.72
#Sta/Elev= 30
  4523.3 2358.26  4539.9 2355.35  4546.2 2351.98  4557.1 2349.56  4592.3 2347.98
  4658.9 2339.27  4738.3 2330.21  4843.0 2322.98  4906.1 2314.46  4932.3 2313.02
  4935.1 2311.48  4949.7 2312.39  4955.9 2310.16  4979.0 2309.36  5018.7 2295.20
  5019.0 2294.70  5022.7 2295.20  5064.7 2302.27  5106.4 2303.81  5151.5 2311.11
  5296.0 2313.43  5401.8 2319.04  5430.0 2327.27  5435.3 2331.41  5440.5 2330.90
  5468.8 2346.07  5474.0 2345.91  5502.4 2356.63  5507.6 2354.82  5523.9 2358.33
#Mann=4,-1,0
  4523.3    0.07       0  4658.9    0.16       0  5018.7    0.07       0
  5022.7    0.16       0
Bank Sta=5018.7,5022.7
Exp/Cntr=0.3,0.1

Type RM Length L Ch R = 1,1334,433,433,433
BEGIN DESCRIPTION:
Mapping XS 2e6d931b
END DESCRIPTION:
XS GIS Cut Line= 4
      1454961.81      6801854.11      1455423.59      6802117.98
      1455687.91      6802264.25      1456166.68      6802197.84
#Sta/Elev= 30
  4319.9 2361.84  4398.4 2345.75  4457.4 2321.81  4529.6 2317.02  4611.5 2309.59
  4640.2 2304.60  4646.4 2300.51  4661.8 2297.23  4677.7 2305.08  4720.9 2303.68
  4779.9 2308.33  4876.2 2306.48  4898.4 2305.06  4933.4 2295.55  4989.6 2295.83
  5001.5 2293.63  5013.4 2285.70  5021.2 2285.56  5021.5 2285.06  5025.2 2285.56
  5036.2 2289.73  5081.9 2294.99  5088.5 2300.66  5094.2 2298.29  5148.0 2306.60
  5191.6 2308.07  5474.0 2327.88  5514.4 2332.91  5554.7 2344.15  5637.2 2359.87
#Mann=7,-1,0
  4319.9    0.16       0  4529.6    0.07       0  4646.4    0.16       0
  4989.6    0.07       0  5021.2    0.07       0  5025.2    0.07       0
  5191.6    0.16       0
Bank Sta=5021.2,5025.2
Exp/Cntr=0.3,0.1

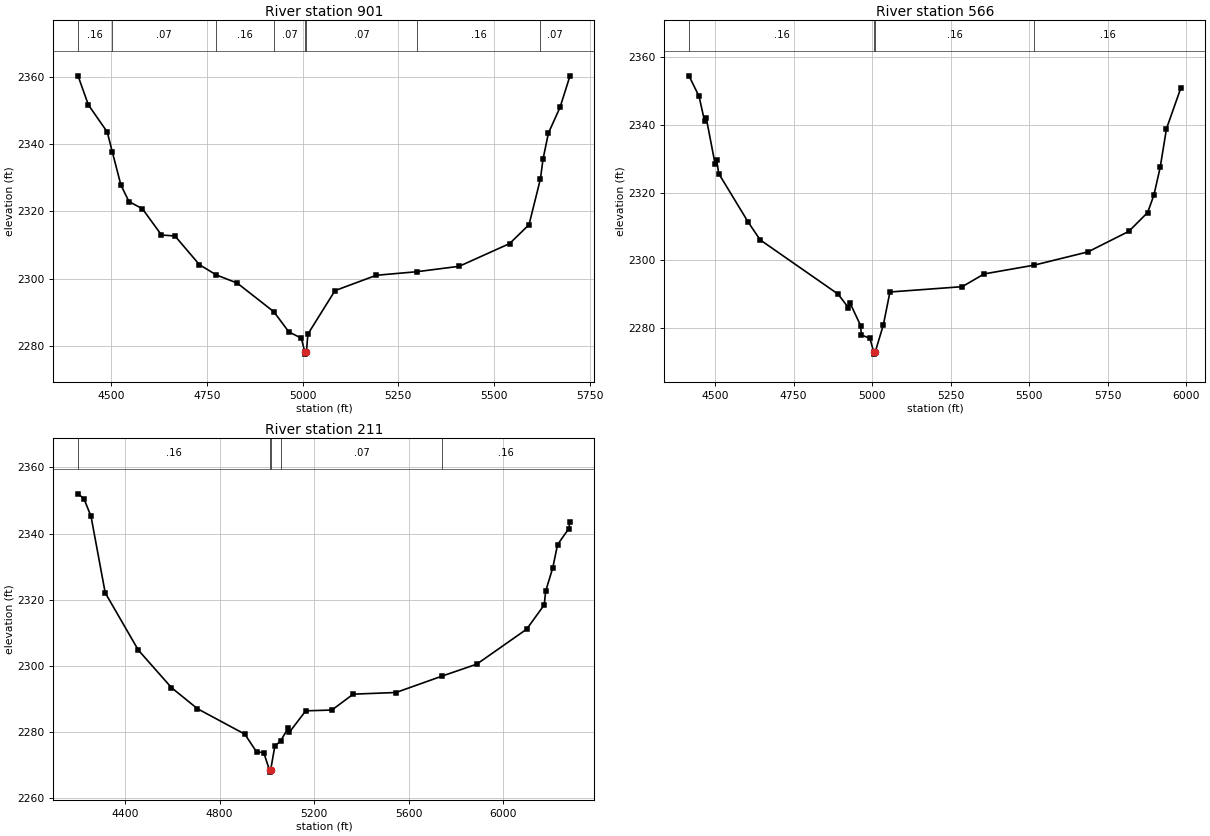
Type RM Length L Ch R = 1,901,335,335,335
BEGIN DESCRIPTION:
Mapping XS 40037d89
END DESCRIPTION:
XS GIS Cut Line= 3
      1454809.01      6802006.01      1455208.31      6802431.35
      1455900.28      6802544.15
#Sta/Elev= 30
  4413.7 2360.22  4440.7 2351.61  4490.0 2343.54  4503.3 2337.61  4525.7 2327.79
  4546.7 2322.88  4581.9 2320.73  4631.7 2312.93  4666.9 2312.65  4730.8 2304.12
  4774.4 2301.10  4829.5 2298.65  4925.1 2290.14  4964.3 2284.16  4997.1 2282.28
  5006.1 2278.05  5006.4 2277.55  5010.1 2278.05  5014.0 2283.49  5084.9 2296.42
  5192.6 2300.97  5298.6 2302.03  5409.2 2303.64  5540.9 2310.39  5591.5 2315.99
  5621.4 2329.62  5628.0 2335.40  5642.2 2343.20  5672.6 2350.87  5698.2 2360.08
#Mann=8,-1,0
  4413.7    0.16       0  4503.3    0.07       0  4774.4    0.16       0
  4925.1    0.07       0  5006.1    0.07       0  5010.1    0.07       0
  5298.6    0.16       0  5621.4    0.07       0
Bank Sta=5006.1,5010.1
Exp/Cntr=0.3,0.1

Type RM Length L Ch R = 1,566,355,355,355
BEGIN DESCRIPTION:
Mapping XS bcf2aa3f
END DESCRIPTION:
XS GIS Cut Line= 4
      1454745.20      6802017.27      1454901.45      6802543.33
      1454979.58      6802613.64      1455890.55      6802592.82
#Sta/Elev= 30
  4417.3 2354.51  4449.4 2348.44  4467.1 2341.05  4472.4 2341.99  4500.4 2328.50
  4505.6 2329.56  4512.0 2325.64  4605.2 2311.39  4643.6 2306.08  4891.7 2290.05
  4924.9 2286.02  4930.1 2287.36  4963.4 2280.76  4965.9 2278.01  4993.3 2276.94
  5005.5 2272.82  5005.7 2272.32  5009.5 2272.82  5035.9 2280.97  5056.8 2290.67
  5286.7 2292.24  5356.7 2296.01  5515.7 2298.60  5686.8 2302.51  5816.8 2308.57
  5876.8 2314.14  5896.8 2319.30  5916.8 2327.52  5936.8 2338.90  5982.4 2350.91
#Mann=4,-1,0
  4417.3    0.16       0  5005.5    0.07       0  5009.5    0.16       0
  5515.7    0.16       0
Bank Sta=5005.5,5009.5
Exp/Cntr=0.3,0.1

Type RM Length L Ch R = 1,211,0,0,0
BEGIN DESCRIPTION:
MULBERRY CREEK TRIBUTARY 27 1.0
END DESCRIPTION:
XS GIS Cut Line= 3
      1454672.29      6801972.98      1454671.58      6802771.48
      1455946.78      6802652.85
#Sta/Elev= 30
  4201.5 2352.01  4226.5 2350.55  4256.5 2345.18  4316.5 2322.05  4456.5 2304.71
  4596.5 2293.36  4706.5 2286.97  4906.5 2279.28  4956.5 2273.88  4986.5 2273.71
  5011.5 2268.28  5011.7 2267.78  5015.5 2268.28  5033.6 2275.67  5057.7 2277.18
  5090.2 2281.18  5095.2 2279.86  5164.1 2286.33  5274.6 2286.57  5365.0 2291.38
  5545.8 2291.88  5741.0 2296.86  5887.2 2300.46  6098.1 2311.04  6172.3 2318.39
  6178.5 2322.56  6208.6 2329.66  6228.7 2336.65  6276.5 2341.50  6280.7 2343.63
#Mann=5,-1,0
  4201.5    0.16       0  5011.5    0.07       0  5015.5    0.16       0
  5057.7    0.07       0  5741.0    0.16       0
Bank Sta=5011.5,5015.5
Exp/Cntr=0.3,0.1

Chan Stop Cuts=-1