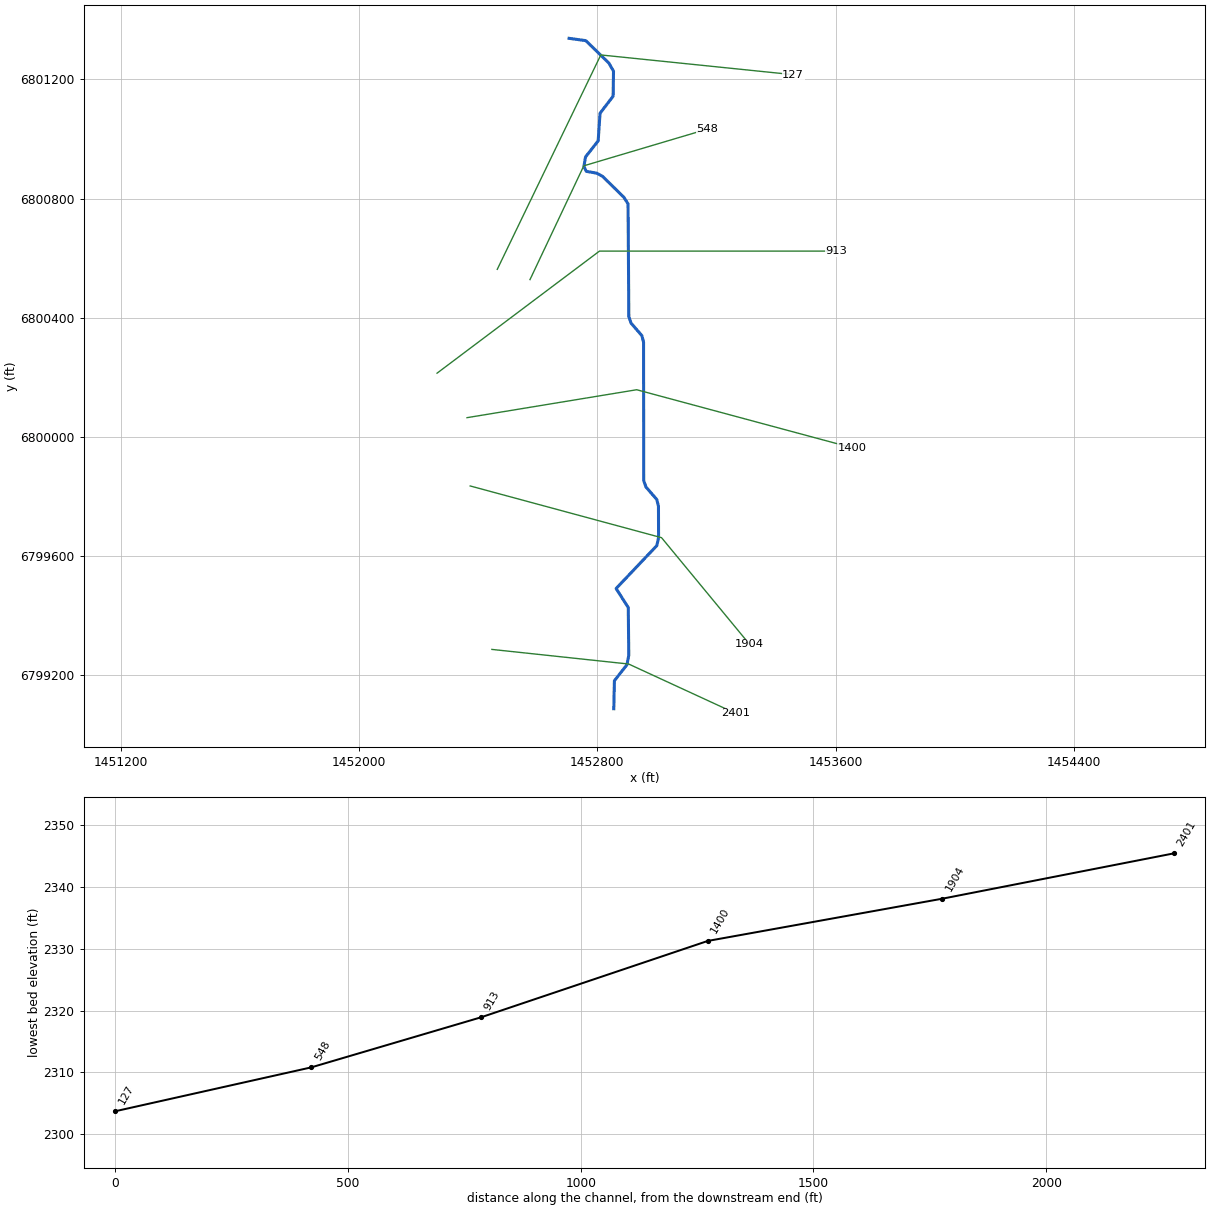
--- MULBERRY CREEK TRIBUTARY 28.prj (project) ---

Proj Title=MULBERRY CREEK TRIBUTARY 28 Base Level Engineering
Current Plan=p01
Default Exp/Contr=0.3,0.1
English Units
Geom File=g01
Flow File=f01
Plan File=p01
Y Axis Title=Elevation
X Axis Title(PF)=Main Channel Distance
X Axis Title(XS)=Station
BEGIN DESCRIPTION:
MULBERRY CREEK TRIBUTARY 28
END DESCRIPTION:
DSS Export Rating Curves= 0
DSS Export Rating Curve Sorted= 0
DSS Export Volume Flow Curves= 0
DXF OffsetX= 0
DXF OffsetY= 0
DXF ScaleX= 1
DXF ScaleY= 10

--- MULBERRY CREEK TRIBUTARY 28.p01 (plan) ---

Plan Title=Multiple Run
Short Identifier=Multiple
Geom File=g01
Flow File=f01
Subcritical Flow
K Sum by GR= 0
Std Step Tol= 0.01
Critical Tol= 0.01
Num of Std Step Trials= 20
Max Error Tol= 0.3
Flow Tol Ratio= 0.001
Split Flow NTrial= 30
Split Flow Tol= 0.02
Split Flow Ratio= 0.02
Log Output Level= 0
Friction Slope Method= 1
Unsteady Friction Slope Method= 2
Unsteady Bridges Friction Slope Method= 1
Parabolic Critical Depth
Global Vel Dist=  1 , 1 , 1
Global Log Level= 0
CheckData=True
Encroach Param= -1, 0, 0, 0
BEGIN DESCRIPTION:
Multiple Run
END DESCRIPTION:

--- MULBERRY CREEK TRIBUTARY 28.f01 (steady flow) ---

Flow Title=Multiple
Program Version=4.10
Number of Profiles= 7
Profile Names=10-year,25-year,50-year,1pct_min,100-year,1pct_plu,500-year
River Rch & RM=MULBERRY CREEK T,Reach-1         ,2401
     201     280     346     214     426     850     653
Boundary for River Rch & Prof#=MULBERRY CREEK T,Reach-1         , 1
Up Type= 0
Dn Type= 3
Dn Slope=0.02
Boundary for River Rch & Prof#=MULBERRY CREEK T,Reach-1         , 2
Up Type= 0
Dn Type= 3
Dn Slope=0.02
Boundary for River Rch & Prof#=MULBERRY CREEK T,Reach-1         , 3
Up Type= 0
Dn Type= 3
Dn Slope=0.02
Boundary for River Rch & Prof#=MULBERRY CREEK T,Reach-1         , 4
Up Type= 0
Dn Type= 3
Dn Slope=0.02
Boundary for River Rch & Prof#=MULBERRY CREEK T,Reach-1         , 5
Up Type= 0
Dn Type= 3
Dn Slope=0.02
Boundary for River Rch & Prof#=MULBERRY CREEK T,Reach-1         , 6
Up Type= 0
Dn Type= 3
Dn Slope=0.02
Boundary for River Rch & Prof#=MULBERRY CREEK T,Reach-1         , 7
Up Type= 0
Dn Type= 3
Dn Slope=0.02
DSS Import GetInterval= 0
DSS Import GetPeak= 0
DSS Import FillOption= 0

--- MULBERRY CREEK TRIBUTARY 28.g01 (geometry) ---

Geom Title=Existing Conditions
Program Version=4.10

River Reach=MULBERRY CREEK T,Reach-1
Reach XY= 30
        1452855.        6799088.       1452857.1      6799182.13
      1452899.29      6799235.65      1452905.36      6799267.85
      1452903.61      6799427.57      1452862.79      6799491.42
      1452999.55      6799635.55      1453005.32      6799662.89
      1453004.95      6799767.96      1452999.26      6799790.33
      1452963.14      6799831.94      1452955.52      6799853.22
      1452954.93      6800317.97      1452949.25      6800340.33
      1452913.14      6800381.94      1452905.52      6800403.22
      1452902.95      6800782.16      1452888.58       6800804.8
      1452817.94      6800874.29      1452798.39      6800885.31
      1452762.74      6800891.54      1452754.69      6800908.34
      1452760.21      6800939.84      1452802.61      6800993.94
      1452808.86       6801086.4      1452852.84      6801143.98
      1452854.07      6801227.53      1452838.63      6801254.79
      1452761.24      6801330.25        1452705.        6801338.

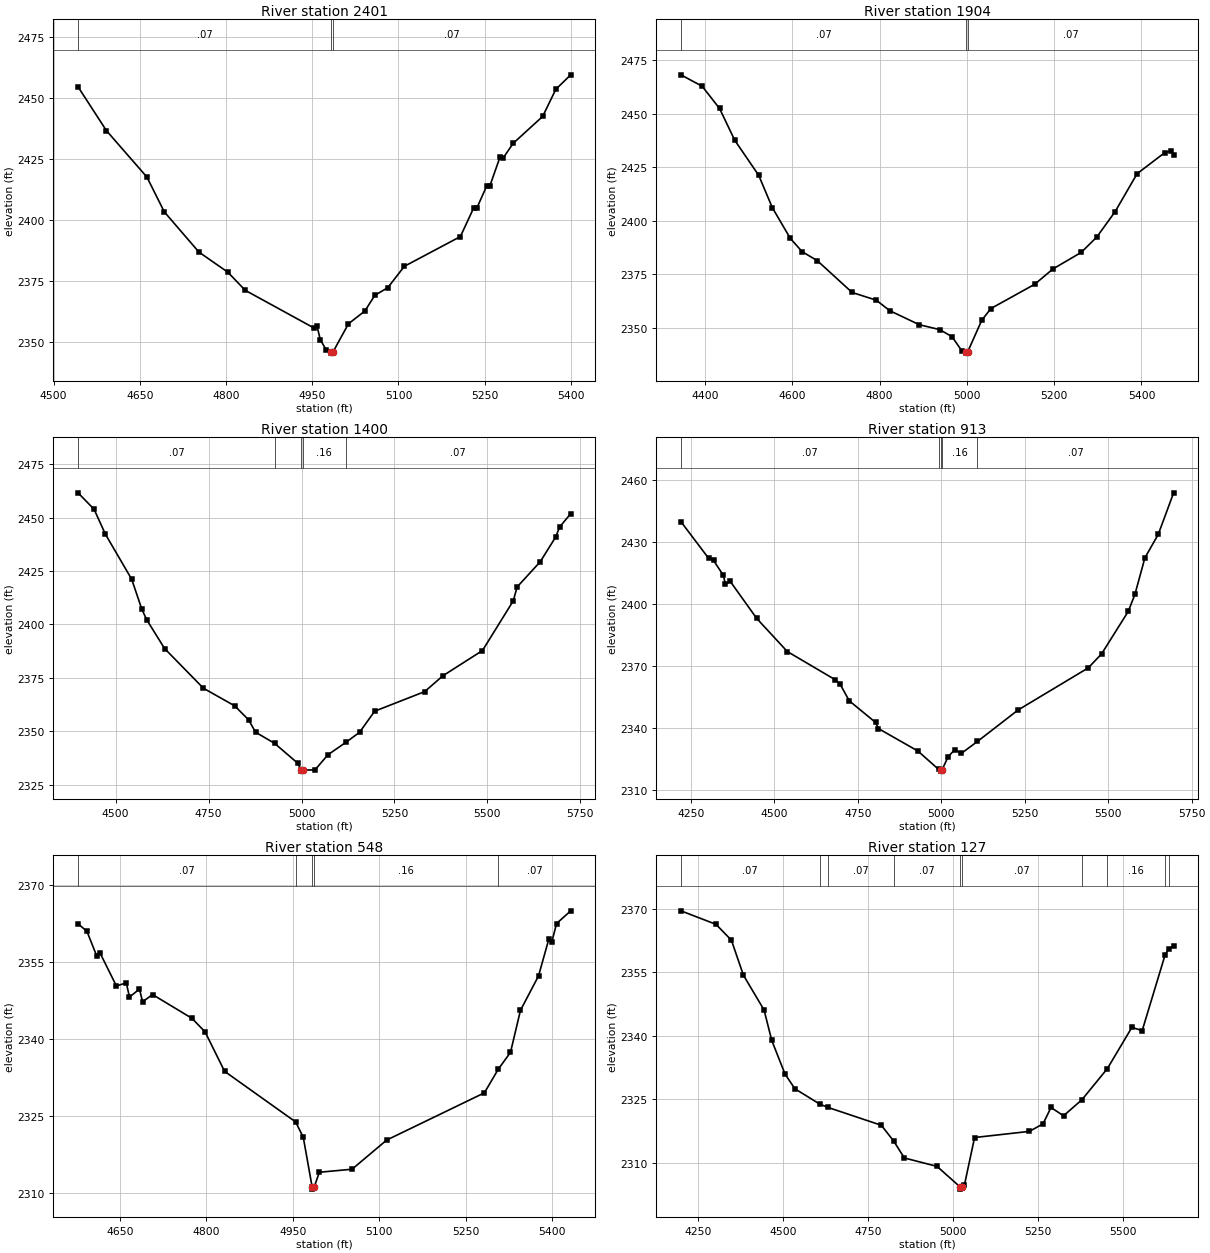
Type RM Length L Ch R = 1 ,2401    ,497,497,497
BEGIN DESCRIPTION:
MULBERRY CREEK TRIBUTARY 28 5.0
END DESCRIPTION:
XS GIS Cut Line= 3
      1452445.89      6799287.08        1452905.        6799238.
      1453264.02      6799072.39
#Sta/Elev= 30
  4542.6 2454.58    4592 2436.63  4662.4  2417.6  4692.6 2403.36  4752.9 2386.85
  4803.2 2378.61  4833.4 2371.19  4953.1 2355.74  4958.2  2356.6  4964.1 2350.91
  4974.2 2346.81  4982.2 2345.94  4982.5 2345.44  4986.2 2345.94    5013 2357.47
  5041.5 2362.69  5058.9 2369.15  5081.4 2372.26  5110.3 2381.03  5207.7 2393.21
  5230.6 2404.81  5236.1 2404.75  5253.6 2414.01  5259.1 2414.05  5276.5 2425.68
    5282 2425.35  5299.5 2431.42  5350.9 2442.47  5373.8  2453.6  5399.7 2459.51
#Mann= 3 ,-1 , 0
  4542.6     .07       0  4982.2     .07       0  4986.2     .07       0
Bank Sta=4982.2,4986.2
XS Rating Curve= 0 ,0
Exp/Cntr=0.3,0.1

Type RM Length L Ch R = 1 ,1904    ,504,504,504
BEGIN DESCRIPTION:
Mapping XS 7d11562e
END DESCRIPTION:
XS GIS Cut Line= 3
      1452372.97      6799835.68      1453015.29      6799662.08
       1453310.2      6799304.72
#Sta/Elev= 30
  4344.9  2468.2  4393.6 2462.85  4433.4 2452.46  4468.1 2437.64  4523.1 2421.21
  4554.2 2406.13  4595.6 2391.71  4622.5 2385.55  4657.2 2381.35    4737 2366.47
  4792.4 2362.86  4823.5 2357.92  4891.3 2351.37  4937.5 2349.12  4965.9 2345.81
  4989.3 2338.91  4997.6 2338.61  4997.9 2338.11  5001.6 2338.61  5034.2 2353.53
    5055 2358.95  5155.4  2370.3  5197.1 2377.45  5261.9 2385.19  5297.4 2392.33
  5339.7 2404.28  5389.9 2421.98  5453.7 2431.89  5468.1  2432.6  5473.6  2430.8
#Mann= 3 ,-1 , 0
  4344.9     .07       0  4997.6     .07       0  5001.6     .07       0
Bank Sta=4997.6,5001.6
XS Rating Curve= 0 ,0
Exp/Cntr=0.3,0.1

Type RM Length L Ch R = 1 ,1400    ,487,487,487
BEGIN DESCRIPTION:
Mapping XS 999561e5
END DESCRIPTION:
XS GIS Cut Line= 3
       1452362.5      6800064.86      1452931.96      6800158.61
      1453654.22      6799964.15
#Sta/Elev= 30
    4399 2461.57  4442.1 2453.87  4472.5 2442.22  4543.4 2421.07  4570.5 2407.08
    4584 2402.04  4631.7 2388.68    4736 2370.11  4820.3 2361.83  4857.6 2355.31
  4876.4  2349.5  4927.6 2344.27  4989.6 2335.02  4999.4 2331.77  4999.7 2331.27
  5003.4 2331.77  5036.2 2331.83    5071 2338.92    5119  2344.7    5156 2349.42
  5196.7 2359.32  5331.4 2368.51  5380.2  2375.9  5486.7 2387.73  5569.5 2410.98
  5579.9 2417.49  5642.1 2429.31  5683.5 2440.87  5694.5 2445.62  5724.1 2451.84
#Mann= 5 ,-1 , 0
    4399     .07       0  4927.6     .16       0  4999.4     .07       0
  5003.4     .16       0    5119     .07       0
Bank Sta=4999.4,5003.4
XS Rating Curve= 0 ,0
Exp/Cntr=0.3,0.1

Type RM Length L Ch R = 1 ,913     ,365,365,365
BEGIN DESCRIPTION:
Mapping XS 0b787d9a
END DESCRIPTION:
XS GIS Cut Line= 3
      1452261.83      6800214.17      1452806.96      6800623.89
      1453601.03      6800623.89
#Sta/Elev= 30
    4220 2439.84  4303.3    2422  4317.8 2421.02    4347 2413.84  4353.3 2409.54
  4367.8 2410.87    4447 2392.93  4538.6  2376.9  4682.3 2363.21  4696.9 2361.04
  4724.3 2352.99  4803.1  2342.5  4811.4 2339.57    4930 2328.64  4991.8 2319.77
    4998 2319.41  4998.2 2318.91    5002 2319.41    5020 2325.76    5040 2329.27
    5060  2327.5  5108.2 2333.28    5230 2348.54    5440 2368.93    5480  2375.7
    5560 2396.32    5580 2404.56    5610 2422.33    5650 2433.68    5696 2453.82
#Mann= 5 ,-1 , 0
    4220     .07       0  4991.8     .16       0    4998     .07       0
    5002     .16       0  5108.2     .07       0
Bank Sta=4998,5002
XS Rating Curve= 0 ,0
Exp/Cntr=0.3,0.1

Type RM Length L Ch R = 1 ,548     ,421,421,421
BEGIN DESCRIPTION:
Mapping XS bccc445b
END DESCRIPTION:
XS GIS Cut Line= 3
       1452573.8      6800528.22      1452754.34      6800910.13
      1453168.61       6801033.2
#Sta/Elev= 30
  4577.3 2362.52  4592.7 2361.06    4610 2356.16  4615.5 2356.81  4643.8 2350.41
    4661    2351  4666.5 2348.24  4683.8 2349.79  4689.3 2347.32  4706.5 2348.73
  4774.8  2344.1  4797.6 2341.46  4831.5 2333.76  4954.7  2323.9    4968  2320.9
  4983.2  2311.3  4983.4  2310.8  4987.2  2311.3  4995.8 2314.09  5052.6 2314.68
  5112.6 2320.36  5282.1 2329.57  5306.3 2334.19  5327.4 2337.46  5344.7 2345.65
    5376 2352.35  5393.9 2359.54  5399.1 2358.99  5407.3 2362.57  5431.9 2365.05
#Mann= 5 ,-1 , 0
  4577.3     .07       0  4954.7     .16       0  4983.2     .07       0
  4987.2     .16       0  5306.3     .07       0
Bank Sta=4983.2,4987.2
XS Rating Curve= 0 ,0
Exp/Cntr=0.3,0.1

Type RM Length L Ch R = 1 ,127     ,0,0,0
BEGIN DESCRIPTION:
MULBERRY CREEK TRIBUTARY 28 1.0
END DESCRIPTION:
XS GIS Cut Line= 3
      1452463.92       6800562.7      1452811.42      6801282.28
      1453456.94      6801216.05
#Sta/Elev= 30
  4200.9 2369.55    4304 2366.35  4349.2  2362.6  4384.5 2354.33  4445.2 2346.09
  4467.8 2338.89  4506.6 2330.97  4535.6 2327.46  4608.6 2323.83  4632.8 2323.04
  4789.8 2318.81  4826.4 2315.05  4857.6 2311.07  4953.6 2309.08  5021.7  2304.2
  5021.9  2303.7  5025.7  2304.2  5033.8 2304.56  5063.9 2315.91  5224.7 2317.36
    5265 2319.13  5288.5 2323.02  5325.3 2321.05  5379.3 2324.84  5454.2 2332.22
  5526.3 2341.98  5556.5 2341.19  5623.9 2359.14  5634.1  2360.5  5648.9 2361.34
#Mann= 10 ,-1 , 0
  4200.9     .07       0  4608.6     .16       0  4632.8     .07       0
  4826.4     .07       0  5021.7    .035       0  5025.7     .07       0
  5379.3     .07       0  5454.2     .16       0  5623.9     .07       0
  5634.1     .16       0
Bank Sta=5021.7,5025.7
XS Rating Curve= 0 ,0
Exp/Cntr=0.3,0.1

Chan Stop Cuts=-1
Use User Specified Reach Order=0
Composite Channel Slope=5