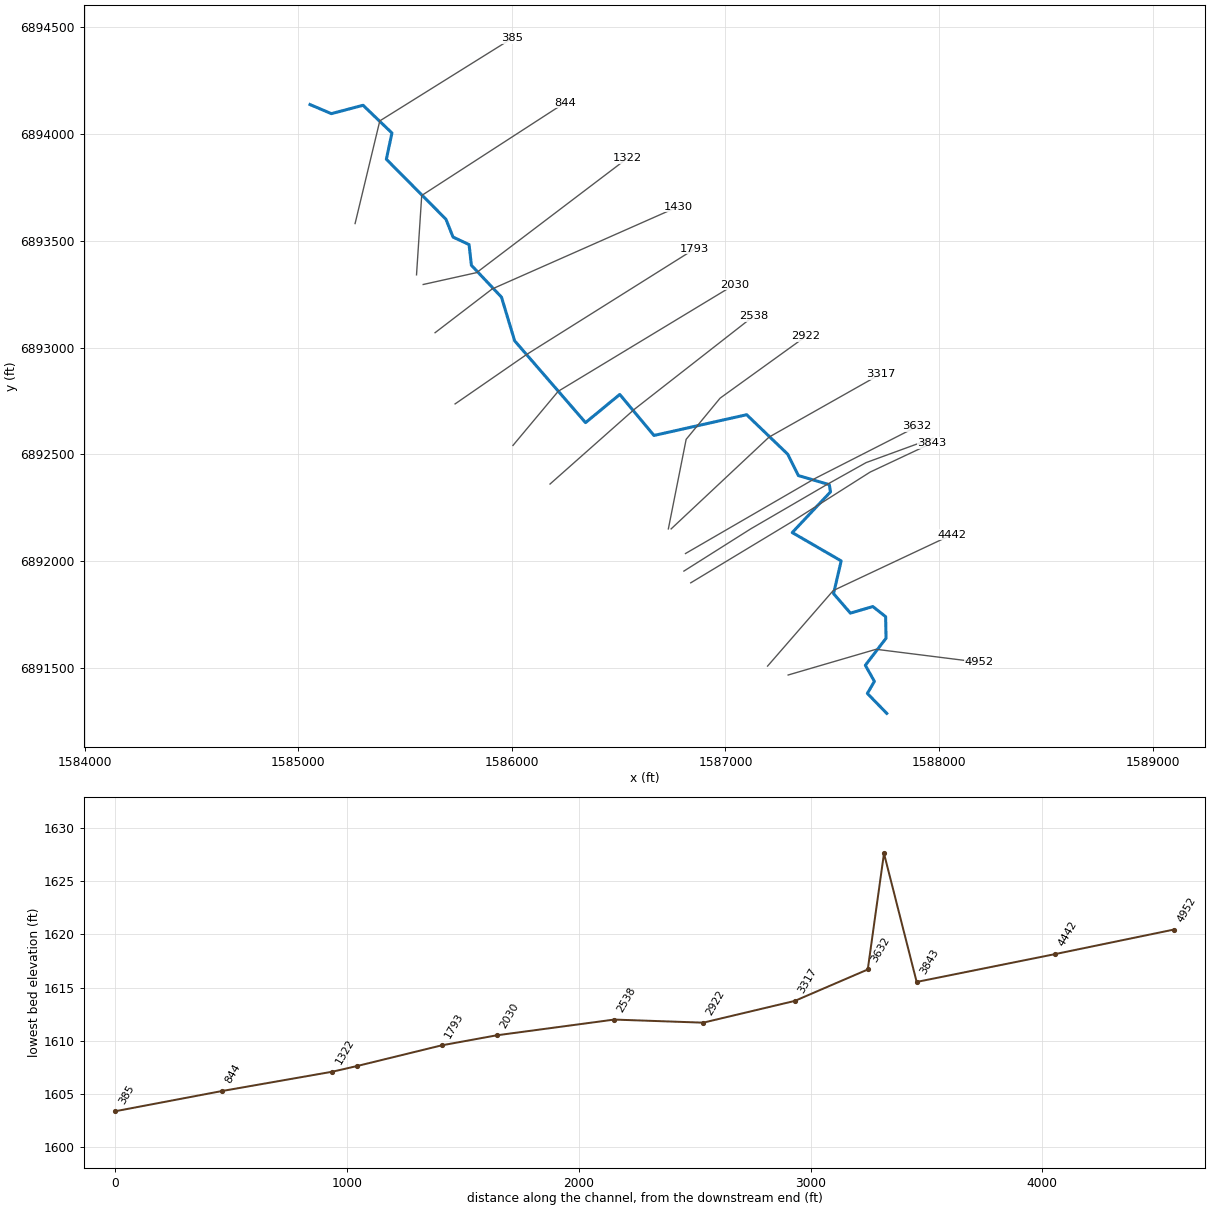
--- MULBERRY CREEK TRIBUTARY 2_1.prj (project) ---

Proj Title=MULBERRY CREEK TRIBUTARY 2_1 Base Level Engineering
Current Plan=p01
Default Exp/Contr=0.3,0.1
English Units
Geom File=g01
Flow File=f01
Plan File=p01
BEGIN DESCRIPTION:
MULBERRY CREEK TRIBUTARY 2_1
END DESCRIPTION:

--- MULBERRY CREEK TRIBUTARY 2_1.p01 (plan) ---

Plan Title=Multiple Run
Short Identifier=Multiple
Geom File=g01
Flow File=f01
Subcritical Flow
K Sum by GR= 0
Std Step Tol= 0.01
Critical Tol= 0.01
Num of Std Step Trials= 20
Max Error Tol= 0.3
Flow Tol Ratio= 0.001
Split Flow NTrial= 30
Split Flow Tol= 0.02
Split Flow Ratio= 0.02
Log Output Level= 0
Friction Slope Method= 1
Unsteady Friction Slope Method= 2
Unsteady Bridges Friction Slope Method= 1
Parabolic Critical Depth
Global Vel Dist=  1 , 1 , 1
Global Log Level= 0
CheckData=True
Encroach Param= -1, 0, 0, 0
BEGIN DESCRIPTION:
Multiple Run
END DESCRIPTION:

--- MULBERRY CREEK TRIBUTARY 2_1.f01 (steady flow) ---

Flow Title=Multiple
Number of Profiles=7
Profile Names=10-year,25-year,50-year,1pct_min,100-year,1pct_plu,500-year
River Rch & RM= MULBERRY CREEK T,Reach-1,4952
     169     229     276     167     333     663     487
Boundary for River Rch & Prof#=MULBERRY CREEK T,Reach-1,1
Up Type=0
Dn Type=3
Dn Slope=0.005
Boundary for River Rch & Prof#=MULBERRY CREEK T,Reach-1,2
Up Type=0
Dn Type=3
Dn Slope=0.005
Boundary for River Rch & Prof#=MULBERRY CREEK T,Reach-1,3
Up Type=0
Dn Type=3
Dn Slope=0.005
Boundary for River Rch & Prof#=MULBERRY CREEK T,Reach-1,4
Up Type=0
Dn Type=3
Dn Slope=0.005
Boundary for River Rch & Prof#=MULBERRY CREEK T,Reach-1,5
Up Type=0
Dn Type=3
Dn Slope=0.005
Boundary for River Rch & Prof#=MULBERRY CREEK T,Reach-1,6
Up Type=0
Dn Type=3
Dn Slope=0.005
Boundary for River Rch & Prof#=MULBERRY CREEK T,Reach-1,7
Up Type=0
Dn Type=3
Dn Slope=0.005

--- MULBERRY CREEK TRIBUTARY 2_1.g01 (geometry) ---

Geom Title=Existing Conditions

River Reach=MULBERRY CREEK T,Reach-1
Reach XY= 30
      1587755.00      6891288.00      1587664.16      6891381.33
      1587697.17      6891437.91      1587654.59      6891513.00
      1587751.53      6891639.50      1587749.71      6891740.75
      1587689.78      6891788.04      1587584.92      6891757.28
      1587505.94      6891848.47      1587541.62      6892001.74
      1587312.48      6892134.42      1587491.64      6892324.79
      1587485.99      6892358.48      1587341.35      6892401.26
      1587291.36      6892501.20      1587099.11      6892686.04
      1586665.33      6892588.87      1586505.01      6892780.93
      1586345.00      6892648.95      1586013.14      6893031.94
      1585951.39      6893236.50      1585810.55      6893385.63
      1585799.71      6893482.52      1585724.74      6893517.57
      1585691.36      6893601.20      1585412.50      6893881.95
      1585438.70      6894004.70      1585303.50      6894134.54
      1585154.96      6894095.32      1585055.00      6894138.00

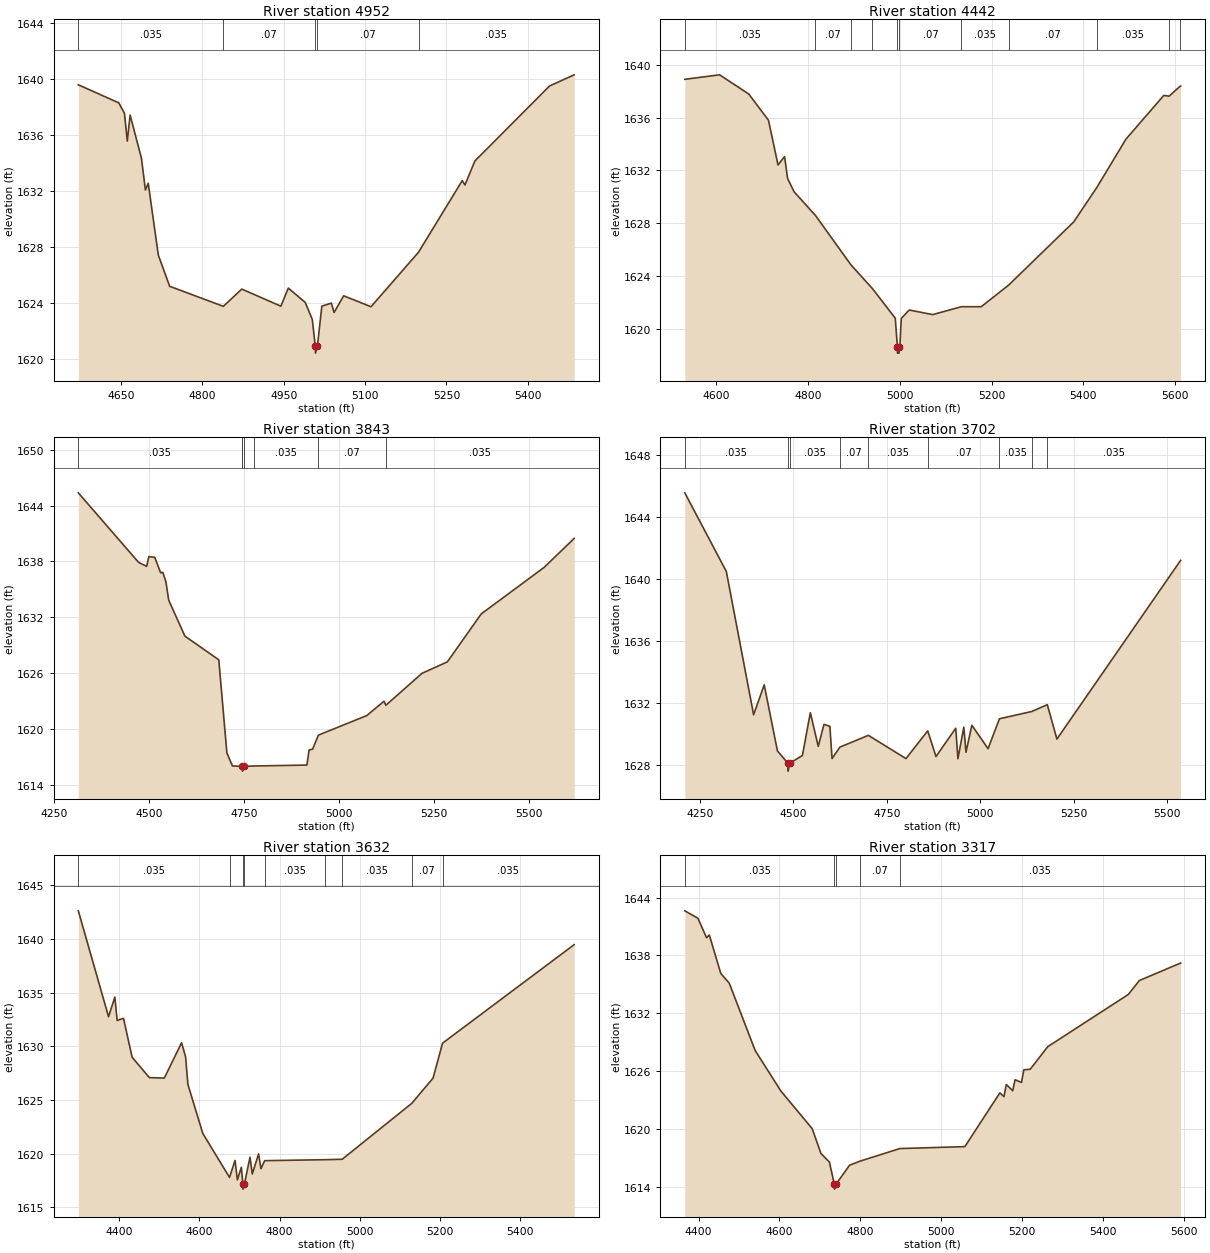
Type RM Length L Ch R = 1,4952,510,510,510
BEGIN DESCRIPTION:
MULBERRY CREEK TRIBUTARY 2_1 10.0
END DESCRIPTION:
XS GIS Cut Line= 3
      1587293.39      6891467.64      1587705.00      6891588.00
      1588186.68      6891527.54
#Sta/Elev= 30
  4571.2 1639.59  4645.8 1638.30  4656.2 1637.56  4661.5 1635.57  4666.7 1637.43
  4687.5 1634.36  4694.9 1632.08  4700.1 1632.56  4718.7 1627.44  4739.6 1625.21
  4838.6 1623.78  4872.6 1625.01  4944.7 1623.79  4958.4 1625.08  4989.6 1624.06
  5002.6 1622.85  5008.1 1620.94  5008.4 1620.44  5012.1 1620.94  5020.2 1623.79
  5037.8 1624.01  5042.8 1623.34  5060.5 1624.53  5110.9 1623.75  5198.5 1627.64
  5279.1 1632.75  5284.2 1632.44  5302.4 1634.15  5440.0 1639.50  5485.5 1640.30
#Mann=5,-1,0
  4571.2   0.035       0  4838.6    0.07       0  5008.1    0.07       0
  5012.1    0.07       0  5198.5   0.035       0
Bank Sta=5008.1,5012.1
Exp/Cntr=0.3,0.1

Type RM Length L Ch R = 1,4442,599,599,599
BEGIN DESCRIPTION:
MULBERRY CREEK TRIBUTARY 2_1 9.0
END DESCRIPTION:
XS GIS Cut Line= 3
      1587197.06      6891509.32      1587504.51      6891862.96
      1588058.09      6892123.45
#Sta/Elev= 30
  4531.4 1638.91  4607.3 1639.25  4670.9 1637.79  4713.7 1635.81  4734.5 1632.42
  4748.8 1633.05  4755.4 1631.39  4769.6 1630.38  4816.1 1628.59  4893.3 1624.85
  4940.3 1623.04  4990.0 1620.80  4994.6 1618.65  4994.8 1618.15  4998.3 1618.15
  4998.6 1618.65  5000.0 1618.65  5003.1 1620.78  5020.4 1621.42  5071.5 1621.07
  5134.3 1621.67  5177.4 1621.67  5236.8 1623.30  5378.9 1628.10  5429.2 1630.71
  5492.8 1634.38  5575.2 1637.69  5586.6 1637.63  5610.2 1638.37  5611.8 1638.39
#Mann=11,-1,0
  4531.4   0.035       0  4816.1    0.07       0  4893.3   0.035       0
  4940.3    0.07       0  4994.6    0.07       0  4998.6    0.07       0
  5134.3   0.035       0  5236.8    0.07       0  5429.2   0.035       0
  5586.6    0.07       0  5610.2   0.035       0
Bank Sta=4994.6,4998.6
Exp/Cntr=0.3,0.1

Type RM Length L Ch R = 1,3843,141,141,141
BEGIN DESCRIPTION:
MULBERRY CREEK TRIBUTARY 2_1 8.0
END DESCRIPTION:
XS GIS Cut Line= 4
      1586837.38      6891899.05      1587307.41      6892182.90
      1587676.99      6892417.38      1587966.60      6892553.54
#Sta/Elev= 30
  4312.9 1645.36  4471.6 1637.91  4492.9 1637.48  4498.8 1638.52  4514.3 1638.45
  4529.8 1636.79  4535.6 1636.84  4543.8 1635.81  4551.1 1633.85  4593.8 1630.00
  4683.1 1627.46  4704.4 1617.49  4719.0 1616.09  4745.1 1616.03  4745.2 1616.03
  4745.4 1615.53  4749.2 1616.03  4774.9 1616.08  4915.3 1616.18  4921.2 1617.81
  4930.2 1617.87  4945.7 1619.39  5072.9 1621.48  5118.6 1623.02  5123.5 1622.59
  5218.6 1626.01  5285.5 1627.24  5374.8 1632.38  5540.6 1637.37  5619.7 1640.47
#Mann=7,-1,0
  4312.9   0.035       0  4745.1    0.07       0  4745.2    0.07       0
  4749.2    0.07       0  4774.9   0.035       0  4945.7    0.07       0
  5123.5   0.035       0
Bank Sta=4745.2,4749.2
Exp/Cntr=0.3,0.1

Type RM Length L Ch R = 1,3702,70,70,70
BEGIN DESCRIPTION:
Mapping XS aba6fa5d
END DESCRIPTION:
XS GIS Cut Line= 5
      1586805.41      6891954.05      1587117.91      6892151.53
      1587475.99      6892359.86      1587658.28      6892461.86
      1587971.49      6892576.34
#Sta/Elev= 30
  4209.6 1645.56  4320.7 1640.48  4393.7 1631.23  4422.0 1633.16  4457.5 1628.89
  4485.8 1628.09  4486.0 1627.59  4489.8 1628.09  4524.2 1628.60  4545.4 1631.36
  4566.6 1629.19  4581.9 1630.61  4597.7 1630.48  4603.5 1628.40  4624.4 1629.14
  4700.6 1629.90  4801.2 1628.40  4859.4 1630.19  4881.5 1628.53  4934.4 1630.36
  4940.2 1628.39  4956.0 1630.43  4961.7 1628.81  4977.5 1630.55  5020.8 1629.04
  5051.3 1630.97  5137.6 1631.44  5179.3 1631.88  5205.0 1629.66  5535.9 1641.20
#Mann=9,-1,0
  4209.6   0.035       0  4485.8    0.07       0  4489.8   0.035       0
  4624.4    0.07       0  4700.6   0.035       0  4859.4    0.07       0
  5051.3   0.035       0  5137.6    0.07       0  5179.3   0.035       0
Bank Sta=4485.8,4489.8
Exp/Cntr=0.3,0.1

Type RM Length L Ch R = 1,3632,315,315,315
BEGIN DESCRIPTION:
Mapping XS 4a8fae63
END DESCRIPTION:
XS GIS Cut Line= 3
      1586812.86      6892036.31      1587420.19      6892388.19
      1587896.97      6892631.12
#Sta/Elev= 30
  4298.1 1642.61  4373.5 1632.75  4389.2 1634.58  4395.0 1632.40  4410.8 1632.60
  4432.3 1628.98  4475.4 1627.08  4512.6 1627.04  4555.7 1630.33  4565.7 1629.01
  4571.5 1626.44  4608.7 1621.88  4675.3 1617.79  4689.1 1619.37  4694.9 1617.56
  4704.8 1618.74  4708.6 1617.20  4708.9 1616.70  4712.6 1617.20  4726.4 1619.67
  4732.1 1618.12  4747.9 1619.98  4753.7 1618.60  4763.0 1619.35  4913.6 1619.44
  4956.4 1619.48  5130.1 1624.69  5183.1 1627.04  5206.8 1630.29  5535.1 1639.46
#Mann=9,-1,0
  4298.1   0.035       0  4675.3    0.07       0  4708.6   0.035       0
  4712.6    0.07       0  4763.0   0.035       0  4913.6    0.07       0
  4956.4   0.035       0  5130.1    0.07       0  5206.8   0.035       0
Bank Sta=4708.6,4712.6
Exp/Cntr=0.3,0.1

Type RM Length L Ch R = 1,3317,395,395,395
BEGIN DESCRIPTION:
Mapping XS 3601bf8f
END DESCRIPTION:
XS GIS Cut Line= 3
      1586745.64      6892151.56      1587203.94      6892581.22
      1587724.75      6892875.47
#Sta/Elev= 30
  4366.0 1642.63  4398.4 1641.86  4419.8 1639.84  4426.7 1640.12  4455.0 1636.13
  4476.0 1635.12  4540.0 1628.14  4603.5 1623.94  4681.2 1620.02  4702.7 1617.45
  4723.7 1616.56  4735.9 1614.25  4736.1 1613.75  4739.9 1614.25  4773.5 1616.23
  4799.8 1616.66  4898.1 1617.96  5058.7 1618.16  5145.3 1623.74  5155.5 1623.35
  5161.2 1624.61  5177.1 1623.96  5182.9 1625.10  5198.8 1624.82  5204.5 1626.13
  5220.4 1626.19  5263.7 1628.53  5463.0 1633.95  5490.4 1635.40  5592.4 1637.21
#Mann=5,-1,0
  4366.0   0.035       0  4735.9   0.035       0  4739.9   0.035       0
  4799.8    0.07       0  4898.1   0.035       0
Bank Sta=4735.9,4739.9
Exp/Cntr=0.3,0.1

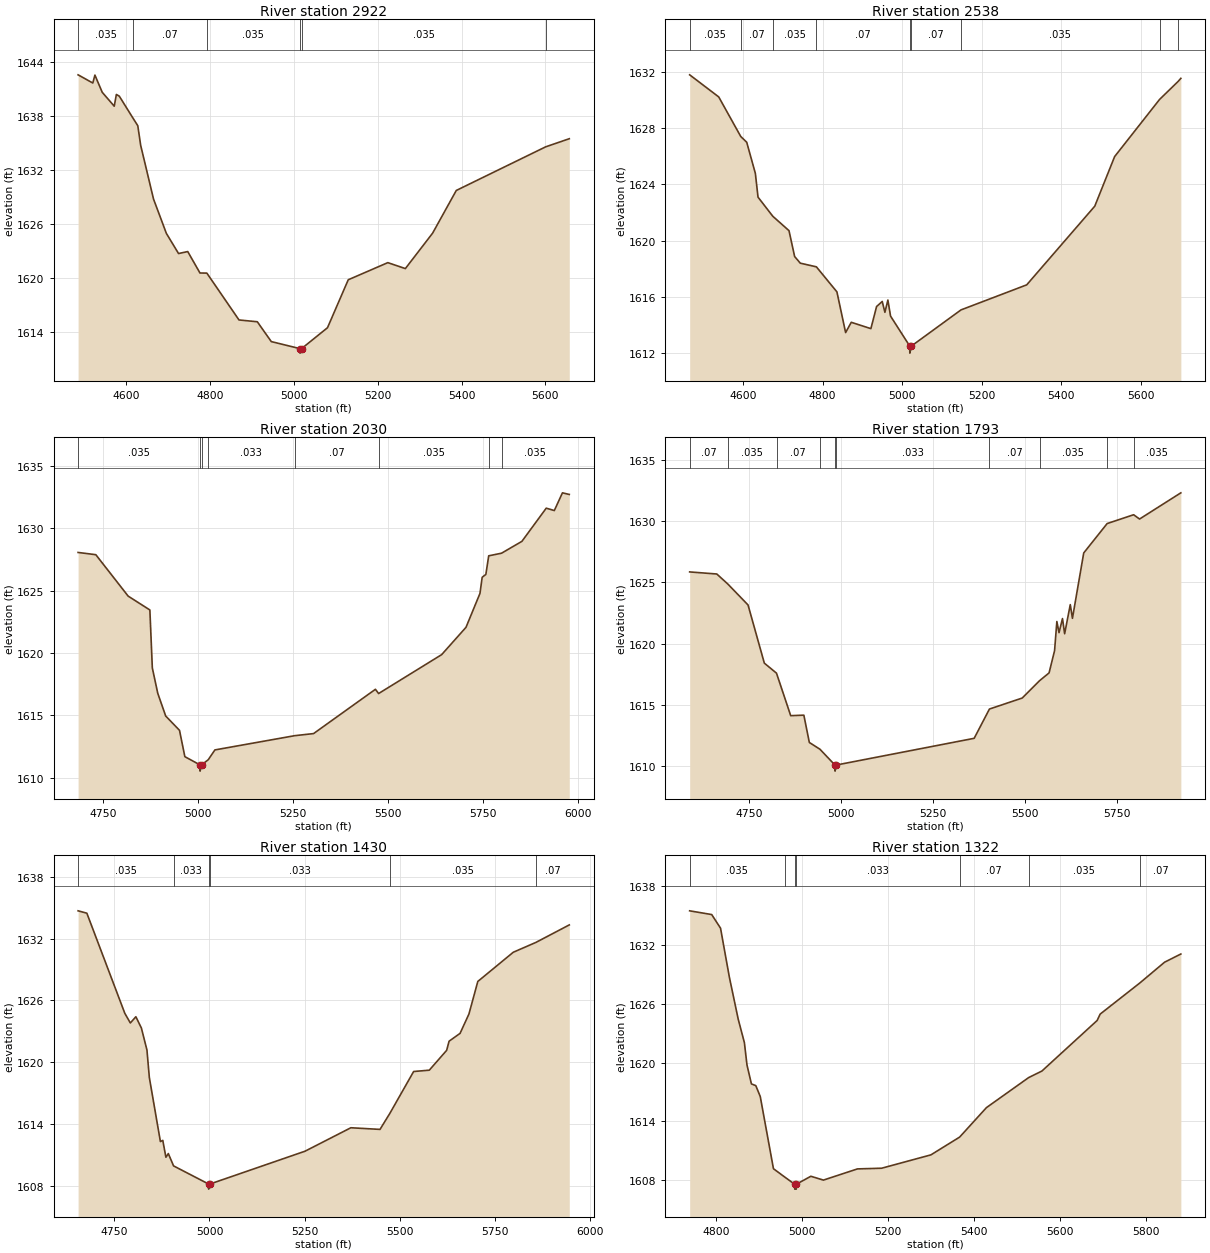
Type RM Length L Ch R = 1,2922,384,384,384
BEGIN DESCRIPTION:
Mapping XS 5ea5d9e5
END DESCRIPTION:
XS GIS Cut Line= 4
      1586732.59      6892151.54      1586815.92      6892570.80
      1586974.77      6892763.51      1587375.85      6893052.60
#Sta/Elev= 30
  4485.3 1642.59  4520.4 1641.68  4525.4 1642.56  4542.9 1640.65  4571.5 1639.11
  4576.6 1640.41  4583.6 1640.22  4616.3 1637.78  4627.7 1636.94  4634.6 1634.76
  4665.2 1628.81  4695.8 1625.00  4724.9 1622.76  4746.8 1622.98  4776.0 1620.60
  4792.4 1620.59  4869.1 1615.39  4912.8 1615.19  4946.1 1612.99  5014.4 1612.21
  5014.6 1611.71  5018.4 1612.21  5080.2 1614.53  5129.7 1619.85  5224.1 1621.75
  5265.9 1621.09  5330.9 1625.02  5387.4 1629.76  5600.6 1634.60  5656.9 1635.50
#Mann=6,-1,0
  4485.3   0.035       0  4616.3    0.07       0  4792.4   0.035       0
  5014.4   0.035       0  5018.4   0.035       0  5600.6    0.07       0
Bank Sta=5014.4,5018.4
Exp/Cntr=0.3,0.1

Type RM Length L Ch R = 1,2538,508,508,508
BEGIN DESCRIPTION:
Mapping XS f933e212
END DESCRIPTION:
XS GIS Cut Line= 3
      1586178.73      6892361.57      1586574.60      6892712.29
      1587130.09      6893146.27
#Sta/Elev= 30
  4466.3 1631.77  4539.3 1630.20  4594.6 1627.39  4609.6 1626.98  4631.3 1624.77
  4638.0 1623.08  4675.2 1621.72  4715.8 1620.70  4730.0 1618.86  4744.2 1618.39
  4784.6 1618.13  4836.2 1616.35  4858.0 1613.46  4872.2 1614.19  4921.5 1613.74
  4935.8 1615.31  4950.0 1615.67  4956.7 1614.90  4964.2 1615.77  4970.9 1614.63
  5019.1 1612.50  5019.3 1612.00  5023.1 1612.50  5147.8 1615.07  5312.9 1616.85
  5483.9 1622.44  5533.7 1625.96  5646.6 1630.02  5693.2 1631.30  5700.1 1631.52
#Mann=9,-1,0
  4466.3   0.035       0  4594.6    0.07       0  4675.2   0.035       0
  4784.6    0.07       0  5019.1    0.07       0  5023.1    0.07       0
  5147.8   0.035       0  5646.6    0.07       0  5693.2   0.035       0
Bank Sta=5019.1,5023.1
Exp/Cntr=0.3,0.1

Type RM Length L Ch R = 1,2030,237,237,237
BEGIN DESCRIPTION:
Mapping XS 467da328
END DESCRIPTION:
XS GIS Cut Line= 3
      1586005.16      6892542.17      1586216.96      6892795.63
      1587041.65      6893294.60
#Sta/Elev= 30
  4683.8 1628.05  4730.5 1627.87  4815.7 1624.55  4872.9 1623.44  4879.4 1618.79
  4893.7 1616.76  4914.6 1614.94  4951.0 1613.79  4965.1 1611.68  5005.0 1611.02
  5005.2 1610.52  5009.0 1611.02  5026.6 1611.43  5044.3 1612.22  5254.2 1613.36
  5304.3 1613.53  5467.2 1617.08  5475.6 1616.74  5641.8 1619.86  5705.9 1622.05
  5742.7 1624.77  5748.5 1626.06  5758.2 1626.29  5765.7 1627.78  5799.5 1627.99
  5853.2 1628.94  5917.3 1631.60  5938.6 1631.41  5960.0 1632.83  5978.0 1632.70
#Mann=8,-1,0
  4683.8   0.035       0  5005.0   0.035       0  5009.0   0.035       0
  5026.6   0.033       0  5254.2    0.07       0  5475.6   0.035       0
  5765.7    0.07       0  5799.5   0.035       0
Bank Sta=5005,5009
Exp/Cntr=0.3,0.1

Type RM Length L Ch R = 1,1793,363,363,363
BEGIN DESCRIPTION:
Mapping XS f54fc725
END DESCRIPTION:
XS GIS Cut Line= 3
      1585734.30      6892736.59      1586071.12      6892969.24
      1586855.82      6893462.28
#Sta/Elev= 30
  4588.8 1625.85  4662.6 1625.68  4692.3 1624.87  4747.6 1623.15  4791.9 1618.40
  4825.0 1617.58  4863.6 1614.11  4899.4 1614.15  4914.3 1611.92  4943.1 1611.37
  4983.9 1610.08  4984.2 1609.58  4987.9 1610.08  5362.7 1612.26  5404.2 1614.65
  5493.4 1615.55  5540.7 1616.97  5566.4 1617.60  5581.4 1619.42  5587.6 1621.80
  5593.5 1620.89  5602.9 1622.04  5608.8 1620.80  5624.1 1623.18  5630.0 1622.06
  5660.7 1627.40  5724.4 1629.80  5796.4 1630.52  5812.6 1630.17  5924.9 1632.31
#Mann=10,-1,0
  4588.8    0.07       0  4692.3   0.035       0  4825.0    0.07       0
  4943.1   0.033       0  4983.9   0.033       0  4987.9   0.033       0
  5404.2    0.07       0  5540.7   0.035       0  5724.4    0.07       0
  5796.4   0.035       0
Bank Sta=4983.9,4987.9
Exp/Cntr=0.3,0.1

Type RM Length L Ch R = 1,1430,108,108,108
BEGIN DESCRIPTION:
Mapping XS 70c1ddda
END DESCRIPTION:
XS GIS Cut Line= 3
      1585640.58      6893069.94      1585907.93      6893274.79
      1586779.50      6893660.23
#Sta/Elev= 30
  4655.0 1634.72  4678.0 1634.49  4777.7 1624.75  4792.2 1623.81  4806.7 1624.42
  4821.2 1623.32  4835.8 1621.18  4842.1 1618.50  4871.1 1612.28  4877.4 1612.39
  4885.6 1610.75  4891.9 1611.11  4905.7 1609.91  4997.5 1608.15  4997.8 1607.65
  5001.5 1608.15  5251.0 1611.34  5371.3 1613.62  5447.8 1613.46  5473.5 1615.01
  5536.1 1619.09  5577.2 1619.22  5622.8 1621.15  5629.2 1622.04  5658.0 1622.80
  5681.3 1624.68  5704.6 1627.85  5797.7 1630.69  5857.3 1631.65  5944.8 1633.35
#Mann=6,-1,0
  4655.0   0.035       0  4905.7   0.033       0  4997.5   0.033       0
  5001.5   0.033       0  5473.5   0.035       0  5857.3    0.07       0
Bank Sta=4997.5,5001.5
Exp/Cntr=0.3,0.1

Type RM Length L Ch R = 1,1322,478,478,478
BEGIN DESCRIPTION:
Mapping XS 39c056e2
END DESCRIPTION:
XS GIS Cut Line= 3
      1585585.03      6893295.63      1585835.01      6893351.18
      1586539.86      6893885.89
#Sta/Elev= 30
  4739.5 1635.46  4790.7 1635.08  4811.2 1633.69  4831.7 1628.70  4852.2 1624.43
  4866.6 1622.03  4872.6 1619.76  4882.9 1617.83  4893.1 1617.65  4903.4 1616.55
  4934.1 1609.19  4960.6 1608.33  4983.3 1607.61  4983.6 1607.11  4987.1 1607.11
  4987.3 1607.61  5021.0 1608.42  5050.1 1608.03  5129.2 1609.17  5185.4 1609.24
  5299.8 1610.60  5366.5 1612.41  5428.7 1615.41  5526.7 1618.47  5557.6 1619.14
  5685.9 1624.29  5692.9 1624.94  5785.0 1628.11  5842.6 1630.23  5880.3 1631.06
#Mann=7,-1,0
  4739.5   0.035       0  4960.6   0.033       0  4983.3   0.033       0
  4987.3   0.033       0  5366.5    0.07       0  5526.7   0.035       0
  5785.0    0.07       0
Bank Sta=4983.3,4987.3
Exp/Cntr=0.3,0.1

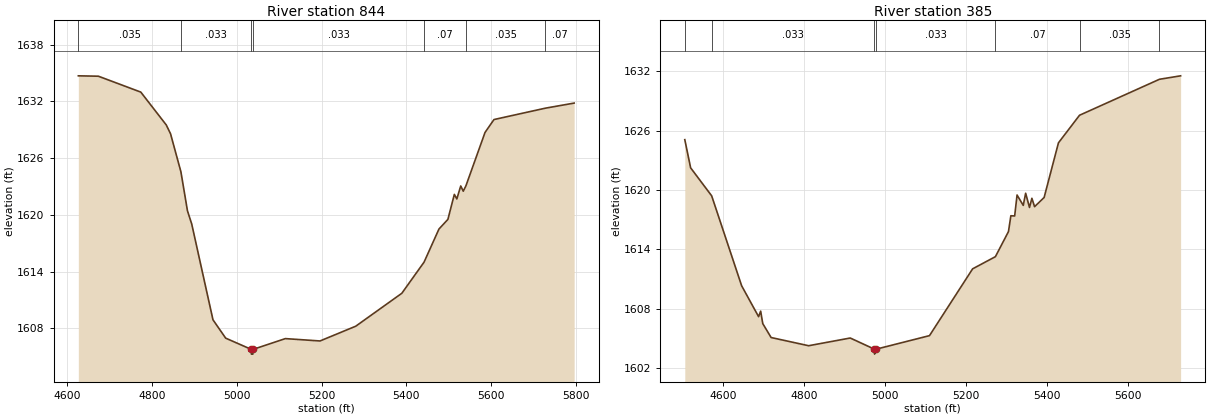
Type RM Length L Ch R = 1,844,459,459,459
BEGIN DESCRIPTION:
Mapping XS 7160e728
END DESCRIPTION:
XS GIS Cut Line= 3
      1585553.77      6893340.80      1585578.07      6893712.29
      1586248.21      6894146.32
#Sta/Elev= 30
  4625.8 1634.70  4673.1 1634.66  4773.3 1632.98  4833.4 1629.51  4843.5 1628.58
  4868.0 1624.56  4883.5 1620.43  4893.6 1619.03  4943.7 1608.92  4973.7 1606.98
  5034.2 1605.79  5034.4 1605.29  5037.9 1605.29  5038.2 1605.79  5114.6 1606.93
  5196.4 1606.68  5280.8 1608.24  5389.6 1611.72  5442.1 1615.01  5477.3 1618.51
  5498.4 1619.53  5513.6 1622.17  5519.5 1621.69  5528.7 1623.06  5534.7 1622.51
  5540.9 1623.07  5586.1 1628.72  5607.2 1630.08  5728.4 1631.28  5796.5 1631.82
#Mann=7,-1,0
  4625.8   0.035       0  4868.0   0.033       0  5034.2   0.033       0
  5038.2   0.033       0  5442.1    0.07       0  5540.9   0.035       0
  5728.4    0.07       0
Bank Sta=5034.2,5038.2
Exp/Cntr=0.3,0.1

Type RM Length L Ch R = 1,385,0,0,0
BEGIN DESCRIPTION:
MULBERRY CREEK TRIBUTARY 2_1 1.0
END DESCRIPTION:
XS GIS Cut Line= 3
      1585266.18      6893580.81      1585381.82      6894061.39
      1586000.87      6894447.90
#Sta/Elev= 30
  4505.7 1625.10  4520.1 1622.25  4572.0 1619.42  4646.0 1610.32  4687.9 1607.19
  4693.0 1607.75  4698.2 1606.49  4718.8 1605.08  4811.4 1604.25  4914.2 1605.03
  4973.9 1603.90  4974.2 1603.40  4977.9 1603.90  5109.8 1605.27  5216.3 1612.03
  5272.5 1613.26  5304.8 1615.80  5310.7 1617.40  5320.1 1617.38  5326.0 1619.50
  5341.3 1618.45  5347.2 1619.68  5356.7 1618.24  5362.6 1619.17  5369.2 1618.32
  5392.8 1619.25  5428.2 1624.78  5480.2 1627.57  5677.5 1631.21  5729.8 1631.56
#Mann=7,-1,0
  4505.7   0.035       0  4572.0   0.033       0  4973.9   0.033       0
  4977.9   0.033       0  5272.5    0.07       0  5480.2   0.035       0
  5677.5    0.07       0
Bank Sta=4973.9,4977.9
Exp/Cntr=0.3,0.1

Chan Stop Cuts=-1