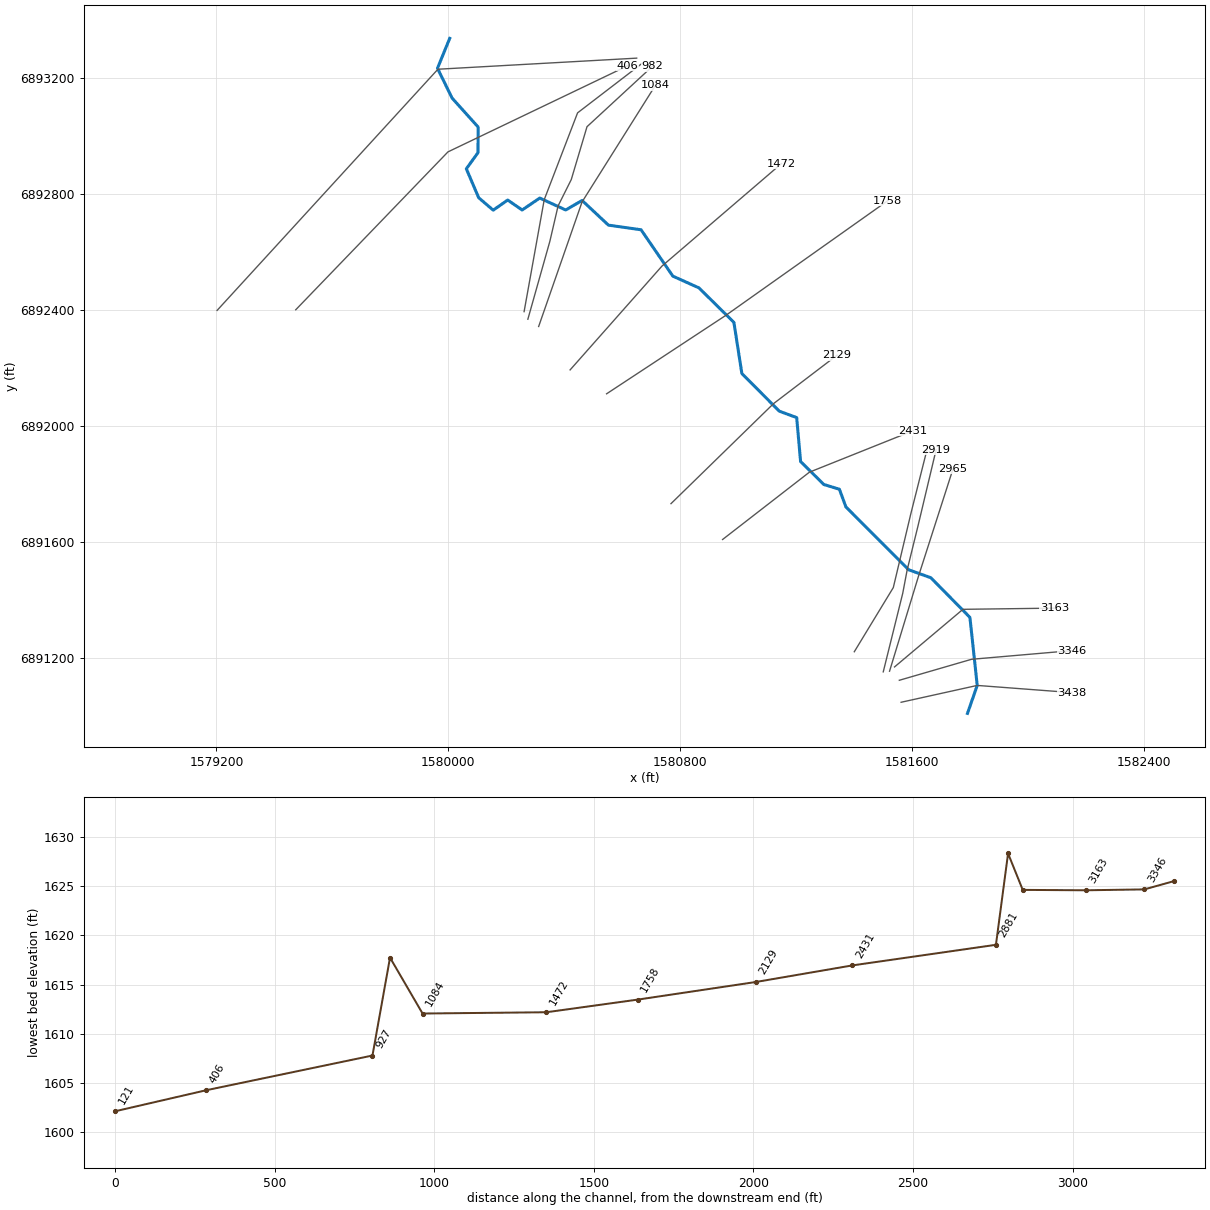
--- MULBERRY CREEK TRIBUTARY 3.prj (project) ---

Proj Title=MULBERRY CREEK TRIBUTARY 3 Base Level Engineering
Current Plan=p01
Default Exp/Contr=0.3,0.1
English Units
Geom File=g01
Flow File=f01
Plan File=p01
BEGIN DESCRIPTION:
MULBERRY CREEK TRIBUTARY 3
END DESCRIPTION:

--- MULBERRY CREEK TRIBUTARY 3.p01 (plan) ---

Plan Title=Multiple Run
Short Identifier=Multiple
Geom File=g01
Flow File=f01
Subcritical Flow
K Sum by GR= 0
Std Step Tol= 0.01
Critical Tol= 0.01
Num of Std Step Trials= 20
Max Error Tol= 0.3
Flow Tol Ratio= 0.001
Split Flow NTrial= 30
Split Flow Tol= 0.02
Split Flow Ratio= 0.02
Log Output Level= 0
Friction Slope Method= 1
Unsteady Friction Slope Method= 2
Unsteady Bridges Friction Slope Method= 1
Parabolic Critical Depth
Global Vel Dist=  1 , 1 , 1
Global Log Level= 0
CheckData=True
Encroach Param= -1, 0, 0, 0
BEGIN DESCRIPTION:
Multiple Run
END DESCRIPTION:

--- MULBERRY CREEK TRIBUTARY 3.f01 (steady flow) ---

Flow Title=Multiple
Number of Profiles=7
Profile Names=10-year,25-year,50-year,1pct_min,100-year,1pct_plu,500-year
River Rch & RM= MULBERRY CREEK T,Reach-1,3438
      79     102     120      71     141     282     196
River Rch & RM= MULBERRY CREEK T,Reach-1,406
     166     225     274     166     330     659     488
Boundary for River Rch & Prof#=MULBERRY CREEK T,Reach-1,1
Up Type=0
Dn Type=3
Dn Slope=0.005
Boundary for River Rch & Prof#=MULBERRY CREEK T,Reach-1,2
Up Type=0
Dn Type=3
Dn Slope=0.005
Boundary for River Rch & Prof#=MULBERRY CREEK T,Reach-1,3
Up Type=0
Dn Type=3
Dn Slope=0.005
Boundary for River Rch & Prof#=MULBERRY CREEK T,Reach-1,4
Up Type=0
Dn Type=3
Dn Slope=0.005
Boundary for River Rch & Prof#=MULBERRY CREEK T,Reach-1,5
Up Type=0
Dn Type=3
Dn Slope=0.005
Boundary for River Rch & Prof#=MULBERRY CREEK T,Reach-1,6
Up Type=0
Dn Type=3
Dn Slope=0.005
Boundary for River Rch & Prof#=MULBERRY CREEK T,Reach-1,7
Up Type=0
Dn Type=3
Dn Slope=0.005

--- MULBERRY CREEK TRIBUTARY 3.g01 (geometry) ---

Geom Title=Existing Conditions

River Reach=MULBERRY CREEK T,Reach-1
Reach XY= 30
      1581791.25      6891009.25      1581824.80      6891105.68
      1581799.57      6891340.47      1581664.68      6891477.22
      1581588.33      6891504.65      1581371.73      6891721.52
      1581349.38      6891782.38      1581295.56      6891798.88
      1581215.47      6891878.18      1581201.92      6892029.69
      1581142.05      6892051.74      1581012.82      6892181.81
      1580985.39      6892358.16      1580864.68      6892477.22
      1580774.77      6892517.58      1580665.10      6892677.61
      1580552.58      6892693.55      1580461.66      6892778.69
      1580405.09      6892745.84      1580315.64      6892787.03
      1580254.91      6892745.80      1580205.00      6892780.12
      1580155.00      6892745.21      1580105.00      6892788.00
      1580062.32      6892887.96      1580102.65      6892943.89
      1580103.03      6893032.10      1580013.14      6893131.96
      1579962.85      6893234.72      1580005.00      6893338.00

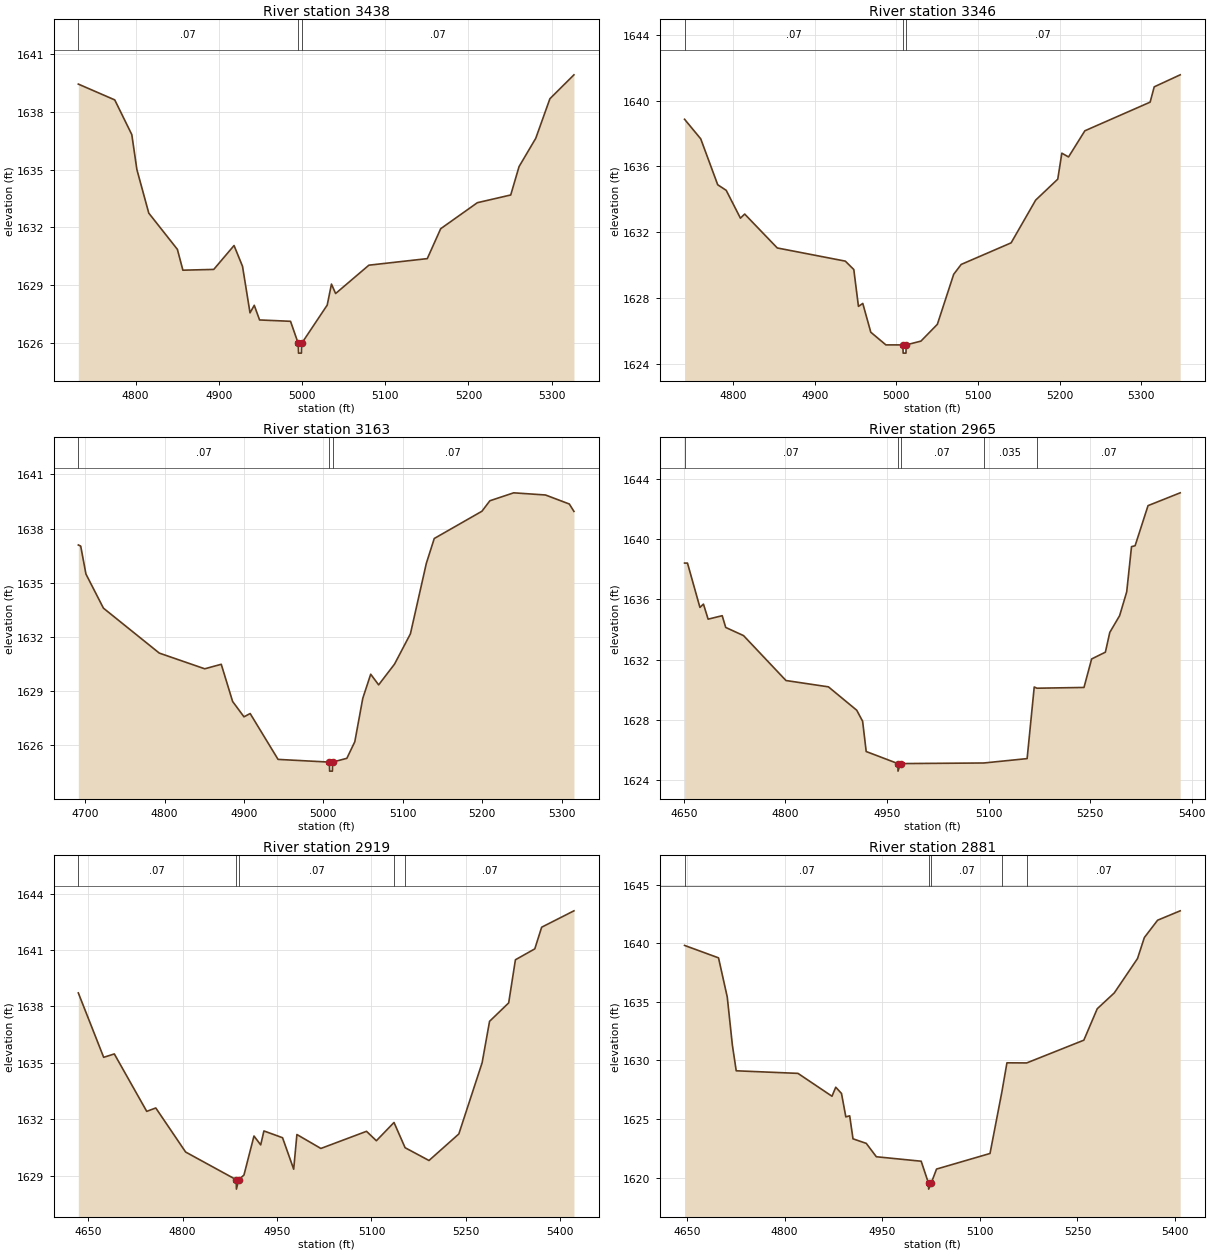
Type RM Length L Ch R = 1,3438,92,92,92
BEGIN DESCRIPTION:
MULBERRY CREEK TRIBUTARY 3 7.0
END DESCRIPTION:
XS GIS Cut Line= 3
      1581562.25      6891047.57      1581824.80      6891105.68
      1582150.77      6891080.97
#Sta/Elev= 30
  4731.1 1639.43  4774.9 1638.61  4795.4 1636.81  4801.5 1635.00  4815.8 1632.74
  4850.2 1630.86  4856.8 1629.78  4893.9 1629.82  4918.3 1631.06  4928.5 1629.98
  4937.5 1627.57  4942.6 1627.96  4949.0 1627.20  4986.2 1627.13  4995.5 1625.98
  4995.8 1625.48  4999.3 1625.48  4999.5 1625.98  5030.3 1627.97  5035.4 1629.06
  5040.4 1628.57  5080.4 1630.04  5150.6 1630.38  5166.7 1631.93  5210.8 1633.28
  5250.9 1633.68  5260.9 1635.15  5281.0 1636.62  5298.0 1638.67  5326.9 1639.91
#Mann=3,-1,0
  4731.1    0.07       0  4995.5    0.07       0  4999.5    0.07       0
Bank Sta=4995.5,4999.5
Exp/Cntr=0.3,0.1

Type RM Length L Ch R = 1,3346,183,183,183
BEGIN DESCRIPTION:
Mapping XS 7cff298e
END DESCRIPTION:
XS GIS Cut Line= 3
      1581556.02      6891123.44      1581805.02      6891195.79
      1582151.22      6891225.78
#Sta/Elev= 30
  4740.7 1638.86  4760.5 1637.67  4781.3 1634.88  4791.7 1634.54  4809.1 1632.85
  4814.3 1633.10  4854.2 1631.04  4937.5 1630.24  4947.9 1629.73  4953.6 1627.49
  4958.9 1627.67  4968.7 1625.92  4987.2 1625.15  5008.0 1625.15  5008.3 1624.65
  5011.8 1624.65  5012.0 1625.15  5030.1 1625.38  5050.2 1626.40  5070.2 1629.44
  5079.4 1630.04  5140.5 1631.35  5170.6 1633.95  5197.6 1635.22  5202.6 1636.80
  5210.8 1636.57  5230.8 1638.16  5310.7 1639.90  5315.7 1640.83  5347.5 1641.56
#Mann=3,-1,0
  4740.7    0.07       0  5008.0    0.07       0  5012.0    0.07       0
Bank Sta=5008,5012
Exp/Cntr=0.3,0.1

Type RM Length L Ch R = 1,3163,198,198,198
BEGIN DESCRIPTION:
Mapping XS 45b632e6
END DESCRIPTION:
XS GIS Cut Line= 3
      1581539.54      6891169.46      1581775.49      6891368.21
      1582090.77      6891372.31
#Sta/Elev= 30
  4691.5 1637.09  4694.5 1637.03  4701.1 1635.48  4723.1 1633.59  4793.4 1631.10
  4850.6 1630.23  4871.4 1630.48  4885.7 1628.42  4900.0 1627.57  4907.8 1627.75
  4942.9 1625.21  5007.5 1625.06  5007.8 1624.56  5011.3 1624.56  5011.5 1625.06
  5029.5 1625.27  5039.5 1626.19  5049.5 1628.59  5059.5 1629.93  5069.5 1629.34
  5089.5 1630.49  5109.5 1632.17  5129.5 1636.07  5139.5 1637.45  5199.5 1638.96
  5209.5 1639.54  5239.5 1639.98  5279.5 1639.86  5309.5 1639.36  5315.3 1638.95
#Mann=3,-1,0
  4691.5    0.07       0  5007.5    0.07       0  5011.5    0.07       0
Bank Sta=5007.5,5011.5
Exp/Cntr=0.3,0.1

Type RM Length L Ch R = 1,2965,46,46,46
BEGIN DESCRIPTION:
Mapping XS 1bf95012
END DESCRIPTION:
XS GIS Cut Line= 3
      1581522.33      6891154.71      1581622.14      6891482.35
      1581741.43      6891853.23
#Sta/Elev= 30
  4651.0 1638.40  4655.3 1638.40  4673.7 1635.46  4678.9 1635.68  4685.8 1634.68
  4706.6 1634.91  4711.8 1634.13  4738.1 1633.59  4800.8 1630.61  4863.5 1630.19
  4905.3 1628.64  4914.0 1627.91  4919.3 1625.90  4966.1 1625.10  4966.3 1624.60
  4970.1 1625.10  5093.1 1625.14  5157.0 1625.43  5167.5 1630.18  5171.5 1630.10
  5241.0 1630.15  5252.3 1632.04  5272.6 1632.49  5279.1 1633.80  5293.6 1634.91
  5304.1 1636.49  5311.2 1639.49  5316.5 1639.55  5335.6 1642.21  5383.1 1643.06
#Mann=5,-1,0
  4651.0    0.07       0  4966.1    0.07       0  4970.1    0.07       0
  5093.1   0.035       0  5171.5    0.07       0
Bank Sta=4966.1,4970.1
Exp/Cntr=0.3,0.1

Type RM Length L Ch R = 1,2919,38,38,38
BEGIN DESCRIPTION:
Mapping XS 9226a74a
END DESCRIPTION:
XS GIS Cut Line= 5
      1581500.62      6891152.51      1581567.89      6891423.76
      1581583.08      6891504.05      1581619.97      6891653.79
      1581682.90      6891918.51
#Sta/Elev= 30
  4634.2 1638.72  4674.5 1635.30  4691.4 1635.48  4742.9 1632.43  4757.3 1632.61
  4804.7 1630.27  4885.1 1628.80  4885.4 1628.30  4889.1 1628.80  4897.4 1629.05
  4913.3 1631.12  4924.0 1630.65  4929.1 1631.39  4958.7 1631.03  4976.4 1629.36
  4981.5 1631.20  5019.6 1630.46  5092.1 1631.37  5107.8 1630.87  5135.8 1631.84
  5153.4 1630.50  5191.4 1629.82  5238.8 1631.23  5275.8 1635.01  5287.6 1637.21
  5318.0 1638.19  5328.7 1640.48  5359.5 1641.06  5370.4 1642.21  5421.7 1643.08
#Mann=5,-1,0
  4634.2    0.07       0  4885.1    0.07       0  4889.1    0.07       0
  5135.8   0.035       0  5153.4    0.07       0
Bank Sta=4885.1,4889.1
Exp/Cntr=0.3,0.1

Type RM Length L Ch R = 1,2881,450,450,450
BEGIN DESCRIPTION:
Mapping XS 0eb5592f
END DESCRIPTION:
XS GIS Cut Line= 4
      1581400.77      6891221.90      1581535.34      6891443.29
      1581596.10      6891699.37      1581654.71      6891931.62
#Sta/Elev= 30
  4646.2 1639.81  4698.4 1638.75  4711.8 1635.42  4719.7 1631.31  4725.6 1629.12
  4820.5 1628.90  4872.8 1626.95  4878.6 1627.72  4887.4 1627.19  4894.1 1625.19
  4900.0 1625.28  4905.1 1623.32  4925.5 1622.93  4941.0 1621.79  5009.9 1621.41
  5021.2 1619.53  5021.4 1619.03  5025.2 1619.53  5033.5 1620.74  5115.7 1622.07
  5134.1 1627.37  5141.7 1629.80  5172.1 1629.79  5259.9 1631.73  5280.5 1634.41
  5306.7 1635.76  5342.4 1638.69  5352.9 1640.48  5373.3 1641.96  5408.0 1642.76
#Mann=5,-1,0
  4646.2    0.07       0  5021.2    0.07       0  5025.2    0.07       0
  5134.1   0.035       0  5172.1    0.07       0
Bank Sta=5021.2,5025.2
Exp/Cntr=0.3,0.1

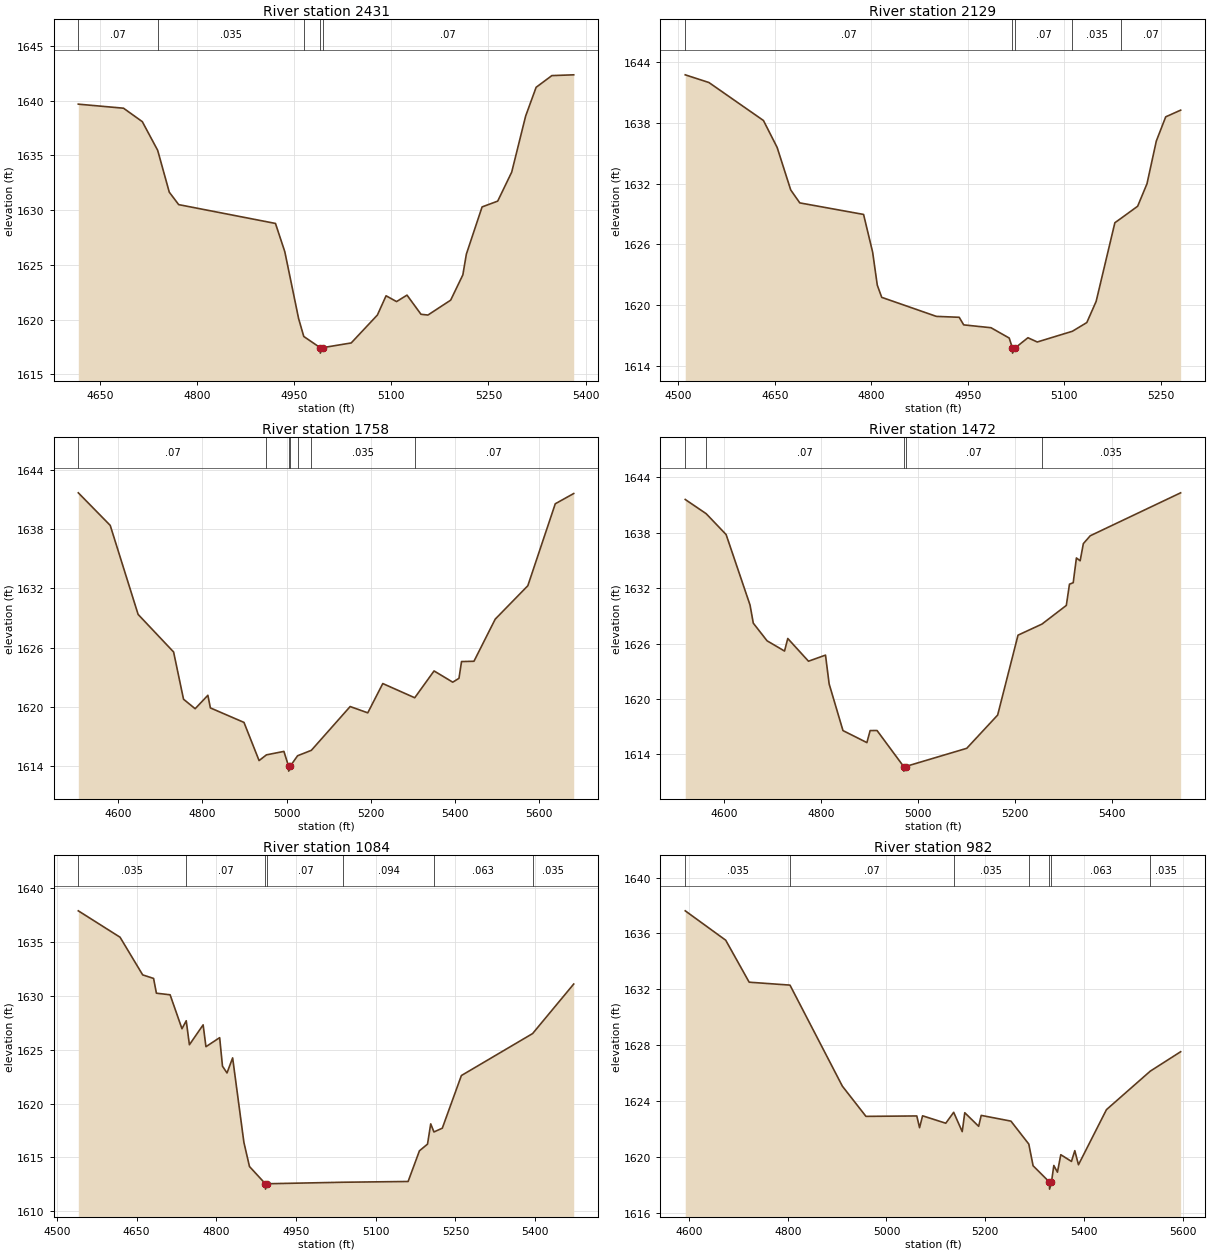
Type RM Length L Ch R = 1,2431,302,302,302
BEGIN DESCRIPTION:
Mapping XS 5739ab5e
END DESCRIPTION:
XS GIS Cut Line= 3
      1580946.33      6891609.07      1581245.84      6891841.29
      1581603.87      6891984.51
#Sta/Elev= 30
  4617.0 1639.69  4686.8 1639.32  4715.8 1638.09  4739.5 1635.47  4757.4 1631.65
  4771.9 1630.51  4921.3 1628.79  4935.7 1626.21  4957.0 1620.10  4965.0 1618.46
  4990.3 1617.44  4990.5 1616.94  4994.3 1617.44  5038.2 1617.87  5078.6 1620.42
  5092.0 1622.18  5108.2 1621.65  5124.3 1622.24  5145.9 1620.49  5156.6 1620.42
  5191.7 1621.78  5210.5 1624.09  5215.9 1625.98  5240.2 1630.30  5264.3 1630.83
  5285.9 1633.48  5307.4 1638.60  5323.6 1641.23  5347.9 1642.30  5381.6 1642.37
#Mann=5,-1,0
  4617.0    0.07       0  4739.5   0.035       0  4965.0    0.07       0
  4990.3    0.07       0  4994.3    0.07       0
Bank Sta=4990.3,4994.3
Exp/Cntr=0.3,0.1

Type RM Length L Ch R = 1,2129,371,371,371
BEGIN DESCRIPTION:
Mapping XS c7c057a9
END DESCRIPTION:
XS GIS Cut Line= 3
      1580768.38      6891732.76      1581122.14      6892077.84
      1581341.32      6892244.93
#Sta/Elev= 30
  4511.0 1642.75  4547.8 1641.99  4632.5 1638.24  4653.8 1635.58  4674.9 1631.38
  4689.0 1630.10  4788.1 1628.96  4802.2 1625.23  4809.4 1621.98  4816.3 1620.77
  4901.2 1618.89  4936.7 1618.80  4943.7 1618.05  4986.1 1617.77  5014.4 1616.75
  5019.4 1615.76  5019.6 1615.26  5023.4 1615.76  5043.5 1616.78  5058.0 1616.36
  5112.6 1617.42  5135.0 1618.28  5149.5 1620.37  5178.6 1628.14  5187.4 1628.54
  5214.0 1629.77  5228.5 1631.99  5243.0 1636.21  5257.6 1638.60  5280.8 1639.26
#Mann=5,-1,0
  4511.0    0.07       0  5019.4    0.07       0  5023.4    0.07       0
  5112.6   0.035       0  5187.4    0.07       0
Bank Sta=5019.4,5023.4
Exp/Cntr=0.3,0.1

Type RM Length L Ch R = 1,1758,286,286,286
BEGIN DESCRIPTION:
Mapping XS de18a551
END DESCRIPTION:
XS GIS Cut Line= 3
      1580546.16      6892111.67      1580958.51      6892382.96
      1581516.23      6892777.92
#Sta/Elev= 30
  4505.0 1641.69  4580.8 1638.39  4647.1 1629.36  4731.4 1625.55  4755.0 1620.76
  4782.6 1619.80  4812.8 1621.16  4818.8 1619.88  4898.6 1618.41  4934.5 1614.54
  4952.0 1615.12  4993.5 1615.47  5004.5 1613.97  5004.8 1613.47  5008.5 1613.97
  5026.0 1615.03  5058.7 1615.58  5150.9 1620.02  5192.7 1619.38  5228.4 1622.35
  5304.3 1620.91  5350.2 1623.63  5394.6 1622.49  5409.4 1622.88  5415.5 1624.58
  5445.0 1624.61  5495.5 1628.88  5573.0 1632.27  5638.2 1640.58  5682.0 1641.62
#Mann=7,-1,0
  4505.0    0.07       0  4952.0   0.035       0  5004.5   0.035       0
  5008.5   0.035       0  5026.0    0.07       0  5058.7   0.035       0
  5304.3    0.07       0
Bank Sta=5004.5,5008.5
Exp/Cntr=0.3,0.1

Type RM Length L Ch R = 1,1472,388,388,388
BEGIN DESCRIPTION:
Mapping XS 3da7c312
END DESCRIPTION:
XS GIS Cut Line= 3
      1580420.34      6892194.18      1580737.16      6892552.23
      1581149.51      6892905.99
#Sta/Elev= 30
  4519.8 1641.60  4563.0 1640.06  4604.1 1637.80  4653.4 1630.17  4660.1 1628.21
  4688.5 1626.30  4724.5 1625.19  4731.2 1626.55  4773.9 1624.09  4809.0 1624.75
  4816.5 1621.63  4845.0 1616.58  4894.3 1615.28  4901.0 1616.58  4915.2 1616.59
  4970.1 1612.69  4970.4 1612.19  4974.1 1612.69  5100.2 1614.66  5163.9 1618.26
  5205.9 1626.91  5255.3 1628.11  5305.5 1630.13  5312.0 1632.43  5319.7 1632.59
  5326.3 1635.27  5334.0 1634.96  5340.6 1636.82  5354.8 1637.67  5541.2 1642.32
#Mann=5,-1,0
  4519.8   0.035       0  4563.0    0.07       0  4970.1    0.07       0
  4974.1    0.07       0  5255.3   0.035       0
Bank Sta=4970.1,4974.1
Exp/Cntr=0.3,0.1

Type RM Length L Ch R = 1,1084,102,102,102
BEGIN DESCRIPTION:
Mapping XS f9692fb7
END DESCRIPTION:
XS GIS Cut Line= 3
      1580311.81      6892343.89      1580461.55      6892773.59
      1580715.46      6893177.23
#Sta/Elev= 30
  4540.5 1637.91  4619.0 1635.46  4661.6 1631.96  4682.1 1631.63  4687.4 1630.26
  4713.2 1630.11  4735.5 1626.96  4743.5 1627.70  4749.5 1625.47  4775.3 1627.32
  4780.6 1625.29  4806.4 1626.13  4811.7 1623.48  4820.2 1622.85  4830.8 1624.25
  4852.0 1616.40  4862.5 1614.16  4892.3 1612.56  4892.6 1612.06  4896.3 1612.56
  5039.0 1612.70  5160.9 1612.77  5182.2 1615.62  5197.4 1616.24  5203.4 1618.12
  5209.5 1617.37  5225.2 1617.72  5261.1 1622.61  5395.1 1626.51  5472.4 1631.11
#Mann=7,-1,0
  4540.5   0.035       0  4743.5    0.07       0  4892.3    0.07       0
  4896.3    0.07       0  5039.0   0.094       0  5209.5   0.063       0
  5395.1   0.035       0
Bank Sta=4892.3,4896.3
Exp/Cntr=0.3,0.1

Type RM Length L Ch R = 1,982,55,55,55
BEGIN DESCRIPTION:
Mapping XS 9e2ed99c
END DESCRIPTION:
XS GIS Cut Line= 6
      1580274.63      6892369.05      1580350.59      6892638.17
      1580378.80      6892759.70      1580424.37      6892850.84
      1580478.62      6893033.13      1580704.29      6893241.44
#Sta/Elev= 30
  4592.3 1637.62  4674.3 1635.52  4721.8 1632.52  4804.5 1632.31  4910.6 1625.09
  4958.4 1622.93  5061.4 1622.96  5067.0 1622.12  5073.1 1622.97  5120.1 1622.44
  5136.1 1623.22  5153.4 1621.84  5158.6 1623.19  5186.7 1622.22  5191.9 1623.00
  5252.1 1622.59  5288.3 1620.95  5297.0 1619.40  5330.2 1618.23  5330.4 1617.73
  5334.2 1618.23  5339.0 1619.42  5346.3 1618.94  5353.1 1620.19  5374.7 1619.71
  5381.5 1620.48  5388.9 1619.47  5445.6 1623.41  5534.3 1626.16  5595.9 1627.55
#Mann=7,-1,0
  4592.3   0.035       0  4804.5    0.07       0  5136.1   0.035       0
  5288.3   0.063       0  5330.2    0.07       0  5334.2   0.063       0
  5534.3   0.035       0
Bank Sta=5330.2,5334.2
Exp/Cntr=0.3,0.1

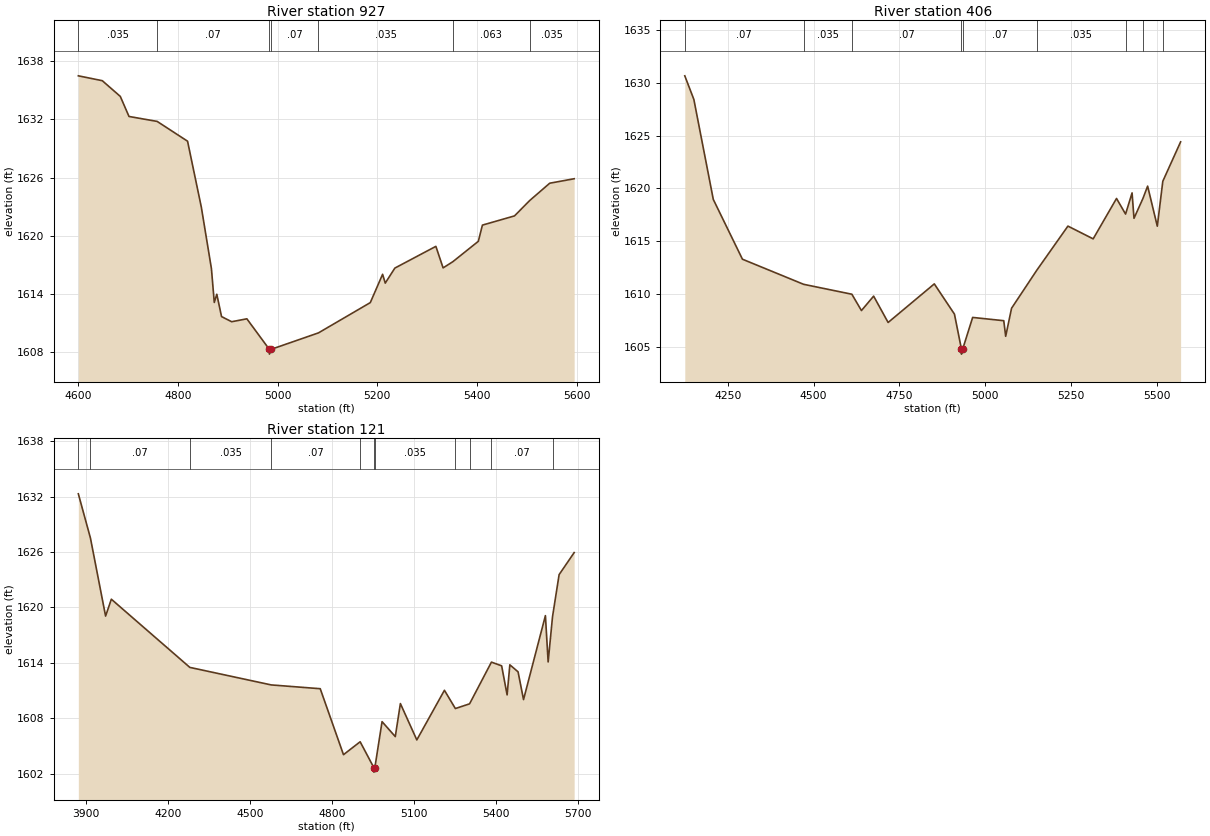
Type RM Length L Ch R = 1,927,521,521,521
BEGIN DESCRIPTION:
Mapping XS 6c4db24e
END DESCRIPTION:
XS GIS Cut Line= 4
      1580261.61      6892395.11      1580331.06      6892781.40
      1580446.07      6893080.88      1580669.60      6893252.32
#Sta/Elev= 30
  4600.3 1636.49  4648.3 1635.99  4684.5 1634.37  4702.0 1632.30  4758.5 1631.79
  4819.5 1629.75  4847.1 1622.96  4867.4 1616.61  4873.1 1613.13  4878.2 1613.97
  4887.7 1611.67  4908.0 1611.14  4938.5 1611.44  4983.5 1608.30  4983.8 1607.80
  4987.5 1608.30  5082.2 1609.99  5186.2 1613.11  5210.9 1616.03  5216.2 1615.12
  5235.5 1616.67  5317.8 1618.91  5332.3 1616.69  5351.9 1617.33  5403.0 1619.43
  5411.2 1621.10  5475.6 1622.05  5506.0 1623.63  5546.3 1625.42  5595.3 1625.88
#Mann=7,-1,0
  4600.3   0.035       0  4758.5    0.07       0  4983.5    0.07       0
  4987.5    0.07       0  5082.2   0.035       0  5351.9   0.063       0
  5506.0   0.035       0
Bank Sta=4983.5,4987.5
Exp/Cntr=0.3,0.1

Type RM Length L Ch R = 1,406,285,285,285
BEGIN DESCRIPTION:
Mapping XS 7dafc1fb
END DESCRIPTION:
XS GIS Cut Line= 3
      1579473.88      6892401.66      1579999.02      6892946.33
      1580619.06      6893243.34
#Sta/Elev= 30
  4125.0 1630.67  4151.4 1628.43  4208.0 1618.95  4292.9 1613.28  4471.1 1610.90
  4611.6 1609.96  4639.5 1608.41  4675.0 1609.78  4717.2 1607.28  4851.7 1610.94
  4910.4 1608.07  4930.6 1604.78  4930.8 1604.28  4934.6 1604.78  4963.4 1607.76
  5054.0 1607.45  5059.6 1605.97  5076.7 1608.63  5150.1 1612.23  5240.9 1616.42
  5314.4 1615.21  5382.4 1619.04  5408.8 1617.56  5427.7 1619.57  5433.3 1617.16
  5459.2 1619.03  5473.0 1620.21  5501.2 1616.41  5517.2 1620.67  5569.1 1624.41
#Mann=9,-1,0
  4125.0    0.07       0  4471.1   0.035       0  4611.6    0.07       0
  4930.6    0.07       0  4934.6    0.07       0  5150.1   0.035       0
  5408.8   0.063       0  5459.2    0.07       0  5517.2   0.035       0
Bank Sta=4930.6,4934.6
Exp/Cntr=0.3,0.1

Type RM Length L Ch R = 1,121,0,0,0
BEGIN DESCRIPTION:
MULBERRY CREEK TRIBUTARY 3 1.0
END DESCRIPTION:
XS GIS Cut Line= 3
      1579202.57      6892399.44      1579964.28      6893231.41
      1580650.01      6893269.68
#Sta/Elev= 30
  3872.0 1632.31  3916.3 1627.52  3971.8 1619.06  3992.8 1620.89  4280.1 1613.50
  4578.1 1611.60  4757.4 1611.19  4842.5 1604.04  4903.5 1605.44  4953.4 1602.65
  4953.6 1602.15  4957.4 1602.65  4983.7 1607.62  5032.1 1606.00  5050.8 1609.58
  5110.9 1605.64  5212.0 1611.02  5252.0 1609.04  5304.0 1609.55  5384.0 1614.07
  5421.4 1613.67  5441.4 1610.52  5451.4 1613.78  5481.5 1613.02  5501.5 1610.01
  5581.6 1619.11  5591.6 1614.09  5607.6 1618.99  5631.7 1623.55  5686.8 1625.94
#Mann=11,-1,0
  3872.0   0.035       0  3916.3    0.07       0  4280.1   0.035       0
  4578.1    0.07       0  4903.5   0.035       0  4953.4   0.035       0
  4957.4   0.035       0  5252.0    0.07       0  5304.0   0.035       0
  5384.0    0.07       0  5607.6   0.035       0
Bank Sta=4953.4,4957.4
Exp/Cntr=0.3,0.1

Chan Stop Cuts=-1