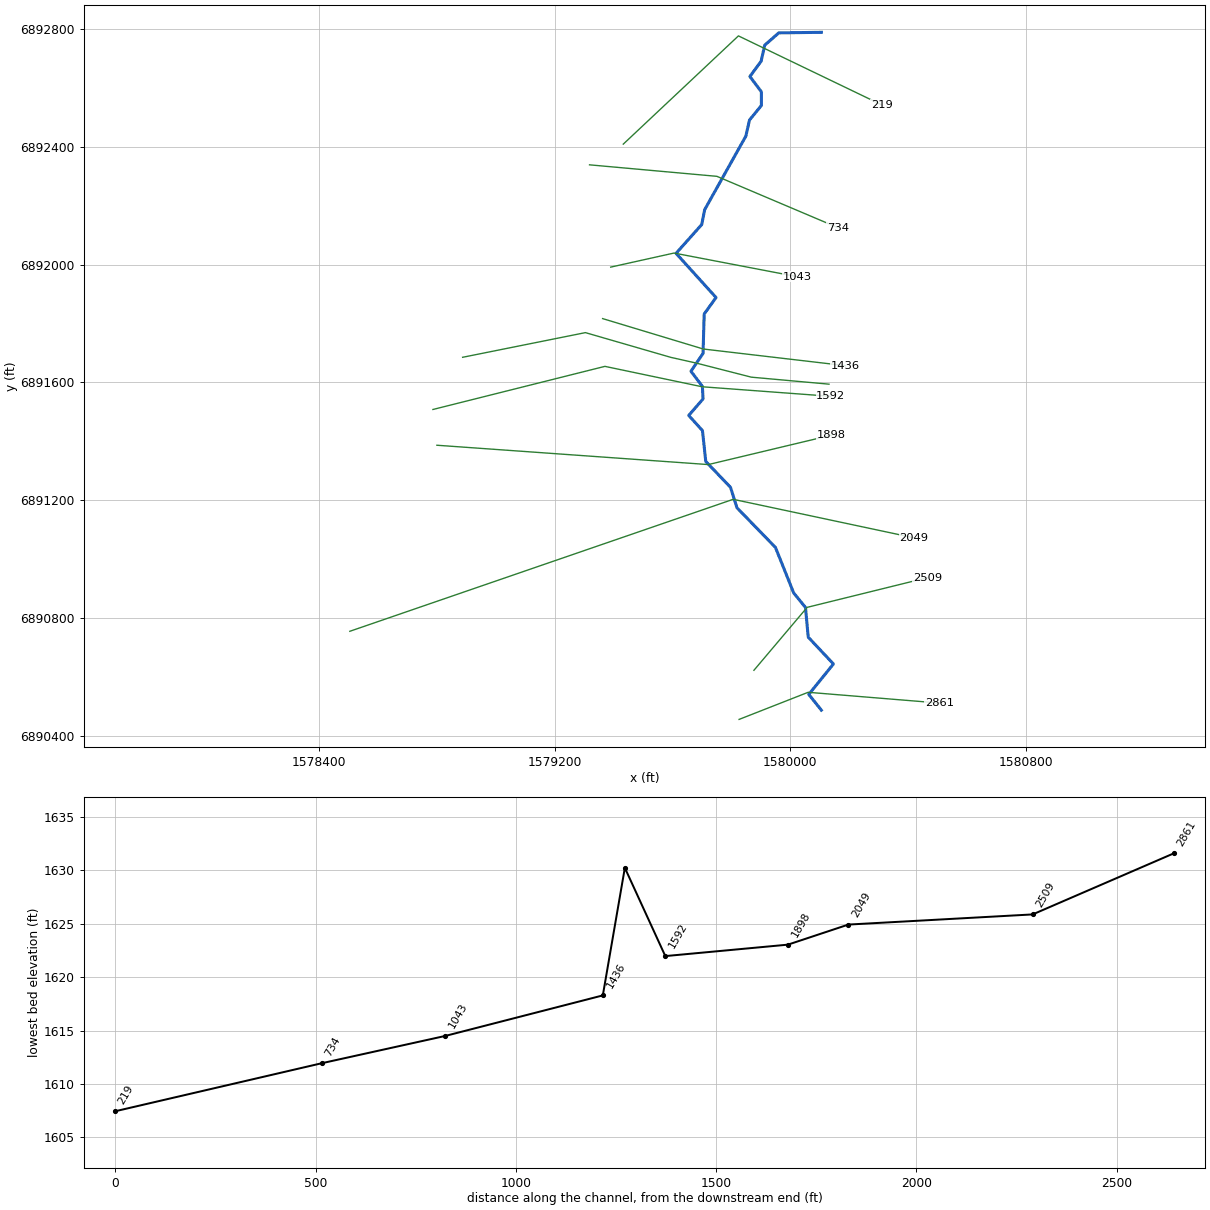
--- MULBERRY CREEK TRIBUTARY 3_1.prj (project) ---

Proj Title=MULBERRY CREEK TRIBUTARY 3_1 Base Level Engineering
Current Plan=p01
Default Exp/Contr=0.3,0.1
English Units
Geom File=g01
Flow File=f01
Plan File=p01
BEGIN DESCRIPTION:
MULBERRY CREEK TRIBUTARY 3_1
END DESCRIPTION:

--- MULBERRY CREEK TRIBUTARY 3_1.p01 (plan) ---

Plan Title=Multiple Run
Short Identifier=Multiple
Geom File=g01
Flow File=f01
Subcritical Flow
K Sum by GR= 0
Std Step Tol= 0.01
Critical Tol= 0.01
Num of Std Step Trials= 20
Max Error Tol= 0.3
Flow Tol Ratio= 0.001
Split Flow NTrial= 30
Split Flow Tol= 0.02
Split Flow Ratio= 0.02
Log Output Level= 0
Friction Slope Method= 1
Unsteady Friction Slope Method= 2
Unsteady Bridges Friction Slope Method= 1
Parabolic Critical Depth
Global Vel Dist=  1 , 1 , 1
Global Log Level= 0
CheckData=True
Encroach Param= -1, 0, 0, 0
BEGIN DESCRIPTION:
Multiple Run
END DESCRIPTION:

--- MULBERRY CREEK TRIBUTARY 3_1.f01 (steady flow) ---

Flow Title=Multiple
Number of Profiles=7
Profile Names=10-year,25-year,50-year,1pct_min,100-year,1pct_plu,500-year
River Rch & RM= MULBERRY CREEK T,Reach-1,2861
      69      88     103      60     120     239     164
River Rch & RM= MULBERRY CREEK T,Reach-1,1592
      97     127     150      89     177     353     250
River Rch & RM= MULBERRY CREEK T,Reach-1,1491
     112     148     177     105     210     419     300
Boundary for River Rch & Prof#=MULBERRY CREEK T,Reach-1,1
Up Type=0
Dn Type=3
Dn Slope=0.005
Boundary for River Rch & Prof#=MULBERRY CREEK T,Reach-1,2
Up Type=0
Dn Type=3
Dn Slope=0.005
Boundary for River Rch & Prof#=MULBERRY CREEK T,Reach-1,3
Up Type=0
Dn Type=3
Dn Slope=0.005
Boundary for River Rch & Prof#=MULBERRY CREEK T,Reach-1,4
Up Type=0
Dn Type=3
Dn Slope=0.005
Boundary for River Rch & Prof#=MULBERRY CREEK T,Reach-1,5
Up Type=0
Dn Type=3
Dn Slope=0.005
Boundary for River Rch & Prof#=MULBERRY CREEK T,Reach-1,6
Up Type=0
Dn Type=3
Dn Slope=0.005
Boundary for River Rch & Prof#=MULBERRY CREEK T,Reach-1,7
Up Type=0
Dn Type=3
Dn Slope=0.005

--- MULBERRY CREEK TRIBUTARY 3_1.g01 (geometry) ---

Geom Title=Existing Conditions

River Reach=MULBERRY CREEK T,Reach-1
Reach XY= 30
      1580105.00      6890488.00      1580062.29      6890541.33
      1580146.02      6890644.66      1580060.55      6890735.57
      1580051.17      6890836.41      1580011.12      6890885.82
      1579949.17      6891040.30      1579818.63      6891174.79
      1579796.82      6891244.04      1579712.86      6891331.83
      1579701.61      6891436.59      1579655.00      6891488.00
      1579703.67      6891544.06      1579701.40      6891586.42
      1579662.57      6891637.99      1579703.61      6891698.44
      1579707.48      6891832.14      1579747.68      6891888.10
      1579612.08      6892038.00      1579699.14      6892135.70
      1579709.19      6892186.26      1579848.92      6892435.80
      1579861.16      6892490.20      1579901.63      6892539.74
      1579901.40      6892586.36      1579862.56      6892638.00
      1579900.53      6892689.68      1579912.98      6892744.38
      1579960.64      6892786.07      1580105.00      6892788.00

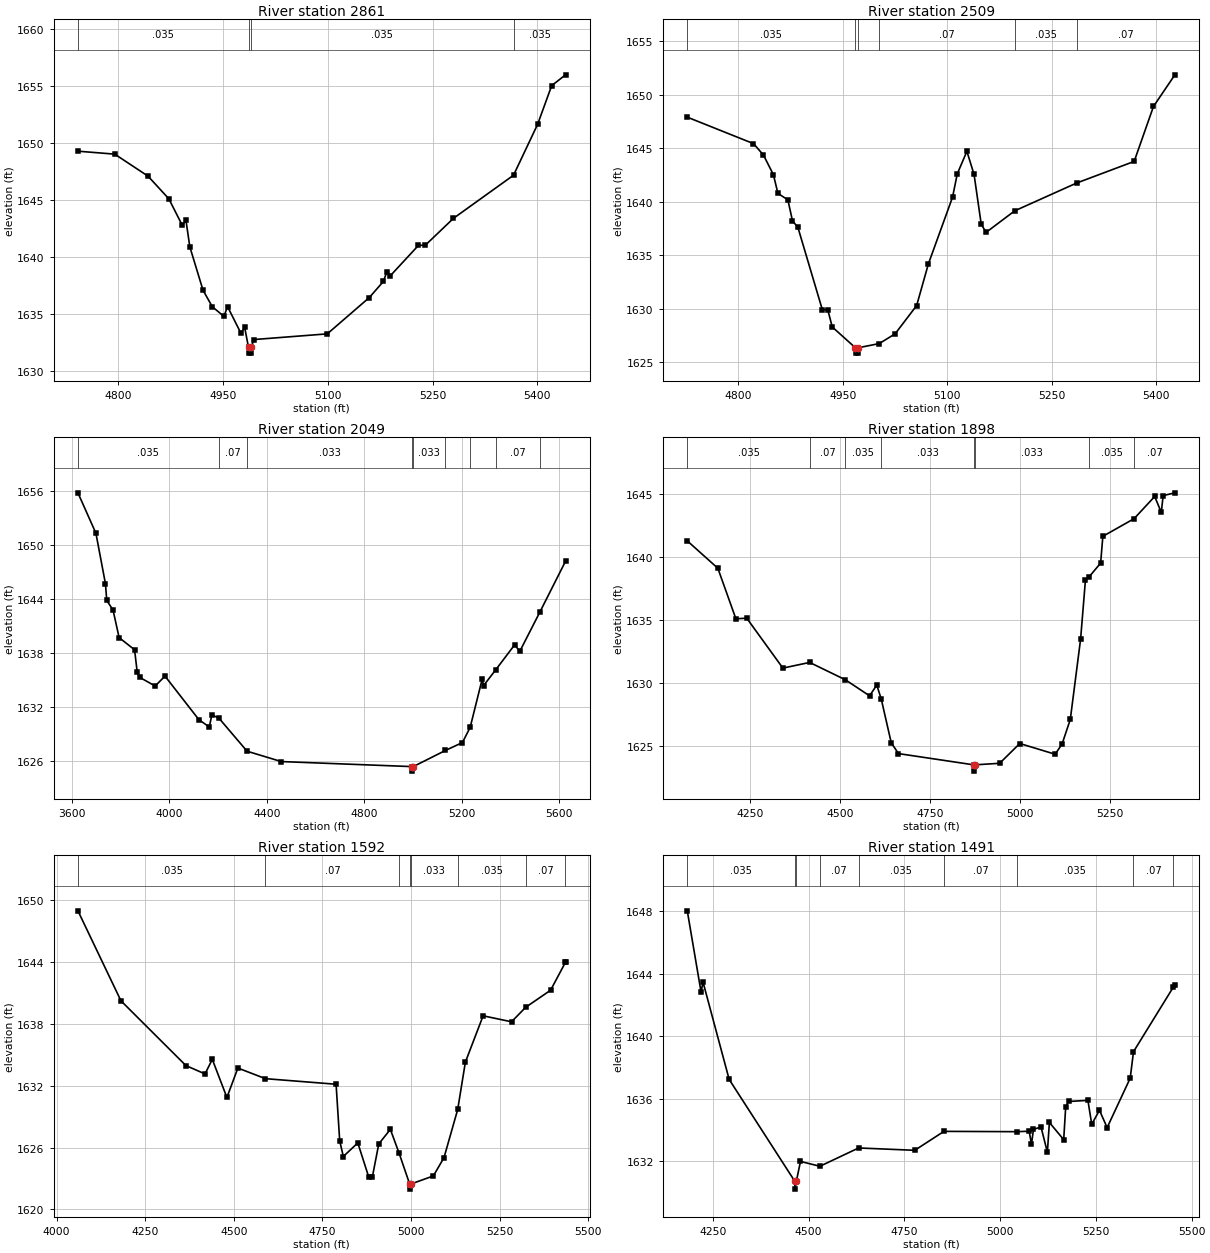
Type RM Length L Ch R = 1,2861,352,352,352
BEGIN DESCRIPTION:
Mapping XS a0d47c7c
END DESCRIPTION:
XS GIS Cut Line= 3
      1579825.96      6890456.58      1580060.31      6890548.58
      1580504.76      6890512.12
#Sta/Elev= 30
  4742.5 1649.30  4795.2 1649.04  4842.8 1647.11  4872.6 1645.12  4891.7 1642.81
  4897.1 1643.23  4902.6 1640.91  4921.5 1637.10  4934.8 1635.65  4951.3 1634.81
  4956.7 1635.65  4975.7 1633.33  4981.1 1633.83  4986.6 1632.08  4986.8 1631.58
  4990.3 1631.58  4990.6 1632.08  4994.1 1632.77  5099.3 1633.27  5159.5 1636.46
  5179.6 1637.87  5184.7 1638.74  5189.7 1638.38  5229.7 1641.03  5239.8 1641.06
  5279.9 1643.41  5365.8 1647.19  5400.3 1651.66  5420.4 1655.05  5440.2 1656.00
#Mann=4,-1,0
  4742.5   0.035       0  4986.6    0.07       0  4990.6   0.035       0
  5365.8   0.035       0
Bank Sta=4986.6,4990.6
Exp/Cntr=0.3,0.1

Type RM Length L Ch R = 1,2509,460,460,460
BEGIN DESCRIPTION:
Mapping XS 3ee6cf5b
END DESCRIPTION:
XS GIS Cut Line= 3
      1579876.30      6890623.26      1580056.83      6890836.77
      1580464.79      6890937.46
#Sta/Elev= 30
  4726.8 1647.89  4821.8 1645.42  4836.1 1644.36  4850.4 1642.52  4856.9 1640.78
  4871.2 1640.17  4877.8 1638.21  4885.5 1637.62  4920.6 1629.93  4928.4 1629.92
  4934.9 1628.31  4968.1 1626.37  4968.3 1625.87  4971.8 1625.87  4972.1 1626.37
  5002.3 1626.76  5025.1 1627.67  5056.0 1630.31  5072.8 1634.19  5107.5 1640.42
  5114.3 1642.60  5128.1 1644.70  5138.4 1642.54  5148.7 1637.89  5155.7 1637.14
  5196.8 1639.15  5285.5 1641.74  5368.2 1643.76  5395.9 1648.89  5426.6 1651.84
#Mann=6,-1,0
  4726.8   0.035       0  4968.1   0.035       0  4972.1   0.035       0
  5002.3    0.07       0  5196.8   0.035       0  5285.5    0.07       0
Bank Sta=4968.1,4972.1
Exp/Cntr=0.3,0.1

Type RM Length L Ch R = 1,2049,151,151,151
BEGIN DESCRIPTION:
Mapping XS bb1770ac
END DESCRIPTION:
XS GIS Cut Line= 3
      1578505.00      6890755.53      1579805.87      6891203.36
      1580419.13      6891072.82
#Sta/Elev= 30
  3624.2 1655.79  3698.2 1651.30  3737.3 1645.70  3742.6 1643.86  3768.5 1642.78
  3793.4 1639.73  3856.9 1638.38  3867.5 1635.95  3878.0 1635.32  3941.5 1634.36
  3981.8 1635.46  4121.3 1630.62  4163.6 1629.82  4174.4 1631.14  4202.6 1630.82
  4318.9 1627.13  4459.7 1625.98  4997.4 1625.42  4997.7 1624.92  5001.4 1625.42
  5133.5 1627.21  5203.6 1628.09  5235.4 1629.78  5285.1 1635.17  5290.2 1634.40
  5339.8 1636.14  5418.3 1638.94  5438.9 1638.19  5522.7 1642.62  5627.0 1648.20
#Mann=9,-1,0
  3624.2   0.035       0  4202.6    0.07       0  4318.9   0.033       0
  4997.4   0.033       0  5001.4   0.033       0  5133.5    0.07       0
  5235.4   0.035       0  5339.8    0.07       0  5522.7   0.035       0
Bank Sta=4997.4,5001.4
Exp/Cntr=0.3,0.1

Type RM Length L Ch R = 1,1898,306,306,306
BEGIN DESCRIPTION:
Mapping XS 3be17af5
END DESCRIPTION:
XS GIS Cut Line= 3
      1578800.42      6891386.87      1579721.48      6891321.26
      1580139.43      6891421.08
#Sta/Elev= 30
  4076.6 1641.30  4161.4 1639.13  4211.5 1635.12  4241.6 1635.17  4341.9 1631.21
  4416.2 1631.66  4515.6 1630.28  4582.5 1629.01  4602.5 1629.87  4615.1 1628.73
  4642.6 1625.29  4662.7 1624.43  4871.2 1623.54  4871.4 1623.04  4875.2 1623.54
  4943.4 1623.66  4999.3 1625.23  5097.4 1624.38  5116.7 1625.19  5139.5 1627.14
  5168.1 1633.51  5181.6 1638.22  5191.5 1638.44  5223.7 1639.54  5229.8 1641.66
  5316.5 1643.06  5373.7 1644.82  5392.0 1643.56  5397.2 1644.89  5429.7 1645.11
#Mann=8,-1,0
  4076.6   0.035       0  4416.2    0.07       0  4515.6   0.035       0
  4615.1   0.033       0  4871.2   0.033       0  4875.2   0.033       0
  5191.5   0.035       0  5316.5    0.07       0
Bank Sta=4871.2,4875.2
Exp/Cntr=0.3,0.1

Type RM Length L Ch R = 1,1592,101,101,101
BEGIN DESCRIPTION:
Mapping XS e379e5ac
END DESCRIPTION:
XS GIS Cut Line= 4
      1578787.10      6891508.19      1579370.57      6891654.49
      1579700.36      6891585.29      1580136.96      6891552.87
#Sta/Elev= 30
  4060.0 1648.93  4181.5 1640.21  4364.8 1633.94  4418.7 1633.13  4439.3 1634.54
  4480.5 1630.85  4511.5 1633.70  4589.4 1632.67  4788.7 1632.13  4798.9 1626.65
  4809.1 1625.13  4850.0 1626.45  4880.6 1623.17  4890.8 1623.10  4909.2 1626.35
  4941.9 1627.76  4966.7 1625.44  4996.3 1622.47  4996.6 1621.97  5000.3 1622.47
  5063.3 1623.25  5093.4 1625.03  5132.0 1629.69  5153.6 1634.27  5203.7 1638.76
  5283.9 1638.18  5323.7 1639.58  5394.2 1641.24  5435.9 1643.93  5436.3 1643.93
#Mann=8,-1,0
  4060.0   0.035       0  4589.4    0.07       0  4966.7   0.033       0
  4996.3   0.033       0  5000.3   0.033       0  5132.0   0.035       0
  5323.7    0.07       0  5435.9   0.035       0
Bank Sta=4996.3,5000.3
Exp/Cntr=0.3,0.1

Type RM Length L Ch R = 1,1491,55,55,55
BEGIN DESCRIPTION:
Mapping XS 73542eb3
END DESCRIPTION:
XS GIS Cut Line= 6
      1578887.81      6891685.28      1579304.46      6891768.99
      1579594.02      6891685.12      1579680.83      6891665.59
      1579867.46      6891617.84      1580131.08      6891594.07
#Sta/Elev= 30
  4183.4 1648.01  4219.4 1642.82  4224.5 1643.46  4292.7 1637.24  4464.1 1630.73
  4464.4 1630.23  4468.1 1630.73  4478.9 1632.00  4529.6 1631.69  4630.7 1632.86
  4777.2 1632.71  4853.5 1633.92  5044.7 1633.90  5075.8 1633.93  5081.9 1633.10
  5087.1 1634.05  5106.8 1634.20  5123.4 1632.58  5128.6 1634.49  5166.0 1633.39
  5171.2 1635.48  5178.7 1635.83  5229.2 1635.90  5239.2 1634.37  5259.3 1635.27
  5279.4 1634.16  5339.6 1637.32  5348.2 1639.01  5452.5 1643.15  5456.2 1643.29
#Mann=9,-1,0
  4183.4   0.035       0  4464.1    0.07       0  4468.1   0.035       0
  4529.6    0.07       0  4630.7   0.035       0  4853.5    0.07       0
  5044.7   0.035       0  5348.2    0.07       0  5452.5   0.035       0
Bank Sta=4464.1,4468.1
Exp/Cntr=0.3,0.1

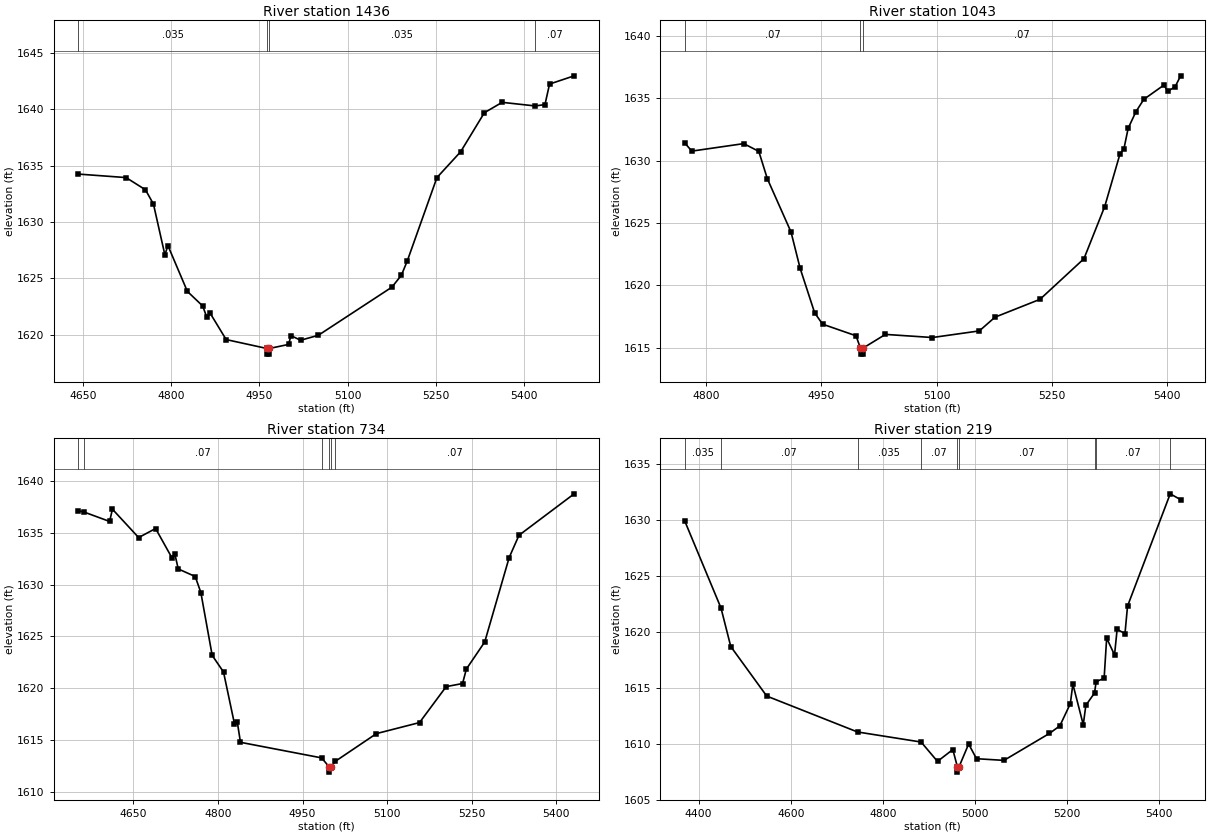
Type RM Length L Ch R = 1,1436,393,393,393
BEGIN DESCRIPTION:
Mapping XS 1ffd9250
END DESCRIPTION:
XS GIS Cut Line= 3
      1579362.85      6891816.57      1579704.70      6891713.33
      1580186.51      6891656.90
#Sta/Elev= 30
  4642.5 1634.25  4723.6 1633.94  4756.5 1632.86  4770.1 1631.59  4789.5 1627.09
  4794.7 1627.91  4827.7 1623.85  4853.7 1622.56  4860.6 1621.58  4865.9 1621.96
  4893.6 1619.58  4962.8 1618.79  4963.0 1618.29  4966.5 1618.29  4966.8 1618.79
  4999.6 1619.15  5003.7 1619.93  5020.0 1619.52  5050.2 1619.96  5175.2 1624.23
  5191.2 1625.28  5201.3 1626.56  5251.6 1633.94  5291.9 1636.23  5332.2 1639.69
  5362.4 1640.61  5418.5 1640.29  5435.1 1640.41  5442.9 1642.23  5484.7 1642.96
#Mann=4,-1,0
  4642.5   0.035       0  4962.8   0.035       0  4966.8   0.035       0
  5418.5    0.07       0
Bank Sta=4962.8,4966.8
Exp/Cntr=0.3,0.1

Type RM Length L Ch R = 1,1043,309,309,309
BEGIN DESCRIPTION:
Mapping XS a00ce790
END DESCRIPTION:
XS GIS Cut Line= 3
      1579390.21      6891991.23      1579605.09      6892038.98
      1580021.98      6891959.06
#Sta/Elev= 30
  4772.7 1631.41  4781.8 1630.76  4849.3 1631.36  4868.9 1630.74  4880.0 1628.55
  4910.8 1624.28  4922.6 1621.38  4941.5 1617.81  4951.8 1616.90  4995.3 1615.97
  5000.9 1615.00  5001.2 1614.50  5004.7 1614.50  5004.9 1615.00  5033.5 1616.08
  5094.6 1615.83  5155.6 1616.36  5176.0 1617.46  5234.5 1618.89  5291.6 1622.14
  5318.6 1626.32  5338.5 1630.54  5343.6 1630.95  5349.1 1632.59  5359.3 1633.93
  5369.5 1634.91  5395.6 1636.05  5400.7 1635.55  5410.2 1635.92  5417.3 1636.79
#Mann=3,-1,0
  4772.7    0.07       0  5000.9    0.07       0  5004.9    0.07       0
Bank Sta=5000.9,5004.9
Exp/Cntr=0.3,0.1

Type RM Length L Ch R = 1,734,515,515,515
BEGIN DESCRIPTION:
Mapping XS b4ab303d
END DESCRIPTION:
XS GIS Cut Line= 3
      1579318.45      6892338.33      1579750.71      6892299.27
      1580161.11      6892125.23
#Sta/Elev= 30
  4552.2 1637.10  4562.2 1636.98  4607.7 1636.07  4612.7 1637.25  4659.2 1634.52
  4689.3 1635.39  4718.5 1632.55  4723.5 1632.92  4729.5 1631.50  4759.6 1630.77
  4769.6 1629.23  4789.7 1623.18  4809.8 1621.58  4829.2 1616.60  4834.3 1616.75
  4839.9 1614.81  4983.9 1613.31  4997.3 1612.44  4997.5 1611.94  5001.3 1612.44
  5007.9 1612.97  5081.2 1615.65  5157.6 1616.71  5204.9 1620.17  5234.0 1620.47
  5240.7 1621.86  5273.3 1624.47  5316.7 1632.60  5334.1 1634.74  5432.0 1638.73
#Mann=6,-1,0
  4552.2   0.035       0  4562.2    0.07       0  4983.9   0.035       0
  4997.3   0.035       0  5001.3   0.035       0  5007.9    0.07       0
Bank Sta=4997.3,5001.3
Exp/Cntr=0.3,0.1

Type RM Length L Ch R = 1,219,0,0,0
BEGIN DESCRIPTION:
Mapping XS 58691edf
END DESCRIPTION:
XS GIS Cut Line= 3
      1579433.00      6892408.64      1579823.62      6892775.83
      1580310.64      6892541.43
#Sta/Elev= 30
  4369.9 1629.89  4448.5 1622.12  4469.7 1618.68  4547.8 1614.25  4744.9 1611.04
  4883.0 1610.14  4918.6 1608.41  4951.9 1609.47  4961.6 1607.95  4961.9 1607.45
  4965.6 1607.95  4986.2 1609.96  5003.3 1608.65  5062.9 1608.50  5161.7 1610.91
  5184.3 1611.59  5207.0 1613.57  5212.5 1615.32  5235.1 1611.69  5240.7 1613.42
  5259.5 1614.52  5263.1 1615.54  5280.4 1615.84  5285.9 1619.43  5303.0 1617.93
  5308.6 1620.21  5325.7 1619.84  5331.2 1622.29  5423.9 1632.33  5446.5 1631.81
#Mann=9,-1,0
  4369.9   0.035       0  4448.5    0.07       0  4744.9   0.035       0
  4883.0    0.07       0  4961.6    0.07       0  4965.6    0.07       0
  5259.5   0.035       0  5263.1    0.07       0  5423.9   0.035       0
Bank Sta=4961.6,4965.6
Exp/Cntr=0.3,0.1

Chan Stop Cuts=-1