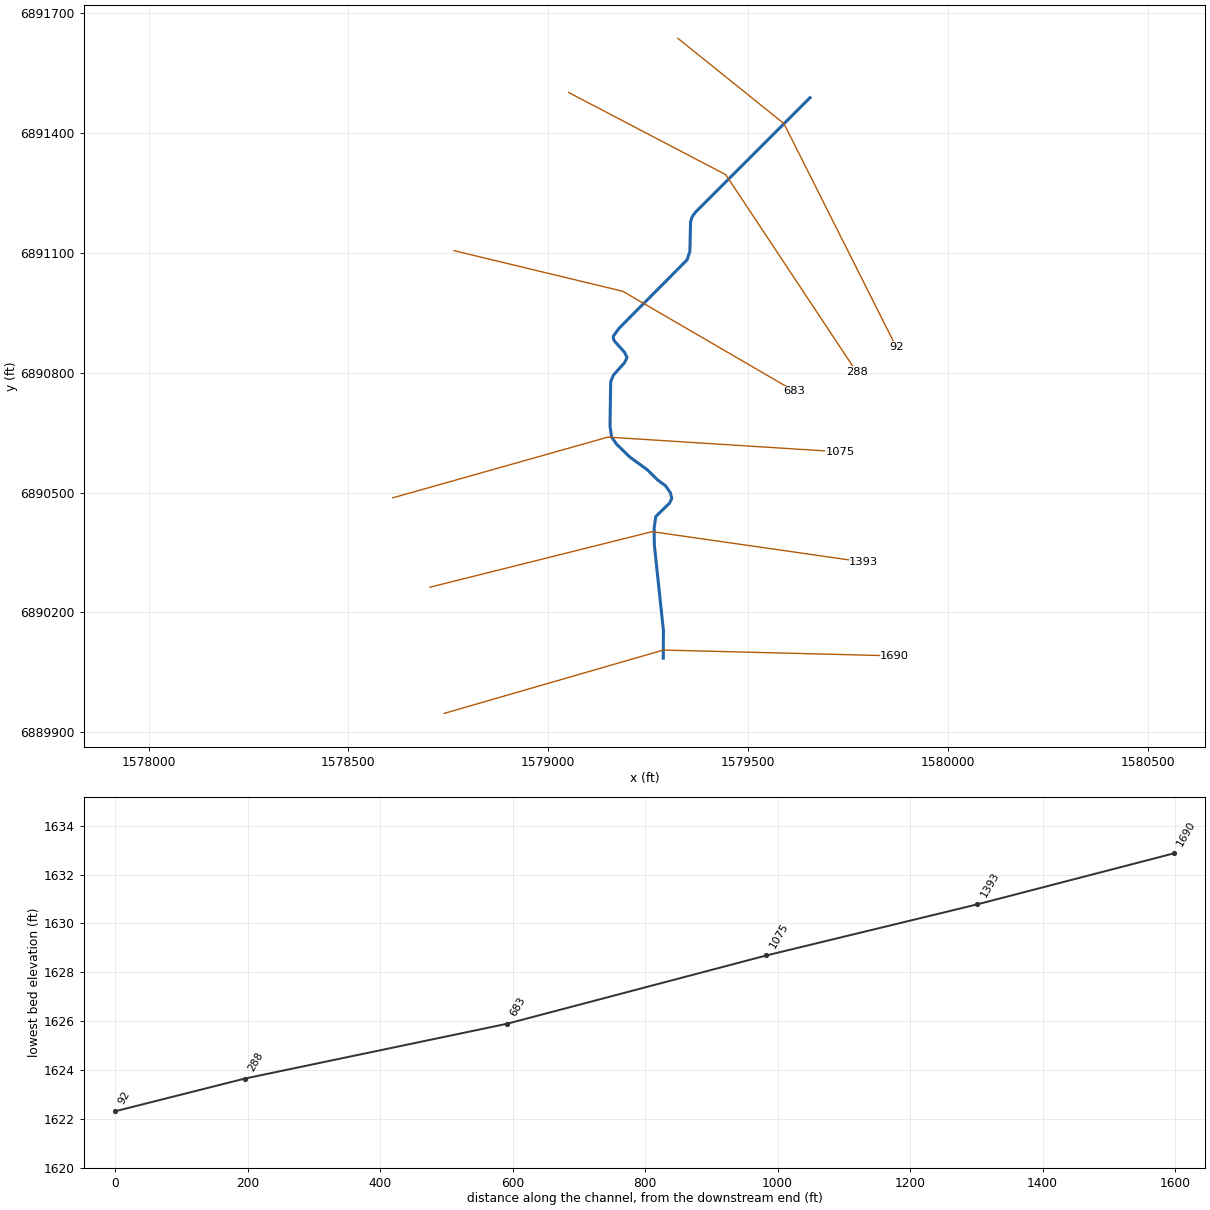
--- MULBERRY CREEK TRIBUTARY 3_1_1.prj (project) ---

Proj Title=MULBERRY CREEK TRIBUTARY 3_1_1 Base Level Engineering
Current Plan=p01
Default Exp/Contr=0.3,0.1
English Units
Geom File=g01
Flow File=f01
Plan File=p01
BEGIN DESCRIPTION:
MULBERRY CREEK TRIBUTARY 3_1_1
END DESCRIPTION:

--- MULBERRY CREEK TRIBUTARY 3_1_1.p01 (plan) ---

Plan Title=Multiple Run
Short Identifier=Multiple
Geom File=g01
Flow File=f01
Subcritical Flow
K Sum by GR= 0
Std Step Tol= 0.01
Critical Tol= 0.01
Num of Std Step Trials= 20
Max Error Tol= 0.3
Flow Tol Ratio= 0.001
Split Flow NTrial= 30
Split Flow Tol= 0.02
Split Flow Ratio= 0.02
Log Output Level= 0
Friction Slope Method= 1
Unsteady Friction Slope Method= 2
Unsteady Bridges Friction Slope Method= 1
Parabolic Critical Depth
Global Vel Dist=  1 , 1 , 1
Global Log Level= 0
CheckData=True
Encroach Param= -1, 0, 0, 0
BEGIN DESCRIPTION:
Multiple Run
END DESCRIPTION:

--- MULBERRY CREEK TRIBUTARY 3_1_1.f01 (steady flow) ---

Flow Title=Multiple
Number of Profiles=7
Profile Names=10-year,25-year,50-year,1pct_min,100-year,1pct_plu,500-year
River Rch & RM= MULBERRY CREEK T,Reach-1,1690
      42      52      59      34      68     135      89
Boundary for River Rch & Prof#=MULBERRY CREEK T,Reach-1,1
Up Type=0
Dn Type=3
Dn Slope=0.005
Boundary for River Rch & Prof#=MULBERRY CREEK T,Reach-1,2
Up Type=0
Dn Type=3
Dn Slope=0.005
Boundary for River Rch & Prof#=MULBERRY CREEK T,Reach-1,3
Up Type=0
Dn Type=3
Dn Slope=0.005
Boundary for River Rch & Prof#=MULBERRY CREEK T,Reach-1,4
Up Type=0
Dn Type=3
Dn Slope=0.005
Boundary for River Rch & Prof#=MULBERRY CREEK T,Reach-1,5
Up Type=0
Dn Type=3
Dn Slope=0.005
Boundary for River Rch & Prof#=MULBERRY CREEK T,Reach-1,6
Up Type=0
Dn Type=3
Dn Slope=0.005
Boundary for River Rch & Prof#=MULBERRY CREEK T,Reach-1,7
Up Type=0
Dn Type=3
Dn Slope=0.005

--- MULBERRY CREEK TRIBUTARY 3_1_1.g01 (geometry) ---

Geom Title=Existing Conditions

River Reach=MULBERRY CREEK T,Reach-1
Reach XY= 30
      1579287.96      6890085.61      1579288.27      6890154.74
      1579265.57      6890369.35      1579265.05      6890412.06
      1579269.21      6890440.18      1579303.59      6890473.52
      1579309.32      6890485.50      1579305.67      6890499.56
      1579293.14      6890517.47      1579274.22      6890531.10
      1579247.14      6890557.66      1579204.46      6890588.62
      1579171.08      6890620.94      1579158.28      6890639.37
      1579154.61      6890667.87      1579156.36      6890777.56
      1579163.43      6890794.19      1579190.93      6890824.84
      1579197.19      6890838.10      1579190.62      6890851.38
      1579166.68      6890878.01      1579163.14      6890884.67
      1579162.99      6890891.34      1579177.52      6890911.33
      1579347.14      6891081.83      1579354.47      6891103.22
      1579356.17      6891177.52      1579360.52      6891190.43
      1579368.40      6891201.30      1579655.00      6891488.00

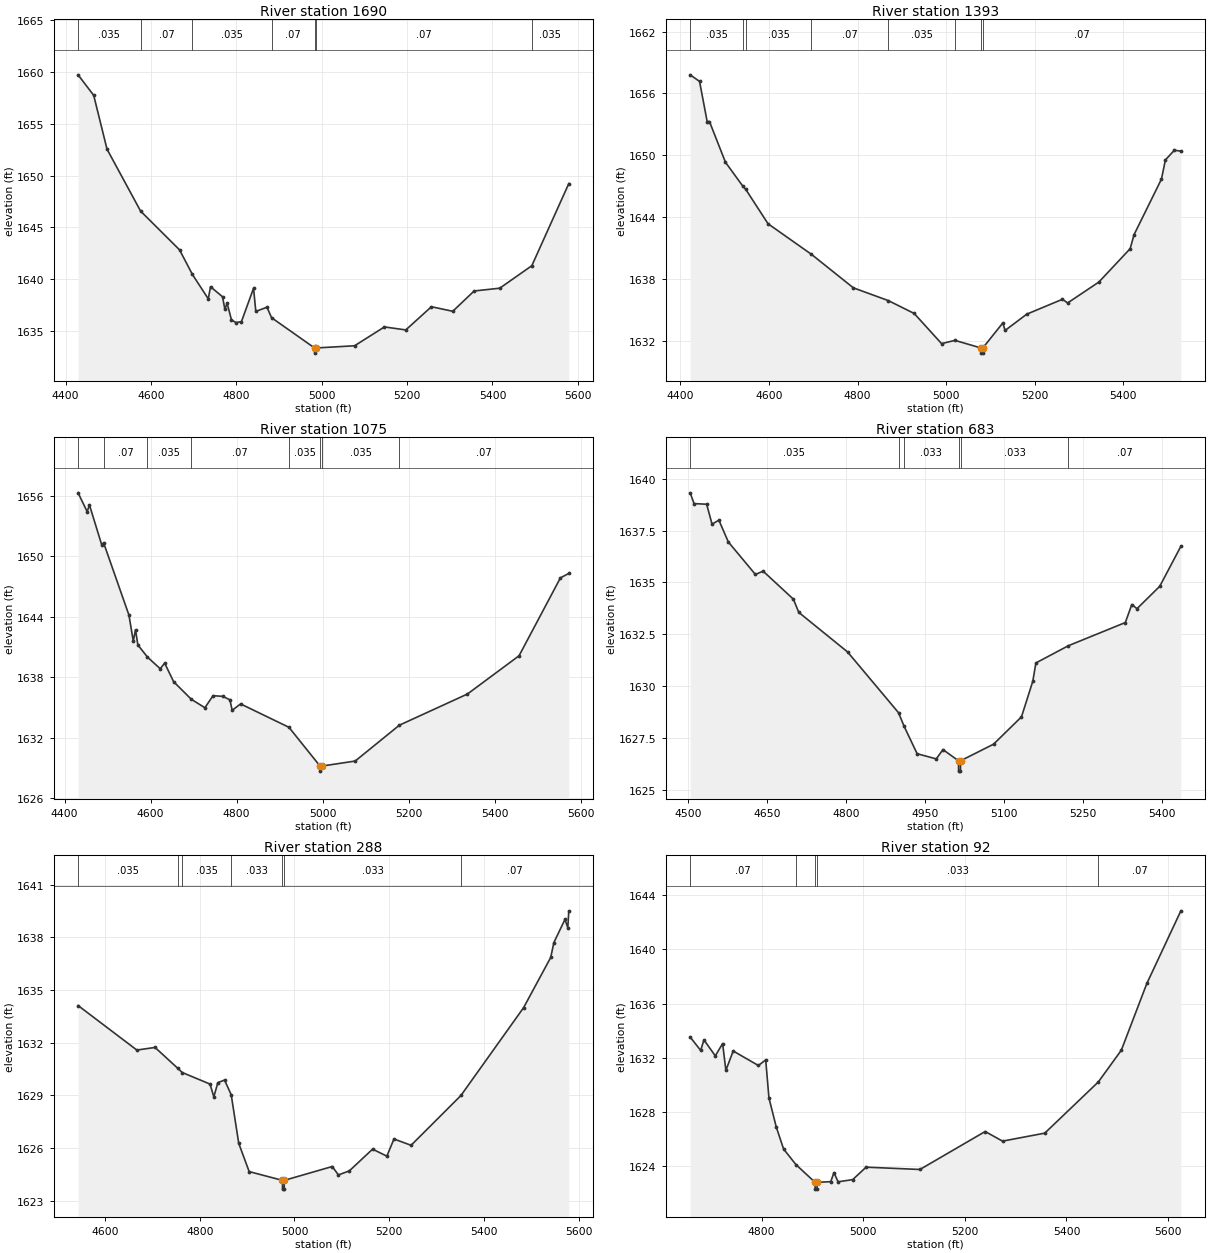
Type RM Length L Ch R = 1,1690,297,297,297
BEGIN DESCRIPTION:
MULBERRY CREEK TRIBUTARY 3_1_1 1.0
END DESCRIPTION:
XS GIS Cut Line= 3
      1578739.89      6889947.49      1579288.05      6890105.92
      1579866.67      6890091.38
#Sta/Elev= 30
  4429.4 1659.74  4466.0 1657.76  4497.2 1652.56  4575.9 1646.58  4667.1 1642.84
  4697.0 1640.48  4734.4 1638.11  4739.6 1639.28  4767.8 1638.31  4773.2 1637.10
  4778.4 1637.70  4788.6 1636.09  4799.0 1635.82  4812.0 1635.91  4840.4 1639.13
  4845.7 1636.90  4871.9 1637.30  4882.6 1636.29  4983.3 1633.37  4983.6 1632.87
  4987.3 1633.37  5077.0 1633.58  5147.0 1635.40  5197.0 1635.11  5257.0 1637.35
  5307.0 1636.91  5357.1 1638.87  5417.1 1639.14  5492.2 1641.31  5578.8 1649.24
#Mann=7,-1,0
  4429.4   0.035       0  4575.9    0.07       0  4697.0   0.035       0
  4882.6    0.07       0  4983.3    0.07       0  4987.3    0.07       0
  5492.2   0.035       0
Bank Sta=4983.3,4987.3
Exp/Cntr=0.3,0.1

Type RM Length L Ch R = 1,1393,318,318,318
BEGIN DESCRIPTION:
Mapping XS d4140447
END DESCRIPTION:
XS GIS Cut Line= 3
      1578704.43      6890263.25      1579259.99      6890402.14
      1579789.51      6890326.19
#Sta/Elev= 30
  4422.1 1657.80  4443.3 1657.16  4460.5 1653.26  4465.7 1653.26  4501.8 1649.31
  4541.0 1646.99  4547.1 1646.71  4597.9 1643.34  4695.9 1640.37  4790.4 1637.12
  4869.4 1635.88  4927.8 1634.63  4989.6 1631.70  5019.7 1632.02  5078.6 1631.28
  5078.9 1630.78  5082.4 1630.78  5082.6 1631.28  5127.8 1633.71  5132.9 1632.98
  5181.7 1634.56  5262.5 1636.01  5274.0 1635.65  5344.6 1637.68  5415.2 1640.92
  5424.1 1642.29  5485.8 1647.67  5494.8 1649.54  5515.0 1650.48  5529.7 1650.39
#Mann=8,-1,0
  4422.1   0.035       0  4541.0    0.07       0  4547.1   0.035       0
  4695.9    0.07       0  4869.4   0.035       0  5019.7    0.07       0
  5078.6   0.035       0  5082.6    0.07       0
Bank Sta=5078.6,5082.6
Exp/Cntr=0.3,0.1

Type RM Length L Ch R = 1,1075,392,392,392
BEGIN DESCRIPTION:
Mapping XS 528994ab
END DESCRIPTION:
XS GIS Cut Line= 3
      1578611.13      6890486.78      1579149.31      6890638.69
      1579730.43      6890601.83
#Sta/Elev= 30
  4431.2 1656.31  4452.4 1654.44  4457.6 1655.11  4486.4 1651.12  4490.5 1651.36
  4549.5 1644.18  4559.6 1641.60  4564.8 1642.71  4570.3 1641.21  4592.6 1640.01
  4622.3 1638.85  4632.6 1639.41  4653.4 1637.57  4694.6 1635.82  4726.2 1634.98
  4745.2 1636.18  4767.7 1636.11  4784.4 1635.77  4789.6 1634.73  4809.3 1635.36
  4921.7 1633.04  4994.1 1629.19  4994.4 1628.69  4998.1 1629.19  5075.8 1629.69
  5178.6 1633.25  5336.8 1636.34  5457.0 1640.14  5553.2 1647.87  5572.7 1648.31
#Mann=8,-1,0
  4431.2   0.035       0  4490.5    0.07       0  4592.6   0.035       0
  4694.6    0.07       0  4921.7   0.035       0  4994.1   0.035       0
  4998.1   0.035       0  5178.6    0.07       0
Bank Sta=4994.1,4998.1
Exp/Cntr=0.3,0.1

Type RM Length L Ch R = 1,683,395,395,395
BEGIN DESCRIPTION:
Mapping XS a61b549a
END DESCRIPTION:
XS GIS Cut Line= 3
      1578764.61      6891105.18      1579186.47      6891003.62
      1579616.12      6890753.64
#Sta/Elev= 30
  4504.6 1639.32  4512.0 1638.80  4535.9 1638.77  4546.1 1637.81  4559.1 1638.00
  4577.0 1636.95  4628.4 1635.38  4643.0 1635.54  4700.4 1634.19  4710.7 1633.55
  4803.3 1631.64  4899.9 1628.71  4910.4 1628.06  4935.2 1626.73  4971.5 1626.48
  4984.2 1626.93  5013.7 1626.39  5013.9 1625.89  5017.4 1625.89  5017.7 1626.39
  5080.2 1627.19  5133.2 1628.51  5154.7 1630.23  5160.5 1631.11  5222.0 1631.94
  5330.2 1633.06  5342.5 1633.93  5352.4 1633.73  5395.5 1634.81  5435.6 1636.74
#Mann=6,-1,0
  4504.6   0.035       0  4899.9    0.07       0  4910.4   0.033       0
  5013.7   0.033       0  5017.7   0.033       0  5222.0    0.07       0
Bank Sta=5013.7,5017.7
Exp/Cntr=0.3,0.1

Type RM Length L Ch R = 1,288,196,196,196
BEGIN DESCRIPTION:
Mapping XS 906f7599
END DESCRIPTION:
XS GIS Cut Line= 3
      1579051.01      6891501.04      1579444.28      6891295.29
      1579771.55      6890801.78
#Sta/Elev= 30
  4543.2 1634.12  4667.3 1631.58  4705.7 1631.73  4754.1 1630.53  4763.1 1630.30
  4821.8 1629.64  4829.8 1628.91  4838.2 1629.72  4852.4 1629.87  4866.5 1629.03
  4882.4 1626.26  4904.4 1624.65  4974.6 1624.15  4974.8 1623.65  4978.3 1623.65
  4978.6 1624.15  5079.8 1624.94  5092.8 1624.46  5115.8 1624.69  5165.0 1625.93
  5195.1 1625.53  5210.1 1626.51  5246.2 1626.15  5351.5 1628.99  5483.8 1634.00
  5541.0 1636.86  5547.7 1637.71  5571.1 1639.03  5577.1 1638.56  5579.2 1639.52
#Mann=7,-1,0
  4543.2   0.035       0  4754.1    0.07       0  4763.1   0.035       0
  4866.5   0.033       0  4974.6   0.033       0  4978.6   0.033       0
  5351.5    0.07       0
Bank Sta=4974.6,4978.6
Exp/Cntr=0.3,0.1

Type RM Length L Ch R = 1,92,0,0,0
BEGIN DESCRIPTION:
MULBERRY CREEK TRIBUTARY 3_1_1 0.0
END DESCRIPTION:
XS GIS Cut Line= 3
      1579324.45      6891636.46      1579590.00      6891423.01
      1579870.68      6890864.36
#Sta/Elev= 30
  4659.3 1633.53  4680.0 1632.54  4686.4 1633.32  4708.8 1632.14  4723.2 1633.05
  4729.6 1631.07  4744.0 1632.50  4793.6 1631.43  4808.0 1631.84  4814.4 1629.03
  4828.8 1626.89  4843.2 1625.27  4867.5 1624.12  4905.2 1622.81  4905.5 1622.31
  4909.0 1622.31  4909.2 1622.81  4936.0 1622.86  4942.4 1623.53  4950.4 1622.85
  4979.2 1623.01  5005.6 1623.93  5111.6 1623.76  5240.0 1626.56  5274.2 1625.85
  5357.3 1626.44  5462.8 1630.22  5508.0 1632.56  5558.2 1637.48  5625.2 1642.84
#Mann=5,-1,0
  4659.3    0.07       0  4867.5   0.033       0  4905.2   0.033       0
  4909.2   0.033       0  5462.8    0.07       0
Bank Sta=4905.2,4909.2
Exp/Cntr=0.3,0.1

Chan Stop Cuts=-1