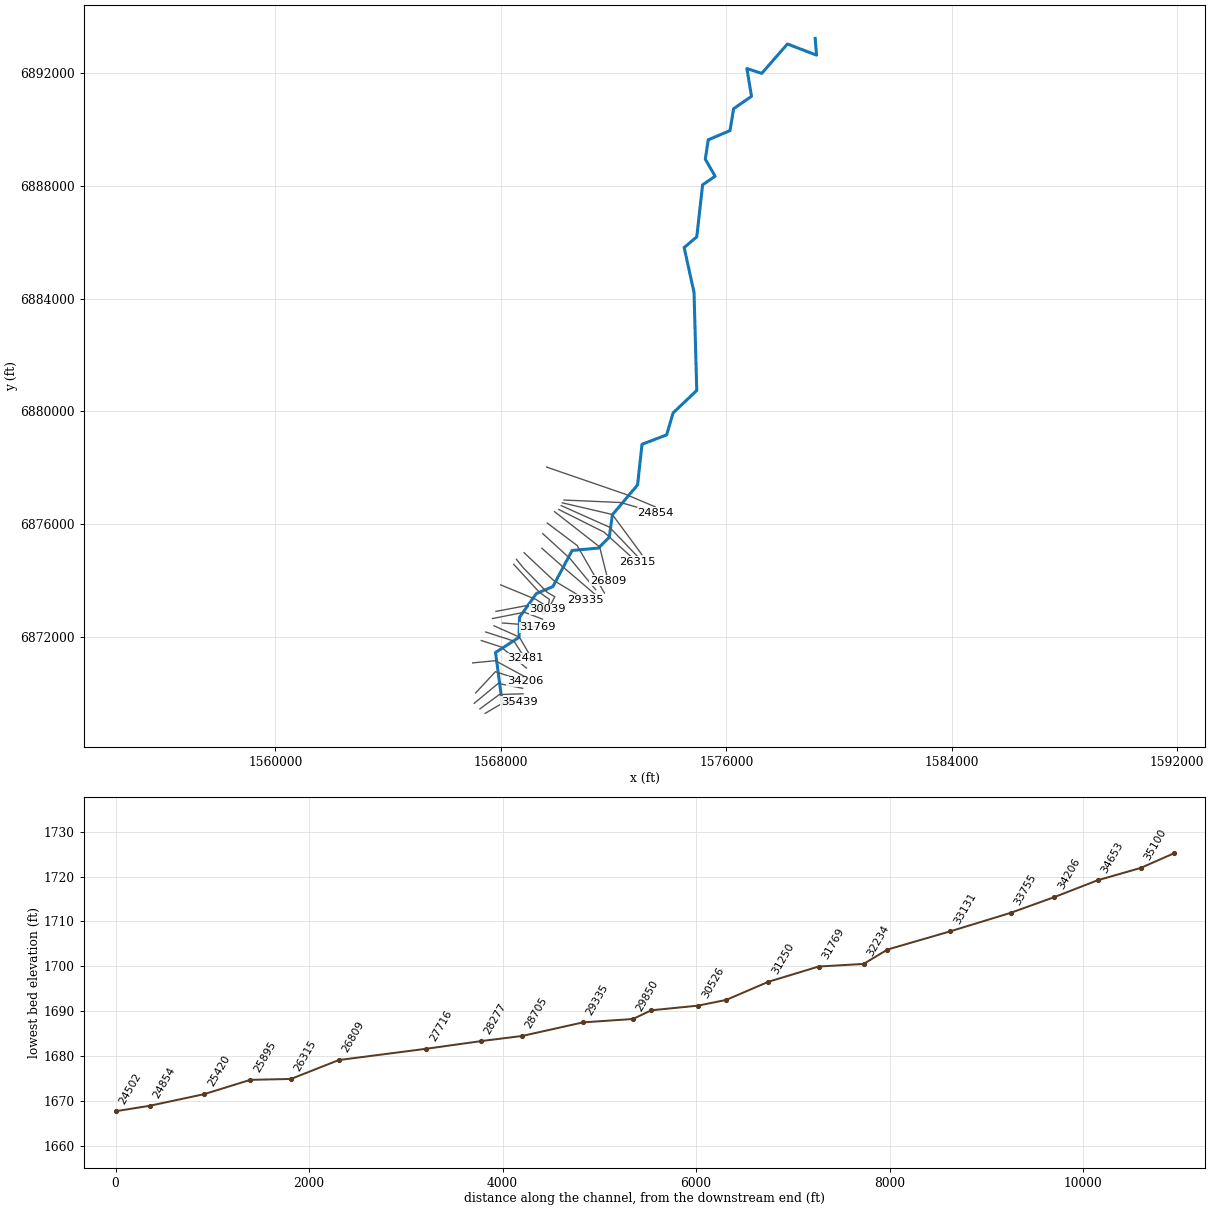
--- MULBERRY CREEK TRIBUTARY 4.prj (project) ---

Proj Title=MULBERRY CREEK TRIBUTARY 4 Base Level Engineering
Current Plan=p01
Default Exp/Contr=0.3,0.1
English Units
Geom File=g01
Flow File=f01
Plan File=p01
Y Axis Title=Elevation
X Axis Title(PF)=Main Channel Distance
X Axis Title(XS)=Station
BEGIN DESCRIPTION:
MULBERRY CREEK TRIBUTARY 4
END DESCRIPTION:
DSS Export Rating Curves= 0
DSS Export Rating Curve Sorted= 0
DSS Export Volume Flow Curves= 0
DXF OffsetX= 0
DXF OffsetY= 0
DXF ScaleX= 1
DXF ScaleY= 10

--- MULBERRY CREEK TRIBUTARY 4.p01 (plan) ---

Plan Title=Multiple Run
Short Identifier=Multiple
Geom File=g01
Flow File=f01
Subcritical Flow
K Sum by GR= 0
Std Step Tol= 0.01
Critical Tol= 0.01
Num of Std Step Trials= 20
Max Error Tol= 0.3
Flow Tol Ratio= 0.001
Split Flow NTrial= 30
Split Flow Tol= 0.02
Split Flow Ratio= 0.02
Log Output Level= 0
Friction Slope Method= 1
Unsteady Friction Slope Method= 2
Unsteady Bridges Friction Slope Method= 1
Parabolic Critical Depth
Global Vel Dist=  1 , 1 , 1
Global Log Level= 0
CheckData=True
Encroach Param= -1, 0, 0, 0
BEGIN DESCRIPTION:
Multiple Run
END DESCRIPTION:

--- MULBERRY CREEK TRIBUTARY 4.f01 (steady flow) ---

Flow Title=Multiple
Program Version=4.10
Number of Profiles= 7
Profile Names=10-year,25-year,50-year,1pct_min,100-year,1pct_plu,500-year
River Rch & RM=MULBERRY CREEK T,Reach-1         ,35439
     175     237     286     173     345     688     506
River Rch & RM=MULBERRY CREEK T,Reach-1         ,29335
     354     499     620     384     765    1527    1181
River Rch & RM=MULBERRY CREEK T,Reach-1         ,23553
     458     653     819     510    1018    2030    1594
River Rch & RM=MULBERRY CREEK T,Reach-1         ,20201
     483     690     865     539    1076    2146    1686
River Rch & RM=MULBERRY CREEK T,Reach-1         ,16169
     585     842    1063     666    1329    2652    2107
River Rch & RM=MULBERRY CREEK T,Reach-1         ,14581
     588     846    1067     668    1332    2658    2107
River Rch & RM=MULBERRY CREEK T,Reach-1         ,12347
     680     985    1247     784    1564    3120    2493
River Rch & RM=MULBERRY CREEK T,Reach-1         ,9777
     732    1061    1345     845    1686    3364    2689
River Rch & RM=MULBERRY CREEK T,Reach-1         ,5391
     761    1103    1397     877    1751    3493    2790
Boundary for River Rch & Prof#=MULBERRY CREEK T,Reach-1         , 1
Up Type= 0
Dn Type= 3
Dn Slope=0.005
Boundary for River Rch & Prof#=MULBERRY CREEK T,Reach-1         , 2
Up Type= 0
Dn Type= 3
Dn Slope=0.005
Boundary for River Rch & Prof#=MULBERRY CREEK T,Reach-1         , 3
Up Type= 0
Dn Type= 3
Dn Slope=0.005
Boundary for River Rch & Prof#=MULBERRY CREEK T,Reach-1         , 4
Up Type= 0
Dn Type= 3
Dn Slope=0.005
Boundary for River Rch & Prof#=MULBERRY CREEK T,Reach-1         , 5
Up Type= 0
Dn Type= 3
Dn Slope=0.005
Boundary for River Rch & Prof#=MULBERRY CREEK T,Reach-1         , 6
Up Type= 0
Dn Type= 3
Dn Slope=0.005
Boundary for River Rch & Prof#=MULBERRY CREEK T,Reach-1         , 7
Up Type= 0
Dn Type= 3
Dn Slope=0.005
DSS Import GetInterval= 0
DSS Import GetPeak= 0
DSS Import FillOption= 0

--- MULBERRY CREEK TRIBUTARY 4.g01 (geometry) ---

Geom Title=Existing Conditions
Program Version=4.10

River Reach=MULBERRY CREEK T,Reach-1
Reach XY= 30
        1568055.        6869588.       1567810.3      6871440.67
      1568644.53      6871978.18       1568660.4      6872690.43
      1569260.38      6873532.83      1569844.52       6873778.2
      1570527.88      6875061.52      1571458.42       6875145.8
      1571844.83      6875528.32      1571958.51      6876329.52
      1572851.45      6877389.47       1573008.5      6878829.54
      1573881.94      6879164.15      1574113.04      6879944.33
      1574951.53       6880739.5      1574855.11      6884217.89
       1574504.7      6885813.12      1574952.95      6886193.84
      1575158.47       6888036.5      1575602.96      6888343.86
      1575255.49      6888948.49      1575358.52      6889636.54
      1576129.53      6889960.86      1576260.45      6890740.47
      1576895.87      6891181.26      1576731.58      6892165.57
       1577257.3      6891993.83       1578170.6       6893037.6
       1579203.6        6892641.        1579155.        6893238.

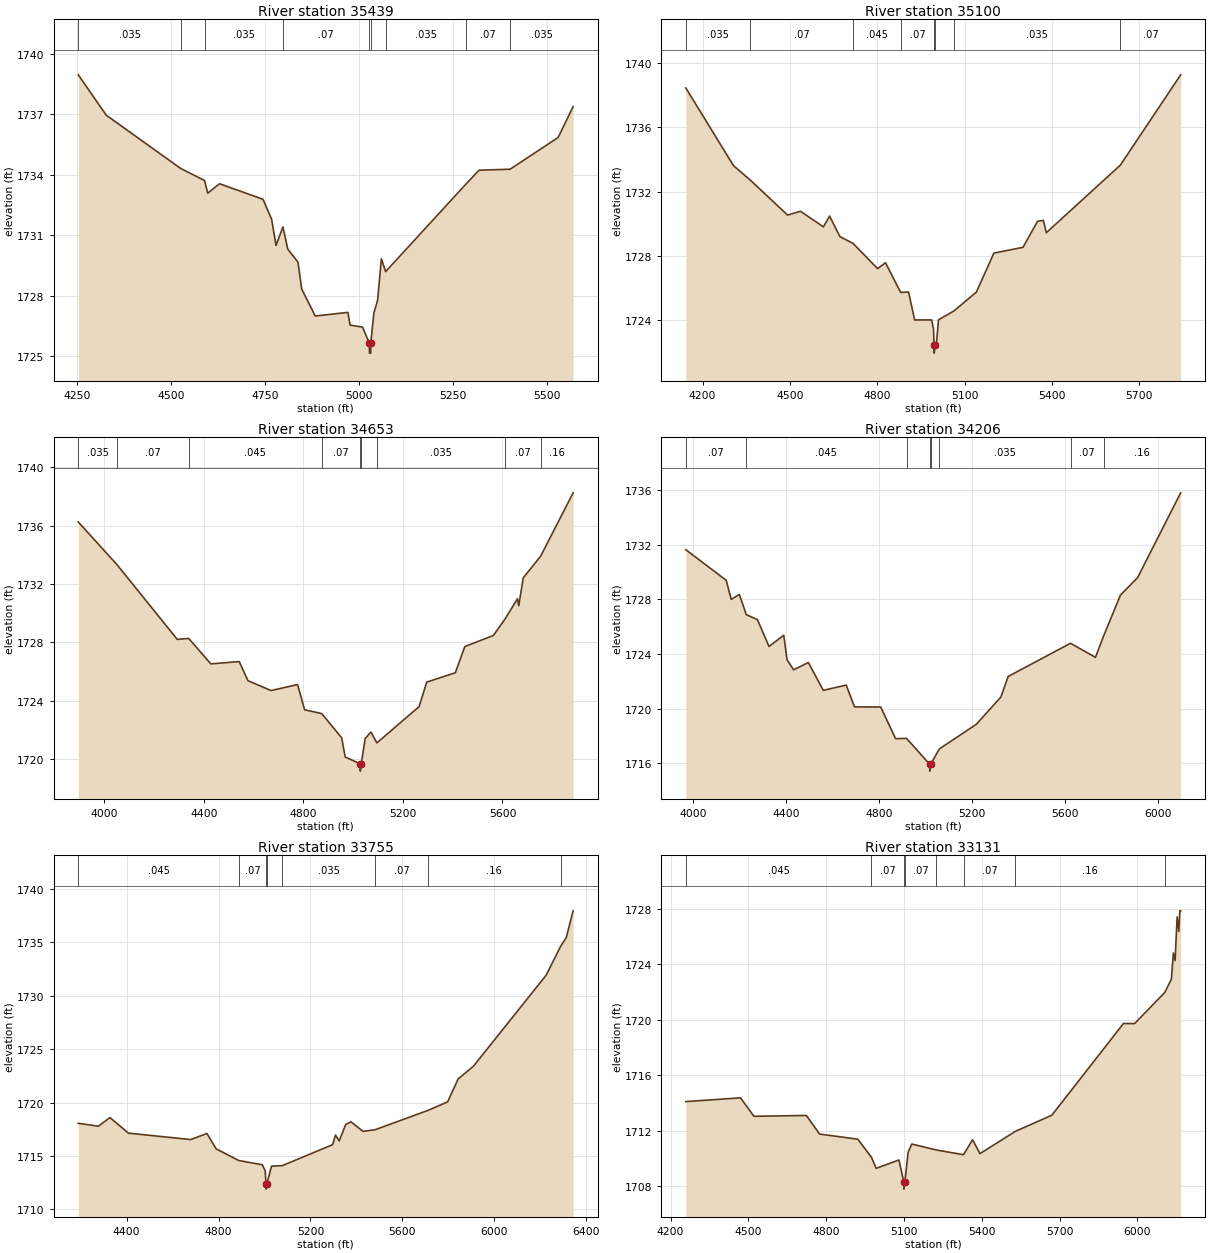
Type RM Length L Ch R = 1 ,35439   ,339,339,339
BEGIN DESCRIPTION:
MULBERRY CREEK TRIBUTARY 4 53.0
END DESCRIPTION:
XS GIS Cut Line= 3
      1567440.72       6869279.6      1568085.61      6869657.98
      1568655.02        6869688.
#Sta/Elev= 30
  4252.3 1738.95  4326.8 1736.95  4524.8 1734.31  4588.5 1733.71  4597.1 1733.08
  4628.3 1733.55  4744.2 1732.78  4767.2 1731.79    4779 1730.49  4797.3 1731.41
  4810.2 1730.31  4837.4 1729.66  4847.3 1728.33  4883.4 1726.99  4970.4 1727.17
  4976.2 1726.54  5009.4 1726.44  5027.4 1725.65  5027.7 1725.15  5031.2 1725.15
  5031.4 1725.65  5039.4 1727.13  5049.5 1727.77  5059.5 1729.83  5070.8 1729.19
  5284.6 1733.53  5319.8 1734.22  5402.4 1734.27  5530.1 1735.84  5570.2 1737.37
#Mann= 9 ,-1 , 0
  4252.3    .035       0  4524.8     .07       0  4588.5    .035       0
  4797.3     .07       0  5027.4     .07       0  5031.4     .07       0
  5070.8    .035       0  5284.6     .07       0  5402.4    .035       0
Bank Sta=5027.4,5031.4
XS Rating Curve= 0 ,0
Exp/Cntr=0.3,0.1

Type RM Length L Ch R = 1 ,35100   ,447,447,447
BEGIN DESCRIPTION:
MULBERRY CREEK TRIBUTARY 4 52.0
END DESCRIPTION:
XS GIS Cut Line= 3
      1567254.96      6869437.97      1567944.46      6869947.78
      1568786.25      6869974.04
#Sta/Elev= 30
  4142.5 1738.46  4306.4 1733.61  4364.1 1732.71  4492.2 1730.53  4536.1 1730.77
  4615.1  1729.8  4636.3 1730.47  4671.7 1729.19  4717.3 1728.76  4801.2 1727.19
  4828.3 1727.56  4880.4 1725.71  4907.6 1725.73  4928.5 1723.99    4987 1723.99
  4993.2 1723.42  4995.2 1722.42  4995.5 1721.92  4999.2 1722.42  5002.8 1722.42
  5010.5    1724  5063.3 1724.55  5140.6 1725.73  5200.6 1728.16  5300.7 1728.52
  5350.7 1730.15  5370.7  1730.2  5380.7 1729.43  5635.2 1733.65  5842.2 1739.28
#Mann= 8 ,-1 , 0
  4142.5    .035       0  4364.1     .07       0  4717.3    .045       0
  4880.4     .07       0  4995.2     .07       0  4999.2     .07       0
  5063.3    .035       0  5635.2     .07       0
Bank Sta=4995.2,4999.2
XS Rating Curve= 0 ,0
Exp/Cntr=0.3,0.1

Type RM Length L Ch R = 1 ,34653   ,447,447,447
BEGIN DESCRIPTION:
MULBERRY CREEK TRIBUTARY 4 51.0
END DESCRIPTION:
XS GIS Cut Line= 3
      1567055.02      6869638.01        1567905.        6870343.
      1568771.64      6870169.66
#Sta/Elev= 30
  3895.7 1736.26  4051.3 1733.33  4293.5  1728.2  4339.2 1728.27  4428.4 1726.52
  4542.3 1726.68  4577.4 1725.37  4669.9 1724.69  4776.7  1725.1  4805.1 1723.37
  4873.8 1723.11  4953.8 1721.45  4968.1 1720.13  5028.6 1719.66  5028.8 1719.16
  5032.6 1719.66  5048.4  1721.4  5071.4 1721.84  5095.5  1721.1  5265.1 1723.59
  5295.7 1725.27  5410.5 1725.91  5448.7 1727.71  5563.4 1728.47  5609.8 1729.59
  5660.3 1730.99  5665.4 1730.51  5683.3 1732.42  5753.6 1733.92  5883.8 1738.26
#Mann= 9 ,-1 , 0
  3895.7    .035       0  4051.3     .07       0  4339.2    .045       0
  4873.8     .07       0  5028.6     .07       0  5032.6     .07       0
  5095.5    .035       0  5609.8     .07       0  5753.6     .16       0
Bank Sta=5028.6,5032.6
XS Rating Curve= 0 ,0
Exp/Cntr=0.3,0.1

Type RM Length L Ch R = 1 ,34206   ,451,451,451
BEGIN DESCRIPTION:
MULBERRY CREEK TRIBUTARY 4 50.0
END DESCRIPTION:
XS GIS Cut Line= 3
      1567103.04      6870004.42      1567805.23       6870758.1
      1568851.54      6870421.57
#Sta/Elev= 30
  3969.9 1731.64  4143.6  1729.4  4165.1    1728  4200.2 1728.36  4230.1 1726.88
  4277.9 1726.52  4327.7 1724.55  4391.3 1725.37  4405.4 1723.57  4433.8 1722.84
  4497.3 1723.37  4561.3 1721.33    4660 1721.72  4695.6 1720.12  4808.5 1720.11
  4872.5 1717.79  4919.6 1717.81  5019.3 1715.91  5019.6 1715.41  5023.3 1715.91
  5060.9 1717.04  5220.4 1718.85  5325.4 1720.84  5356.9 1722.35  5625.1 1724.78
  5732.5 1723.75  5767.4 1725.31  5840.1 1728.32  5913.6 1729.59  6099.1 1735.81
#Mann= 8 ,-1 , 0
  3969.9     .07       0  4230.1    .045       0  4919.6     .07       0
  5019.3     .07       0  5023.3     .07       0  5060.9    .035       0
  5625.1     .07       0  5767.4     .16       0
Bank Sta=5019.3,5023.3
XS Rating Curve= 0 ,0
Exp/Cntr=0.3,0.1

Type RM Length L Ch R = 1 ,33755   ,624,624,624
BEGIN DESCRIPTION:
MULBERRY CREEK TRIBUTARY 4 49.0
END DESCRIPTION:
XS GIS Cut Line= 3
      1566997.75      6871071.46      1567804.51      6871148.17
      1568984.95      6870507.91
#Sta/Elev= 30
  4189.6 1718.06  4277.2 1717.79  4327.5  1718.6  4407.8 1717.14  4679.1 1716.54
  4749.4 1717.11  4789.5 1715.67  4887.8 1714.58  4990.5 1714.18  5003.1  1713.6
  5006.5  1712.4  5006.8  1711.9  5010.5  1712.4  5030.4 1714.05  5077.7  1714.1
  5296.3 1716.06  5308.9 1716.96  5325.1 1716.41  5353.2 1717.95    5376  1718.2
  5428.7 1717.31  5481.4 1717.46  5710.2 1719.26  5796.9 1720.07  5842.4 1722.21
  5908.9  1723.4  6225.4 1731.92  6289.1 1734.65  6312.9 1735.44  6342.9 1737.95
#Mann= 8 ,-1 , 0
  4189.6    .045       0  4887.8     .07       0  5006.5     .07       0
  5010.5     .07       0  5077.7    .035       0  5481.4     .07       0
  5710.2     .16       0  6289.1     .07       0
Bank Sta=5006.5,5010.5
XS Rating Curve= 0 ,0
Exp/Cntr=0.3,0.1

Type RM Length L Ch R = 1 ,33131   ,650,650,650
BEGIN DESCRIPTION:
MULBERRY CREEK TRIBUTARY 4 48.0
END DESCRIPTION:
XS GIS Cut Line= 3
      1567304.41      6871865.45        1568005.        6871638.
      1568904.99      6870888.01
#Sta/Elev= 30
  4258.8 1714.09  4469.7 1714.36  4521.4 1713.03  4723.7 1713.09  4774.6 1711.75
  4921.8 1711.38  4974.5 1710.08  4992.8 1709.28  5080.6 1709.88  5099.5 1708.28
  5099.7 1707.78  5103.5 1708.28  5115.8 1710.43  5130.1 1711.03  5225.3  1710.6
  5329.6 1710.26  5364.4 1711.34  5393.1 1710.34  5529.2 1711.94  5670.3 1713.11
  5946.3 1719.72  5989.2 1719.71  6105.3 1721.95  6131.1 1722.91  6138.9  1724.8
  6145.4 1724.25  6153.3 1727.41  6159.8 1726.36  6163.7 1727.84  6166.9 1727.84
#Mann= 8 ,-1 , 0
  4258.8    .045       0  4974.5     .07       0  5099.5     .07       0
  5103.5     .07       0  5225.3    .035       0  5329.6     .07       0
  5529.2     .16       0  6105.3     .07       0
#XS Ineff= 2 , 0
       0                  5364.4       0 1711.34
Permanent Ineff=
       F       F
Bank Sta=5099.5,5103.5
XS Rating Curve= 0 ,0
Exp/Cntr=0.3,0.1

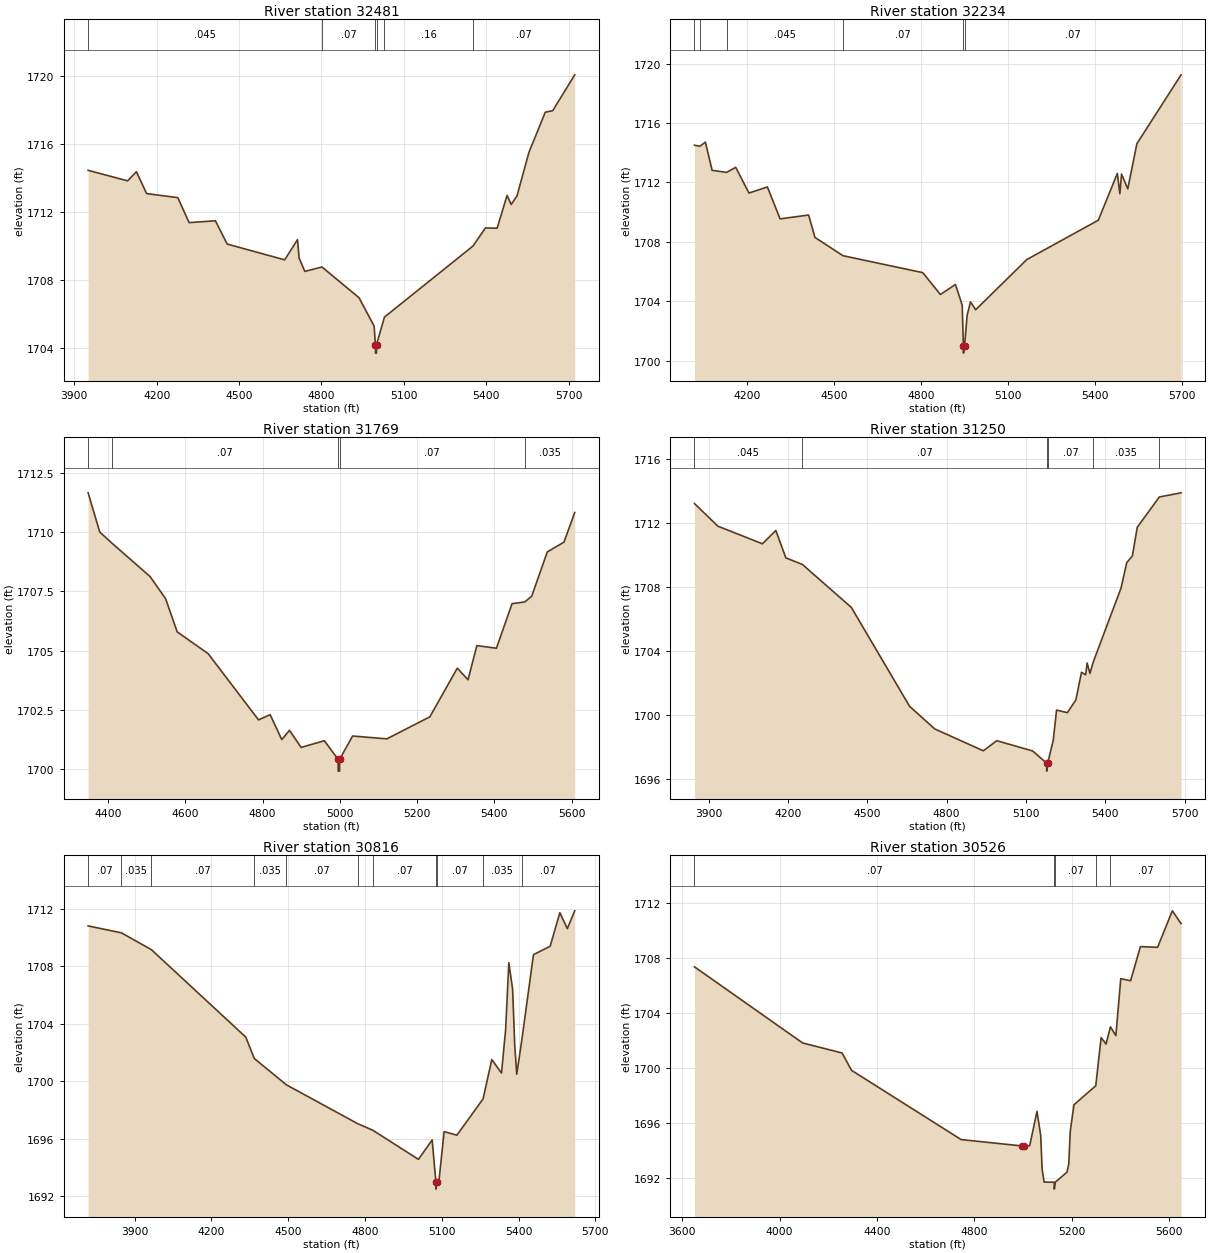
Type RM Length L Ch R = 1 ,32481   ,247,247,247
BEGIN DESCRIPTION:
MULBERRY CREEK TRIBUTARY 4 47.0
END DESCRIPTION:
XS GIS Cut Line= 3
      1567464.14      6872167.53      1568462.77       6871844.4
        1568855.        6871238.
#Sta/Elev= 30
  3950.4 1714.47  4094.1 1713.85  4126.1 1714.39  4163.4  1713.1  4277.1 1712.86
  4318.2 1711.39  4413.8  1711.5  4456.7 1710.13    4666  1709.2  4712.8 1710.39
  4718.6 1709.31  4739.5 1708.52  4801.9 1708.78  4936.8 1706.97  4991.8  1705.3
  4996.5 1704.21  4996.8 1703.71  5000.3 1703.71  5000.5 1704.21  5029.3 1705.83
  5351.5 1710.01  5397.3 1711.08  5439.6 1711.06  5475.8 1712.99    5491 1712.46
  5512.1 1712.97  5555.5 1715.53    5615 1717.89  5642.1 1717.98  5722.2 1720.09
#Mann= 6 ,-1 , 0
  3950.4    .045       0  4801.9     .07       0  4996.5     .07       0
  5000.5     .07       0  5029.3     .16       0  5351.5     .07       0
Bank Sta=4996.5,5000.5
XS Rating Curve= 0 ,0
Exp/Cntr=0.3,0.1

Type RM Length L Ch R = 1 ,32234   ,465,465,465
BEGIN DESCRIPTION:
MULBERRY CREEK TRIBUTARY 4 46.0
END DESCRIPTION:
XS GIS Cut Line= 3
      1567754.95      6872388.02        1568655.        6871988.
      1569005.02      6871387.96
#Sta/Elev= 30
  4018.9  1714.5    4038 1714.43  4056.6 1714.71  4079.8 1712.81  4129.9 1712.67
  4161.2 1713.01    4207 1711.28  4270.6 1711.69  4314.4 1709.54  4412.9  1709.8
  4434.8 1708.29  4531.6 1707.06  4806.9 1705.92  4867.7 1704.45  4919.7 1705.12
    4943 1703.73  4947.1    1701  4947.4  1700.5  4951.1    1701  4960.1 1703.06
  4971.7 1703.95  4989.5 1703.42  5165.9  1706.8  5412.8 1709.45  5478.5  1712.6
  5487.2 1711.23    5493 1712.56  5514.5 1711.56  5545.9  1714.6  5698.5 1719.24
#Mann= 6 ,-1 , 0
  4018.9    .045       0    4038     .07       0  4129.9    .045       0
  4531.6     .07       0  4947.1     .07       0  4951.1     .07       0
Bank Sta=4947.1,4951.1
XS Rating Curve= 0 ,0
Exp/Cntr=0.3,0.1

Type RM Length L Ch R = 1 ,31769   ,519,519,519
BEGIN DESCRIPTION:
MULBERRY CREEK TRIBUTARY 4 45.0
END DESCRIPTION:
XS GIS Cut Line= 3
      1568055.01        6872488.        1568705.        6872438.
      1569305.01        6872338.
#Sta/Elev= 30
    4348 1711.65  4378.1    1710    4411 1709.51  4508.5 1708.12  4548.6 1707.19
  4578.7 1705.79  4658.9 1704.87  4789.3 1702.08  4819.4  1702.3  4849.5 1701.25
  4869.5 1701.64  4899.6 1700.92  4959.8  1701.2  4995.4 1700.42  4995.7 1699.92
  4999.2 1699.92  4999.4 1700.42  5032.9  1701.4  5121.6 1701.28  5233.1 1702.21
  5304.1 1704.26  5331.9 1703.77  5354.7 1705.21  5405.4  1705.1    5446 1706.98
  5478.7 1707.05  5496.7 1707.29  5537.2 1709.16  5580.3 1709.57  5608.2 1710.82
#Mann= 5 ,-1 , 0
    4348    .045       0    4411     .07       0  4995.4     .07       0
  4999.4     .07       0  5478.7    .035       0
Bank Sta=4995.4,4999.4
XS Rating Curve= 0 ,0
Exp/Cntr=0.3,0.1

Type RM Length L Ch R = 1 ,31250   ,434,434,434
BEGIN DESCRIPTION:
MULBERRY CREEK TRIBUTARY 4 44.0
END DESCRIPTION:
XS GIS Cut Line= 3
      1567703.03      6872646.08      1568834.97      6872868.08
      1569477.31      6872625.27
#Sta/Elev= 30
  3846.5 1713.22  3934.8 1711.81  4103.3 1710.71  4154.2 1711.54    4192 1709.83
  4254.6 1709.42  4439.6 1706.74  4660.2 1700.56  4755.5 1699.15  4938.9 1697.79
  4989.8 1698.42  5125.2 1697.78  5178.2 1697.02  5178.5 1696.52  5182.2 1697.02
  5203.2 1698.43  5215.8 1700.33  5256.6 1700.17  5288.7 1700.96  5310.1 1702.69
  5325.8 1702.53  5331.4 1703.27  5342.1 1702.62  5354.5 1703.33  5459.7 1707.95
  5481.1 1709.53  5502.5 1709.95    5521 1711.74  5604.4 1713.63  5686.7 1713.89
#Mann= 6 ,-1 , 0
  3846.5    .045       0  4254.6     .07       0  5178.2     .07       0
  5182.2     .07       0  5354.5    .035       0  5604.4     .07       0
Bank Sta=5178.2,5182.2
XS Rating Curve= 0 ,0
Exp/Cntr=0.3,0.1

Type RM Length L Ch R = 1 ,30816   ,290,290,290
BEGIN DESCRIPTION:
Mapping XS ccfceae5
END DESCRIPTION:
XS GIS Cut Line= 4
      1567824.57      6872899.56      1568935.68      6873107.89
      1569324.57      6873135.67       1569508.4       6872802.7
#Sta/Elev= 30
  3718.8 1710.79  3848.9 1710.31  3965.9 1709.14  4334.6 1703.06  4367.9 1701.57
  4493.5 1699.74  4771.9 1697.04  4831.2 1696.58    5009 1694.56  5062.7 1695.91
  5077.2 1692.99  5077.4 1692.49  5081.2 1692.99  5089.2 1693.07  5109.3 1696.49
  5159.4 1696.24  5261.7 1698.77  5295.5  1701.5  5333.4 1700.56  5349.4 1703.53
  5362.1 1708.23  5376.9 1706.39    5385 1702.55    5393 1700.48  5412.3 1702.79
  5458.3 1708.79  5523.6 1709.38  5561.4 1711.71  5590.6  1710.6  5619.5 1711.84
#Mann= 11 ,-1 , 0
  3718.8     .07       0  3848.9    .035       0  3965.9     .07       0
  4367.9    .035       0  4493.5     .07       0  4771.9    .035       0
  4831.2     .07       0  5077.2     .07       0  5081.2     .07       0
  5261.7    .035       0  5412.3     .07       0
Bank Sta=5077.2,5081.2
XS Rating Curve= 0 ,0
Exp/Cntr=0.3,0.1

Type RM Length L Ch R = 1 ,30526   ,487,487,487
BEGIN DESCRIPTION:
Mapping XS f9d4fea2
END DESCRIPTION:
XS GIS Cut Line= 4
      1567994.03      6873839.14       1569233.6      6873328.73
      1569504.43      6873158.59      1569549.49      6872822.37
#Sta/Elev= 30
  3650.2 1707.36  4094.6 1701.83  4256.9  1701.1  4295.7 1699.84    4746 1694.81
  4994.5 1694.35  5005.8 1694.31  5027.8 1694.37  5057.6 1696.86  5072.9 1695.12
  5078.8 1692.66  5086.9 1691.72  5128.6 1691.71  5128.9 1691.21  5132.6 1691.71
  5181.3 1692.45  5188.4 1693.05  5194.3 1695.39  5209.6 1697.34  5299.2 1698.72
  5321.3 1702.22  5341.4 1701.75  5359.6    1703  5381.8 1702.36    5402  1706.5
  5442.3 1706.35  5482.7 1708.83  5553.3 1708.78  5613.9 1711.43  5649.8  1710.5
#Mann= 5 ,-1 , 0
  3650.2     .07       0  5128.6     .07       0  5132.6     .07       0
  5299.2    .035       0  5359.6     .07       0
#XS Ineff= 2 , 0
       0                  5057.6       0 1696.86
Permanent Ineff=
       F       F
Bank Sta=4994.5,5005.8
XS Rating Curve= 0 ,0
Exp/Cntr=0.3,0.1

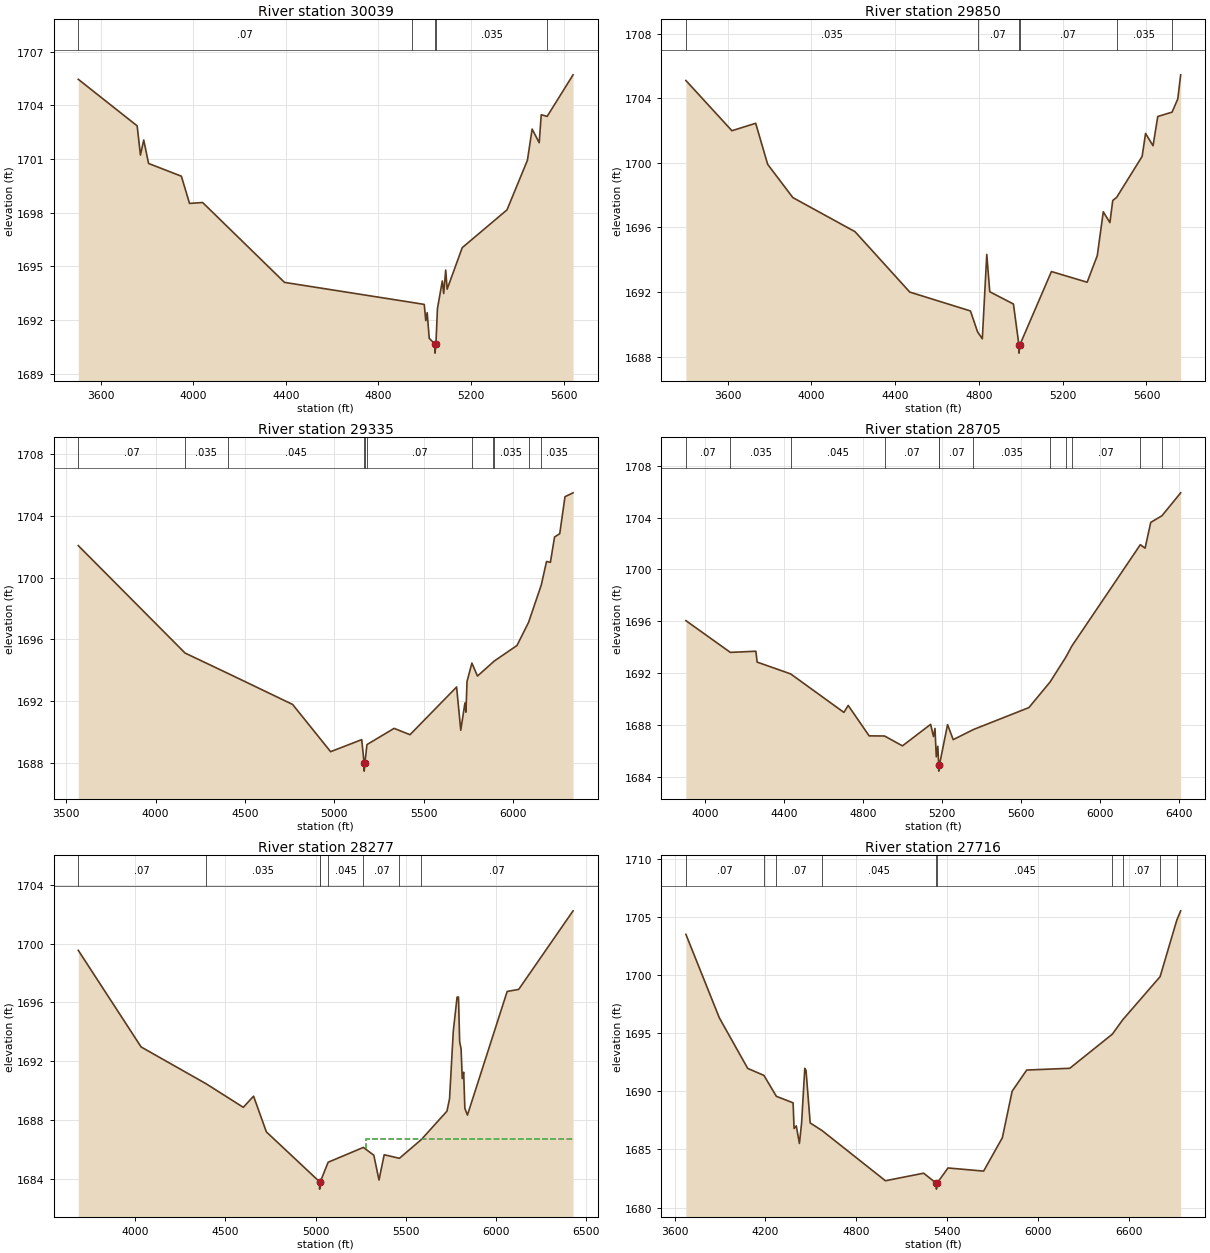
Type RM Length L Ch R = 1 ,30039   ,189,189,189
BEGIN DESCRIPTION:
Mapping XS 0580722c
END DESCRIPTION:
XS GIS Cut Line= 5
      1568455.85      6874568.27       1569358.6      6873585.67
      1569487.07      6873488.45      1569723.18      6873321.78
      1569653.73      6872974.52
#Sta/Elev= 30
  3502.6 1705.45  3757.1 1702.85  3771.3 1701.22  3785.5 1702.06  3806.4 1700.75
  3948.2 1700.04  3983.4 1698.52  4040.1 1698.57    4394 1694.11  4945.6 1692.99
    4998 1692.88  5004.6 1691.97  5010.7 1692.42  5019.4 1690.99  5044.4 1690.66
  5044.6 1690.16  5048.4 1690.66  5055.1 1692.65    5076 1694.19  5082.1 1693.49
  5090.8  1694.8  5096.9 1693.73  5162.2 1696.05  5355.7 1698.16  5443.9 1700.93
  5464.3 1702.67  5494.9 1701.91  5503.6 1703.47  5529.3 1703.38  5641.2  1705.7
#Mann= 5 ,-1 , 0
  3502.6     .07       0  4945.6    .035       0  5044.4    .035       0
  5048.4    .035       0  5529.3     .07       0
Bank Sta=5044.4,5048.4
XS Rating Curve= 0 ,0
Exp/Cntr=0.3,0.1

Type RM Length L Ch R = 1 ,29850   ,515,515,515
BEGIN DESCRIPTION:
Mapping XS 4c56f905
END DESCRIPTION:
XS GIS Cut Line= 5
      1568553.02      6874745.42      1568799.57      6874439.84
      1569643.32      6873575.25      1569914.15        6873419.
      1569703.23      6873021.36
#Sta/Elev= 30
    3400  1705.1  3619.8 1701.99  3733.4 1702.45  3790.6 1699.91  3910.9 1697.85
  4207.9 1695.74  4469.5    1692  4759.4 1690.83  4793.1 1689.54    4816 1689.11
  4837.3 1694.33  4851.5 1692.02  4964.6 1691.26  4990.9 1688.72  4991.2 1688.22
  4994.9 1688.72  5146.1 1693.27  5316.8 1692.61  5365.2 1694.26  5393.8 1696.97
  5425.5  1696.3    5439 1697.67  5457.5 1697.86  5579.4  1700.4  5595.8 1701.82
  5631.5 1701.06  5654.1 1702.87  5722.4 1703.14  5749.7 1703.96  5763.5 1705.45
#Mann= 6 ,-1 , 0
    3400    .035       0  4793.1     .07       0  4990.9     .07       0
  4994.9     .07       0  5457.5    .035       0  5722.4     .07       0
#XS Ineff= 2 , 0
       0  4837.3 1694.33               0
Permanent Ineff=
       F       F
Bank Sta=4990.9,4994.9
XS Rating Curve= 0 ,0
Exp/Cntr=0.3,0.1

Type RM Length L Ch R = 1 ,29335   ,630,630,630
BEGIN DESCRIPTION:
MULBERRY CREEK TRIBUTARY 4 39.0
END DESCRIPTION:
XS GIS Cut Line= 3
      1568822.83      6874981.16       1569868.2      6874001.73
      1571013.78      6873314.51
#Sta/Elev= 30
  3567.5 1702.08    4165 1695.12  4403.3 1693.81  4766.8 1691.79  4979.3 1688.73
  5153.4 1689.51  5166.9 1687.97  5167.2 1687.47  5170.9 1687.97  5182.7 1689.19
  5334.5 1690.24  5423.6 1689.83  5684.3 1692.92  5707.6 1690.12  5730.7 1691.88
  5736.5 1691.29  5742.6 1693.28  5769.9 1694.47  5800.9 1693.63  5887.3 1694.52
  5892.1 1694.58  6022.2 1695.61    6087 1697.11  6157.8 1699.52  6187.4 1701.05
  6209.1    1701  6232.4 1702.64  6261.3 1702.85  6290.7 1705.25  6335.9  1705.5
#Mann= 11 ,-1 , 0
  3567.5     .07       0    4165    .035       0  4403.3    .045       0
  5166.9    .045       0  5170.9    .045       0  5182.7     .07       0
  5769.9    .035       0  5887.3     .07       0  5892.1    .035       0
    6087     .07       0  6157.8    .035       0
Bank Sta=5166.9,5170.9
XS Rating Curve= 0 ,0
Exp/Cntr=0.3,0.1

Type RM Length L Ch R = 1 ,28705   ,428,428,428
BEGIN DESCRIPTION:
MULBERRY CREEK TRIBUTARY 4 38.0
END DESCRIPTION:
XS GIS Cut Line= 3
        1569455.        6875138.      1570278.39      6874411.31
      1571350.28       6873498.8
#Sta/Elev= 30
  3901.8 1696.05    4127  1693.6  4256.1 1693.69  4262.8 1692.85  4432.5 1691.94
  4702.1 1688.97  4723.7 1689.51    4830 1687.16  4907.8 1687.15  4998.7 1686.39
  5141.4 1688.05  5155.7 1687.11  5163.4 1687.73    5170 1685.54  5177.7 1686.36
  5182.2 1684.94  5182.5 1684.44  5186.2 1684.94  5227.1 1688.03  5255.6 1686.87
  5358.1 1687.65  5638.9 1689.34  5746.5 1691.32  5826.8 1693.25    5857  1694.1
  6203.4 1701.91  6227.5 1701.64  6256.1 1703.63  6312.8 1704.14  6407.7 1705.91
#Mann= 12 ,-1 , 0
  3901.8     .07       0    4127    .035       0  4432.5    .045       0
  4907.8     .07       0  5182.2     .07       0  5186.2     .07       0
  5358.1    .035       0  5746.5     .07       0  5826.8    .035       0
    5857     .07       0  6203.4    .035       0  6312.8     .07       0
Bank Sta=5182.2,5186.2
XS Rating Curve= 0 ,0
Exp/Cntr=0.3,0.1

Type RM Length L Ch R = 1 ,28277   ,561,561,561
BEGIN DESCRIPTION:
MULBERRY CREEK TRIBUTARY 4 37.0
END DESCRIPTION:
XS GIS Cut Line= 3
      1569485.18      6875659.95      1570455.45      6874772.81
      1571362.53      6873671.73
#Sta/Elev= 30
  3685.3 1699.54  4033.5 1692.96  4394.2 1690.45  4599.6 1688.85  4656.4 1689.61
  4727.3 1687.18  5022.3 1683.78  5022.5 1683.28  5026.3 1683.78  5069.6 1685.11
  5264.7 1686.12  5322.7 1685.59  5351.4  1683.9  5380.1 1685.62  5464.6 1685.38
  5586.3 1686.66    5728 1688.59  5742.3 1689.44  5763.1 1694.05  5783.9 1696.35
  5791.8 1696.36  5798.3 1693.31  5806.2 1692.83  5812.6 1690.81  5820.5 1691.24
    5827 1688.79  5841.3 1688.32  6061.5 1696.74  6125.4 1696.88  6426.6 1702.23
#Mann= 8 ,-1 , 0
  3685.3     .07       0  4394.2    .035       0  5022.3    .035       0
  5026.3    .035       0  5069.6    .045       0  5264.7     .07       0
  5464.6    .035       0  5586.3     .07       0
#XS Ineff= 2 , 0
       0                  5279.7       0 1686.66
Permanent Ineff=
       F       F
Bank Sta=5022.3,5026.3
XS Rating Curve= 0 ,0
Exp/Cntr=0.3,0.1

Type RM Length L Ch R = 1 ,27716   ,907,907,907
BEGIN DESCRIPTION:
MULBERRY CREEK TRIBUTARY 4 36.0
END DESCRIPTION:
XS GIS Cut Line= 3
      1569648.33      6876032.56        1570705.        6875238.
      1571676.14      6873548.84
#Sta/Elev= 30
  3674.1  1703.5  3895.5 1696.31  4082.8 1691.97  4189.9 1691.37  4272.3 1689.57
  4382.8 1689.01  4389.1  1686.8  4403.7 1687.03  4424.5 1685.52  4439.1  1687.3
  4459.9 1691.98  4468.2 1691.79  4495.7 1687.28  4574.8 1686.62    4993 1682.31
  5245.6 1682.96  5329.8 1682.09  5330.1 1681.59  5333.8 1682.09  5406.6 1683.41
  5642.1 1683.14  5765.9 1686.01  5830.6 1690.01  5926.9 1691.83  6211.6 1691.98
  6493.3 1694.92  6560.9 1696.14  6808.6 1699.86  6919.3 1704.73  6944.6 1705.52
#Mann= 10 ,-1 , 0
  3674.1     .07       0  4189.9    .045       0  4272.3     .07       0
  4574.8    .045       0  5329.8    .045       0  5333.8    .045       0
  6493.3    .035       0  6560.9     .07       0  6808.6    .035       0
  6919.3     .07       0
Bank Sta=5329.8,5333.8
XS Rating Curve= 0 ,0
Exp/Cntr=0.3,0.1

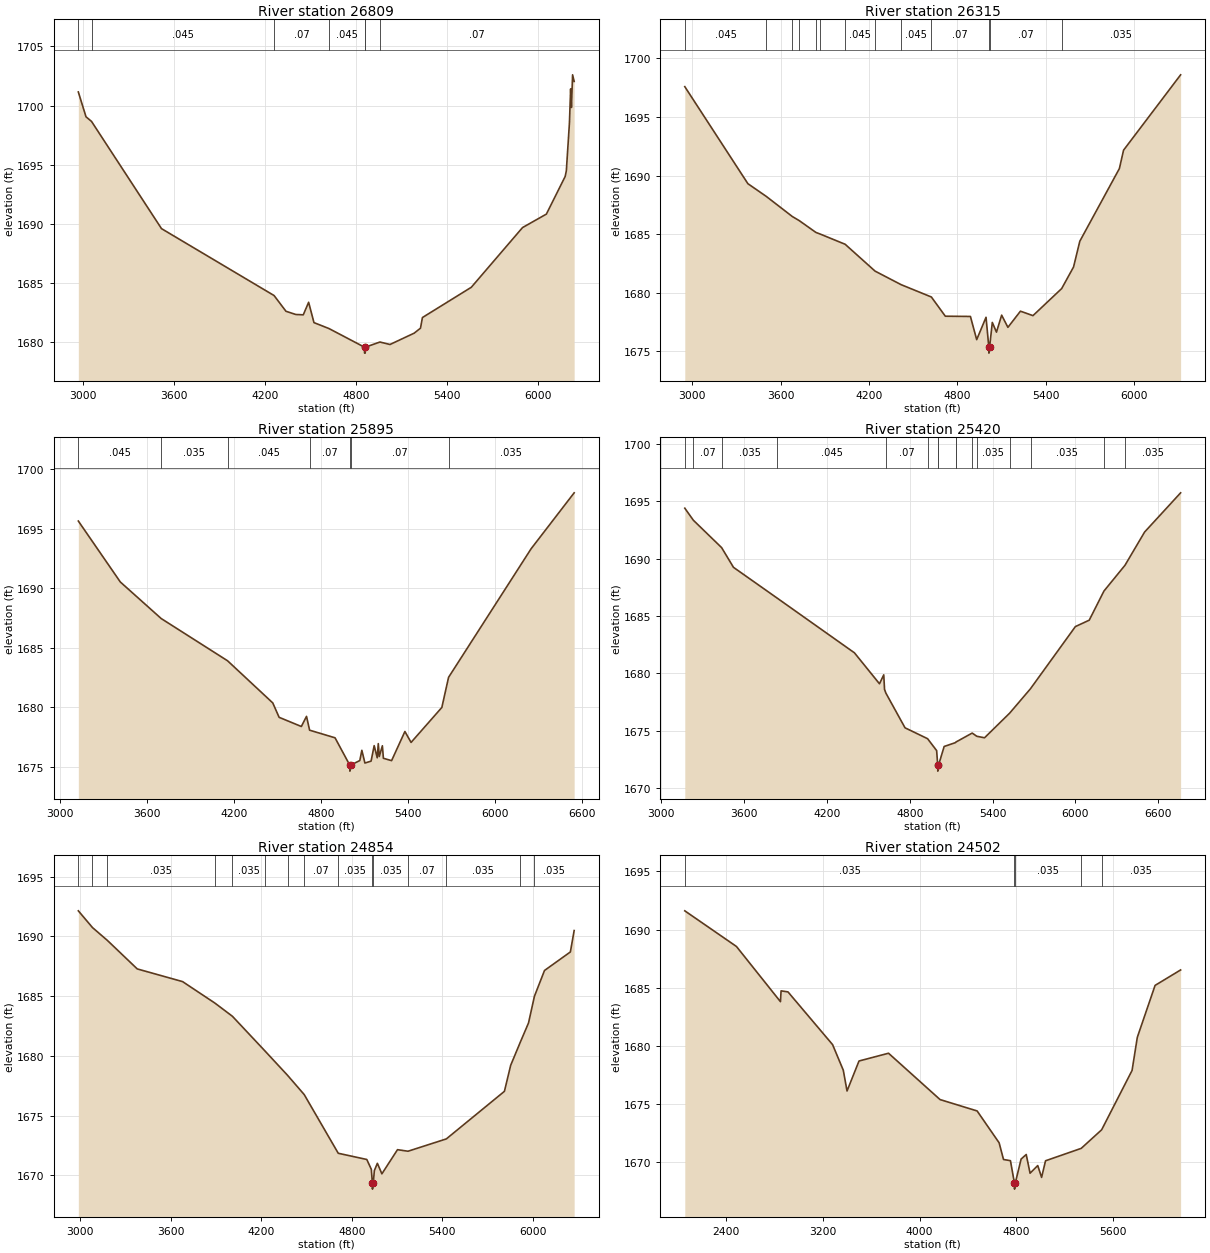
Type RM Length L Ch R = 1 ,26809   ,494,494,494
BEGIN DESCRIPTION:
MULBERRY CREEK TRIBUTARY 4 35.0
END DESCRIPTION:
XS GIS Cut Line= 3
      1569905.02      6876437.99        1571505.        6875188.
        1571805.        6873988.
#Sta/Elev= 30
  2969.2 1701.15  3019.8 1699.05  3056.1 1698.66  3517.3 1689.59  4259.2 1683.93
  4337.5  1682.6  4401.7 1682.33  4451.5  1682.3  4486.8 1683.36    4522 1681.64
  4620.7 1681.14  4855.2 1679.56  4855.5 1679.06  4859.6 1679.06    4860 1679.56
  4956.7    1680  5022.8 1679.79  5182.5 1680.75  5223.8 1681.17  5236.7 1682.07
  5558.8 1684.63  5896.3 1689.68  6053.5 1690.82  6177.2    1694    6185 1694.48
  6205.6 1698.57  6213.3 1701.41  6218.5 1699.84  6226.2  1702.6  6236.5 1702.04
#Mann= 7 ,-1 , 0
  2969.2     .07       0  3056.1    .045       0  4259.2     .07       0
  4620.7    .045       0  4855.2     .07       0    4860    .045       0
  4956.7     .07       0
Bank Sta=4855.2,4860
XS Rating Curve= 0 ,0
Exp/Cntr=0.3,0.1

Type RM Length L Ch R = 1 ,26315   ,420,420,420
BEGIN DESCRIPTION:
MULBERRY CREEK TRIBUTARY 4 34.0
END DESCRIPTION:
XS GIS Cut Line= 3
      1570057.06      6876515.09      1571657.08      6875715.08
      1572828.03      6874653.21
#Sta/Elev= 30
  2948.7 1697.59  3377.5 1689.31  3502.9 1688.22  3679.3 1686.51  3727.4 1686.15
  3839.7 1685.15  3867.1 1685.02  4038.4 1684.14  4241.6 1681.85  4419.3 1680.69
  4624.4 1679.64  4719.2    1678  4889.8 1677.98  4932.4    1676  4995.9 1677.91
    5015 1675.35  5015.4 1674.85    5020 1675.35  5038.5 1677.47  5066.8 1676.64
    5102 1678.09  5144.6 1677.05  5229.7 1678.43  5314.9 1678.05    5510 1680.36
  5590.6  1682.2  5633.2  1684.4  5902.1  1690.6  5930.5 1692.17  6318.3  1698.6
#Mann= 13 ,-1 , 0
  2948.7    .045       0  3502.9     .07       0  3679.3    .045       0
  3727.4     .07       0  3839.7    .045       0  3867.1    .035       0
  4038.4    .045       0  4241.6    .035       0  4419.3    .045       0
  4624.4     .07       0    5015     .07       0    5020     .07       0
    5510    .035       0
Bank Sta=5015,5020
XS Rating Curve= 0 ,0
Exp/Cntr=0.3,0.1

Type RM Length L Ch R = 1 ,25895   ,475,475,475
BEGIN DESCRIPTION:
MULBERRY CREEK TRIBUTARY 4 33.0
END DESCRIPTION:
XS GIS Cut Line= 3
      1570140.51      6876653.22        1571855.        6875888.
      1572920.93       6874773.9
#Sta/Elev= 30
    3127 1695.66  3416.6 1690.54  3698.3 1687.47  4156.2 1683.92  4467.9 1680.38
  4511.7 1679.17    4665  1678.4  4700.6 1679.25    4722 1678.09  4897.3 1677.45
  4999.1 1675.15  4999.6 1674.65  5004.4 1675.15  5068.2 1675.54  5082.3  1676.4
  5103.4 1675.33  5145.9 1675.49  5167.3 1676.79  5188.3 1675.77  5195.6 1676.96
  5202.5 1675.88  5223.9 1676.78  5230.8 1675.73  5287.4 1675.53  5379.2 1677.98
  5421.7 1677.06    5634    1680  5680.3 1682.53  6249.5 1693.33  6546.4 1698.03
#Mann= 7 ,-1 , 0
    3127    .045       0  3698.3    .035       0  4156.2    .045       0
    4722     .07       0  4999.1     .07       0  5004.4     .07       0
  5680.3    .035       0
Bank Sta=4999.1,5004.4
XS Rating Curve= 0 ,0
Exp/Cntr=0.3,0.1

Type RM Length L Ch R = 1 ,25420   ,566,566,566
BEGIN DESCRIPTION:
MULBERRY CREEK TRIBUTARY 4 32.0
END DESCRIPTION:
XS GIS Cut Line= 3
      1570182.24      6876752.16        1571955.        6876338.
      1573005.11      6874913.65
#Sta/Elev= 30
  3171.3 1694.41  3233.2 1693.36  3437.9 1690.97  3523.8 1689.25  3841.8 1686.55
  4399.8 1681.79    4581 1679.09  4611.8 1679.87  4617.6  1678.6  4627.6 1678.27
  4765.9 1675.25  4929.2  1674.3  4994.9 1673.26  5002.6 1671.97  5003.1 1671.47
    5008 1671.97  5049.2 1673.62    5132 1673.96  5133.4    1674  5252.1 1674.79
  5285.8 1674.51  5341.6 1674.38  5522.9 1676.52  5674.4 1678.66  5999.4 1684.08
  6099.7 1684.64  6206.2 1687.18  6358.6 1689.43  6500.7 1692.33  6761.4 1695.75
#Mann= 16 ,-1 , 0
  3171.3    .045       0  3233.2     .07       0  3437.9    .035       0
  3841.8    .045       0  4627.6     .07       0  4929.2    .035       0
  5002.6    .035       0    5008    .035       0    5132     .07       0
  5133.4    .035       0  5252.1     .07       0  5285.8    .035       0
  5522.9     .07       0  5674.4    .035       0  6206.2     .07       0
  6358.6    .035       0
Bank Sta=5002.6,5008
XS Rating Curve= 0 ,0
Exp/Cntr=0.3,0.1

Type RM Length L Ch R = 1 ,24854   ,352,352,352
BEGIN DESCRIPTION:
MULBERRY CREEK TRIBUTARY 4 31.0
END DESCRIPTION:
XS GIS Cut Line= 3
      1570244.73      6876851.12        1572255.        6876763.
      1573479.08      6876408.42
#Sta/Elev= 30
  2987.8 1692.14  3081.6 1690.74  3180.8 1689.66  3378.4 1687.28  3678.7 1686.22
  3893.3 1684.42    4009 1683.32    4227 1680.39  4374.7 1678.38    4485 1676.77
  4710.7 1671.86  4899.9 1671.34  4929.9 1670.52  4936.9 1669.36  4937.4 1668.86
  4942.9 1669.36    4950 1670.41    4970 1671.02    5000 1670.14  5103.4 1672.16
  5173.1 1672.03    5427 1673.06  5812.1 1677.04  5853.7 1679.22  5917.7 1681.16
  5971.9 1682.76    6011 1684.99  6077.9 1687.15  6249.3  1688.7  6274.4 1690.49
#Mann= 15 ,-1 , 0
  2987.8    .035       0  3081.6     .07       0  3180.8    .035       0
  3893.3     .07       0    4009    .035       0    4227     .07       0
  4374.7    .035       0    4485     .07       0  4710.7    .035       0
  4936.9    .035       0  4942.9    .035       0  5173.1     .07       0
    5427    .035       0  5917.7     .07       0    6011    .035       0
Bank Sta=4936.9,4942.9
XS Rating Curve= 0 ,0
Exp/Cntr=0.3,0.1

Type RM Length L Ch R = 1 ,24502   ,949,949,949
BEGIN DESCRIPTION:
Mapping XS 306d8f3e
END DESCRIPTION:
XS GIS Cut Line= 3
      1569622.42      6878021.14      1572405.08      6877062.98
      1573475.25        6876611.
#Sta/Elev= 30
    2057 1691.61  2484.7 1688.54  2848.8 1683.79  2854.1 1684.72  2911.2 1684.63
  3280.6 1680.09    3369 1677.89  3400.2  1676.1  3499.1 1678.68  3743.6 1679.35
  4170.2 1675.36  4477.1 1674.38  4659.1 1671.64  4695.6  1670.2  4752.8  1670.1
  4786.3 1668.15  4786.8 1667.65  4792.4 1668.15  4841.2 1670.24  4883.6 1670.63
  4915.3 1669.02  4978.8 1669.68  5010.8 1668.66  5043.3 1670.09  5338.9 1671.16
    5508 1672.76  5759.8 1677.87  5803.2 1680.72  5950.3 1685.19  6161.7 1686.52
#Mann= 5 ,-1 , 0
    2057    .035       0  4786.3    .035       0  4792.4    .035       0
  5338.9     .07       0    5508    .035       0
Bank Sta=4786.3,4792.4
XS Rating Curve= 0 ,0
Exp/Cntr=0.3,0.1