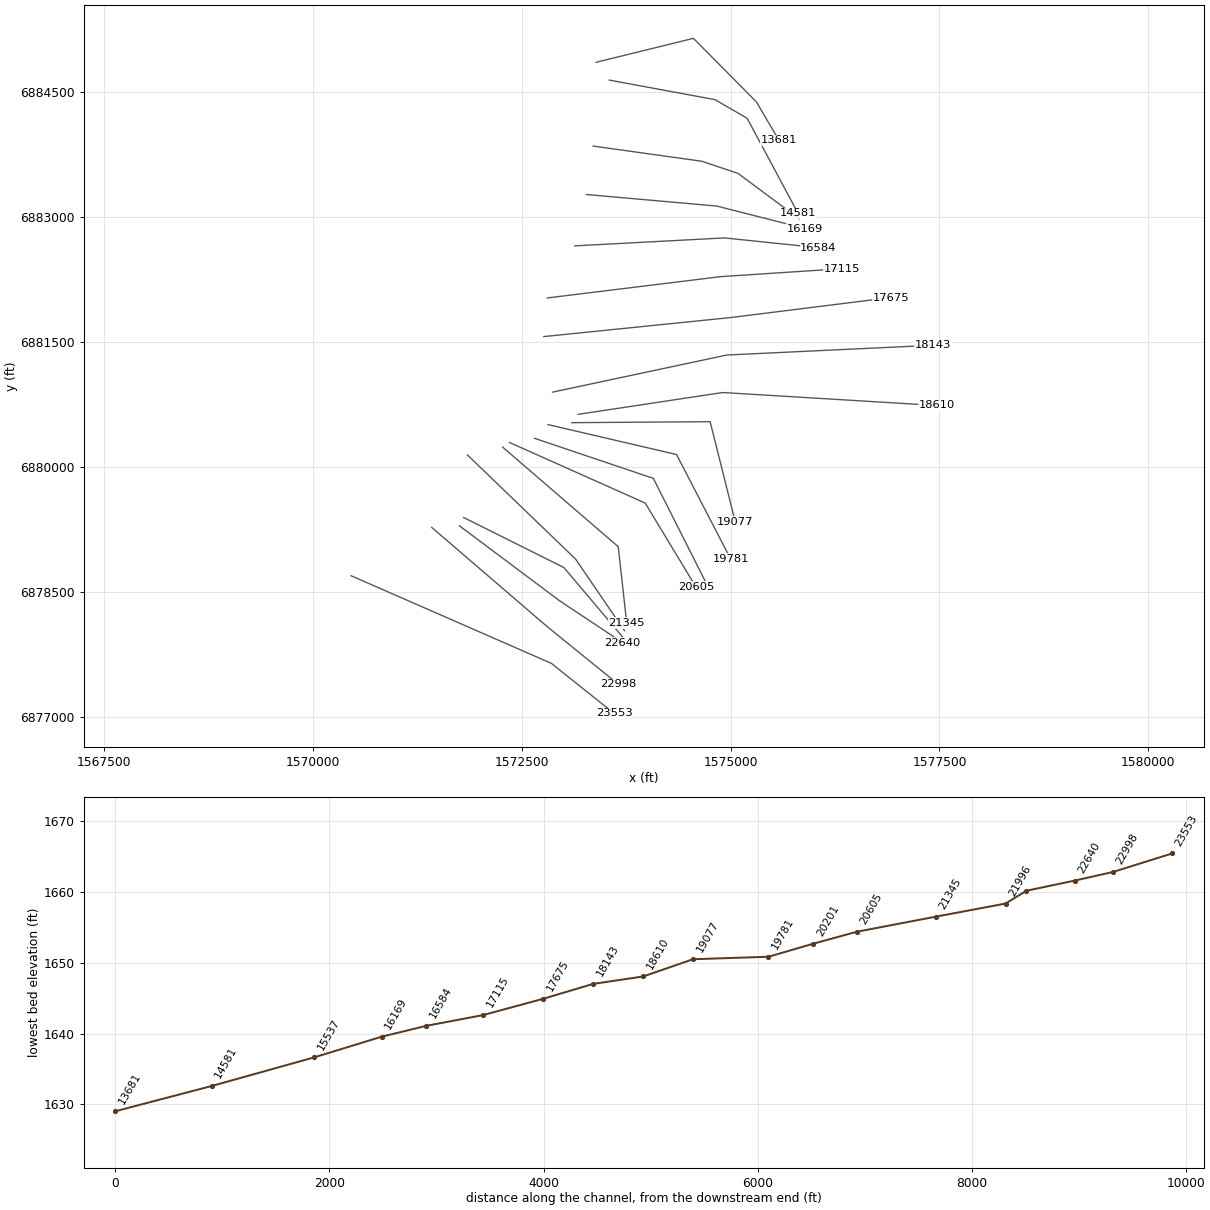
HEC-RAS study MULBERRY CREEK TRIBUTARY 4.prj: MULBERRY CREEK TRIBUTARY 4 Base Level Engineering

--- MULBERRY CREEK TRIBUTARY 4.g01 (geometry) --- (continued)

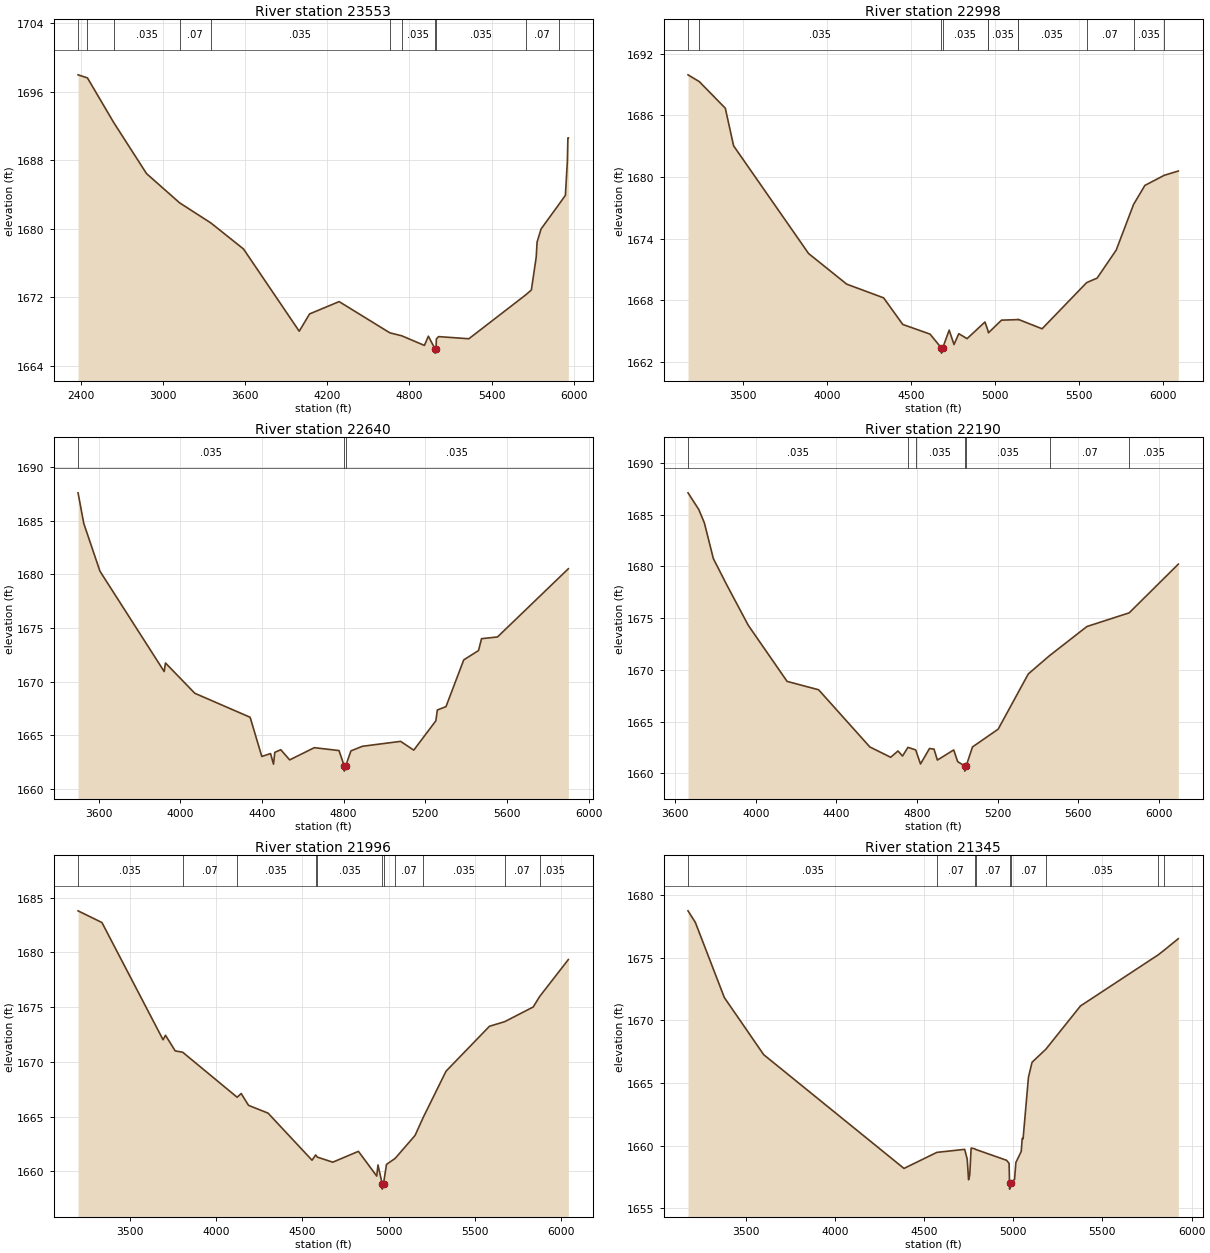
Type RM Length L Ch R = 1 ,23553   ,555,555,555
BEGIN DESCRIPTION:
MULBERRY CREEK TRIBUTARY 4 30.0
END DESCRIPTION:
XS GIS Cut Line= 3
      1570457.47      6878689.55        1572855.        6877638.
      1573605.03      6877037.98
#Sta/Elev= 30
  2381.9    1698  2450.5 1697.64  2641.7 1692.44  2881.5 1686.46  3123.3 1683.04
  3351.4 1680.69  3589.5 1677.65  3996.2 1668.04  4071.7 1670.06  4287.5  1671.5
  4657.8 1667.85  4743.6 1667.51  4909.9 1666.38  4938.7 1667.46  4987.2 1665.98
  4987.7 1665.48  4994.7 1665.98  4997.2 1667.13  5013.5 1667.41  5234.4 1667.16
  5650.5  1672.3  5690.6 1672.86  5725.9 1676.71  5732.3 1678.46  5761.1 1679.98
  5888.8  1682.8  5938.8 1683.92  5953.2 1687.87  5957.2 1690.63  5960.4 1690.63
#Mann= 11 ,-1 , 0
  2381.9    .035       0  2450.5     .07       0  2641.7    .035       0
  3123.3     .07       0  3351.4    .035       0  4657.8     .07       0
  4743.6    .035       0  4987.2    .035       0  4994.7    .035       0
  5650.5     .07       0  5888.8    .035       0
Bank Sta=4987.2,4994.7
XS Rating Curve= 0 ,0
Exp/Cntr=0.3,0.1

Type RM Length L Ch R = 1 ,22998   ,358,358,358
BEGIN DESCRIPTION:
MULBERRY CREEK TRIBUTARY 4 29.0
END DESCRIPTION:
XS GIS Cut Line= 3
      1571423.07      6879269.11      1572806.71      6878077.25
        1573655.        6877388.
#Sta/Elev= 30
  3173.8 1689.93    3241 1689.27  3395.9 1686.68  3445.3 1683.02  3891.8 1672.54
  4118.9 1669.56  4338.4 1668.23  4452.5 1665.64    4615  1664.7  4682.4 1663.35
  4682.9 1662.85    4690 1663.35  4728.9 1665.09  4757.5 1663.69    4786 1664.74
  4835.4 1664.26  4941.8 1665.88  4958.1 1665.12  4962.6 1664.83  5040.7 1666.06
  5138.4 1666.11  5139.3 1666.14    5282 1665.22  5547.2 1669.71  5609.6 1670.15
  5723.1 1672.87  5826.7 1677.32    5894 1679.17  6010.2 1680.16    6093 1680.57
#Mann= 11 ,-1 , 0
  3173.8     .07       0    3241    .035       0  4682.4    .035       0
    4690    .035       0  4958.1     .07       0  4962.6    .035       0
  5138.4     .07       0  5139.3    .035       0  5547.2     .07       0
  5826.7    .035       0  6010.2     .07       0
Bank Sta=4682.4,4690
XS Rating Curve= 0 ,0
Exp/Cntr=0.3,0.1

Type RM Length L Ch R = 1 ,22640   ,450,450,450
BEGIN DESCRIPTION:
MULBERRY CREEK TRIBUTARY 4 28.0
END DESCRIPTION:
XS GIS Cut Line= 3
      1571754.97      6879288.03        1572955.        6878388.
      1573704.98      6877888.02
#Sta/Elev= 30
    3499 1687.62  3527.2 1684.75  3606.3  1680.3  3920.9 1670.93  3927.2 1671.73
  4070.9  1668.9  4341.8 1666.66    4399    1663  4441.8 1663.27  4456.3 1662.28
  4462.6 1663.38  4491.8 1663.63  4535.5 1662.68  4656.3 1663.82  4777.2 1663.55
  4802.5 1662.13    4803 1661.63  4810.1 1662.13  4835.5 1663.52  4891.8 1663.95
  5078.7 1664.41  5143.3 1663.59  5251.4 1666.33  5258.9 1667.34    5301 1667.65
  5388.1 1672.02  5460.3 1672.89  5475.3    1674  5553.4 1674.16  5900.4 1680.53
#Mann= 3 ,-1 , 0
    3499    .035       0  4802.5    .035       0  4810.1    .035       0
Bank Sta=4802.5,4810.1
XS Rating Curve= 0 ,0
Exp/Cntr=0.3,0.1

Type RM Length L Ch R = 1 ,22190   ,194,194,194
BEGIN DESCRIPTION:
MULBERRY CREEK TRIBUTARY 4 27.0
END DESCRIPTION:
XS GIS Cut Line= 3
      1571804.98      6879388.01        1573005.        6878788.
      1573708.89      6877952.17
#Sta/Elev= 30
  3663.2 1687.12  3716.3 1685.52  3744.3 1684.22    3789 1680.76  3856.1  1678.2
  3962.3 1674.31  4155.2 1668.88  4311.7 1668.07    4566 1662.54  4669.5 1661.54
  4705.8 1662.15  4728.2 1661.66  4755.3  1662.5  4793.8 1662.25  4817.6 1660.89
  4862.3 1662.39  4884.7 1662.33  4901.4 1661.27  4982.5 1662.25  5002.1 1661.12
  5036.8  1660.7  5037.3  1660.2  5044.4  1660.7  5075.7 1662.54  5203.2 1664.26
  5352.7  1669.6  5458.3 1671.37    5644 1674.19  5853.7 1675.51  6097.6 1680.22
#Mann= 7 ,-1 , 0
  3663.2    .035       0  4755.3     .07       0  4793.8    .035       0
  5036.8    .035       0  5044.4    .035       0  5458.3     .07       0
  5853.7    .035       0
Bank Sta=5036.8,5044.4
XS Rating Curve= 0 ,0
Exp/Cntr=0.3,0.1

Type RM Length L Ch R = 1 ,21996   ,651,651,651
BEGIN DESCRIPTION:
MULBERRY CREEK TRIBUTARY 4 26.0
END DESCRIPTION:
XS GIS Cut Line= 3
      1571850.15      6880138.91      1573144.37      6878889.51
      1573730.17      6878029.82
#Sta/Elev= 30
  3201.1  1683.8  3339.5 1682.73  3693.3 1672.03  3707.4 1672.44  3763.8 1671.01
    3807 1670.89  4122.3 1666.78  4145.8 1667.12  4188.2 1666.04  4301.4 1665.33
  4556.1 1661.03  4576.9 1661.51    4587 1661.31  4676.2 1660.85  4824.7 1661.84
  4930.9 1659.58  4937.9  1660.6  4962.3 1658.89  4962.8 1658.39  4969.9 1658.89
  4987.2 1660.65    5037 1661.19  5152.6 1663.29    5200 1664.94  5332.1 1669.16
  5583.5 1673.26  5671.8 1673.68  5836.8 1675.02  5873.8 1675.97  6040.3 1679.35
#Mann= 11 ,-1 , 0
  3201.1    .035       0    3807     .07       0  4122.3    .035       0
  4576.9     .07       0    4587    .035       0  4962.3    .035       0
  4969.9    .035       0    5037     .07       0    5200    .035       0
  5671.8     .07       0  5873.8    .035       0
Bank Sta=4962.3,4969.9
XS Rating Curve= 0 ,0
Exp/Cntr=0.3,0.1

Type RM Length L Ch R = 1 ,21345   ,740,740,740
BEGIN DESCRIPTION:
MULBERRY CREEK TRIBUTARY 4 25.0
END DESCRIPTION:
XS GIS Cut Line= 3
      1572272.08      6880232.61        1573655.        6879038.
      1573756.43      6878123.25
#Sta/Elev= 30
  3177.5 1678.72  3218.6  1677.8    3381 1671.81  3601.4 1667.26  4387.9 1658.19
  4572.4 1659.47    4728 1659.71  4742.3 1658.93  4749.9 1657.29  4756.5 1657.67
  4764.2 1659.81  4783.9 1659.76  4790.4  1659.7  4962.7 1658.84    4977 1658.59
  4979.4 1657.04  4979.9 1656.54  4987.7 1657.04  5007.5 1657.31    5015 1658.66
  5045.2 1659.55  5050.3 1660.58  5055.3 1660.54  5085.4 1665.45  5105.6 1666.65
  5183.6  1667.7  5377.2 1671.14  5812.5 1675.21  5843.2 1675.55  5925.3  1676.5
#Mann= 9 ,-1 , 0
  3177.5    .035       0  4572.4     .07       0  4783.9    .035       0
  4790.4     .07       0  4979.4     .07       0  4987.7     .07       0
  5183.6    .035       0  5812.5     .07       0  5843.2    .035       0
Bank Sta=4979.4,4987.7
XS Rating Curve= 0 ,0
Exp/Cntr=0.3,0.1

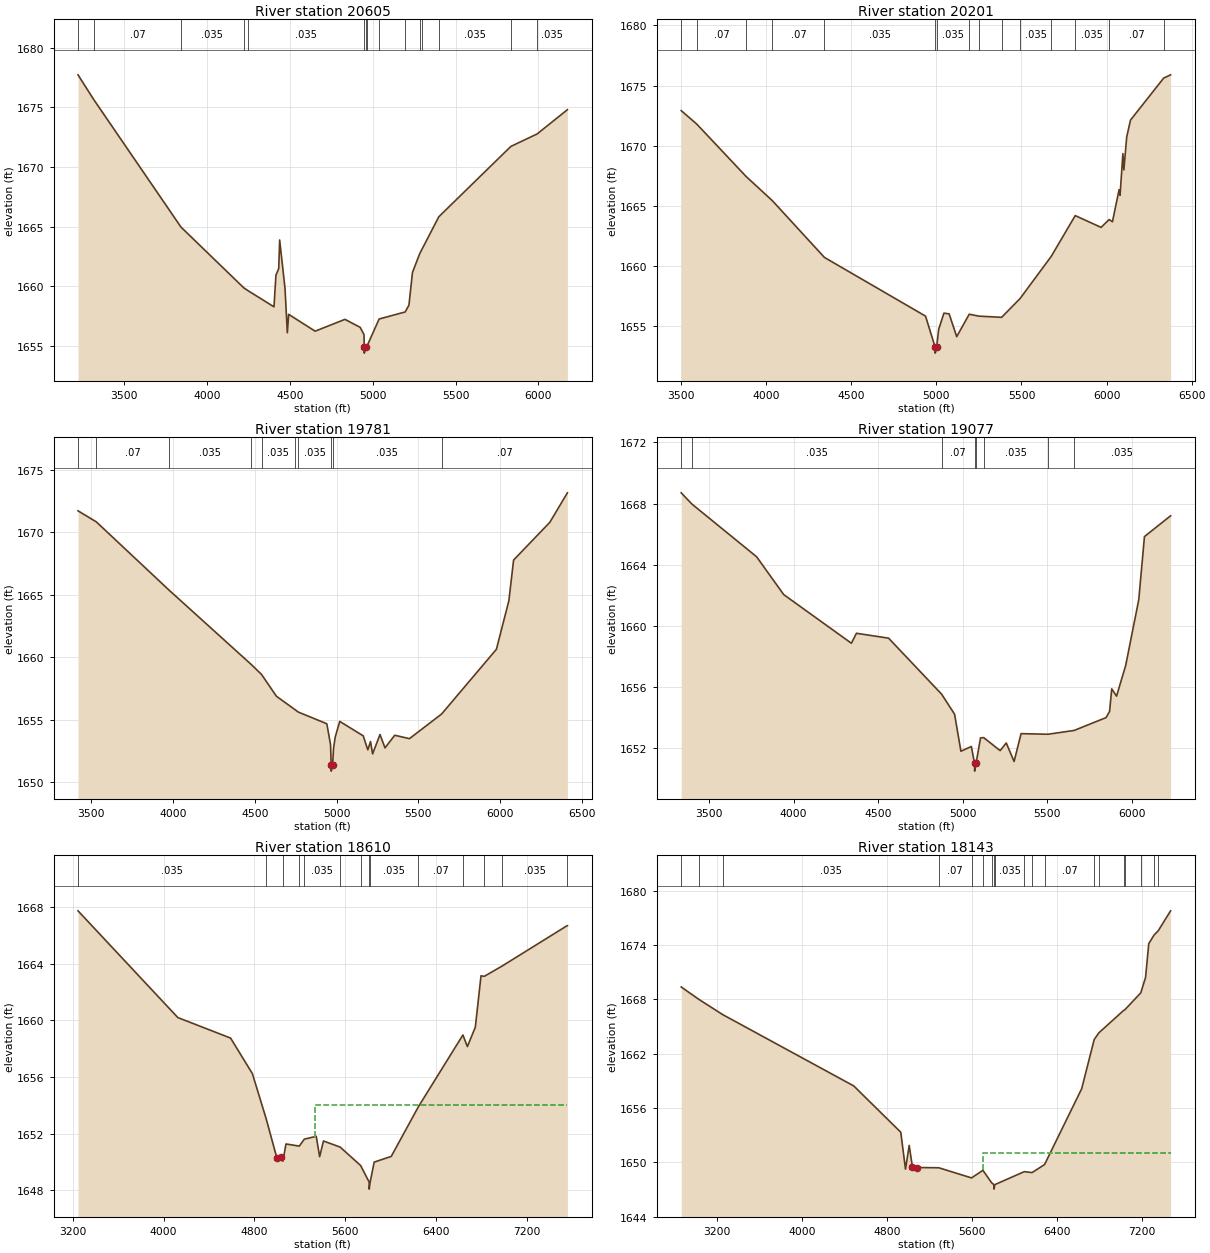
Type RM Length L Ch R = 1 ,20605   ,404,404,404
BEGIN DESCRIPTION:
MULBERRY CREEK TRIBUTARY 4 24.0
END DESCRIPTION:
XS GIS Cut Line= 3
      1572355.01        6880288.      1573978.01      6879561.47
      1574584.53      6878555.58
#Sta/Elev= 30
  3221.8 1677.72  3316.1 1675.66  3843.2 1664.96  4222.1 1659.87    4248 1659.63
  4404.2 1658.28    4416 1660.93  4432.9 1661.49  4438.4 1663.88  4470.8 1659.82
  4484.8 1656.11  4492.7 1657.65  4652.6 1656.24  4832.4 1657.23  4924.2 1656.56
  4947.3 1655.95  4948.6  1654.9  4949.1  1654.4  4957.1  1654.9  4963.6 1654.93
  5038.7 1657.26  5195.8 1657.85  5218.5 1658.42  5239.8 1661.16  5283.9 1662.75
  5295.6 1663.06  5398.9 1665.83  5833.4 1671.72  5992.3 1672.77  6174.6  1674.8
#Mann= 15 ,-1 , 0
  3221.8    .035       0  3316.1     .07       0  3843.2    .035       0
  4222.1     .07       0    4248    .035       0  4948.6     .07       0
  4957.1    .035       0  4963.6     .07       0  5038.7    .035       0
  5195.8     .07       0  5283.9    .035       0  5295.6     .07       0
  5398.9    .035       0  5833.4     .07       0  5992.3    .035       0
Bank Sta=4948.6,4957.1
XS Rating Curve= 0 ,0
Exp/Cntr=0.3,0.1

Type RM Length L Ch R = 1 ,20201   ,420,420,420
BEGIN DESCRIPTION:
MULBERRY CREEK TRIBUTARY 4 23.0
END DESCRIPTION:
XS GIS Cut Line= 3
      1572654.99        6880338.      1574075.22      6879857.84
      1574693.93      6878628.46
#Sta/Elev= 30
  3500.8 1672.91  3592.2 1671.79  3881.9 1667.43  4037.2  1665.4  4342.2 1660.69
  4936.4  1655.8  4992.9 1653.22  4993.4 1652.72  5001.6 1653.22  5013.6  1654.7
  5044.6 1656.05    5075 1655.99  5119.6 1654.09  5193.1 1655.96    5250  1655.8
  5383.5  1655.7  5491.6 1657.26  5675.2 1660.78    5816 1664.17  5967.7 1663.19
  6015.2 1663.84  6034.6 1663.66  6073.7 1666.33  6079.3 1665.86    6096 1669.33
  6101.6 1667.97  6118.3 1670.71  6140.6 1672.12  6335.7 1675.62  6376.3 1675.89
#Mann= 15 ,-1 , 0
  3500.8    .035       0  3592.2     .07       0  3881.9    .035       0
  4037.2     .07       0  4342.2    .035       0  4992.9    .035       0
  5001.6    .035       0  5193.1     .07       0    5250    .035       0
  5383.5     .07       0  5491.6    .035       0  5675.2     .07       0
    5816    .035       0  6015.2     .07       0  6335.7    .035       0
Bank Sta=4992.9,5001.6
XS Rating Curve= 0 ,0
Exp/Cntr=0.3,0.1

Type RM Length L Ch R = 1 ,19781   ,704,704,704
BEGIN DESCRIPTION:
MULBERRY CREEK TRIBUTARY 4 21.0
END DESCRIPTION:
XS GIS Cut Line= 3
      1572813.73      6880503.46      1574352.81      6880143.99
      1575000.62      6878890.04
#Sta/Elev= 30
  3419.5  1671.7  3531.2 1670.82  3977.3 1665.34    4479  1659.4  4541.4 1658.61
  4632.6 1656.86  4746.1 1655.79  4765.7  1655.6  4940.6 1654.66  4963.3    1653
  4967.1 1651.37  4967.6 1650.87  4975.8 1651.37  4981.7  1652.7    4992  1653.6
  5019.6 1654.85  5163.4 1653.69  5191.2 1652.57  5207.7 1653.24  5220.6 1652.25
  5265.6  1653.8  5296.3 1652.73  5355.7 1653.74  5445.7 1653.47  5642.3 1655.44
  5977.3 1660.62  6053.5  1664.5  6082.4 1667.76  6303.9 1670.78  6411.4 1673.14
#Mann= 10 ,-1 , 0
  3419.5    .035       0  3531.2     .07       0  3977.3    .035       0
    4479     .07       0  4541.4    .035       0  4746.1     .07       0
  4765.7    .035       0  4967.1    .035       0  4975.8    .035       0
  5642.3     .07       0
Bank Sta=4967.1,4975.8
XS Rating Curve= 0 ,0
Exp/Cntr=0.3,0.1

Type RM Length L Ch R = 1 ,19077   ,467,467,467
BEGIN DESCRIPTION:
MULBERRY CREEK TRIBUTARY 4 20.0
END DESCRIPTION:
XS GIS Cut Line= 3
      1573099.17      6880526.18        1574755.        6880538.
        1575055.      6879338.01
#Sta/Elev= 30
  3335.9 1668.71  3398.8 1667.98  3781.7 1664.53  3941.7 1662.06  4341.8 1658.88
  4371.8 1659.53  4561.8 1659.21  4875.2 1655.55  4951.8 1654.24  4989.3 1651.82
    5051 1652.13  5069.8 1651.02  5070.3 1650.52  5078.6 1651.02  5105.2 1652.69
  5124.1 1652.71  5221.1 1651.86  5257.2 1652.36  5303.6 1651.15  5344.8 1652.97
  5503.6 1652.93    5659 1653.18  5847.3 1654.02  5867.9 1654.42  5880.8  1655.9
  5909.2 1655.42  5963.3 1657.43  6040.6 1661.73  6074.1 1665.85  6228.7 1667.21
#Mann= 8 ,-1 , 0
  3335.9     .07       0  3398.8    .035       0  4875.2     .07       0
  5069.8     .07       0  5078.6     .07       0  5124.1    .035       0
  5503.6     .07       0    5659    .035       0
Bank Sta=5069.8,5078.6
XS Rating Curve= 0 ,0
Exp/Cntr=0.3,0.1

Type RM Length L Ch R = 1 ,18610   ,467,467,467
BEGIN DESCRIPTION:
MULBERRY CREEK TRIBUTARY 4 19.0
END DESCRIPTION:
XS GIS Cut Line= 3
      1573174.85      6880625.95        1574905.        6880888.
      1577465.41       6880732.6
#Sta/Elev= 30
  3245.4 1667.74  4125.5  1660.2  4590.7 1658.75  4782.9 1656.24  4904.1 1653.06
  4997.8 1650.31  5035.4 1650.38  5051.6 1650.05  5079.1 1651.27  5196.3 1651.12
  5240.9 1651.61  5345.9 1651.81    5376 1650.37  5409.5 1651.48  5556.6 1651.05
  5737.1 1649.75  5812.3 1648.58  5812.8 1648.08  5821.2 1648.58  5856.9 1649.99
  6007.1 1650.39  6245.8 1653.89    6639 1658.97  6678.4 1658.15  6748.5 1659.52
  6798.6 1663.15  6827.2 1663.11  6982.7 1663.83  7557.6 1666.69  7560.4 1666.69
#Mann= 14 ,-1 , 0
  3245.4    .035       0  4904.1     .07       0  5051.6    .035       0
  5196.3     .07       0  5240.9    .035       0  5556.6     .07       0
  5737.1    .035       0  5812.3     .07       0  5821.2    .035       0
  6245.8     .07       0    6639    .035       0  6827.2     .07       0
  6982.7    .035       0  7557.6     .07       0
#XS Ineff= 2 , 0
       0                  5335.9       0    1654
Permanent Ineff=
       F       F
Bank Sta=4997.8,5035.4
XS Rating Curve= 0 ,0
Exp/Cntr=0.3,0.1

Type RM Length L Ch R = 1 ,18143   ,468,468,468
BEGIN DESCRIPTION:
MULBERRY CREEK TRIBUTARY 4 18.0
END DESCRIPTION:
XS GIS Cut Line= 3
      1572868.23      6880892.49        1574955.        6881338.
      1577420.12      6881454.99
#Sta/Elev= 30
  2866.2 1669.38  3034.9 1667.99  3257.3 1666.32  4488.7 1658.44  4930.8 1653.32
  4975.2 1649.24    5010 1651.86    5040 1649.49  5080.1 1649.42  5288.8 1649.39
  5596.2 1648.27  5703.2 1649.11  5785.4 1647.73  5806.5 1647.53    5807 1647.03
  5815.4 1647.53  6091.6 1648.96  6165.8 1648.86  6282.9 1649.75  6631.8 1658.13
  6749.2 1663.56  6791.6 1664.29  7027.2  1666.8  7035.2 1666.83  7187.5 1668.73
  7232.5 1670.44  7262.5 1674.17  7311.5 1675.11  7351.1 1675.59  7467.9  1677.8
#Mann= 19 ,-1 , 0
  2866.2    .035       0  3034.9     .07       0  3257.3    .035       0
  5288.8     .07       0  5596.2    .035       0  5703.2     .07       0
  5785.4    .035       0  5806.5    .035       0  5815.4    .035       0
  6091.6     .07       0  6165.8    .035       0  6282.9     .07       0
  6749.2    .035       0  6791.6    .063       0  7027.2    .094       0
  7035.2    .063       0  7187.5    .094       0  7311.5    .063       0
  7351.1    .094       0
#XS Ineff= 2 , 0
       0                  5700.8       0    1651
Permanent Ineff=
       F       F
Bank Sta=5040,5080.1
XS Rating Curve= 0 ,0
Exp/Cntr=0.3,0.1

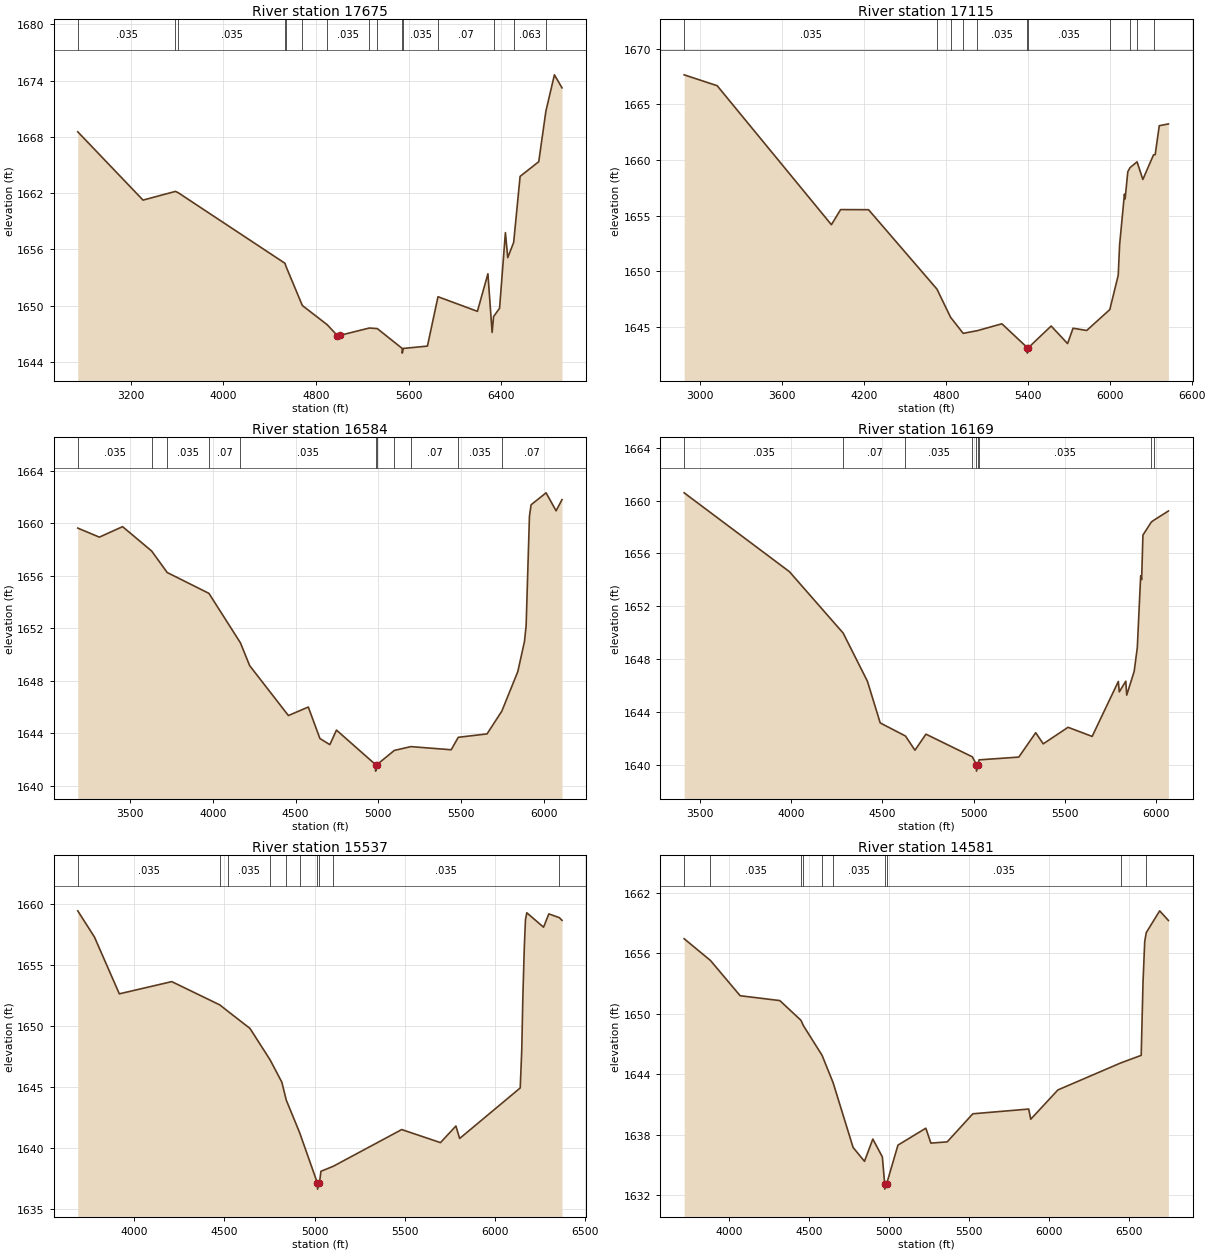
Type RM Length L Ch R = 1 ,17675   ,560,560,560
BEGIN DESCRIPTION:
MULBERRY CREEK TRIBUTARY 4 17.0
END DESCRIPTION:
XS GIS Cut Line= 3
      1572764.09      6881559.17        1575005.        6881788.
      1576920.17      6882027.89
#Sta/Elev= 30
  2742.4 1668.54  3306.2 1661.25  3586.4 1662.18    3610 1662.04    4532 1654.51
  4541.9 1654.15  4682.4    1650  4896.2 1647.96  4984.9 1646.79    5005 1646.81
  5260.6  1647.6  5329.5 1647.54  5544.8 1645.42  5545.3 1644.92  5553.7 1645.42
  5762.6 1645.67    5854 1650.94  6194.3 1649.38    6285 1653.39  6321.4 1647.13
    6334 1648.82  6385.7 1649.71  6436.1 1657.78  6456.3 1655.11  6507.5 1656.74
    6563 1663.78  6724.1 1665.35  6785.8 1670.74  6859.4 1674.62  6925.1 1673.23
#Mann= 15 ,-1 , 0
  2742.4    .035       0  3586.4     .07       0    3610    .035       0
    4532     .07       0  4541.9    .035       0  4682.4     .07       0
  4896.2    .035       0  5260.6     .07       0  5329.5    .035       0
  5544.8    .035       0  5553.7    .035       0    5854     .07       0
    6334    .035       0  6507.5    .063       0  6785.8    .094       0
Bank Sta=4984.9,5005
XS Rating Curve= 0 ,0
Exp/Cntr=0.3,0.1

Type RM Length L Ch R = 1 ,17115   ,531,531,531
BEGIN DESCRIPTION:
Mapping XS c03023e0
END DESCRIPTION:
XS GIS Cut Line= 3
      1572804.91      6882022.71      1574883.89      6882278.78
      1576331.76      6882374.15
#Sta/Elev= 30
  2884.1 1667.67    3126 1666.69  3962.3 1654.18  4029.7 1655.54  4234.3 1655.53
  4735.3 1648.38  4834.7 1645.85  4927.1  1644.4  5029.8 1644.64  5210.4 1645.26
  5396.3 1643.12  5396.8 1642.62  5405.3 1643.12  5571.2 1645.06  5691.4 1643.48
  5731.5 1644.86  5831.7 1644.66  6000.6 1646.54  6062.2 1649.62  6072.3 1652.35
  6107.7 1656.93  6112.7  1656.5  6132.4 1658.95  6149.1 1659.32  6200.3 1659.84
  6242.6 1658.25  6320.8 1660.47  6332.8 1660.48  6362.9 1663.09  6429.8 1663.25
#Mann= 11 ,-1 , 0
  2884.1    .035       0  4735.3     .07       0  4834.7    .035       0
  4927.1     .07       0  5029.8    .035       0  5396.3     .07       0
  5405.3    .035       0  6000.6     .07       0  6149.1    .035       0
  6200.3     .07       0  6320.8    .063       0
Bank Sta=5396.3,5405.3
XS Rating Curve= 0 ,0
Exp/Cntr=0.3,0.1

Type RM Length L Ch R = 1 ,16584   ,415,415,415
BEGIN DESCRIPTION:
Mapping XS 44f38353
END DESCRIPTION:
XS GIS Cut Line= 3
      1573134.71       6882647.7      1574927.29      6882743.19
      1576050.68      6882626.08
#Sta/Elev= 30
  3184.8 1659.64  3315.3 1658.95  3455.5 1659.75  3631.2 1657.89  3725.2 1656.25
    3977 1654.66  4167.6 1650.88  4222.9 1649.15  4456.9 1645.34  4577.1 1645.99
  4647.2 1643.59  4707.2 1643.12  4747.3 1644.23  4983.1  1641.6  4983.6  1641.1
  4992.2  1641.6  5096.6 1642.68  5196.7 1642.97  5440.1 1642.73  5482.8 1643.68
  5656.6 1643.94    5746 1645.68  5842.3 1648.69  5882.5 1650.98  5892.6 1652.19
  5912.7 1660.54  5922.7 1661.42  6013.2 1662.33  6073.5 1660.96  6109.4 1661.81
#Mann= 11 ,-1 , 0
  3184.8    .035       0  3631.2     .07       0  3725.2    .035       0
    3977     .07       0  4167.6    .035       0  4983.1     .07       0
  4992.2    .035       0  5096.6    .035       0  5196.7     .07       0
  5482.8    .035       0    5746     .07       0
Bank Sta=4983.1,4992.2
XS Rating Curve= 0 ,0
Exp/Cntr=0.3,0.1

Type RM Length L Ch R = 1 ,16169   ,632,632,632
BEGIN DESCRIPTION:
Mapping XS 2ae136ef
END DESCRIPTION:
XS GIS Cut Line= 3
      1573273.67      6883264.02      1574836.14      6883125.14
      1575890.43      6882856.14
#Sta/Elev= 30
  3411.9 1660.58  3989.3 1654.63  4284.3 1649.99  4417.2 1646.36  4487.5 1643.21
  4626.1 1642.22  4678.2 1641.15  4738.4 1642.36  4992.9 1640.65  5015.1 1640.07
  5015.6 1639.57  5026.2 1640.07  5029.4 1640.42  5247.7 1640.63  5340.6 1642.47
  5381.9 1641.63  5518.1 1642.88  5650.2 1642.19  5793.8 1646.34    5799 1645.55
  5834.7 1646.36  5839.9 1645.31  5880.7  1647.1  5897.9 1648.89  5916.4 1654.32
  5921.6 1654.03  5928.8 1657.39  5974.5 1658.37  5988.4 1658.51  6068.6 1659.21
#Mann= 9 ,-1 , 0
  3411.9    .035       0  4284.3     .07       0  4626.1    .035       0
  4992.9     .07       0  5015.1     .07       0  5026.2     .07       0
  5029.4    .035       0  5974.5     .07       0  5988.4    .035       0
Bank Sta=5015.1,5026.2
XS Rating Curve= 0 ,0
Exp/Cntr=0.3,0.1

Type RM Length L Ch R = 1 ,15537   ,956,956,956
BEGIN DESCRIPTION:
Mapping XS 598ae9b6
END DESCRIPTION:
XS GIS Cut Line= 4
      1573354.39      6883845.33      1574656.46      6883663.04
      1575088.75      6883517.21      1575821.58      6882971.48
#Sta/Elev= 30
  3687.2 1659.44  3779.9 1657.29  3917.7 1652.64  4208.4 1653.64  4475.1 1651.73
  4519.6 1651.21  4641.8 1649.81  4753.2 1647.24  4818.7  1645.4  4843.3 1643.93
  4916.7 1641.29  5015.8 1637.14  5016.3 1636.64  5027.2 1637.14  5035.4  1638.1
  5104.7 1638.52  5483.3 1641.52  5698.1 1640.45  5783.6 1641.81  5804.5 1640.79
  6140.2 1644.93  6148.6 1648.01  6154.8 1652.38  6163.2 1656.62  6169.4 1658.72
  6176.7 1659.28  6269.5  1658.1  6298.8 1659.19  6357.2 1658.88  6371.9 1658.66
#Mann= 10 ,-1 , 0
  3687.2    .035       0  4475.1     .07       0  4519.6    .035       0
  4753.2     .07       0  4843.3    .035       0  4916.7     .07       0
  5015.8     .07       0  5027.2     .07       0  5104.7    .035       0
  6357.2    .063       0
Bank Sta=5015.8,5027.2
XS Rating Curve= 0 ,0
Exp/Cntr=0.3,0.1

Type RM Length L Ch R = 1 ,14581   ,900,900,900
BEGIN DESCRIPTION:
Mapping XS a622d2ce
END DESCRIPTION:
XS GIS Cut Line= 4
      1573547.07        6884637.      1574812.71      6884402.63
      1575198.12      6884178.67      1575807.49      6883038.06
#Sta/Elev= 30
  3720.3 1657.46  3884.8  1655.3  4070.4  1651.8  4318.2 1651.32  4450.3 1649.36
  4465.5 1648.83    4582 1645.89  4651.3 1643.16  4775.9 1636.74  4847.1 1635.36
  4899.3 1637.57  4958.9  1635.8  4973.4  1633.1  4973.9  1632.6  4985.1  1633.1
  5056.4 1636.97  5230.6 1638.65  5262.1 1637.17  5363.9 1637.29  5524.3 1640.08
  5873.5 1640.55  5886.1 1639.54    6056 1642.45  6447.2 1645.12  6576.3 1645.88
  6587.7 1653.14  6598.3 1657.18  6607.7 1658.06  6691.8 1660.23  6746.4 1659.27
#Mann= 10 ,-1 , 0
  3720.3     .07       0  3884.8    .035       0  4450.3     .07       0
  4465.5    .035       0    4582     .07       0  4651.3    .035       0
  4973.4    .035       0  4985.1    .035       0  6447.2    .063       0
  6607.7    .035       0
Bank Sta=4973.4,4985.1
XS Rating Curve= 0 ,0
Exp/Cntr=0.3,0.1

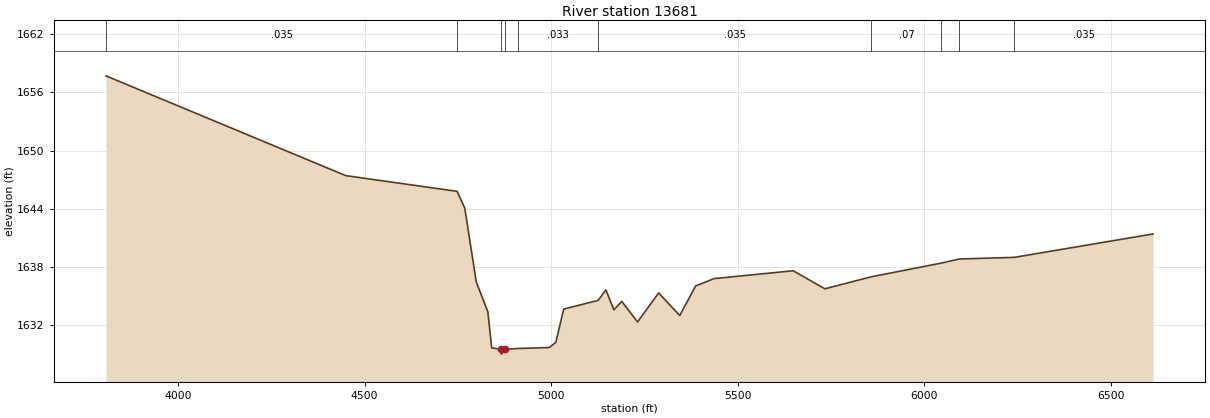
Type RM Length L Ch R = 1 ,13681   ,266,266,266
BEGIN DESCRIPTION:
MULBERRY CREEK TRIBUTARY 4 10.0
END DESCRIPTION:
XS GIS Cut Line= 4
      1573390.85      6884850.55        1574555.        6885138.
       1575307.5      6884376.58      1575580.01      6883912.98
#Sta/Elev= 30
  3806.6  1657.7  4449.5 1647.42  4748.2  1645.8  4768.8 1644.06  4799.7 1636.45
  4830.6 1633.39  4840.9 1629.67  4865.9 1629.53  4866.4 1629.03  4877.7 1629.53
  4910.8 1629.61  4995.4 1629.71  5012.8 1630.24    5034 1633.67  5126.5 1634.57
  5147.1 1635.65  5168.4 1633.59  5189.5 1634.47    5232 1632.34  5288.5 1635.34
  5345.1    1633  5387.5 1636.05  5437.1 1636.81  5649.2 1637.62  5734.1 1635.76
  5858.9    1637  6046.5 1638.41  6094.6 1638.83  6242.3    1639    6614 1641.41
#Mann= 10 ,-1 , 0
  3806.6    .035       0  4748.2     .07       0  4865.9    .033       0
  4877.7     .07       0  4910.8    .033       0  5126.5    .035       0
  5858.9     .07       0  6046.5    .035       0  6094.6     .07       0
  6242.3    .035       0
Bank Sta=4865.9,4877.7
XS Rating Curve= 0 ,0
Exp/Cntr=0.3,0.1