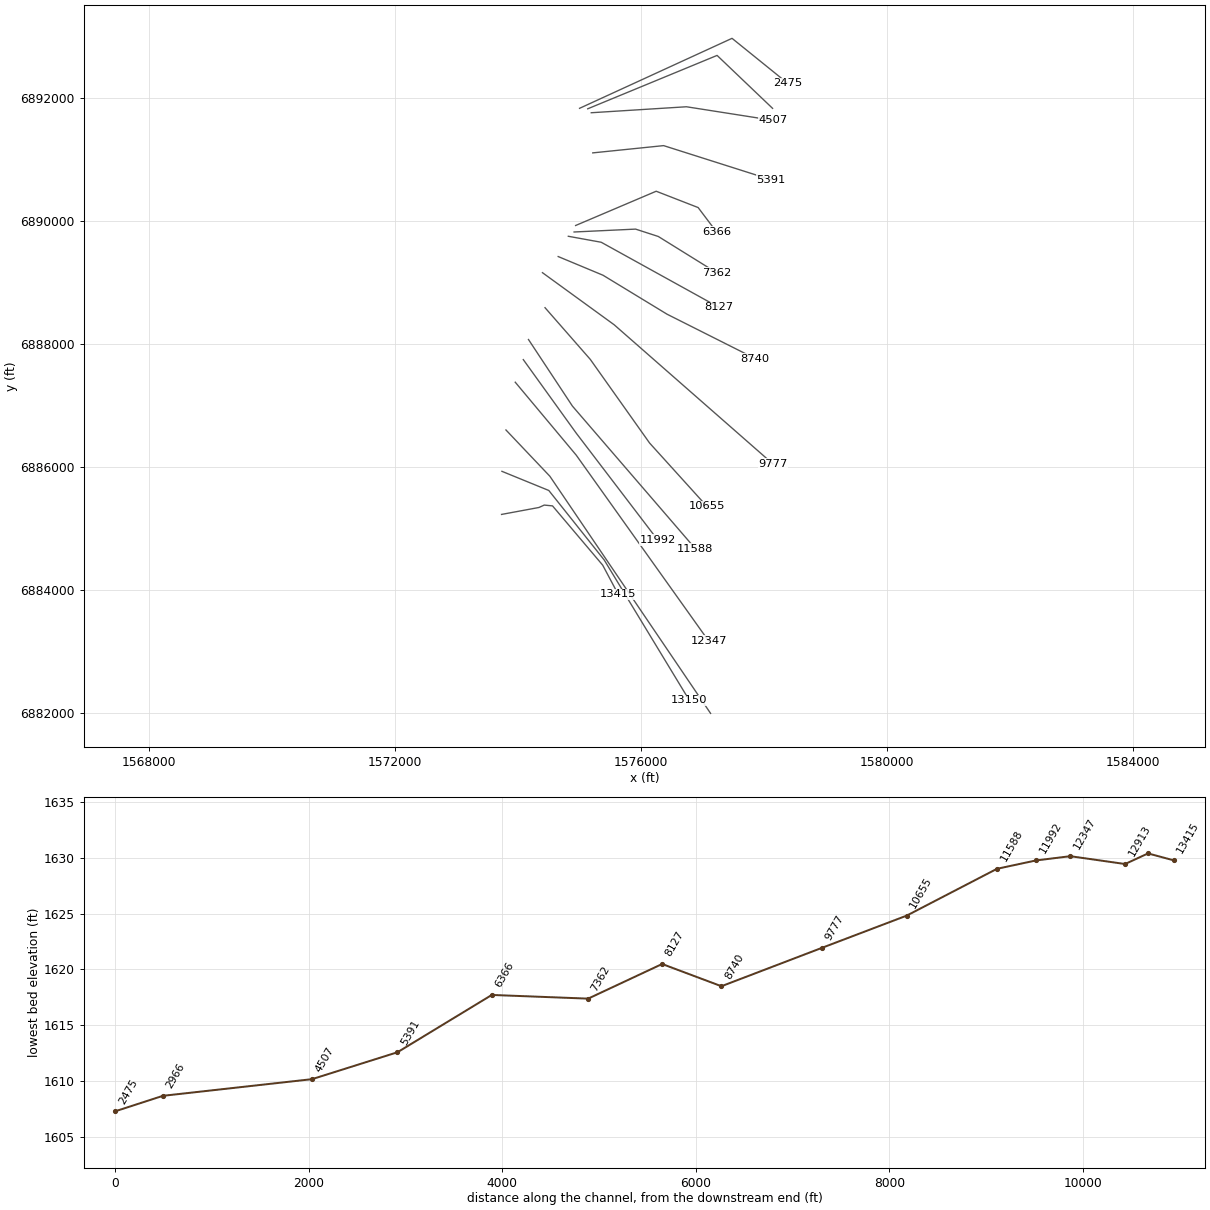
HEC-RAS study MULBERRY CREEK TRIBUTARY 4.prj: MULBERRY CREEK TRIBUTARY 4 Base Level Engineering

--- MULBERRY CREEK TRIBUTARY 4.g01 (geometry) --- (continued)

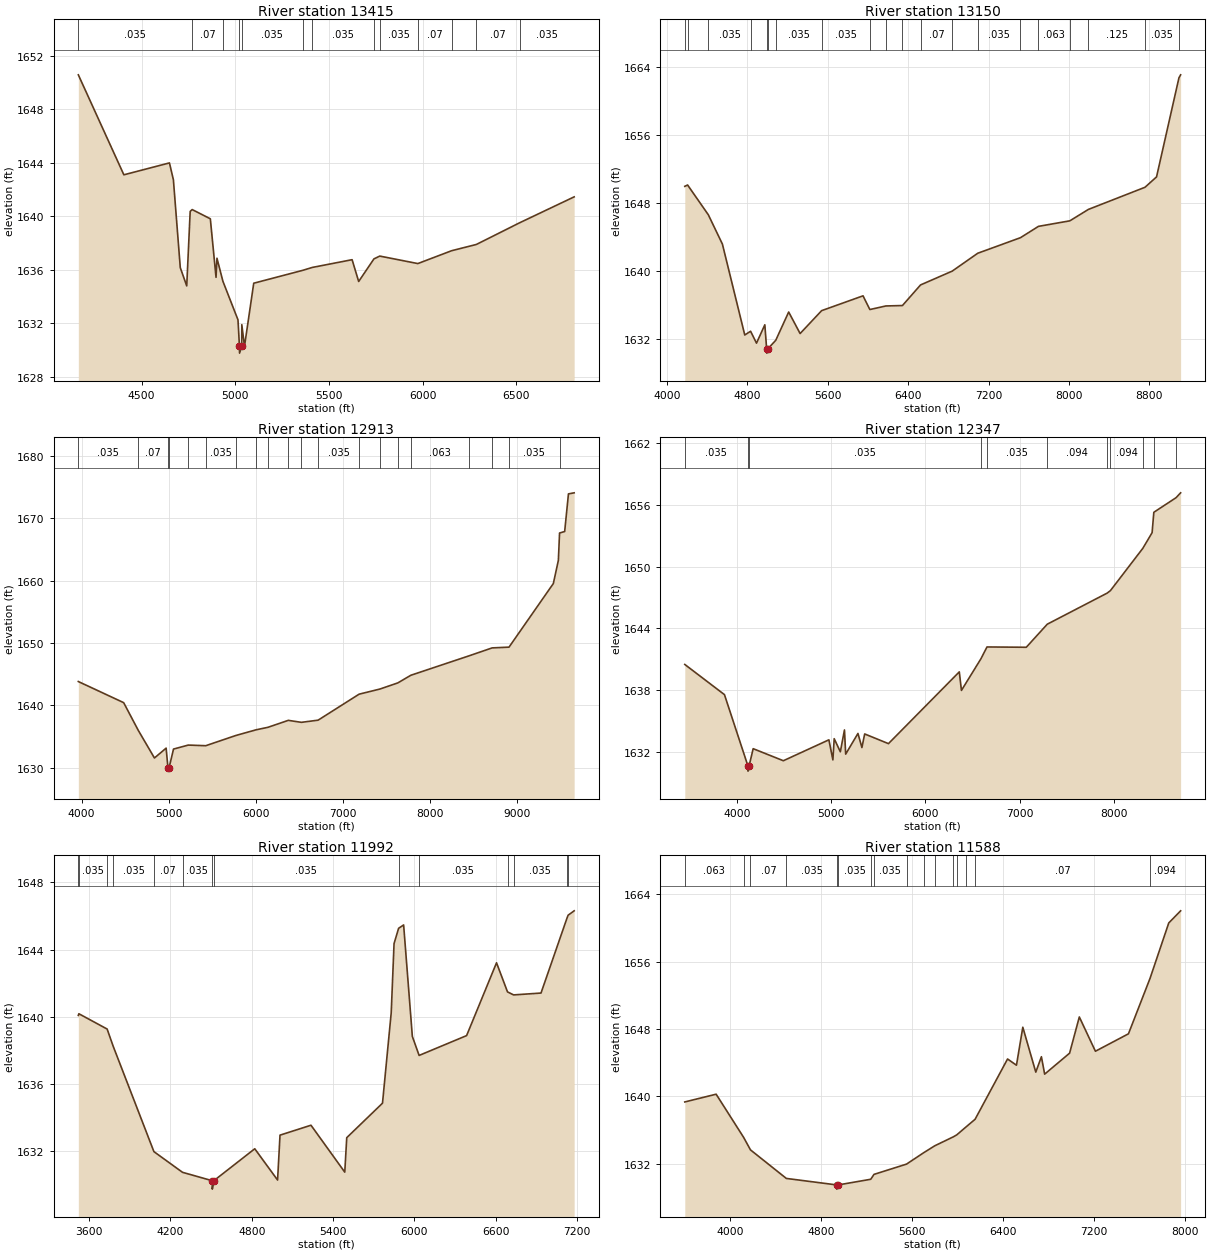
Type RM Length L Ch R = 1 ,13415   ,265,265,265
BEGIN DESCRIPTION:
Mapping XS 8dbdbffc
END DESCRIPTION:
XS GIS Cut Line= 6
      1573735.99      6885233.41      1574343.63      6885346.26
      1574430.44      6885385.33      1574564.99      6885372.31
      1575380.96      6884408.76      1575632.68       6883935.7
#Sta/Elev= 30
    4162 1650.58  4405.1  1643.1  4648.4 1643.99  4669.5 1642.73  4706.3 1636.15
  4740.7 1634.79  4759.1 1640.36  4769.8  1640.5  4866.7 1639.81  4897.1 1635.43
  4902.1 1636.86  4933.7 1635.14  5014.3 1632.25  5022.2 1630.26  5022.7 1629.76
    5034 1630.26  5034.7 1631.89    5049 1630.27  5098.4 1634.99  5359.1 1635.95
  5410.9 1636.17  5623.5 1636.75  5658.6 1635.12  5740.1 1636.81  5771.3 1637.02
  5974.3 1636.46  6154.6 1637.42  6286.9 1637.89  6517.6 1639.51  6808.9 1641.45
#Mann= 13 ,-1 , 0
    4162    .035       0  4769.8     .07       0  4933.7    .035       0
  5022.2    .035       0    5034    .035       0  5359.1     .07       0
  5410.9    .035       0  5740.1     .07       0  5771.3    .035       0
  5974.3     .07       0  6154.6    .035       0  6286.9     .07       0
  6517.6    .035       0
Bank Sta=5022.2,5034
XS Rating Curve= 0 ,0
Exp/Cntr=0.3,0.1

Type RM Length L Ch R = 1 ,13150   ,237,237,237
BEGIN DESCRIPTION:
MULBERRY CREEK TRIBUTARY 4 9.0
END DESCRIPTION:
XS GIS Cut Line= 4
      1573742.35      6885934.03      1574504.57      6885622.82
        1575407.      6884490.84      1576788.95      6882213.05
#Sta/Elev= 30
  4176.7 1649.97  4204.5 1650.13    4411 1646.63    4551 1643.19  4773.6 1632.51
  4831.6 1632.95  4890.4 1631.55  4973.3 1633.71  4991.4 1630.88  4991.9 1630.38
  5003.2 1630.88  5082.1 1631.89  5210.8 1635.21  5324.5 1632.68  5538.7 1635.37
  5950.7 1637.11  6018.7  1635.5  6178.2 1635.92    6343 1635.97  6523.3 1638.39
    6838 1640.01  7092.3 1642.11  7517.9 1643.94    7697 1645.27  8009.3 1645.92
  8193.8 1647.26  8757.1 1649.86  8872.2 1651.08  9095.1 1662.71  9111.9 1663.07
#Mann= 20 ,-1 , 0
  4176.7    .035       0  4204.5     .07       0    4411    .035       0
  4831.6     .07       0  4991.4     .07       0  5003.2     .07       0
  5082.1    .035       0  5538.7    .035       0  6018.7    .035       0
  6178.2     .07       0    6343    .035       0  6523.3     .07       0
    6838    .035       0  7092.3    .035       0  7517.9    .035       0
    7697    .063       0  8009.3    .063       0  8193.8    .125       0
  8757.1    .035       0  9095.1    .094       0
Bank Sta=4991.4,5003.2
XS Rating Curve= 0 ,0
Exp/Cntr=0.3,0.1

Type RM Length L Ch R = 1 ,12913   ,566,566,566
BEGIN DESCRIPTION:
MULBERRY CREEK TRIBUTARY 4 8.0
END DESCRIPTION:
XS GIS Cut Line= 3
       1573807.5      6886606.75      1574521.43      6885854.77
      1577136.14      6881997.82
#Sta/Elev= 30
  3963.1 1643.81    4484 1640.42  4652.4 1635.96  4837.6 1631.54  4971.9 1633.12
    4993 1629.93  4993.5 1629.43  5004.9 1629.93  5056.7 1632.97  5226.1 1633.61
  5427.1 1633.51  5772.8 1635.15  6007.8 1636.07  6140.9 1636.46  6375.9 1637.58
  6525.7 1637.26    6718 1637.61  7188.7 1641.78  7429.3 1642.61  7633.7 1643.59
  7783.9 1644.82  8446.7 1647.91  8717.7 1649.21  8911.3 1649.33  9420.5 1659.54
  9478.3 1663.26    9492 1667.65  9550.7 1667.89  9594.2 1673.93  9659.7  1674.1
#Mann= 20 ,-1 , 0
  3963.1    .035       0  4652.4     .07       0    4993     .07       0
  5004.9     .07       0  5226.1    .035       0  5427.1    .035       0
  5772.8     .07       0  6007.8     .07       0  6140.9    .035       0
  6375.9     .07       0  6525.7    .035       0    6718    .035       0
  7188.7     .07       0  7429.3     .07       0  7633.7    .063       0
  7783.9    .063       0  8446.7    .125       0  8717.7    .125       0
  8911.3    .035       0    9492    .063       0
Bank Sta=4993,5004.9
XS Rating Curve= 0 ,0
Exp/Cntr=0.3,0.1

Type RM Length L Ch R = 1 ,12347   ,355,355,355
BEGIN DESCRIPTION:
Mapping XS 27146180
END DESCRIPTION:
XS GIS Cut Line= 3
      1573958.65      6887383.63       1574951.7      6886196.14
      1577104.46      6883175.33
#Sta/Elev= 30
  3449.7 1640.49  3870.2 1637.56  4119.3 1630.63  4119.8 1630.13  4131.2 1630.63
  4174.7 1632.31  4494.8 1631.14  4977.6 1633.17    5020 1631.22  5033.8 1633.28
    5099 1632.01  5142.8 1634.13  5155.5 1631.78  5285.8 1633.79  5327.6 1632.42
  5357.1 1633.74  5609.2  1632.8  6360.3 1639.77    6383 1637.97  6590.2 1641.05
  6654.1 1642.19  7070.6 1642.16  7293.1  1644.4  7928.2 1647.42  7962.6 1647.66
  8306.4 1651.77  8404.7 1653.29  8423.1 1655.27    8659 1656.69  8707.1 1657.16
#Mann= 11 ,-1 , 0
  3449.7    .035       0  4119.3    .035       0  4131.2    .035       0
  6590.2     .07       0  6654.1    .035       0  7293.1    .094       0
  7928.2    .063       0  7962.6    .094       0  8306.4    .063       0
  8423.1    .125       0    8659    .035       0
Bank Sta=4119.3,4131.2
XS Rating Curve= 0 ,0
Exp/Cntr=0.3,0.1

Type RM Length L Ch R = 1 ,11992   ,404,404,404
BEGIN DESCRIPTION:
Mapping XS 871186bc
END DESCRIPTION:
XS GIS Cut Line= 3
      1574089.69      6887750.95      1574949.07      6886557.36
      1576277.21       6884816.9
#Sta/Elev= 30
  3519.7 1640.08  3523.6 1640.18  3732.3 1639.27  3775.9 1638.27  4077.6 1631.98
  4288.7 1630.75  4508.1 1630.25  4508.6 1629.75    4520 1630.25  4822.1 1632.15
  4990.5 1630.29  5008.5 1632.96  5237.1 1633.55  5486.5 1630.76  5501.1 1632.81
    5765 1634.86  5829.4 1640.24  5850.3 1644.35  5883.9 1645.26    5921 1645.46
  5985.4 1638.83  6035.3  1637.7  6385.9 1638.88  6606.8 1643.21  6687.8 1641.48
  6732.7  1641.3  6935.1 1641.41  7125.4 1645.83  7135.3 1646.04  7179.8  1646.3
#Mann= 14 ,-1 , 0
  3519.7     .07       0  3523.6    .035       0  3732.3     .07       0
  3775.9    .035       0  4077.6     .07       0  4288.7    .035       0
  4508.1    .035       0    4520    .035       0  5883.9     .07       0
  6035.3    .035       0  6687.8     .07       0  6732.7    .035       0
  7125.4     .07       0  7135.3    .035       0
Bank Sta=4508.1,4520
XS Rating Curve= 0 ,0
Exp/Cntr=0.3,0.1

Type RM Length L Ch R = 1 ,11588   ,933,933,933
BEGIN DESCRIPTION:
Mapping XS e7dfb604
END DESCRIPTION:
XS GIS Cut Line= 3
      1574173.95      6888078.05       1574889.2      6886994.75
      1576889.22      6884675.29
#Sta/Elev= 30
  3601.4 1639.35  3877.1 1640.27  4118.1 1635.16  4179.1 1633.66  4494.5 1630.27
  4937.3  1629.5  4937.8    1629  4950.9  1629.5  5236.9 1630.17  5265.5 1630.75
  5551.6 1631.97  5702.1 1633.32  5800.6 1634.15  5963.5 1635.21  5993.2 1635.44
  6076.4  1636.4  6154.4 1637.29  6440.1 1644.45  6518.4 1643.71  6574.3 1648.22
  6688.4 1642.89  6737.8 1644.72  6766.3 1642.65  6985.7 1645.14  7071.3 1649.44
  7212.8 1645.37  7503.5 1647.44  7692.9 1654.01  7857.9  1660.6  7962.2 1662.04
#Mann= 16 ,-1 , 0
  3601.4    .063       0  4118.1    .035       0  4179.1     .07       0
  4494.5    .035       0  4937.3    .035       0  4950.9    .035       0
  5236.9     .07       0  5265.5    .035       0  5551.6     .07       0
  5702.1    .035       0  5800.6     .07       0  5963.5    .035       0
  5993.2     .07       0  6076.4    .035       0  6154.4     .07       0
  7692.9    .094       0
Bank Sta=4937.3,4950.9
XS Rating Curve= 0 ,0
Exp/Cntr=0.3,0.1

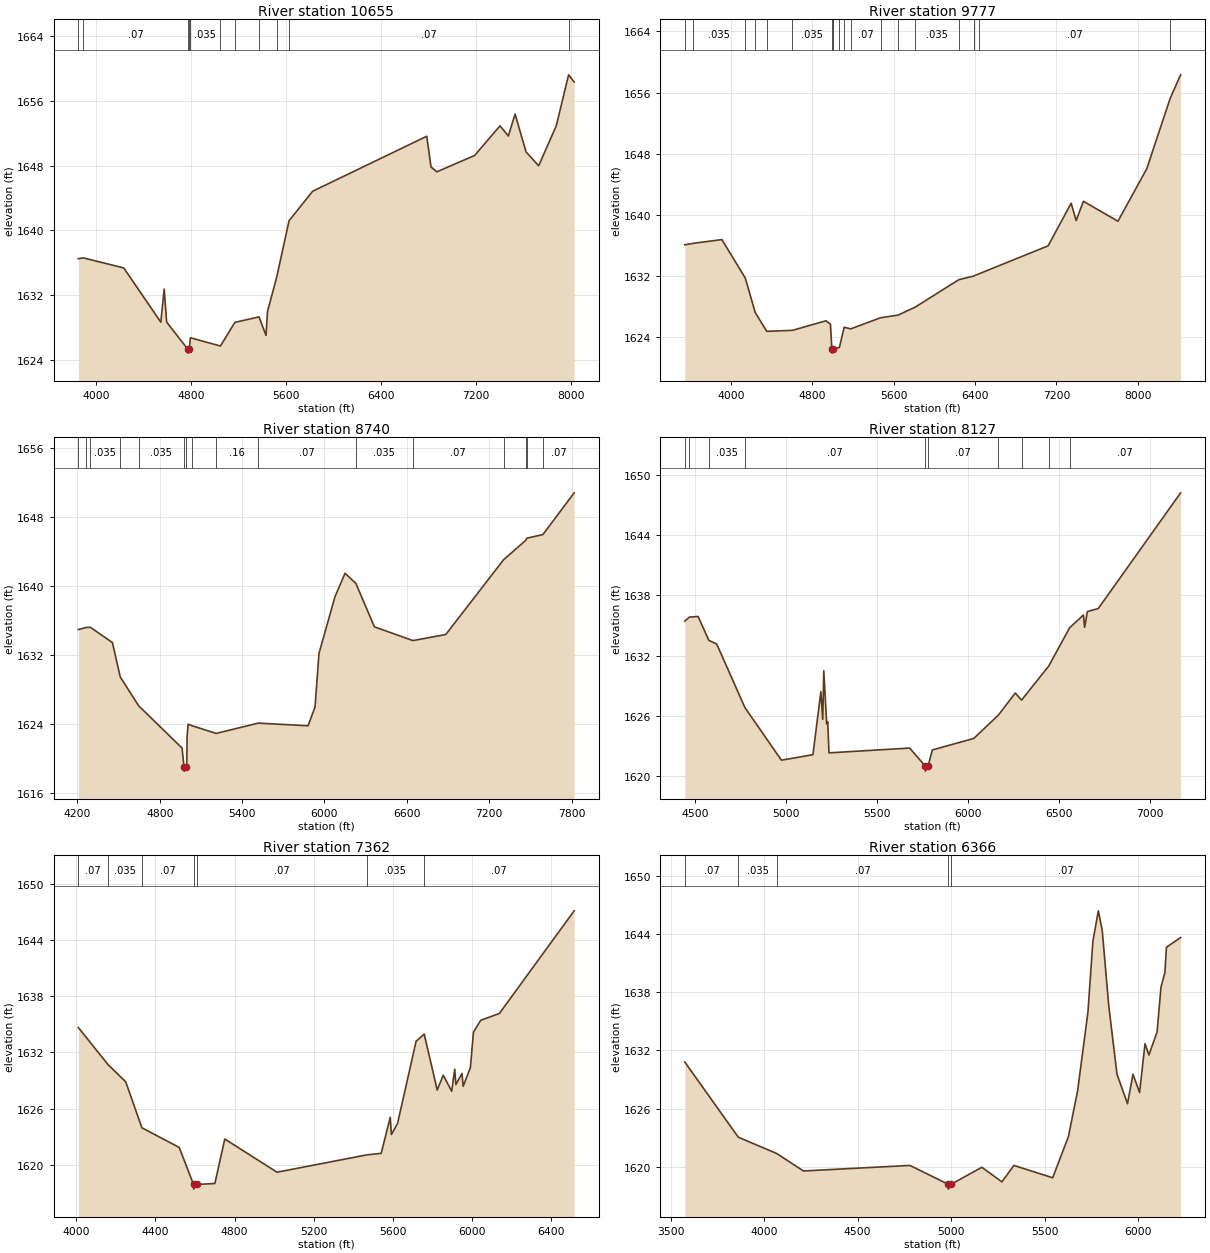
Type RM Length L Ch R = 1 ,10655   ,878,878,878
BEGIN DESCRIPTION:
Mapping XS 136b5c60
END DESCRIPTION:
XS GIS Cut Line= 4
      1574443.01      6888595.45      1575179.13      6887755.17
      1576144.41      6886394.05      1577074.95      6885366.29
#Sta/Elev= 30
    3853 1636.48  3896.2 1636.58  4235.2 1635.34    4547 1628.64  4575.5 1632.72
  4596.4 1628.64  4773.7 1625.31  4774.2 1624.81  4787.4 1625.31  4796.1 1626.71
  5048.9 1625.69  5170.3 1628.61  5373.2 1629.29  5432.4    1627  5444.8 1629.95
  5522.4 1634.22  5626.1 1641.17  5824.8 1644.82  6784.9 1651.62  6820.7 1647.82
    6870 1647.22  7188.4 1649.25  7401.3 1652.91  7471.6 1651.65  7528.3 1654.36
  7620.2 1649.69  7726.4 1647.97    7875 1652.92  7978.5 1659.21  8025.2 1658.32
#Mann= 11 ,-1 , 0
    3853    .035       0  3896.2     .07       0  4773.7    .035       0
  4787.4     .07       0  4796.1    .035       0  5048.9     .07       0
  5170.3    .035       0  5373.2     .07       0  5522.4    .035       0
  5626.1     .07       0  7978.5    .035       0
Bank Sta=4773.7,4787.4
XS Rating Curve= 0 ,0
Exp/Cntr=0.3,0.1

Type RM Length L Ch R = 1 ,9777    ,1037,1037,1037
BEGIN DESCRIPTION:
Mapping XS 50cd324f
END DESCRIPTION:
XS GIS Cut Line= 3
      1574401.35      6889164.89      1575568.02      6888317.67
      1578150.69      6886054.36
#Sta/Elev= 30
  3545.8 1636.09  3622.9 1636.27  3910.6 1636.77  4140.7 1631.74  4238.3 1627.23
  4352.1 1624.77  4604.2  1624.9  4934.5 1626.15  4978.1 1625.71  4992.2 1622.42
  4992.7 1621.92    5006 1622.42  5006.1 1622.43    5066 1622.67  5113.2 1625.31
  5176.5 1625.09  5472.3 1626.55  5642.3 1626.89  5809.6 1627.92  6239.7 1631.52
  6385.8    1632    6442 1632.31  7118.3 1635.95  7345.1 1641.52  7394.5 1639.26
  7465.7 1641.78  7805.4 1639.17  8089.2 1646.05  8319.7 1655.27  8421.7 1658.32
#Mann= 19 ,-1 , 0
  3545.8     .07       0  3622.9    .035       0  4140.7     .07       0
  4238.3    .035       0  4352.1     .07       0  4604.2    .035       0
  4992.2    .035       0    5006    .035       0  5006.1     .16       0
    5066    .035       0  5113.2     .16       0  5176.5     .07       0
  5472.3    .035       0  5642.3     .07       0  5809.6    .035       0
  6239.7     .07       0  6385.8    .035       0    6442     .07       0
  8319.7    .035       0
Bank Sta=4992.2,5006
XS Rating Curve= 0 ,0
Exp/Cntr=0.3,0.1

Type RM Length L Ch R = 1 ,8740    ,613,613,613
BEGIN DESCRIPTION:
Mapping XS 2ec7520a
END DESCRIPTION:
XS GIS Cut Line= 4
       1574657.4      6889427.06       1575386.6      6889123.22
      1576428.27      6888489.54      1577860.26      6887769.21
#Sta/Elev= 30
  4207.1 1634.94  4264.4 1635.19  4295.4  1635.2  4455.4 1633.43  4512.4 1629.44
  4646.2 1626.09  4962.8 1621.17  4977.1 1618.99  4977.6 1618.49    4992 1618.99
  4997.1 1619.31  4999.3  1622.5  5006.9 1623.94  5036.4 1623.76    5211 1622.87
  5518.2 1624.07  5880.8 1623.76  5931.6 1625.94  5960.2 1632.16  6076.5 1638.75
  6150.1 1641.48  6228.9 1640.32  6364.1 1635.26  6644.4 1633.66  6884.3 1634.37
    7305 1643.05  7466.5 1645.31  7474.6 1645.56  7591.8 1645.98  7819.3 1650.83
#Mann= 16 ,-1 , 0
  4207.1    .035       0  4264.4     .07       0  4295.4    .035       0
  4512.4     .07       0  4646.2    .035       0  4977.1    .035       0
    4992    .035       0  5036.4     .07       0    5211     .16       0
  5518.2     .07       0  6228.9    .035       0  6644.4     .07       0
    7305    .035       0  7466.5     .07       0  7474.6    .035       0
  7591.8     .07       0
Bank Sta=4977.1,4992
XS Rating Curve= 0 ,0
Exp/Cntr=0.3,0.1

Type RM Length L Ch R = 1 ,8127    ,765,765,765
BEGIN DESCRIPTION:
Mapping XS 992e82fd
END DESCRIPTION:
XS GIS Cut Line= 3
      1574822.36       6889756.9      1575357.08      6889659.68
      1577266.79      6888604.13
#Sta/Elev= 30
  4442.2 1635.44  4467.7 1635.84  4515.4  1635.9  4574.3 1633.52  4617.7 1633.15
  4772.8 1626.81  4973.4 1621.57  5146.6 1622.12  5190.1  1628.4  5200.4 1625.64
  5206.2 1630.49  5222.2 1625.18  5227.9  1625.4  5234.7  1622.3  5678.1 1622.78
  5764.2 1620.98  5764.7 1620.48  5779.2 1620.98    5803 1622.59  6030.9 1623.74
  6166.1 1626.07  6258.9 1628.27  6293.3 1627.56  6442.8 1630.96  6557.7 1634.78
  6633.5 1636.05  6640.1 1634.82  6655.2 1636.39  6714.8 1636.69  7167.7 1648.23
#Mann= 10 ,-1 , 0
  4442.2    .035       0  4467.7     .07       0  4574.3    .035       0
  4772.8     .07       0  5764.2     .07       0  5779.2     .07       0
  6166.1    .035       0  6293.3     .07       0  6442.8    .035       0
  6557.7     .07       0
Bank Sta=5764.2,5779.2
XS Rating Curve= 0 ,0
Exp/Cntr=0.3,0.1

Type RM Length L Ch R = 1 ,7362    ,996,996,996
BEGIN DESCRIPTION:
Mapping XS 8aba16ea
END DESCRIPTION:
XS GIS Cut Line= 4
      1574915.81      6889826.66      1575915.78      6889873.53
      1576285.57      6889753.74      1577233.45      6889165.22
#Sta/Elev= 30
  4010.5 1634.67  4160.6  1630.7    4250 1628.86  4331.8 1623.94  4520.3 1621.84
  4592.7 1617.88  4593.2 1617.38  4607.9 1617.88  4700.4 1617.98  4750.5 1622.74
  5014.6 1619.19    5467 1621.04  5540.9 1621.21  5586.7 1625.07  5592.5 1623.22
  5623.3 1624.39  5717.4  1633.2  5758.4 1633.96    5824 1627.98  5854.7 1629.57
  5897.2 1627.85  5912.6  1630.2  5918.5 1628.57  5949.2 1629.76  5955.1 1628.38
  5991.7 1630.38  6007.1 1634.17  6043.7 1635.44  6138.2 1636.17    6516 1647.15
#Mann= 7 ,-1 , 0
  4010.5     .07       0  4160.6    .035       0  4331.8     .07       0
  4592.7     .07       0  4607.9     .07       0    5467    .035       0
  5758.4     .07       0
Bank Sta=4592.7,4607.9
XS Rating Curve= 0 ,0
Exp/Cntr=0.3,0.1

Type RM Length L Ch R = 1 ,6366    ,975,975,975
BEGIN DESCRIPTION:
Mapping XS ebacf231
END DESCRIPTION:
XS GIS Cut Line= 4
      1574940.89      6889932.26      1576251.45      6890489.47
      1576933.91      6890223.92       1577232.5      6889828.11
#Sta/Elev= 30
  3575.9  1630.8    3862 1623.06  4067.4 1621.38  4210.6 1619.58    4780 1620.15
  4985.3 1618.21  4985.8 1617.71  5000.6 1618.21  5164.8 1619.96  5272.1 1618.46
  5336.4 1620.15  5543.7 1618.88    5628 1623.12  5677.1 1627.84  5732.3 1635.94
  5758.8 1643.23  5787.9 1646.37  5808.7 1644.37  5844.1 1636.52  5887.8 1629.54
    5944  1626.5  5973.2 1629.54  6008.6 1627.66  6037.7 1632.69  6058.5 1631.52
  6102.2  1633.9    6123 1638.51  6143.9 1639.99  6152.2 1642.62  6228.1 1643.62
#Mann= 5 ,-1 , 0
  3575.9     .07       0    3862    .035       0  4067.4     .07       0
  4985.3     .07       0  5000.6     .07       0
Bank Sta=4985.3,5000.6
XS Rating Curve= 0 ,0
Exp/Cntr=0.3,0.1

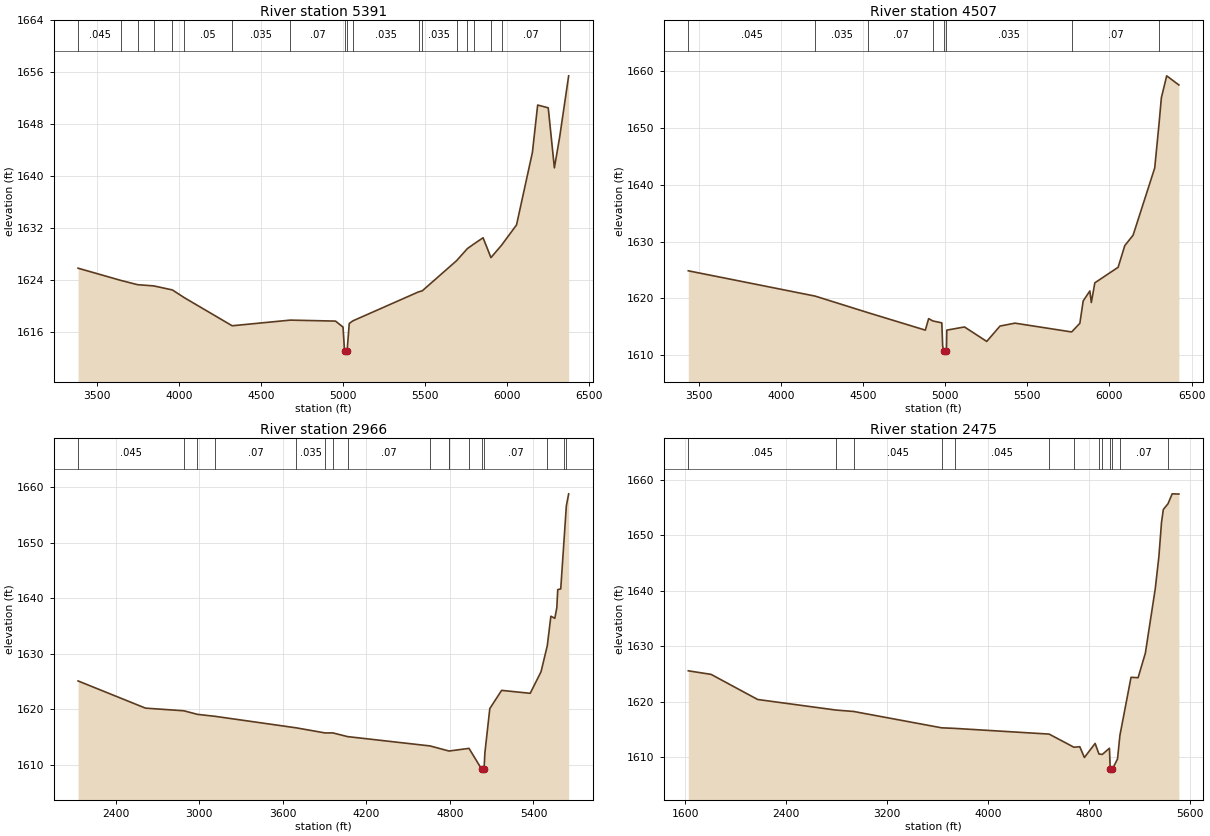
Type RM Length L Ch R = 1 ,5391    ,884,884,884
BEGIN DESCRIPTION:
Mapping XS d9c7e741
END DESCRIPTION:
XS GIS Cut Line= 3
      1575219.51      6891113.24      1576372.28      6891231.29
      1578121.17      6890676.09
#Sta/Elev= 30
  3382.6 1625.82  3644.8 1623.93  3745.7 1623.28  3844.9 1623.09  3958.2 1622.47
  4031.5 1621.27  4322.8 1616.95  4677.5 1617.82  4953.4 1617.67  4999.5 1616.75
  5008.5 1613.08    5009 1612.58  5024.3 1613.08  5037.4  1617.3    5059  1617.7
  5460.1 1622.17  5482.8 1622.33  5692.5 1626.98  5758.2 1628.84  5797.3 1629.54
  5854.1 1630.51  5902.1 1627.45  5967.4 1629.38  6058.2 1632.49    6155 1643.65
  6187.2 1650.96  6251.7 1650.53  6289.2 1641.28  6321.3 1646.01  6376.3 1655.46
#Mann= 19 ,-1 , 0
  3382.6    .045       0  3644.8    .035       0  3745.7    .045       0
  3844.9     .05       0  3958.2    .035       0  4031.5     .05       0
  4322.8    .035       0  4677.5     .07       0  5008.5     .07       0
  5024.3     .07       0    5059    .035       0  5460.1     .07       0
  5482.8    .035       0  5692.5     .07       0  5758.2    .035       0
  5797.3     .07       0  5902.1    .035       0  5967.4     .07       0
  6321.3    .035       0
Bank Sta=5008.5,5024.3
XS Rating Curve= 0 ,0
Exp/Cntr=0.3,0.1

Type RM Length L Ch R = 1 ,4507    ,1541,1541,1541
BEGIN DESCRIPTION:
Mapping XS a99f1f89
END DESCRIPTION:
XS GIS Cut Line= 3
      1575195.19      6891766.02       1576743.8      6891863.24
      1578160.22      6891641.06
#Sta/Elev= 30
    3437 1624.86  4208.9  1620.4  4531.9 1617.47  4879.6  1614.4  4899.7 1616.43
  4924.2 1616.03  4979.8 1615.68  4984.9 1611.62    4992 1610.67  4992.5 1610.17
  5007.9 1610.67  5010.1  1614.4  5117.8 1614.96  5253.2 1612.41    5334 1615.12
  5425.1 1615.63    5770 1614.08  5819.9 1615.61  5840.1 1619.55  5880.6 1621.31
  5889.7 1619.27    5911 1622.74  6052.7 1625.48  6093.2  1629.3  6143.8 1631.13
  6275.4 1642.99  6301.8 1650.81  6315.9 1655.37  6348.3 1659.23  6422.4 1657.62
#Mann= 8 ,-1 , 0
    3437    .045       0  4208.9    .035       0  4531.9     .07       0
  4924.2    .035       0    4992    .035       0  5007.9    .035       0
    5770     .07       0  6301.8    .035       0
Bank Sta=4992,5007.9
XS Rating Curve= 0 ,0
Exp/Cntr=0.3,0.1

Type RM Length L Ch R = 1 ,2966    ,491,491,491
BEGIN DESCRIPTION:
Mapping XS a8d7b9a0
END DESCRIPTION:
XS GIS Cut Line= 3
      1575137.91      6891830.26      1577242.07      6892698.31
      1578144.86      6891837.18
#Sta/Elev= 30
  2129.2 1625.11  2613.3 1620.21  2889.3 1619.73  2986.2 1619.09  3114.4 1618.73
  3695.9 1616.66  3903.6 1615.74  3958.8 1615.75  4064.6 1615.08  4657.2  1613.4
  4795.2 1612.47  4796.5 1612.49  4937.1 1612.96    5029 1609.18  5029.5 1608.68
  5045.2 1609.18  5051.3 1612.17  5086.6 1620.13  5171.4 1623.41  5376.8 1622.88
  5454.5 1626.76  5499.4 1631.44  5525.3 1636.77  5553.6 1636.39  5567.8  1638.3
  5574.7 1641.56  5596.1 1641.69  5622.6 1651.54  5636.4 1656.65    5653 1658.82
#Mann= 17 ,-1 , 0
  2129.2    .045       0  2889.3    .035       0  2986.2    .045       0
  3114.4     .07       0  3695.9    .035       0  3903.6    .045       0
  3958.8    .035       0  4064.6     .07       0  4657.2    .035       0
  4795.2     .07       0  4796.5    .035       0  4937.1     .07       0
    5029     .07       0  5045.2     .07       0  5499.4    .035       0
  5622.6     .07       0  5636.4    .035       0
Bank Sta=5029,5045.2
XS Rating Curve= 0 ,0
Exp/Cntr=0.3,0.1

Type RM Length L Ch R = 1 ,2475    ,0,0,0
BEGIN DESCRIPTION:
MULBERRY CREEK TRIBUTARY 4 1.0
END DESCRIPTION:
XS GIS Cut Line= 3
      1575005.01      6891838.01      1577485.12      6892976.09
      1578387.87      6892246.94
#Sta/Elev= 30
  1625.6 1625.57  1806.3 1624.93  2175.7  1620.4  2797.2 1618.49  2936.4 1618.24
  3634.4 1615.29  3738.1 1615.19  4486.1 1614.16    4683 1611.79  4729.4 1611.88
  4765.6 1609.94  4850.9 1612.47  4881.2 1610.57  4907.6 1610.49  4964.4 1611.61
  4970.7  1607.8  4971.2  1607.3  4986.9  1607.8  5028.4 1609.68  5047.2 1613.91
  5135.5  1624.4  5191.5 1624.33  5249.1 1628.76  5327.4 1640.35  5356.2 1646.13
    5377  1652.3  5391.4 1654.66  5428.5  1655.7  5461.8 1657.49  5514.8 1657.45
#Mann= 13 ,-1 , 0
  1625.6    .045       0  2797.2     .07       0  2936.4    .045       0
  3634.4     .07       0  3738.1    .045       0  4486.1     .07       0
    4683    .035       0  4881.2     .07       0  4907.6    .035       0
  4970.7    .035       0  4986.9    .035       0  5047.2     .07       0
  5428.5    .035       0
Bank Sta=4970.7,4986.9
XS Rating Curve= 0 ,0
Exp/Cntr=0.3,0.1

Chan Stop Cuts=-1
Use User Specified Reach Order=0
Composite Channel Slope=5