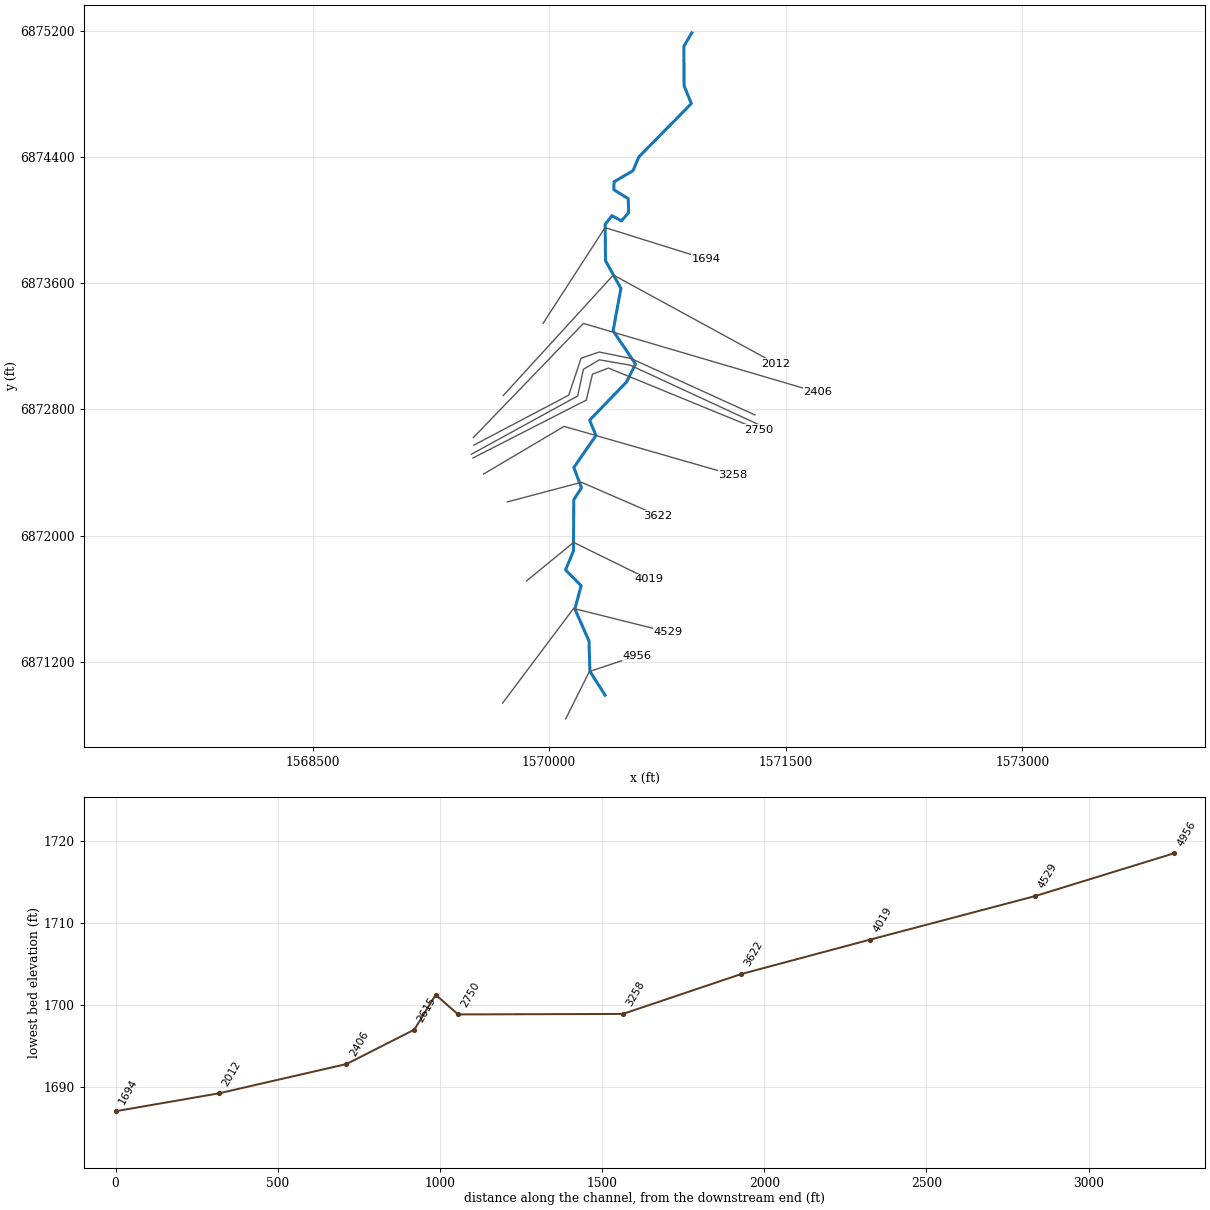
--- MULBERRY CREEK TRIBUTARY 4_1.prj (project) ---

Proj Title=MULBERRY CREEK TRIBUTARY 4_1 Base Level Engineering
Current Plan=p01
Default Exp/Contr=0.3,0.1
English Units
Geom File=g01
Flow File=f01
Plan File=p01
Y Axis Title=Elevation
X Axis Title(PF)=Main Channel Distance
X Axis Title(XS)=Station
BEGIN DESCRIPTION:
MULBERRY CREEK TRIBUTARY 4_1
END DESCRIPTION:
DSS Export Rating Curves= 0
DSS Export Rating Curve Sorted= 0
DSS Export Volume Flow Curves= 0
DXF OffsetX= 0
DXF OffsetY= 0
DXF ScaleX= 1
DXF ScaleY= 10

--- MULBERRY CREEK TRIBUTARY 4_1.p01 (plan) ---

Plan Title=Multiple Run
Short Identifier=Multiple
Geom File=g01
Flow File=f01
Subcritical Flow
K Sum by GR= 0
Std Step Tol= 0.01
Critical Tol= 0.01
Num of Std Step Trials= 20
Max Error Tol= 0.3
Flow Tol Ratio= 0.001
Split Flow NTrial= 30
Split Flow Tol= 0.02
Split Flow Ratio= 0.02
Log Output Level= 0
Friction Slope Method= 1
Unsteady Friction Slope Method= 2
Unsteady Bridges Friction Slope Method= 1
Parabolic Critical Depth
Global Vel Dist=  1 , 1 , 1
Global Log Level= 0
CheckData=True
Encroach Param= -1, 0, 0, 0
BEGIN DESCRIPTION:
Multiple Run
END DESCRIPTION:

--- MULBERRY CREEK TRIBUTARY 4_1.f01 (steady flow) ---

Flow Title=Multiple
Program Version=4.10
Number of Profiles= 7
Profile Names=10-year,25-year,50-year,1pct_min,100-year,1pct_plu,500-year
River Rch & RM=MULBERRY CREEK T,Reach-1         ,4956
     141     189     227     136     272     543     395
Boundary for River Rch & Prof#=MULBERRY CREEK T,Reach-1         , 1
Up Type= 0
Dn Type= 3
Dn Slope=0.00821
Boundary for River Rch & Prof#=MULBERRY CREEK T,Reach-1         , 2
Up Type= 0
Dn Type= 3
Dn Slope=0.00821
Boundary for River Rch & Prof#=MULBERRY CREEK T,Reach-1         , 3
Up Type= 0
Dn Type= 3
Dn Slope=0.00821
Boundary for River Rch & Prof#=MULBERRY CREEK T,Reach-1         , 4
Up Type= 0
Dn Type= 3
Dn Slope=0.00821
Boundary for River Rch & Prof#=MULBERRY CREEK T,Reach-1         , 5
Up Type= 0
Dn Type= 3
Dn Slope=0.00821
Boundary for River Rch & Prof#=MULBERRY CREEK T,Reach-1         , 6
Up Type= 0
Dn Type= 3
Dn Slope=0.00821
Boundary for River Rch & Prof#=MULBERRY CREEK T,Reach-1         , 7
Up Type= 0
Dn Type= 3
Dn Slope=0.00821
DSS Import GetInterval= 0
DSS Import GetPeak= 0
DSS Import FillOption= 0

--- MULBERRY CREEK TRIBUTARY 4_1.g01 (geometry) ---

Geom Title=Existing Conditions
Program Version=4.10

River Reach=MULBERRY CREEK T,Reach-1
Reach XY= 30
        1570355.        6870988.      1570258.54      6871139.46
      1570252.74      6871332.06      1570163.08       6871534.7
      1570203.08      6871682.28        1570104.      6871782.57
      1570154.48      6871903.21      1570156.24       6872227.5
       1570204.9       6872303.4      1570156.63      6872431.96
      1570296.93      6872634.69      1570256.84      6872731.88
      1570491.41      6872974.76       1570547.5        6873088.
      1570405.94      6873298.48      1570454.96      6873567.97
      1570357.24      6873743.93      1570355.38      6873973.11
      1570398.01      6874028.83      1570458.61      6873995.89
      1570504.07      6874048.16       1570501.6       6874136.7
      1570409.76      6874193.66      1570412.22      6874244.03
      1570532.13      6874314.17      1570568.64       6874401.2
      1570901.87      6874739.63      1570855.54      6874853.21
      1570854.59      6875103.17        1570905.        6875188.

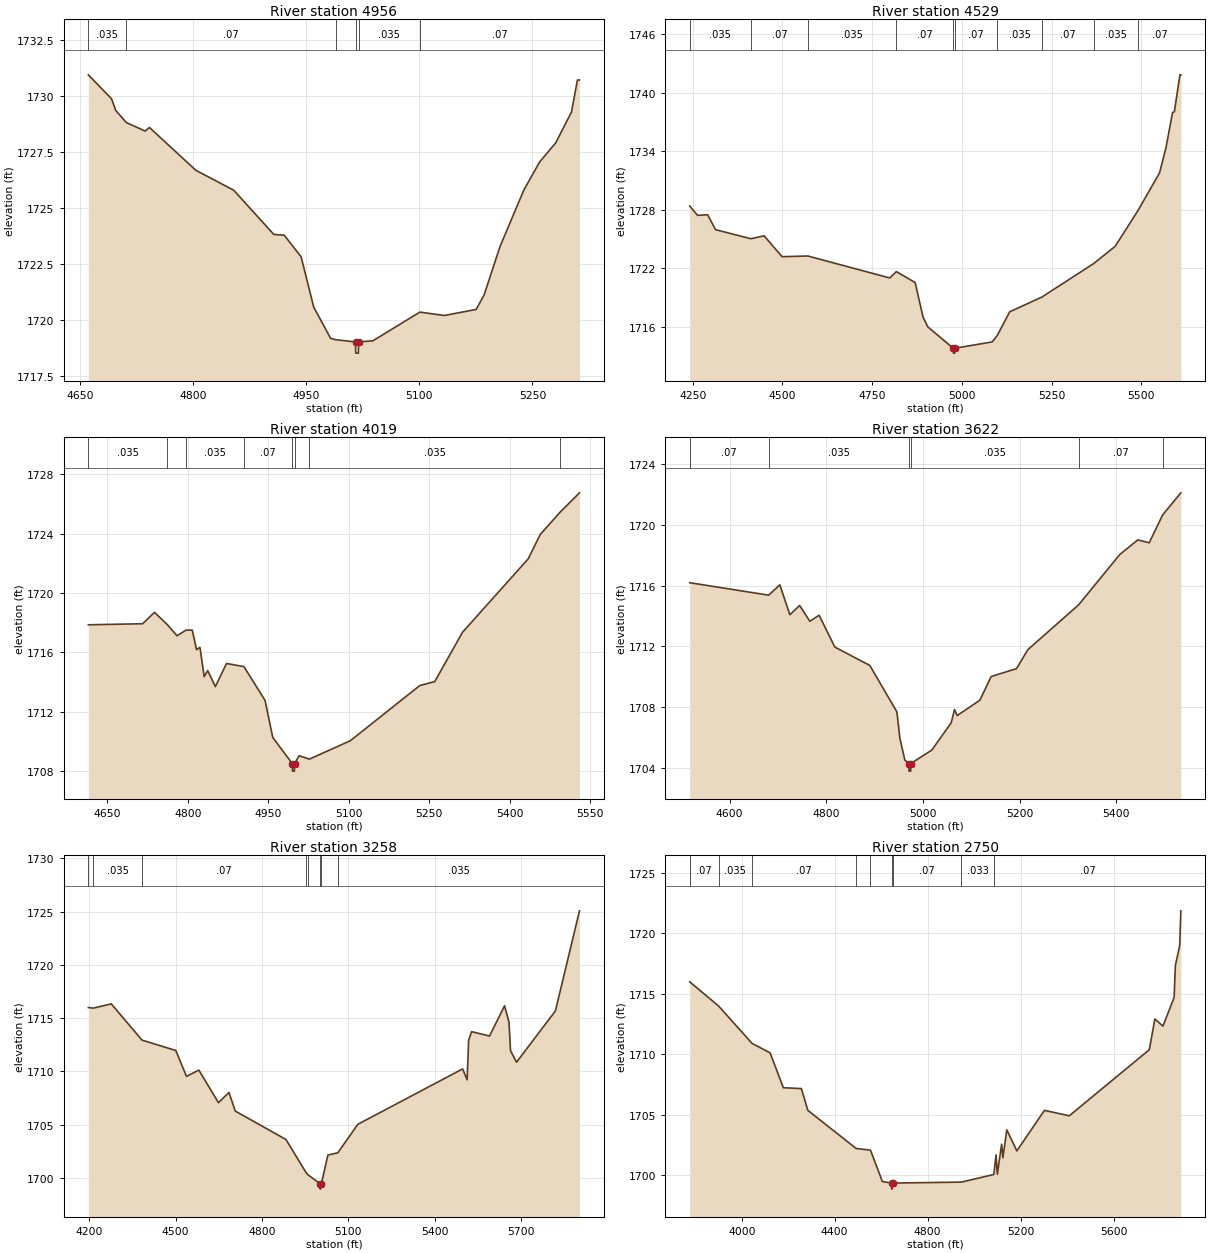
Type RM Length L Ch R = 1 ,4956    ,427,427,427
BEGIN DESCRIPTION:
MULBERRY CREEK TRIBUTARY 4_1 6.0
END DESCRIPTION:
XS GIS Cut Line= 3
      1570104.98      6870837.97        1570255.        6871138.
      1570555.03      6871238.01
#Sta/Elev= 30
  4660.7 1730.95  4691.5 1729.88  4697.1 1729.36  4711.1 1728.82  4736.2 1728.44
  4741.8  1728.6  4803.3 1726.69  4853.6  1725.8  4906.7 1723.83  4920.7 1723.79
    4943 1722.83  4959.8 1720.58  4982.2 1719.19  4988.7 1719.13  5015.2 1719.03
  5015.5 1718.53    5019 1718.53  5019.2 1719.03  5038.3 1719.08  5100.6 1720.36
  5133.2 1720.21  5175.3 1720.48  5185.9 1721.13    5207 1723.29  5238.6 1725.81
  5259.7 1727.07  5280.8 1727.91  5301.8 1729.29  5309.7 1730.72  5312.4 1730.72
#Mann= 6 ,-1 , 0
  4660.7    .035       0  4711.1     .07       0  4988.7    .035       0
  5015.2    .035       0  5019.2    .035       0  5100.6     .07       0
Bank Sta=5015.2,5019.2
XS Rating Curve= 0 ,0
Exp/Cntr=0.3,0.1

Type RM Length L Ch R = 1 ,4529    ,510,510,510
BEGIN DESCRIPTION:
MULBERRY CREEK TRIBUTARY 4_1 5.0
END DESCRIPTION:
XS GIS Cut Line= 3
      1569705.01      6870938.01        1570155.        6871538.
      1570755.05      6871387.99
#Sta/Elev= 30
  4241.9  1728.4  4263.8 1727.45  4291.9 1727.51  4313.8 1725.98  4412.5 1725.05
  4449.2 1725.35  4499.2 1723.21  4570.9 1723.28  4799.2 1721.03  4817.7 1721.68
    4870 1720.56  4891.9 1717.03  4905.4 1716.01  4976.3 1713.82  4976.6 1713.32
  4980.1 1713.32  4980.3 1713.82  5084.7 1714.47  5098.8 1715.13  5133.6 1717.56
  5223.2 1719.07  5367.3  1722.5  5427.4 1724.27  5491.7 1727.99  5551.1 1731.81
  5569.1 1734.41  5587.2 1737.99  5592.3 1738.07  5607.8 1741.86  5610.4 1741.86
#Mann= 10 ,-1 , 0
  4241.9    .035       0  4412.5     .07       0  4570.9    .035       0
  4817.7     .07       0  4976.3     .07       0  4980.3     .07       0
  5098.8    .035       0  5223.2     .07       0  5367.3    .035       0
  5491.7     .07       0
Bank Sta=4976.3,4980.3
XS Rating Curve= 0 ,0
Exp/Cntr=0.3,0.1

Type RM Length L Ch R = 1 ,4019    ,397,397,397
BEGIN DESCRIPTION:
MULBERRY CREEK TRIBUTARY 4_1 4.0
END DESCRIPTION:
XS GIS Cut Line= 3
      1569857.13      6871712.76      1570155.27      6871957.15
      1570630.68      6871723.33
#Sta/Elev= 30
  4614.5 1717.86  4715.6 1717.93  4737.8  1718.7  4761.7 1717.87  4779.8 1717.12
  4796.6  1717.5  4808.2  1717.5  4816.1 1716.18  4822.5 1716.34  4830.4 1714.36
  4836.9 1714.77  4851.2 1713.69    4872 1715.25  4904.4 1715.04  4943.8 1712.76
  4958.2 1710.26  4994.7 1708.49    4995 1707.99  4998.5 1707.99  4998.7 1708.49
  5007.3 1709.03  5026.4  1708.8  5102.8 1710.04  5232.1 1713.76  5260.1 1714.03
  5311.7 1717.35  5434.3 1722.31  5456.6 1723.95  5494.1 1725.47  5529.8 1726.76
#Mann= 8 ,-1 , 0
  4614.5    .035       0  4761.7     .07       0  4796.6    .035       0
  4904.4     .07       0  4994.7     .07       0  4998.7     .07       0
  5026.4    .035       0  5494.1     .07       0
Bank Sta=4994.7,4998.7
XS Rating Curve= 0 ,0
Exp/Cntr=0.3,0.1

Type RM Length L Ch R = 1 ,3622    ,364,364,364
BEGIN DESCRIPTION:
MULBERRY CREEK TRIBUTARY 4_1 3.0
END DESCRIPTION:
XS GIS Cut Line= 3
      1569734.76      6872213.63        1570205.        6872338.
      1570690.84      6872127.22
#Sta/Elev= 30
  4517.5  1716.2  4680.8 1715.38  4703.9 1716.06  4724.6 1714.09  4744.9  1714.7
    4766 1713.66  4785.2 1714.06  4817.7 1711.96  4890.1 1710.75  4946.1 1707.69
  4952.2 1705.97  4962.5 1704.52  4970.9 1704.29  4971.1 1703.79  4974.6 1703.79
  4974.9 1704.29  5018.4 1705.18  5058.4 1706.97  5065.3 1707.85  5070.7 1707.45
  5117.7 1708.46  5141.1 1710.02  5193.5 1710.54    5217 1711.79  5321.9 1714.74
  5407.2 1718.06  5444.5 1719.02    5468 1718.83    5496 1720.67  5533.5 1722.12
#Mann= 6 ,-1 , 0
  4517.5     .07       0  4680.8    .035       0  4970.9    .035       0
  4974.9    .035       0  5321.9     .07       0    5496    .035       0
Bank Sta=4970.9,4974.9
XS Rating Curve= 0 ,0
Exp/Cntr=0.3,0.1

Type RM Length L Ch R = 1 ,3258    ,508,508,508
BEGIN DESCRIPTION:
Mapping XS 1e2c4127
END DESCRIPTION:
XS GIS Cut Line= 3
      1569584.56      6872390.53      1570094.98      6872692.62
      1571165.33      6872385.32
#Sta/Elev= 30
  4196.8 1715.99  4214.1 1715.93  4276.5 1716.33  4383.2 1712.93  4500.7 1711.95
  4537.8 1709.52  4580.8 1710.11    4649 1707.05  4685.4 1708.01  4707.5 1706.26
  4883.6 1703.59  4952.5 1700.52  4959.8 1700.28  5002.6 1699.43  5002.8 1698.93
  5006.6 1699.43  5029.2 1702.13  5063.7 1702.34  5133.3 1705.02  5497.4 1710.22
  5513.1  1709.2  5518.3 1712.91  5528.6 1713.72    5591 1713.31  5643.1 1716.15
  5658.5 1714.62  5663.9 1711.93  5684.7 1710.85  5819.9 1715.67  5903.5 1725.07
#Mann= 8 ,-1 , 0
  4196.8     .07       0  4214.1    .035       0  4383.2     .07       0
  4952.5    .035       0  4959.8     .07       0  5002.6     .07       0
  5006.6     .07       0  5063.7    .035       0
Bank Sta=5002.6,5006.6
XS Rating Curve= 0 ,0
Exp/Cntr=0.3,0.1

Type RM Length L Ch R = 1 ,2750    ,69,69,69
BEGIN DESCRIPTION:
Mapping XS 1aded5f9
END DESCRIPTION:
XS GIS Cut Line= 5
      1569516.88      6872492.11      1570235.61      6872859.29
      1570274.67      6873023.35      1570376.23      6873062.41
      1571327.86       6872672.4
#Sta/Elev= 30
  3776.4    1716  3900.4 1714.01  4044.3 1710.92  4122.4 1710.13  4179.1 1707.25
  4256.7 1707.18  4284.6 1705.38  4492.4 1702.23  4554.1 1702.09  4605.2  1699.5
  4645.3 1699.37  4645.5 1698.87  4649.3 1699.37  4945.4 1699.45  5084.8 1700.08
  5094.3  1701.7  5099.8  1700.1  5118.3 1702.58  5123.7 1701.46  5140.6 1703.77
  5183.8 1702.03  5302.5 1705.38  5409.3 1704.93  5753.6 1710.39  5777.6 1712.93
  5812.4 1712.34  5860.4 1714.71  5865.8 1717.35  5884.4    1719  5889.4 1721.87
#Mann= 9 ,-1 , 0
  3776.4     .07       0  3900.4    .035       0  4044.3     .07       0
  4492.4    .035       0  4554.1     .07       0  4645.3    .033       0
  4649.3     .07       0  4945.4    .033       0  5084.8     .07       0
Bank Sta=4645.3,4649.3
XS Rating Curve= 0 ,0
Exp/Cntr=0.3,0.1

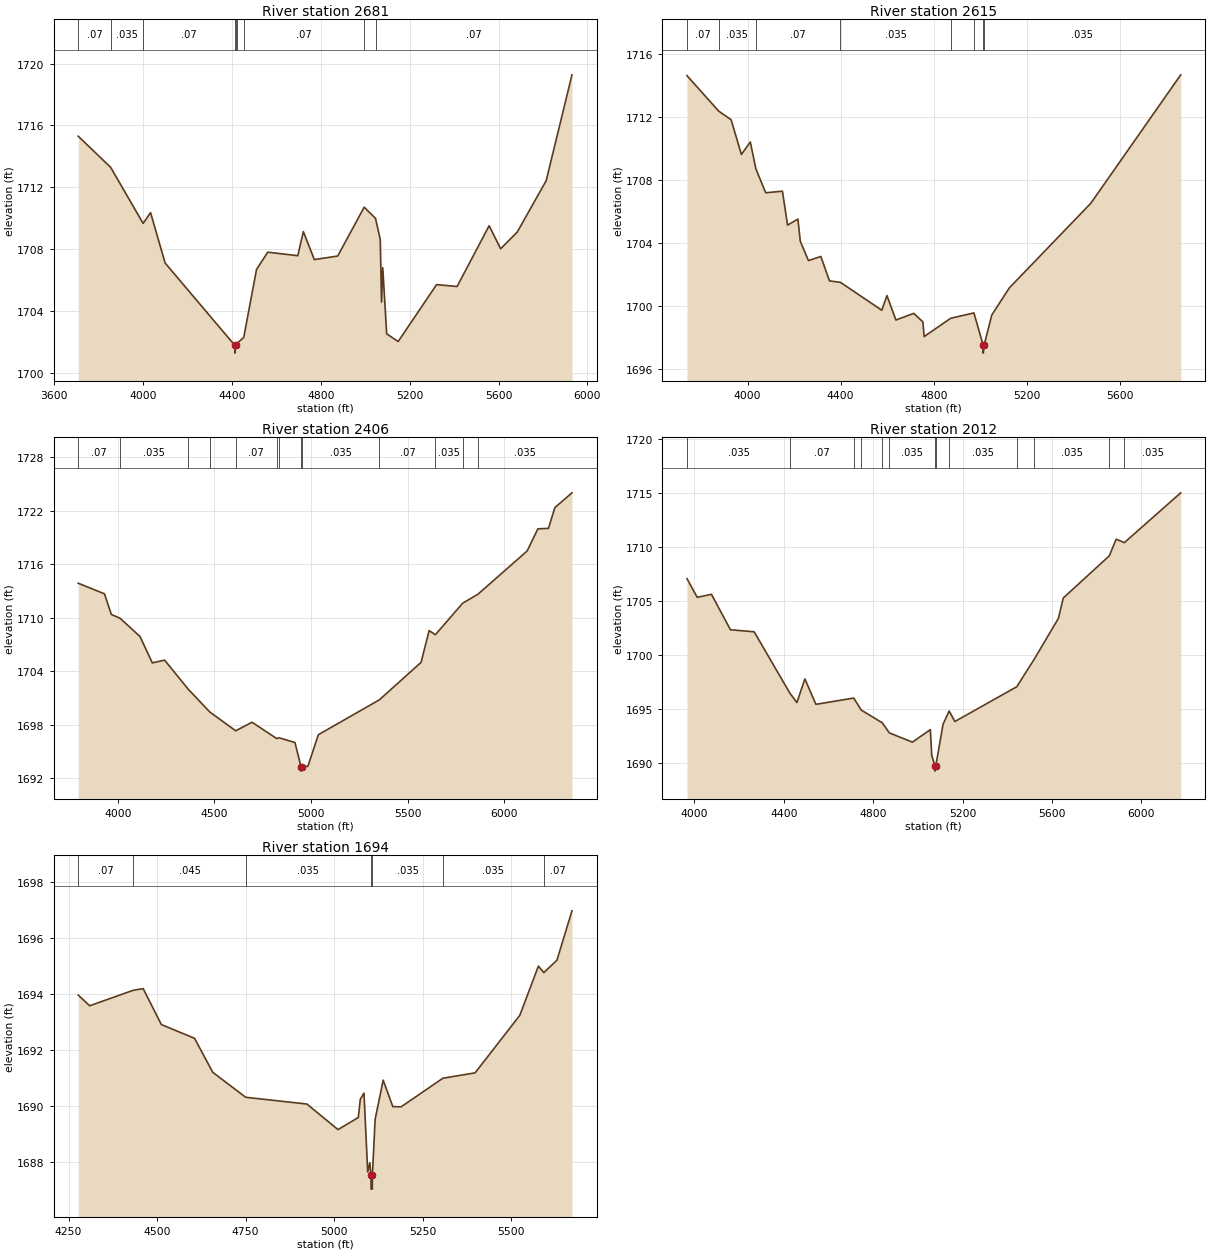
Type RM Length L Ch R = 1 ,2681    ,66,66,66
BEGIN DESCRIPTION:
Mapping XS ca35fdde
END DESCRIPTION:
XS GIS Cut Line= 6
      1569506.47      6872515.55      1570180.92      6872885.33
      1570217.38       6873054.6      1570318.94      6873114.49
      1570514.25      6873080.64      1571380.74      6872679.92
#Sta/Elev= 30
  3709.3  1715.3    3855 1713.29  4001.3 1709.66  4034.7 1710.36  4100.1  1707.1
  4413.8 1701.77  4414.1 1701.27  4417.8 1701.77  4425.1 1701.92  4453.9 1702.29
  4511.4 1706.68  4561.8  1707.8  4696.9 1707.57    4722 1709.13  4771.4 1707.32
  4876.5 1707.55  4995.6 1710.71  5046.6 1709.99    5068 1708.62  5073.7 1704.57
  5079.2  1706.8  5096.8 1702.52  5148.5 1702.02  5321.2  1705.7  5413.6 1705.58
  5557.7 1709.51  5609.4 1708.02  5684.2  1709.1  5814.3 1712.42  5930.4 1719.27
#Mann= 9 ,-1 , 0
  3709.3     .07       0    3855    .035       0  4001.3     .07       0
  4413.8    .035       0  4417.8     .07       0  4425.1    .035       0
  4453.9     .07       0  4995.6    .035       0  5046.6     .07       0
Bank Sta=4413.8,4417.8
XS Rating Curve= 0 ,0
Exp/Cntr=0.3,0.1

Type RM Length L Ch R = 1 ,2615    ,209,209,209
BEGIN DESCRIPTION:
Mapping XS bbb87f8c
END DESCRIPTION:
XS GIS Cut Line= 6
      1569523.44       6872573.9       1570124.6      6872890.76
      1570202.72      6873125.13      1570317.74       6873164.2
      1570519.56      6873122.96      1571305.15      6872764.89
#Sta/Elev= 30
    3740 1714.61  3876.2 1712.36  3929.7 1711.81  3973.7 1709.61  4012.1  1710.4
  4035.9  1708.7  4078.2 1707.18    4150 1707.28    4172 1705.13  4216.5 1705.51
  4226.8  1704.1  4261.7 1702.88  4314.9 1703.14  4352.2 1701.59    4399  1701.5
  4576.7 1699.73  4598.8 1700.66  4637.3 1699.11  4713.8 1699.53  4753.3 1698.99
  4758.6 1698.06  4872.6 1699.22  4972.3 1699.56  5012.1 1697.51  5012.4 1697.01
  5016.1 1697.51  5048.9 1699.42    5124 1701.14  5474.7 1706.52  5860.5 1714.66
#Mann= 8 ,-1 , 0
    3740     .07       0  3876.2    .035       0  4035.9     .07       0
    4399    .035       0  4872.6     .07       0  4972.3    .035       0
  5012.1    .035       0  5016.1    .035       0
Bank Sta=5012.1,5016.1
XS Rating Curve= 0 ,0
Exp/Cntr=0.3,0.1

Type RM Length L Ch R = 1 ,2406    ,394,394,394
BEGIN DESCRIPTION:
Mapping XS c9c353ff
END DESCRIPTION:
XS GIS Cut Line= 3
      1569519.44      6872621.42      1570217.38       6873345.4
      1571704.34       6872907.9
#Sta/Elev= 30
    3795 1713.87  3930.8 1712.68  3966.3 1710.37  4012.2 1709.93  4114.7  1707.9
  4178.5 1704.94  4242.1 1705.25  4364.9 1701.98  4476.4 1699.43  4610.1 1697.33
  4694.6 1698.29    4823 1696.45  4832.1 1696.56  4916.7 1696.02    4948 1693.31
  4948.3 1692.81    4952 1693.31  4983.4 1693.34  5037.9 1696.89  5353.7  1700.8
  5569.5    1705  5611.2 1708.56  5643.6  1708.1  5784.8 1711.63  5863.6 1712.63
  6118.4 1717.48  6174.1 1719.96  6228.8 1720.02  6262.2 1722.35  6350.6    1724
#Mann= 13 ,-1 , 0
    3795     .07       0  4012.2    .035       0  4364.9     .07       0
  4476.4    .035       0  4610.1     .07       0    4823    .045       0
  4832.1    .035       0    4948    .035       0    4952    .035       0
  5353.7     .07       0  5643.6    .035       0  5784.8     .07       0
  5863.6    .035       0
Bank Sta=4948,4952
XS Rating Curve= 0 ,0
Exp/Cntr=0.3,0.1

Type RM Length L Ch R = 1 ,2012    ,318,318,318
BEGIN DESCRIPTION:
Mapping XS 93953d1f
END DESCRIPTION:
XS GIS Cut Line= 3
      1569709.46      6872888.44      1570407.39      6873652.34
      1571438.63      6873089.84
#Sta/Elev= 30
  3966.9 1707.04  4012.9 1705.31  4076.5 1705.59  4161.6 1702.31  4267.6 1702.12
  4428.1 1696.42  4458.8 1695.58  4494.6 1697.76  4543.9 1695.41  4713.1 1695.99
  4746.6 1694.88  4840.9  1693.7  4872.4 1692.77  4975.6 1691.91  5055.9 1693.07
  5062.2 1690.68  5076.4 1689.73  5076.6 1689.23  5080.4 1689.73  5112.8 1693.57
  5140.1 1694.79  5165.7 1693.82  5442.8 1697.04    5520 1699.56  5628.9 1703.36
  5650.8 1705.25  5856.7 1709.15  5887.4 1710.69    5924 1710.37  6176.3 1714.98
#Mann= 13 ,-1 , 0
  3966.9    .035       0  4428.1     .07       0  4713.1    .045       0
  4746.6     .07       0  4840.9    .045       0  4872.4    .035       0
  5076.4    .035       0  5080.4    .035       0  5140.1    .035       0
  5442.8     .07       0    5520    .035       0  5856.7     .07       0
    5924    .035       0
Bank Sta=5076.4,5080.4
XS Rating Curve= 0 ,0
Exp/Cntr=0.3,0.1

Type RM Length L Ch R = 1 ,1694    ,0,0,0
BEGIN DESCRIPTION:
MULBERRY CREEK TRIBUTARY 4_1 1.0
END DESCRIPTION:
XS GIS Cut Line= 3
      1569962.12      6873346.42      1570354.51      6873953.32
      1570995.53      6873752.66
#Sta/Elev= 30
  4277.3 1693.96  4309.6 1693.58  4432.6 1694.13  4460.7 1694.19  4512.1 1692.91
  4605.8 1692.42  4657.2 1691.21  4750.3 1690.32  4923.1 1690.08    5011 1689.17
  5068.3  1689.6  5073.9 1690.25  5084.3 1690.47  5094.8 1687.66  5100.8 1687.99
    5104 1687.55  5104.3 1687.05  5107.8 1687.05    5108 1687.55  5115.8 1689.54
  5138.5 1690.93  5165.7 1689.99  5189.1 1689.98  5307.3    1691  5398.1 1691.19
  5524.4 1693.24  5576.8 1694.99  5592.1 1694.76  5629.2  1695.2  5671.7 1696.96
#Mann= 7 ,-1 , 0
  4277.3     .07       0  4432.6    .045       0  4750.3    .035       0
    5104    .035       0    5108    .035       0  5307.3    .035       0
  5592.1     .07       0
Bank Sta=5104,5108
XS Rating Curve= 0 ,0
Exp/Cntr=0.3,0.1

Chan Stop Cuts=-1
Use User Specified Reach Order=0
Composite Channel Slope=5