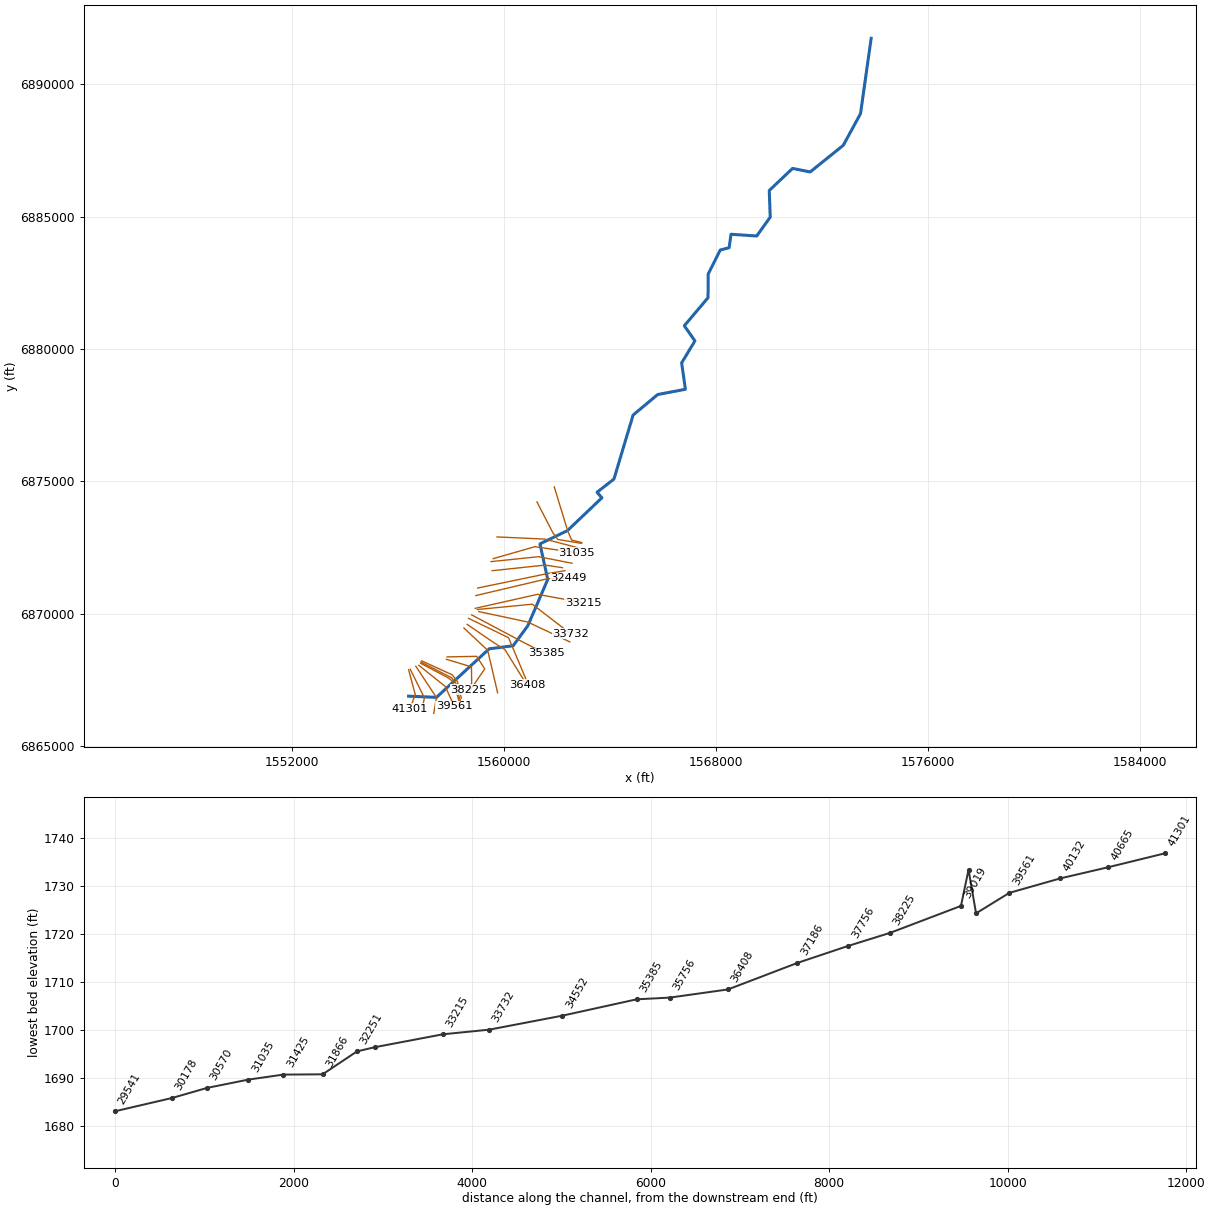
--- MULBERRY CREEK TRIBUTARY 5.prj (project) ---

Proj Title=MULBERRY CREEK TRIBUTARY 5 Base Level Engineering
Current Plan=p01
Default Exp/Contr=0.3,0.1
English Units
Geom File=g01
Flow File=f01
Plan File=p01
Y Axis Title=Elevation
X Axis Title(PF)=Main Channel Distance
X Axis Title(XS)=Station
BEGIN DESCRIPTION:
FMULBERRY CREEK TRIBUTARY 5
END DESCRIPTION:
DSS Export Rating Curves= 0
DSS Export Rating Curve Sorted= 0
DSS Export Volume Flow Curves= 0
DXF OffsetX= 0
DXF OffsetY= 0
DXF ScaleX= 1
DXF ScaleY= 10

--- MULBERRY CREEK TRIBUTARY 5.p01 (plan) ---

Plan Title=Multiple Run
Short Identifier=Multiple
Geom File=g01
Flow File=f01
Subcritical Flow
K Sum by GR= 0
Std Step Tol= 0.01
Critical Tol= 0.01
Num of Std Step Trials= 20
Max Error Tol= 0.3
Flow Tol Ratio= 0.001
Split Flow NTrial= 30
Split Flow Tol= 0.02
Split Flow Ratio= 0.02
Log Output Level= 0
Friction Slope Method= 1
Unsteady Friction Slope Method= 2
Unsteady Bridges Friction Slope Method= 1
Parabolic Critical Depth
Global Vel Dist=  1 , 1 , 1
Global Log Level= 0
CheckData=True
Encroach Param= -1, 0, 0, 0
BEGIN DESCRIPTION:
Multiple Run
END DESCRIPTION:

--- MULBERRY CREEK TRIBUTARY 5.f01 (steady flow) ---

Flow Title=Multiple
Program Version=4.10
Number of Profiles= 7
Profile Names=10-year,25-year,50-year,1pct_min,100-year,1pct_plu,500-year
River Rch & RM=MULBERRY CREEK T,Reach-1         ,41301
     243     339     418     258     514    1025     786
River Rch & RM=MULBERRY CREEK T,Reach-1         ,36408
     364     519     649     405     808    1611    1266
River Rch & RM=MULBERRY CREEK T,Reach-1         ,33215
     426     608     763     475     949    1893    1488
River Rch & RM=MULBERRY CREEK T,Reach-1         ,30178
     523     752     949     594    1186    2366    1879
River Rch & RM=MULBERRY CREEK T,Reach-1         ,22176
     745    1086    1382     873    1741    3474    2802
River Rch & RM=MULBERRY CREEK T,Reach-1         ,15979
     925    1357    1734    1098    2191    4372    3550
River Rch & RM=MULBERRY CREEK T,Reach-1         ,6166
     951    1396    1783    1129    2253    4495    3649
River Rch & RM=MULBERRY CREEK T,Reach-1         ,2586
     953    1398    1785    1129    2253    4496    3645
Boundary for River Rch & Prof#=MULBERRY CREEK T,Reach-1         , 1
Up Type= 0
Dn Type= 3
Dn Slope=0.00172
Boundary for River Rch & Prof#=MULBERRY CREEK T,Reach-1         , 2
Up Type= 0
Dn Type= 3
Dn Slope=0.00172
Boundary for River Rch & Prof#=MULBERRY CREEK T,Reach-1         , 3
Up Type= 0
Dn Type= 3
Dn Slope=0.00172
Boundary for River Rch & Prof#=MULBERRY CREEK T,Reach-1         , 4
Up Type= 0
Dn Type= 3
Dn Slope=0.00172
Boundary for River Rch & Prof#=MULBERRY CREEK T,Reach-1         , 5
Up Type= 0
Dn Type= 3
Dn Slope=0.00172
Boundary for River Rch & Prof#=MULBERRY CREEK T,Reach-1         , 6
Up Type= 0
Dn Type= 3
Dn Slope=0.00172
Boundary for River Rch & Prof#=MULBERRY CREEK T,Reach-1         , 7
Up Type= 0
Dn Type= 3
Dn Slope=0.00172
DSS Import GetInterval= 0
DSS Import GetPeak= 0
DSS Import FillOption= 0

--- MULBERRY CREEK TRIBUTARY 5.g01 (geometry) ---

Geom Title=Existing Conditions
Program Version=4.10

River Reach=MULBERRY CREEK T,Reach-1
Reach XY= 30
        1556405.        6866888.      1557457.29       6866843.1
        1559445.      6868676.76      1560349.56      6868793.09
      1560901.93       6869546.3      1561653.95      6871298.44
      1561360.72      6872640.58      1562399.44      6873142.81
      1563697.31      6874381.53      1563512.75      6874591.02
      1564151.85      6875089.17      1564874.61       6877508.2
      1565802.71      6878282.19      1566847.37      6878481.49
      1566705.93      6879477.53      1567205.43      6880308.18
      1566806.74      6880881.84      1567701.39       6881939.5
      1567706.28      6882831.96      1568160.71      6883740.58
      1568497.66      6883831.61      1568566.88      6884336.48
      1569538.71      6884271.26       1570047.4      6884984.67
      1570010.29      6885990.75      1570891.28      6886824.77
      1571553.54      6886690.99      1572802.09      6887695.91
      1573452.94      6888893.86        1573855.        6891738.

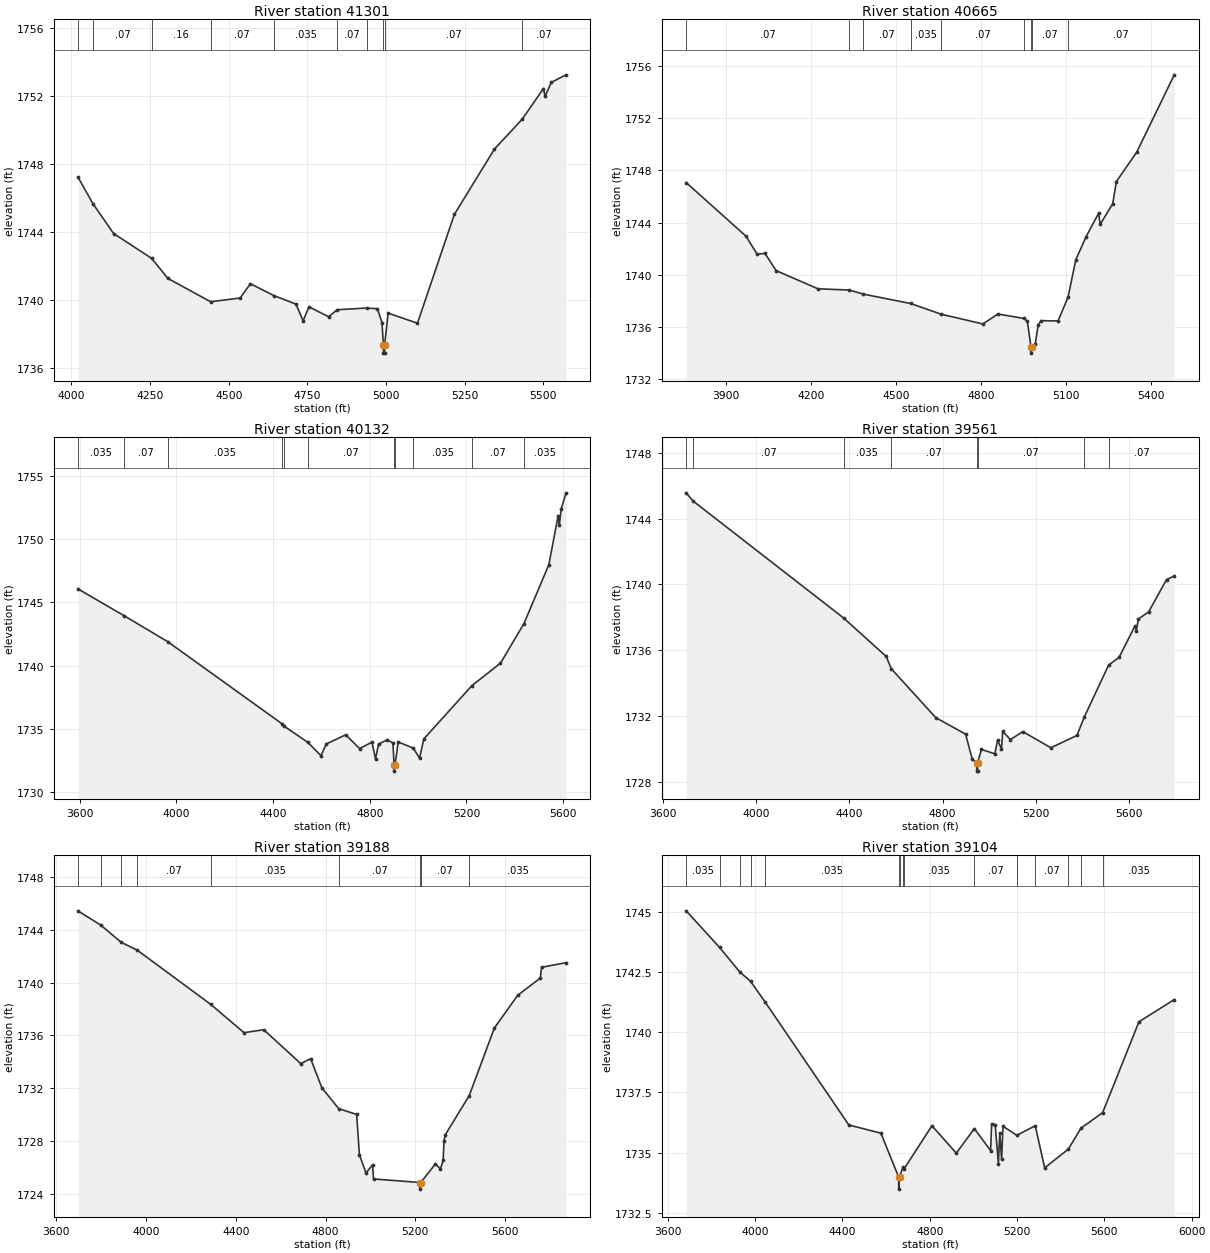
Type RM Length L Ch R = 1 ,41301   ,636,636,636
BEGIN DESCRIPTION:
MULBERRY CREEK TRIBUTARY 5 53.0
END DESCRIPTION:
XS GIS Cut Line= 3
       1556405.5      6867887.57      1556655.81      6866954.17
      1556455.81      6866404.18
#Sta/Elev= 30
  4020.7 1747.23  4068.8 1745.65  4134.1 1743.91  4255.2 1742.45  4306.7 1741.27
  4442.4  1739.9  4536.4 1740.12    4569 1740.96  4643.7 1740.26  4713.9 1739.76
  4736.4 1738.78  4755.3  1739.6  4817.5 1739.02  4844.9 1739.43  4938.2 1739.53
  4972.8 1739.49  4987.1 1738.68  4991.6 1737.38  4991.9 1736.88  4995.4 1736.88
  4995.6 1737.38  5006.8 1739.23    5100 1738.64  5217.1 1745.03  5344.8 1748.88
  5432.9 1750.63  5500.3 1752.43  5505.6 1751.98  5525.6  1752.8  5572.3 1753.24
#Mann= 10 ,-1 , 0
  4020.7    .035       0  4068.8     .07       0  4255.2     .16       0
  4442.4     .07       0  4643.7    .035       0  4844.9     .07       0
  4938.2     .07       0  4991.6     .07       0  4995.6     .07       0
  5432.9     .07       0
Bank Sta=4991.6,4995.6
XS Rating Curve= 0 ,0
Exp/Cntr=0.3,0.1

Type RM Length L Ch R = 1 ,40665   ,533,533,533
BEGIN DESCRIPTION:
Mapping XS 7efefea3
END DESCRIPTION:
XS GIS Cut Line= 3
      1556467.99      6867904.92      1557002.72      6866821.57
      1556895.08      6866318.08
#Sta/Elev= 30
  3758.7 1747.07  3969.7 1742.96    4009 1741.58    4037 1741.63  4076.3 1740.31
  4223.6 1738.92  4335.1 1738.82  4383.8 1738.51  4550.6 1737.79  4658.3 1736.97
  4805.8 1736.22  4859.3 1736.98  4951.6 1736.64    4963 1736.43  4975.7 1734.48
    4976 1733.98  4979.7 1734.48  4990.9 1734.68  5001.2 1736.14  5011.4 1736.47
  5071.6 1736.45  5106.9 1738.29  5134.1 1741.15  5170.5 1742.92  5214.9 1744.73
    5220 1743.86  5264.4 1745.45  5277.3 1747.15  5348.8 1749.39  5481.7 1755.34
#Mann= 9 ,-1 , 0
  3758.7     .07       0  4335.1    .035       0  4383.8     .07       0
  4550.6    .035       0  4658.3     .07       0  4951.6     .07       0
  4975.7     .07       0  4979.7     .07       0  5106.9     .07       0
Bank Sta=4975.7,4979.7
XS Rating Curve= 0 ,0
Exp/Cntr=0.3,0.1

Type RM Length L Ch R = 1 ,40132   ,571,571,571
BEGIN DESCRIPTION:
MULBERRY CREEK TRIBUTARY 5 52.0
END DESCRIPTION:
XS GIS Cut Line= 3
       1556679.8      6868016.03        1557455.        6866838.
        1557355.      6866237.99
#Sta/Elev= 30
  3593.4 1746.07  3784.2 1743.95  3964.6  1741.9  4438.1  1735.4  4446.3 1735.22
  4544.2 1733.94  4598.4 1732.89  4620.5 1733.82  4700.9 1734.54  4758.1 1733.45
  4809.3 1733.96    4824 1732.63  4836.4 1733.81  4872.5 1734.14  4895.9  1733.9
  4900.7 1732.17    4901 1731.67  4904.7 1732.17  4917.8 1733.97  4980.3 1733.49
  5006.1  1732.7  5023.9 1734.22  5222.3 1738.42  5340.7  1740.2  5437.6 1743.32
  5540.9 1747.99  5578.9 1751.83    5584 1751.12  5591.6 1752.38  5611.9 1753.66
#Mann= 11 ,-1 , 0
  3593.4    .035       0  3784.2     .07       0  3964.6    .035       0
  4438.1     .07       0  4446.3    .035       0  4544.2     .07       0
  4900.7     .07       0  4904.7     .07       0  4980.3    .035       0
  5222.3     .07       0  5437.6    .035       0
Bank Sta=4900.7,4904.7
XS Rating Curve= 0 ,0
Exp/Cntr=0.3,0.1

Type RM Length L Ch R = 1 ,39561   ,373,373,373
BEGIN DESCRIPTION:
Mapping XS 8036956a
END DESCRIPTION:
XS GIS Cut Line= 3
      1556792.44      6868052.99       1557785.5      6867257.84
      1558129.25      6866507.84
#Sta/Elev= 30
  3698.4 1745.57  3728.3 1745.07  4374.8 1737.96    4558 1735.62  4579.4 1734.88
  4770.8  1731.9  4898.9  1730.9  4927.7 1729.37  4946.5 1729.15  4946.8 1728.65
  4950.3 1728.65  4950.5 1729.15  4967.1 1729.97  5024.6  1729.7  5036.4 1730.53
  5053.1    1730  5058.6 1731.06  5091.4 1730.57  5145.1 1731.05  5265.6 1730.07
  5377.4 1730.82  5409.1 1731.94  5513.5  1735.1  5558.2 1735.56  5627.2 1737.49
  5632.7 1737.19  5641.4  1737.9  5685.4 1738.33  5762.4  1740.3  5795.6 1740.51
#Mann= 8 ,-1 , 0
  3698.4    .035       0  3728.3     .07       0  4374.8    .035       0
  4579.4     .07       0  4946.5     .07       0  4950.5     .07       0
  5409.1    .035       0  5513.5     .07       0
Bank Sta=4946.5,4950.5
XS Rating Curve= 0 ,0
Exp/Cntr=0.3,0.1

Type RM Length L Ch R = 1 ,39188   ,84,84,84
BEGIN DESCRIPTION:
Mapping XS 584052ef
END DESCRIPTION:
XS GIS Cut Line= 5
      1556863.87      6868127.11      1557877.72       6867592.4
      1558016.61      6867491.71      1558158.97       6867217.4
      1558311.26      6866691.32
#Sta/Elev= 30
  3697.1 1745.42  3798.8 1744.34  3890.6 1743.03    3961 1742.45  4289.3 1738.34
  4436.8 1736.21  4524.9 1736.43  4689.8 1733.87  4733.8 1734.24  4783.7 1732.04
    4859 1730.46  4938.6 1730.03  4951.1 1726.98  4980.3  1725.6  5009.7 1726.22
  5013.8 1725.15  5220.5 1724.88  5220.8 1724.38  5224.5 1724.88  5289.4 1726.28
    5312 1725.91  5323.9 1726.55    5328 1728.04  5333.7 1728.49  5440.2 1731.45
  5552.3 1736.56  5656.5 1739.04  5757.2 1740.34  5762.5 1741.15  5871.6  1741.5
#Mann= 9 ,-1 , 0
  3697.1    .035       0  3798.8     .07       0  3890.6    .035       0
    3961     .07       0  4289.3    .035       0    4859     .07       0
  5220.5     .07       0  5224.5     .07       0  5440.2    .035       0
Bank Sta=5220.5,5224.5
XS Rating Curve= 0 ,0
Exp/Cntr=0.3,0.1

Type RM Length L Ch R = 1 ,39104   ,85,85,85
BEGIN DESCRIPTION:
Mapping XS b24afb1d
END DESCRIPTION:
XS GIS Cut Line= 6
      1556870.82      6868175.72       1558030.5      6867581.99
      1558186.75      6867373.65      1558224.95      6867241.71
      1558273.56      6866977.82      1558356.89      6866724.34
#Sta/Elev= 30
  3684.1 1745.03  3837.5 1743.51  3929.1  1742.5    3979 1742.11  4044.2 1741.27
  4429.4 1736.15  4576.3 1735.81  4657.6 1733.99  4657.9 1733.49  4661.6 1733.99
  4677.3 1734.41  4683.2 1734.34  4810.1 1736.12  4921.7 1734.98  5004.3    1736
  5078.9 1735.09  5083.7 1736.21  5099.8 1736.16  5114.6 1734.54  5120.7 1735.83
  5129.3 1734.72  5135.5  1736.1    5199 1735.72  5283.5 1736.12  5326.5 1734.37
  5435.1 1735.15    5493 1736.02  5592.1 1736.66  5758.6 1740.43  5920.4 1741.35
#Mann= 15 ,-1 , 0
  3684.1    .035       0  3837.5     .07       0  3929.1    .035       0
    3979     .07       0  4044.2    .035       0  4657.6    .035       0
  4661.6    .035       0  4677.3     .07       0  4683.2    .035       0
  5004.3     .07       0    5199    .035       0  5283.5     .07       0
  5435.1    .035       0    5493     .07       0  5592.1    .035       0
Bank Sta=4657.6,4661.6
XS Rating Curve= 0 ,0
Exp/Cntr=0.3,0.1

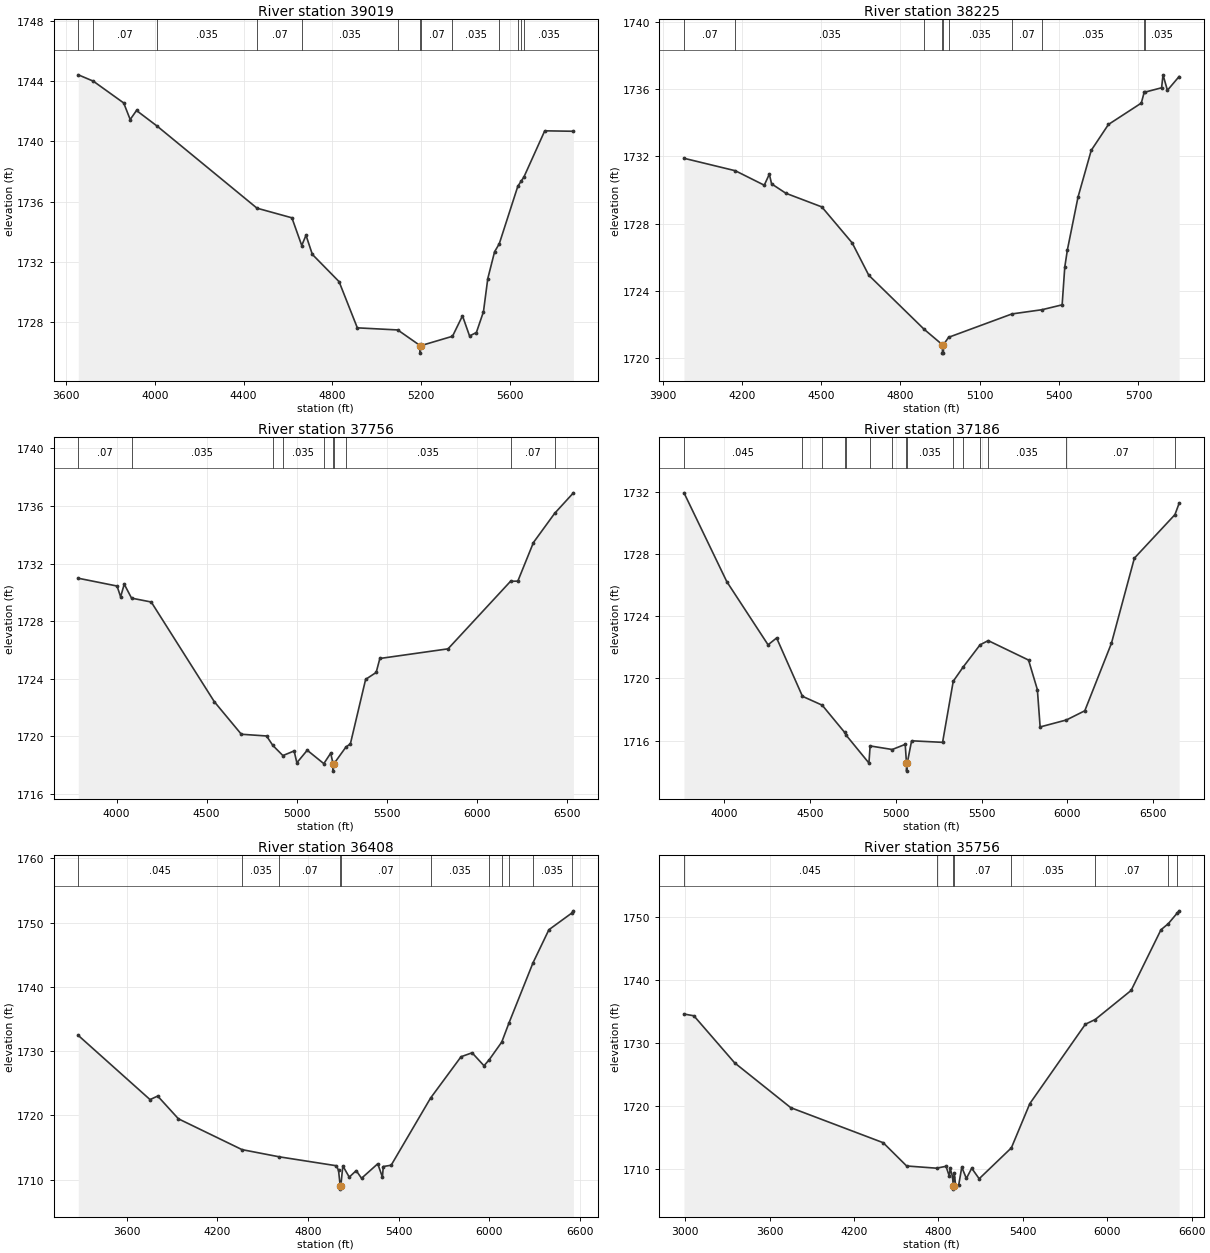
Type RM Length L Ch R = 1 ,39019   ,794,794,794
BEGIN DESCRIPTION:
Mapping XS e09e1d2d
END DESCRIPTION:
XS GIS Cut Line= 4
      1556898.58      6868220.86      1558047.86      6867696.57
      1558242.31      6867453.51      1558394.86      6866812.09
#Sta/Elev= 30
  3654.5 1744.42  3722.1    1744  3859.4 1742.55  3888.6 1741.45  3917.1 1742.05
  4010.4 1741.01  4460.8 1735.56  4618.2 1734.92  4662.6 1733.08  4681.8 1733.76
  4710.4 1732.49    4831 1730.68  4913.4 1727.61  5095.7 1727.47  5196.7 1726.43
  5196.9 1725.93  5200.7 1726.43  5342.7 1727.05  5387.8 1728.41  5419.7 1727.07
  5450.5  1727.3  5482.4 1728.68  5501.9 1730.88  5532.7 1732.67  5553.6 1733.19
  5637.5 1737.02  5653.6 1737.38  5664.9 1737.63  5758.9  1740.7  5888.3 1740.67
#Mann= 13 ,-1 , 0
  3654.5    .035       0  3722.1     .07       0  4010.4    .035       0
  4460.8     .07       0  4662.6    .035       0  5095.7     .07       0
  5196.7    .035       0  5200.7     .07       0  5342.7    .035       0
  5553.6     .07       0  5637.5    .035       0  5653.6     .07       0
  5664.9    .035       0
Bank Sta=5196.7,5200.7
XS Rating Curve= 0 ,0
Exp/Cntr=0.3,0.1

Type RM Length L Ch R = 1 ,38225   ,469,469,469
BEGIN DESCRIPTION:
Mapping XS 9bb2b100
END DESCRIPTION:
XS GIS Cut Line= 4
      1557836.05       6868279.9      1558777.03      6867995.18
      1558783.97      6867384.07      1558676.35      6867127.16
#Sta/Elev= 30
  3981.1 1731.89  4175.2 1731.15  4284.7 1730.29  4303.9 1730.95  4312.4 1730.37
  4366.6 1729.81  4502.4    1729  4617.3 1726.86    4680 1724.94  4889.9 1721.72
  4958.5 1720.81  4958.8 1720.31  4962.3 1720.31  4962.5 1720.81  4981.9 1721.25
  5221.7 1722.64  5335.2 1722.89  5411.4 1723.18  5421.4 1725.43  5431.4 1726.46
  5471.4 1729.58  5521.4 1732.36  5586.5  1733.9  5710.8 1735.17  5721.7 1735.81
  5724.3 1735.82  5787.6 1736.08    5793 1736.85  5809.6 1735.93  5853.9 1736.75
#Mann= 10 ,-1 , 0
  3981.1     .07       0  4175.2    .035       0  4889.9     .07       0
  4958.5    .035       0  4962.5     .07       0  4981.9    .035       0
  5221.7     .07       0  5335.2    .035       0  5721.7     .07       0
  5724.3    .035       0
Bank Sta=4958.5,4962.5
XS Rating Curve= 0 ,0
Exp/Cntr=0.3,0.1

Type RM Length L Ch R = 1 ,37756   ,570,570,570
BEGIN DESCRIPTION:
Mapping XS 20d024b3
END DESCRIPTION:
XS GIS Cut Line= 4
      1557860.04      6868371.57       1558974.6       6868392.4
      1559276.68      6867918.44      1558672.52      6867033.03
#Sta/Elev= 30
  3787.4 1730.98  4002.4 1730.44  4022.4 1729.69  4042.4 1730.57    4083  1729.6
  4192.4 1729.33  4542.5 1722.41  4692.5 1720.15  4832.5 1720.03  4867.6 1719.37
  4923.2 1718.67  4985.5 1718.99  5000.8 1718.17  5058.3 1719.04  5150.4 1718.11
  5188.7 1718.84  5201.8 1718.09  5202.1 1717.59  5205.8 1718.09  5273.6 1719.27
  5297.8 1719.48  5382.5 1723.96    5441 1724.44  5461.5 1725.41    5840 1726.08
  6187.1 1730.77  6227.4 1730.78  6314.1 1733.46  6432.2 1735.49  6536.1 1736.91
#Mann= 10 ,-1 , 0
  3787.4     .07       0    4083    .035       0  4867.6     .07       0
  4923.2    .035       0  5150.4     .07       0  5201.8    .035       0
  5205.8     .07       0  5273.6    .035       0  6187.1     .07       0
  6432.2    .035       0
Bank Sta=5201.8,5205.8
XS Rating Curve= 0 ,0
Exp/Cntr=0.3,0.1

Type RM Length L Ch R = 1 ,37186   ,778,778,778
BEGIN DESCRIPTION:
Mapping XS 0ff8e75b
END DESCRIPTION:
XS GIS Cut Line= 3
      1558490.23      6869465.31      1559388.33      6868621.53
       1559764.1      6867014.27
#Sta/Elev= 30
  3767.7 1731.93  4016.9 1726.22  4257.2 1722.16    4307  1722.6  4457.4 1718.85
  4572.3 1718.28  4702.3 1716.54  4712.6 1716.34  4844.5 1714.56  4851.4 1715.66
  4980.2 1715.43  5055.7 1715.76  5063.2 1714.54  5063.5 1714.04  5067.2 1714.54
    5093 1715.99  5273.3 1715.89  5335.4 1719.82    5393 1720.73  5491.7 1722.16
    5539 1722.43  5773.8 1721.18  5825.2 1719.28  5841.3 1716.88  5994.6 1717.33
  6101.4 1717.92  6256.5 1722.26    6390 1727.73  6626.3 1730.53  6650.6 1731.26
#Mann= 15 ,-1 , 0
  3767.7    .045       0  4457.4     .07       0  4572.3    .035       0
  4702.3     .07       0  4712.6    .035       0  4851.4     .07       0
  4980.2    .035       0  5063.2    .035       0  5067.2    .035       0
  5335.4     .07       0    5393    .035       0  5491.7     .07       0
    5539    .035       0  5994.6     .07       0  6626.3    .035       0
Bank Sta=5063.2,5067.2
XS Rating Curve= 0 ,0
Exp/Cntr=0.3,0.1

Type RM Length L Ch R = 1 ,36408   ,652,652,652
BEGIN DESCRIPTION:
Mapping XS b4f04071
END DESCRIPTION:
XS GIS Cut Line= 4
      1558615.26      6869600.71      1559521.47      6868975.74
      1560042.31       6868642.4      1560865.23      6867314.27
#Sta/Elev= 30
  3277.6 1732.44  3753.1 1722.45  3803.8    1723  3941.1 1719.46  4362.7 1714.66
  4609.5 1713.54  4988.1 1712.15  5002.3 1711.43  5013.5 1709.01  5013.8 1708.51
  5017.5 1709.01  5030.9 1712.13  5073.4 1710.38  5119.5 1711.39  5154.9  1710.2
  5262.4 1712.46  5293.2 1710.37  5299.1 1712.03  5351.1 1712.23  5612.1 1722.68
  5814.2 1729.12  5887.5 1729.74  5966.6 1727.72  6001.8 1728.68  6084.2 1731.41
    6131 1734.32  6291.2 1743.74  6396.7  1748.9  6548.7  1751.5  6559.2 1751.84
#Mann= 11 ,-1 , 0
  3277.6    .045       0  4362.7    .035       0  4609.5     .07       0
  5013.5     .07       0  5017.5     .07       0  5612.1    .035       0
  6001.8     .07       0  6084.2    .035       0    6131     .07       0
  6291.2    .035       0  6548.7     .07       0
Bank Sta=5013.5,5017.5
XS Rating Curve= 0 ,0
Exp/Cntr=0.3,0.1

Type RM Length L Ch R = 1 ,35756   ,371,371,371
BEGIN DESCRIPTION:
Mapping XS d53bc70d
END DESCRIPTION:
XS GIS Cut Line= 3
      1558670.79      6869825.56      1560175.99       6869096.4
      1560889.54      6867393.25
#Sta/Elev= 30
    2992 1734.65  3062.2 1734.37  3352.3 1726.88  3750.8 1719.76  4407.8 1714.19
  4574.5 1710.49  4786.9 1710.14  4854.3 1710.44  4878.1 1708.84  4883.5 1710.12
  4901.3 1708.74  4905.3 1707.31  4905.5 1706.81  4909.3 1707.31  4912.7 1709.42
    4923 1707.35  4944.7 1707.49  4966.4  1710.3  4998.9 1708.51    5037 1710.13
    5090 1708.46  5318.7 1713.37    5450 1720.41  5844.7 1733.03  5914.7 1733.78
  6169.8  1738.4  6382.1 1748.05  6433.9 1749.01  6495.8 1750.66  6511.1 1751.06
#Mann= 8 ,-1 , 0
    2992    .045       0  4786.9     .07       0  4905.3     .07       0
  4909.3     .07       0  5318.7    .035       0  5914.7     .07       0
  6433.9    .035       0  6495.8     .07       0
Bank Sta=4905.3,4909.3
XS Rating Curve= 0 ,0
Exp/Cntr=0.3,0.1

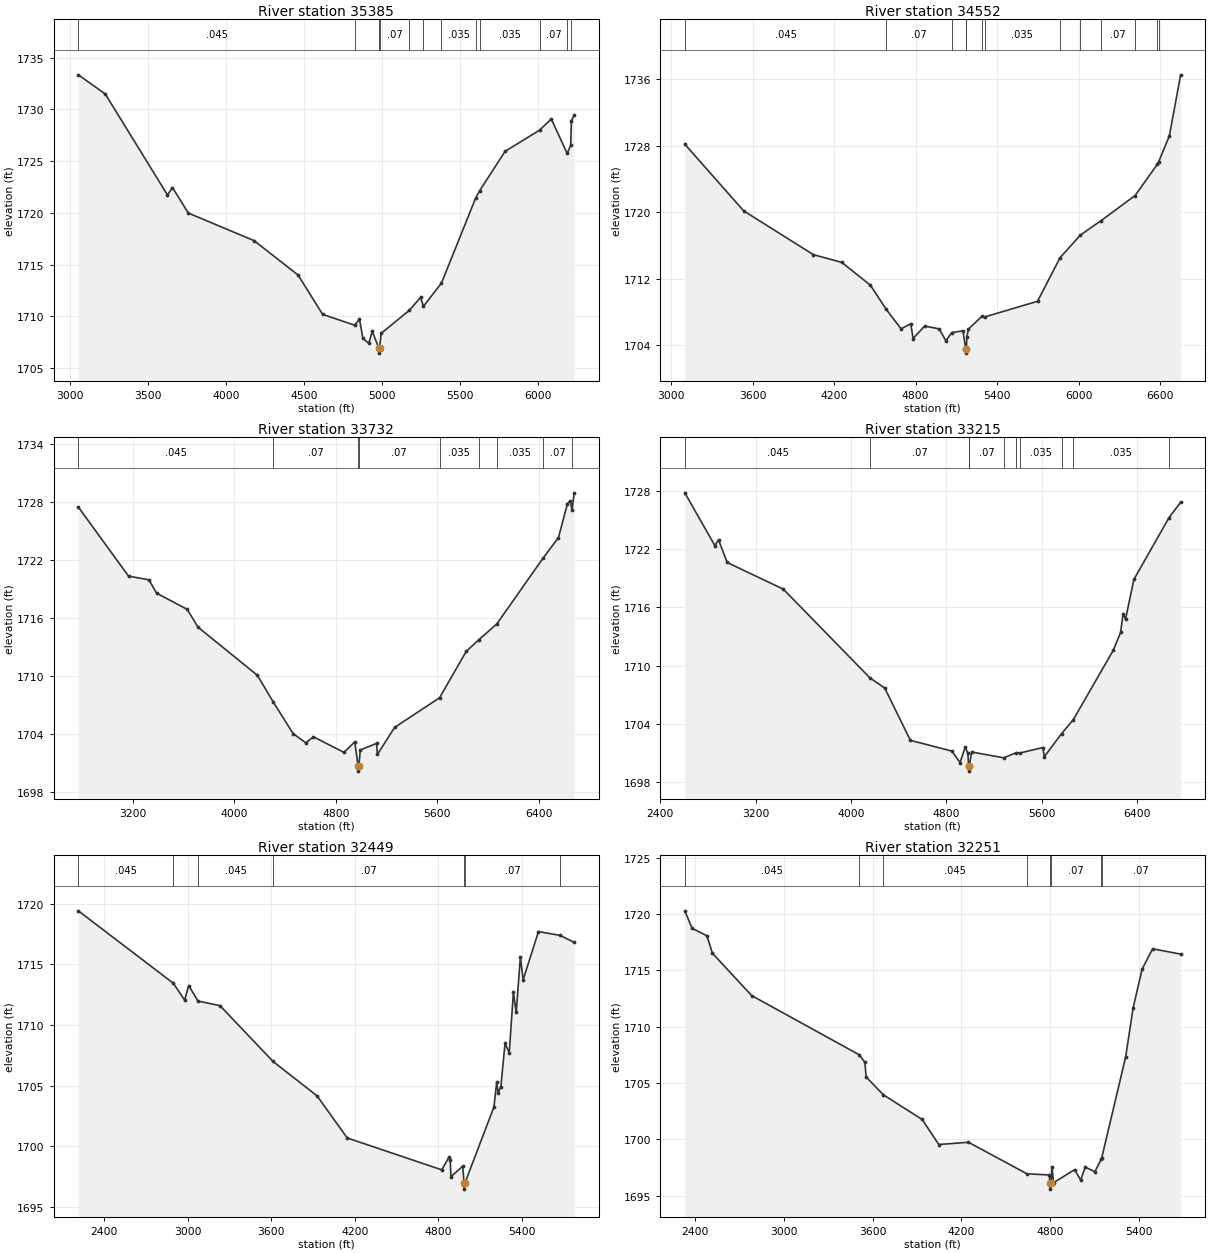
Type RM Length L Ch R = 1 ,35385   ,833,833,833
BEGIN DESCRIPTION:
Mapping XS e9a660a7
END DESCRIPTION:
XS GIS Cut Line= 4
       1558782.8      6869959.22      1560505.85      6869043.44
      1561248.04      6868657.16      1561603.98      6868505.23
#Sta/Elev= 30
  3054.1 1733.34  3226.5 1731.49  3624.9 1721.73  3656.8 1722.45  3758.7 1719.98
  4179.4 1717.32  4460.9    1714  4618.3  1710.2    4823 1709.15  4854.4 1709.72
  4876.4 1707.87  4913.8  1707.4  4936.5 1708.55  4978.1 1706.95  4978.4 1706.45
  4983.1 1706.95  4993.1 1708.36  5173.4 1710.58  5245.7 1711.84  5263.8 1710.97
  5379.6 1713.22  5597.9 1721.42  5624.6 1722.16    5787 1725.95  6007.4 1727.99
  6082.7 1729.07  6184.2 1725.75  6206.9 1726.52  6211.6 1728.91  6229.1 1729.43
#Mann= 12 ,-1 , 0
  3054.1    .045       0    4823     .07       0  4978.1     .07       0
  4983.1     .07       0  5173.4    .035       0  5263.8     .07       0
  5379.6    .035       0  5597.9     .07       0  5624.6    .035       0
  6007.4     .07       0  6184.2    .035       0  6206.9     .07       0
Bank Sta=4978.1,4983.1
XS Rating Curve= 0 ,0
Exp/Cntr=0.3,0.1

Type RM Length L Ch R = 1 ,34552   ,820,820,820
BEGIN DESCRIPTION:
Mapping XS ec064c46
END DESCRIPTION:
XS GIS Cut Line= 3
      1559049.27      6870084.24      1560898.21      6869689.28
      1562486.74      6868938.41
#Sta/Elev= 30
  3101.8 1728.19  3535.3 1720.16  4048.4 1714.89  4257.3 1713.96  4467.7 1711.21
  4583.2 1708.32  4692.6 1705.97  4764.2 1706.57  4781.3  1704.8  4866.5  1706.3
  4974.2 1705.96  5022.1 1704.53    5067 1705.52  5148.4 1705.72  5168.6 1703.54
    5169 1703.04  5173.7 1703.54  5176.9 1704.98    5188 1705.92  5288.6 1707.49
    5307 1707.39  5696.8 1709.28  5862.6 1714.53  6012.7 1717.26  6164.6 1718.99
  6414.4 1722.01  6579.3 1725.79  6588.4 1726.09  6666.6 1729.19  6749.5 1736.54
#Mann= 13 ,-1 , 0
  3101.8    .045       0  4583.2     .07       0    5067    .035       0
  5168.6     .07       0  5173.7    .035       0  5288.6     .07       0
    5307    .035       0  5862.6     .07       0  6012.7    .035       0
  6164.6     .07       0  6414.4    .035       0  6579.3     .07       0
  6588.4    .035       0
Bank Sta=5168.6,5173.7
XS Rating Curve= 0 ,0
Exp/Cntr=0.3,0.1

Type RM Length L Ch R = 1 ,33732   ,517,517,517
BEGIN DESCRIPTION:
Mapping XS ec959f9e
END DESCRIPTION:
XS GIS Cut Line= 3
      1559001.54      6870162.37      1561071.82      6870362.02
      1562517.15      6869246.55
#Sta/Elev= 30
  2772.8 1727.45  3168.1  1720.3  3328.8 1719.92  3389.1 1718.54  3630.2 1716.86
  3716.3 1715.01  4182.8 1710.04  4306.3 1707.32  4464.1 1704.01  4564.5 1703.05
  4624.8 1703.67  4865.2 1702.06  4950.4 1703.15  4976.6 1700.62  4977.1 1700.12
  4982.1 1700.62  4993.9 1702.31    5122 1702.99  5128.8 1701.85  5263.7 1704.64
  5618.2 1707.71  5828.1 1712.51  5927.7 1713.72  6069.1 1715.35  6434.9 1722.19
  6554.5 1724.28  6625.2 1727.78  6647.8  1728.1  6661.8 1727.11  6678.4 1728.92
#Mann= 9 ,-1 , 0
  2772.8    .045       0  4306.3     .07       0  4976.6     .07       0
  4982.1     .07       0  5618.2    .035       0  5927.7     .07       0
  6069.1    .035       0  6434.9     .07       0  6661.8    .035       0
Bank Sta=4976.6,4982.1
XS Rating Curve= 0 ,0
Exp/Cntr=0.3,0.1

Type RM Length L Ch R = 1 ,33215   ,766,766,766
BEGIN DESCRIPTION:
Mapping XS 87bb760d
END DESCRIPTION:
XS GIS Cut Line= 3
      1558919.05      6870205.77      1561271.47      6870735.28
      1562990.13      6870418.46
#Sta/Elev= 30
    2606  1727.8  2858.1 1722.37  2888.9 1722.96  2961.7 1720.63  3432.1 1717.89
  4160.2 1708.74  4283.1 1707.71  4498.1 1702.33  4846.6 1701.22  4914.5 1700.04
  4957.8 1701.62  4979.9 1701.02  4987.4 1699.66  4987.8 1699.16  4992.9 1699.66
  5011.3 1701.13  5281.1 1700.53  5386.7 1701.06  5417.3 1701.03  5610.6 1701.59
  5620.8 1700.63  5767.2 1703.03  5865.5 1704.47  6200.4 1711.61  6261.4 1713.43
  6281.8 1715.33  6302.9 1714.81  6373.3  1718.9  6668.2 1725.26  6764.9 1726.83
#Mann= 10 ,-1 , 0
    2606    .045       0  4160.2     .07       0  4987.4     .07       0
  4992.9     .07       0  5281.1    .035       0  5386.7     .07       0
  5417.3    .035       0  5767.2     .07       0  5865.5    .035       0
  6668.2     .07       0
Bank Sta=4987.4,4992.9
XS Rating Curve= 0 ,0
Exp/Cntr=0.3,0.1

Type RM Length L Ch R = 1 ,32449   ,198,198,198
BEGIN DESCRIPTION:
Mapping XS 9a3457cb
END DESCRIPTION:
XS GIS Cut Line= 3
      1558943.25      6870688.42       1561647.2      6871326.43
      1562431.41      6871343.76
#Sta/Elev= 30
  2213.5 1719.41  2895.7 1713.44  2977.2 1712.05  3006.4 1713.25  3072.8 1711.97
  3231.2 1711.59  3612.5 1706.99  3928.9 1704.15  4145.6 1700.68    4825 1698.05
  4876.4 1699.09  4885.6 1698.87  4890.8 1697.49  4975.4 1698.35  4985.1 1696.96
  4985.6 1696.46    4991 1696.96  5199.6 1703.23  5219.6  1705.3  5229.6 1704.41
  5249.6 1704.92  5279.6  1708.5  5309.6 1707.69  5339.6 1712.69  5359.6 1711.03
  5389.6 1715.58  5409.6 1713.73  5519.6  1717.7  5675.9 1717.38  5776.1 1716.81
#Mann= 7 ,-1 , 0
  2213.5    .045       0  2895.7    .035       0  3072.8    .045       0
  3612.5     .07       0  4985.1     .07       0    4991     .07       0
  5675.9    .035       0
Bank Sta=4985.1,4991
XS Rating Curve= 0 ,0
Exp/Cntr=0.3,0.1

Type RM Length L Ch R = 1 ,32251   ,385,385,385
BEGIN DESCRIPTION:
Mapping XS 2ef92810
END DESCRIPTION:
XS GIS Cut Line= 3
      1559012.15      6870972.96       1561640.6       6871518.1
       1562301.9      6871628.89
#Sta/Elev= 30
  2328.4 1720.29  2377.5 1718.74  2477.9 1718.08  2515.1 1716.53  2780.7 1712.77
    3509 1707.51  3546.6 1706.85  3555.7 1705.54    3672 1703.96  3934.7 1701.77
    4047 1699.55  4247.6 1699.75  4643.8 1696.95  4794.2 1696.85  4799.9 1696.09
  4800.4 1695.59  4805.8 1696.09    4813 1697.59  4823.2 1696.16  4966.2 1697.32
  5007.1 1696.39  5037.5 1697.54  5103.2 1697.14  5146.8 1698.26  5148.7 1698.32
  5311.3 1707.32    5362 1711.68  5422.8 1715.12  5493.8 1716.92  5683.3 1716.45
#Mann= 8 ,-1 , 0
  2328.4    .045       0    3509    .035       0    3672    .045       0
  4643.8     .07       0  4799.9     .07       0  4805.8     .07       0
  5146.8     .16       0  5148.7     .07       0
Bank Sta=4799.9,4805.8
XS Rating Curve= 0 ,0
Exp/Cntr=0.3,0.1

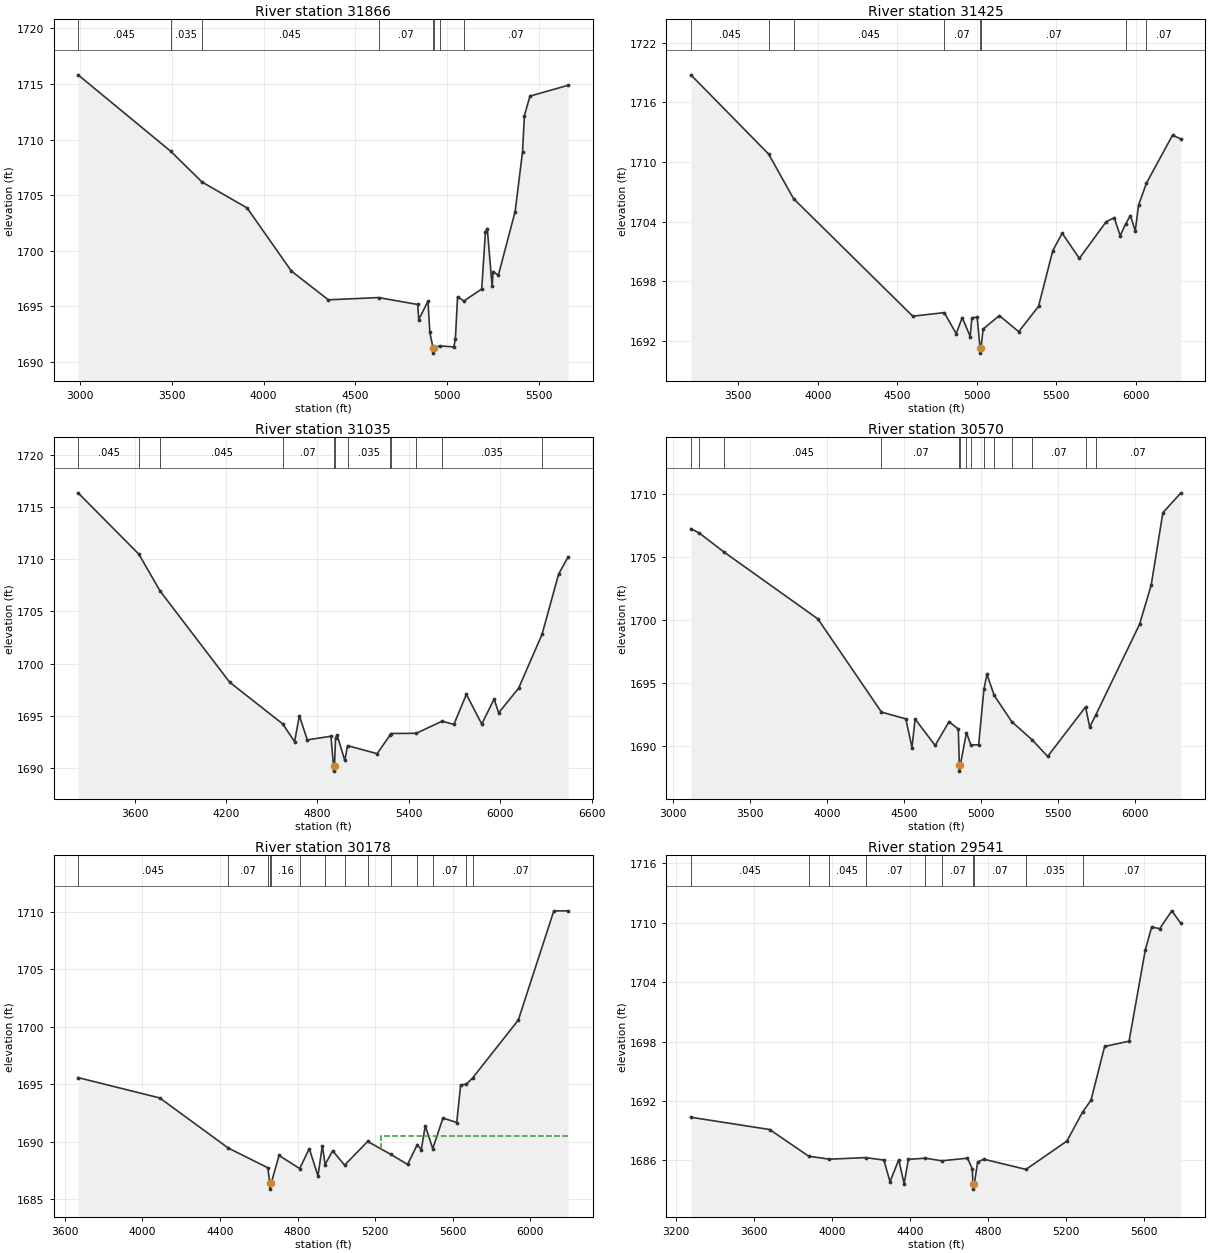
Type RM Length L Ch R = 1 ,31866   ,441,441,441
BEGIN DESCRIPTION:
Mapping XS 2b2f8b0e
END DESCRIPTION:
XS GIS Cut Line= 3
      1559558.98      6871627.47      1561559.87      6871840.15
      1562210.41       6871740.4
#Sta/Elev= 30
  2988.6 1715.81  3492.4 1708.96  3664.3 1706.18  3909.8 1703.85  4151.1 1698.18
  4352.3  1695.6  4626.6  1695.8  4839.3 1695.18    4845 1693.82  4895.3 1695.48
  4905.4 1692.68  4922.5 1691.31    4923 1690.81  4928.5 1691.31  4958.4 1691.46
  5036.3 1691.37  5044.6 1692.09  5056.5 1695.88  5090.6 1695.49  5188.1 1696.57
  5208.3 1701.68  5218.4    1702  5244.8  1696.8  5249.8  1698.1  5279.1 1697.83
  5370.2 1703.53  5410.6 1708.91  5420.7 1712.15  5451.1  1713.9  5658.9 1714.87
#Mann= 8 ,-1 , 0
  2988.6    .045       0  3492.4    .035       0  3664.3    .045       0
  4626.6     .07       0  4922.5     .07       0  4928.5     .07       0
  4958.4     .16       0  5090.6     .07       0
Bank Sta=4922.5,4928.5
XS Rating Curve= 0 ,0
Exp/Cntr=0.3,0.1

Type RM Length L Ch R = 1 ,31425   ,390,390,390
BEGIN DESCRIPTION:
Mapping XS 011c1cc6
END DESCRIPTION:
XS GIS Cut Line= 3
      1559515.65      6871970.36      1561308.14      6872156.99
      1562566.78       6871909.6
#Sta/Elev= 30
  3200.9 1718.78  3690.6  1710.8  3847.4 1706.31  4597.8 1694.47  4795.9 1694.83
  4871.1 1692.72  4909.4 1694.33  4959.6 1692.42  4969.8 1694.32  5003.1 1694.36
  5021.6 1691.25  5022.1 1690.75  5027.6 1691.25  5040.6 1693.17  5142.6 1694.53
  5264.9 1692.91  5389.5 1695.46  5478.9 1701.06  5538.6 1702.83  5646.5 1700.29
  5815.2 1703.98  5866.1 1704.39  5903.5 1702.58  5938.9 1703.79  5968.1 1704.61
  5998.6 1703.06    6019 1705.65  6069.1 1707.88    6233  1712.7  6285.8 1712.32
#Mann= 8 ,-1 , 0
  3200.9    .045       0  3690.6    .035       0  3847.4    .045       0
  4795.9     .07       0  5021.6     .07       0  5027.6     .07       0
  5938.9    .035       0  6069.1     .07       0
Bank Sta=5021.6,5027.6
XS Rating Curve= 0 ,0
Exp/Cntr=0.3,0.1

Type RM Length L Ch R = 1 ,31035   ,465,465,465
BEGIN DESCRIPTION:
Mapping XS f37626d7
END DESCRIPTION:
XS GIS Cut Line= 3
      1559598.06       6872083.2      1561169.25      6872534.59
      1562736.11      6872304.55
#Sta/Elev= 30
  3227.9 1716.34  3627.3 1710.47  3767.8 1706.92  4223.5 1698.22  4571.9 1694.23
  4650.1 1692.53  4681.3 1695.01  4733.4  1692.7  4888.7 1693.05  4905.6 1690.21
  4906.1 1689.71  4912.1 1690.21    4919 1692.89  4929.1 1693.17  4979.6 1690.73
  4997.8 1692.15  5191.9 1691.38    5278 1693.18  5283.2 1693.31    5449 1693.33
  5618.9 1694.49    5696 1694.18  5778.1 1697.06  5879.2 1694.21    5960  1696.6
  5990.4 1695.29  6121.7 1697.66  6275.3 1702.81  6383.8 1708.56  6446.3 1710.22
#Mann= 12 ,-1 , 0
  3227.9    .045       0  3627.3    .035       0  3767.8    .045       0
  4571.9     .07       0  4905.6    .035       0  4912.1     .07       0
  4997.8    .035       0    5278     .07       0  5283.2    .035       0
    5449     .07       0  5618.9    .035       0  6275.3     .07       0
Bank Sta=4905.6,4912.1
XS Rating Curve= 0 ,0
Exp/Cntr=0.3,0.1

Type RM Length L Ch R = 1 ,30570   ,392,392,392
BEGIN DESCRIPTION:
Mapping XS 39af9a32
END DESCRIPTION:
XS GIS Cut Line= 3
      1559741.25      6872903.52      1561546.85      6872821.05
      1562874.93      6872473.84
#Sta/Elev= 30
  3117.3 1707.22  3169.5 1706.91  3331.1 1705.39  3941.9 1700.06  4354.3 1692.66
  4512.5 1692.12  4552.5 1689.84  4572.6 1692.11  4702.7 1690.01  4792.8  1691.9
  4852.9 1691.31  4859.6 1688.47  4860.1 1687.97  4866.2 1688.47    4906 1691.03
  4934.2 1690.05  4984.9 1690.06  5019.4 1694.49  5038.7 1695.67  5085.7 1693.99
  5199.7  1691.9    5331 1690.47  5432.8 1689.14  5678.8 1693.07  5705.5 1691.48
  5743.4 1692.39    6029 1699.63  6104.7 1702.75  6180.5  1708.5  6297.5 1710.08
#Mann= 14 ,-1 , 0
  3117.3     .07       0  3169.5    .035       0  3331.1    .045       0
  4354.3     .07       0  4859.6     .07       0  4866.2     .07       0
    4906    .035       0  4934.2     .07       0  5019.4    .035       0
  5085.7     .07       0  5199.7    .035       0    5331     .07       0
  5678.8    .035       0  5743.4     .07       0
#XS Ineff= 2 , 0
       0                  5038.7       0 1695.67
Permanent Ineff=
       F       F
Bank Sta=4859.6,4866.2
XS Rating Curve= 0 ,0
Exp/Cntr=0.3,0.1

Type RM Length L Ch R = 1 ,30178   ,637,637,637
BEGIN DESCRIPTION:
Mapping XS 813dde4d
END DESCRIPTION:
XS GIS Cut Line= 4
      1561247.38      6874227.28      1561846.33       6873064.1
      1562032.96      6872808.03      1562921.32      6872660.69
#Sta/Elev= 30
  3668.8 1695.58  4089.7 1693.81  4442.8 1689.45  4646.8 1687.73  4657.2 1686.37
  4657.7 1685.87  4663.8 1686.37  4704.8  1688.8  4811.2 1687.66  4860.3 1689.39
  4905.3 1687.03  4927.8 1689.65  4942.1 1688.01  4980.9 1689.21  5042.5 1687.96
  5161.3 1690.02  5280.1  1688.9    5367 1688.02  5416.4 1689.72    5438 1689.32
  5458.3 1691.39  5496.7 1689.39  5549.5 1692.06  5620.4 1691.67  5640.7 1694.95
  5670.1    1695  5703.2 1695.57  5937.8 1700.59  6120.7 1710.09  6194.5  1710.1
#Mann= 14 ,-1 , 0
  3668.8    .045       0  4442.8     .07       0  4646.8     .16       0
  4657.2    .035       0  4663.8     .16       0  4811.2     .07       0
  4942.1    .035       0  5042.5     .07       0  5161.3    .035       0
  5280.1     .07       0  5416.4    .035       0  5496.7     .07       0
  5670.1    .035       0  5703.2     .07       0
#XS Ineff= 2 , 0
       0                    5232       0 1690.48
Permanent Ineff=
       F       F
Bank Sta=4657.2,4663.8
XS Rating Curve= 0 ,0
Exp/Cntr=0.3,0.1

Type RM Length L Ch R = 1 ,29541   ,749,749,749
BEGIN DESCRIPTION:
Mapping XS 10f20197
END DESCRIPTION:
XS GIS Cut Line= 4
      1561899.58      6874794.68      1562404.78      6873138.47
      1562555.82       6872784.3      1562940.62       6872690.7
#Sta/Elev= 30
  3277.6 1690.36  3681.9 1689.12  3881.8 1686.43  3987.7 1686.13  4173.2 1686.29
  4267.3 1686.04  4298.7 1683.86  4343.7 1686.07  4371.2 1683.65  4392.8 1686.11
  4478.1 1686.23    4564 1685.97    4696 1686.23  4720.4 1685.17    4724 1683.61
  4724.5 1683.11  4730.7 1683.61  4747.9 1685.84  4779.6 1686.13  4995.8  1685.1
  5205.8 1687.96    5286 1690.88  5329.4 1692.09  5399.1  1697.5  5524.3 1698.03
  5607.8 1707.25  5640.3 1709.55  5681.5 1709.38  5743.3 1711.18  5790.2 1709.91
#Mann= 10 ,-1 , 0
  3277.6    .045       0  3881.8     .07       0  3987.7    .045       0
  4173.2     .07       0  4478.1    .035       0    4564     .07       0
    4724    .035       0  4730.7     .07       0  4995.8    .035       0
    5286     .07       0
Bank Sta=4724,4730.7
XS Rating Curve= 0 ,0
Exp/Cntr=0.3,0.1