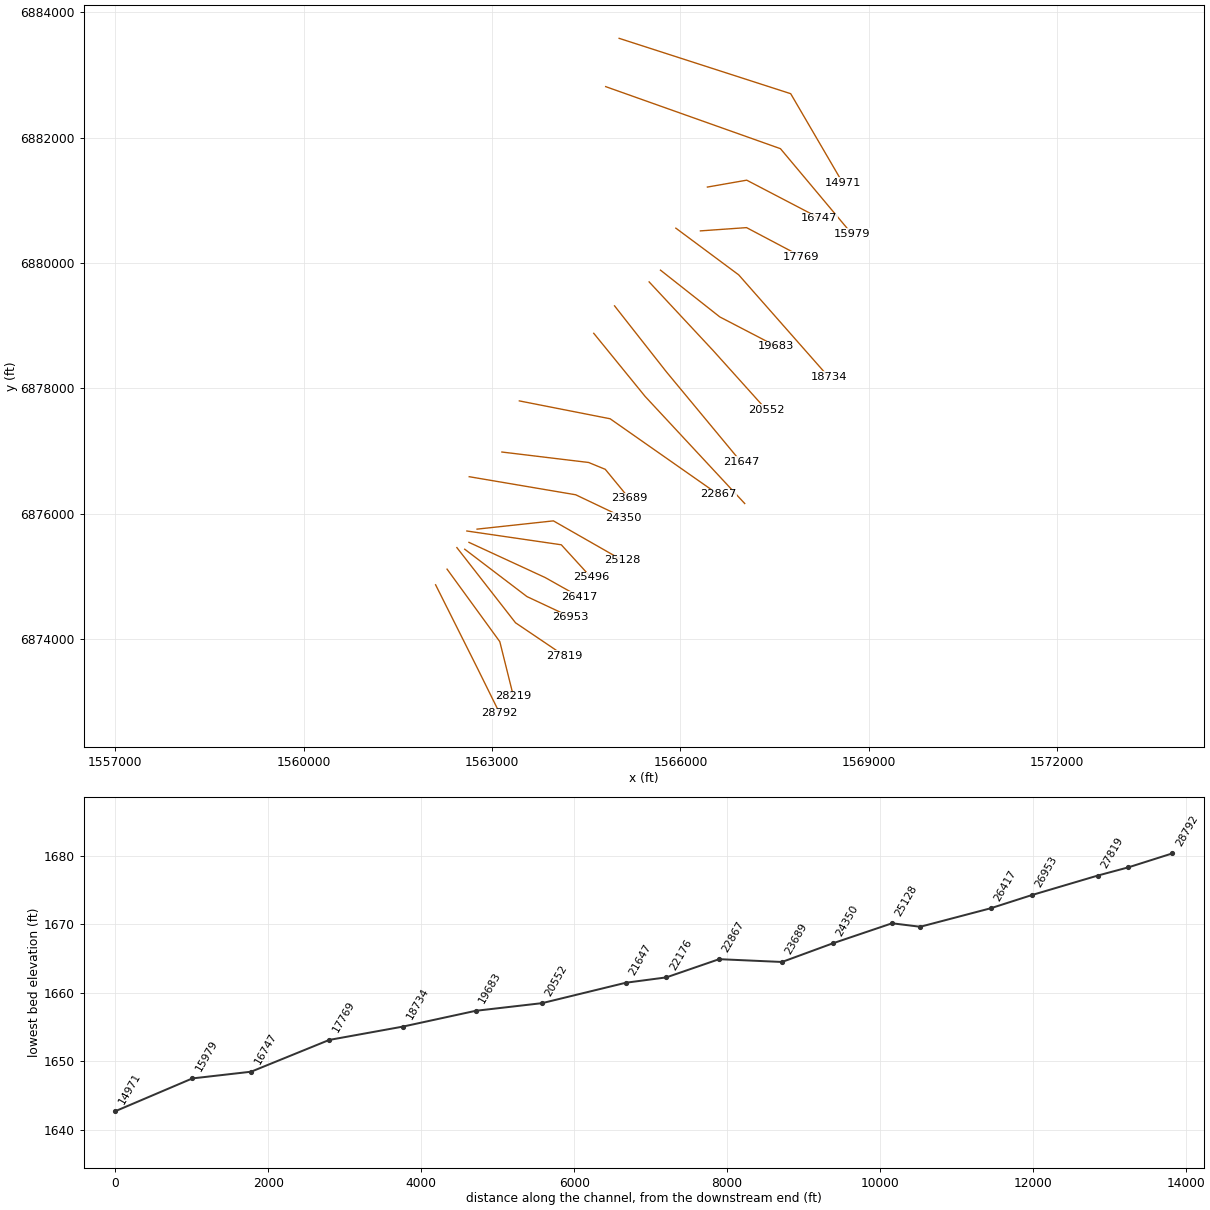
HEC-RAS study MULBERRY CREEK TRIBUTARY 5.prj: MULBERRY CREEK TRIBUTARY 5 Base Level Engineering

--- MULBERRY CREEK TRIBUTARY 5.g01 (geometry) --- (continued)

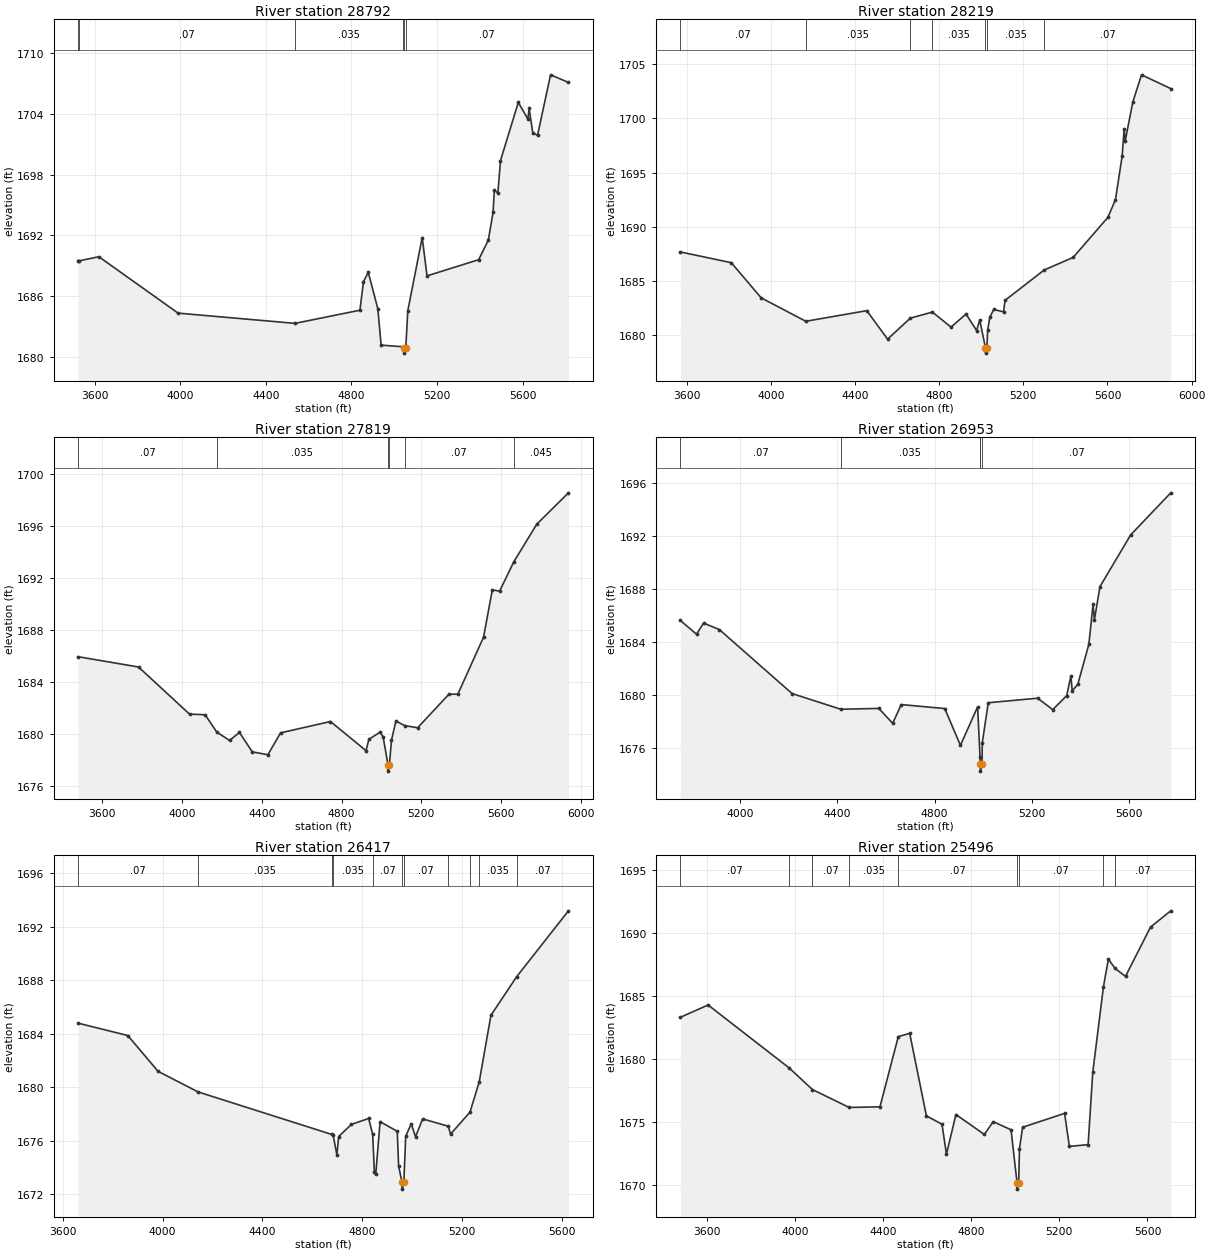
Type RM Length L Ch R = 1 ,28792   ,573,573,573
BEGIN DESCRIPTION:
MULBERRY CREEK TRIBUTARY 5 30.0
END DESCRIPTION:
XS GIS Cut Line= 3
      1562102.85      6874865.11      1562763.52      6873543.66
      1563123.69      6872813.01
#Sta/Elev= 30
  3522.6 1689.51  3525.9 1689.48    3620 1689.89  3990.2 1684.32  4536.6 1683.31
  4839.9 1684.61  4856.7 1687.43    4879 1688.35  4923.8 1684.74  4939.2 1681.16
  5040.1    1681  5047.6 1680.87  5048.1 1680.37  5054.3 1680.87  5063.8 1684.56
  5131.1 1691.79  5153.6    1688    5395  1689.6    5440 1691.52  5462.4 1694.27
    5468 1696.44  5484.9  1696.2  5496.9 1699.38  5580.3 1705.14  5625.2 1703.48
  5630.8 1704.56  5647.7 1702.16  5670.1 1701.88    5731 1707.86  5814.6 1707.11
#Mann= 6 ,-1 , 0
  3522.6    .045       0  3525.9     .07       0  4536.6    .035       0
  5040.1     .07       0  5047.6    .035       0  5054.3     .07       0
Bank Sta=5047.6,5054.3
XS Rating Curve= 0 ,0
Exp/Cntr=0.3,0.1

Type RM Length L Ch R = 1 ,28219   ,400,400,400
BEGIN DESCRIPTION:
MULBERRY CREEK TRIBUTARY 5 29.0
END DESCRIPTION:
XS GIS Cut Line= 3
      1562285.16      6875115.08      1563124.77      6873957.76
      1563342.44      6873083.86
#Sta/Elev= 30
  3570.2 1687.68  3812.2 1686.69  3954.4 1683.44  4166.4 1681.28  4456.1 1682.26
  4555.1 1679.63  4663.1 1681.57  4767.9 1682.13  4856.6 1680.74  4927.8 1681.95
    4978 1680.42  4992.7  1681.4  5020.2 1678.84  5020.7 1678.34    5027 1678.84
  5030.7 1680.47    5041 1681.67  5059.7 1682.37  5106.2 1682.15  5113.1 1683.21
  5299.5 1686.02  5436.6 1687.17  5601.8 1690.87  5637.9  1692.5  5669.6 1696.51
  5679.2 1698.99  5684.3 1697.94  5720.5 1701.53  5761.8 1704.03  5900.6 1702.76
#Mann= 7 ,-1 , 0
  3570.2     .07       0  4166.4    .035       0  4663.1     .07       0
  4767.9    .035       0  5020.2    .035       0    5027    .035       0
  5299.5     .07       0
Bank Sta=5020.2,5027
XS Rating Curve= 0 ,0
Exp/Cntr=0.3,0.1

Type RM Length L Ch R = 1 ,27819   ,866,866,866
BEGIN DESCRIPTION:
MULBERRY CREEK TRIBUTARY 5 28.0
END DESCRIPTION:
XS GIS Cut Line= 3
      1562441.42      6875458.81      1563374.91      6874258.97
      1564150.82       6873733.5
#Sta/Elev= 30
  3479.8 1685.93  3782.7 1685.14  4038.3 1681.52  4116.6 1681.47  4175.5 1680.13
  4238.8  1679.5  4288.6 1680.11  4352.8 1678.62  4431.1  1678.4  4494.4 1680.08
  4744.6 1680.95  4922.9 1678.71  4937.3 1679.59  4993.4 1680.13  5008.4 1679.78
  5032.8 1677.64  5033.3 1677.14  5039.9 1677.64  5050.4 1679.51  5072.6 1680.99
  5115.9 1680.64  5181.3 1680.47  5338.3 1683.05  5382.8 1683.05  5511.7 1687.43
  5555.7 1691.07  5591.9 1690.96  5663.7 1693.23  5778.3 1696.11  5937.1 1698.52
#Mann= 6 ,-1 , 0
  3479.8     .07       0  4175.5    .035       0  5032.8    .035       0
  5039.9    .035       0  5115.9     .07       0  5663.7    .045       0
Bank Sta=5032.8,5039.9
XS Rating Curve= 0 ,0
Exp/Cntr=0.3,0.1

Type RM Length L Ch R = 1 ,26953   ,536,536,536
BEGIN DESCRIPTION:
MULBERRY CREEK TRIBUTARY 5 27.0
END DESCRIPTION:
XS GIS Cut Line= 3
      1562566.43      6875432.77      1563556.45      6874677.37
      1564253.91      6874349.45
#Sta/Elev= 30
  3754.7 1685.62  3821.2 1684.59  3850.2 1685.42  3914.7 1684.94    4214 1680.12
    4414 1678.94  4570.5    1679  4627.6 1677.88  4662.9 1679.29  4841.7 1678.99
  4906.1 1676.22  4976.8 1679.12  4986.7 1675.35  4987.7 1674.78  4988.2 1674.28
  4994.9 1674.78  4995.9 1676.41  5020.5 1679.43  5223.4 1679.77  5285.7 1678.91
  5342.9 1679.96  5360.2 1681.44  5365.7 1680.33  5388.5 1680.81  5434.1 1683.83
  5451.4 1686.84  5456.9 1685.67  5479.7 1688.17  5606.2 1692.07  5770.7 1695.23
#Mann= 5 ,-1 , 0
  3754.7     .07       0    4414    .035       0  4986.7     .07       0
  4987.7     .07       0  4994.9     .07       0
Bank Sta=4987.7,4994.9
XS Rating Curve= 0 ,0
Exp/Cntr=0.3,0.1

Type RM Length L Ch R = 1 ,26417   ,921,921,921
BEGIN DESCRIPTION:
MULBERRY CREEK TRIBUTARY 5 26.0
END DESCRIPTION:
XS GIS Cut Line= 3
      1562634.12      6875542.15      1563848.62      6874979.98
        1564394.      6874672.67
#Sta/Elev= 30
  3661.7 1684.79    3861 1683.86  3982.2 1681.18  4142.3 1679.64  4677.2 1676.46
  4683.5 1676.39  4698.5 1674.92  4705.6  1676.3  4756.9 1677.21  4825.7 1677.65
  4841.9 1676.46  4848.6 1673.65  4854.1 1673.47  4871.5 1677.41  4940.3 1676.69
  4945.8 1674.09  4959.4 1672.86  4959.9 1672.36  4966.6 1672.86  4974.2 1676.33
  4996.4 1677.25  5013.6 1676.28  5041.8 1677.62  5144.6 1677.07  5153.8 1676.48
  5231.5 1678.12  5268.5 1680.38  5315.6 1685.38  5418.3 1688.26    5626  1693.2
#Mann= 11 ,-1 , 0
  3661.7     .07       0  4142.3    .035       0  4677.2     .07       0
  4683.5    .035       0  4841.9     .07       0  4959.4     .07       0
  4966.6     .07       0  5144.6    .035       0  5231.5     .07       0
  5268.5    .035       0  5418.3     .07       0
Bank Sta=4959.4,4966.6
XS Rating Curve= 0 ,0
Exp/Cntr=0.3,0.1

Type RM Length L Ch R = 1 ,25496   ,368,368,368
BEGIN DESCRIPTION:
MULBERRY CREEK TRIBUTARY 5 25.0
END DESCRIPTION:
XS GIS Cut Line= 3
       1562600.5      6875723.58      1564103.71       6875503.7
      1564578.76      6874981.97
#Sta/Elev= 30
  3480.8 1683.29  3606.6 1684.27  3974.1 1679.28  4080.1 1677.56  4246.8 1676.14
  4386.4 1676.19  4469.6 1681.76  4521.2 1682.02  4597.1 1675.47  4667.8 1674.81
    4688 1672.43    4731 1675.58  4859.8    1674  4900.2 1675.01  4981.1 1674.37
  5008.3 1670.16  5008.8 1669.66  5015.6 1670.16  5019.3 1672.85  5033.5 1674.57
  5224.1 1675.67  5245.7 1673.05  5330.8 1673.19  5351.8 1678.92  5400.3 1685.71
  5422.7 1687.91  5452.4 1687.18  5500.4 1686.54  5613.9 1690.45  5705.6 1691.74
#Mann= 9 ,-1 , 0
  3480.8     .07       0  3974.1    .035       0  4080.1     .07       0
  4246.8    .035       0  4469.6     .07       0  5008.3     .07       0
  5015.6     .07       0  5400.3    .035       0  5452.4     .07       0
Bank Sta=5008.3,5015.6
XS Rating Curve= 0 ,0
Exp/Cntr=0.3,0.1

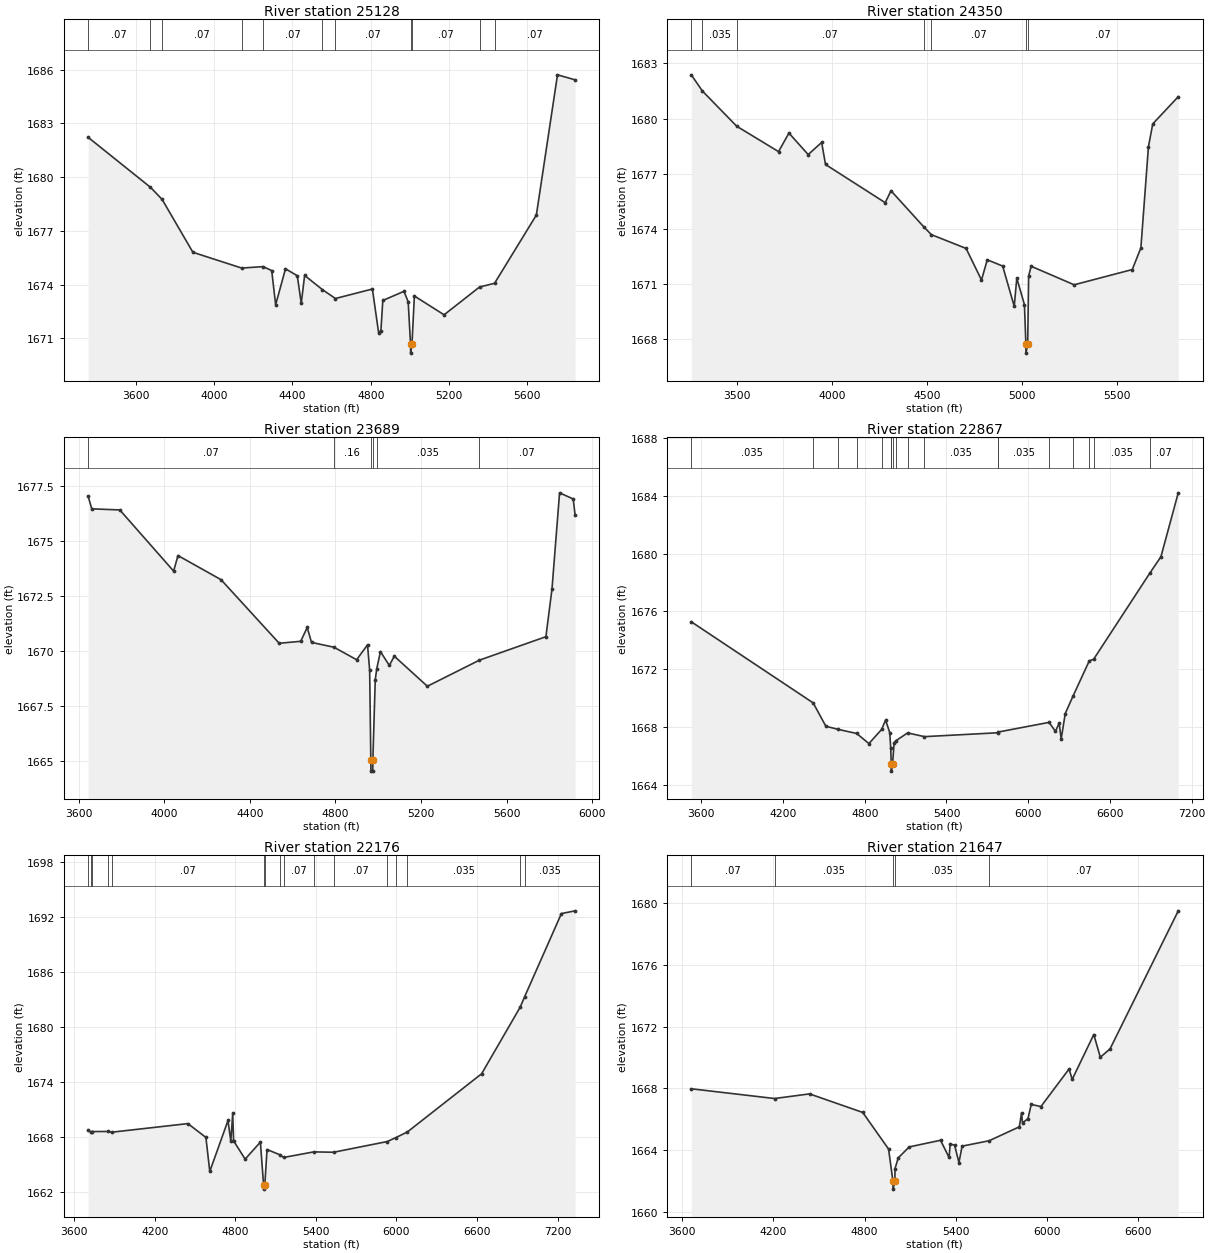
Type RM Length L Ch R = 1 ,25128   ,778,778,778
BEGIN DESCRIPTION:
MULBERRY CREEK TRIBUTARY 5 24.0
END DESCRIPTION:
XS GIS Cut Line= 3
      1562762.99      6875753.44      1563978.27      6875885.39
      1565075.51      6875256.91
#Sta/Elev= 30
  3356.7 1682.22  3674.9 1679.43  3734.1 1678.76  3891.8  1675.8  4140.8 1674.92
  4250.1    1675  4294.2 1674.78  4314.3 1672.87  4364.6 1674.88  4424.9 1674.49
  4445.1 1672.95  4462.3 1674.51  4552.6 1673.72  4619.6 1673.22  4808.4 1673.75
  4840.1 1671.32  4851.9 1671.43  4861.6 1673.11  4969.6 1673.62  4991.1 1673.04
  5003.3 1670.67  5003.8 1670.17  5010.6 1670.67  5022.8 1673.36  5174.6 1672.31
  5355.4 1673.86  5432.3 1674.07  5645.8 1677.88  5753.7 1685.71  5843.6 1685.43
#Mann= 11 ,-1 , 0
  3356.7     .07       0  3674.9    .035       0  3734.1     .07       0
  4140.8    .035       0  4250.1     .07       0  4552.6    .035       0
  4619.6     .07       0  5003.3     .07       0  5010.6     .07       0
  5355.4    .035       0  5432.3     .07       0
Bank Sta=5003.3,5010.6
XS Rating Curve= 0 ,0
Exp/Cntr=0.3,0.1

Type RM Length L Ch R = 1 ,24350   ,661,661,661
BEGIN DESCRIPTION:
Mapping XS 758b7c79
END DESCRIPTION:
XS GIS Cut Line= 3
      1562637.97      6876590.25      1564332.44      6876302.05
       1565096.3      6875937.48
#Sta/Elev= 30
  3259.2 1682.38  3317.5  1681.5  3498.7 1679.58  3718.8  1678.2  3773.5 1679.21
  3874.9 1678.04  3945.9  1678.7  3966.2  1677.5  4280.7 1675.42  4311.1 1676.07
  4483.3 1674.11  4523.8 1673.68  4706.7 1672.93  4787.9 1671.21  4818.3 1672.31
  4899.4 1671.97  4960.3 1669.78  4973.9 1671.31  5014.1 1669.87  5021.7 1667.73
  5022.2 1667.23  5031.2 1667.73  5036.2 1671.42  5049.2 1671.96    5276 1670.95
  5582.1 1671.78  5627.5 1672.96  5667.3 1678.46    5690 1679.71  5824.4 1681.19
#Mann= 7 ,-1 , 0
  3259.2     .07       0  3317.5    .035       0  3498.7     .07       0
  4483.3    .035       0  4523.8     .07       0  5021.7     .07       0
  5031.2     .07       0
Bank Sta=5021.7,5031.2
XS Rating Curve= 0 ,0
Exp/Cntr=0.3,0.1

Type RM Length L Ch R = 1 ,23689   ,822,822,822
BEGIN DESCRIPTION:
Mapping XS 38d98261
END DESCRIPTION:
XS GIS Cut Line= 4
      1563158.05      6876984.06      1564538.28      6876817.39
      1564803.91      6876708.01      1565184.09       6876244.5
#Sta/Elev= 30
  3643.4 1677.05  3660.5 1676.48  3791.4 1676.43  4043.2 1673.64  4063.4 1674.35
  4264.8 1673.25  4536.8 1670.35  4637.5 1670.44  4667.7 1671.07  4687.9 1670.39
  4792.7 1670.17  4898.9  1669.6  4949.8 1670.28  4959.8 1669.11  4965.2 1665.02
  4965.7 1664.52  4974.2 1664.52  4974.7 1665.02  4985.9 1668.68  4992.9 1669.19
  5010.2 1669.97  5051.7 1669.34  5075.1 1669.76  5229.6 1668.39  5472.9 1669.58
  5783.9 1670.65  5812.4 1672.83  5847.8 1677.21  5911.7 1676.93  5920.4  1676.2
#Mann= 6 ,-1 , 0
  3643.4     .07       0  4792.7     .16       0  4965.2    .035       0
  4974.7     .16       0  4992.9    .035       0  5472.9     .07       0
Bank Sta=4965.2,4974.7
XS Rating Curve= 0 ,0
Exp/Cntr=0.3,0.1

Type RM Length L Ch R = 1 ,22867   ,691,691,691
BEGIN DESCRIPTION:
MULBERRY CREEK TRIBUTARY 5 21.0
END DESCRIPTION:
XS GIS Cut Line= 3
      1563435.81      6877800.03      1564881.15      6877514.93
      1566601.28      6876307.84
#Sta/Elev= 30
  3526.8 1675.28  4421.4 1669.66  4514.7 1668.04  4606.5 1667.82  4740.7 1667.54
  4830.6 1666.84  4923.9 1667.82    4953 1668.47  4983.5  1667.6  4990.6 1666.54
  4994.6 1665.43  4995.1 1664.93  5004.2 1665.43  5015.8  1666.9  5027.5 1667.03
  5114.9 1667.58  5238.3 1667.32  5777.7 1667.59  5779.6 1667.64  6153.3 1668.31
  6200.2 1667.68  6227.2 1668.27    6242 1667.15  6271.7 1668.92  6328.8 1670.13
  6448.5 1672.58  6479.8 1672.68  6893.8 1678.67  6974.1 1679.79  7101.4 1684.22
#Mann= 18 ,-1 , 0
  3526.8    .035       0  4421.4     .07       0  4606.5    .035       0
  4740.7     .07       0  4923.9    .035       0  4990.6     .07       0
  4994.6     .07       0  5004.2     .07       0  5027.5    .035       0
  5114.9     .07       0  5238.3    .035       0  5777.7     .07       0
  5779.6    .035       0  6153.3     .07       0  6328.8    .035       0
  6448.5     .07       0  6479.8    .035       0  6893.8     .07       0
Bank Sta=4994.6,5004.2
XS Rating Curve= 0 ,0
Exp/Cntr=0.3,0.1

Type RM Length L Ch R = 1 ,22176   ,529,529,529
BEGIN DESCRIPTION:
MULBERRY CREEK TRIBUTARY 5 20.0
END DESCRIPTION:
XS GIS Cut Line= 3
      1564620.37      6878878.74      1565438.35       6877871.3
      1567023.45      6876162.48
#Sta/Elev= 30
  3702.3 1668.72  3723.3 1668.47  3731.3 1668.56  3846.7 1668.57  3877.9 1668.49
  4445.6 1669.43  4579.9 1667.92  4608.7  1664.2  4744.5 1669.77  4765.3 1667.51
  4779.7 1670.56  4786.1 1667.54  4872.4 1665.55  4985.8 1667.41  5009.4 1662.77
  5009.9 1662.27    5019 1662.77  5035.2  1666.6  5128.4 1666.04  5158.9 1665.73
    5383 1666.34  5531.1  1666.3  5931.1 1667.47  5996.8 1667.91  6081.3 1668.52
  6634.5 1674.88  6921.5 1682.15  6955.3 1683.31  7228.7 1692.38  7330.8 1692.68
#Mann= 16 ,-1 , 0
  3702.3    .035       0  3723.3     .16       0  3731.3     .07       0
  3846.7     .16       0  3877.9     .07       0  5009.4     .07       0
    5019     .07       0  5128.4     .16       0  5158.9     .07       0
    5383    .035       0  5531.1     .07       0  5931.1    .035       0
  5996.8     .07       0  6081.3    .035       0  6921.5     .07       0
  6955.3    .035       0
Bank Sta=5009.4,5019
XS Rating Curve= 0 ,0
Exp/Cntr=0.3,0.1

Type RM Length L Ch R = 1 ,21647   ,1095,1095,1095
BEGIN DESCRIPTION:
MULBERRY CREEK TRIBUTARY 5 18.0
END DESCRIPTION:
XS GIS Cut Line= 3
      1564951.52      6879316.85      1565778.18      6878261.71
      1566965.13      6876826.17
#Sta/Elev= 30
  3659.6 1667.98  4207.2 1667.35  4437.4 1667.65  4787.3 1666.45  4957.3 1664.08
    4986 1661.99  4986.5 1661.49  4999.1 1661.99  4999.2 1662.81  5021.4 1663.52
  5093.1 1664.22  5298.9 1664.65  5355.2 1663.54  5362.7  1664.4  5391.4 1664.34
    5420 1663.21  5440.9 1664.27  5618.7 1664.62  5817.3 1665.52  5831.7 1666.41
  5838.2 1665.77  5874.2 1666.05  5895.5 1666.97  5959.3 1666.83  6144.3 1669.26
  6165.1 1668.59  6307.1 1671.49  6350.1 1670.02    6414 1670.56  6862.7 1679.49
#Mann= 5 ,-1 , 0
  3659.6     .07       0  4207.2    .035       0    4986    .035       0
  4999.1    .035       0  5618.7     .07       0
Bank Sta=4986,4999.1
XS Rating Curve= 0 ,0
Exp/Cntr=0.3,0.1

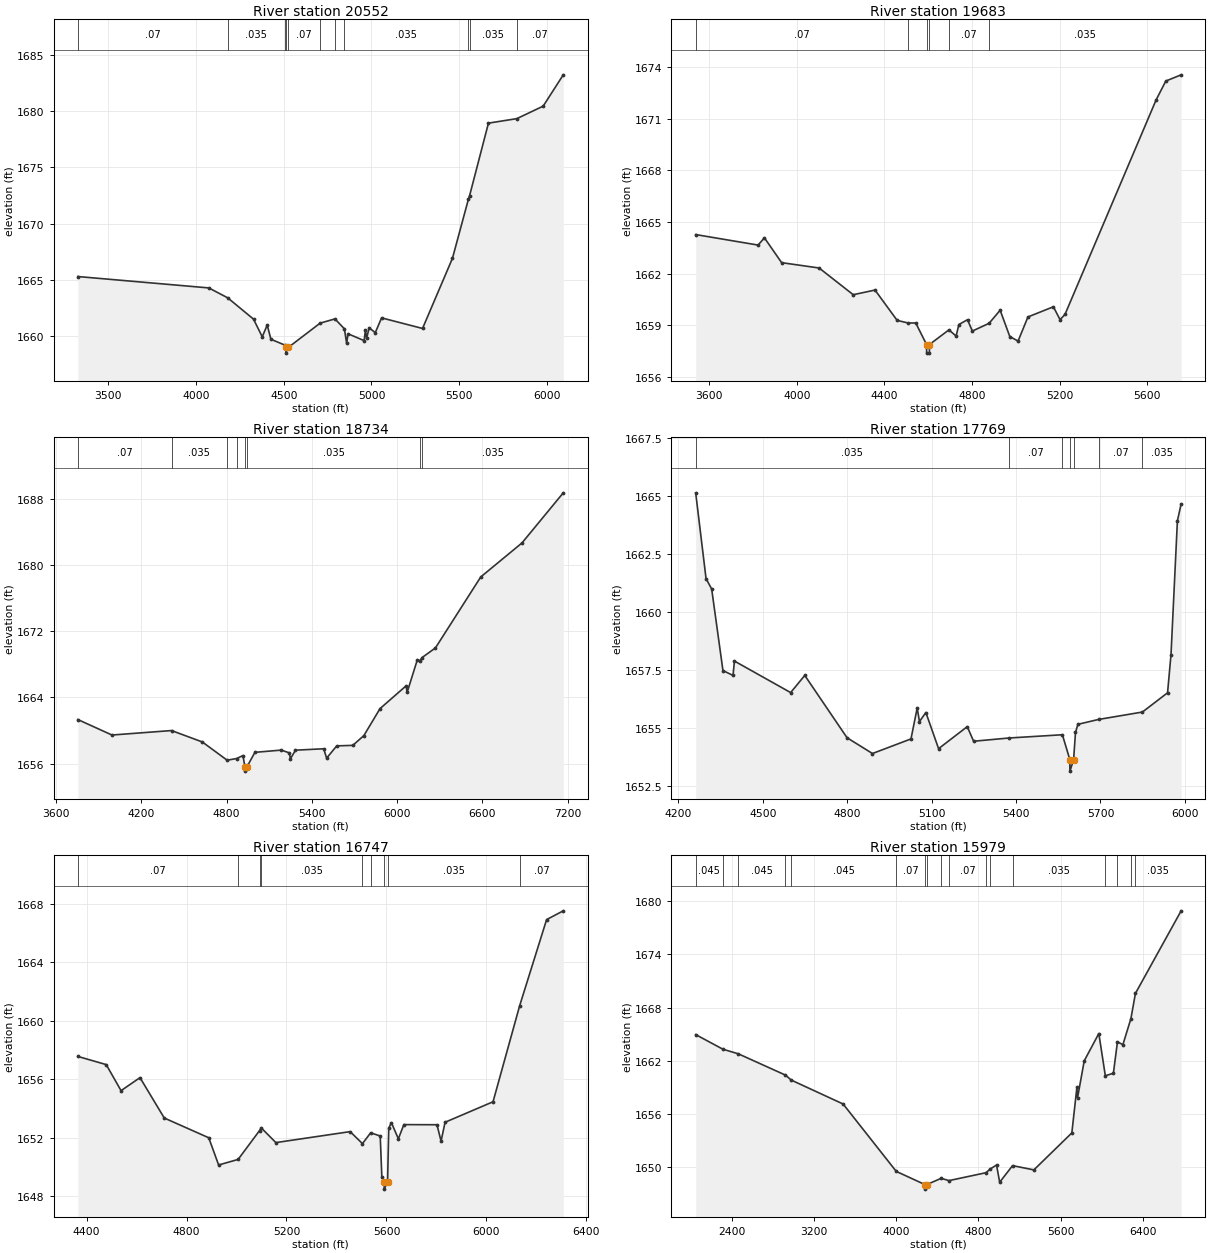
Type RM Length L Ch R = 1 ,20552   ,869,869,869
BEGIN DESCRIPTION:
MULBERRY CREEK TRIBUTARY 5 17.0
END DESCRIPTION:
XS GIS Cut Line= 3
      1565502.04      6879699.22      1566520.69      6878603.94
       1567367.9      6877659.51
#Sta/Elev= 30
  3327.6 1665.31  4073.5  1664.3  4181.2 1663.42  4328.1 1661.53  4377.9 1659.96
  4406.2    1661  4427.2 1659.74  4507.3 1659.22  4512.4 1659.01  4512.9 1658.51
  4525.7 1659.01  4707.3 1661.17  4791.9 1661.55  4845.6 1660.67  4858.6 1659.37
  4866.1 1660.23    4958 1659.62  4965.5 1660.56  4972.2 1659.82  4986.4 1660.76
  5021.6 1660.33  5057.5 1661.64  5290.7  1660.7  5461.1 1666.93  5552.2 1672.19
  5558.3 1672.47    5666 1678.93  5827.6 1679.33  5977.7 1680.44  6092.1 1683.22
#Mann= 11 ,-1 , 0
  3327.6     .07       0  4181.2    .035       0  4507.3     .07       0
  4512.4    .035       0  4525.7     .07       0  4707.3    .035       0
  4791.9     .07       0  4845.6    .035       0  5552.2     .07       0
  5558.3    .035       0  5827.6     .07       0
Bank Sta=4512.4,4525.7
XS Rating Curve= 0 ,0
Exp/Cntr=0.3,0.1

Type RM Length L Ch R = 1 ,19683   ,949,949,949
BEGIN DESCRIPTION:
Mapping XS deef392b
END DESCRIPTION:
XS GIS Cut Line= 3
      1565682.84      6879886.84      1566627.29       6879140.3
      1567525.17       6878672.3
#Sta/Elev= 30
  3538.6 1664.27  3823.5 1663.66  3852.4 1664.08    3931 1662.64  4102.2 1662.33
  4257.9 1660.78  4357.3 1661.05  4458.4 1659.29    4508 1659.14  4543.3 1659.14
  4592.6 1657.89  4593.1 1657.39  4605.5 1657.39    4606 1657.89  4694.7 1658.74
  4727.6 1658.38  4740.3 1659.05  4779.6 1659.33  4801.7 1658.67  4878.1 1659.12
  4928.7 1659.88  4972.8 1658.35  5010.5 1658.09  5055.6 1659.49  5171.7 1660.08
  5202.2 1659.33  5224.8 1659.64  5640.9 1672.09    5685 1673.18    5755 1673.54
#Mann= 6 ,-1 , 0
  3538.6     .07       0    4508    .035       0  4592.6    .035       0
    4606    .035       0  4694.7     .07       0  4878.1    .035       0
Bank Sta=4592.6,4606
XS Rating Curve= 0 ,0
Exp/Cntr=0.3,0.1

Type RM Length L Ch R = 1 ,18734   ,965,965,965
BEGIN DESCRIPTION:
MULBERRY CREEK TRIBUTARY 5 16.0
END DESCRIPTION:
XS GIS Cut Line= 3
      1565927.53      6880556.82      1566927.91      6879811.51
      1568359.65      6878182.58
#Sta/Elev= 30
  3752.5 1661.32  3992.9 1659.45    4412 1659.99  4628.9 1658.61  4803.3 1656.41
  4869.8 1656.61  4914.6 1656.97  4928.6 1655.59  4929.1 1655.09  4942.1 1655.59
  4998.8 1657.36  5184.7 1657.63  5241.6 1657.29  5248.2 1656.57  5284.3 1657.62
  5482.6 1657.79  5503.5 1656.66  5574.6 1658.14  5687.6  1658.2  5765.4 1659.38
  5879.2 1662.64  6063.3  1665.4  6069.9  1664.6  6141.1  1668.5  6161.5 1668.44
  6175.6 1668.81  6269.2 1669.97    6588 1678.54  6878.3 1682.65  7168.7  1688.7
#Mann= 8 ,-1 , 0
  3752.5     .07       0    4412    .035       0  4803.3     .07       0
  4869.8    .035       0  4928.6    .035       0  4942.1    .035       0
  6161.5     .07       0  6175.6    .035       0
Bank Sta=4928.6,4942.1
XS Rating Curve= 0 ,0
Exp/Cntr=0.3,0.1

Type RM Length L Ch R = 1 ,17769   ,1022,1022,1022
BEGIN DESCRIPTION:
Mapping XS 6fc782ff
END DESCRIPTION:
XS GIS Cut Line= 3
      1566318.31      6880513.57      1567052.63      6880565.65
      1567926.78      6880102.56
#Sta/Elev= 30
  4261.4 1665.15  4298.2 1661.45  4318.2    1661  4358.3 1657.48  4394.1 1657.27
  4399.1 1657.89  4598.9 1656.53  4649.1 1657.27  4799.4 1654.58  4889.7  1653.9
  5026.6 1654.53  5048.6 1655.86  5056.8 1655.28  5079.5 1655.67  5124.7 1654.11
  5226.6 1655.06  5249.2 1654.43  5375.4 1654.57  5564.7 1654.71  5591.1 1653.64
  5591.6 1653.14  5604.6 1653.64  5611.3 1654.81  5619.9 1655.16  5693.2 1655.37
  5849.2 1655.69  5938.5 1656.52  5950.8 1658.17  5973.5 1663.94  5986.8 1664.67
#Mann= 7 ,-1 , 0
  4261.4    .035       0  5375.4     .07       0  5564.7    .035       0
  5591.1    .035       0  5604.6    .035       0  5693.2     .07       0
  5849.2    .035       0
Bank Sta=5591.1,5604.6
XS Rating Curve= 0 ,0
Exp/Cntr=0.3,0.1

Type RM Length L Ch R = 1 ,16747   ,768,768,768
BEGIN DESCRIPTION:
MULBERRY CREEK TRIBUTARY 5 15.0
END DESCRIPTION:
XS GIS Cut Line= 3
      1566429.96      6881212.99      1567055.47      6881322.91
      1568214.07      6880716.71
#Sta/Elev= 30
  4364.9 1657.57  4478.6 1657.01  4537.9 1655.23  4613.7 1656.12  4710.9 1653.36
  4888.9 1652.01  4928.4 1650.15  5006.4 1650.53  5092.1  1652.5  5099.3 1652.68
  5157.5 1651.68  5454.7 1652.43    5504 1651.61  5536.8 1652.35  5575.1 1652.13
  5581.5 1649.36  5590.7    1649  5591.2  1648.5  5604.5    1649  5609.2 1652.67
  5619.9 1653.04  5647.7 1651.94  5669.7 1652.91  5802.2  1652.9  5818.6 1651.78
  5834.6 1653.07  6026.5 1654.47  6133.2 1661.04  6240.9 1666.92  6307.6 1667.52
#Mann= 9 ,-1 , 0
  4364.9     .07       0  5006.4    .035       0  5092.1     .07       0
  5099.3    .035       0    5504     .07       0  5536.8    .035       0
  5590.7     .07       0  5604.5    .035       0  6133.2     .07       0
Bank Sta=5590.7,5604.5
XS Rating Curve= 0 ,0
Exp/Cntr=0.3,0.1

Type RM Length L Ch R = 1 ,15979   ,1008,1008,1008
BEGIN DESCRIPTION:
MULBERRY CREEK TRIBUTARY 5 14.0
END DESCRIPTION:
XS GIS Cut Line= 3
      1564810.63      6882815.74      1567592.55      6881825.52
      1568730.65      6880463.79
#Sta/Elev= 30
  2047.1 1664.95  2312.5  1663.3  2462.6 1662.78  2921.7 1660.38  2977.6 1659.82
    3483 1657.12  4000.5 1649.52  4282.1 1648.02  4282.6 1647.52  4295.9 1648.02
  4437.3 1648.74  4513.4 1648.48  4873.6 1649.37  4916.8  1649.8  4976.9 1650.24
  5007.5  1648.3    5133 1650.17  5340.6 1649.69  5710.2 1653.86  5759.6    1659
  5766.2 1657.84  5830.9 1661.99  5973.1 1665.07  6036.4 1660.31  6114.9 1660.59
  6154.6 1664.14  6207.3 1663.81  6285.5 1666.75  6329.6  1669.6  6774.7 1678.91
#Mann= 17 ,-1 , 0
  2047.1    .045       0  2312.5     .07       0  2462.6    .045       0
  2921.7     .07       0  2977.6    .045       0  4000.5     .07       0
  4282.1     .07       0  4295.9     .07       0  4437.3    .035       0
  4513.4     .07       0  4873.6    .035       0  4916.8     .07       0
    5133    .035       0  6036.4     .07       0  6154.6    .035       0
  6285.5     .07       0  6329.6    .035       0
Bank Sta=4282.1,4295.9
XS Rating Curve= 0 ,0
Exp/Cntr=0.3,0.1

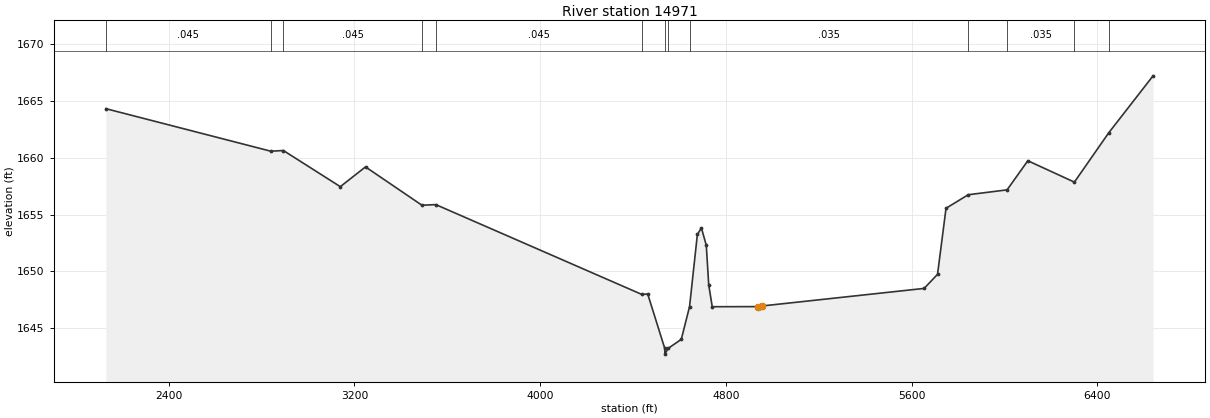
Type RM Length L Ch R = 1 ,14971   ,795,795,795
BEGIN DESCRIPTION:
MULBERRY CREEK TRIBUTARY 5 13.0
END DESCRIPTION:
XS GIS Cut Line= 3
      1565024.18      6883586.58      1567755.47      6882703.16
      1568580.75      6881285.71
#Sta/Elev= 30
  2129.4 1664.32  2839.8 1660.58  2893.9 1660.64  3139.2 1657.46  3247.7  1659.2
  3490.6 1655.83  3550.8 1655.88  4436.9 1647.99  4463.5 1648.01  4536.8 1643.23
  4537.3 1642.73  4551.1 1643.23    4608 1644.03  4643.6 1646.91  4677.3 1653.26
  4694.7 1653.83  4715.7  1652.3  4726.2 1648.81  4741.3  1646.9  4938.6 1646.91
  4957.5 1646.97    5654 1648.51  5711.8 1649.75  5748.4 1655.56  5843.9 1656.75
  6011.4 1657.18  6100.8 1659.74  6301.3 1657.86  6449.3  1662.2  6640.2 1667.21
#Mann= 13 ,-1 , 0
  2129.4    .045       0  2839.8     .07       0  2893.9    .045       0
  3490.6    .035       0  3550.8    .045       0  4436.9     .07       0
  4536.8    .035       0  4551.1     .07       0  4643.6    .035       0
  5843.9     .07       0  6011.4    .035       0  6301.3     .07       0
  6449.3    .035       0
#XS Ineff= 2 , 0
       0  4694.7 1653.83               0
Permanent Ineff=
       F       F
Bank Sta=4938.6,4957.5
XS Rating Curve= 0 ,0
Exp/Cntr=0.3,0.1