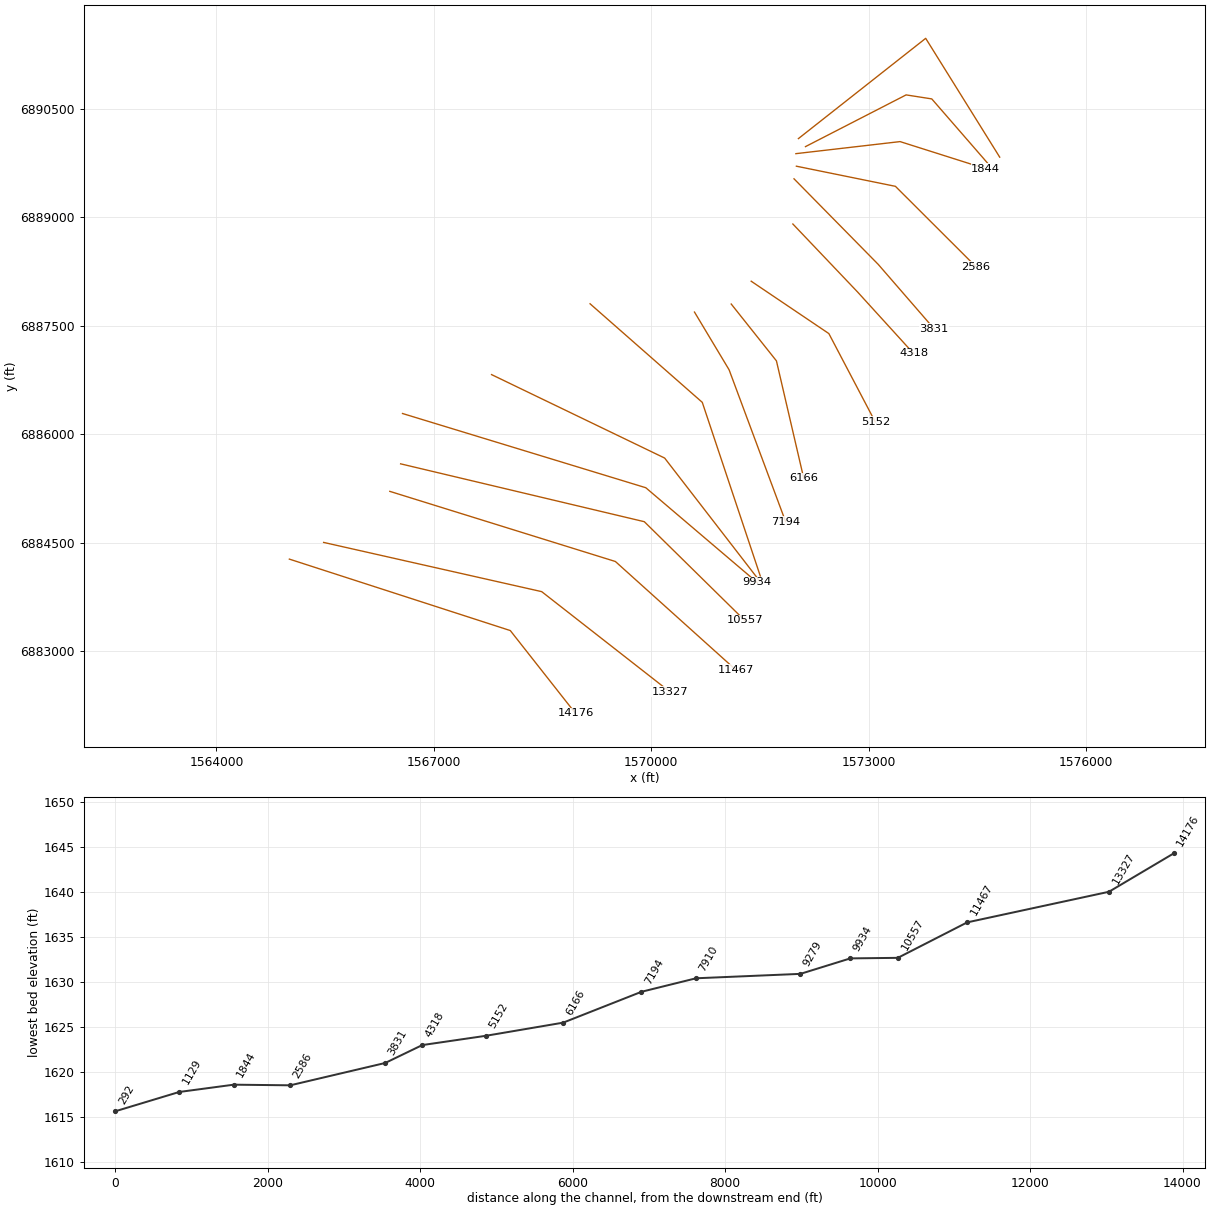
HEC-RAS study MULBERRY CREEK TRIBUTARY 5.prj: MULBERRY CREEK TRIBUTARY 5 Base Level Engineering

--- MULBERRY CREEK TRIBUTARY 5.g01 (geometry) --- (continued)

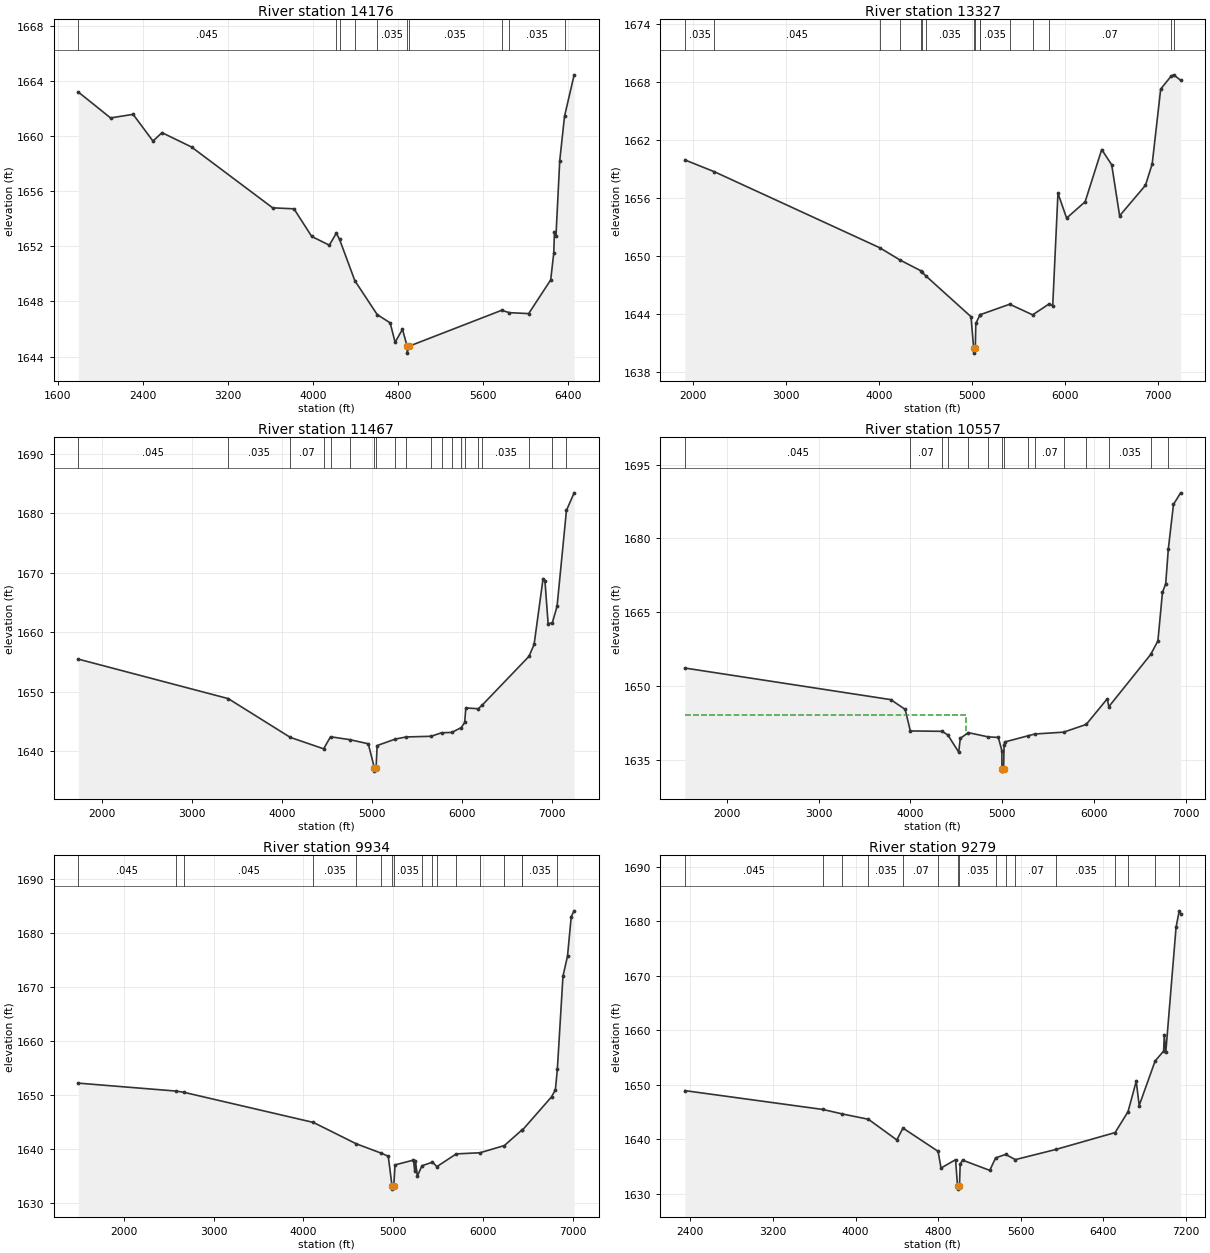
Type RM Length L Ch R = 1 ,14176   ,849,849,849
BEGIN DESCRIPTION:
MULBERRY CREEK TRIBUTARY 5 12.0
END DESCRIPTION:
XS GIS Cut Line= 3
      1565006.82       6884270.6      1568055.48       6883282.8
      1568954.99      6882138.02
#Sta/Elev= 30
  1795.3 1663.21  2098.2 1661.33  2310.2 1661.59  2496.8 1659.65  2581.8 1660.26
  2859.2 1659.22  3622.4  1654.8  3822.2 1654.73  3989.4 1652.72  4154.6 1652.09
  4220.4 1652.96  4250.8 1652.51  4394.4 1649.51  4604.5 1647.05  4726.2 1646.45
  4772.9 1645.04  4842.1 1645.98  4885.8 1644.75  4886.3 1644.25    4903 1644.75
  5774.2 1647.36  5846.2 1647.19  6028.4 1647.12  6235.4 1649.57  6264.3 1651.52
  6270.7 1653.06  6285.1 1652.79  6320.4 1658.23  6365.4 1661.45  6455.9 1664.46
#Mann= 10 ,-1 , 0
  1795.3    .045       0  4220.4    .035       0  4250.8    .045       0
  4394.4     .07       0  4604.5    .035       0  4885.8    .035       0
    4903    .035       0  5774.2     .07       0  5846.2    .035       0
  6365.4     .07       0
Bank Sta=4885.8,4903
XS Rating Curve= 0 ,0
Exp/Cntr=0.3,0.1

Type RM Length L Ch R = 1 ,13327   ,1860,1860,1860
BEGIN DESCRIPTION:
MULBERRY CREEK TRIBUTARY 5 11.0
END DESCRIPTION:
XS GIS Cut Line= 3
       1565479.9      6884501.51      1568488.97      6883820.86
      1570254.98      6882438.01
#Sta/Elev= 30
  1914.9 1659.98  2233.8 1658.75  4008.1  1650.9  4230.1 1649.61  4449.7 1648.52
  4458.9 1648.41    4504 1647.99  4990.5 1643.76  5019.1 1640.49  5019.6 1639.99
  5036.6 1640.49  5042.3 1643.07    5089 1643.98  5090.4 1643.97  5406.4 1645.05
  5652.9 1643.95    5828 1645.07  5868.7 1644.91  5924.8 1656.53  6017.9 1653.96
  6216.8 1655.65  6394.9 1661.05  6502.5 1659.47  6587.5  1654.2  6865.1 1657.35
  6937.4 1659.56  7028.8 1667.31  7139.8 1668.63  7167.7 1668.78    7243 1668.22
#Mann= 16 ,-1 , 0
  1914.9    .035       0  2233.8    .045       0  4008.1    .035       0
  4230.1     .07       0  4449.7    .035       0  4458.9     .07       0
    4504    .035       0  5019.1    .035       0  5036.6    .035       0
    5089     .07       0  5090.4    .035       0  5406.4     .07       0
  5652.9    .035       0    5828     .07       0  7139.8    .035       0
  7167.7     .07       0
Bank Sta=5019.1,5036.6
XS Rating Curve= 0 ,0
Exp/Cntr=0.3,0.1

Type RM Length L Ch R = 1 ,11467   ,910,910,910
BEGIN DESCRIPTION:
MULBERRY CREEK TRIBUTARY 5 10.0
END DESCRIPTION:
XS GIS Cut Line= 3
      1566392.82      6885207.52      1569505.57      6884237.78
      1571171.13      6882736.37
#Sta/Elev= 30
  1739.7 1655.46  3403.1 1648.81  4091.7 1642.28  4462.1 1640.35  4538.5 1642.38
  4753.4 1641.89  4957.5  1641.2    5026 1637.09  5026.5 1636.59    5044 1637.09
  5055.9  1640.9  5259.6    1642  5378.2 1642.35  5654.1 1642.46  5770.4 1643.05
  5884.2 1643.11  5989.8 1643.93  6027.3 1644.79  6040.2 1647.24    6177  1647.1
  6218.9 1647.67  6741.1 1655.93    6798 1657.94  6897.4 1669.04  6918.3 1668.66
  6953.4 1661.45  7000.4 1661.58  7052.8 1664.38  7156.9 1680.52  7242.4 1683.48
#Mann= 20 ,-1 , 0
  1739.7    .045       0  3403.1    .035       0  4091.7     .07       0
  4462.1    .035       0  4538.5    .035       0  4753.4     .07       0
    5026     .07       0    5044    .035       0  5259.6     .07       0
  5378.2    .035       0  5654.1    .035       0  5770.4     .07       0
  5884.2    .035       0  5989.8     .07       0  6027.3    .035       0
    6177     .07       0  6218.9    .035       0  6741.1     .07       0
  7000.4    .035       0  7156.9     .07       0
Bank Sta=5026,5044
XS Rating Curve= 0 ,0
Exp/Cntr=0.3,0.1

Type RM Length L Ch R = 1 ,10557   ,623,623,623
BEGIN DESCRIPTION:
MULBERRY CREEK TRIBUTARY 5 9.0
END DESCRIPTION:
XS GIS Cut Line= 3
      1566542.09      6885588.03        1569905.        6884788.
      1571290.11      6883423.06
#Sta/Elev= 30
  1542.8 1653.63  3786.6  1647.2  3943.5 1645.21  3999.4 1640.83  4344.7 1640.75
  4407.5 1640.03  4526.7 1636.52    4544 1639.33  4632.5 1640.48  4846.6 1639.62
  4958.4 1639.51    4997  1636.8  4997.5 1633.15    4998 1632.65  5015.7 1633.15
  5020.8 1637.87  5027.8 1638.58  5285.6 1639.86  5358.9 1640.21  5669.7 1640.58
  5915.7 1642.15  6145.1 1647.37  6161.8 1645.76  6618.4  1656.4  6696.7 1659.15
  6746.2 1669.02  6781.6 1670.78  6810.2 1677.85  6866.4 1686.93  6944.2 1689.28
#Mann= 15 ,-1 , 0
  1542.8    .045       0  3999.4     .07       0  4344.7    .035       0
  4407.5     .07       0  4632.5    .035       0  4846.6     .07       0
  4997.5     .07       0  5015.7     .07       0  5285.6    .035       0
  5358.9     .07       0  5669.7    .035       0  5915.7     .07       0
  6161.8    .035       0  6618.4     .07       0  6810.2    .035       0
#XS Ineff= 2 , 0
       0    4609    1644               0
Permanent Ineff=
       F       F
Bank Sta=4997.5,5015.7
XS Rating Curve= 0 ,0
Exp/Cntr=0.3,0.1

Type RM Length L Ch R = 1 ,9934    ,655,655,655
BEGIN DESCRIPTION:
MULBERRY CREEK TRIBUTARY 5 8.0
END DESCRIPTION:
XS GIS Cut Line= 3
      1566568.13      6886283.92      1569925.22      6885257.84
      1571461.14      6883948.92
#Sta/Elev= 30
  1489.6 1652.23  2578.8 1650.76  2664.5 1650.54  4110.1 1644.95    4587    1641
  4868.9 1639.24  4945.2 1638.68  4988.1 1633.09  4988.6 1632.59  5006.4 1633.09
  5021.1 1637.08  5226.5 1637.97  5240.7 1635.86  5248.5 1637.83  5269.3 1634.98
  5320.9 1636.92  5438.2 1637.59  5487.2 1636.76  5703.6 1639.12  5967.8 1639.33
  6239.3 1640.66    6438 1643.58  6440.7 1643.52  6765.9 1649.69  6808.8 1651.01
  6830.9 1654.88  6893.3 1672.06  6943.9 1675.77  6985.5  1683.1    7018 1684.16
#Mann= 17 ,-1 , 0
  1489.6    .045       0  2578.8    .035       0  2664.5    .045       0
  4110.1    .035       0    4587     .07       0  4868.9    .035       0
  4988.1    .035       0  5006.4    .035       0  5320.9     .07       0
  5438.2    .035       0  5487.2     .07       0  5703.6    .035       0
  5967.8     .07       0  6239.3    .035       0    6438     .07       0
  6440.7    .035       0  6830.9     .07       0
Bank Sta=4988.1,5006.4
XS Rating Curve= 0 ,0
Exp/Cntr=0.3,0.1

Type RM Length L Ch R = 1 ,9279    ,1369,1369,1369
BEGIN DESCRIPTION:
MULBERRY CREEK TRIBUTARY 5 7.0
END DESCRIPTION:
XS GIS Cut Line= 3
      1567796.97      6886821.94      1570185.48      6885668.11
      1571496.65      6883967.73
#Sta/Elev= 30
  2347.4 1648.93  3685.2 1645.47  3872.7 1644.65  4124.6 1643.68  4399.8 1639.89
  4459.5 1642.06  4799.3  1637.8  4827.6 1634.73  4968.7 1636.27  4987.8 1631.37
  4988.3 1630.87  5006.1 1631.37  5013.2 1635.43  5035.9 1636.19  5299.5 1634.31
  5356.4  1636.6  5453.2 1637.24  5547.2 1636.28  5938.5 1638.14    6513 1641.24
    6638 1645.06  6717.5 1650.65  6746.2  1646.2  6900.3 1654.36  6982.7 1656.18
    6989  1659.2  7003.5 1655.94  7103.1 1678.88  7133.4 1681.89  7147.2 1681.35
#Mann= 16 ,-1 , 0
  2347.4    .045       0  3685.2    .035       0  3872.7     .07       0
  4124.6    .035       0  4459.5     .07       0  4799.3    .035       0
  4987.8    .035       0  5006.1    .035       0  5356.4     .07       0
  5453.2    .035       0  5547.2     .07       0  5938.5    .035       0
    6513     .07       0    6638    .035       0  6900.3     .07       0
  7133.4    .035       0
Bank Sta=4987.8,5006.1
XS Rating Curve= 0 ,0
Exp/Cntr=0.3,0.1

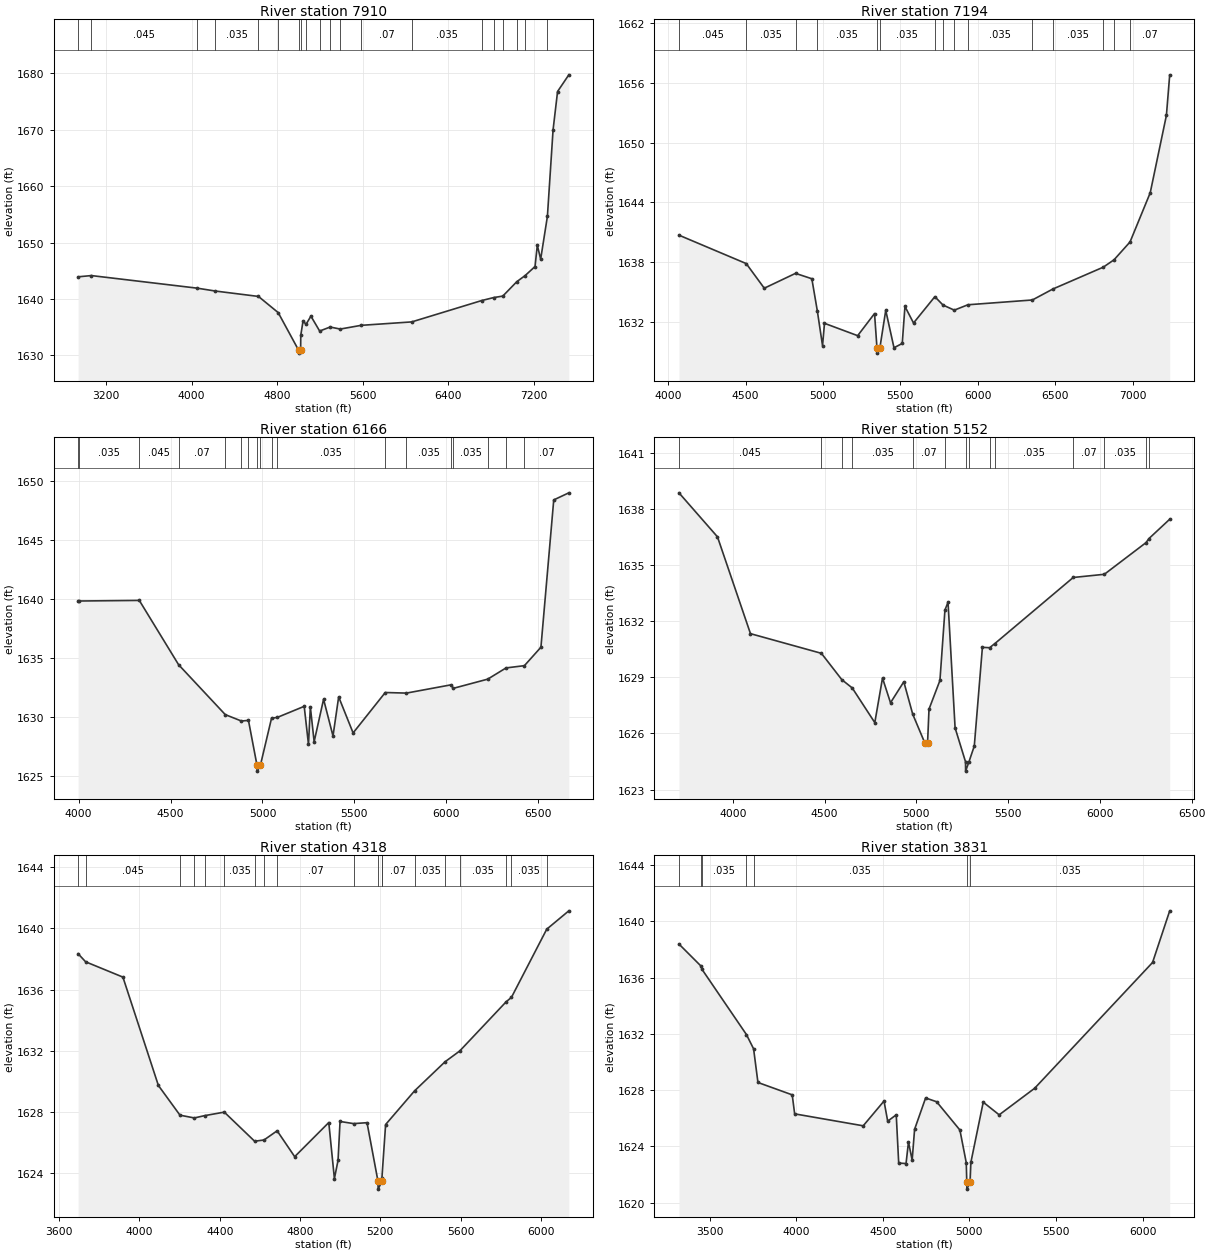
Type RM Length L Ch R = 1 ,7910    ,716,716,716
BEGIN DESCRIPTION:
MULBERRY CREEK TRIBUTARY 5 6.0
END DESCRIPTION:
XS GIS Cut Line= 3
      1569156.33      6887801.12        1570705.        6886438.
      1571504.99      6884038.04
#Sta/Elev= 30
  2936.9 1643.92  3061.4 1644.14  4050.6 1641.91  4220.3  1641.4  4624.9 1640.44
  4809.7 1637.57  5001.4 1630.88  5001.9 1630.38  5019.8 1630.88  5021.1 1633.55
  5042.2 1636.05  5070.9 1635.51    5116 1636.94  5197.8  1634.3  5295.9 1635.01
  5390.4 1634.65  5585.6 1635.31  6059.7 1635.92  6714.5 1639.71  6826.8 1640.24
  6911.8  1640.5  7043.1 1643.06  7120.8 1644.14  7213.6 1645.75  7234.7 1649.52
  7266.3 1647.06  7329.3 1654.64  7382.3 1669.99  7424.4  1676.8  7529.8 1679.76
#Mann= 20 ,-1 , 0
  2936.9    .035       0  3061.4    .045       0  4050.6    .035       0
  4220.3    .035       0  4624.9     .07       0  4809.7    .035       0
  5001.4    .035       0  5019.8    .035       0  5070.9     .07       0
  5197.8    .035       0  5295.9     .07       0  5390.4    .035       0
  5585.6     .07       0  6059.7    .035       0  6714.5     .07       0
  6826.8    .035       0  6911.8    .035       0  7043.1     .07       0
  7120.8    .035       0  7329.3     .07       0
Bank Sta=5001.4,5019.8
XS Rating Curve= 0 ,0
Exp/Cntr=0.3,0.1

Type RM Length L Ch R = 1 ,7194    ,1028,1028,1028
BEGIN DESCRIPTION:
MULBERRY CREEK TRIBUTARY 5 5.0
END DESCRIPTION:
XS GIS Cut Line= 3
      1570597.29      6887686.56       1571075.1       6886888.1
      1571854.99      6884788.04
#Sta/Elev= 30
  4069.5 1640.71  4504.2 1637.86  4620.7 1635.39  4822.6 1636.88    4928 1636.34
  4963.2 1633.14  4997.1 1629.63  5009.8 1631.87  5224.1 1630.63  5333.1 1632.85
  5348.9 1629.38  5349.4 1628.88  5367.3 1629.38  5405.5 1633.17  5458.8 1629.42
  5512.1 1629.85  5529.6 1633.56    5585  1631.9  5722.8 1634.54  5775.6  1633.7
  5848.3 1633.19  5936.6 1633.73  6352.9 1634.21  6485.4 1635.31  6810.9  1637.5
  6880.5 1638.24  6983.9 1640.03  7114.3 1644.96  7218.9 1652.73  7240.2 1656.79
#Mann= 15 ,-1 , 0
  4069.5    .045       0  4504.2    .035       0  4822.6     .07       0
  4963.2    .035       0  5348.9    .035       0  5367.3    .035       0
  5722.8     .07       0  5775.6    .035       0  5848.3     .07       0
  5936.6    .035       0  6352.9     .07       0  6485.4    .035       0
  6810.9     .07       0  6880.5    .035       0  6983.9     .07       0
Bank Sta=5348.9,5367.3
XS Rating Curve= 0 ,0
Exp/Cntr=0.3,0.1

Type RM Length L Ch R = 1 ,6166    ,1014,1014,1014
BEGIN DESCRIPTION:
MULBERRY CREEK TRIBUTARY 5 4.0
END DESCRIPTION:
XS GIS Cut Line= 3
      1571104.26      6887797.62      1571728.11      6887011.99
      1572104.99      6885388.05
#Sta/Elev= 30
  3996.8  1639.8  4003.9 1639.84  4329.9 1639.89  4543.8 1634.45  4797.7 1630.23
  4885.3 1629.69  4923.9 1629.74  4970.3 1625.95  4970.8 1625.45  4988.9 1625.95
  5049.4 1629.92  5081.9    1630  5227.2 1630.93  5250.5 1627.71  5260.7 1630.87
  5281.3 1627.94  5332.6 1631.53  5383.9 1628.42  5414.7 1631.73  5493.3 1628.68
  5668.3  1632.1  5783.4 1632.05  6026.4 1632.75  6037.9 1632.45  6225.7 1633.23
  6325.5 1634.18  6425.4 1634.37  6515.3 1635.93    6585 1648.39  6667.1 1648.99
#Mann= 18 ,-1 , 0
  3996.8    .045       0  4003.9    .035       0  4329.9    .045       0
  4543.8     .07       0  4797.7    .035       0  4885.3     .07       0
  4923.9    .035       0  4970.3    .035       0  4988.9    .035       0
  5049.4     .07       0  5081.9    .035       0  5668.3     .07       0
  5783.4    .035       0  6026.4     .07       0  6037.9    .035       0
  6225.7     .07       0  6325.5    .035       0  6425.4     .07       0
Bank Sta=4970.3,4988.9
XS Rating Curve= 0 ,0
Exp/Cntr=0.3,0.1

Type RM Length L Ch R = 1 ,5152    ,834,834,834
BEGIN DESCRIPTION:
MULBERRY CREEK TRIBUTARY 5 3.0
END DESCRIPTION:
XS GIS Cut Line= 3
        1571380.        6888113.      1572451.54      6887389.19
      1573092.24      6886166.48
#Sta/Elev= 30
  3706.9 1638.85  3916.7  1636.5  4096.5 1631.33  4482.9 1630.28  4594.4 1628.87
    4651 1628.43  4773.8 1626.58  4815.8 1628.96  4859.4 1627.64  4931.8 1628.76
  4980.4 1627.03  5046.5 1625.49  5061.3 1625.51  5069.1  1627.3  5128.6 1628.83
  5155.9 1632.59  5172.7 1633.01  5211.2  1626.3    5268 1624.49  5268.5 1623.99
  5286.8 1624.49  5315.8 1625.33    5360  1630.6  5399.3 1630.58  5427.7  1630.8
  5854.8 1634.33  6024.3  1634.5  6251.2 1636.19  6267.5 1636.41  6380.4 1637.44
#Mann= 14 ,-1 , 0
  3706.9    .045       0  4482.9    .035       0  4594.4    .045       0
    4651    .035       0  4980.4     .07       0  5155.9    .035       0
    5268     .07       0  5286.8    .035       0  5399.3     .07       0
  5427.7    .035       0  5854.8     .07       0  6024.3    .035       0
  6251.2     .07       0  6267.5    .035       0
#XS Ineff= 2 , 0
       0                  5172.7       0 1633.01
Permanent Ineff=
       F       F
Bank Sta=5046.5,5061.3
XS Rating Curve= 0 ,0
Exp/Cntr=0.3,0.1

Type RM Length L Ch R = 1 ,4318    ,487,487,487
BEGIN DESCRIPTION:
Mapping XS 26c15769
END DESCRIPTION:
XS GIS Cut Line= 3
      1571955.14      6888903.96      1572845.75      6887966.47
      1573620.55      6887113.67
#Sta/Elev= 30
  3694.1 1638.34  3731.7 1637.81  3917.5 1636.81  4094.3 1629.73  4201.9 1627.79
  4273.4 1627.61  4324.3 1627.76  4422.7 1627.99  4573.7 1626.09  4620.5 1626.17
    4686 1626.77  4773.4 1625.08  4943.3 1627.31  4971.3 1623.65  4989.5 1624.84
  4999.4 1627.38  5066.9 1627.24  5133.9  1627.3  5188.7 1623.46  5189.2 1622.96
  5207.6 1623.46  5208.1 1623.69  5226.5 1627.18  5370.8 1629.38  5522.7 1631.28
  5595.4 1631.98  5826.5 1635.19  5853.6 1635.49  6029.3 1639.94  6139.4 1641.14
#Mann= 19 ,-1 , 0
  3694.1     .07       0  3731.7    .045       0  4201.9     .07       0
  4273.4    .045       0  4324.3     .07       0  4422.7    .035       0
  4573.7     .07       0  4620.5    .035       0    4686     .07       0
  5066.9    .035       0  5188.7     .07       0  5207.6    .035       0
  5208.1     .07       0  5370.8    .035       0  5522.7     .07       0
  5595.4    .035       0  5826.5     .07       0  5853.6    .035       0
  6029.3     .07       0
Bank Sta=5188.7,5207.6
XS Rating Curve= 0 ,0
Exp/Cntr=0.3,0.1

Type RM Length L Ch R = 1 ,3831    ,1245,1245,1245
BEGIN DESCRIPTION:
Mapping XS ed9c37a9
END DESCRIPTION:
XS GIS Cut Line= 3
      1571970.75      6889528.97      1573132.21      6888346.68
      1573903.02      6887456.08
#Sta/Elev= 30
  3321.9 1638.39  3447.8 1636.84  3455.6 1636.58  3711.5 1631.96  3753.1 1630.94
  3778.2 1628.55  3976.2 1627.67  3990.3 1626.32  4386.3 1625.47  4506.5 1627.23
  4527.8  1625.8  4577.2 1626.25  4591.4 1622.82  4633.8 1622.79  4647.9 1624.32
  4669.1 1623.03  4683.2 1625.22  4746.9 1627.45  4810.5 1627.18    4945 1625.17
  4981.7 1622.85  4984.7 1621.47  4985.2 1620.97  5003.7 1621.47  5008.5 1622.88
  5079.8 1627.15  5171.9 1626.25    5377 1628.14  6058.1 1637.08  6157.1 1640.75
#Mann= 7 ,-1 , 0
  3321.9    .094       0  3447.8    .063       0  3455.6    .035       0
  3711.5    .063       0  3753.1    .035       0  4984.7    .035       0
  5003.7    .035       0
Bank Sta=4984.7,5003.7
XS Rating Curve= 0 ,0
Exp/Cntr=0.3,0.1

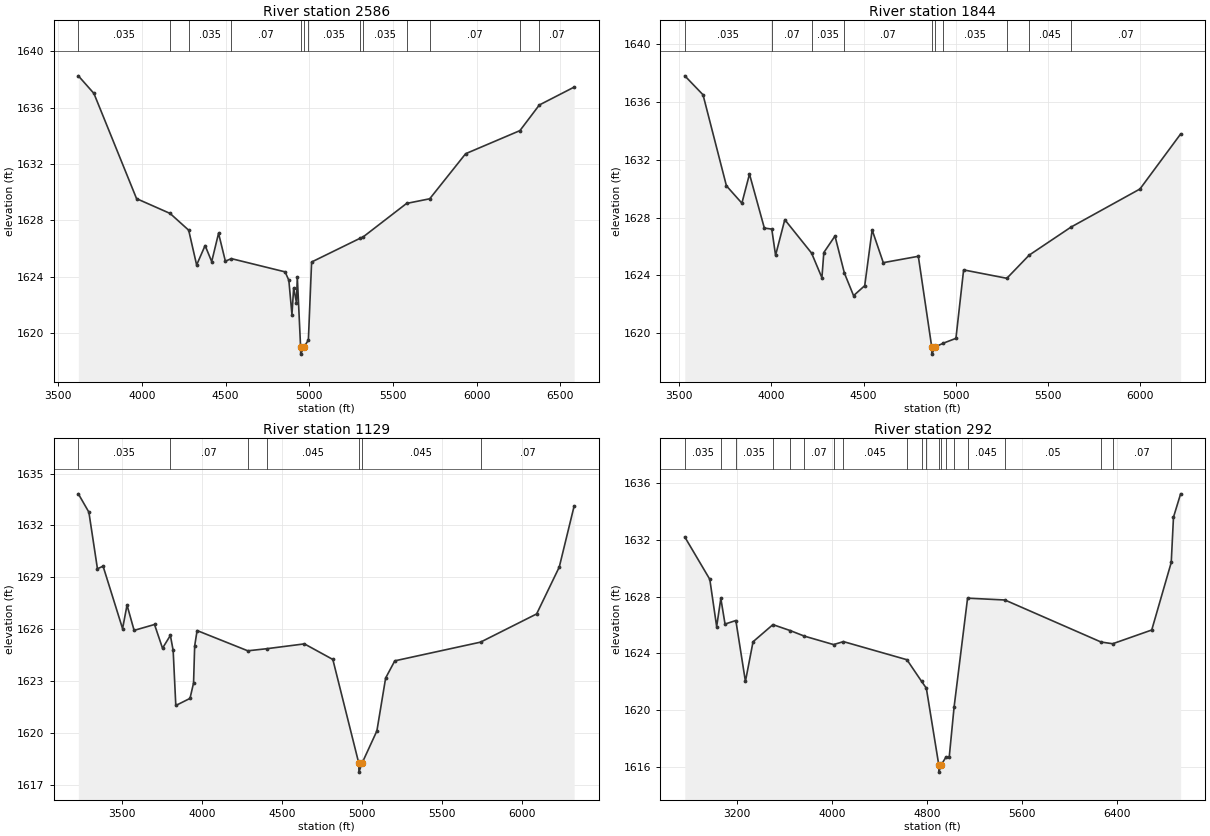
Type RM Length L Ch R = 1 ,2586    ,742,742,742
BEGIN DESCRIPTION:
MULBERRY CREEK TRIBUTARY 5 2.0
END DESCRIPTION:
XS GIS Cut Line= 3
      1572003.69      6889703.46      1573370.28      6889425.15
      1574479.99      6888315.44
#Sta/Elev= 30
  3619.6 1638.25  3712.8    1637  3967.7 1629.53    4168 1628.48  4279.3 1627.29
  4326.8 1624.82  4377.4  1626.2  4416.9 1625.06  4457.8 1627.07  4498.6 1625.09
  4534.5 1625.27  4855.8 1624.33    4878 1623.73  4896.6  1621.3  4906.8  1623.2
  4923.5 1622.15  4928.6 1623.97  4948.3 1618.99  4948.8 1618.49  4967.4 1618.99
  4994.7 1619.48  5014.1 1625.03  5302.8 1626.71  5323.1 1626.82  5581.9 1629.19
  5720.2 1629.52  5934.8 1632.72  6259.4 1634.36  6375.4 1636.18  6583.6 1637.45
#Mann= 13 ,-1 , 0
  3619.6    .035       0    4168     .07       0  4279.3    .035       0
  4534.5     .07       0  4948.3    .035       0  4967.4     .07       0
  4994.7    .035       0  5302.8     .07       0  5323.1    .035       0
  5581.9    .045       0  5720.2     .07       0  6259.4    .035       0
  6375.4     .07       0
Bank Sta=4948.3,4967.4
XS Rating Curve= 0 ,0
Exp/Cntr=0.3,0.1

Type RM Length L Ch R = 1 ,1844    ,715,715,715
BEGIN DESCRIPTION:
Mapping XS 8ef4a081
END DESCRIPTION:
XS GIS Cut Line= 3
      1571996.92      6889876.91      1573434.44      6890043.58
      1574614.97      6889668.59
#Sta/Elev= 30
  3531.7 1637.79  3630.4 1636.48  3757.2 1630.19  3840.9 1628.99  3882.1    1631
  3962.6 1627.27  4002.8  1627.2  4023.4 1625.39  4073.4 1627.85  4218.5 1625.54
  4274.4 1623.84  4284.8 1625.58  4345.2 1626.72  4396.2 1624.16  4445.9  1622.6
  4506.3 1623.29  4546.5 1627.14  4606.9 1624.88  4796.7 1625.32  4869.2 1619.06
  4869.7 1618.56  4888.3 1619.06  4932.8 1619.32  5000.4 1619.65    5042 1624.38
  5276.2  1623.8  5397.1  1625.4    5624 1627.34  5997.2 1629.97  6217.5 1633.77
#Mann= 10 ,-1 , 0
  3531.7    .035       0  4002.8     .07       0  4218.5    .035       0
  4396.2     .07       0  4869.2    .035       0  4888.3     .07       0
  4932.8    .035       0  5276.2     .07       0  5397.1    .045       0
    5624     .07       0
Bank Sta=4869.2,4888.3
XS Rating Curve= 0 ,0
Exp/Cntr=0.3,0.1

Type RM Length L Ch R = 1 ,1129    ,837,837,837
BEGIN DESCRIPTION:
Mapping XS ac6ec976
END DESCRIPTION:
XS GIS Cut Line= 4
      1572128.84      6889974.12      1573517.77      6890689.41
      1573871.94      6890633.86       1574642.8      6889744.94
#Sta/Elev= 30
  3228.5 1633.83  3294.4 1632.77  3347.9  1629.5  3383.1 1629.65  3504.9 1626.04
  3532.7  1627.4    3577 1625.94  3704.4 1626.28  3754.4 1624.91  3803.5 1625.65
  3820.9 1624.78  3837.4  1621.6  3926.1 1622.01  3948.3  1622.9  3955.3 1625.04
  3970.4 1625.93  4287.1 1624.76  4404.5 1624.88  4640.8 1625.16  4818.4 1624.26
  4980.9 1618.25  4981.4 1617.75    5000 1618.25  5093.5 1620.13  5148.3 1623.19
  5205.4 1624.18  5740.9 1625.26  6091.4 1626.89  6232.9  1629.6  6325.9 1633.13
#Mann= 7 ,-1 , 0
  3228.5    .035       0  3803.5     .07       0  4287.1    .035       0
  4404.5    .045       0  4980.9    .045       0    5000    .045       0
  5740.9     .07       0
Bank Sta=4980.9,5000
XS Rating Curve= 0 ,0
Exp/Cntr=0.3,0.1

Type RM Length L Ch R = 1 ,292     ,0,0,0
BEGIN DESCRIPTION:
MULBERRY CREEK TRIBUTARY 5 1.0
END DESCRIPTION:
XS GIS Cut Line= 3
      1572031.64      6890085.23      1573787.97      6891471.48
      1574809.44       6889828.3
#Sta/Elev= 30
  2762.5 1632.22  2972.9 1629.23  3030.6 1625.89  3065.7 1627.88  3101.1 1626.07
  3192.1 1626.32  3272.7 1622.02  3336.8 1624.82    3504 1626.03  3649.5 1625.61
  3767.8 1625.22  4014.6 1624.62  4097.5 1624.83  4631.7 1623.55  4755.1 1622.02
    4795 1621.54  4899.9 1616.11  4900.4 1615.61  4919.1 1616.11  4958.7 1616.65
  4988.1 1616.71  5028.6 1620.21    5142  1627.9  5456.1 1627.77  6265.5  1624.8
  6363.2 1624.68  6691.7 1625.65  6855.8 1630.42  6874.7 1633.62  6934.8 1635.27
#Mann= 20 ,-1 , 0
  2762.5    .035       0  3065.7     .07       0  3192.1    .035       0
    3504     .07       0  3649.5    .045       0  3767.8     .07       0
  4014.6     .07       0  4097.5    .045       0  4631.7    .045       0
  4755.1     .07       0    4795    .035       0  4899.9    .035       0
  4919.1    .045       0  4958.7    .035       0  5028.6     .07       0
    5142    .045       0  5456.1     .05       0  6265.5    .045       0
  6363.2     .07       0  6855.8    .035       0
Bank Sta=4899.9,4919.1
XS Rating Curve= 0 ,0
Exp/Cntr=0.3,0.1

Chan Stop Cuts=-1
Use User Specified Reach Order=0
Composite Channel Slope=5