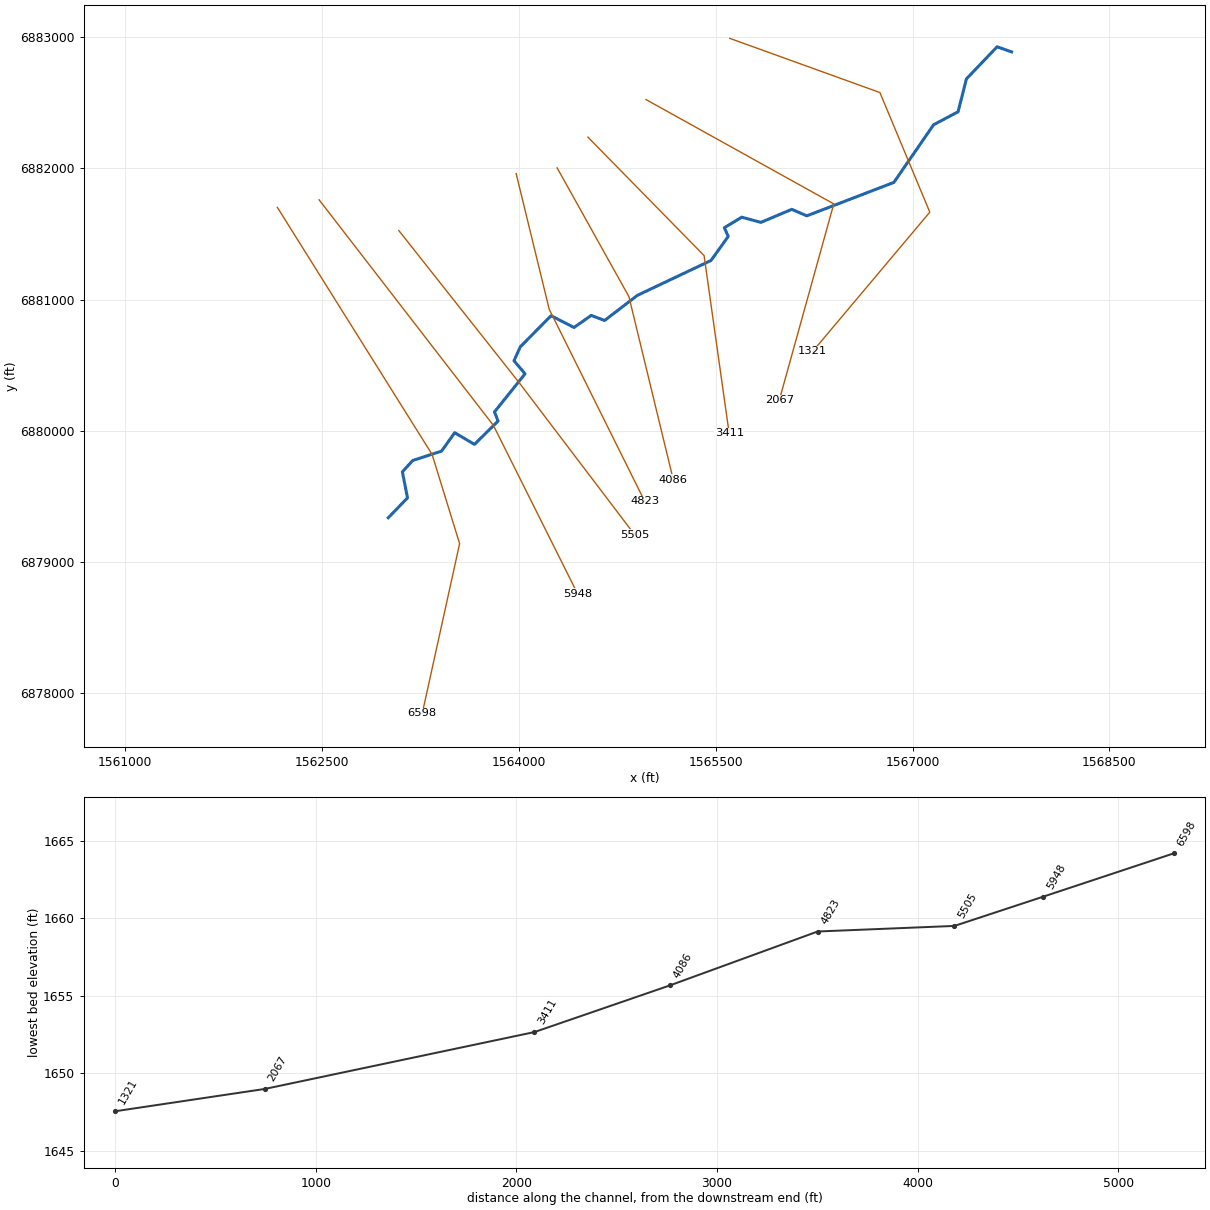
--- MULBERRY CREEK TRIBUTARY 5_1.prj (project) ---

Proj Title=MULBERRY CREEK TRIBUTARY 5_1 Base Level Engineering
Current Plan=p01
Default Exp/Contr=0.3,0.1
English Units
Geom File=g01
Flow File=f01
Plan File=p01
BEGIN DESCRIPTION:
MULBERRY CREEK TRIBUTARY 5_1
END DESCRIPTION:

--- MULBERRY CREEK TRIBUTARY 5_1.p01 (plan) ---

Plan Title=Multiple Run
Short Identifier=Multiple
Geom File=g01
Flow File=f01
Subcritical Flow
K Sum by GR= 0
Std Step Tol= 0.01
Critical Tol= 0.01
Num of Std Step Trials= 20
Max Error Tol= 0.3
Flow Tol Ratio= 0.001
Split Flow NTrial= 30
Split Flow Tol= 0.02
Split Flow Ratio= 0.02
Log Output Level= 0
Friction Slope Method= 1
Unsteady Friction Slope Method= 2
Unsteady Bridges Friction Slope Method= 1
Parabolic Critical Depth
Global Vel Dist=  1 , 1 , 1
Global Log Level= 0
CheckData=True
Encroach Param= -1, 0, 0, 0
BEGIN DESCRIPTION:
Multiple Run
END DESCRIPTION:

--- MULBERRY CREEK TRIBUTARY 5_1.f01 (steady flow) ---

Flow Title=Multiple
Number of Profiles=7
Profile Names=10-year,25-year,50-year,1pct_min,100-year,1pct_plu,500-year
River Rch & RM= MULBERRY CREEK T,Reach-1,6598
     266     367     451     275     548    1094     823
Boundary for River Rch & Prof#=MULBERRY CREEK T,Reach-1,1
Up Type=0
Dn Type=3
Dn Slope=0.005
Boundary for River Rch & Prof#=MULBERRY CREEK T,Reach-1,2
Up Type=0
Dn Type=3
Dn Slope=0.005
Boundary for River Rch & Prof#=MULBERRY CREEK T,Reach-1,3
Up Type=0
Dn Type=3
Dn Slope=0.005
Boundary for River Rch & Prof#=MULBERRY CREEK T,Reach-1,4
Up Type=0
Dn Type=3
Dn Slope=0.005
Boundary for River Rch & Prof#=MULBERRY CREEK T,Reach-1,5
Up Type=0
Dn Type=3
Dn Slope=0.005
Boundary for River Rch & Prof#=MULBERRY CREEK T,Reach-1,6
Up Type=0
Dn Type=3
Dn Slope=0.005
Boundary for River Rch & Prof#=MULBERRY CREEK T,Reach-1,7
Up Type=0
Dn Type=3
Dn Slope=0.005

--- MULBERRY CREEK TRIBUTARY 5_1.g01 (geometry) ---

Geom Title=Existing Conditions

River Reach=MULBERRY CREEK T,Reach-1
Reach XY= 30
      1563005.00      6879338.00      1563151.48      6879489.47
      1563112.31      6879688.11      1563191.64      6879774.60
      1563411.34      6879846.02      1563510.87      6879986.49
      1563661.67      6879896.96      1563841.35      6880074.67
      1563814.30      6880144.68      1564047.15      6880434.77
      1563962.80      6880534.59      1564010.80      6880640.29
      1564245.32      6880877.83      1564420.36      6880787.90
      1564551.60      6880880.16      1564653.35      6880841.17
      1564902.58      6881032.46      1565464.70      6881298.76
      1565595.41      6881481.46      1565566.11      6881548.32
      1565698.38      6881628.59      1565844.52      6881588.95
      1566079.96      6881688.31      1566194.31      6881638.77
      1566857.71      6881893.41      1567160.44      6882332.75
      1567347.19      6882431.79      1567410.59      6882682.39
      1567644.62      6882927.15      1567755.00      6882888.00

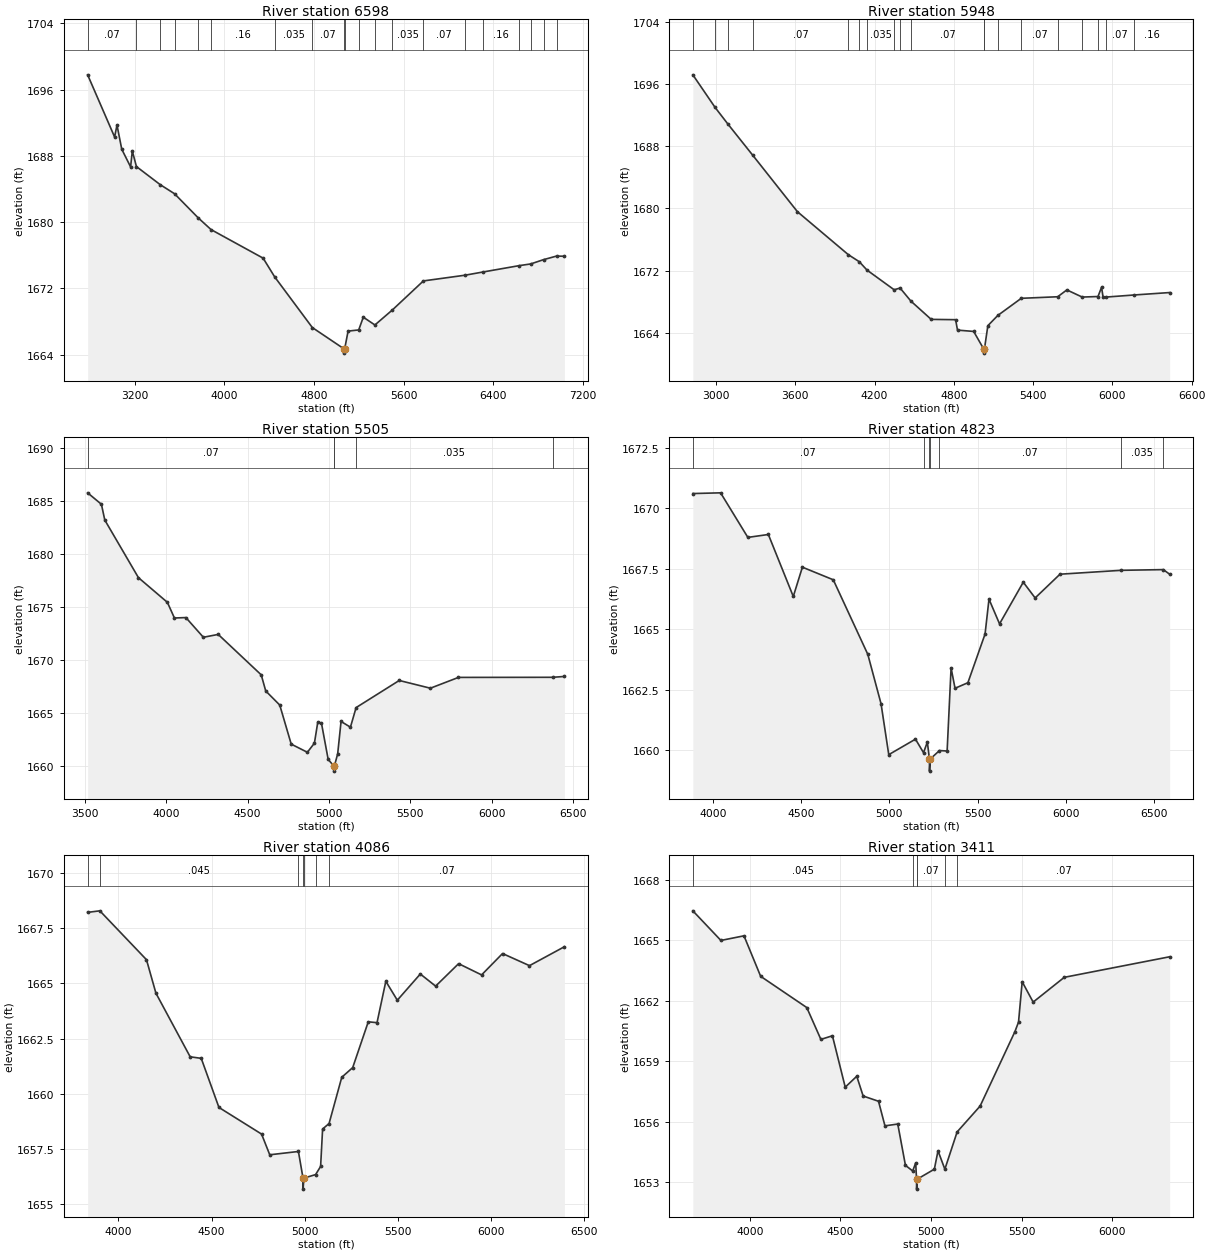
Type RM Length L Ch R = 1,6598,650,650,650
BEGIN DESCRIPTION:
MULBERRY CREEK TRIBUTARY 5_1 2.0
END DESCRIPTION:
XS GIS Cut Line= 4
      1562159.59      6881703.16      1563338.52      6879820.89
      1563548.51      6879140.62      1563263.78      6877847.23
#Sta/Elev= 30
  2779.0 1697.79  3019.9 1690.28  3041.2 1691.72  3083.6 1688.81  3162.7 1686.67
  3177.9 1688.59  3214.8 1686.71  3426.7 1684.53  3554.9 1683.43  3767.5 1680.50
  3881.0 1679.10  4346.0 1675.65  4449.0 1673.39  4785.2 1667.27  5069.9 1664.68
  5070.1 1664.18  5074.0 1664.68  5104.6 1666.84  5199.5 1666.98  5240.4 1668.52
  5344.1 1667.58  5499.8 1669.39  5776.9 1672.90  6148.8 1673.59  6309.9 1673.98
  6634.0 1674.75  6734.8 1674.95  6849.9 1675.47  6965.6 1675.90  7036.3 1675.88
#Mann=20,-1,0
  2779.0    0.07       0  3214.8    0.16       0  3426.7    0.07       0
  3554.9   0.035       0  3767.5    0.07       0  3881.0    0.16       0
  4449.0   0.035       0  4785.2    0.07       0  5069.9    0.07       0
  5074.0    0.07       0  5199.5    0.07       0  5344.1    0.16       0
  5499.8   0.035       0  5776.9    0.07       0  6148.8   0.035       0
  6309.9    0.16       0  6634.0    0.07       0  6734.8    0.16       0
  6849.9    0.07       0  6965.6    0.16       0
Bank Sta=5069.9,5074
Exp/Cntr=0.3,0.1

Type RM Length L Ch R = 1,5948,443,443,443
BEGIN DESCRIPTION:
Mapping XS e2c1ea2e
END DESCRIPTION:
XS GIS Cut Line= 3
      1562477.55      6881761.03      1563805.69      6880042.26
      1564448.06      6878757.53
#Sta/Elev= 30
  2824.8 1697.18  2993.5 1692.98  3092.0 1690.81  3277.6 1686.85  3616.2 1679.58
  4001.7 1674.05  4084.9 1673.14  4142.9 1672.07  4348.2 1669.54  4393.3 1669.76
  4475.2 1668.08  4628.7 1665.73  4813.4 1665.69  4827.9 1664.35  4950.2 1664.18
  5027.2 1661.89  5027.5 1661.39  5031.4 1661.89  5057.6 1664.92  5133.1 1666.24
  5310.5 1668.44  5586.1 1668.64  5655.4 1669.52  5771.4 1668.60  5891.1 1668.67
  5918.1 1669.86  5929.7 1668.59  5953.2 1668.60  6166.3 1668.87  6433.3 1669.18
#Mann=19,-1,0
  2824.8   0.035       0  2993.5    0.07       0  3092.0   0.035       0
  3277.6    0.07       0  4001.7   0.035       0  4084.9    0.07       0
  4142.9   0.035       0  4348.2    0.07       0  4393.3   0.035       0
  4475.2    0.07       0  5027.2    0.07       0  5031.4    0.07       0
  5133.1   0.035       0  5310.5    0.07       0  5586.1    0.16       0
  5771.4    0.07       0  5891.1    0.16       0  5953.2    0.07       0
  6166.3    0.16       0
Bank Sta=5027.2,5031.4
Exp/Cntr=0.3,0.1

Type RM Length L Ch R = 1,5505,682,682,682
BEGIN DESCRIPTION:
Mapping XS abb98656
END DESCRIPTION:
XS GIS Cut Line= 3
      1563085.23      6881526.60      1564005.34      6880363.44
      1564881.01      6879210.33
#Sta/Elev= 30
  3517.2 1685.78  3601.9 1684.70  3622.7 1683.21  3829.5 1677.77  4007.4 1675.44
  4050.7 1673.96  4121.2 1674.00  4228.6 1672.14  4319.9 1672.41  4584.4 1668.59
  4612.0 1667.07  4698.2 1665.74  4768.7 1662.05  4868.0 1661.28  4911.3 1662.14
  4932.1 1664.14  4954.6 1664.03  4996.0 1660.60  5030.0 1660.00  5030.3 1659.50
  5034.4 1660.00  5054.3 1661.13  5075.1 1664.19  5132.7 1663.65  5167.6 1665.50
  5432.8 1668.06  5624.2 1667.33  5796.8 1668.35  6375.9 1668.36  6448.2 1668.44
#Mann=5,-1,0
  3517.2    0.07       0  5030.0    0.07       0  5034.4    0.07       0
  5167.6   0.035       0  6375.9    0.07       0
Bank Sta=5030,5034.4
Exp/Cntr=0.3,0.1

Type RM Length L Ch R = 1,4823,737,737,737
BEGIN DESCRIPTION:
Mapping XS 1aca7f53
END DESCRIPTION:
XS GIS Cut Line= 3
      1563979.31      6881960.64      1564231.04      6880927.67
      1564959.53      6879462.03
#Sta/Elev= 30
  3887.1 1670.60  4044.2 1670.63  4198.6 1668.79  4314.7 1668.91  4455.9 1666.35
  4507.4 1667.56  4682.3 1667.04  4877.9 1663.96  4952.9 1661.92  4996.5 1659.82
  5147.8 1660.46  5193.4 1659.90  5215.0 1660.34  5226.9 1659.64  5227.2 1659.14
  5231.4 1659.64  5283.7 1659.99  5327.0 1659.97  5349.4 1663.40  5371.8 1662.56
  5444.6 1662.79  5541.8 1664.80  5564.1 1666.24  5623.8 1665.22  5758.2 1666.94
  5825.4 1666.29  5966.1 1667.27  6310.7 1667.43  6551.0 1667.46  6587.0 1667.27
#Mann=7,-1,0
  3887.1    0.07       0  5193.4   0.035       0  5226.9    0.07       0
  5231.4   0.035       0  5283.7    0.07       0  6310.7   0.035       0
  6551.0    0.07       0
Bank Sta=5226.9,5231.4
Exp/Cntr=0.3,0.1

Type RM Length L Ch R = 1,4086,675,675,675
BEGIN DESCRIPTION:
Mapping XS e2a1e17d
END DESCRIPTION:
XS GIS Cut Line= 3
      1564291.80      6882004.06      1564838.68      6881023.16
      1565177.21      6879625.62
#Sta/Elev= 30
  3834.2 1668.23  3899.8 1668.30  4150.3 1666.08  4201.0 1664.56  4385.0 1661.67
  4444.4 1661.60  4539.5 1659.37  4768.5 1658.16  4812.4 1657.22  4966.4 1657.37
  4991.1 1656.16  4991.5 1655.66  4995.7 1656.16  5058.6 1656.32  5085.6 1656.69
  5096.3 1658.39  5131.0 1658.64  5199.2 1660.74  5258.0 1661.18  5341.6 1663.26
  5388.6 1663.22  5435.9 1665.10  5497.6 1664.24  5621.1 1665.43  5703.4 1664.88
  5826.8 1665.90  5950.3 1665.39  6062.8 1666.36  6207.5 1665.81  6395.2 1666.67
#Mann=7,-1,0
  3834.2    0.07       0  3899.8   0.045       0  4966.4    0.07       0
  4991.1    0.07       0  4995.7    0.07       0  5058.6   0.035       0
  5131.0    0.07       0
Bank Sta=4991.1,4995.7
Exp/Cntr=0.3,0.1

Type RM Length L Ch R = 1,3411,1344,1344,1344
BEGIN DESCRIPTION:
Mapping XS e2a0ed16
END DESCRIPTION:
XS GIS Cut Line= 3
      1564526.20      6882238.41      1565411.59      6881335.66
      1565602.46      6879982.22
#Sta/Elev= 30
  3686.1 1666.46  3841.0 1664.99  3968.3 1665.22  4060.4 1663.21  4314.9 1661.66
  4392.7 1660.08  4456.4 1660.26  4527.1 1657.71  4590.7 1658.25  4626.0 1657.27
  4710.8 1657.01  4746.3 1655.79  4817.0 1655.88  4859.4 1653.83  4899.4 1653.55
  4916.0 1653.95  4920.6 1653.15  4921.0 1652.65  4925.5 1653.15  5018.9 1653.64
  5039.1 1654.55  5076.9 1653.64  5144.7 1655.49  5271.4 1656.77  5463.3 1660.46
  5483.5 1660.94  5503.7 1662.94  5564.2 1661.93  5735.9 1663.16  6317.4 1664.18
#Mann=6,-1,0
  3686.1   0.045       0  4899.4    0.07       0  4920.6    0.07       0
  4925.5    0.07       0  5076.9   0.035       0  5144.7    0.07       0
Bank Sta=4920.6,4925.5
Exp/Cntr=0.3,0.1

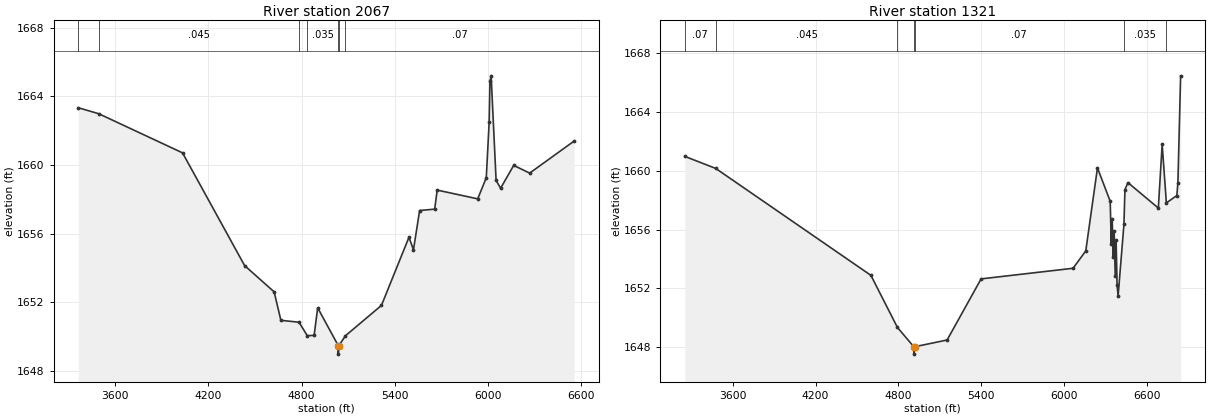
Type RM Length L Ch R = 1,2067,746,746,746
BEGIN DESCRIPTION:
Mapping XS 9c9cd68f
END DESCRIPTION:
XS GIS Cut Line= 3
      1564968.84      6882524.92      1566399.88      6881729.76
      1565984.51      6880233.24
#Sta/Elev= 30
  3363.5 1663.34  3495.1 1662.99  4034.1 1660.71  4433.4 1654.14  4623.3 1652.61
  4666.8 1650.95  4783.4 1650.84  4836.1 1650.06  4880.6 1650.07  4903.5 1651.68
  5035.6 1649.48  5036.0 1648.98  5040.6 1649.48  5082.1 1650.05  5313.8 1651.82
  5490.8 1655.79  5519.9 1655.06  5559.3 1657.35  5656.3 1657.43  5672.5 1658.54
  5933.1 1658.03  5988.3 1659.26  6006.8 1662.50  6012.0 1664.87  6019.5 1665.20
  6051.5 1659.10  6080.5 1658.65  6164.8 1659.98  6267.4 1659.53  6553.7 1661.40
#Mann=7,-1,0
  3363.5    0.07       0  3495.1   0.045       0  4783.4    0.07       0
  4836.1   0.035       0  5035.6   0.035       0  5040.6   0.035       0
  5082.1    0.07       0
Bank Sta=5035.6,5040.6
Exp/Cntr=0.3,0.1

Type RM Length L Ch R = 1,1321,0,0,0
BEGIN DESCRIPTION:
Mapping XS cc49e4e5
END DESCRIPTION:
XS GIS Cut Line= 4
      1565606.90      6882991.48      1566751.44      6882578.28
      1567131.65      6881666.82      1566239.24      6880605.73
#Sta/Elev= 30
  3253.2 1660.97  3477.4 1660.15  4601.0 1652.89  4793.3 1649.35  4912.0 1648.04
  4912.4 1647.54  4917.1 1648.04  5153.0 1648.50  5399.1 1652.65  6064.9 1653.37
  6157.2 1654.55  6241.8 1660.19  6334.1 1657.92  6341.9 1655.03  6348.4 1656.74
  6356.2 1654.14  6362.7 1655.91  6370.5 1652.85  6377.0 1655.26  6383.8 1652.25
  6391.3 1651.48  6433.7 1656.37  6440.8 1658.70  6462.2 1659.19  6682.7 1657.46
  6710.5 1661.79  6740.8 1657.81  6816.7 1658.31  6824.5 1659.19  6844.1 1666.44
#Mann=7,-1,0
  3253.2    0.07       0  3477.4   0.045       0  4793.3    0.07       0
  4912.0    0.07       0  4917.1    0.07       0  6433.7   0.035       0
  6740.8    0.07       0
Bank Sta=4912,4917.1
Exp/Cntr=0.3,0.1

Chan Stop Cuts=-1