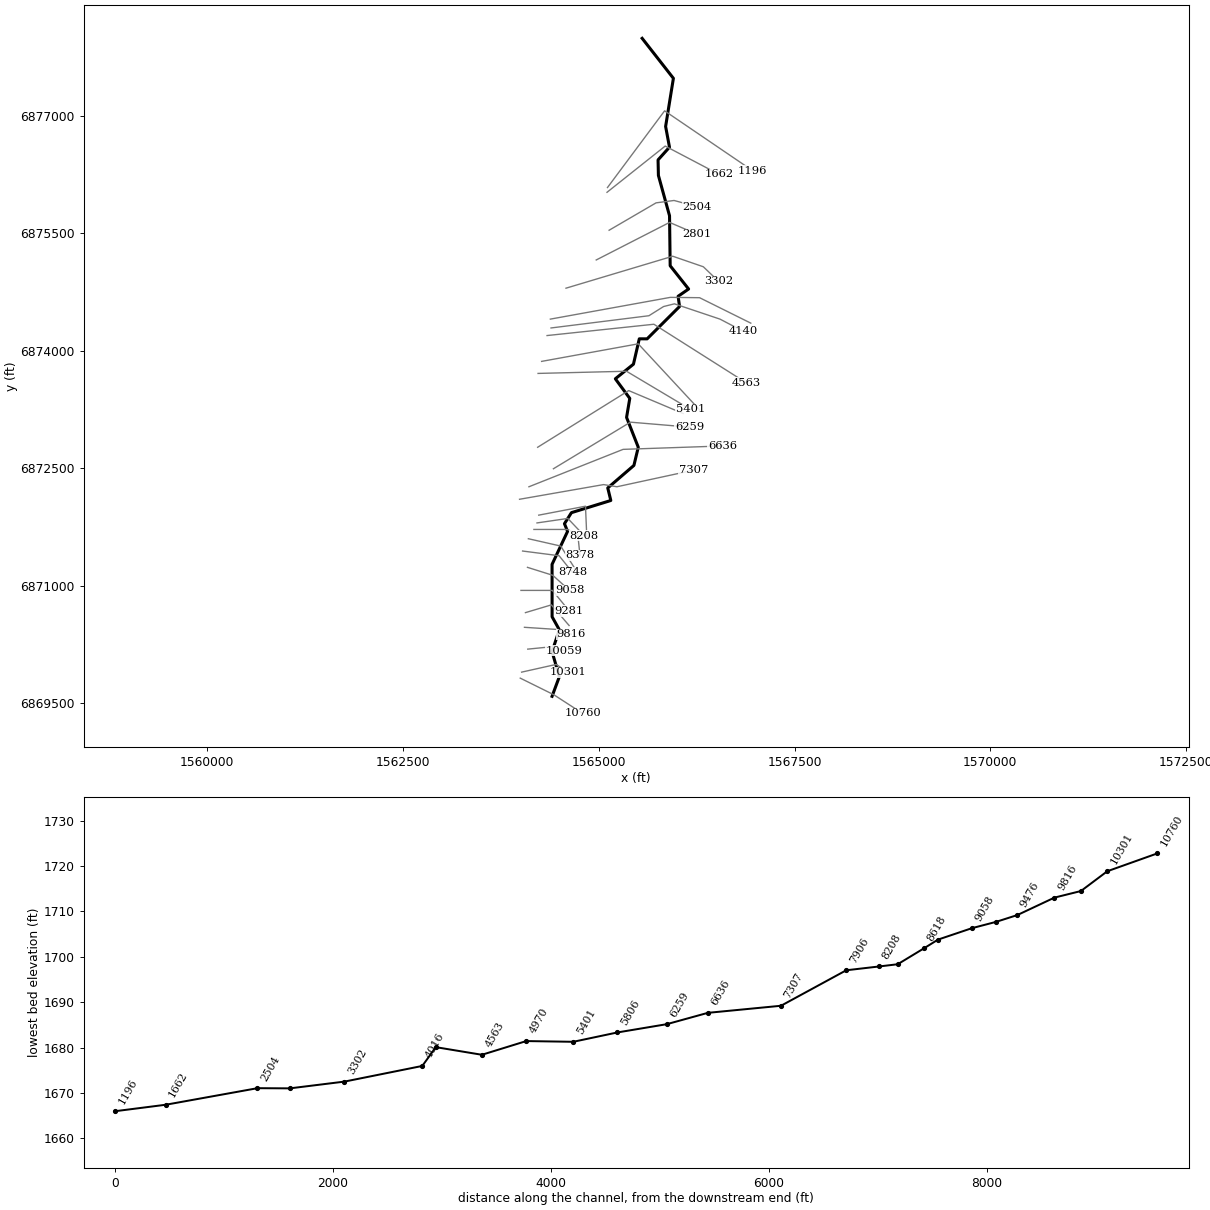
--- MULBERRY CREEK TRIBUTARY 5_2.prj (project) ---

Proj Title=MULBERRY CREEK TRIBUTARY 5_2 Base Level Engineering
Current Plan=p01
Default Exp/Contr=0.3,0.1
English Units
Geom File=g01
Flow File=f01
Plan File=p01
Y Axis Title=Elevation
X Axis Title(PF)=Main Channel Distance
X Axis Title(XS)=Station
BEGIN DESCRIPTION:
MULBERRY CREEK TRIBUTARY 5_2
END DESCRIPTION:
DSS Export Rating Curves= 0
DSS Export Rating Curve Sorted= 0
DSS Export Volume Flow Curves= 0
DXF OffsetX= 0
DXF OffsetY= 0
DXF ScaleX= 1
DXF ScaleY= 10

--- MULBERRY CREEK TRIBUTARY 5_2.p01 (plan) ---

Plan Title=Multiple Run
Short Identifier=Multiple
Geom File=g01
Flow File=f01
Subcritical Flow
K Sum by GR= 0
Std Step Tol= 0.01
Critical Tol= 0.01
Num of Std Step Trials= 20
Max Error Tol= 0.3
Flow Tol Ratio= 0.001
Split Flow NTrial= 30
Split Flow Tol= 0.02
Split Flow Ratio= 0.02
Log Output Level= 0
Friction Slope Method= 1
Unsteady Friction Slope Method= 2
Unsteady Bridges Friction Slope Method= 1
Parabolic Critical Depth
Global Vel Dist=  1 , 1 , 1
Global Log Level= 0
CheckData=True
Encroach Param= -1, 0, 0, 0
BEGIN DESCRIPTION:
Multiple Run
END DESCRIPTION:

--- MULBERRY CREEK TRIBUTARY 5_2.f01 (steady flow) ---

Flow Title=Multiple
Program Version=4.10
Number of Profiles= 7
Profile Names=10-year,25-year,50-year,1pct_min,100-year,1pct_plu,500-year
River Rch & RM=MULBERRY CREEK T,Reach-1         ,10760
      83     108     127      75     150     299     210
River Rch & RM=MULBERRY CREEK T,Reach-1         ,7307
     220     302     370     226     451     900     678
River Rch & RM=MULBERRY CREEK T,Reach-1         ,1662
     247     342     421     258     514    1026     778
Boundary for River Rch & Prof#=MULBERRY CREEK T,Reach-1         , 1
Up Type= 0
Dn Type= 3
Dn Slope=0.006
Boundary for River Rch & Prof#=MULBERRY CREEK T,Reach-1         , 2
Up Type= 0
Dn Type= 3
Dn Slope=0.006
Boundary for River Rch & Prof#=MULBERRY CREEK T,Reach-1         , 3
Up Type= 0
Dn Type= 3
Dn Slope=0.006
Boundary for River Rch & Prof#=MULBERRY CREEK T,Reach-1         , 4
Up Type= 0
Dn Type= 3
Dn Slope=0.006
Boundary for River Rch & Prof#=MULBERRY CREEK T,Reach-1         , 5
Up Type= 0
Dn Type= 3
Dn Slope=0.006
Boundary for River Rch & Prof#=MULBERRY CREEK T,Reach-1         , 6
Up Type= 0
Dn Type= 3
Dn Slope=0.006
Boundary for River Rch & Prof#=MULBERRY CREEK T,Reach-1         , 7
Up Type= 0
Dn Type= 3
Dn Slope=0.006
DSS Import GetInterval= 0
DSS Import GetPeak= 0
DSS Import FillOption= 0

--- MULBERRY CREEK TRIBUTARY 5_2.g01 (geometry) ---

Geom Title=Existing Conditions
Program Version=4.10

River Reach=MULBERRY CREEK T,Reach-1
Reach XY= 30
        1564405.        6869588.      1564497.66       6869837.9
      1564405.05      6870158.04       1564497.5        6870438.
      1564405.51      6870603.21      1564405.02      6871272.64
      1564603.16      6871694.12      1564563.07      6871791.31
      1564652.32      6871932.58        1565155.        6872088.
      1565115.95      6872248.02      1565449.88      6872535.71
      1565505.46      6872767.84      1565356.11      6873148.55
      1565397.02      6873391.33      1565212.67      6873641.66
      1565443.89      6873827.95      1565518.62        6874152.
      1565618.68      6874151.51      1566032.44      6874564.16
      1566014.04      6874695.01      1566148.01      6874787.79
      1565912.83       6875084.6      1565904.63      6875722.83
      1565762.56        6876238.      1565758.13      6876436.37
      1565903.96      6876598.44       1565854.6        6876863.
      1565953.94      6877477.57        1565555.        6877988.

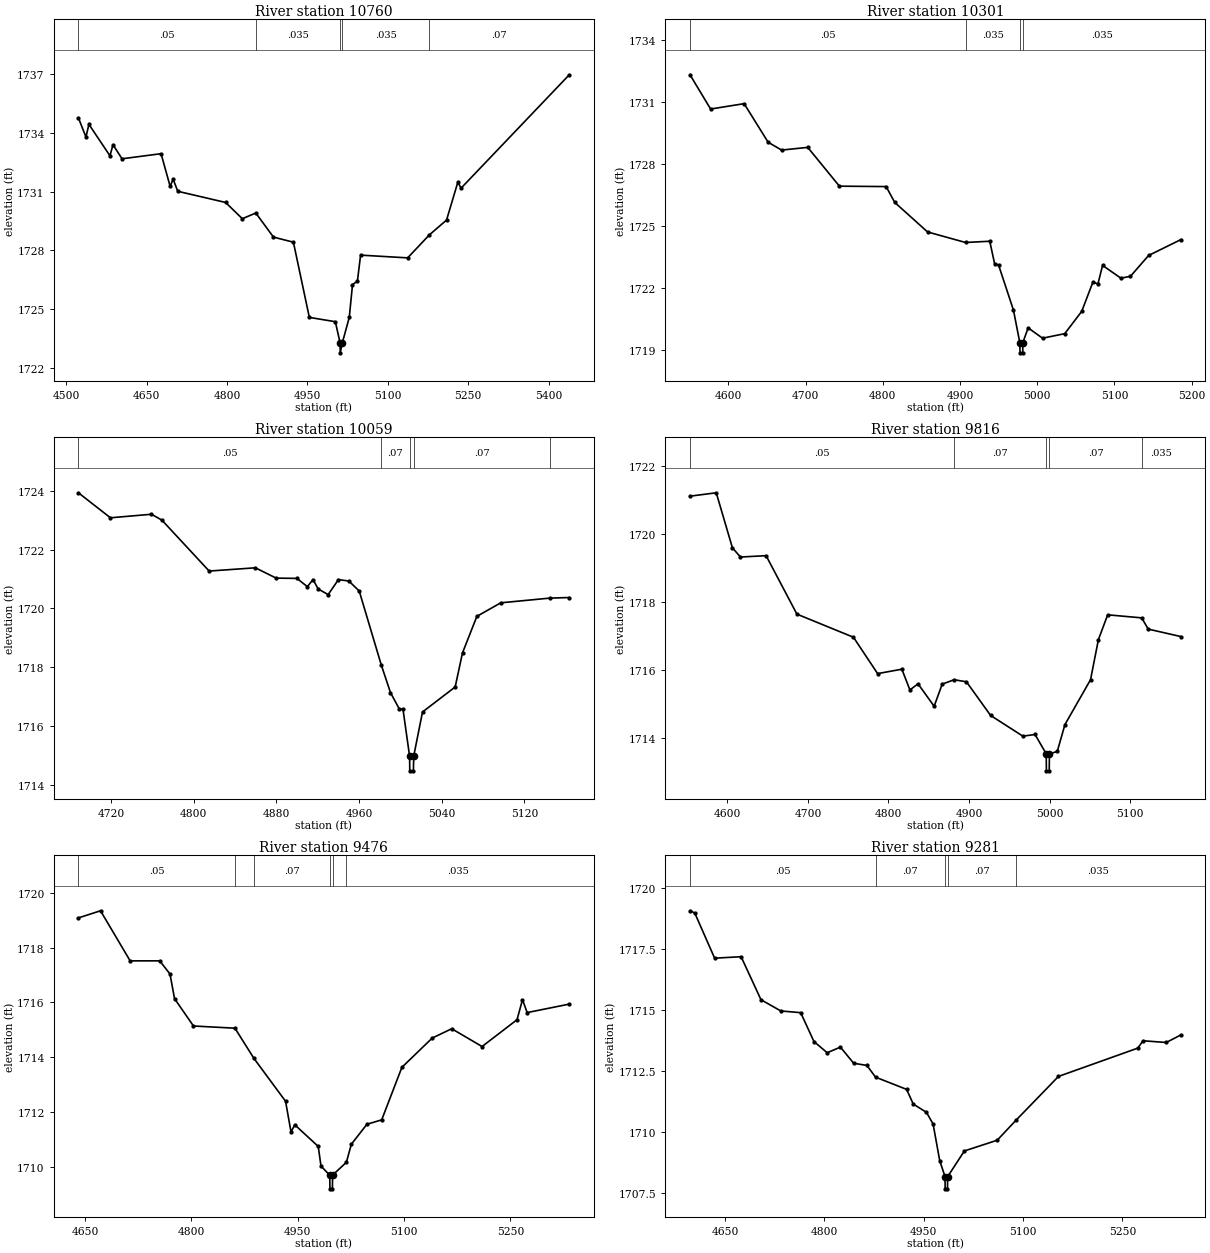
Type RM Length L Ch R = 1 ,10760   ,459,459,459
BEGIN DESCRIPTION:
MULBERRY CREEK TRIBUTARY 5_2 16.0
END DESCRIPTION:
XS GIS Cut Line= 3
      1563998.94        6869820.      1564426.55      6869608.39
      1564794.61      6869370.22
#Sta/Elev= 30
  4522.9 1734.77    4537 1733.79  4542.5 1734.44  4581.8 1732.83  4587.4  1733.4
  4604.3 1732.68  4677.1 1732.94    4694 1731.27  4699.6 1731.64  4708.2 1731.02
  4797.4 1730.45  4828.6 1729.62  4853.8 1729.91  4886.7 1728.68  4923.9 1728.42
  4953.6 1724.58  5002.1 1724.36    5011 1723.27  5011.2 1722.77    5015 1723.27
  5028.1 1724.58  5034.1 1726.25  5043.3 1726.44  5049.2 1727.76    5137 1727.62
  5177.3 1728.79  5209.5 1729.55  5230.6 1731.49  5236.6 1731.18  5438.4 1736.97
#Mann= 5 ,-1 , 0
  4522.9     .05       0  4853.8    .035       0    5011    .035       0
    5015    .035       0  5177.3     .07       0
Bank Sta=5011,5015
XS Rating Curve= 0 ,0
Exp/Cntr=0.3,0.1

Type RM Length L Ch R = 1 ,10301   ,242,242,242
BEGIN DESCRIPTION:
Mapping XS 6568fc46
END DESCRIPTION:
XS GIS Cut Line= 3
       1564016.2      6869896.68      1564458.87      6869995.63
      1564608.78      6869892.25
#Sta/Elev= 30
  4550.3 1732.32    4577 1730.66  4620.4 1730.92  4651.5 1729.05  4668.9 1728.67
  4702.8  1728.8  4743.8 1726.92  4804.3  1726.9  4815.5 1726.13    4858  1724.7
  4907.1 1724.19  4938.5 1724.25  4944.8 1723.16  4949.9  1723.1  4969.2 1720.91
  4977.4 1719.34  4977.7 1718.84  4981.2 1718.84  4981.4 1719.34  4988.2 1720.05
  5006.9 1719.55  5035.6 1719.77  5057.6 1720.85  5072.1 1722.27  5078.6 1722.18
  5084.6 1723.08  5108.3 1722.46  5120.7 1722.55  5144.2 1723.56    5186 1724.33
#Mann= 4 ,-1 , 0
  4550.3     .05       0  4907.1    .035       0  4977.4    .035       0
  4981.4    .035       0
Bank Sta=4977.4,4981.4
XS Rating Curve= 0 ,0
Exp/Cntr=0.3,0.1

Type RM Length L Ch R = 1 ,10059   ,243,243,243
BEGIN DESCRIPTION:
Mapping XS f25b4c4e
END DESCRIPTION:
XS GIS Cut Line= 3
      1564094.62      6870190.37      1564407.08      6870221.62
      1564559.88      6870171.26
#Sta/Elev= 30
  4688.5 1723.93  4719.5 1723.08  4759.2  1723.2  4769.3    1723    4815 1721.27
  4859.7 1721.38  4879.8 1721.03  4899.9 1721.02    4910 1720.74  4915.5 1720.98
  4920.5 1720.66  4930.1 1720.47  4940.1 1720.98  4950.2 1720.93  4960.2 1720.59
  4981.5 1718.08  4990.4 1717.14    4999 1716.58  5002.5 1716.58  5008.9 1714.98
  5009.1 1714.48  5012.6 1714.48  5012.9 1714.98  5021.4 1716.48    5053 1717.33
  5060.1 1718.49    5074 1719.73  5097.1 1720.19  5144.5 1720.35  5163.4 1720.37
#Mann= 5 ,-1 , 0
  4688.5     .05       0  4981.5     .07       0  5008.9     .07       0
  5012.9     .07       0  5144.5    .035       0
Bank Sta=5008.9,5012.9
XS Rating Curve= 0 ,0
Exp/Cntr=0.3,0.1

Type RM Length L Ch R = 1 ,9816    ,340,340,340
BEGIN DESCRIPTION:
Mapping XS a10665ff
END DESCRIPTION:
XS GIS Cut Line= 3
      1564052.46      6870469.01      1564479.99       6870440.8
      1564650.72      6870380.29
#Sta/Elev= 30
  4553.5 1721.11  4586.1 1721.21  4606.2 1719.59  4616.2 1719.32    4648 1719.36
  4686.3 1717.64  4756.5 1716.96  4786.5 1715.89  4816.6 1716.02  4826.6 1715.41
  4836.7 1715.59  4856.7 1714.93  4866.7 1715.58  4881.5 1715.71  4896.8 1715.65
  4926.8 1714.66  4966.9 1714.05    4982  1714.1  4995.9 1713.53  4996.1 1713.03
  4999.6 1713.03  4999.9 1713.53  5009.6  1713.6  5019.1 1714.39  5050.9 1715.71
  5060.7 1716.89  5072.2 1717.62  5114.5 1717.53  5122.5  1717.2  5163.1 1716.98
#Mann= 5 ,-1 , 0
  4553.5     .05       0  4881.5     .07       0  4995.9     .07       0
  4999.9     .07       0  5114.5    .035       0
Bank Sta=4995.9,4999.9
XS Rating Curve= 0 ,0
Exp/Cntr=0.3,0.1

Type RM Length L Ch R = 1 ,9476    ,195,195,195
BEGIN DESCRIPTION:
Mapping XS 02c45e6c
END DESCRIPTION:
XS GIS Cut Line= 3
      1564065.07       6870656.3      1564395.79      6870755.25
      1564622.38       6870492.2
#Sta/Elev= 30
  4640.7 1719.09  4671.9 1719.35  4713.7 1717.52  4755.4 1717.52  4769.9 1717.04
  4776.3 1716.14    4803 1715.14  4861.5 1715.06  4888.2 1713.96  4932.9 1712.39
  4940.6 1711.27  4945.9 1711.53    4979 1710.74  4982.9 1710.02  4995.2 1709.69
  4995.5 1709.19    4999 1709.19  4999.2 1709.69  5018.7 1710.16  5025.7 1710.82
  5047.7 1711.55  5068.5 1711.71    5097 1713.63  5139.8  1714.7  5167.3 1715.04
  5210.1 1714.39  5259.4 1715.37  5267.1  1716.1  5273.7 1715.63  5333.1 1715.94
#Mann= 6 ,-1 , 0
  4640.7     .05       0  4861.5    .035       0  4888.2     .07       0
  4995.2     .07       0  4999.2     .07       0  5018.7    .035       0
Bank Sta=4995.2,4999.2
XS Rating Curve= 0 ,0
Exp/Cntr=0.3,0.1

Type RM Length L Ch R = 1 ,9281    ,223,223,223
BEGIN DESCRIPTION:
Mapping XS b01db4bb
END DESCRIPTION:
XS GIS Cut Line= 3
      1564007.81      6870940.15      1564408.81      6870940.15
      1564624.93      6870677.16
#Sta/Elev= 30
    4597 1719.07  4604.2 1718.98  4634.2 1717.13  4674.2 1717.19  4704.2 1715.43
  4734.2 1714.97  4764.2  1714.9  4784.2 1713.72  4804.2 1713.26  4824.2 1713.49
  4844.2 1712.83  4864.2 1712.74  4877.3 1712.26  4924.2 1711.76  4934.2 1711.16
  4954.2 1710.82  4964.2 1710.34  4974.2 1708.84  4982.2 1708.19  4982.4 1707.69
  4985.9 1707.69  4986.2 1708.19  5011.4 1709.24    5061 1709.68  5089.5  1710.5
  5153.5 1712.29  5273.4 1713.45  5281.2 1713.75  5316.4 1713.68  5338.4 1713.99
#Mann= 5 ,-1 , 0
    4597     .05       0  4877.3     .07       0  4982.2     .07       0
  4986.2     .07       0  5089.5    .035       0
Bank Sta=4982.2,4986.2
XS Rating Curve= 0 ,0
Exp/Cntr=0.3,0.1

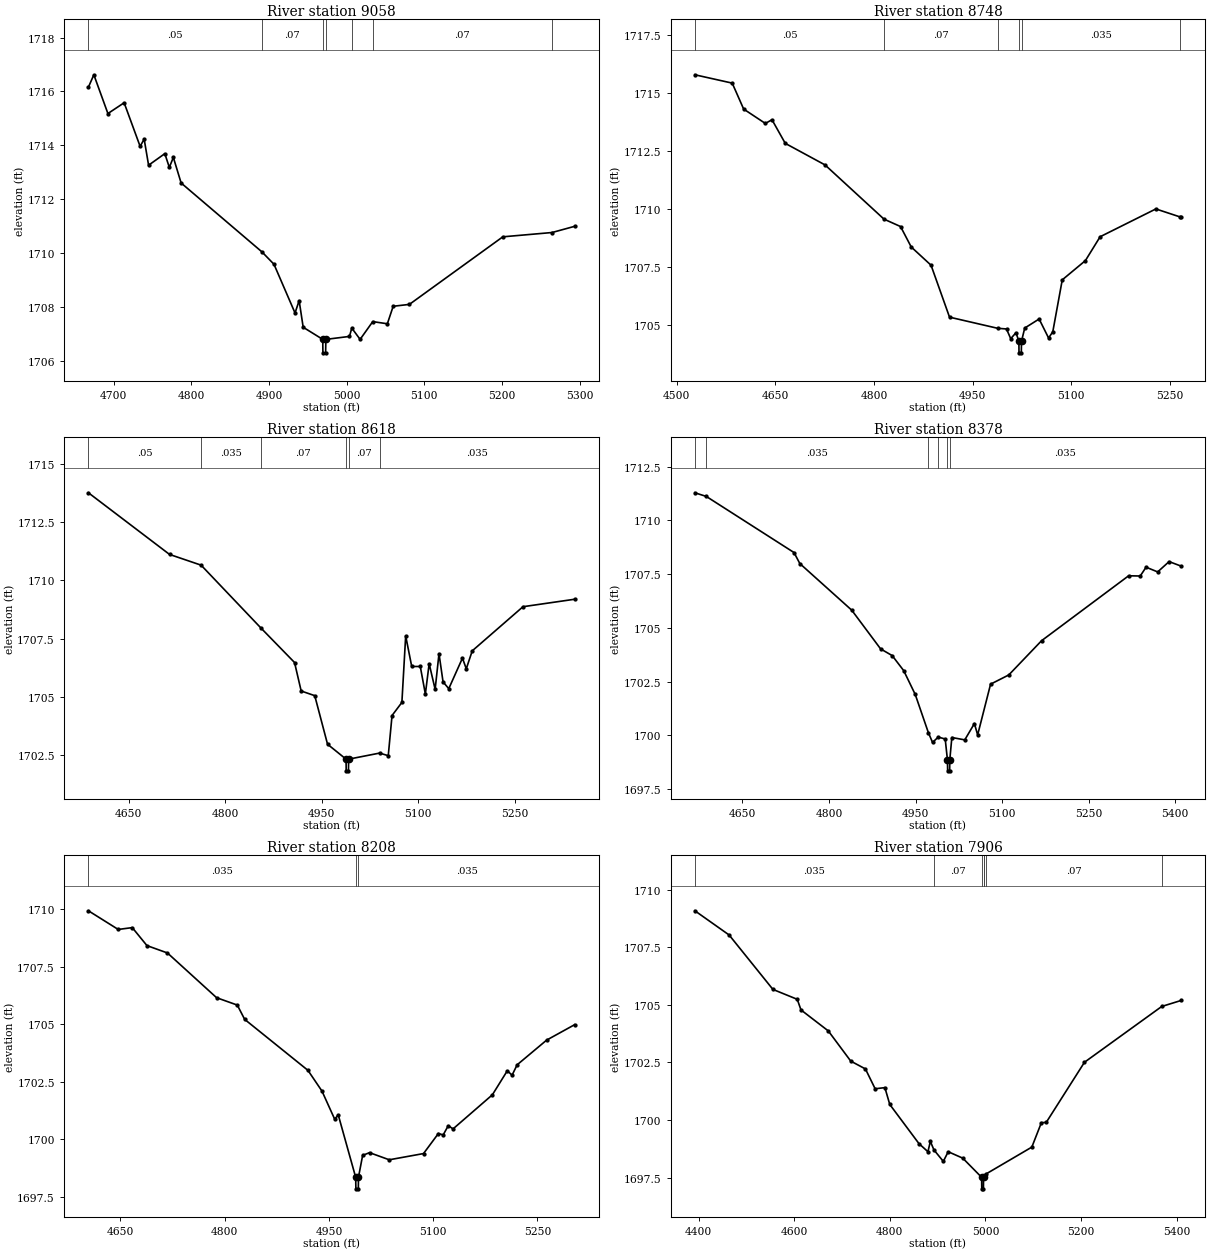
Type RM Length L Ch R = 1 ,9058    ,310,310,310
BEGIN DESCRIPTION:
Mapping XS 69920f2c
END DESCRIPTION:
XS GIS Cut Line= 3
       1564091.1      6871234.42      1564414.02      6871132.86
       1564627.6      6870940.12
#Sta/Elev= 30
  4667.5 1716.16  4674.5 1716.62  4692.6 1715.18  4713.5 1715.58  4734.1 1713.96
  4739.3 1714.23    4745 1713.26  4765.9 1713.69  4771.7 1713.18  4776.9 1713.55
  4786.9  1712.6    4891 1710.04  4906.5 1709.58  4933.6 1707.77  4938.9 1708.23
  4944.1 1707.24  4969.3 1706.79  4969.5 1706.29    4973 1706.29  4973.3 1706.79
  5003.7  1706.9  5006.7 1707.21  5017.4 1706.79  5033.7 1707.45  5052.5 1707.37
    5060 1708.02  5080.9 1708.09  5201.2  1710.6  5264.6 1710.76  5293.7 1710.99
#Mann= 7 ,-1 , 0
  4667.5     .05       0    4891     .07       0  4969.3     .07       0
  4973.3     .07       0  5006.7    .035       0  5033.7     .07       0
  5264.6    .035       0
Bank Sta=4969.3,4973.3
XS Rating Curve= 0 ,0
Exp/Cntr=0.3,0.1

Type RM Length L Ch R = 1 ,8748    ,130,130,130
BEGIN DESCRIPTION:
Mapping XS 47f9a84d
END DESCRIPTION:
XS GIS Cut Line= 3
      1564028.63      6871442.75      1564494.75      6871382.86
      1564663.58      6871172.47
#Sta/Elev= 30
  4527.4 1715.78  4584.2 1715.42  4601.6  1714.3  4634.6 1713.68  4644.7 1713.84
  4664.9 1712.82  4725.4 1711.89  4815.1 1709.55  4840.3 1709.23  4856.5 1708.35
  4886.7 1707.56  4914.8 1705.32  4987.9 1704.84  5001.5 1704.81  5007.9 1704.39
  5015.9 1704.65  5020.3 1704.28  5020.5 1703.78    5024 1703.78  5024.3 1704.28
  5029.2 1704.85  5051.1 1705.24  5065.5 1704.42  5071.9 1704.69  5086.3 1706.93
  5121.5 1707.76  5143.9 1708.79  5228.7 1709.99    5265 1709.65  5267.1 1709.63
#Mann= 6 ,-1 , 0
  4527.4     .05       0  4815.1     .07       0  4987.9    .035       0
  5020.3    .035       0  5024.3    .035       0    5265     .07       0
Bank Sta=5020.3,5024.3
XS Rating Curve= 0 ,0
Exp/Cntr=0.3,0.1

Type RM Length L Ch R = 1 ,8618    ,240,240,240
BEGIN DESCRIPTION:
Mapping XS f1d9ba60
END DESCRIPTION:
XS GIS Cut Line= 3
      1564102.41      6871599.87      1564515.58      6871506.12
      1564692.65       6871224.9
#Sta/Elev= 30
  4587.5 1713.75  4713.6 1711.11  4762.7 1710.65  4855.3 1707.97    4908 1706.48
  4918.3 1705.26  4939.4 1705.06  4959.3 1702.98  4988.1 1702.34  4988.3 1701.84
  4991.8 1701.84  4992.1 1702.34  5040.2  1702.6  5053.7 1702.49  5059.6 1704.21
  5074.9 1704.77  5080.8 1707.62  5090.2 1706.31  5103.5 1706.31  5111.4 1705.13
  5117.3 1706.43  5126.6 1705.33  5132.6 1706.86  5138.9 1705.65  5147.8 1705.36
  5169.1 1706.67    5175 1706.21  5184.3 1706.98  5263.2 1708.87  5343.5 1709.19
#Mann= 6 ,-1 , 0
  4587.5     .05       0  4762.7    .035       0  4855.3     .07       0
  4988.1     .07       0  4992.1     .07       0  5040.2    .035       0
Bank Sta=4988.1,4992.1
XS Rating Curve= 0 ,0
Exp/Cntr=0.3,0.1

Type RM Length L Ch R = 1 ,8378    ,170,170,170
BEGIN DESCRIPTION:
Mapping XS 0f46c7c7
END DESCRIPTION:
XS GIS Cut Line= 4
      1564173.18       6871718.3      1564602.87       6871718.3
      1564733.08       6871653.2      1564761.72      6871387.61
#Sta/Elev= 30
  4567.7 1711.28  4587.5 1711.11  4739.5  1708.5  4749.5 1707.99  4839.5 1705.82
  4889.5 1704.02  4909.5 1703.71  4929.5 1703.01  4949.5  1701.9  4972.3 1700.12
  4979.5 1699.67  4989.3 1699.92  5001.4 1699.83  5005.3 1698.85  5005.6 1698.35
  5009.1 1698.35  5009.3 1698.85  5012.9  1699.9  5035.3 1699.79    5052 1700.55
  5057.6 1700.02    5080 1702.38  5111.6 1702.81  5168.3  1704.4  5319.2 1707.42
  5339.3 1707.41  5349.4 1707.82  5369.5  1707.6  5389.3 1708.08  5410.1 1707.87
#Mann= 6 ,-1 , 0
  4567.7     .05       0  4587.5    .035       0  4972.3     .07       0
  4989.3    .035       0  5005.3    .035       0  5009.3    .035       0
Bank Sta=5005.3,5009.3
XS Rating Curve= 0 ,0
Exp/Cntr=0.3,0.1

Type RM Length L Ch R = 1 ,8208    ,302,302,302
BEGIN DESCRIPTION:
Mapping XS 8eaffed8
END DESCRIPTION:
XS GIS Cut Line= 3
      1564212.52      6871801.46      1564605.77      6871858.76
      1564814.11        6871640.
#Sta/Elev= 30
    4604 1709.92  4646.9 1709.11  4667.1 1709.19  4688.2 1708.41  4717.7 1708.09
  4788.4 1706.15  4818.2 1705.83  4828.8 1705.21  4919.8    1703    4940  1702.1
  4958.3 1700.88  4963.4 1701.07  4988.5 1698.36  4988.8 1697.86  4992.3 1697.86
  4992.5 1698.36  4998.5 1699.31  5008.4 1699.43  5036.8 1699.12  5086.1 1699.39
  5107.5 1700.26  5114.4  1700.2  5121.7  1700.6  5128.6 1700.46  5185.2 1701.94
  5206.6 1702.98  5213.5 1702.79  5220.8 1703.24  5263.2 1704.31  5303.5 1704.98
#Mann= 3 ,-1 , 0
    4604    .035       0  4988.5    .035       0  4992.5    .035       0
Bank Sta=4988.5,4992.5
XS Rating Curve= 0 ,0
Exp/Cntr=0.3,0.1

Type RM Length L Ch R = 1 ,7906    ,599,599,599
BEGIN DESCRIPTION:
MULBERRY CREEK TRIBUTARY 5_2 11.0
END DESCRIPTION:
XS GIS Cut Line= 3
      1564234.66      6871900.85      1564831.55      6872014.94
      1564849.25      6871606.12
#Sta/Elev= 30
  4392.3 1709.08  4463.9 1708.03  4555.5 1705.67  4606.4 1705.24  4614.2 1704.78
  4671.3 1703.87  4718.3 1702.56    4749 1702.22  4769.3 1701.36  4789.7 1701.41
  4799.9 1700.68    4861 1698.98  4879.7 1698.63  4884.8 1699.08  4892.2 1698.71
  4911.9 1698.21  4922.1 1698.63  4952.6 1698.35    4992 1697.52  4992.3 1697.02
  4995.8 1697.02    4996 1697.52  4996.9 1697.54  5001.6 1697.67    5097 1698.83
    5117 1699.89  5127.1  1699.9  5207.1 1702.51  5368.7 1704.93  5409.2 1705.19
#Mann= 7 ,-1 , 0
  4392.3    .035       0  4892.2     .07       0    4992    .035       0
    4996     .07       0  4996.9    .035       0  5001.6     .07       0
  5368.7    .035       0
Bank Sta=4992,4996
XS Rating Curve= 0 ,0
Exp/Cntr=0.3,0.1

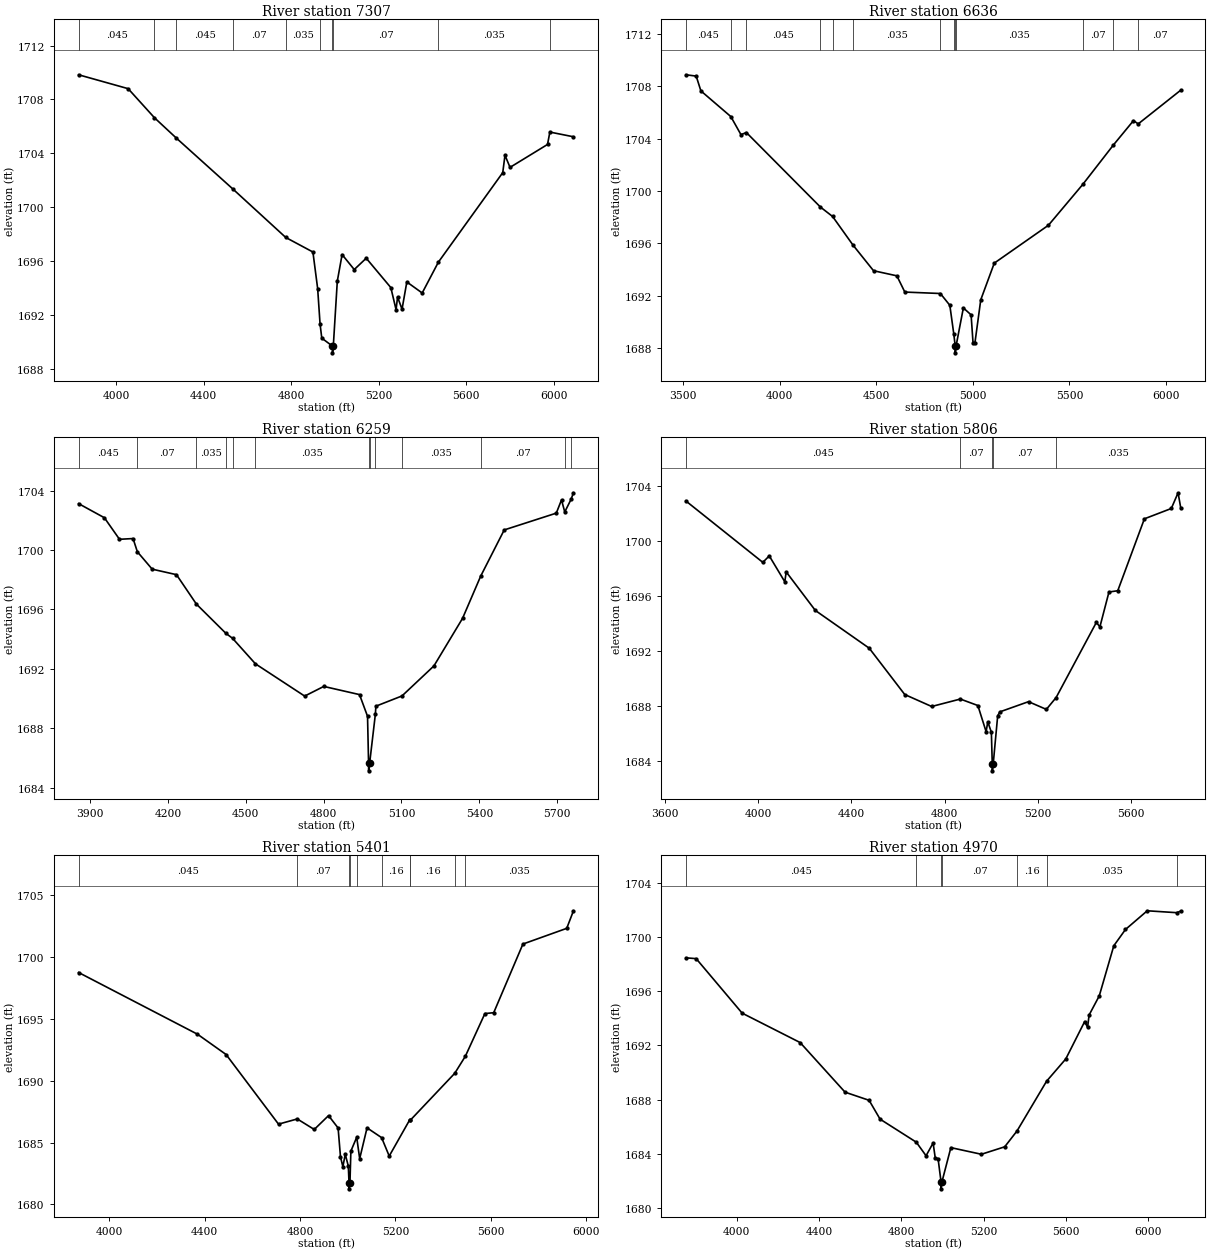
Type RM Length L Ch R = 1 ,7307    ,671,671,671
BEGIN DESCRIPTION:
Mapping XS 8f175310
END DESCRIPTION:
XS GIS Cut Line= 4
      1563989.81      6872103.54      1565062.75      6872291.05
      1565232.89      6872263.27      1566210.98      6872474.84
#Sta/Elev= 30
  3828.6 1709.83    4055  1708.8  4175.5 1706.64  4275.6 1705.13  4534.9 1701.34
  4775.6 1697.76  4899.8 1696.68  4921.5 1693.96  4932.4 1691.35  4940.3 1690.29
    4989  1689.7  4989.3  1689.2    4993  1689.7  5011.3 1694.52  5033.2 1696.49
  5088.7 1695.38  5143.5 1696.22    5256 1694.04  5279.9  1692.4  5286.7 1693.34
  5307.2 1692.44  5329.1 1694.46  5399.3 1693.64  5473.4 1695.93  5767.6 1702.57
  5777.8 1703.86  5800.9 1702.96  5972.2 1704.66    5983 1705.58  6090.9 1705.23
#Mann= 10 ,-1 , 0
  3828.6    .045       0  4175.5    .035       0  4275.6    .045       0
  4534.9     .07       0  4775.6    .035       0  4932.4     .07       0
    4989     .07       0    4993     .07       0  5473.4    .035       0
    5983     .07       0
Bank Sta=4989,4993
XS Rating Curve= 0 ,0
Exp/Cntr=0.3,0.1

Type RM Length L Ch R = 1 ,6636    ,377,377,377
BEGIN DESCRIPTION:
Mapping XS cb354e41
END DESCRIPTION:
XS GIS Cut Line= 3
      1564109.67      6872263.29      1565311.88       6872740.7
       1566579.2       6872784.1
#Sta/Elev= 30
  3514.1 1708.87  3567.9 1708.77  3592.2 1707.64  3747.1 1705.68  3799.6  1704.3
  3827.7 1704.46    4211 1698.77    4274 1698.05  4379.4 1695.87  4485.8 1693.91
  4606.6 1693.52  4647.8 1692.28  4831.8 1692.17  4880.8 1691.27  4901.2 1689.09
  4908.8 1688.14  4909.1 1687.64  4912.8 1688.14  4950.8 1691.07  4990.9 1690.54
  5000.9 1688.41  5010.9 1688.42  5040.9 1691.69  5110.9 1694.49  5391.1 1697.38
    5569  1700.5    5727  1703.5  5831.4 1705.37    5856 1705.12  6075.7 1707.69
#Mann= 13 ,-1 , 0
  3514.1    .045       0  3747.1    .035       0  3827.7    .045       0
    4211     .07       0    4274    .045       0  4379.4    .035       0
  4831.8     .07       0  4901.2    .035       0  4908.8    .035       0
  4912.8    .035       0    5569     .07       0    5727    .035       0
    5856     .07       0
Bank Sta=4908.8,4912.8
XS Rating Curve= 0 ,0
Exp/Cntr=0.3,0.1

Type RM Length L Ch R = 1 ,6259    ,453,453,453
BEGIN DESCRIPTION:
MULBERRY CREEK TRIBUTARY 5_2 7.0
END DESCRIPTION:
XS GIS Cut Line= 3
      1564422.34      6872493.16        1565405.        6873088.
      1566160.95      6873024.46
#Sta/Elev= 30
  3855.5 1703.12  3954.9 1702.17  4013.1 1700.72  4065.4 1700.77    4082 1699.88
  4139.1 1698.71  4232.7 1698.34  4309.5 1696.36  4423.3 1694.39  4448.7 1694.06
  4537.1 1692.34  4726.8 1690.17  4800.5 1690.82  4938.2 1690.27  4969.1 1688.81
  4973.1 1685.64  4973.3 1685.14  4977.1 1685.64  4999.3 1688.95  5001.3 1689.49
  5101.9 1690.18    5225  1692.2  5335.3  1695.4  5405.2 1698.24  5495.9 1701.35
  5696.6 1702.48  5716.7 1703.37  5729.2 1702.56  5753.3  1703.4  5762.8 1703.85
#Mann= 13 ,-1 , 0
  3855.5    .045       0    4082     .07       0  4309.5    .035       0
  4423.3    .045       0  4448.7     .07       0  4537.1    .035       0
  4973.1     .07       0  4977.1    .035       0  4999.3     .07       0
  5101.9    .035       0  5405.2     .07       0  5729.2    .035       0
  5753.3     .07       0
Bank Sta=4973.1,4977.1
XS Rating Curve= 0 ,0
Exp/Cntr=0.3,0.1

Type RM Length L Ch R = 1 ,5806    ,405,405,405
BEGIN DESCRIPTION:
MULBERRY CREEK TRIBUTARY 5_2 6.0
END DESCRIPTION:
XS GIS Cut Line= 3
      1564220.92      6872767.45      1565383.31      6873491.09
      1566078.52        6873198.
#Sta/Elev= 30
  3689.8 1702.91  4020.3 1698.45    4048 1698.92  4114.7 1697.04  4120.6 1697.76
  4245.7 1694.96    4477 1692.22  4629.3 1688.86  4744.9 1687.99  4867.9 1688.53
  4943.2 1688.06  4978.6 1686.16  4985.7 1686.88  5001.1 1686.12    5005 1683.82
  5005.2 1683.32    5009 1683.82  5028.2 1687.31  5037.5  1687.6  5160.5 1688.34
  5237.1 1687.78    5279 1688.64  5451.6 1694.09  5466.9 1693.77  5505.8  1696.3
  5543.5 1696.39  5657.8 1701.61  5773.3 1702.36  5802.4  1703.5  5813.5 1702.43
#Mann= 5 ,-1 , 0
  3689.8    .045       0  4867.9     .07       0    5005     .07       0
    5009     .07       0    5279    .035       0
Bank Sta=5005,5009
XS Rating Curve= 0 ,0
Exp/Cntr=0.3,0.1

Type RM Length L Ch R = 1 ,5401    ,431,431,431
BEGIN DESCRIPTION:
MULBERRY CREEK TRIBUTARY 5_2 5.0
END DESCRIPTION:
XS GIS Cut Line= 3
      1564226.07      6873710.14        1565355.        6873738.
      1566169.31      6873252.55
#Sta/Elev= 30
  3870.5 1698.75  4369.6 1693.76  4489.6 1692.12  4709.7 1686.49  4788.4 1686.91
  4859.7 1686.06  4919.7 1687.18  4959.8 1686.18  4969.8 1683.85  4979.8 1683.05
  4989.8 1684.05  5002.7  1683.1  5005.6 1681.76  5005.8 1681.26  5009.6 1681.76
  5013.4 1684.31  5037.9 1685.43  5050.4  1683.7  5081.3 1686.19  5142.4  1685.4
  5174.4 1683.91  5259.6 1686.81  5263.5 1686.82  5449.4  1690.6    5494 1691.98
    5576 1695.43    5613  1695.5  5735.6 1701.05  5919.5 1702.32  5947.8 1703.74
#Mann= 10 ,-1 , 0
  3870.5    .045       0  4788.4     .07       0  5005.6     .07       0
  5009.6     .07       0  5037.9     .07       0  5142.4     .16       0
  5259.6     .07       0  5263.5     .16       0  5449.4     .07       0
    5494    .035       0
Bank Sta=5005.6,5009.6
XS Rating Curve= 0 ,0
Exp/Cntr=0.3,0.1

Type RM Length L Ch R = 1 ,4970    ,407,407,407
BEGIN DESCRIPTION:
MULBERRY CREEK TRIBUTARY 5_2 4.0
END DESCRIPTION:
XS GIS Cut Line= 3
      1564271.56      6873863.79        1565505.        6874088.
       1566289.8       6873243.1
#Sta/Elev= 30
    3752 1698.46  3802.4  1698.4    4026 1694.38  4308.1 1692.21  4526.6 1688.55
  4643.5 1687.95  4696.9 1686.56  4873.1 1684.86  4920.5 1683.86  4954.8  1684.8
    4965 1683.72    4979 1683.64  4993.5 1681.92  4993.7 1681.42  4997.5 1681.92
  5041.1 1684.46  5189.6 1683.97    5303 1684.52  5362.9 1685.69  5506.7 1689.36
    5600    1691  5691.9 1693.76  5706.1 1693.33  5713.4 1694.24  5762.8 1695.65
  5833.6 1699.35  5890.3 1700.55  5996.3 1701.93  6139.1 1701.79  6158.8  1701.9
#Mann= 7 ,-1 , 0
    3752    .045       0  4873.1     .07       0  4993.5     .07       0
  4997.5     .07       0  5362.9     .16       0  5506.7    .035       0
  6139.1     .07       0
Bank Sta=4993.5,4997.5
XS Rating Curve= 0 ,0
Exp/Cntr=0.3,0.1

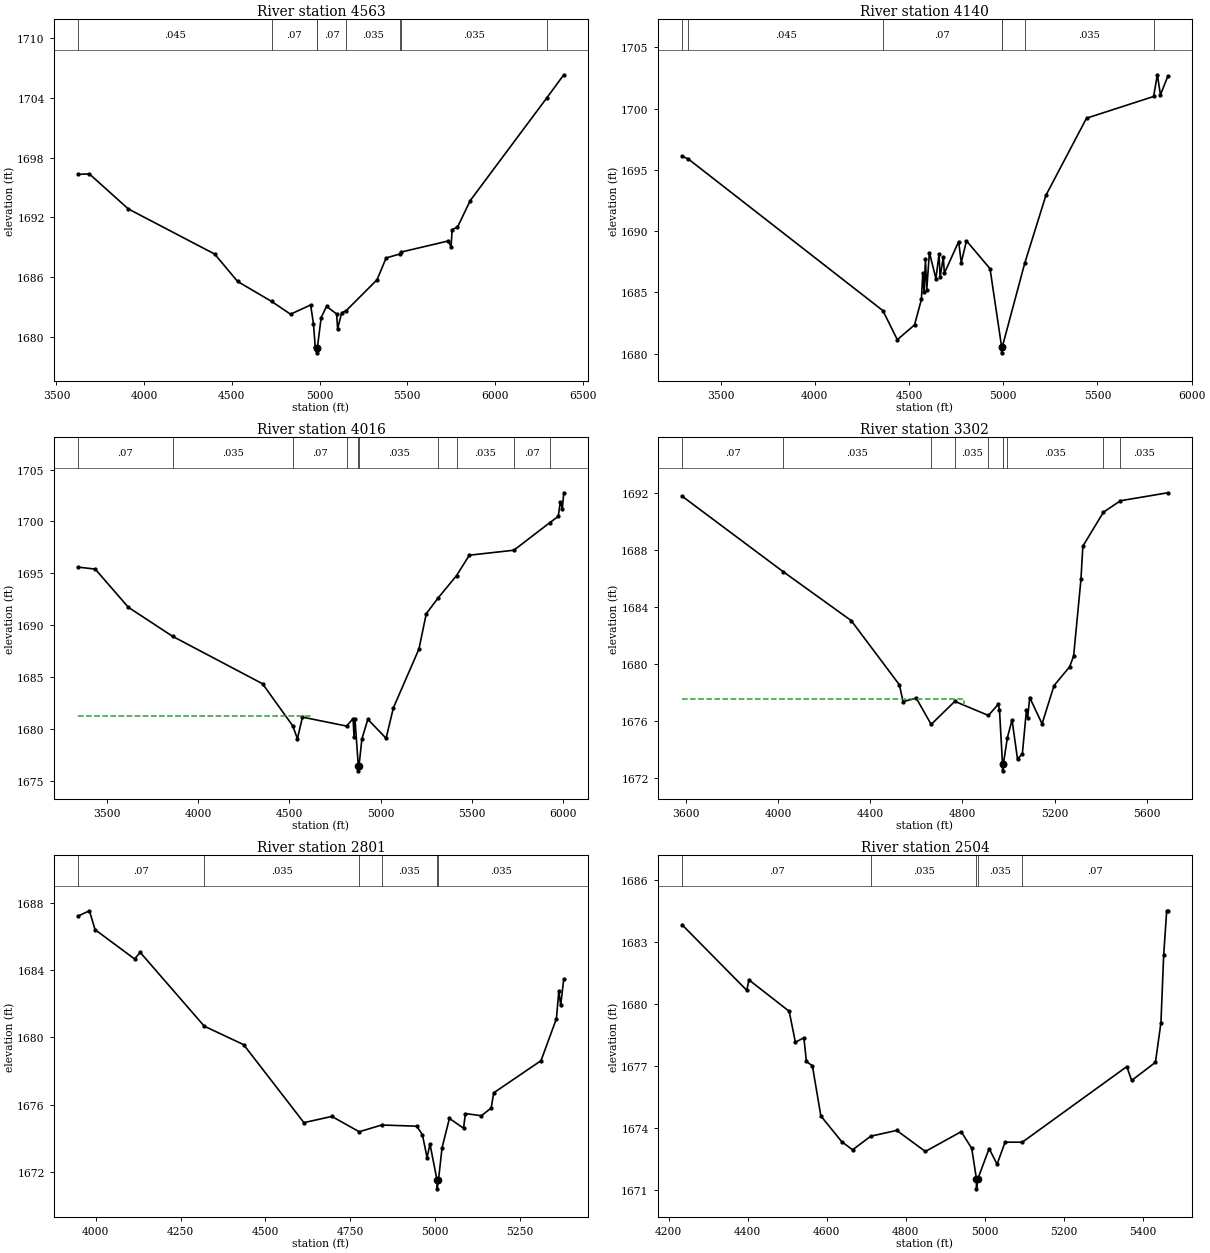
Type RM Length L Ch R = 1 ,4563    ,423,423,423
BEGIN DESCRIPTION:
MULBERRY CREEK TRIBUTARY 5_2 3.0
END DESCRIPTION:
XS GIS Cut Line= 3
      1564341.01      6874193.65        1565705.        6874338.
      1566884.38      6873590.36
#Sta/Elev= 30
    3624 1696.33  3688.3 1696.37  3909.6 1692.86  4402.3 1688.32    4533 1685.57
  4727.1 1683.56  4834.7 1682.28  4949.2 1683.21  4965.4 1681.31  4975.5 1678.97
  4983.6  1678.9  4983.8  1678.4  4987.6  1678.9  5009.2 1681.94  5039.7 1683.06
  5097.3 1682.31  5103.2 1680.81  5125.8 1682.41  5151.8 1682.64  5327.8 1685.74
  5379.4 1687.93    5460 1688.34    5467 1688.53  5734.5 1689.64  5749.7 1689.02
  5755.7 1690.78  5786.2 1691.02  5859.1  1693.7  6296.7 1704.04    6392 1706.33
#Mann= 8 ,-1 , 0
    3624    .045       0  4727.1     .07       0  4983.6     .07       0
  4987.6     .07       0  5151.8    .035       0    5460     .07       0
    5467    .035       0  6296.7     .07       0
Bank Sta=4983.6,4987.6
XS Rating Curve= 0 ,0
Exp/Cntr=0.3,0.1

Type RM Length L Ch R = 1 ,4140    ,124,124,124
BEGIN DESCRIPTION:
Mapping XS 06aaf149
END DESCRIPTION:
XS GIS Cut Line= 6
      1564391.63      6874290.52      1565641.68      6874446.78
      1565828.31      6874563.96       1565967.2      6874598.69
       1566548.8      6874403.37      1566848.26      6874247.13
#Sta/Elev= 30
  3295.6 1696.11  3328.8 1695.88  4361.3 1683.52  4437.8 1681.15  4529.2 1682.36
  4565.6 1684.43    4573 1686.57  4579.8 1685.04  4587.1 1687.71    4594 1685.23
  4608.1 1688.26  4642.5 1686.14  4659.3 1688.12  4664.9 1686.23  4681.9  1687.9
  4687.5 1686.57  4763.3 1689.15    4777 1687.44  4804.9 1689.21  4929.9 1686.94
  4991.2 1680.58  4991.5 1680.08  4995.2 1680.58  5113.7 1687.37  5226.4 1692.92
  5441.9 1699.21    5798 1700.98  5817.8 1702.75  5834.3 1701.12    5873 1702.61
#Mann= 7 ,-1 , 0
  3295.6     .07       0  3328.8    .045       0  4361.3     .07       0
  4991.2     .07       0  4995.2     .07       0  5113.7    .035       0
    5798     .07       0
#XS Ineff= 2 , 0
       0  4763.3 1689.15               0
Permanent Ineff=
       F       F
Bank Sta=4991.2,4995.2
XS Rating Curve= 0 ,0
Exp/Cntr=0.3,0.1

Type RM Length L Ch R = 1 ,4016    ,714,714,714
BEGIN DESCRIPTION:
Mapping XS e019ed11
END DESCRIPTION:
XS GIS Cut Line= 4
      1564382.96      6874403.36      1565915.12      6874681.15
      1566288.38      6874676.81      1566942.06      6874352.14
#Sta/Elev= 30
  3342.7 1695.59  3436.2  1695.4  3617.5 1691.72  3860.6 1688.91  4352.8 1684.34
    4518 1680.29    4544 1679.04  4571.6 1681.12  4813.1 1680.26  4848.9 1680.98
  4854.1 1679.23  4859.2 1680.95  4877.4 1676.44  4877.6 1675.94  4881.4 1676.44
  4897.2 1679.01  4929.7 1680.91  5029.7 1679.08  5069.7 1682.02  5209.7 1687.69
  5249.7 1691.09  5314.9 1692.62  5415.7 1694.77  5485.6 1696.74  5729.7 1697.22
  5927.4 1699.89  5972.8 1700.48  5984.1 1701.88  5995.1 1701.23    6003 1702.76
#Mann= 10 ,-1 , 0
  3342.7     .07       0  3860.6    .035       0    4518     .07       0
  4813.1    .035       0  4877.4    .035       0  4881.4    .035       0
  5314.9     .07       0  5415.7    .035       0  5729.7     .07       0
  5927.4    .035       0
#XS Ineff= 2 , 0
       0  4615.2  1681.2               0
Permanent Ineff=
       F       F
Bank Sta=4877.4,4881.4
XS Rating Curve= 0 ,0
Exp/Cntr=0.3,0.1

Type RM Length L Ch R = 1 ,3302    ,501,501,501
BEGIN DESCRIPTION:
Mapping XS bbb9e31e
END DESCRIPTION:
XS GIS Cut Line= 4
      1564582.69      6874798.35       1565945.5      6875206.32
      1566336.13      6875071.78      1566530.74      6874885.81
#Sta/Elev= 30
  3584.7 1691.78  4021.8 1686.49  4317.8 1683.04  4526.6 1678.53  4542.3 1677.35
  4599.6  1677.6  4664.2 1675.75  4766.7 1677.37  4912.4 1676.38  4954.6 1677.16
  4960.3 1676.78  4973.4 1672.99  4973.7 1672.49  4977.4 1672.99  4994.4 1674.81
  5014.8 1676.07  5038.5 1673.31  5059.6  1673.7  5077.2 1676.77  5082.5 1676.23
  5091.4 1677.64  5144.9 1675.79  5196.8 1678.48  5264.5  1679.8  5281.7 1680.56
  5313.5 1685.95  5321.6 1688.27  5411.1 1690.66  5484.6 1691.46  5689.6 1692.02
#Mann= 10 ,-1 , 0
  3584.7     .07       0  4021.8    .035       0  4664.2     .07       0
  4766.7    .035       0  4912.4     .07       0  4973.4    .035       0
  4977.4     .07       0  4994.4    .035       0  5411.1     .07       0
  5484.6    .035       0
#XS Ineff= 2 , 0
       0  4808.4 1677.53               0
Permanent Ineff=
       F       F
Bank Sta=4973.4,4977.4
XS Rating Curve= 0 ,0
Exp/Cntr=0.3,0.1

Type RM Length L Ch R = 1 ,2801    ,297,297,297
BEGIN DESCRIPTION:
MULBERRY CREEK TRIBUTARY 5_2 2.0
END DESCRIPTION:
XS GIS Cut Line= 3
      1564968.91      6875158.57        1565905.        6875638.
      1566254.99        6875488.
#Sta/Elev= 30
  3947.8  1687.2  3981.1 1687.51  3997.7 1686.39  4114.3 1684.65  4130.9 1685.04
  4319.8 1680.66  4436.1 1679.56  4613.8 1674.93  4696.2  1675.3  4776.9 1674.39
  4843.3 1674.79  4946.8 1674.72  4963.4 1674.21  4977.1 1672.85  4985.6 1673.67
  5006.6  1671.5  5006.8    1671  5010.6  1671.5  5021.3 1673.44    5043 1675.18
  5084.7  1674.6  5090.2 1675.47  5137.3 1675.34  5166.3  1675.8  5173.6  1676.7
  5313.2 1678.61  5358.6  1681.1  5365.8 1682.76  5371.2 1681.89  5380.3 1683.46
#Mann= 6 ,-1 , 0
  3947.8     .07       0  4319.8    .035       0  4776.9     .07       0
  4843.3    .035       0  5006.6    .035       0  5010.6    .035       0
Bank Sta=5006.6,5010.6
XS Rating Curve= 0 ,0
Exp/Cntr=0.3,0.1

Type RM Length L Ch R = 1 ,2504    ,842,842,842
BEGIN DESCRIPTION:
Mapping XS f6d28ea3
END DESCRIPTION:
XS GIS Cut Line= 4
      1565133.22      6875537.99      1565732.83      6875887.75
      1565962.86      6875918.13      1566254.98      6875838.01
#Sta/Elev= 30
  4233.8 1683.83  4397.3 1680.66  4403.1 1681.16  4504.8 1679.64  4520.5 1678.14
    4542 1678.36  4548.4 1677.21  4563.5    1677    4585 1674.57    4638 1673.32
  4665.3 1672.93  4711.3 1673.59  4776.9 1673.87  4849.4 1672.85  4940.2 1673.81
  4966.8    1673  4978.6 1671.54  4978.8 1671.04  4982.6 1671.54  5010.8 1672.99
    5031 1672.23  5051.2  1673.3  5094.8  1673.3  5359.2 1676.96  5371.6 1676.29
  5431.8 1677.17  5445.7 1679.09  5452.6 1682.36  5460.3 1684.51  5462.9 1684.51
#Mann= 5 ,-1 , 0
  4233.8     .07       0  4711.3    .035       0  4978.6    .035       0
  4982.6    .035       0  5094.8     .07       0
Bank Sta=4978.6,4982.6
XS Rating Curve= 0 ,0
Exp/Cntr=0.3,0.1

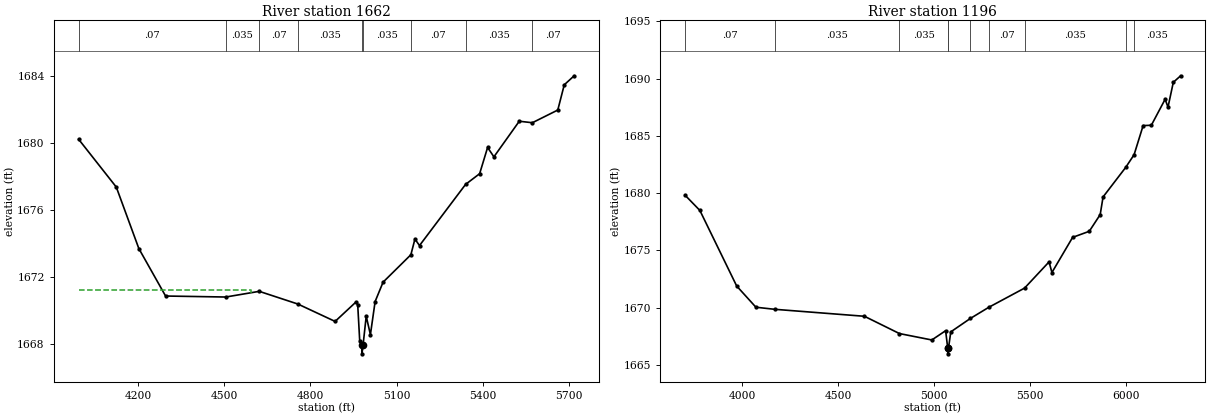
Type RM Length L Ch R = 1 ,1662    ,466,466,466
BEGIN DESCRIPTION:
Mapping XS e0aeeeb2
END DESCRIPTION:
XS GIS Cut Line= 3
      1565106.32      6876022.36      1565849.41      6876612.66
       1566535.5      6876252.29
#Sta/Elev= 30
    3994 1680.23    4125 1677.37  4203.5 1673.69  4296.5 1670.85  4505.8 1670.79
  4622.4 1671.13  4756.8 1670.37  4886.3 1669.33  4959.4  1670.5    4965 1670.31
  4971.9 1668.16  4979.4 1667.89  4979.7 1667.39  4983.4 1667.89  4994.5 1669.64
  5009.1 1668.54  5025.5 1670.52  5053.2 1671.68  5149.9 1673.32    5164 1674.26
  5179.9 1673.87  5340.2 1677.53  5389.1 1678.17  5416.8 1679.74  5438.8 1679.18
    5527 1681.31  5572.5 1681.22    5661 1681.98  5683.5 1683.49    5718 1684.03
#Mann= 9 ,-1 , 0
    3994     .07       0  4505.8    .035       0  4622.4     .07       0
  4756.8    .035       0  4979.4    .035       0  4983.4    .035       0
  5149.9     .07       0  5340.2    .035       0  5572.5     .07       0
#XS Ineff= 2 , 0
       0  4594.4 1671.22               0
Permanent Ineff=
       F       F
Bank Sta=4979.4,4983.4
XS Rating Curve= 0 ,0
Exp/Cntr=0.3,0.1

Type RM Length L Ch R = 1 ,1196    ,0,0,0
BEGIN DESCRIPTION:
MULBERRY CREEK TRIBUTARY 5_2 1.0
END DESCRIPTION:
XS GIS Cut Line= 3
      1565112.48       6876083.3      1565841.67       6877062.5
      1566966.58      6876297.44
#Sta/Elev= 30
  3702.1 1679.81  3779.1 1678.48  3970.9 1671.88    4071 1670.03  4167.9 1669.85
  4636.2 1669.24  4818.7 1667.73  4987.3 1667.17  5059.2 1667.98  5070.1 1666.46
  5070.4 1665.96  5074.1 1666.46  5086.2 1667.88  5188.1 1669.05  5284.7 1670.03
  5470.4  1671.7    5598 1673.99  5612.9 1673.06  5720.7 1676.13  5807.5 1676.66
  5864.4 1678.12  5879.3 1679.66  5997.2 1682.24    6041 1683.35    6088 1685.89
  6130.8 1685.92  6202.6 1688.19  6217.6  1687.5  6245.2 1689.67  6283.4 1690.24
#Mann= 10 ,-1 , 0
  3702.1     .07       0  4167.9    .035       0  4818.7    .035       0
  5070.1    .035       0  5074.1    .035       0  5188.1    .035       0
  5284.7     .07       0  5470.4    .035       0  5997.2     .07       0
    6041    .035       0
Bank Sta=5070.1,5074.1
XS Rating Curve= 0 ,0
Exp/Cntr=0.3,0.1

Chan Stop Cuts=-1
Use User Specified Reach Order=0
Composite Channel Slope=5