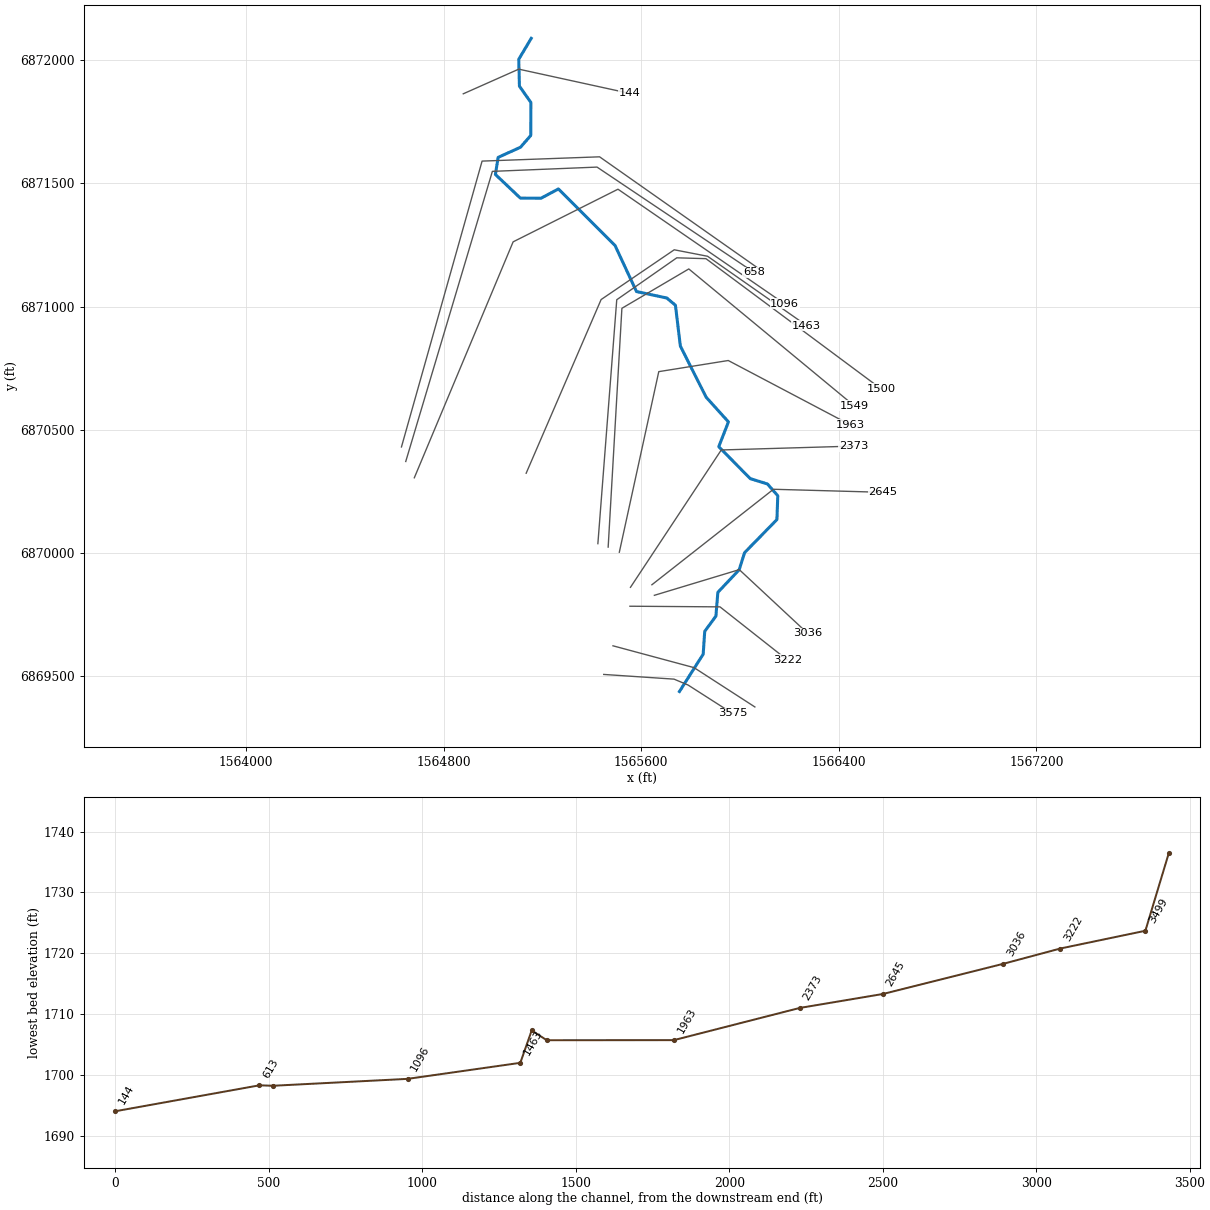
--- MULBERRY CREEK TRIBUTARY 5_2_1.prj (project) ---

Proj Title=MULBERRY CREEK TRIBUTARY 5_2_1 Base Level Engineering
Current Plan=p01
Default Exp/Contr=0.3,0.1
English Units
Geom File=g01
Flow File=f01
Plan File=p01
BEGIN DESCRIPTION:
MULBERRY CREEK TRIBUTARY 5_2_1
END DESCRIPTION:

--- MULBERRY CREEK TRIBUTARY 5_2_1.p01 (plan) ---

Plan Title=Multiple Run
Short Identifier=Multiple
Geom File=g01
Flow File=f01
Subcritical Flow
K Sum by GR= 0
Std Step Tol= 0.01
Critical Tol= 0.01
Num of Std Step Trials= 20
Max Error Tol= 0.3
Flow Tol Ratio= 0.001
Split Flow NTrial= 30
Split Flow Tol= 0.02
Split Flow Ratio= 0.02
Log Output Level= 0
Friction Slope Method= 1
Unsteady Friction Slope Method= 2
Unsteady Bridges Friction Slope Method= 1
Parabolic Critical Depth
Global Vel Dist=  1 , 1 , 1
Global Log Level= 0
CheckData=True
Encroach Param= -1, 0, 0, 0
BEGIN DESCRIPTION:
Multiple Run
END DESCRIPTION:

--- MULBERRY CREEK TRIBUTARY 5_2_1.f01 (steady flow) ---

Flow Title=Multiple
Number of Profiles=7
Profile Names=10-year,25-year,50-year,1pct_min,100-year,1pct_plu,500-year
River Rch & RM= MULBERRY CREEK T,Reach-1,3575
      93     121     143      85     169     337     238
Boundary for River Rch & Prof#=MULBERRY CREEK T,Reach-1,1
Up Type=0
Dn Type=3
Dn Slope=0.005
Boundary for River Rch & Prof#=MULBERRY CREEK T,Reach-1,2
Up Type=0
Dn Type=3
Dn Slope=0.005
Boundary for River Rch & Prof#=MULBERRY CREEK T,Reach-1,3
Up Type=0
Dn Type=3
Dn Slope=0.005
Boundary for River Rch & Prof#=MULBERRY CREEK T,Reach-1,4
Up Type=0
Dn Type=3
Dn Slope=0.005
Boundary for River Rch & Prof#=MULBERRY CREEK T,Reach-1,5
Up Type=0
Dn Type=3
Dn Slope=0.005
Boundary for River Rch & Prof#=MULBERRY CREEK T,Reach-1,6
Up Type=0
Dn Type=3
Dn Slope=0.005
Boundary for River Rch & Prof#=MULBERRY CREEK T,Reach-1,7
Up Type=0
Dn Type=3
Dn Slope=0.005

--- MULBERRY CREEK TRIBUTARY 5_2_1.g01 (geometry) ---

Geom Title=Existing Conditions

River Reach=MULBERRY CREEK T,Reach-1
Reach XY= 30
      1565755.00      6869438.00      1565851.18      6869589.58
      1565857.35      6869682.03      1565902.64      6869743.98
      1565910.54      6869840.42      1565996.82      6869931.96
      1566018.63      6870001.21      1566149.61      6870135.58
      1566153.12      6870232.29      1566111.38      6870279.98
      1566041.80      6870301.64      1565914.15      6870431.27
      1565953.33      6870531.95      1565863.16      6870631.95
      1565758.76      6870839.56      1565738.76      6871005.22
      1565703.75      6871034.49      1565581.10      6871060.72
      1565494.24      6871247.68      1565265.06      6871476.90
      1565194.52      6871439.27      1565110.88      6871439.96
      1565010.05      6871535.72      1565021.06      6871605.05
      1565111.36      6871646.03      1565153.03      6871693.68
      1565153.79      6871827.49      1565107.25      6871893.94
      1565104.55      6872003.15      1565155.00      6872088.00

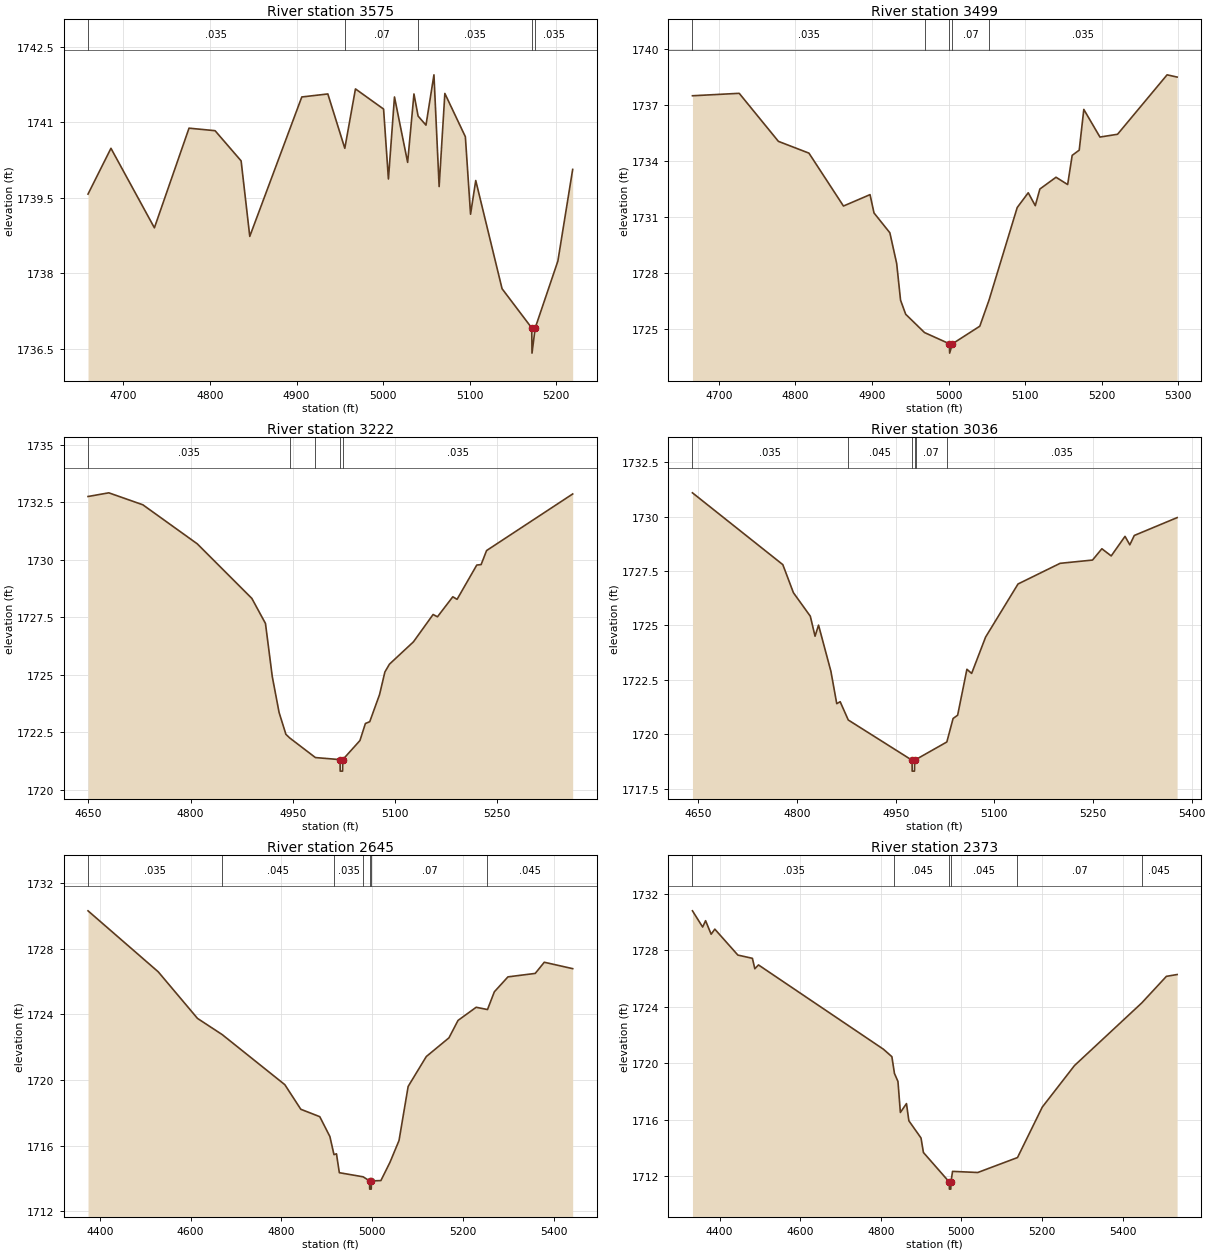
Type RM Length L Ch R = 1,3575,76,76,76
BEGIN DESCRIPTION:
MULBERRY CREEK TRIBUTARY 5_2_1 4.0
END DESCRIPTION:
XS GIS Cut Line= 4
      1565448.52      6869507.32      1565733.27      6869488.22
      1565790.33      6869464.13      1565969.37      6869349.34
#Sta/Elev= 30
  4659.1 1739.57  4685.6 1740.48  4735.8 1738.90  4775.8 1740.88  4805.9 1740.83
  4836.0 1740.23  4846.0 1738.73  4906.1 1741.50  4936.2 1741.56  4955.8 1740.48
  4968.1 1741.66  5000.6 1741.26  5006.2 1739.87  5013.2 1741.50  5028.4 1740.20
  5035.7 1741.56  5040.5 1741.12  5049.6 1740.94  5058.8 1741.94  5064.8 1739.72
  5071.4 1741.57  5095.1 1740.71  5101.1 1739.17  5107.1 1739.84  5137.5 1737.69
  5171.8 1736.91  5172.1 1736.41  5175.8 1736.91  5202.0 1738.24  5219.1 1740.06
#Mann=5,-1,0
  4659.1   0.035       0  4955.8    0.07       0  5040.5   0.035       0
  5171.8    0.07       0  5175.8   0.035       0
Bank Sta=5171.8,5175.8
Exp/Cntr=0.3,0.1

Type RM Length L Ch R = 1,3499,277,277,277
BEGIN DESCRIPTION:
Mapping XS 4c6c0bea
END DESCRIPTION:
XS GIS Cut Line= 3
      1565486.02      6869623.46      1565814.12      6869534.92
      1566060.33      6869375.41
#Sta/Elev= 30
  4665.4 1737.49  4726.5 1737.62  4777.7 1735.05  4817.6 1734.42  4862.7 1731.59
  4897.4 1732.20  4902.6 1731.22  4923.3 1730.16  4932.2 1728.52  4937.3 1726.55
  4944.0 1725.80  4968.6 1724.82  5001.1 1724.22  5001.4 1723.72  5005.1 1724.22
  5040.8 1725.16  5052.9 1726.56  5089.7 1731.51  5104.1 1732.30  5113.3 1731.61
  5119.3 1732.50  5140.4 1733.13  5155.6 1732.74  5161.5 1734.30  5170.7 1734.58
  5176.7 1736.76  5197.8 1735.28  5220.8 1735.43  5285.5 1738.61  5298.6 1738.49
#Mann=5,-1,0
  4665.4   0.035       0  4968.6    0.07       0  5001.1    0.07       0
  5005.1    0.07       0  5052.9   0.035       0
Bank Sta=5001.1,5005.1
Exp/Cntr=0.3,0.1

Type RM Length L Ch R = 1,3222,186,186,186
BEGIN DESCRIPTION:
Mapping XS cb09d7bd
END DESCRIPTION:
XS GIS Cut Line= 3
      1565554.55      6869784.06      1565919.15      6869781.45
      1566191.28      6869566.34
#Sta/Elev= 30
  4649.5 1732.75  4680.0 1732.91  4730.0 1732.39  4810.0 1730.69  4890.0 1728.32
  4910.0 1727.23  4920.0 1724.92  4930.0 1723.36  4940.0 1722.41  4945.7 1722.25
  4983.3 1721.40  5019.5 1721.31  5019.7 1720.81  5023.2 1720.81  5023.5 1721.31
  5048.7 1722.14  5056.7 1722.88  5063.1 1722.96  5077.5 1724.14  5085.3 1725.12
  5092.0 1725.46  5127.2 1726.43  5156.1 1727.62  5162.5 1727.52  5185.0 1728.39
  5191.3 1728.28  5220.2 1729.77  5226.6 1729.79  5234.6 1730.40  5361.0 1732.86
#Mann=5,-1,0
  4649.5   0.035       0  4945.7    0.07       0  4983.3   0.035       0
  5019.5   0.035       0  5023.5   0.035       0
Bank Sta=5019.5,5023.5
Exp/Cntr=0.3,0.1

Type RM Length L Ch R = 1,3036,391,391,391
BEGIN DESCRIPTION:
Mapping XS 35708ea0
END DESCRIPTION:
XS GIS Cut Line= 3
      1565653.55      6869828.33      1565997.28      6869932.49
      1566273.34      6869674.67
#Sta/Elev= 30
  4641.0 1731.09  4778.4 1727.79  4794.5 1726.50  4820.2 1725.42  4827.4 1724.50
  4832.7 1725.01  4851.5 1722.89  4860.4 1721.40  4865.6 1721.49  4877.9 1720.65
  4974.9 1718.80  4975.1 1718.30  4978.6 1718.30  4978.9 1718.80  4980.5 1718.83
  5027.8 1719.64  5037.3 1720.72  5044.2 1720.87  5058.3 1722.98  5065.5 1722.79
  5086.7 1724.46  5136.0 1726.90  5200.0 1727.85  5249.3 1728.00  5263.5 1728.52
  5277.7 1728.19  5298.7 1729.09  5306.0 1728.70  5312.8 1729.13  5377.9 1729.95
#Mann=6,-1,0
  4641.0   0.035       0  4877.9   0.045       0  4974.9    0.07       0
  4978.9   0.045       0  4980.5    0.07       0  5027.8   0.035       0
Bank Sta=4974.9,4978.9
Exp/Cntr=0.3,0.1

Type RM Length L Ch R = 1,2645,272,272,272
BEGIN DESCRIPTION:
MULBERRY CREEK TRIBUTARY 5_2_1 3.0
END DESCRIPTION:
XS GIS Cut Line= 3
      1565643.57      6869871.18      1566135.58      6870258.54
      1566577.61      6870246.19
#Sta/Elev= 30
  4373.8 1730.30  4528.5 1726.59  4615.2 1723.75  4669.4 1722.77  4807.6 1719.72
  4842.9 1718.22  4884.7 1717.77  4907.0 1716.56  4916.0 1715.46  4921.5 1715.51
  4927.8 1714.36  4980.2 1714.11  4994.5 1713.86  4994.7 1713.36  4998.2 1713.36
  4998.5 1713.86  5019.4 1713.88  5039.4 1714.99  5059.4 1716.32  5079.5 1719.61
  5119.5 1721.43  5169.5 1722.57  5189.5 1723.63  5229.5 1724.43  5254.4 1724.29
  5269.5 1725.37  5299.5 1726.28  5359.6 1726.49  5379.6 1727.17  5442.2 1726.78
#Mann=7,-1,0
  4373.8   0.035       0  4669.4   0.045       0  4916.0   0.035       0
  4980.2    0.07       0  4994.5    0.07       0  4998.5    0.07       0
  5254.4   0.045       0
Bank Sta=4994.5,4998.5
Exp/Cntr=0.3,0.1

Type RM Length L Ch R = 1,2373,410,410,410
BEGIN DESCRIPTION:
MULBERRY CREEK TRIBUTARY 5_2_1 2.0
END DESCRIPTION:
XS GIS Cut Line= 3
      1565556.77      6869860.76      1565924.30      6870417.97
      1566459.57      6870433.69
#Sta/Elev= 30
  4332.5 1730.81  4357.8 1729.66  4365.1 1730.11  4378.9 1729.15  4388.0 1729.51
  4445.2 1727.67  4481.3 1727.44  4487.3 1726.70  4496.4 1726.97  4806.5 1720.99
  4827.5 1720.46  4833.9 1719.27  4842.6 1718.70  4848.6 1716.50  4863.7 1717.13
  4869.7 1715.91  4899.8 1714.69  4905.8 1713.66  4970.1 1711.56  4970.3 1711.06
  4973.8 1711.06  4974.1 1711.56  4978.1 1712.32  5040.7 1712.24  5139.3 1713.30
  5200.8 1716.88  5280.8 1719.83  5447.6 1724.27  5508.9 1726.16  5535.5 1726.29
#Mann=6,-1,0
  4332.5   0.035       0  4833.9   0.045       0  4970.1   0.045       0
  4974.1   0.045       0  5139.3    0.07       0  5447.6   0.045       0
Bank Sta=4970.1,4974.1
Exp/Cntr=0.3,0.1

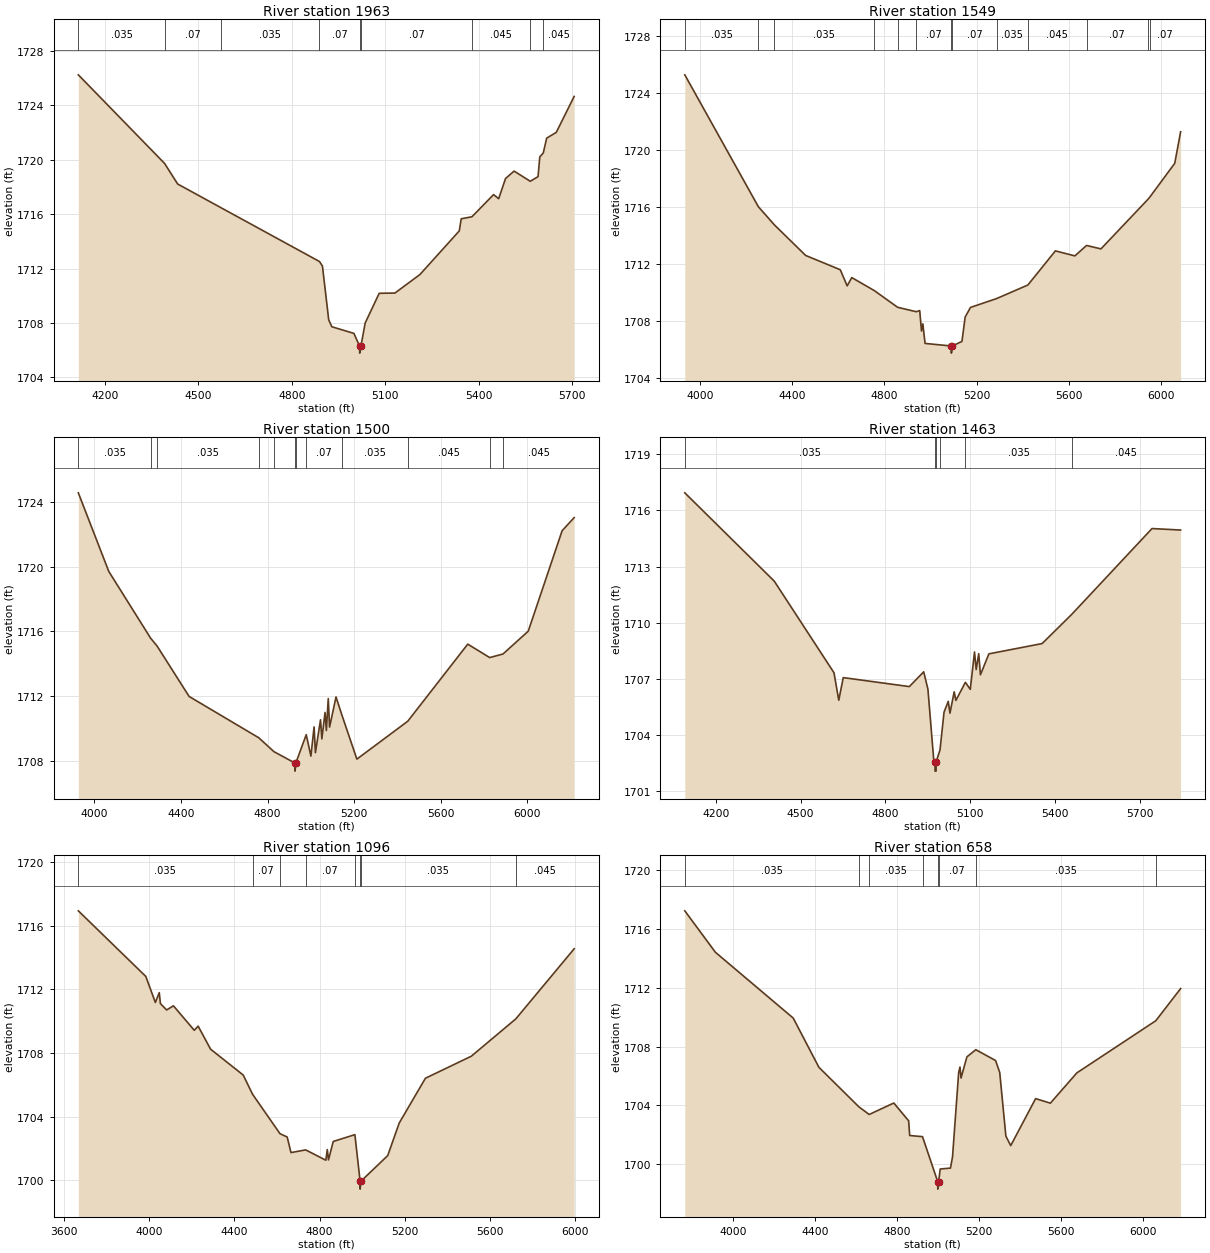
Type RM Length L Ch R = 1,1963,414,414,414
BEGIN DESCRIPTION:
Mapping XS 648ec8b5
END DESCRIPTION:
XS GIS Cut Line= 4
      1565511.65      6870003.19      1565671.36      6870735.78
      1565952.61      6870780.92      1566445.71      6870520.48
#Sta/Elev= 30
  4114.3 1726.25  4391.4 1719.73  4433.3 1718.22  4573.7 1716.46  4888.6 1712.52
  4898.2 1712.19  4918.4 1708.23  4928.5 1707.72  4999.4 1707.23  5017.7 1706.28
  5017.9 1705.78  5021.7 1706.28  5035.4 1707.99  5080.5 1710.18  5131.1 1710.20
  5211.3 1711.56  5337.7 1714.77  5343.9 1715.66  5378.4 1715.81  5447.8 1717.44
  5464.2 1717.14  5486.2 1718.62  5513.8 1719.17  5565.6 1718.42  5590.6 1718.76
  5596.2 1720.21  5607.4 1720.50  5618.3 1721.59  5649.2 1722.02  5706.6 1724.66
#Mann=9,-1,0
  4114.3   0.035       0  4391.4    0.07       0  4573.7   0.035       0
  4888.6    0.07       0  5017.7    0.07       0  5021.7    0.07       0
  5378.4   0.045       0  5565.6    0.07       0  5607.4   0.045       0
Bank Sta=5017.7,5021.7
Exp/Cntr=0.3,0.1

Type RM Length L Ch R = 1,1549,49,49,49
BEGIN DESCRIPTION:
Mapping XS 1e835cd3
END DESCRIPTION:
XS GIS Cut Line= 4
      1565466.50      6870023.95      1565522.06      6870992.72
      1565792.89      6871152.44      1566461.52      6870598.14
#Sta/Elev= 30
  3932.8 1725.26  4252.4 1716.02  4322.0 1714.75  4457.7 1712.61  4608.0 1711.61
  4638.0 1710.48  4658.0 1711.06  4755.8 1710.15  4857.0 1708.98  4937.9 1708.67
  4953.0 1708.75  4960.8 1707.32  4966.6 1707.82  4976.2 1706.45  5090.3 1706.27
  5090.6 1705.77  5094.3 1706.27  5136.4 1706.59  5150.4 1708.30  5173.5 1708.97
  5286.9 1709.59  5422.7 1710.54  5542.2 1712.93  5626.8 1712.58  5677.6 1713.31
  5740.1 1713.07  5944.1 1716.54  5951.0 1716.67  6060.5 1719.06  6086.1 1721.27
#Mann=13,-1,0
  3932.8   0.035       0  4252.4    0.07       0  4322.0   0.035       0
  4755.8    0.07       0  4857.0   0.035       0  4937.9    0.07       0
  5090.3    0.07       0  5094.3    0.07       0  5286.9   0.035       0
  5422.7   0.045       0  5677.6    0.07       0  5944.1   0.045       0
  5951.0    0.07       0
Bank Sta=5090.3,5094.3
Exp/Cntr=0.3,0.1

Type RM Length L Ch R = 1,1500,37,37,37
BEGIN DESCRIPTION:
Mapping XS 85da3ebb
END DESCRIPTION:
XS GIS Cut Line= 5
      1565424.84      6870037.86      1565501.23      6871027.44
      1565744.28      6871197.58      1565862.34      6871194.11
      1566570.30      6870666.61
#Sta/Elev= 30
  3925.5 1724.55  4066.1 1719.70  4259.3 1715.58  4289.4 1715.09  4437.2 1711.98
  4758.8 1709.43  4829.2 1708.57  4926.2 1707.87  4926.5 1707.37  4930.2 1707.87
  4978.2 1709.62  4999.7 1708.30  5014.5 1710.10  5020.6 1708.51  5044.2 1710.54
  5050.3 1709.36  5065.1 1710.99  5071.2 1709.88  5079.9 1711.85  5086.0 1710.09
  5115.7 1711.95  5143.0 1710.83  5212.1 1708.11  5447.1 1710.45  5724.3 1715.21
  5825.5 1714.38  5887.0 1714.60  6003.7 1716.01  6160.1 1722.21  6215.7 1723.02
#Mann=12,-1,0
  3925.5   0.035       0  4259.3    0.07       0  4289.4   0.035       0
  4758.8    0.07       0  4829.2   0.035       0  4926.2    0.07       0
  4930.2   0.035       0  4978.2    0.07       0  5143.0   0.035       0
  5447.1   0.045       0  5825.5    0.07       0  5887.0   0.045       0
Bank Sta=4926.2,4930.2
Exp/Cntr=0.3,0.1

Type RM Length L Ch R = 1,1463,367,367,367
BEGIN DESCRIPTION:
Mapping XS d20b1158
END DESCRIPTION:
XS GIS Cut Line= 5
      1565134.57      6870323.67      1565437.96      6871028.24
      1565733.96      6871230.14      1565868.93      6871203.84
      1566269.68      6870922.80
#Sta/Elev= 30
  4090.9 1716.94  4407.0 1712.22  4618.2 1707.32  4635.1 1705.85  4650.9 1707.06
  4884.5 1706.58  4935.3 1707.37  4950.2 1706.44  4971.2 1702.58  4975.2 1702.56
  4975.5 1702.06  4979.0 1702.06  4979.2 1702.56  4992.9 1703.19  5007.1 1705.21
  5022.0 1705.79  5028.1 1705.16  5043.0 1706.30  5049.0 1705.84  5082.6 1706.81
  5099.9 1706.43  5114.8 1708.43  5120.8 1707.49  5129.7 1708.34  5135.8 1707.21
  5165.6 1708.33  5353.8 1708.88  5458.4 1710.44  5742.2 1715.03  5843.3 1714.95
#Mann=6,-1,0
  4090.9   0.035       0  4975.2    0.07       0  4979.2   0.035       0
  4992.9    0.07       0  5082.6   0.035       0  5458.4   0.045       0
Bank Sta=4975.2,4979.2
Exp/Cntr=0.3,0.1

Type RM Length L Ch R = 1,1096,438,438,438
BEGIN DESCRIPTION:
Mapping XS 0cd6b8da
END DESCRIPTION:
XS GIS Cut Line= 4
      1564681.76      6870305.18      1565081.75      6871262.36
      1565506.23      6871475.90      1566180.92      6871010.68
#Sta/Elev= 30
  3665.5 1716.95  3982.9 1712.82  4027.8 1711.18  4046.2 1711.80  4051.6 1711.11
  4080.9 1710.71  4112.9 1710.97  4210.7 1709.43  4229.1 1709.69  4287.6 1708.24
  4441.2 1706.61  4484.7 1705.41  4614.0 1702.92  4647.9 1702.71  4665.7 1701.73
  4734.8 1701.90  4829.7 1701.25  4836.5 1701.92  4842.1 1701.27  4864.5 1702.43
  4966.3 1702.86  4990.8 1699.93  4991.0 1699.43  4994.8 1699.93  5120.7 1701.54
  5174.8 1703.59  5298.0 1706.41  5514.2 1707.80  5723.4 1710.15  5997.6 1714.56
#Mann=8,-1,0
  3665.5   0.035       0  4484.7    0.07       0  4614.0   0.035       0
  4734.8    0.07       0  4966.3   0.035       0  4990.8   0.035       0
  4994.8   0.035       0  5723.4   0.045       0
Bank Sta=4990.8,4994.8
Exp/Cntr=0.3,0.1

Type RM Length L Ch R = 1,658,45,45,45
BEGIN DESCRIPTION:
Mapping XS 6babd68f
END DESCRIPTION:
XS GIS Cut Line= 4
      1564647.06      6870371.21      1564997.75      6871548.28
      1565421.36      6871565.64      1566056.80      6871138.54
#Sta/Elev= 30
  3764.0 1717.24  3913.2 1714.42  4292.8 1709.94  4418.0 1706.59  4613.0 1703.90
  4663.2 1703.38  4783.2 1704.16  4855.5 1702.95  4860.7 1701.95  4923.2 1701.87
  4997.5 1698.80  4997.7 1698.30  5001.5 1698.80  5009.5 1699.67  5059.5 1699.73
  5069.5 1700.49  5099.5 1706.24  5106.0 1706.61  5111.0 1705.86  5139.6 1707.30
  5183.1 1707.79  5279.7 1707.05  5299.7 1706.24  5329.7 1701.91  5353.3 1701.26
  5474.7 1704.46  5546.7 1704.15  5675.7 1706.21  6060.8 1709.76  6181.8 1711.95
#Mann=8,-1,0
  3764.0   0.035       0  4613.0    0.07       0  4663.2   0.035       0
  4923.2    0.07       0  4997.5    0.07       0  5001.5    0.07       0
  5183.1   0.035       0  6060.8   0.045       0
Bank Sta=4997.5,5001.5
Exp/Cntr=0.3,0.1

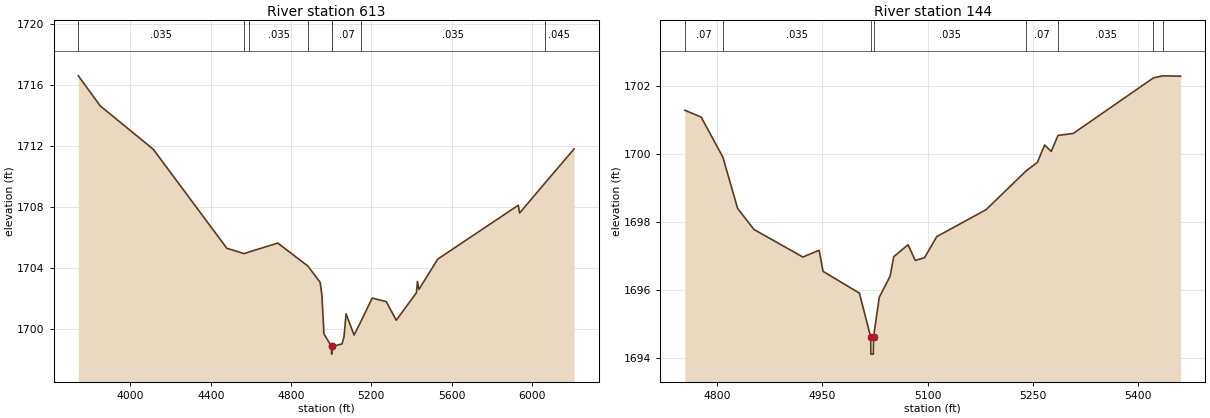
Type RM Length L Ch R = 1,613,469,469,469
BEGIN DESCRIPTION:
Mapping XS 6e88223d
END DESCRIPTION:
XS GIS Cut Line= 4
      1564629.69      6870430.19      1564956.09      6871589.94
      1565431.78      6871607.30      1566077.25      6871152.70
#Sta/Elev= 30
  3740.4 1716.59  3849.7 1714.62  4114.0 1711.78  4480.3 1705.30  4567.1 1704.95
  4591.0 1705.06  4734.2 1705.64  4883.8 1704.14  4945.2 1703.07  4954.1 1702.21
  4964.1 1699.69  5002.2 1698.87  5002.4 1698.37  5006.2 1698.87  5054.2 1699.04
  5064.2 1699.51  5074.2 1701.01  5114.2 1699.62  5147.6 1700.49  5204.3 1702.04
  5274.3 1701.81  5324.4 1700.59  5425.0 1702.39  5430.0 1703.13  5437.4 1702.61
  5531.0 1704.59  5932.5 1708.12  5938.9 1707.61  6064.0 1709.55  6210.7 1711.81
#Mann=8,-1,0
  3740.4   0.035       0  4567.1    0.07       0  4591.0   0.035       0
  4883.8    0.07       0  5002.2    0.07       0  5006.2    0.07       0
  5147.6   0.035       0  6064.0   0.045       0
Bank Sta=5002.2,5006.2
Exp/Cntr=0.3,0.1

Type RM Length L Ch R = 1,144,0,0,0
BEGIN DESCRIPTION:
MULBERRY CREEK TRIBUTARY 5_2_1 1.0
END DESCRIPTION:
XS GIS Cut Line= 3
      1564879.97      6871862.99      1565104.61      6871962.99
      1565554.25      6871864.47
#Sta/Elev= 30
  4754.1 1701.28  4777.4 1701.08  4808.4 1699.90  4829.3 1698.40  4852.6 1697.78
  4922.3 1696.97  4945.5 1697.17  4951.0 1696.55  5002.8 1695.91  5018.9 1694.62
  5019.1 1694.12  5022.6 1694.12  5022.9 1694.62  5031.1 1695.79  5046.6 1696.41
  5051.7 1696.98  5072.1 1697.33  5082.3 1696.87  5095.5 1696.95  5113.0 1697.57
  5183.2 1698.36  5240.3 1699.50  5256.3 1699.75  5266.6 1700.26  5276.0 1700.07
  5285.7 1700.54  5307.5 1700.60  5421.6 1702.23  5435.1 1702.29  5460.3 1702.28
#Mann=8,-1,0
  4754.1    0.07       0  4808.4   0.035       0  5018.9   0.035       0
  5022.9   0.035       0  5240.3    0.07       0  5285.7   0.035       0
  5421.6    0.07       0  5435.1   0.035       0
Bank Sta=5018.9,5022.9
Exp/Cntr=0.3,0.1

Chan Stop Cuts=-1