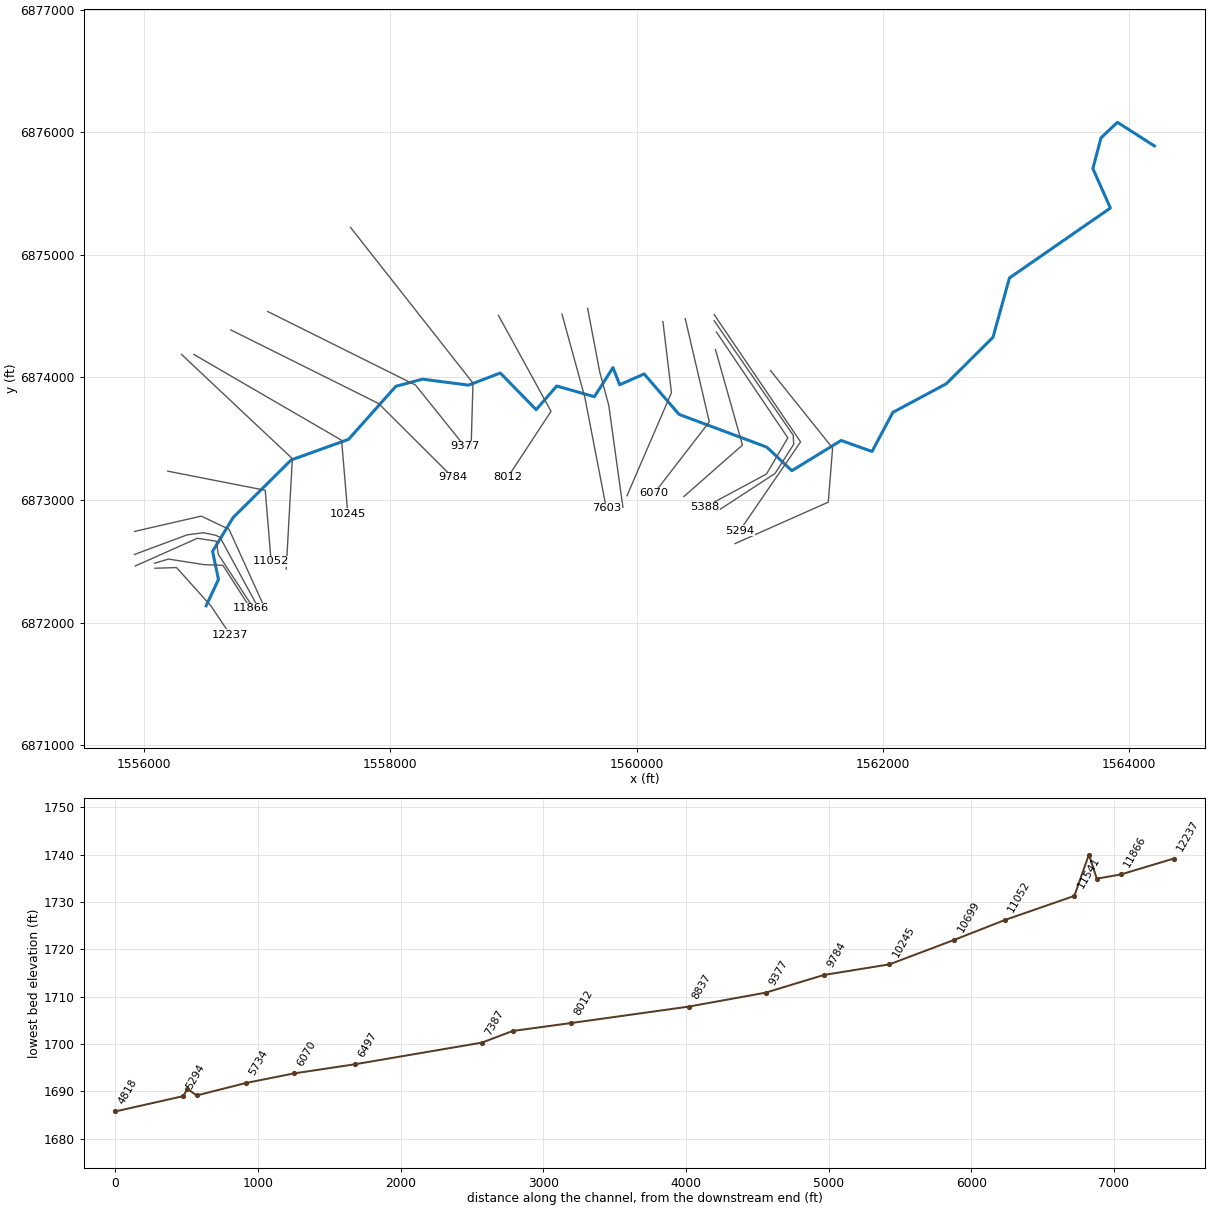
--- MULBERRY CREEK TRIBUTARY 5_3.prj (project) ---

Proj Title=MULBERRY CREEK TRIBUTARY 5_3 Base Level Engineering
Current Plan=p01
Default Exp/Contr=0.3,0.1
English Units
Geom File=g01
Flow File=f01
Plan File=p01
Y Axis Title=Elevation
X Axis Title(PF)=Main Channel Distance
X Axis Title(XS)=Station
BEGIN DESCRIPTION:
MULBERRY CREEK TRIBUTARY 5_3
END DESCRIPTION:
DSS Export Rating Curves= 0
DSS Export Rating Curve Sorted= 0
DSS Export Volume Flow Curves= 0
DXF OffsetX= 0
DXF OffsetY= 0
DXF ScaleX= 1
DXF ScaleY= 10

--- MULBERRY CREEK TRIBUTARY 5_3.p01 (plan) ---

Plan Title=Multiple Run
Short Identifier=Multiple
Geom File=g01
Flow File=f01
Subcritical Flow
K Sum by GR= 0
Std Step Tol= 0.01
Critical Tol= 0.01
Num of Std Step Trials= 20
Max Error Tol= 0.3
Flow Tol Ratio= 0.001
Split Flow NTrial= 30
Split Flow Tol= 0.02
Split Flow Ratio= 0.02
Log Output Level= 0
Friction Slope Method= 1
Unsteady Friction Slope Method= 2
Unsteady Bridges Friction Slope Method= 1
Parabolic Critical Depth
Global Vel Dist=  1 , 1 , 1
Global Log Level= 0
CheckData=True
Encroach Param= -1, 0, 0, 0
BEGIN DESCRIPTION:
Multiple Run
END DESCRIPTION:

--- MULBERRY CREEK TRIBUTARY 5_3.f01 (steady flow) ---

Flow Title=Multiple
Number of Profiles=7
Profile Names=10-year,25-year,50-year,1pct_min,100-year,1pct_plu,500-year
River Rch & RM= MULBERRY CREEK T,Reach-1,12237
     213     294     360     220     440     877     663
Boundary for River Rch & Prof#=MULBERRY CREEK T,Reach-1,1
Up Type=0
Dn Type=3
Dn Slope=0.005
Boundary for River Rch & Prof#=MULBERRY CREEK T,Reach-1,2
Up Type=0
Dn Type=3
Dn Slope=0.005
Boundary for River Rch & Prof#=MULBERRY CREEK T,Reach-1,3
Up Type=0
Dn Type=3
Dn Slope=0.005
Boundary for River Rch & Prof#=MULBERRY CREEK T,Reach-1,4
Up Type=0
Dn Type=3
Dn Slope=0.005
Boundary for River Rch & Prof#=MULBERRY CREEK T,Reach-1,5
Up Type=0
Dn Type=3
Dn Slope=0.005
Boundary for River Rch & Prof#=MULBERRY CREEK T,Reach-1,6
Up Type=0
Dn Type=3
Dn Slope=0.005
Boundary for River Rch & Prof#=MULBERRY CREEK T,Reach-1,7
Up Type=0
Dn Type=3
Dn Slope=0.005

--- MULBERRY CREEK TRIBUTARY 5_3.g01 (geometry) ---

Geom Title=Existing Conditions
Program Version=4.10

River Reach=MULBERRY CREEK T,Reach-1
Reach XY= 30
        1556505.        6872138.      1556604.91      6872353.39
      1556557.05      6872582.14      1556724.47      6872858.54
        1557195.      6873327.37      1557661.46      6873495.75
      1558045.03      6873927.87      1558261.04      6873986.36
      1558634.95      6873937.79      1558893.19       6874036.4
      1559184.66      6873737.68      1559351.66       6873930.4
       1559657.7      6873843.36      1559808.43       6874080.6
      1559863.01      6873940.84      1560061.69      6874029.05
      1560345.01      6873699.26      1561057.29      6873432.19
      1561260.89      6873239.96      1561661.05      6873486.34
      1561911.95      6873396.85      1562081.18      6873715.68
       1562514.7      6873948.74      1562894.24      6874328.32
      1563027.84      6874811.58      1563847.53      6875381.93
      1563705.01      6875703.36      1563771.63      6875954.68
      1563904.91      6876080.72        1564205.        6875888.

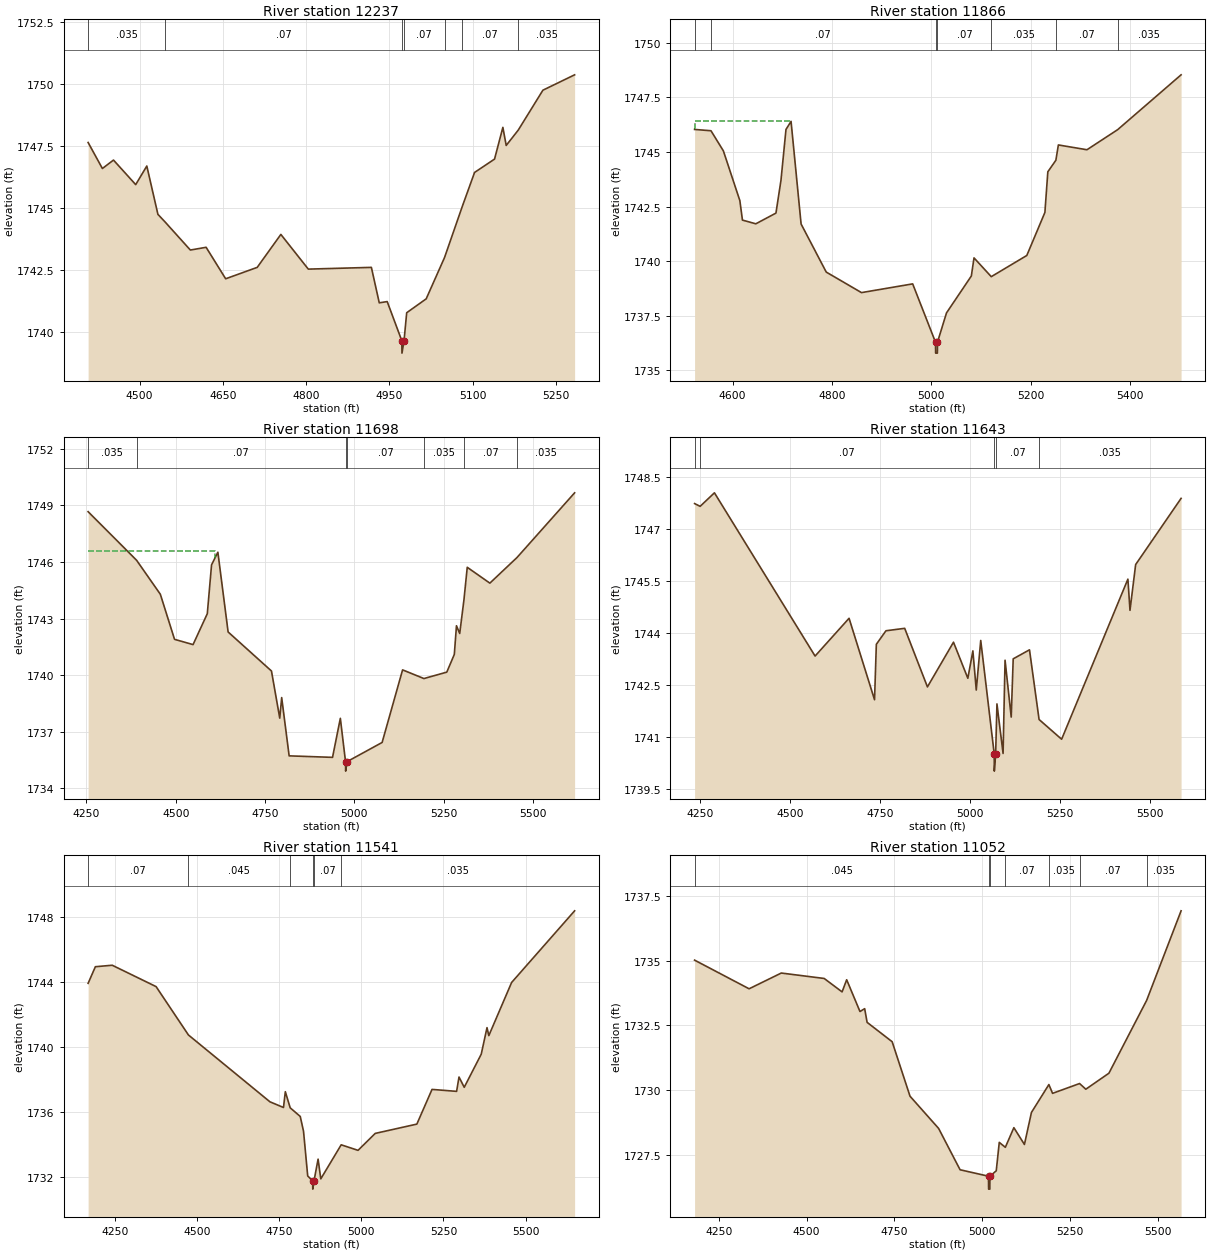
Type RM Length L Ch R = 1 ,12237   ,371,371,371
BEGIN DESCRIPTION:
MULBERRY CREEK TRIBUTARY 5_3 11.0
END DESCRIPTION:
XS GIS Cut Line= 4
      1556089.31      6872444.69      1556264.44      6872450.07
      1556542.56      6872138.84      1556700.18      6871903.19
#Sta/Elev= 30
  4407.4 1747.65  4433.1  1746.6  4453.1 1746.94  4493.1 1745.95  4513.1  1746.7
  4533.1 1744.75  4546.1 1744.44  4591.5 1743.31  4619.9 1743.42  4655.1 1742.15
  4711.9 1742.61  4754.5 1743.94  4803.9 1742.54  4917.5 1742.61  4931.7 1741.18
    4946 1741.23  4972.3 1739.65  4972.6 1739.15  4976.3 1739.65  4981.1 1740.78
  5016.2 1741.34  5049.3 1743.01  5080.9 1745.05  5103.3 1746.44  5139.3 1746.98
  5154.3 1748.26  5160.3 1747.53    5182 1748.15  5226.4 1749.76  5283.5 1750.38
#Mann= 7 ,-1 , 0
  4407.4    .035       0  4546.1     .07       0  4972.3     .07       0
  4976.3     .07       0  5049.3    .035       0  5080.9     .07       0
    5182    .035       0
Bank Sta=4972.3,4976.3
XS Rating Curve= 0 ,0
Exp/Cntr=0.3,0.1

Type RM Length L Ch R = 1 ,11866   ,168,168,168
BEGIN DESCRIPTION:
Mapping XS 7cf85df1
END DESCRIPTION:
XS GIS Cut Line= 5
      1556086.79      6872485.74      1556199.45      6872519.39
      1556488.13      6872473.89       1556640.9      6872468.68
      1556864.86      6872117.98
#Sta/Elev= 30
  4523.7 1746.03  4556.7 1745.97  4581.6 1745.05  4614.8 1742.77    4620 1741.88
  4646.9 1741.71  4687.4  1742.2  4697.5  1743.7  4707.6 1746.03  4717.8  1746.4
    4738  1741.7  4788.6  1739.5  4859.5 1738.56  4962.5 1738.96  5008.4 1736.29
  5008.7 1735.79  5012.2 1735.79  5012.4 1736.29  5030.5 1737.63  5080.5 1739.32
  5085.9 1740.15  5120.6 1739.29  5192.1 1740.26  5228.5 1742.23  5234.4 1744.09
  5250.6 1744.62  5255.6 1745.32  5313.1  1745.1  5374.9 1746.02  5502.5 1748.53
#Mann= 7 ,-1 , 0
  4523.7    .035       0  4556.7     .07       0  5008.4     .07       0
  5012.4     .07       0  5120.6    .035       0  5250.6     .07       0
  5374.9    .035       0
#XS Ineff= 2 , 0
       0  4717.8  1746.4               0
Permanent Ineff=
       F       F
Bank Sta=5008.4,5012.4
XS Rating Curve= 0 ,0
Exp/Cntr=0.3,0.1

Type RM Length L Ch R = 1 ,11698   ,55,55,55
BEGIN DESCRIPTION:
Mapping XS 9c99b623
END DESCRIPTION:
XS GIS Cut Line= 5
      1555930.42      6872463.42      1556433.86       6872689.1
      1556586.63       6872664.8      1556603.99      6872557.16
      1556902.63      6872098.79
#Sta/Elev= 30
  4254.7 1748.67  4390.6 1746.09    4457 1744.29  4496.7  1741.9  4548.6 1741.62
  4588.5 1743.26  4600.4 1745.85  4618.1 1746.52  4646.8 1742.29  4768.2 1740.22
  4791.4 1737.72  4796.8 1738.81  4817.7 1735.72  4939.2 1735.64  4961.1 1737.71
  4975.6 1735.41  4975.9 1734.91  4979.6 1735.41  5078.1 1736.43  5135.4 1740.28
  5195.2 1739.82  5259.2 1740.16  5280.3  1741.1  5286.3 1742.62  5295.4 1742.21
  5307.4 1744.02  5316.5 1745.72  5379.8 1744.88  5455.9 1746.24  5617.2 1749.67
#Mann= 7 ,-1 , 0
  4254.7    .035       0  4390.6     .07       0  4975.6     .07       0
  4979.6     .07       0  5195.2    .035       0  5307.4     .07       0
  5455.9    .035       0
#XS Ineff= 2 , 0
       0  4610.4 1746.57               0
Permanent Ineff=
       F       F
Bank Sta=4975.6,4979.6
XS Rating Curve= 0 ,0
Exp/Cntr=0.3,0.1

Type RM Length L Ch R = 1 ,11643   ,102,102,102
BEGIN DESCRIPTION:
Mapping XS aa5c52e8
END DESCRIPTION:
XS GIS Cut Line= 6
      1555923.42      6872557.15      1556350.52      6872716.88
      1556482.47      6872734.24      1556583.16      6872713.41
      1556617.88      6872696.05      1556912.42      6872151.94
#Sta/Elev= 30
    4235 1747.73  4250.4 1747.65  4290.1 1748.04  4569.4 1743.33  4663.7 1744.42
  4734.4 1742.07  4739.4 1743.67  4766.1 1744.06  4818.1 1744.13  4881.2 1742.44
  4953.5 1743.73  4993.3 1742.69  5007.3 1743.48  5016.7 1742.35  5029.1 1743.78
  5066.5 1740.51  5066.8 1740.01  5070.5 1740.51  5074.1 1741.95  5091.1 1740.52
  5096.6 1743.21  5113.7 1741.57  5119.2 1743.25  5164.4 1743.51    5191  1741.5
  5253.6 1740.93  5437.5 1745.55  5443.3 1744.65    5459 1745.97  5585.1 1747.88
#Mann= 5 ,-1 , 0
    4235    .035       0  4250.4     .07       0  5066.5     .07       0
  5070.5     .07       0    5191    .035       0
Bank Sta=5066.5,5070.5
XS Rating Curve= 0 ,0
Exp/Cntr=0.3,0.1

Type RM Length L Ch R = 1 ,11541   ,489,489,489
BEGIN DESCRIPTION:
Mapping XS 005915b8
END DESCRIPTION:
XS GIS Cut Line= 4
      1555923.47      6872744.66      1556465.11      6872869.66
       1556690.8      6872762.02       1556968.6       6872147.4
#Sta/Elev= 30
  4168.9  1743.9    4191 1744.92  4242.3 1745.01  4375.7  1743.7  4474.2 1740.73
  4722.1 1736.63  4763.4 1736.28    4769 1737.25  4783.8 1736.26  4814.4 1735.73
  4824.4 1734.82  4837.1 1732.08  4852.2 1731.77  4852.5 1731.27  4856.2 1731.77
  4868.7 1733.11  4876.9  1731.9    4939 1733.99  4990.2 1733.65  5042.6 1734.69
  5169.2 1735.26  5215.4 1737.39  5290.2 1737.27  5297.5 1738.15  5313.4 1737.52
  5365.1 1739.55  5382.7 1741.18  5388.2 1740.69  5457.5 1743.95  5649.3 1748.35
#Mann= 6 ,-1 , 0
  4168.9     .07       0  4474.2    .045       0  4783.8     .07       0
  4852.2    .035       0  4856.2     .07       0    4939    .035       0
Bank Sta=4852.2,4856.2
XS Rating Curve= 0 ,0
Exp/Cntr=0.3,0.1

Type RM Length L Ch R = 1 ,11052   ,353,353,353
BEGIN DESCRIPTION:
Mapping XS b661f5b5
END DESCRIPTION:
XS GIS Cut Line= 3
      1556192.56      6873236.47      1556984.68      6873080.22
      1557032.42      6872502.97
#Sta/Elev= 30
  4180.5 1735.03  4335.9 1733.92  4427.6 1734.53  4549.9 1734.32  4600.9  1733.8
    4614 1734.27  4651.9 1733.04  4665.3 1733.15  4672.2 1732.62  4743.6 1731.87
  4794.5 1729.76  4876.1 1728.51  4937.2 1726.91  5018.2 1726.66  5018.5 1726.16
    5022 1726.16  5022.2 1726.66  5040.3 1726.87  5048.9 1727.97  5066.2 1727.78
  5090.5 1728.54  5120.6 1727.89  5140.6 1729.13  5190.3 1730.21  5200.8 1729.87
  5277.8 1730.25  5295.6 1730.03  5361.4 1730.65  5468.9 1733.47  5567.1 1736.94
#Mann= 7 ,-1 , 0
  4180.5    .045       0  5018.2    .045       0  5022.2    .045       0
  5066.2     .07       0  5190.3    .035       0  5277.8     .07       0
  5468.9    .035       0
Bank Sta=5018.2,5022.2
XS Rating Curve= 0 ,0
Exp/Cntr=0.3,0.1

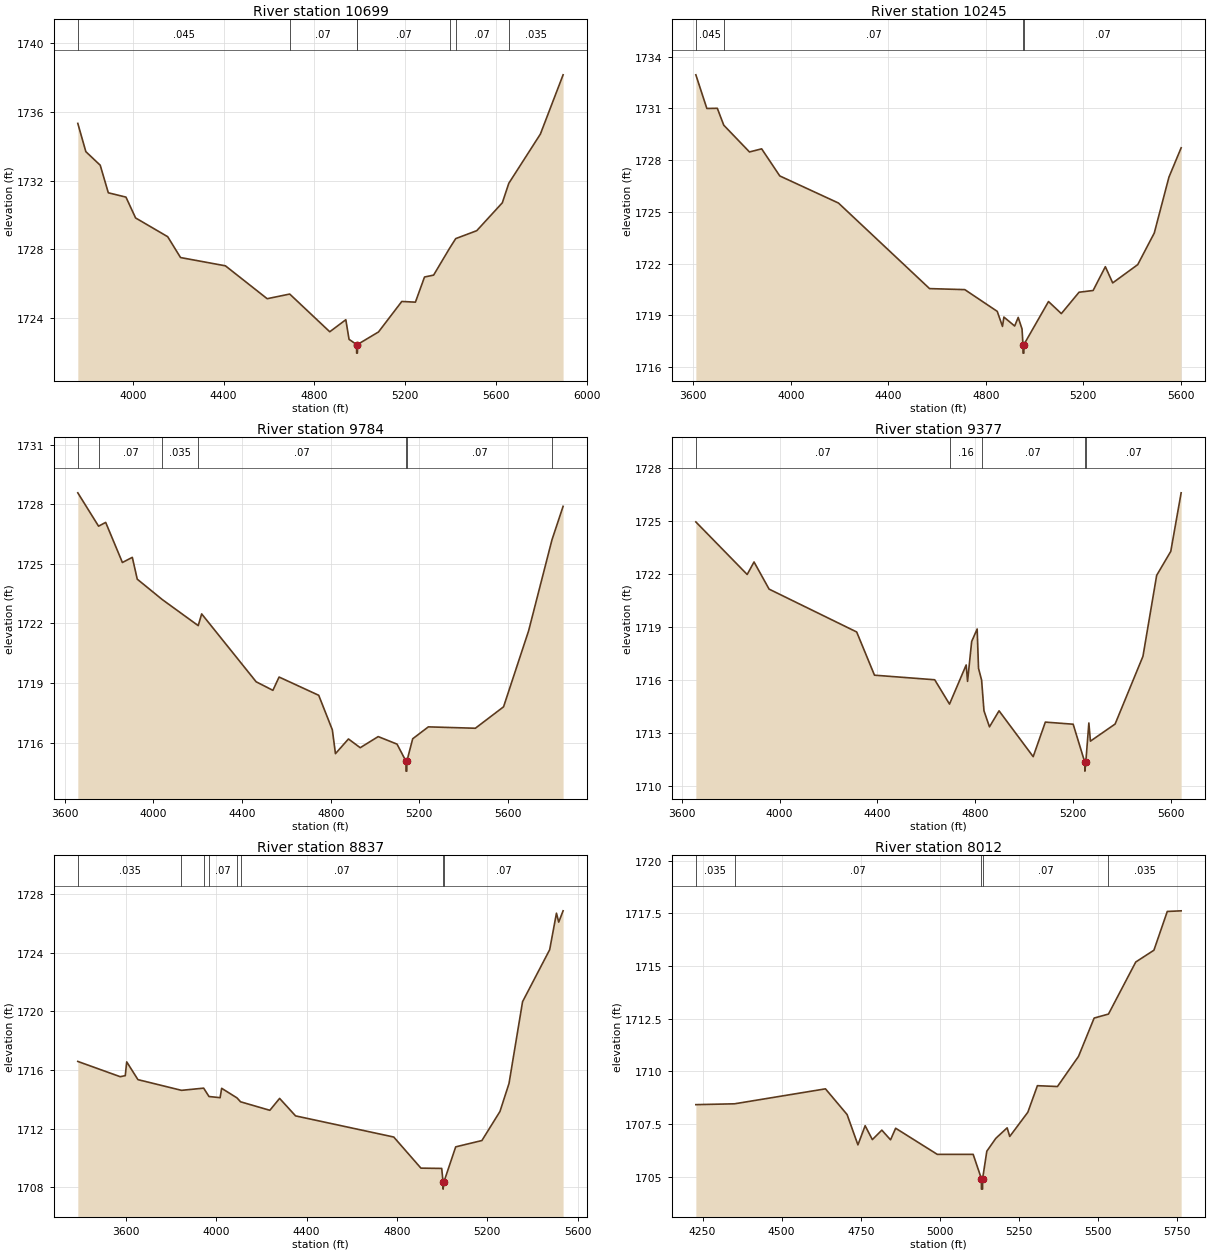
Type RM Length L Ch R = 1 ,10699   ,454,454,454
BEGIN DESCRIPTION:
MULBERRY CREEK TRIBUTARY 5_3 8.0
END DESCRIPTION:
XS GIS Cut Line= 3
        1556305.        6874188.        1557205.        6873338.
        1557155.      6872438.03
#Sta/Elev= 30
  3757.4 1735.32  3792.8 1733.68  3856.3 1732.89  3891.9 1731.29  3969.6 1731.04
  4012.1 1729.83  4153.7 1728.74  4210.3 1727.53  4408.1 1727.05  4592.2 1725.14
  4691.6 1725.41  4868.1 1723.22  4938.9 1723.92  4953.1 1722.78  4986.3 1722.48
  4986.5 1721.98    4990 1721.98  4990.3 1722.48    5083 1723.21  5185.6 1724.98
  5245.7 1724.94  5285.8  1726.4  5325.9 1726.51  5396.8 1728.08  5423.4 1728.63
  5516.1 1729.09  5628.8 1730.71  5657.3 1731.84  5796.6  1734.7  5896.7 1738.14
#Mann= 7 ,-1 , 0
  3757.4    .045       0  4691.6     .07       0  4986.3     .07       0
  4990.3     .07       0  5396.8    .035       0  5423.4     .07       0
  5657.3    .035       0
Bank Sta=4986.3,4990.3
XS Rating Curve= 0 ,0
Exp/Cntr=0.3,0.1

Type RM Length L Ch R = 1 ,10245   ,461,461,461
BEGIN DESCRIPTION:
MULBERRY CREEK TRIBUTARY 5_3 7.0
END DESCRIPTION:
XS GIS Cut Line= 3
      1556404.98      6874188.01        1557605.        6873488.
        1557655.      6872888.05
#Sta/Elev= 30
  3610.7 1732.94  3655.8 1730.99  3698.8    1731  3725.3 1730.02  3830.7 1728.47
  3880.7 1728.65  3955.1 1727.08  4195.8 1725.51  4569.6 1720.55  4714.3 1720.49
  4847.4 1719.23  4868.9 1718.36  4874.7  1718.9  4918.9 1718.38  4933.4 1718.88
  4949.1 1718.21  4952.9 1717.31  4953.2 1716.81  4956.7 1716.81  4956.9 1717.31
  5057.7  1719.8  5110.4  1719.1  5183.1 1720.34  5240.8 1720.44    5291 1721.82
  5321.1 1720.88  5423.9 1721.94  5491.7 1723.77  5551.9 1727.01    5602 1728.71
#Mann= 4 ,-1 , 0
  3610.7    .045       0  3725.3     .07       0  4952.9     .07       0
  4956.9     .07       0
Bank Sta=4952.9,4956.9
XS Rating Curve= 0 ,0
Exp/Cntr=0.3,0.1

Type RM Length L Ch R = 1 ,9784    ,407,407,407
BEGIN DESCRIPTION:
MULBERRY CREEK TRIBUTARY 5_3 6.0
END DESCRIPTION:
XS GIS Cut Line= 3
      1556704.99      6874388.01        1557905.        6873788.
      1558505.01      6873187.99
#Sta/Elev= 30
  3658.5 1728.58  3752.2  1726.9  3784.3 1727.09  3859.8 1725.07  3904.5 1725.33
  3926.8 1724.23  4040.1  1723.2  4201.9 1721.89  4217.5 1722.48  4463.5 1719.06
    4539 1718.63  4566.9  1719.3  4745.8 1718.38  4807.3 1716.64  4821.3 1715.44
    4880 1716.18  4933.1 1715.74  5014.3  1716.3  5099.2 1715.92  5139.6 1715.06
  5139.8 1714.56  5143.3 1714.56  5143.6 1715.06  5169.9 1716.19  5240.6 1716.79
  5452.7 1716.72    5580  1717.8  5693.1 1721.63  5798.4 1726.21  5848.7  1727.9
#Mann= 7 ,-1 , 0
  3658.5    .045       0  3752.2     .07       0  4040.1    .035       0
  4201.9     .07       0  5139.6     .07       0  5143.6     .07       0
  5798.4    .035       0
Bank Sta=5139.6,5143.6
XS Rating Curve= 0 ,0
Exp/Cntr=0.3,0.1

Type RM Length L Ch R = 1 ,9377    ,540,540,540
BEGIN DESCRIPTION:
MULBERRY CREEK TRIBUTARY 5_3 5.0
END DESCRIPTION:
XS GIS Cut Line= 3
      1557005.02      6874537.99        1558205.        6873938.
      1558604.98      6873438.03
#Sta/Elev= 30
  3658.3 1724.96  3867.9 1721.98  3895.9 1722.69  3957.4 1721.15  4315.1 1718.72
  4387.8 1716.27  4633.8 1716.01  4694.2 1714.63  4762.3 1716.85  4767.9 1715.92
  4784.7 1718.18  4807.1 1718.89  4812.7 1716.66  4825.3 1715.99    4835 1714.25
  4857.4 1713.34  4896.5 1714.25  5035.9 1711.65  5085.6 1713.61  5199.2 1713.49
  5246.8 1711.33  5247.1 1710.83  5250.8 1711.33  5263.3 1713.56  5269.7 1712.53
  5370.5  1713.5  5484.2 1717.34  5540.2 1721.93  5597.8 1723.29  5640.2 1726.61
#Mann= 5 ,-1 , 0
  3658.3     .07       0  4694.2     .16       0  4825.3     .07       0
  5246.8     .07       0  5250.8     .07       0
Bank Sta=5246.8,5250.8
XS Rating Curve= 0 ,0
Exp/Cntr=0.3,0.1

Type RM Length L Ch R = 1 ,8837    ,825,825,825
BEGIN DESCRIPTION:
MULBERRY CREEK TRIBUTARY 5_3 4.0
END DESCRIPTION:
XS GIS Cut Line= 3
      1557676.94      6875224.14      1558671.74      6873954.44
      1558656.08      6873418.57
#Sta/Elev= 30
    3387 1716.58  3574.7 1715.54  3597.2 1715.61  3603.6 1716.55  3653.3 1715.34
  3846.2 1714.61  3944.3 1714.76    3968 1714.19  4017.3 1714.11    4024 1714.75
  4092.4 1714.09  4107.7 1713.83  4237.4 1713.25  4280.7 1714.06  4351.3 1712.87
  4786.1 1711.43  4906.5 1709.31  4998.6 1709.29  5004.4 1708.38  5004.7 1707.88
  5008.4 1708.38  5060.5 1710.76  5176.5 1711.19  5256.5 1713.17  5296.6 1715.08
  5356.6 1720.65  5476.6 1724.19  5506.7 1726.68  5516.7 1726.07  5536.1 1726.84
#Mann= 8 ,-1 , 0
    3387    .035       0  3846.2     .07       0  3944.3    .035       0
    3968     .07       0  4092.4    .035       0  4107.7     .07       0
  5004.4     .07       0  5008.4     .07       0
Bank Sta=5004.4,5008.4
XS Rating Curve= 0 ,0
Exp/Cntr=0.3,0.1

Type RM Length L Ch R = 1 ,8012    ,409,409,409
BEGIN DESCRIPTION:
MULBERRY CREEK TRIBUTARY 5_3 3.0
END DESCRIPTION:
XS GIS Cut Line= 3
      1558877.87      6874507.34      1559305.38      6873724.17
      1558954.98      6873187.97
#Sta/Elev= 30
    4229 1708.42  4351.3 1708.46  4638.4 1709.17  4706.7 1707.95  4740.9 1706.51
  4763.7 1707.42  4786.5 1706.76  4816.4 1707.21  4843.9 1706.75  4860.1  1707.3
  4991.6 1706.06  5104.9 1706.06  5130.8 1704.91  5131.1 1704.41  5134.6 1704.41
  5134.8 1704.91    5148 1706.21  5176.4 1706.82  5212.2 1707.32  5220.4 1706.91
  5277.6 1708.06  5307.8 1709.32  5371.1 1709.28  5437.6 1710.71    5487 1712.53
  5532.3 1712.72  5618.4 1715.19  5675.8 1715.75    5718 1717.59  5761.8 1717.62
#Mann= 5 ,-1 , 0
    4229    .035       0  4351.3     .07       0  5130.8     .07       0
  5134.8     .07       0  5532.3    .035       0
Bank Sta=5130.8,5134.8
XS Rating Curve= 0 ,0
Exp/Cntr=0.3,0.1

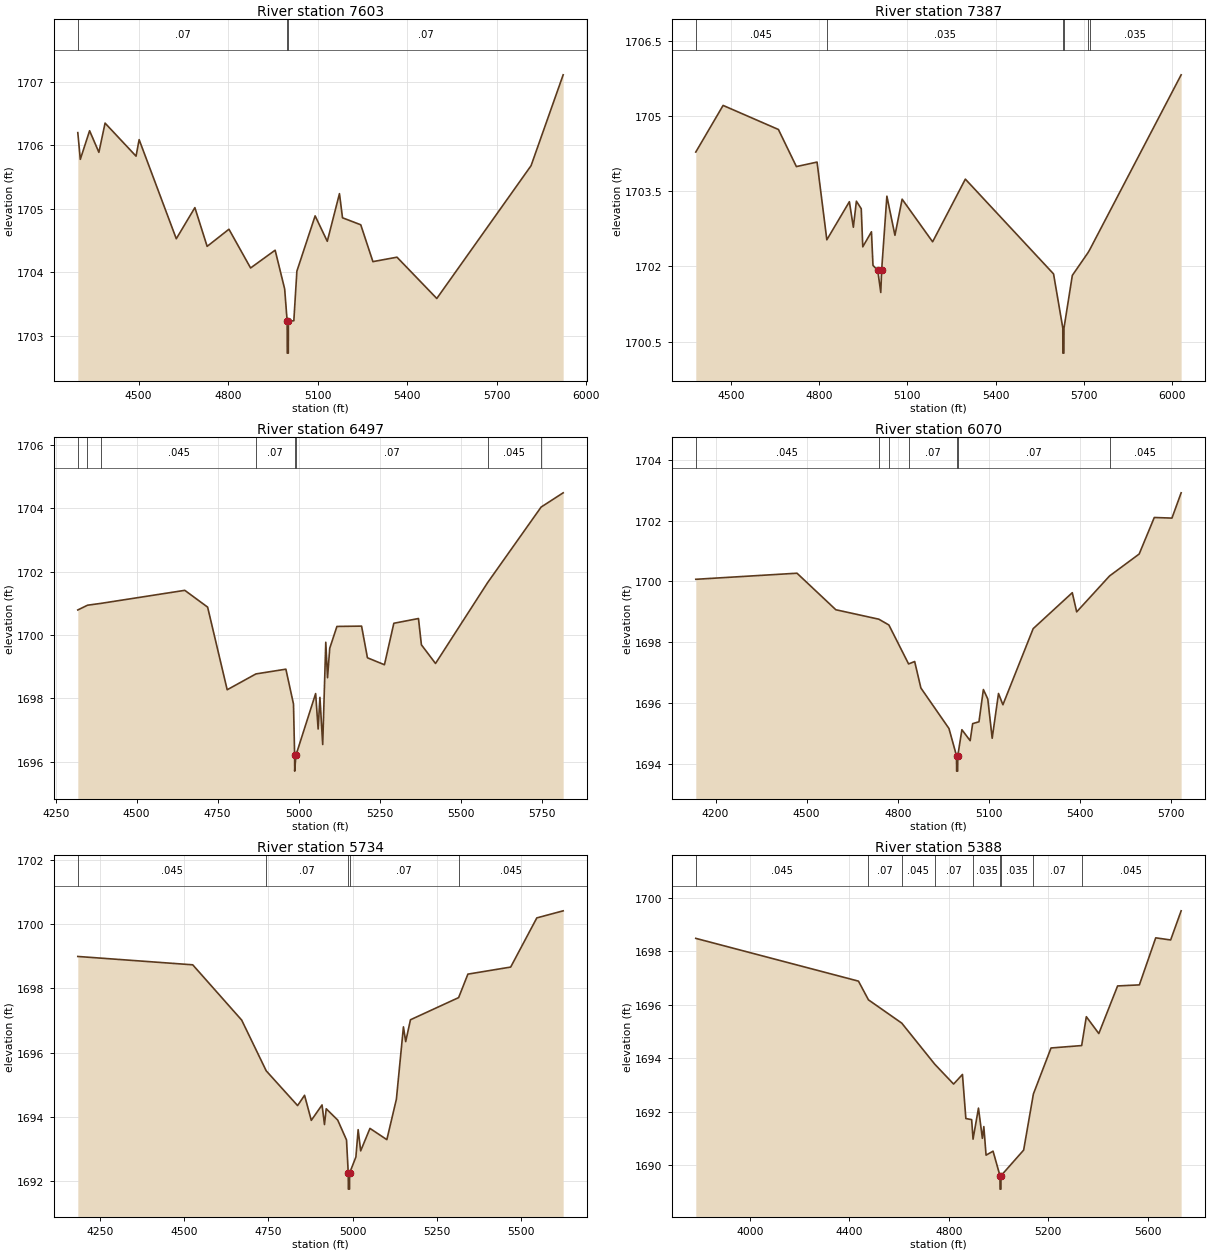
Type RM Length L Ch R = 1 ,7603    ,216,216,216
BEGIN DESCRIPTION:
MULBERRY CREEK TRIBUTARY 5_3 2.0
END DESCRIPTION:
XS GIS Cut Line= 3
      1559394.33      6874516.09      1559580.09      6873837.76
      1559754.48       6872932.4
#Sta/Elev= 30
  4296.7  1706.2  4305.1 1705.78  4336.2 1706.23  4367.3 1705.89    4388 1706.35
  4491.7 1705.83  4502.1 1706.09  4626.5 1704.53  4688.7 1705.02  4729.8 1704.41
  4802.8 1704.68  4875.3 1704.07  4957.5 1704.35  4989.4 1703.74  4997.8 1703.23
  4998.1 1702.73  5001.6 1702.73  5001.8 1703.23  5020.1 1703.24  5030.3 1704.02
  5091.4 1704.89  5132.1 1704.49  5172.9 1705.24  5183.1 1704.86  5244.2 1704.75
  5284.9 1704.17  5365.5 1704.24  5498.8 1703.59  5814.5 1705.68    5922 1707.11
#Mann= 3 ,-1 , 0
  4296.7     .07       0  4997.8     .07       0  5001.8     .07       0
#XS Ineff= 2 , 0
       0                  5172.9       0 1705.24
Permanent Ineff=
       F       F
Bank Sta=4997.8,5001.8
XS Rating Curve= 0 ,0
Exp/Cntr=0.3,0.1

Type RM Length L Ch R = 1 ,7387    ,890,890,890
BEGIN DESCRIPTION:
Mapping XS 07128fe0
END DESCRIPTION:
XS GIS Cut Line= 4
      1559602.67      6874563.81      1559700.61      6874046.05
      1559774.39      6873772.61      1559888.97      6872941.73
#Sta/Elev= 30
  4381.1 1704.28  4473.9 1705.21  4661.8 1704.73  4722.9 1703.99  4793.1 1704.08
  4826.3 1702.53  4902.9 1703.29  4916.4 1702.78  4926.7  1703.3  4943.2 1703.15
  4948.4 1702.39  4977.9 1702.69  4983.1 1702.02  4999.2 1701.92  5009.6 1701.48
 5012.581701.931  5030.3  1703.4  5057.7 1702.62  5082.1 1703.34  5185.7 1702.49
  5296.9 1703.74  5596.5 1701.85    5628 1700.77  5628.2 1700.27  5631.7 1700.27
    5632 1700.77  5660.3 1701.82  5713.2 1702.27  5719.2 1702.33    6030 1705.82
#Mann= 6 ,-1 , 0
  4381.1    .045       0  4826.3    .035       0    5628    .035       0
    5632    .035       0  5713.2    .045       0  5719.2    .035       0
#XS Ineff= 2 , 0
       0                  5296.9       0 1703.74
Permanent Ineff=
       F       F
Bank Sta=4999.2,5012.58
XS Rating Curve= 0 ,0
Exp/Cntr=0.3,0.1

Type RM Length L Ch R = 1 ,6497    ,427,427,427
BEGIN DESCRIPTION:
Mapping XS fb1d5087
END DESCRIPTION:
XS GIS Cut Line= 3
      1560213.86      6874455.95       1560283.3      6873876.13
      1559922.21      6873035.89
#Sta/Elev= 30
  4318.3 1700.79  4348.2 1700.94  4390.8    1701  4648.6 1701.41  4719.1 1700.88
  4779.5 1698.27  4868.2 1698.77  4960.7 1698.92  4984.2 1697.82  4987.7  1696.2
  4987.9  1695.7  4991.7  1696.2  5052.6 1698.15  5060.3 1697.03  5065.8 1698.03
  5074.4 1696.54  5083.9 1699.77  5089.3 1698.65  5096.1 1699.58  5118.3 1700.27
  5194.4 1700.28  5212.5 1699.28    5265 1699.06    5294 1700.37  5370.1 1700.52
  5379.1 1699.69  5422.7  1699.1  5583.3 1701.65  5748.7 1704.04  5816.8 1704.49
#Mann= 8 ,-1 , 0
  4318.3    .045       0  4348.2     .07       0  4390.8    .045       0
  4868.2     .07       0  4987.7     .07       0  4991.7     .07       0
  5583.3    .045       0  5748.7    .035       0
Bank Sta=4987.7,4991.7
XS Rating Curve= 0 ,0
Exp/Cntr=0.3,0.1

Type RM Length L Ch R = 1 ,6070    ,336,336,336
BEGIN DESCRIPTION:
Mapping XS 9a551990
END DESCRIPTION:
XS GIS Cut Line= 3
      1560395.28      6874479.93      1560590.58      6873637.95
      1560143.53      6873056.35
#Sta/Elev= 30
    4135 1700.07  4468.2 1700.27  4596.1 1699.07  4737.5 1698.76  4770.7 1698.57
  4835.6 1697.29  4855.6 1697.37  4876.1  1696.5  4968.5 1695.17  4993.5 1694.27
  4993.7 1693.77  4997.2 1693.77  4997.5 1694.27  5011.1 1695.13  5038.3 1694.77
  5046.5 1695.33  5067.3 1695.39  5081.8 1696.45  5096.3 1696.14  5110.8 1694.85
  5131.6 1696.32  5146.1 1695.95  5245.8 1698.45  5374.5 1699.63    5389    1699
  5497.2 1700.18  5594.7  1700.9  5644.5  1702.1  5702.6 1702.08  5732.9 1702.91
#Mann= 7 ,-1 , 0
    4135    .045       0  4737.5     .07       0  4770.7    .045       0
  4835.6     .07       0  4993.5     .07       0  4997.5     .07       0
  5497.2    .045       0
Bank Sta=4993.5,4997.5
XS Rating Curve= 0 ,0
Exp/Cntr=0.3,0.1

Type RM Length L Ch R = 1 ,5734    ,346,346,346
BEGIN DESCRIPTION:
Mapping XS f80425b0
END DESCRIPTION:
XS GIS Cut Line= 3
      1560640.93      6874226.87      1560859.69      6873449.05
      1560383.97      6873028.89
#Sta/Elev= 30
  4183.2 1698.99  4524.8 1698.73  4670.3 1697.01  4743.3 1695.43  4836.5 1694.35
  4857.2 1694.67  4877.2 1693.89  4909.2 1694.37  4916.4 1693.76  4921.6 1694.25
  4955.7  1693.9  4981.9 1693.28  4987.1 1692.25  4987.4 1691.75  4990.9 1691.75
  4991.1 1692.25  5009.8 1692.75  5016.5  1693.6    5024 1692.94  5051.6 1693.64
  5101.8 1693.29  5130.2 1694.55  5151.1  1696.8  5157.8 1696.34    5172 1697.02
  5315.2 1697.71  5342.7 1698.44  5469.9 1698.66  5547.6 1700.19  5625.9 1700.41
#Mann= 5 ,-1 , 0
  4183.2    .045       0  4743.3     .07       0  4987.1     .07       0
  4991.1     .07       0  5315.2    .045       0
Bank Sta=4987.1,4991.1
XS Rating Curve= 0 ,0
Exp/Cntr=0.3,0.1

Type RM Length L Ch R = 1 ,5388    ,64,64,64
BEGIN DESCRIPTION:
Mapping XS 087989bd
END DESCRIPTION:
XS GIS Cut Line= 4
      1560648.49      6874370.63      1561228.39      6873507.85
      1561054.78      6873212.71      1560553.64      6872942.53
#Sta/Elev= 30
  3782.8 1698.49  4436.8 1696.89    4477 1696.19  4610.8 1695.32  4743.8 1693.78
  4819.3 1693.04  4854.9  1693.4  4868.6 1691.75  4891.8 1691.71  4897.5 1690.98
  4919.3 1692.14    4935 1691.01  4940.8 1691.45  4949.8 1690.38  4977.9 1690.53
  5005.8 1689.61  5006.1 1689.11  5009.6 1689.11  5009.8 1689.61  5100.9 1690.57
  5140.1 1692.67    5211 1694.39  5334.2 1694.48  5352.9 1695.56  5403.1 1694.93
  5478.6 1696.71  5566.2 1696.75  5631.9 1698.51  5691.9 1698.43  5734.1 1699.52
#Mann= 9 ,-1 , 0
  3782.8    .045       0    4477     .07       0  4610.8    .045       0
  4743.8     .07       0  4897.5    .035       0  5005.8    .035       0
  5009.8    .035       0  5140.1     .07       0  5334.2    .045       0
Bank Sta=5005.8,5009.8
XS Rating Curve= 0 ,0
Exp/Cntr=0.3,0.1

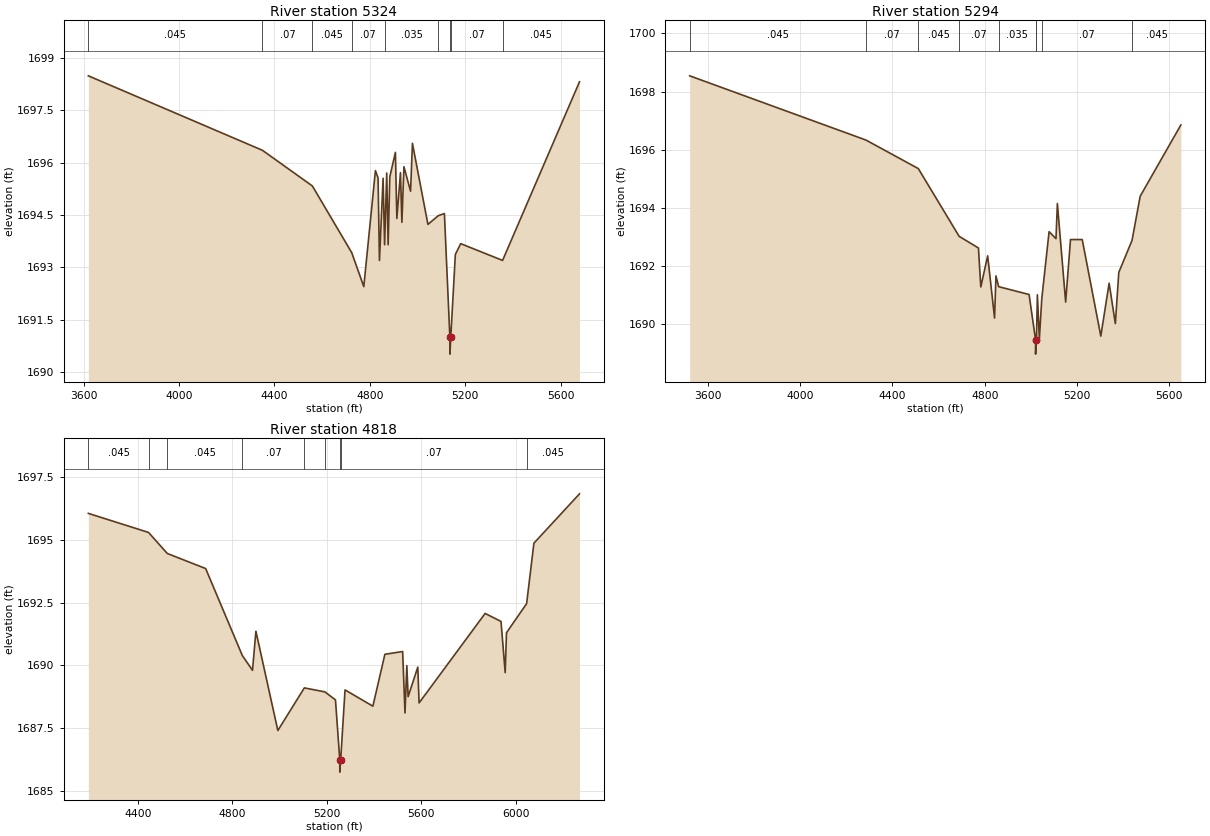
Type RM Length L Ch R = 1 ,5324    ,30,30,30
BEGIN DESCRIPTION:
Mapping XS 3d8b6300
END DESCRIPTION:
XS GIS Cut Line= 5
      1560630.02      6874462.97      1561271.79      6873529.55
      1561276.13      6873455.77      1561124.22      6873217.05
       1560648.4      6872905.61
#Sta/Elev= 30
  3620.2 1698.48  4349.7 1696.35    4559 1695.33  4724.1 1693.42  4774.5 1692.45
  4823.2 1695.77  4834.2 1695.56  4840.1  1693.2  4855.4 1695.55  4861.7 1693.65
  4870.6  1695.7  4876.5 1693.65  4883.5 1695.59    4907 1696.29    4913  1694.4
  4928.2 1695.71  4934.1 1694.29  4942.7 1695.88  4970.5 1695.18  4978.3 1696.55
  5043.3 1694.23  5086.6 1694.48  5112.3 1694.54  5135.1 1691.02  5135.4 1690.52
  5139.1 1691.02  5158.2 1693.37  5180.6 1693.68  5356.1  1693.2  5678.5 1698.31
#Mann= 9 ,-1 , 0
  3620.2    .045       0  4349.7     .07       0    4559    .045       0
  4724.1     .07       0  4861.7    .035       0  5086.6     .07       0
  5135.1    .035       0  5139.1     .07       0  5356.1    .045       0
Bank Sta=5135.1,5139.1
XS Rating Curve= 0 ,0
Exp/Cntr=0.3,0.1

Type RM Length L Ch R = 1 ,5294    ,476,476,476
BEGIN DESCRIPTION:
Mapping XS ad15b9ae
END DESCRIPTION:
XS GIS Cut Line= 3
      1560630.02      6874512.97      1561331.69      6873474.86
      1560837.91      6872751.53
#Sta/Elev= 30
  3521.1 1698.54  4285.4 1696.33    4512 1695.35    4689 1693.02  4772.6 1692.62
  4782.8 1691.28  4812.6 1692.35  4842.5 1690.21  4848.5 1691.66  4860.1 1691.29
  4992.1 1691.02    5020 1689.47  5020.2 1688.97    5024 1689.47    5028 1691.01
  5036.7  1689.5  5047.2 1690.88  5078.8 1693.18  5108.7 1692.94  5114.7 1694.15
  5150.6 1690.76  5171.6 1692.91  5222.4 1692.91    5303 1689.59    5339 1691.41
    5366 1690.02  5380.9 1691.78  5438.3 1692.88  5473.7  1694.4  5649.9 1696.85
#Mann= 9 ,-1 , 0
  3521.1    .045       0  4285.4     .07       0    4512    .045       0
    4689     .07       0  4860.1    .035       0    5020    .035       0
    5024    .035       0  5047.2     .07       0  5438.3    .045       0
Bank Sta=5020,5024
XS Rating Curve= 0 ,0
Exp/Cntr=0.3,0.1

Type RM Length L Ch R = 1 ,4818    ,0,0,0
BEGIN DESCRIPTION:
MULBERRY CREEK TRIBUTARY 5_3 1.0
END DESCRIPTION:
XS GIS Cut Line= 4
      1561087.05      6874057.34      1561591.77      6873424.45
      1561556.51      6872983.55      1560799.98      6872645.84
#Sta/Elev= 30
  4190.5 1696.06  4445.4  1695.3    4525 1694.46  4687.3 1693.86  4842.7 1690.39
  4885.8  1689.8  4900.2 1691.36  4993.1  1687.4  5105.4  1689.1  5192.5 1688.94
  5237.2 1688.62  5255.3 1686.24  5255.5 1685.74  5259.3 1686.24  5277.7 1689.02
  5395.6 1688.37  5446.5 1690.44  5521.7 1690.55  5531.6  1688.1  5539.4 1689.99
  5544.9 1688.75  5585.9 1689.93  5591.3  1688.5  5871.1 1692.07  5938.3 1691.75
    5956 1689.71  5961.5  1691.3  6046.8 1692.46  6077.6 1694.87  6270.8 1696.84
#Mann= 9 ,-1 , 0
  4190.5    .045       0  4445.4     .07       0    4525    .045       0
  4842.7     .07       0  5105.4     .16       0  5192.5     .07       0
  5255.3     .07       0  5259.3     .07       0  6046.8    .045       0
Bank Sta=5255.3,5259.3
XS Rating Curve= 0 ,0
Exp/Cntr=0.3,0.1

Chan Stop Cuts=-1
Use User Specified Reach Order=0
Composite Channel Slope=5