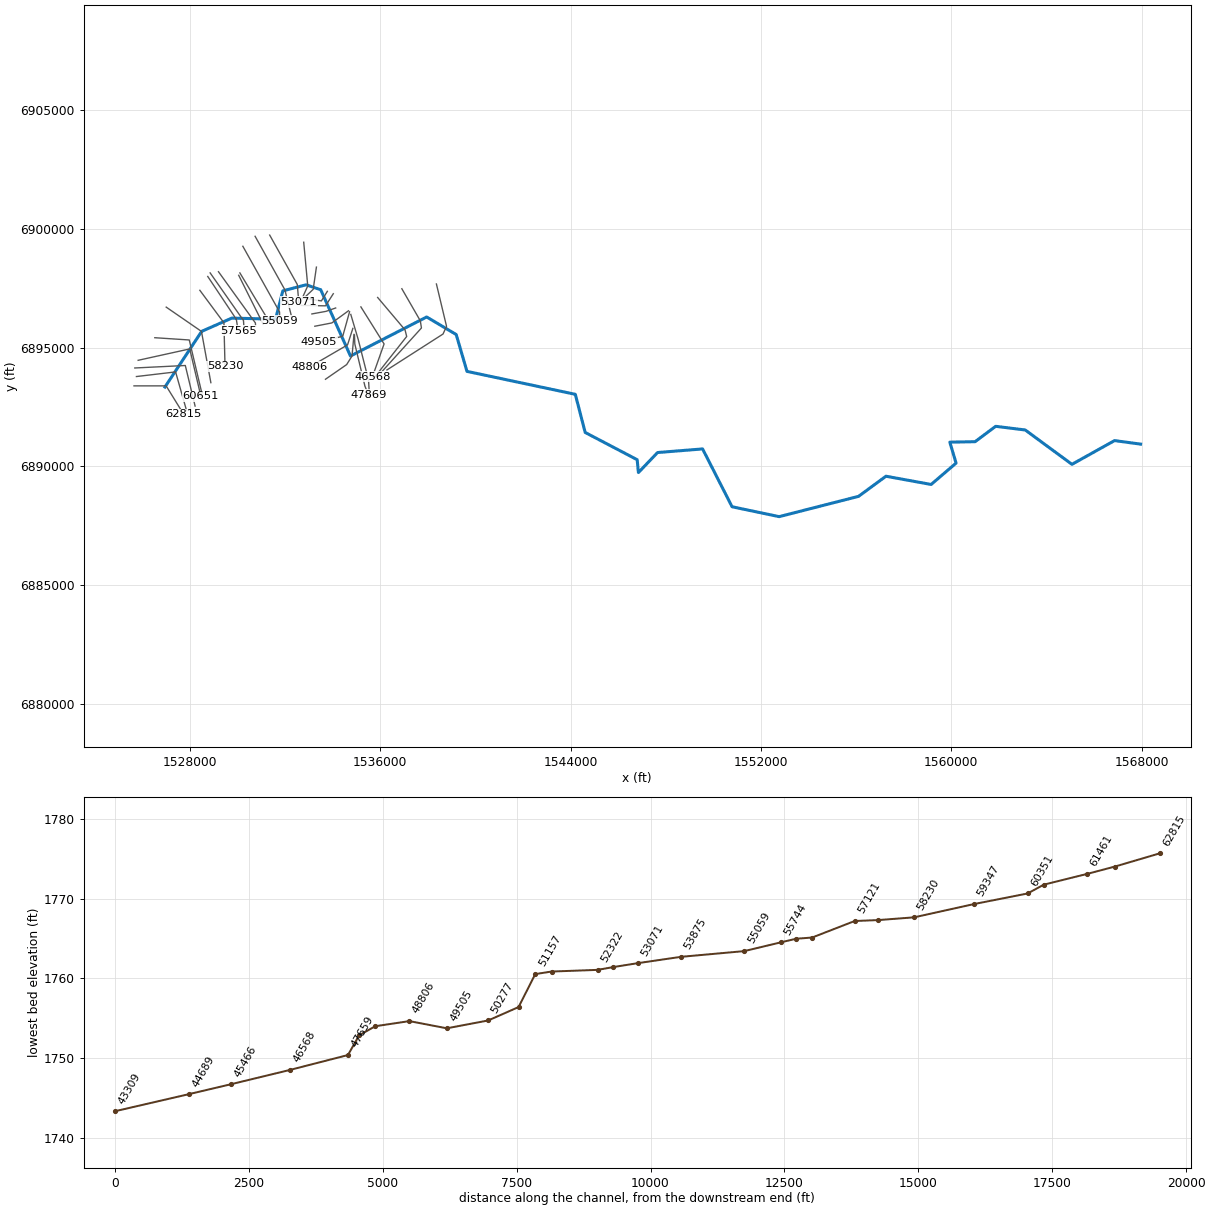
--- MULBERRY CREEK TRIBUTARY 6.prj (project) ---

Proj Title=MULBERRY CREEK TRIBUTARY 6 Base Level Engineering
Current Plan=p01
Default Exp/Contr=0.3,0.1
English Units
Geom File=g01
Flow File=f01
Plan File=p01
Y Axis Title=Elevation
X Axis Title(PF)=Main Channel Distance
X Axis Title(XS)=Station
BEGIN DESCRIPTION:
MULBERRY CREEK TRIBUTARY 6
END DESCRIPTION:
DSS Export Rating Curves= 0
DSS Export Rating Curve Sorted= 0
DSS Export Volume Flow Curves= 0
DXF OffsetX= 0
DXF OffsetY= 0
DXF ScaleX= 1
DXF ScaleY= 10

--- MULBERRY CREEK TRIBUTARY 6.p01 (plan) ---

Plan Title=Multiple Run
Short Identifier=Multiple
Geom File=g01
Flow File=f01
Subcritical Flow
K Sum by GR= 0
Std Step Tol= 0.01
Critical Tol= 0.01
Num of Std Step Trials= 20
Max Error Tol= 0.3
Flow Tol Ratio= 0.001
Split Flow NTrial= 30
Split Flow Tol= 0.02
Split Flow Ratio= 0.02
Log Output Level= 0
Friction Slope Method= 1
Unsteady Friction Slope Method= 2
Unsteady Bridges Friction Slope Method= 1
Parabolic Critical Depth
Global Vel Dist=  1 , 1 , 1
Global Log Level= 0
CheckData=True
Encroach Param= -1, 0, 0, 0
BEGIN DESCRIPTION:
Multiple Run
END DESCRIPTION:

--- MULBERRY CREEK TRIBUTARY 6.f01 (steady flow) ---

Flow Title=Multiple
Program Version=4.10
Number of Profiles= 7
Profile Names=10-year,25-year,50-year,1pct_min,100-year,1pct_plu,500-year
River Rch & RM=MULBERRY CREEK T,Reach-1         ,62815
     121     156     183     107     213     425     292
River Rch & RM=MULBERRY CREEK T,Reach-1         ,61980
     154     201     238     140     279     557     389
River Rch & RM=MULBERRY CREEK T,Reach-1         ,53875
     218     292     349     208     415     828     593
River Rch & RM=MULBERRY CREEK T,Reach-1         ,49505
     262     353     425     254     508    1013     733
River Rch & RM=MULBERRY CREEK T,Reach-1         ,48169
     328     448     545     329     656    1308     962
River Rch & RM=MULBERRY CREEK T,Reach-1         ,40658
     389     538     659     401     799    1595    1193
River Rch & RM=MULBERRY CREEK T,Reach-1         ,28022
     504     706     874     536    1070    2135    1627
River Rch & RM=MULBERRY CREEK T,Reach-1         ,24037
     550     775     962     592    1182    2358    1809
River Rch & RM=MULBERRY CREEK T,Reach-1         ,19781
     602     851    1060     654    1304    2603    2006
River Rch & RM=MULBERRY CREEK T,Reach-1         ,15418
     710    1011    1264     783    1562    3117    2422
River Rch & RM=MULBERRY CREEK T,Reach-1         ,14333
     890    1278    1609    1002    2000    3991    3136
River Rch & RM=MULBERRY CREEK T,Reach-1         ,5952
     949    1367    1724    1077    2148    4286    3380
Boundary for River Rch & Prof#=MULBERRY CREEK T,Reach-1         , 1
Up Type= 0
Dn Type= 3
Dn Slope=0.0025
Boundary for River Rch & Prof#=MULBERRY CREEK T,Reach-1         , 2
Up Type= 0
Dn Type= 3
Dn Slope=0.0025
Boundary for River Rch & Prof#=MULBERRY CREEK T,Reach-1         , 3
Up Type= 0
Dn Type= 3
Dn Slope=0.0025
Boundary for River Rch & Prof#=MULBERRY CREEK T,Reach-1         , 4
Up Type= 0
Dn Type= 3
Dn Slope=0.0025
Boundary for River Rch & Prof#=MULBERRY CREEK T,Reach-1         , 5
Up Type= 0
Dn Type= 3
Dn Slope=0.0025
Boundary for River Rch & Prof#=MULBERRY CREEK T,Reach-1         , 6
Up Type= 0
Dn Type= 3
Dn Slope=0.0025
Boundary for River Rch & Prof#=MULBERRY CREEK T,Reach-1         , 7
Up Type= 0
Dn Type= 3
Dn Slope=0.0025
DSS Import GetInterval= 0
DSS Import GetPeak= 0
DSS Import FillOption= 0

--- MULBERRY CREEK TRIBUTARY 6.g01 (geometry) ---

Geom Title=Existing Conditions
Program Version=4.10

River Reach=MULBERRY CREEK T,Reach-1
Reach XY= 30
        1526955.        6893338.      1528498.81      6895680.18
      1529765.62       6896237.4      1531603.54      6896191.54
      1531909.83      6897382.37      1532884.97      6897637.93
      1533502.03      6897429.69      1534752.33      6894643.42
      1537953.37      6896284.87      1539194.49      6895547.81
      1539647.94      6893997.02      1544199.56      6893032.75
      1544615.51      6891428.19      1546799.89      6890283.04
      1546852.69      6889743.08      1547656.47      6890584.45
      1549549.11      6890736.03      1550787.78      6888304.24
      1552765.68      6887888.75      1556103.45      6888741.75
        1557255.        6889588.      1559153.45      6889241.75
      1560201.48      6890139.28       1559938.2      6891021.58
      1560999.06      6891040.14      1561865.49      6891687.52
      1563107.29      6891532.94      1565070.22      6890088.52
      1566861.39      6891086.48        1567955.        6890938.

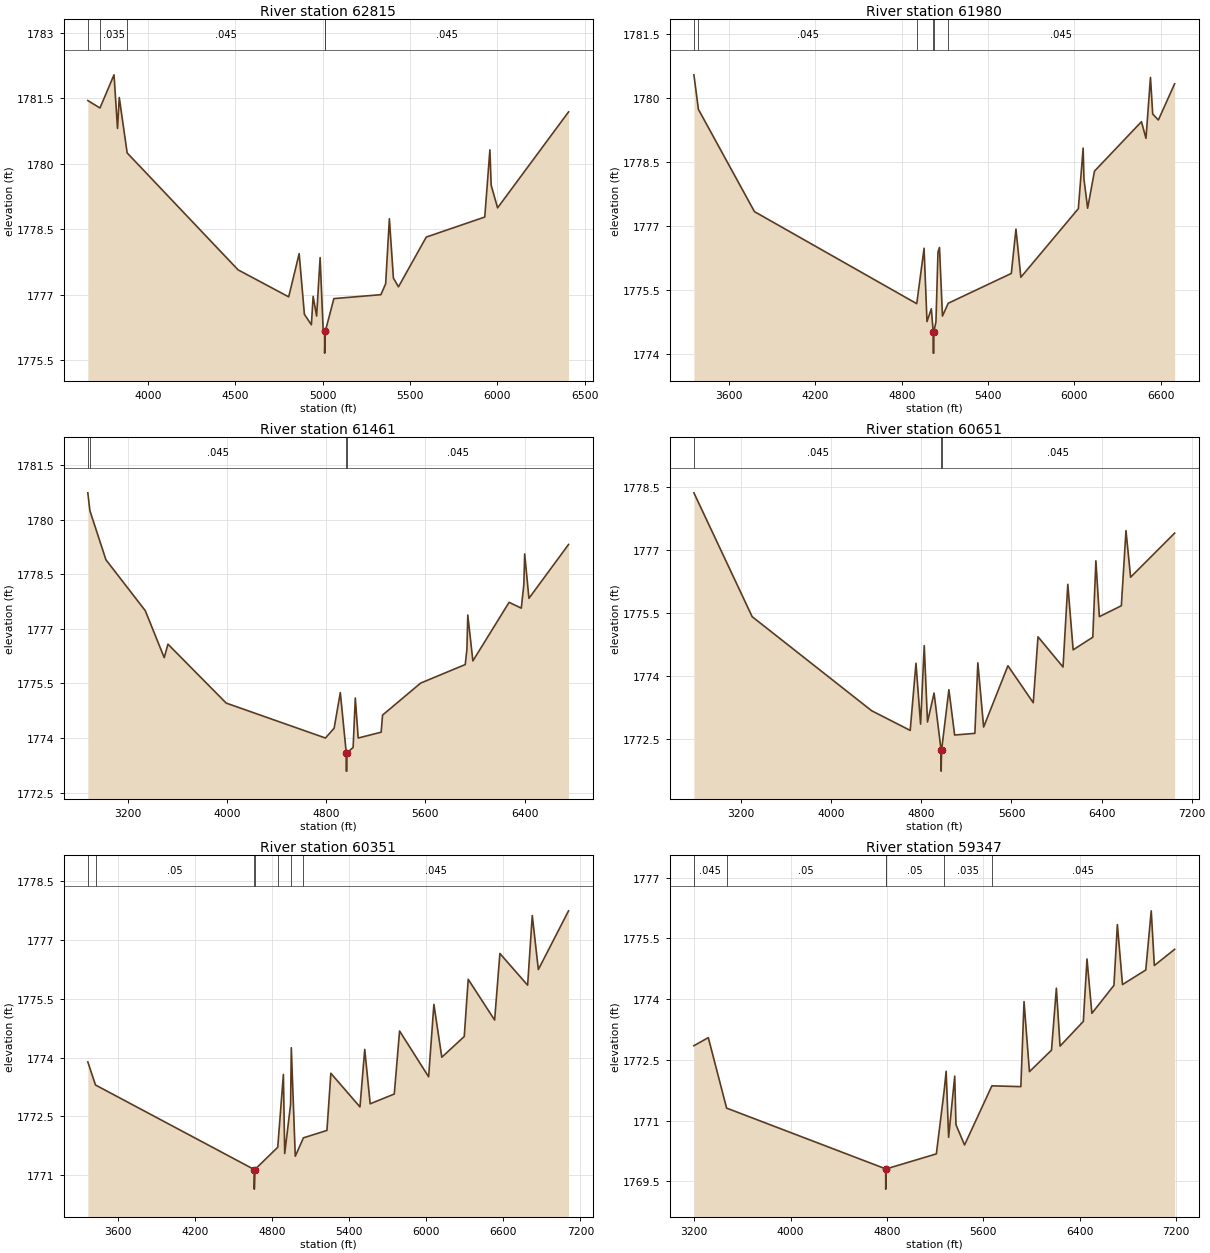
Type RM Length L Ch R = 1 ,62815   ,835,835,835
BEGIN DESCRIPTION:
MULBERRY CREEK TRIBUTARY 6 47.0
END DESCRIPTION:
XS GIS Cut Line= 3
        1525655.        6893388.        1527005.        6893388.
      1527742.16      6892194.97
#Sta/Elev= 30
  3654.6 1781.45  3724.1 1781.28  3804.6 1782.04  3824.6 1780.81  3834.6 1781.52
  3879.8 1780.25  4514.6 1777.57  4804.6 1776.95  4864.6 1777.94  4894.6 1776.55
  4934.6 1776.31  4944.6 1776.96  4964.6 1776.51  4984.6 1777.85  5002.1 1776.18
  5010.3 1776.16  5010.5 1775.66  5014.3 1776.16  5063.4 1776.91  5332.7    1777
  5359.8 1777.25  5381.1 1778.74  5404.3 1777.38  5433.2 1777.18  5592.3 1778.32
  5927.3 1778.78  5956.7 1780.32    5964 1779.51  6000.6 1778.99    6407 1781.19
#Mann= 5 ,-1 , 0
  3654.6    .045       0  3724.1    .035       0  3879.8    .045       0
  5010.3    .045       0  5014.3    .045       0
Bank Sta=5010.3,5014.3
XS Rating Curve= 0 ,0
Exp/Cntr=0.3,0.1

Type RM Length L Ch R = 1 ,61980   ,519,519,519
BEGIN DESCRIPTION:
MULBERRY CREEK TRIBUTARY 6 46.0
END DESCRIPTION:
XS GIS Cut Line= 3
      1525757.31      6893780.19      1527403.11      6893974.63
      1527861.46      6892356.55
#Sta/Elev= 30
  3356.6 1780.54  3387.9 1779.73  3777.2 1777.33  4904.4 1775.17  4955.3 1776.47
  4975.5 1774.75  5005.7 1775.05  5018.7 1774.51    5019 1774.01  5022.5 1774.01
  5022.7 1774.51  5037.7 1774.74  5051.9 1776.38  5062.3 1776.49  5083.1 1774.88
  5122.8 1775.18  5561.2 1775.88  5593.5 1776.92  5627.5 1775.79  6026.8  1777.4
  6060.1 1778.82  6065.9 1778.09  6091.3 1777.41    6139 1778.28  6465.2 1779.44
  6496.6 1779.05  6527.8 1780.48  6543.4 1779.62  6582.6 1779.48  6695.6 1780.33
#Mann= 6 ,-1 , 0
  3356.6    .035       0  3387.9    .045       0  4904.4     .07       0
  5018.7    .045       0  5022.7     .07       0  5122.8    .045       0
Bank Sta=5018.7,5022.7
XS Rating Curve= 0 ,0
Exp/Cntr=0.3,0.1

Type RM Length L Ch R = 1 ,61461   ,810,810,810
BEGIN DESCRIPTION:
MULBERRY CREEK TRIBUTARY 6 45.0
END DESCRIPTION:
XS GIS Cut Line= 3
      1525689.02      6894140.14      1527811.39      6894244.31
      1528222.55      6892537.15
#Sta/Elev= 30
  2874.6 1780.74  2891.2 1780.25  3020.8  1778.9  3338.5  1777.5  3491.3 1776.21
  3521.4 1776.58  3991.9 1774.96  4792.9    1774    4863 1774.27    4913 1775.25
  4960.9 1773.59  4961.2 1773.09  4964.9 1773.09  4965.2 1773.59  5016.3 1773.74
    5034  1775.1  5057.4    1774  5242.6 1774.16  5253.9 1774.63  5561.5 1775.51
  5921.5 1776.02    5935 1776.44    5942 1777.38  5983.2 1776.12  6275.6 1777.73
    6374 1777.57  6394.6 1778.22  6401.3 1779.06  6435.8 1777.84  6755.5 1779.32
#Mann= 4 ,-1 , 0
  2874.6    .035       0  2891.2    .045       0  4960.9    .045       0
  4965.2    .045       0
Bank Sta=4960.9,4965.2
XS Rating Curve= 0 ,0
Exp/Cntr=0.3,0.1

Type RM Length L Ch R = 1 ,60651   ,300,300,300
BEGIN DESCRIPTION:
MULBERRY CREEK TRIBUTARY 6 44.0
END DESCRIPTION:
XS GIS Cut Line= 3
      1525830.04      6894463.01      1527996.98      6894941.34
      1528467.14      6892947.62
#Sta/Elev= 30
  2780.9 1778.37    3298 1775.42  4358.1 1773.18    4701 1772.71  4752.2 1774.31
  4793.2 1772.86  4825.6 1774.73  4854.6 1772.91  4912.9  1773.6  4975.3 1772.24
  4975.6 1771.74  4979.6 1772.24  5044.5 1773.68  5095.5  1772.6  5275.1 1772.64
  5301.4 1774.32  5352.8 1772.79  5568.5 1774.25  5793.4 1773.37  5835.6 1774.94
  6057.7 1774.22    6100 1776.19  6147.5 1774.63  6321.9 1774.93  6349.4 1776.75
  6380.2 1775.42  6575.4 1775.68  6616.5 1777.47  6657.6 1776.36  7048.4 1777.41
#Mann= 3 ,-1 , 0
  2780.9    .045       0  4975.3    .045       0  4979.6    .045       0
Bank Sta=4975.3,4979.6
XS Rating Curve= 0 ,0
Exp/Cntr=0.3,0.1

Type RM Length L Ch R = 1 ,60351   ,1004,1004,1004
BEGIN DESCRIPTION:
MULBERRY CREEK TRIBUTARY 6 43.0
END DESCRIPTION:
XS GIS Cut Line= 3
      1526529.98        6895413.      1527977.38      6895317.71
      1528504.99      6893088.02
#Sta/Elev= 30
  3365.6 1773.89  3425.5  1773.3  4661.3 1771.14  4661.5 1770.64  4665.6 1771.14
  4843.8 1771.71  4887.8 1773.57    4898 1771.55  4943.8  1772.8  4949.4 1774.25
  4980.3 1771.48  5043.7 1771.95  5226.9 1772.14  5257.2  1773.6  5483.9 1772.74
    5521 1774.21  5563.3 1772.82    5751 1773.07  5792.1 1774.68  6018.2 1773.51
  6059.3 1775.36  6120.9 1774.01  6295.6 1774.54  6326.4    1776    6532 1774.96
  6573.1 1776.66  6788.9 1775.85    6825 1777.63  6872.4 1776.25  7107.4 1777.75
#Mann= 7 ,-1 , 0
  3365.6    .045       0  3425.5     .05       0  4661.3    .035       0
  4665.6     .05       0  4843.8    .045       0  4943.8    .035       0
  5043.7    .045       0
Bank Sta=4661.3,4665.6
XS Rating Curve= 0 ,0
Exp/Cntr=0.3,0.1

Type RM Length L Ch R = 1 ,59347   ,1117,1117,1117
BEGIN DESCRIPTION:
Mapping XS 6cd8dbe2
END DESCRIPTION:
XS GIS Cut Line= 3
       1527008.7      6896698.85      1528490.21      6895678.12
      1528885.08      6893522.39
#Sta/Elev= 30
  3196.7 1772.85  3316.2 1773.05  3468.2 1771.31    4789 1769.81  4789.3 1769.31
  4793.4 1769.81  5209.4 1770.18  5274.6 1771.75  5290.7 1772.22  5311.1 1770.59
  5361.9  1772.1  5372.1  1770.9  5443.5  1770.4  5670.4 1771.86  5910.9 1771.84
  5937.2 1773.94  5982.1 1772.21  6165.2 1772.74  6205.7 1774.27  6236.2 1772.84
  6429.4 1773.45  6459.9 1774.99  6500.5 1773.65  6683.5 1774.34  6712.1 1775.84
  6754.7 1774.36  6947.9 1774.72  6993.2 1776.18    7019 1774.83  7187.4 1775.23
#Mann= 6 ,-1 , 0
  3196.7    .045       0  3468.2     .05       0    4789    .035       0
  4793.4     .05       0  5274.6    .035       0  5670.4    .045       0
Bank Sta=4789,4793.4
XS Rating Curve= 0 ,0
Exp/Cntr=0.3,0.1

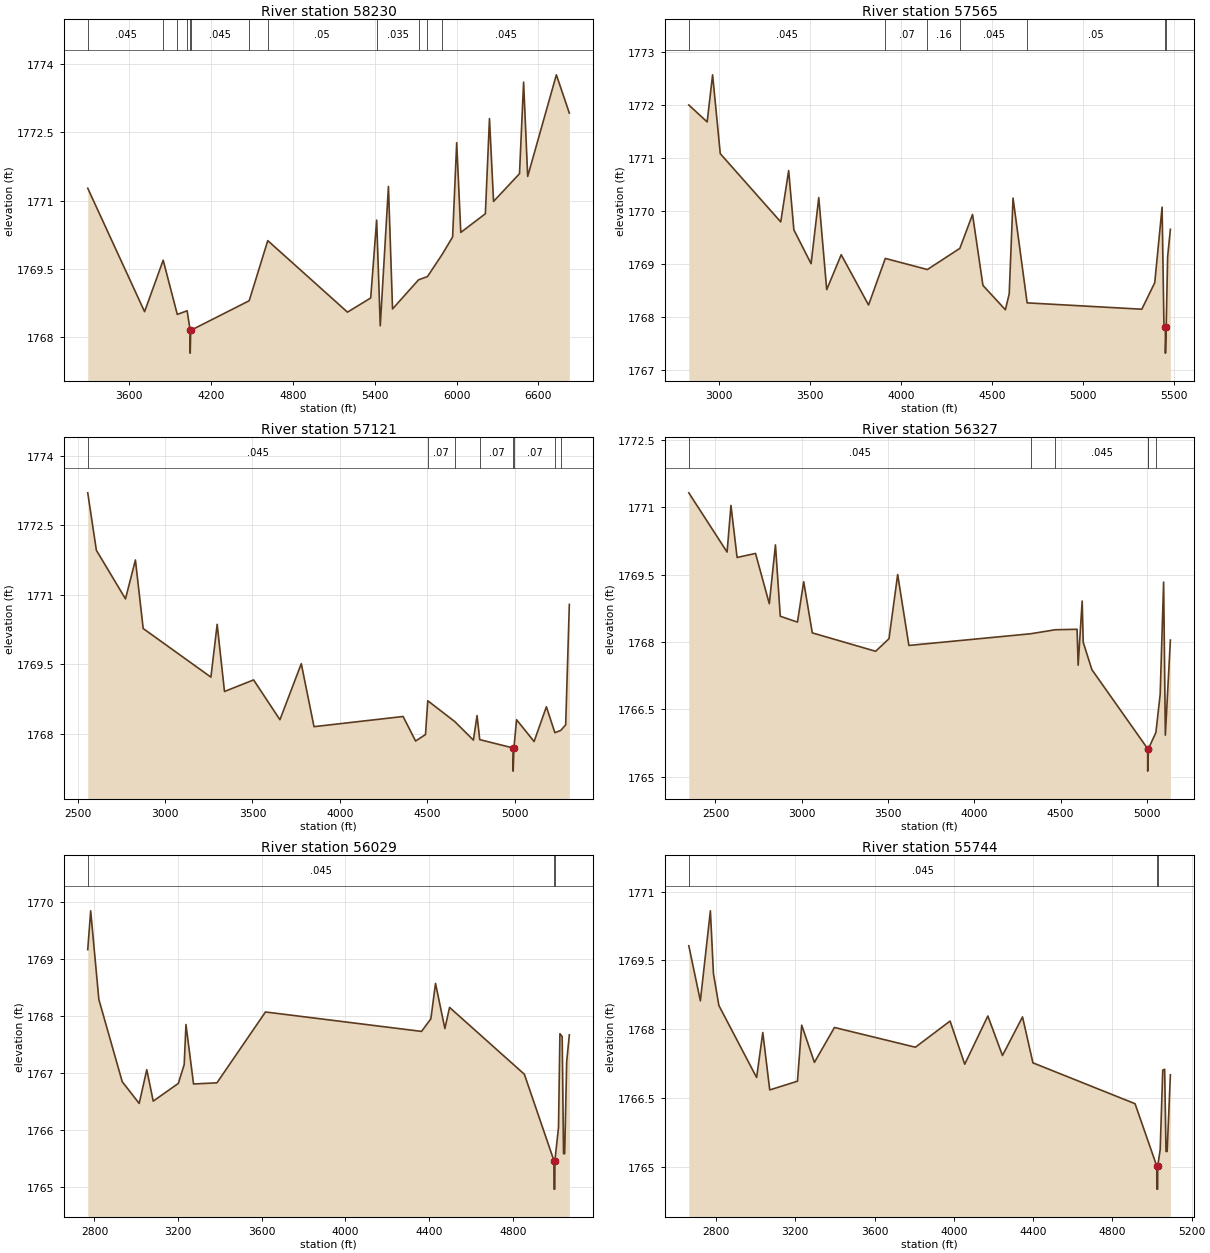
Type RM Length L Ch R = 1 ,58230   ,665,665,665
BEGIN DESCRIPTION:
MULBERRY CREEK TRIBUTARY 6 42.0
END DESCRIPTION:
XS GIS Cut Line= 3
      1528421.89      6897407.19      1529434.66      6896038.43
        1529480.        6894213.
#Sta/Elev= 30
  3297.3 1771.27  3713.7 1768.56  3850.1 1769.69  3953.4  1768.5  4025.6 1768.58
  4047.6 1768.15  4047.9 1767.65    4052 1768.15  4480.2  1768.8  4616.4 1770.12
  5200.5 1768.55  5370.5 1768.86  5414.2 1770.57  5440.6 1768.25  5500.6 1771.31
  5530.6 1768.62  5721.4 1769.26  5786.4 1769.33  5894.8 1769.82  5970.7  1770.2
  6000.7 1772.27  6030.7  1770.3  6210.8 1770.71  6240.8  1772.8  6270.8 1770.98
  6460.9 1771.59  6490.9  1773.6  6520.9 1771.53    6731 1773.76    6826 1772.92
#Mann= 12 ,-1 , 0
  3297.3    .045       0  3850.1     .07       0  3953.4     .16       0
  4025.6    .045       0  4047.6    .035       0    4052    .045       0
  4480.2     .16       0  4616.4     .05       0  5414.2    .035       0
  5721.4    .045       0  5786.4    .035       0  5894.8    .045       0
Bank Sta=4047.6,4052
XS Rating Curve= 0 ,0
Exp/Cntr=0.3,0.1

Type RM Length L Ch R = 1 ,57565   ,444,444,444
BEGIN DESCRIPTION:
MULBERRY CREEK TRIBUTARY 6 41.0
END DESCRIPTION:
XS GIS Cut Line= 3
        1528755.        6897988.        1529955.        6896188.
        1530030.      6895713.01
#Sta/Elev= 30
  2836.2    1772  2936.9 1771.68  2966.9 1772.57    3009 1771.08    3341 1769.79
  3384.5 1770.76  3413.1 1769.64  3507.7    1769  3549.8 1770.25  3593.4 1768.51
    3673 1769.17  3823.2 1768.22  3915.1  1769.1  4146.2 1768.89  4324.4 1769.29
  4394.1 1769.93  4451.2 1768.59  4574.4 1768.13  4595.4 1768.43  4616.4 1770.24
  4693.8 1768.26  5323.5 1768.14  5394.4 1768.64  5434.9 1770.07    5445 1767.83
  5452.9 1767.81  5453.2 1767.31  5457.3 1767.81  5465.2 1769.13  5480.4 1769.65
#Mann= 7 ,-1 , 0
  2836.2    .045       0  3915.1     .07       0  4146.2     .16       0
  4324.4    .045       0  4693.8     .05       0  5452.9    .035       0
  5457.3    .035       0
Bank Sta=5452.9,5457.3
XS Rating Curve= 0 ,0
Exp/Cntr=0.3,0.1

Type RM Length L Ch R = 1 ,57121   ,794,794,794
BEGIN DESCRIPTION:
MULBERRY CREEK TRIBUTARY 6 40.0
END DESCRIPTION:
XS GIS Cut Line= 3
        1528855.        6898138.        1530255.        6896138.
      1530277.54      6895827.13
#Sta/Elev= 30
  2558.3  1773.2  2607.6 1771.96  2774.1 1770.91  2830.8 1771.75  2875.2 1770.27
  3262.4 1769.22  3298.1 1770.36    3340 1768.91  3506.5 1769.16  3656.9  1768.3
    3779 1769.51  3851.8 1768.15    4361 1768.37  4432.4 1767.84  4489.1 1767.98
  4502.1 1768.71  4656.5 1768.26  4762.9 1767.86  4783.8 1768.39  4799.2 1767.87
  4989.9 1767.69  4990.2 1767.19  4994.6 1767.69  5009.6  1768.3  5109.9 1767.83
  5180.1 1768.58  5228.7 1768.02  5262.5 1768.07  5290.4 1768.19  5311.3 1770.79
#Mann= 8 ,-1 , 0
  2558.3    .045       0  4502.1     .07       0  4656.5     .16       0
  4799.2     .07       0  4989.9    .035       0  4994.6     .07       0
  5228.7     .16       0  5262.5     .07       0
Bank Sta=4989.9,4994.6
XS Rating Curve= 0 ,0
Exp/Cntr=0.3,0.1

Type RM Length L Ch R = 1 ,56327   ,298,298,298
BEGIN DESCRIPTION:
MULBERRY CREEK TRIBUTARY 6 39.0
END DESCRIPTION:
XS GIS Cut Line= 3
      1529204.98      6898188.03      1530756.52      6896034.17
      1530765.81      6895898.89
#Sta/Elev= 30
  2345.5 1771.32  2567.4    1770  2589.7 1771.04  2625.3 1769.88  2732.1 1769.97
  2811.9 1768.85  2847.5 1770.16  2875.5 1768.57  2975.1 1768.44  3011.1 1769.34
    3061  1768.2  3427.9 1767.79  3505.3 1768.07  3555.6  1769.5  3620.6 1767.92
  4325.6 1768.18  4469.8 1768.27    4595 1768.28  4601.2 1767.48  4624.5 1768.91
  4630.6 1767.99  4680.9 1767.38  5003.8 1765.62  5004.2 1765.12  5008.5 1765.62
  5051.6 1765.98  5076.4 1766.83  5096.4 1769.33  5106.4 1765.92  5135.6 1768.04
#Mann= 6 ,-1 , 0
  2345.5    .045       0  4325.6     .07       0  4469.8    .045       0
  5003.8    .035       0  5008.5    .045       0  5051.6     .07       0
Bank Sta=5003.8,5008.5
XS Rating Curve= 0 ,0
Exp/Cntr=0.3,0.1

Type RM Length L Ch R = 1 ,56029   ,285,285,285
BEGIN DESCRIPTION:
MULBERRY CREEK TRIBUTARY 6 38.0
END DESCRIPTION:
XS GIS Cut Line= 3
      1530054.99      6898038.01      1531053.43      6896041.78
      1531080.01      6895976.27
#Sta/Elev= 30
    2768 1769.16    2782 1769.84  2821.1 1768.29  2932.9 1766.85    3014 1766.47
  3050.3 1767.06  3081.1 1766.51  3201.2 1766.82  3229.2 1767.15  3237.6 1767.85
  3273.9 1766.81  3385.7 1766.83  3617.8 1768.07  4363.9 1767.73  4408.6 1767.95
  4430.9 1768.57  4475.6 1767.78    4498 1768.15  4855.7 1766.98    4997 1765.47
  4997.3 1764.97  5001.3 1764.97  5001.7 1765.47  5018.9 1766.05  5025.7 1767.69
  5036.5 1767.64    5043 1765.59  5048.4 1765.59    5058  1767.2  5070.7 1767.67
#Mann= 3 ,-1 , 0
    2768    .045       0    4997    .035       0  5001.7    .045       0
Bank Sta=4997,5001.7
XS Rating Curve= 0 ,0
Exp/Cntr=0.3,0.1

Type RM Length L Ch R = 1 ,55744   ,685,685,685
BEGIN DESCRIPTION:
MULBERRY CREEK TRIBUTARY 6 37.0
END DESCRIPTION:
XS GIS Cut Line= 3
        1530105.      6898138.01        1531305.        6896138.
      1531349.61       6896052.3
#Sta/Elev= 30
  2663.4 1769.82  2721.7 1768.62  2772.3 1770.58  2787.8 1769.21    2815 1768.52
  3005.5 1766.95  3036.6 1767.93  3071.6 1766.68  3211.5 1766.87  3232.9 1768.09
    3297 1767.28  3398.1 1768.04  3806.3 1767.61  3981.2 1768.18  4055.1 1767.24
  4171.7 1768.29  4245.5 1767.43  4346.6 1768.27  4399.1 1767.27  4914.2 1766.38
  5023.8 1765.02  5024.1 1764.52  5028.1 1764.52  5028.5 1765.02  5040.9 1765.38
  5053.9 1767.11  5063.4 1767.13  5070.3 1765.34    5076 1765.34  5092.4 1767.01
#Mann= 3 ,-1 , 0
  2663.4    .045       0  5023.8    .035       0  5028.5     .07       0
Bank Sta=5023.8,5028.5
XS Rating Curve= 0 ,0
Exp/Cntr=0.3,0.1

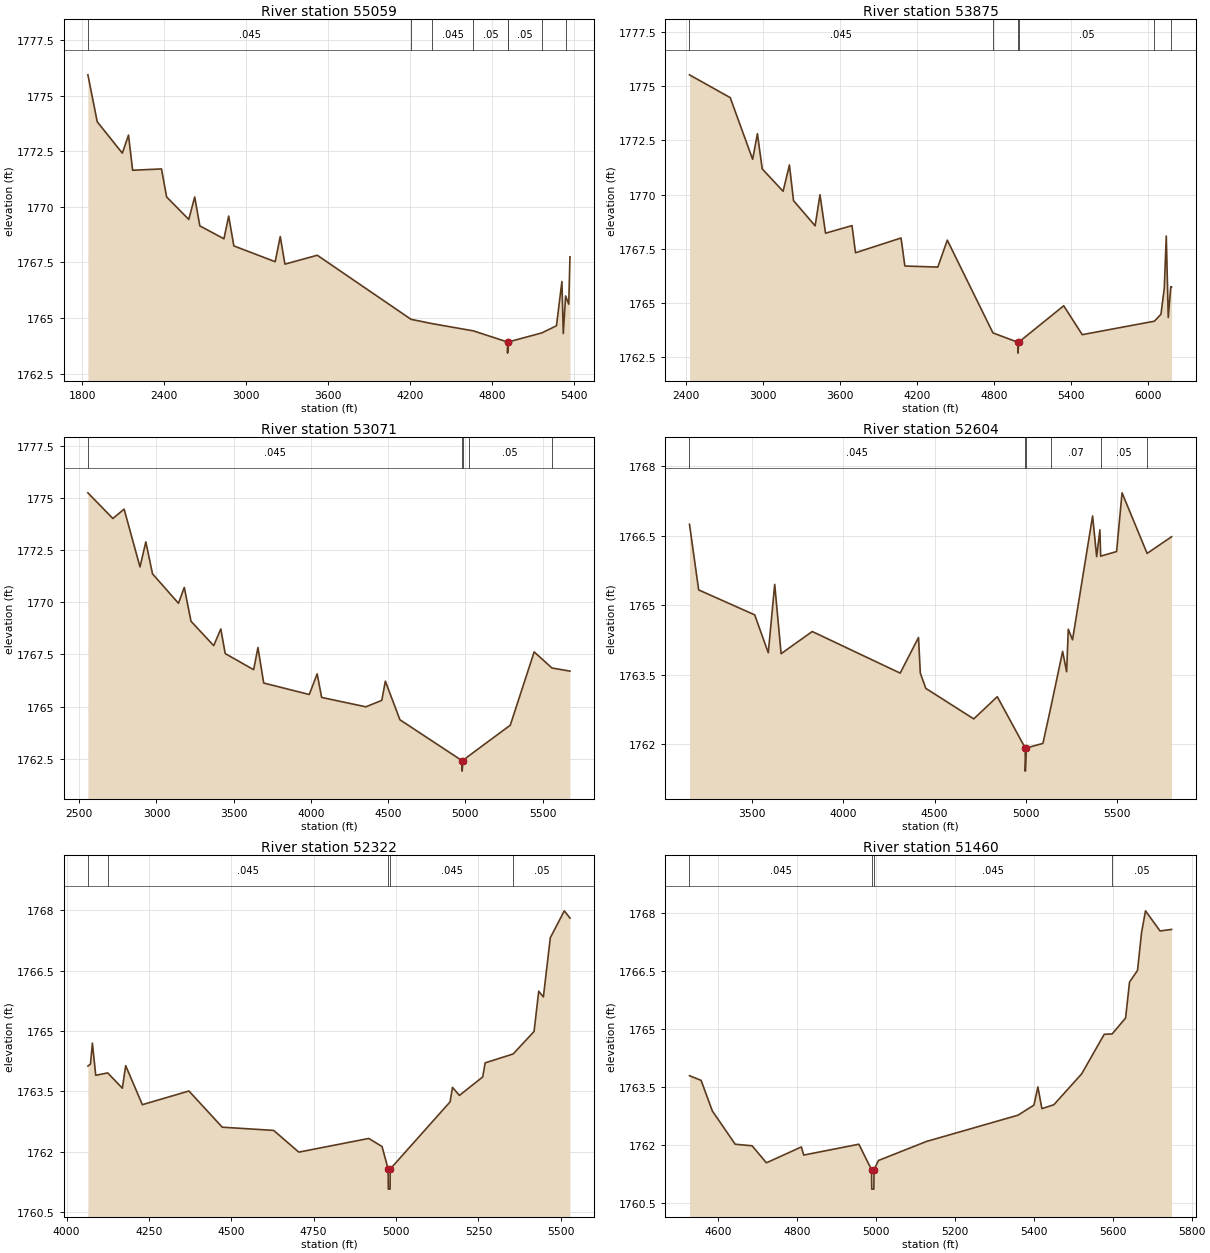
Type RM Length L Ch R = 1 ,55059   ,1184,1184,1184
BEGIN DESCRIPTION:
MULBERRY CREEK TRIBUTARY 6 36.0
END DESCRIPTION:
XS GIS Cut Line= 3
      1530229.41      6899257.61      1531772.02      6896498.03
      1531775.73      6896129.03
#Sta/Elev= 30
  1842.8 1775.93  1911.2 1773.82    2095 1772.41  2140.2 1773.22  2170.4 1771.64
  2381.7  1771.7  2419.4 1770.44  2581.6 1769.43    2625 1770.44  2662.6 1769.14
  2839.1 1768.56  2873.9 1769.58  2911.6 1768.24  3214.3 1767.53  3251.5 1768.66
  3285.9 1767.42  3522.6 1767.82  4209.3 1764.94  4360.4 1764.75  4666.2 1764.42
  4915.9 1763.92  4916.2 1763.42  4920.6 1763.92  5167.6 1764.33  5274.3 1764.65
  5314.3 1766.64  5324.3  1764.3  5341.3 1765.99  5364.3 1765.62  5373.3 1767.75
#Mann= 8 ,-1 , 0
  1842.8    .045       0  4209.3     .05       0  4360.4    .045       0
  4666.2     .05       0  4915.9    .035       0  4920.6     .05       0
  5167.6    .045       0  5341.3     .07       0
Bank Sta=4915.9,4920.6
XS Rating Curve= 0 ,0
Exp/Cntr=0.3,0.1

Type RM Length L Ch R = 1 ,53875   ,804,804,804
BEGIN DESCRIPTION:
Mapping XS c5bc68a2
END DESCRIPTION:
XS GIS Cut Line= 3
      1530744.54      6899677.86      1531994.52      6897429.63
      1532279.99      6896282.98
#Sta/Elev= 30
  2426.7 1775.51  2743.9 1774.46  2918.5 1771.62  2955.5  1772.8  2993.2 1771.18
  3155.6 1770.15  3204.8 1771.36  3236.8 1769.72    3405 1768.56  3442.7 1769.99
  3486.2 1768.22  3692.1 1768.57  3719.5 1767.32  4074.1    1768  4103.8 1766.71
  4360.2 1766.66  4434.3  1767.9  4789.8 1763.63  4983.9  1763.2  4984.4  1762.7
  4989.6  1763.2  5340.8 1764.88  5485.1 1763.55  6046.9 1764.17  6098.1 1764.49
    6124 1765.69  6139.4 1768.09  6154.9 1764.34  6174.5 1765.76  6180.7 1765.74
#Mann= 6 ,-1 , 0
  2426.7    .045       0  4789.8     .05       0  4983.9    .035       0
  4989.6     .05       0  6046.9    .045       0  6174.5    .035       0
Bank Sta=4983.9,4989.6
XS Rating Curve= 0 ,0
Exp/Cntr=0.3,0.1

Type RM Length L Ch R = 1 ,53071   ,467,467,467
BEGIN DESCRIPTION:
Mapping XS cb04e631
END DESCRIPTION:
XS GIS Cut Line= 3
      1531356.48      6899729.14      1532516.22      6897652.72
        1532580.      6896913.01
#Sta/Elev= 30
  2556.1 1775.24  2717.8 1774.01  2790.6 1774.46  2893.4 1771.69  2931.1 1772.89
  2974.5 1771.36  3142.4 1769.95  3180.1 1770.71  3223.5 1769.09  3370.6 1767.92
  3416.5 1768.72  3445.1 1767.54    3629 1766.77    3657 1767.83  3694.2 1766.13
  3989.2 1765.58  4040.3 1766.57  4069.3 1765.44  4355.7 1764.99  4458.8  1765.3
  4481.7 1766.22  4576.1 1764.37  4978.4 1762.41  4978.9 1761.91  4984.3 1762.41
    5020 1762.63  5290.5 1764.11  5445.1 1767.62  5560.1 1766.85  5676.9  1766.7
#Mann= 5 ,-1 , 0
  2556.1    .045       0  4978.4    .035       0  4984.3    .045       0
    5020     .05       0  5560.1    .045       0
Bank Sta=4978.4,4984.3
XS Rating Curve= 0 ,0
Exp/Cntr=0.3,0.1

Type RM Length L Ch R = 1 ,52604   ,282,282,282
BEGIN DESCRIPTION:
Mapping XS 9e52b7cb
END DESCRIPTION:
XS GIS Cut Line= 3
      1532787.04      6899428.05       1532956.6      6897591.86
        1532630.      6896862.99
#Sta/Elev= 30
    3156 1766.75  3206.3 1765.33  3513.5 1764.79  3587.9 1763.97  3623.1 1765.45
  3658.2 1763.95  3828.9 1764.43  4310.9 1763.53  4411.4  1764.3  4421.4 1763.53
  4451.5  1763.2  4714.2 1762.54  4843.2 1763.02  4996.5 1761.91  4996.9 1761.41
  5002.4 1761.91  5093.4 1762.01  5135.6 1762.77  5201.5    1764  5223.4 1763.56
  5232.5 1764.48  5255.7 1764.25  5365.8 1766.93  5388.1 1766.05  5405.8 1766.63
  5409.9 1766.06  5497.3 1766.16  5527.2 1767.43  5664.6 1766.12  5798.7 1766.48
#Mann= 6 ,-1 , 0
    3156    .045       0  4996.5    .035       0  5002.4    .045       0
  5135.6     .07       0  5409.9     .05       0  5664.6    .035       0
Bank Sta=4996.5,5002.4
XS Rating Curve= 0 ,0
Exp/Cntr=0.3,0.1

Type RM Length L Ch R = 1 ,52322   ,862,862,862
BEGIN DESCRIPTION:
Mapping XS 137cfe53
END DESCRIPTION:
XS GIS Cut Line= 3
      1533321.01      6898381.54      1533185.16      6897446.83
       1532808.8      6897089.94
#Sta/Elev= 30
  4064.8 1764.13  4072.6 1764.18  4078.5  1764.7  4088.6  1763.9    4125 1763.96
  4169.4 1763.58  4179.5 1764.14  4230.1 1763.17  4371.5 1763.51  4472.6 1762.61
  4628.6 1762.53    4705 1761.99  4917.2 1762.33  4957.6 1762.13  4976.1 1761.57
  4976.6 1761.07  4981.9 1761.07  4982.4 1761.57  5164.1 1763.24  5171.4  1763.6
  5192.4  1763.4  5263.2 1763.86  5270.5 1764.21  5355.4 1764.43    5419 1764.99
  5433.1 1765.99  5447.3 1765.85  5468.3 1767.32  5510.8 1767.99    5528 1767.81
#Mann= 5 ,-1 , 0
  4064.8     .07       0    4125    .045       0  4976.1    .035       0
  4982.4    .045       0  5355.4     .05       0
Bank Sta=4976.1,4982.4
XS Rating Curve= 0 ,0
Exp/Cntr=0.3,0.1

Type RM Length L Ch R = 1 ,51460   ,303,303,303
BEGIN DESCRIPTION:
Mapping XS 11fb5c2a
END DESCRIPTION:
XS GIS Cut Line= 3
      1533779.98      6897362.97      1533531.14      6896961.07
      1532789.56      6897066.91
#Sta/Elev= 30
  4527.3 1763.79  4556.7 1763.67  4585.2 1762.88  4643.1 1762.02    4686 1761.98
  4722.2 1761.54  4810.9 1761.95  4816.8 1761.74  4956.6 1762.02  4988.7 1761.36
  4989.2 1760.86  4994.5 1760.86    4995 1761.36  5006.2  1761.6  5127.4 1762.09
  5359.8 1762.77  5400.2 1763.03  5410.3  1763.5  5420.4 1762.94  5450.7 1763.04
  5521.4 1763.84  5578.4 1764.86  5598.5 1764.87  5632.5 1765.28  5642.6 1766.21
  5662.8 1766.51  5672.9 1767.48    5683 1768.05  5719.9 1767.53  5749.1 1767.57
#Mann= 4 ,-1 , 0
  4527.3    .045       0  4988.7    .035       0    4995    .045       0
  5598.5     .05       0
Bank Sta=4988.7,4995
XS Rating Curve= 0 ,0
Exp/Cntr=0.3,0.1

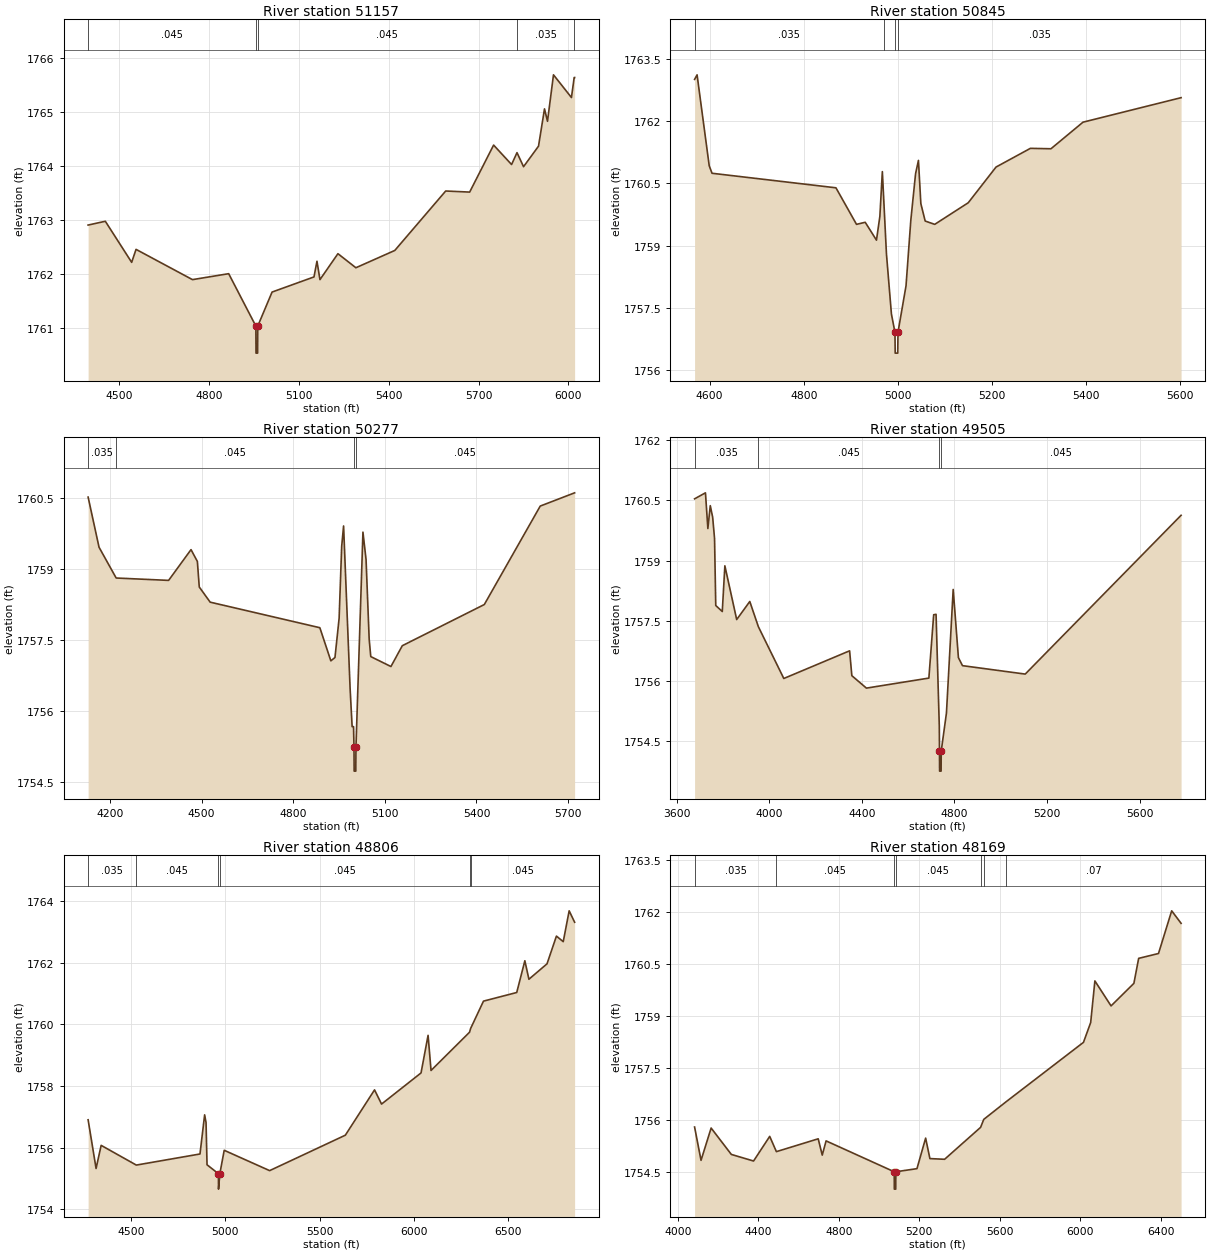
Type RM Length L Ch R = 1 ,51157   ,312,312,312
BEGIN DESCRIPTION:
Mapping XS 1096873a
END DESCRIPTION:
XS GIS Cut Line= 3
        1534030.        6897263.      1533704.75      6896753.22
      1532684.42      6896771.35
#Sta/Elev= 30
  4395.3 1762.91  4452.8 1762.98  4540.8 1762.22  4555.4 1762.46  4743.9  1761.9
  4864.9 1762.01  4955.7 1761.04  4956.2 1760.54  4961.5 1760.54    4962 1761.04
  5009.8 1761.67  5149.8 1761.95  5159.8 1762.24  5169.8  1761.9  5229.8 1762.38
  5289.8 1762.12  5419.8 1762.44  5589.8 1763.54  5669.9 1763.52  5749.9 1764.39
  5809.9 1764.03    5828 1764.25  5849.9 1763.99  5899.9 1764.37  5919.9 1765.06
  5929.9 1764.83  5949.9 1765.69  6009.9 1765.27    6019 1765.64  6020.5 1765.64
#Mann= 5 ,-1 , 0
  4395.3    .045       0  4955.7    .035       0    4962    .045       0
    5828    .035       0    6019    .045       0
Bank Sta=4955.7,4962
XS Rating Curve= 0 ,0
Exp/Cntr=0.3,0.1

Type RM Length L Ch R = 1 ,50845   ,568,568,568
BEGIN DESCRIPTION:
Mapping XS 9d299124
END DESCRIPTION:
XS GIS Cut Line= 3
      1534130.03      6896663.01      1533722.03      6896521.02
        1533130.        6896413.
#Sta/Elev= 30
    4568    1763  4573.3 1763.11  4599.1 1760.92  4605.1 1760.74  4868.4 1760.39
  4912.1 1759.51  4930.6 1759.56  4954.5 1759.13  4961.7  1759.7    4967 1760.78
  4969.9 1760.12  4975.7  1758.8  4986.3 1757.35  4993.8 1756.91  4994.3 1756.41
  4999.7 1756.41  5000.2 1756.91  5017.3 1758.03  5027.5 1759.61  5037.6 1760.73
  5043.7 1761.05  5048.8 1760.01    5058 1759.59  5078.3 1759.51  5149.5 1760.03
  5208.6 1760.89  5281.6 1761.34  5325.3 1761.33  5393.4 1761.97  5601.8 1762.56
#Mann= 4 ,-1 , 0
    4568    .035       0  4969.9    .045       0  4993.8    .035       0
  5000.2    .035       0
Bank Sta=4993.8,5000.2
XS Rating Curve= 0 ,0
Exp/Cntr=0.3,0.1

Type RM Length L Ch R = 1 ,50277   ,772,772,772
BEGIN DESCRIPTION:
Mapping XS 71043dae
END DESCRIPTION:
XS GIS Cut Line= 3
      1534667.72      6896544.98      1533969.22      6896034.56
      1533254.51      6895895.67
#Sta/Elev= 30
  4128.2 1760.52    4164 1759.46  4220.1 1758.81  4391.8 1758.76  4465.2 1759.41
    4486 1759.16  4492.2 1758.62  4527.9  1758.3  4887.1 1757.76  4923.1 1757.06
  4936.6 1757.13  4950.2 1757.96  4958.6 1759.48  4964.8 1759.91  4986.2 1756.47
  4992.8 1755.67  4997.4 1755.67  4998.9 1755.23  4999.4 1754.73  5004.8 1754.73
  5005.3 1755.23  5028.2 1759.78  5038.4  1759.2  5048.6 1757.52  5053.8 1757.15
  5119.9 1756.94  5157.1 1757.38  5425.7 1758.25  5608.8 1760.33  5721.4 1760.61
#Mann= 4 ,-1 , 0
  4128.2    .035       0  4220.1    .045       0  4998.9    .045       0
  5005.3    .045       0
Bank Sta=4998.9,5005.3
XS Rating Curve= 0 ,0
Exp/Cntr=0.3,0.1

Type RM Length L Ch R = 1 ,49505   ,699,699,699
BEGIN DESCRIPTION:
Mapping XS 279e3b73
END DESCRIPTION:
XS GIS Cut Line= 3
      1534714.01       6896503.3      1534427.55      6895477.26
       1533424.7      6895211.66
#Sta/Elev= 30
  3676.9 1760.54  3723.9 1760.69  3734.3  1759.8  3744.7 1760.37  3755.1 1760.08
  3763.2 1759.55  3768.4 1757.88  3796.6 1757.73  3807.8 1758.87  3858.9 1757.53
  3915.5 1757.98  3952.7 1757.35  4062.5 1756.06  4346.9 1756.75  4356.6 1756.13
  4419.6 1755.82  4689.5 1756.07  4710.3 1757.65  4720.6 1757.66  4734.6 1754.86
  4735.4 1754.25  4735.9 1753.75  4742.4 1753.75  4742.9 1754.25  4765.5  1755.2
  4794.6 1758.28  4817.2 1756.58  4834.8 1756.38    5106 1756.17  5779.6 1760.13
#Mann= 4 ,-1 , 0
  3676.9    .035       0  3952.7    .045       0  4735.4    .045       0
  4742.9    .045       0
Bank Sta=4735.4,4742.9
XS Rating Curve= 0 ,0
Exp/Cntr=0.3,0.1

Type RM Length L Ch R = 1 ,48806   ,637,637,637
BEGIN DESCRIPTION:
Mapping XS e098066d
END DESCRIPTION:
XS GIS Cut Line= 3
      1534852.14       6895805.7      1534628.61      6895111.24
      1533031.75      6894180.41
#Sta/Elev= 30
  4273.1  1756.9  4315.3 1755.32  4342.2 1756.07  4528.6 1755.43  4865.9 1755.79
  4890.5 1757.06    4898 1756.81  4903.2 1755.44  4963.6 1755.15  4964.1 1754.65
  4971.1 1755.15  4994.2 1755.91    5235 1755.25  5636.1  1756.4  5790.8 1757.87
    5828 1757.41  6037.2 1758.42  6074.5 1759.64  6090.2  1758.5  6294.1 1759.74
  6299.8 1759.86  6368.1 1760.75  6544.3 1761.03  6587.3 1762.06  6608.8 1761.46
  6704.7 1761.96  6754.6 1762.86  6790.7 1762.68  6822.1 1763.68    6851 1763.31
#Mann= 6 ,-1 , 0
  4273.1    .035       0  4528.6    .045       0  4963.6    .045       0
  4971.1    .045       0  6294.1     .07       0  6299.8    .045       0
Bank Sta=4963.6,4971.1
XS Rating Curve= 0 ,0
Exp/Cntr=0.3,0.1

Type RM Length L Ch R = 1 ,48169   ,300,300,300
BEGIN DESCRIPTION:
Mapping XS ec802e79
END DESCRIPTION:
XS GIS Cut Line= 4
      1534899.56      6895549.98       1534817.1      6894642.89
       1534591.4      6894282.64      1533701.65      6893666.33
#Sta/Elev= 30
  4083.4  1755.8  4115.5 1754.84  4165.7 1755.77  4266.1 1755.01  4376.6 1754.82
  4456.9 1755.53    4490 1755.09  4697.9 1755.46    4718 1754.99  4737.1  1755.4
  5075.8 1754.51  5076.3 1754.01  5083.3 1754.01  5083.8 1754.51  5188.8  1754.6
  5231.9 1755.48  5253.1 1754.89  5326.2 1754.87  5505.1 1755.79  5520.9 1756.02
  5630.1 1756.52  6016.5 1758.24  6052.3 1758.81  6073.2 1760.01  6153.6 1759.29
  6267.1 1759.94  6290.8 1760.66  6389.4  1760.8    6455 1762.03  6501.7 1761.67
#Mann= 7 ,-1 , 0
  4083.4    .035       0    4490    .045       0  5075.8    .045       0
  5083.8    .045       0  5505.1     .07       0  5520.9    .045       0
  5630.1     .07       0
Bank Sta=5075.8,5083.8
XS Rating Curve= 0 ,0
Exp/Cntr=0.3,0.1

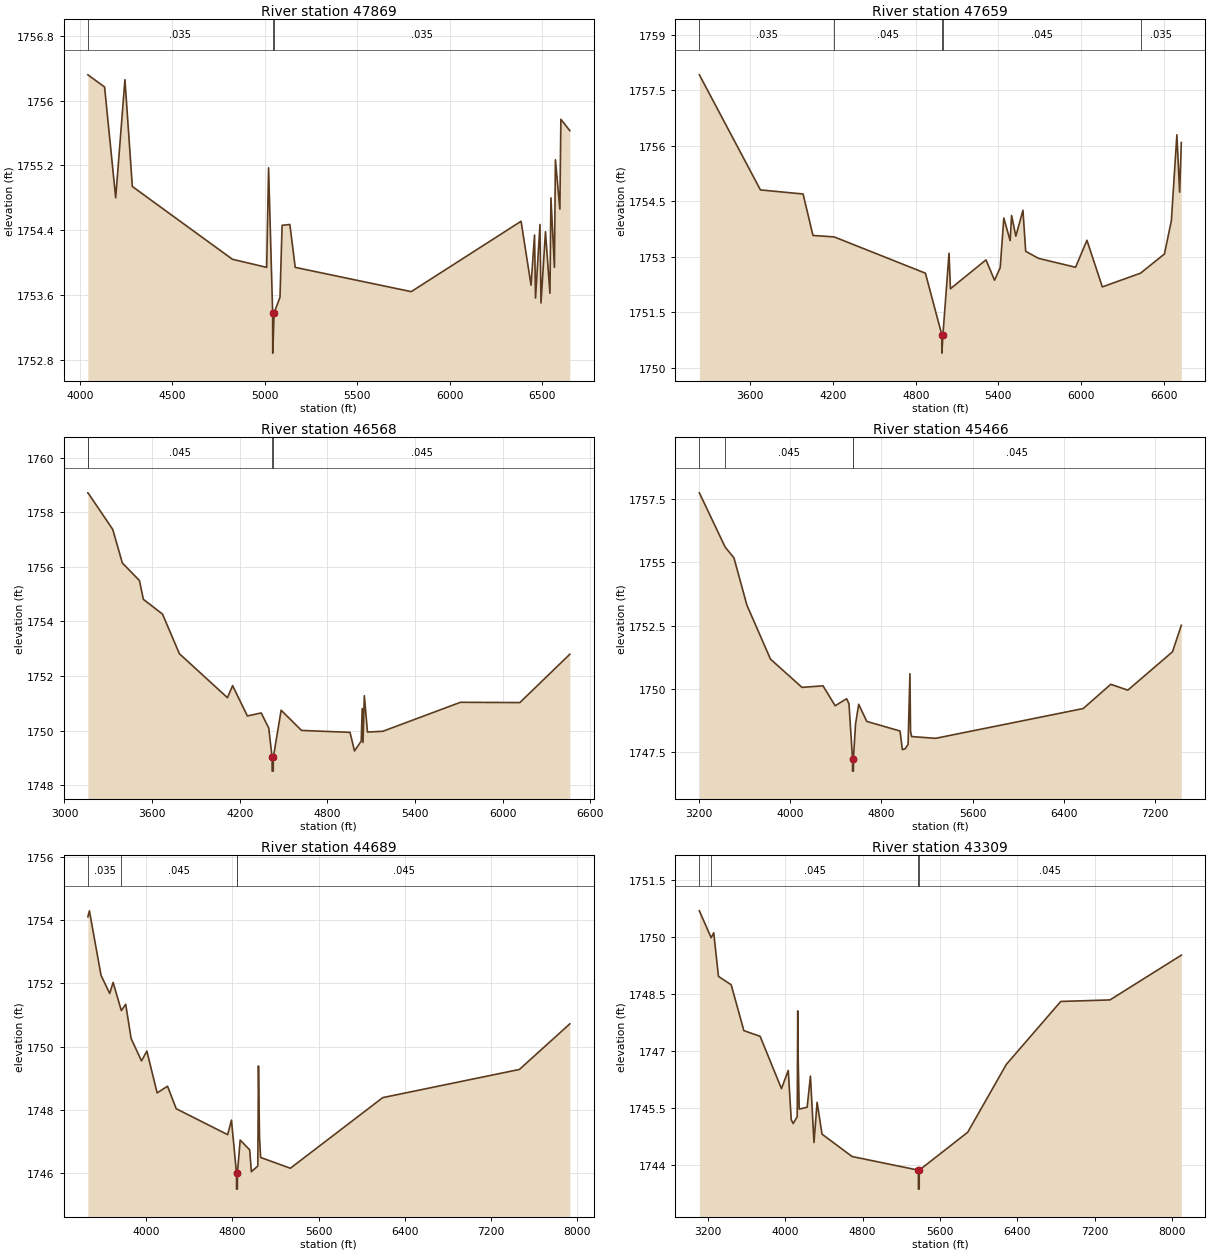
Type RM Length L Ch R = 1 ,47869   ,210,210,210
BEGIN DESCRIPTION:
Mapping XS d51450ee
END DESCRIPTION:
XS GIS Cut Line= 4
      1534920.02      6895528.16      1534934.28       6895150.7
      1535359.63      6893375.53      1535509.62      6893002.07
#Sta/Elev= 30
  4043.9 1756.32  4134.1 1756.17  4194.2  1754.8  4244.2 1756.26  4284.2 1754.94
  4825.4 1754.04  5010.5 1753.94  5020.8 1755.17  5042.8 1753.38  5043.3 1752.88
  5050.8 1753.38  5082.5 1753.57  5093.9 1754.46  5135.9 1754.47  5164.8 1753.94
  5792.1 1753.64    6386 1754.51  6439.8 1753.72  6458.6 1754.34    6464 1753.56
  6488.2 1754.47  6493.6  1753.5  6517.8 1754.38    6542 1753.62  6547.4  1754.8
  6566.2 1753.94  6571.5 1755.27  6595.7 1754.66  6601.1 1755.77  6649.5 1755.63
#Mann= 3 ,-1 , 0
  4043.9    .035       0  5042.8    .035       0  5050.8    .035       0
Bank Sta=5042.8,5050.8
XS Rating Curve= 0 ,0
Exp/Cntr=0.3,0.1

Type RM Length L Ch R = 1 ,47659   ,1091,1091,1091
BEGIN DESCRIPTION:
Mapping XS a66b6e75
END DESCRIPTION:
XS GIS Cut Line= 4
      1534765.34      6896392.31      1535074.47      6895350.31
      1535511.19      6893625.82      1535547.91       6892995.9
#Sta/Elev= 30
  3230.4 1757.92  3673.4 1754.81  3982.9  1754.7  4054.6 1753.58    4209 1753.54
  4870.5 1752.56  4989.3  1750.9  4989.8  1750.4  4997.6  1750.9  5041.8  1753.1
  5052.1 1752.14    5310 1752.92  5371.9 1752.37  5413.1 1752.71  5439.3 1754.05
  5485.4 1753.44  5495.7 1754.12  5526.6 1753.56  5578.2 1754.26  5598.1 1753.15
  5691.7 1752.96  5959.9 1752.72  6042.4 1753.45  6154.1 1752.19  6431.2 1752.56
  6604.9 1753.08    6655 1753.98    6695  1756.3  6715.1 1754.75  6727.2 1756.09
#Mann= 5 ,-1 , 0
  3230.4    .035       0    4209    .045       0  4989.3    .045       0
  4997.6    .045       0  6431.2    .035       0
Bank Sta=4989.3,4997.6
XS Rating Curve= 0 ,0
Exp/Cntr=0.3,0.1

Type RM Length L Ch R = 1 ,46568   ,1102,1102,1102
BEGIN DESCRIPTION:
Mapping XS d2bcb74e
END DESCRIPTION:
XS GIS Cut Line= 3
      1535190.34      6896708.19      1536164.31      6895150.88
      1535675.16      6893771.87
#Sta/Elev= 30
  3160.4 1758.71  3161.1 1758.71  3330.6 1757.37  3396.5 1756.14  3513.3  1755.5
  3540.4 1754.81  3671.3 1754.27  3786.9 1752.82  4115.8 1751.21  4151.4 1751.65
  4252.6 1750.54  4346.9 1750.65  4398.8  1750.1  4421.8 1749.02  4422.3 1748.52
  4429.6 1748.52  4430.1 1749.02  4483.7 1750.75  4623.2 1750.01  4955.3 1749.94
    4986 1749.26  5032.1 1749.62  5038.7 1750.81    5044 1749.57  5053.3 1751.28
  5074.9 1749.95  5180.6 1749.98  5711.2 1751.04  6118.3 1751.03  6460.4  1752.8
#Mann= 4 ,-1 , 0
  3160.4    .035       0  3161.1    .045       0  4421.8    .045       0
  4430.1    .045       0
Bank Sta=4421.8,4430.1
XS Rating Curve= 0 ,0
Exp/Cntr=0.3,0.1

Type RM Length L Ch R = 1 ,45466   ,777,777,777
BEGIN DESCRIPTION:
Mapping XS 3f95070b
END DESCRIPTION:
XS GIS Cut Line= 4
      1535894.63      6897104.88      1537044.81      6895742.02
      1537114.26      6895464.24      1535782.34      6893772.24
#Sta/Elev= 30
  3204.8 1757.76  3430.7 1755.61    3508 1755.18  3621.1 1753.31  3827.8 1751.17
  4103.6 1750.05  4288.1 1750.11  4394.8 1749.32  4494.8  1749.6  4515.7  1749.4
  4546.6 1747.23  4547.1 1746.73  4554.5 1746.73    4555 1747.23  4572.8 1748.58
  4600.8 1749.38  4671.7  1748.7  4962.9 1748.32  4983.8 1747.58  5008.6 1747.62
  5033.5 1747.79  5049.9 1750.59    5055 1748.32  5064.4  1748.1  5274.5 1748.03
  6567.8 1749.21  6809.6 1750.17  6959.3 1749.94  7350.6 1751.46  7427.8 1752.51
#Mann= 4 ,-1 , 0
  3204.8    .035       0  3430.7    .045       0  4546.6    .045       0
    4555    .045       0
Bank Sta=4546.6,4555
XS Rating Curve= 0 ,0
Exp/Cntr=0.3,0.1

Type RM Length L Ch R = 1 ,44689   ,1380,1380,1380
BEGIN DESCRIPTION:
Mapping XS 68c88b9c
END DESCRIPTION:
XS GIS Cut Line= 4
      1536911.15      6897472.02      1537687.17       6896123.1
      1537734.05      6895821.01      1535984.03      6893888.71
#Sta/Elev= 30
  3460.8  1754.1  3474.9 1754.29  3582.7 1752.25  3663.2 1751.68  3694.8 1752.03
  3770.8 1751.14  3811.5 1751.34  3861.5 1750.26  3957.8 1749.55  4007.7 1749.86
    4103 1748.54  4199.3 1748.75  4279.7 1748.04  4756.9 1747.22  4792.2 1747.68
  4838.9    1746  4839.4  1745.5  4846.8  1745.5  4847.3    1746  4872.9 1747.05
    4961 1746.74  4976.8 1746.05  5036.4 1746.23  5042.4 1749.39  5052.5 1747.11
  5062.7  1746.5  5338.6 1746.16  6194.9 1748.39  7462.1 1749.28  7929.7 1750.72
#Mann= 4 ,-1 , 0
  3460.8    .035       0  3770.8    .045       0  4838.9    .045       0
  4847.3    .045       0
Bank Sta=4838.9,4847.3
XS Rating Curve= 0 ,0
Exp/Cntr=0.3,0.1

Type RM Length L Ch R = 1 ,43309   ,406,406,406
BEGIN DESCRIPTION:
Mapping XS f558ea48
END DESCRIPTION:
XS GIS Cut Line= 4
      1538363.39      6897672.55      1538788.73      6895893.06
      1538641.17      6895567.54      1536284.36       6894057.1
#Sta/Elev= 30
  3110.8  1750.7  3232.7 1749.99  3259.4 1750.12  3308.5 1748.97  3439.8 1748.75
  3571.2 1747.54  3739.5 1747.39  3960.1 1746.01  4030.5 1746.49  4061.4 1745.19
  4081.2 1745.09  4123.1 1745.27  4128.4 1748.06  4133.5 1746.75  4143.6 1745.47
  4225.9 1745.52  4259.8 1746.34  4296.7 1744.59  4328.7 1745.65  4380.1 1744.81
  4690.7 1744.22  5376.9 1743.86  5377.4 1743.36  5385.3 1743.36  5385.8 1743.86
  5887.1 1744.86  6286.8 1746.65  6849.8 1748.31  7358.7 1748.35  8097.1 1749.53
#Mann= 4 ,-1 , 0
  3110.8    .035       0  3232.7    .045       0  5376.9    .045       0
  5385.8    .045       0
Bank Sta=5376.9,5385.8
XS Rating Curve= 0 ,0
Exp/Cntr=0.3,0.1