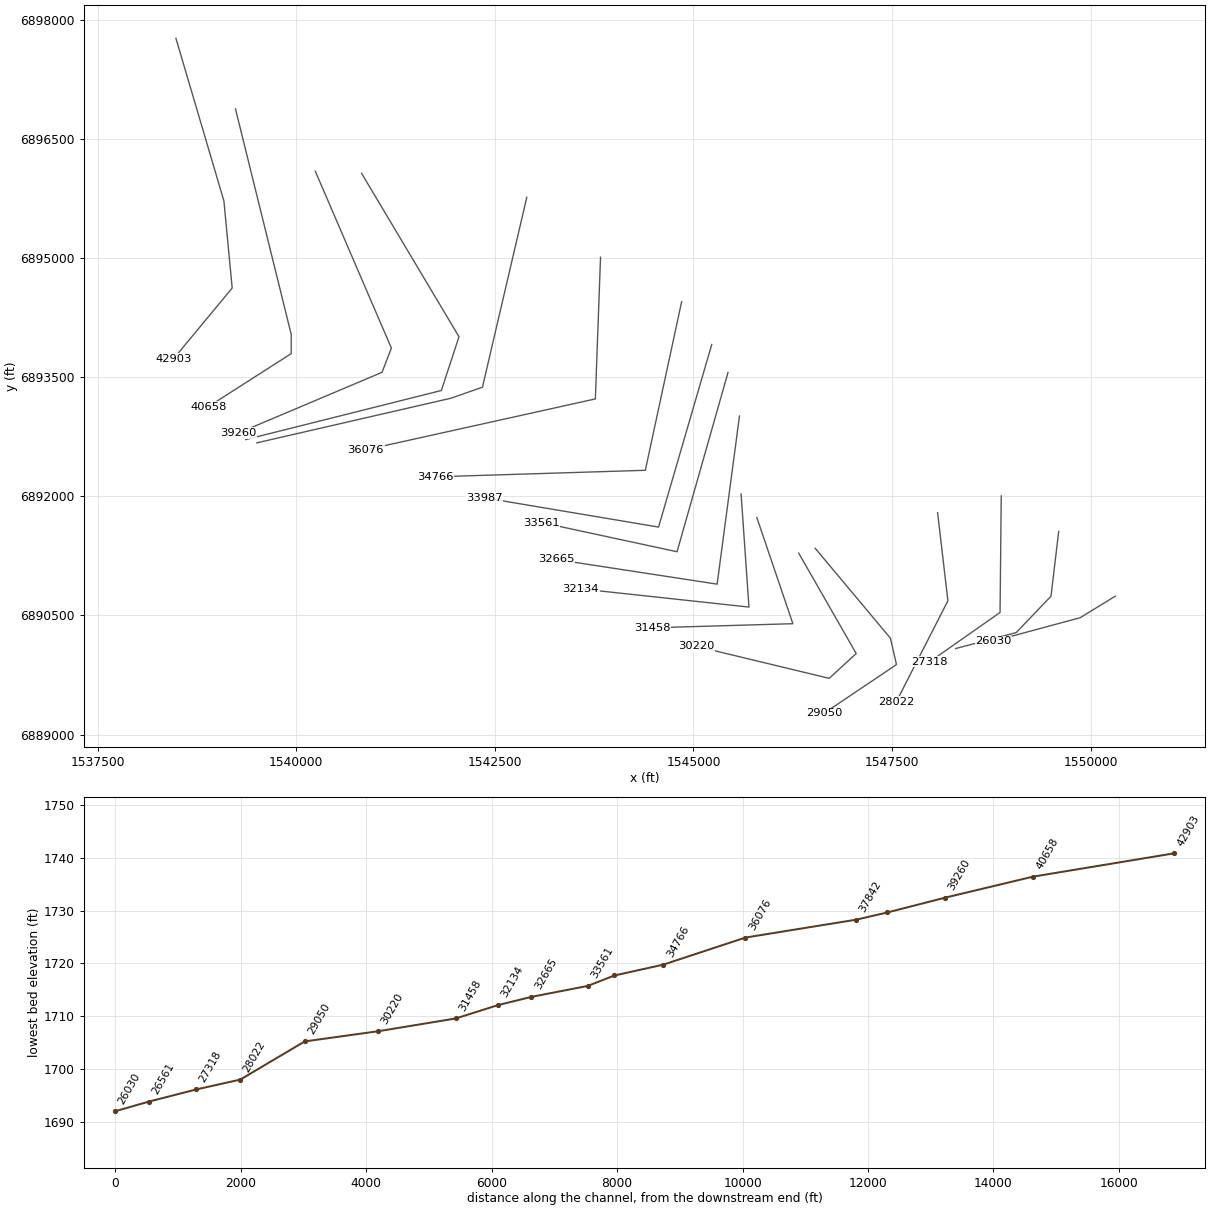
HEC-RAS study MULBERRY CREEK TRIBUTARY 6.prj: MULBERRY CREEK TRIBUTARY 6 Base Level Engineering

--- MULBERRY CREEK TRIBUTARY 6.g01 (geometry) --- (continued)

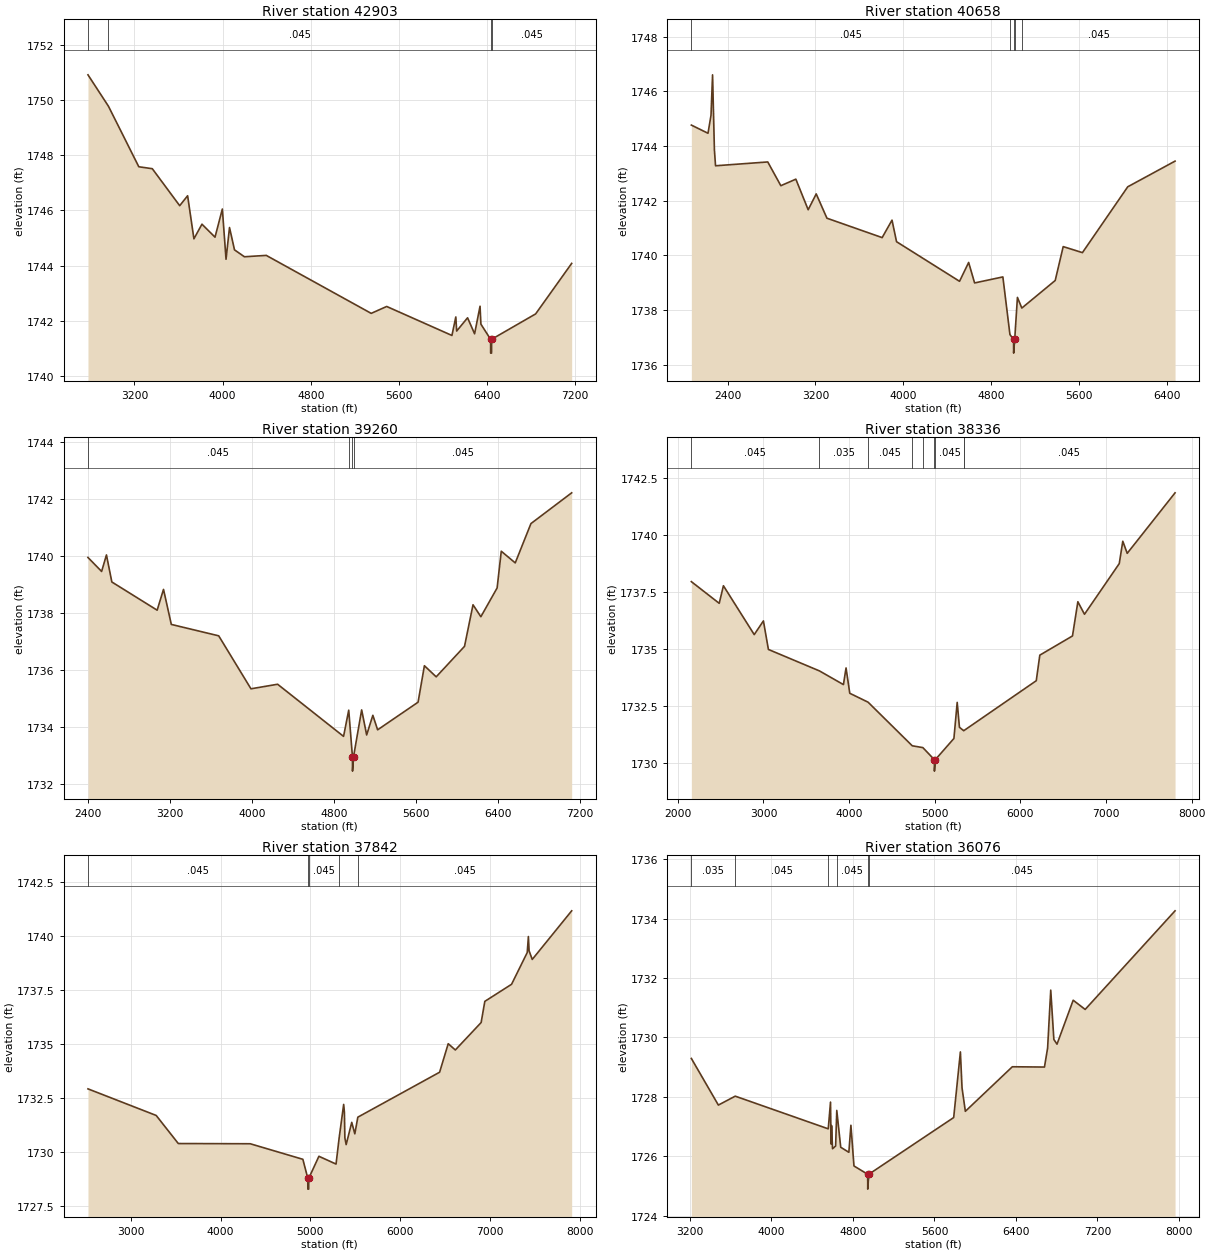
Type RM Length L Ch R = 1 ,42903   ,2245,2245,2245
BEGIN DESCRIPTION:
Mapping XS 40ea1396
END DESCRIPTION:
XS GIS Cut Line= 4
      1538484.04       6897770.7      1539088.21      6895722.06
      1539192.38      6894624.83      1538456.24      6893735.91
#Sta/Elev= 30
  2777.7 1750.91    2964 1749.77  3239.3 1747.58  3361.8 1747.51  3610.6 1746.17
  3682.5 1746.53  3739.7 1744.97  3812.7  1745.5  3931.3 1745.03  3997.9 1746.05
  4031.3 1744.23  4062.9 1745.38  4108.3 1744.57  4198.4 1744.32  4396.5 1744.37
  5349.6 1742.27  5490.2 1742.52  6082.6 1741.47  6117.8 1742.14  6125.6 1741.63
  6224.6 1742.11  6288.4 1741.53  6337.9 1742.53  6345.7 1741.88  6433.7 1741.33
  6434.2 1740.83  6442.1 1740.83  6442.6 1741.33  6842.6 1742.25  7169.9 1744.08
#Mann= 4 ,-1 , 0
  2777.7    .035       0    2964    .045       0  6433.7    .045       0
  6442.6    .045       0
Bank Sta=6433.7,6442.6
XS Rating Curve= 0 ,0
Exp/Cntr=0.3,0.1

Type RM Length L Ch R = 1 ,40658   ,1398,1398,1398
BEGIN DESCRIPTION:
Mapping XS eb68f378
END DESCRIPTION:
XS GIS Cut Line= 4
      1539234.04      6896881.79      1539935.44       6894041.5
      1539935.44      6893798.44       1538894.7      6893132.37
#Sta/Elev= 30
  2070.8 1744.77  2222.4 1744.47  2249.8 1745.13  2263.9 1746.61  2280.7 1743.86
    2291 1743.28  2766.5 1743.42  2885.7 1742.55  3022.3 1742.79  3134.5 1741.67
  3207.7 1742.25  3305.4 1741.36  3808.1 1740.65  3897.9 1741.29  3939.1  1740.5
  4512.8 1739.05  4595.7 1739.74  4649.8 1738.99  4907.3 1739.21  4971.7  1737.1
  5004.8 1736.92  5005.3 1736.42    5015 1736.92  5039.9 1738.46    5080 1738.07
  5383.9 1739.08  5456.6 1740.32  5631.8  1740.1  6044.3 1742.51  6475.1 1743.45
#Mann= 5 ,-1 , 0
  2070.8    .045       0  4971.7     .07       0  5004.8    .045       0
    5015     .07       0    5080    .045       0
Bank Sta=5004.8,5015
XS Rating Curve= 0 ,0
Exp/Cntr=0.3,0.1

Type RM Length L Ch R = 1 ,39260   ,924,924,924
BEGIN DESCRIPTION:
Mapping XS 1587644d
END DESCRIPTION:
XS GIS Cut Line= 4
      1540238.41      6896097.45      1541196.72      6893868.32
      1541078.67      6893562.77      1539273.07      6892798.86
#Sta/Elev= 30
  2402.1 1739.95  2535.1 1739.46  2582.2 1740.04  2634.8 1739.09  3076.4  1738.1
  3138.3 1738.83  3214.4  1737.6  3676.3  1737.2  3990.7 1735.34  4250.5  1735.5
  4893.2 1733.67  4943.6 1734.59    4980 1732.95  4980.5 1732.45  4990.2 1732.95
  5069.6  1734.6  5118.3 1733.72  5178.7 1734.41  5225.2  1733.9  5619.5 1734.87
  5681.2 1736.15  5796.2 1735.76  6072.1 1736.83    6155 1738.29  6231.5 1737.87
  6389.9 1738.88  6430.4 1740.17  6566.6 1739.76  6719.6 1741.14  7116.6 1742.22
#Mann= 4 ,-1 , 0
  2402.1    .045       0  4943.6     .07       0    4980    .045       0
  4990.2    .045       0
Bank Sta=4980,4990.2
XS Rating Curve= 0 ,0
Exp/Cntr=0.3,0.1

Type RM Length L Ch R = 1 ,38336   ,494,494,494
BEGIN DESCRIPTION:
Mapping XS 6c3a1244
END DESCRIPTION:
XS GIS Cut Line= 4
      1540821.75      6896069.67      1542048.17      6894011.27
      1541825.95      6893334.18      1539363.35      6892715.54
#Sta/Elev= 30
  2158.5 1737.94  2483.9 1736.99  2532.9 1737.76  2892.7 1735.62  2999.8 1736.22
  3058.2 1734.97    3654 1734.03  3934.3 1733.43  3964.7 1734.16  4008.3 1733.05
    4222 1732.66  4737.6 1730.75  4861.7 1730.67  4996.3 1730.14  4996.8 1729.64
  5006.6 1730.14  5224.2 1731.07  5262.5 1732.65  5288.8 1731.56  5338.4 1731.41
  5338.8 1731.41  6185.8  1733.6  6227.1 1734.72  6608.6 1735.56  6671.5 1737.06
  6748.7 1736.51  7154.9 1738.73  7196.1 1739.71  7247.8 1739.18  7806.3 1741.83
#Mann= 9 ,-1 , 0
  2158.5    .045       0    3654    .035       0    4222    .045       0
  4737.6    .035       0  4861.7    .045       0  4996.3    .035       0
  5006.6    .045       0  5338.4     .07       0  5338.8    .045       0
Bank Sta=4996.3,5006.6
XS Rating Curve= 0 ,0
Exp/Cntr=0.3,0.1

Type RM Length L Ch R = 1 ,37842   ,1766,1766,1766
BEGIN DESCRIPTION:
Mapping XS 45df2eb2
END DESCRIPTION:
XS GIS Cut Line= 4
      1542901.53      6895766.95      1542343.31      6893375.85
      1541947.48      6893236.96      1539503.05      6892674.47
#Sta/Elev= 30
  2524.4 1732.92  3283.6 1731.69  3529.7 1730.39    4330 1730.38    4916 1729.66
  4970.9 1728.78  4971.4 1728.28  4980.9 1728.28  4981.4 1728.78  5094.6  1729.8
  5285.2 1729.44  5319.5 1730.64  5370.1  1732.2  5378.2 1731.84  5383.5 1730.65
  5397.9 1730.34  5459.9 1731.37  5494.2 1730.84  5527.7 1731.61  6437.8 1733.69
  6533.7 1735.01  6612.7 1734.72    6900 1735.99    6941 1736.97  7238.6 1737.76
  7413.1 1739.23    7426 1739.97  7433.6 1739.31  7468.8 1738.91  7907.6 1741.16
#Mann= 5 ,-1 , 0
  2524.4    .045       0  4970.9    .035       0  4981.4    .045       0
  5319.5     .07       0  5527.7    .045       0
Bank Sta=4970.9,4981.4
XS Rating Curve= 0 ,0
Exp/Cntr=0.3,0.1

Type RM Length L Ch R = 1 ,36076   ,1310,1310,1310
BEGIN DESCRIPTION:
Mapping XS 2d01445b
END DESCRIPTION:
XS GIS Cut Line= 3
        1543830.      6895013.01      1543764.87       6893227.9
      1540873.79       6892586.4
#Sta/Elev= 30
  3213.7 1729.29  3478.9 1727.72  3644.4 1728.02  4557.3 1726.92  4579.6 1727.82
  4584.8 1726.41  4589.8 1727.03  4599.6 1726.25  4629.7 1726.34  4641.1 1727.54
  4679.7  1726.3  4759.7 1726.13  4779.8 1727.04  4809.8 1725.67  4944.5 1725.39
    4945 1724.89  4955.3 1725.39  5788.6  1727.3  5854.4 1729.51  5870.5  1728.3
  5903.1 1727.51  6364.3 1729.01  6679.6    1729  6710.5 1729.64  6741.2 1731.59
  6771.8 1729.93  6802.7 1729.77  6961.5 1731.25  7079.2 1730.94  7961.4 1734.26
#Mann= 6 ,-1 , 0
  3213.7    .035       0  3644.4    .045       0  4557.3     .07       0
  4641.1    .045       0  4944.5    .035       0  4955.3    .045       0
Bank Sta=4944.5,4955.3
XS Rating Curve= 0 ,0
Exp/Cntr=0.3,0.1

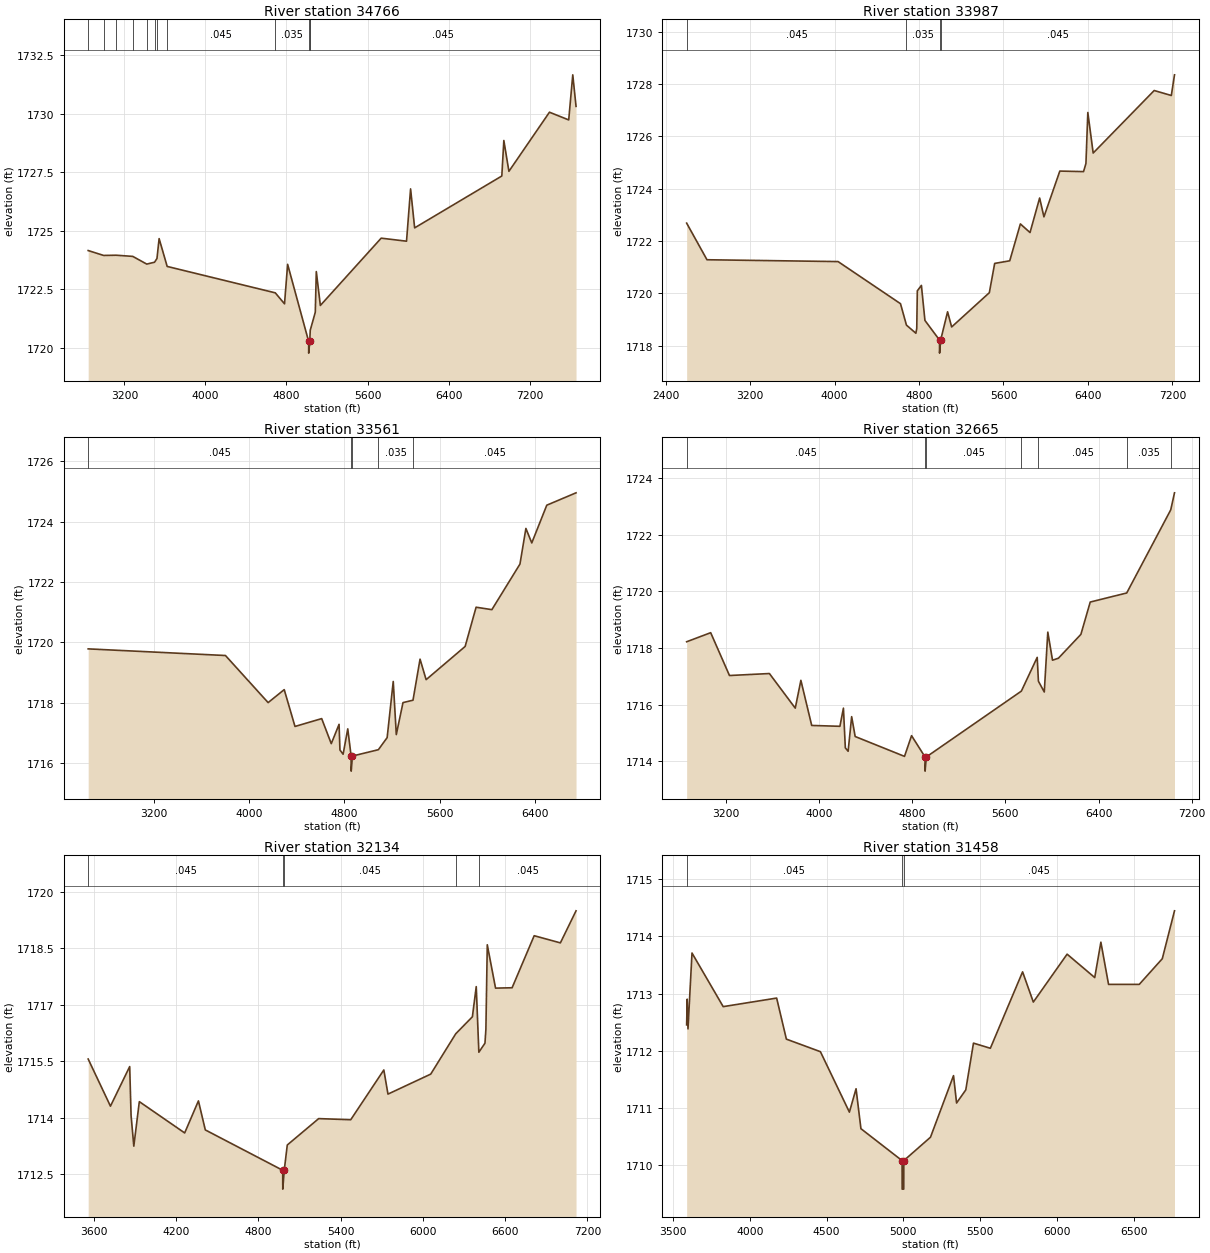
Type RM Length L Ch R = 1 ,34766   ,779,779,779
BEGIN DESCRIPTION:
Mapping XS 8d0da3b3
END DESCRIPTION:
XS GIS Cut Line= 3
      1544850.97       6894452.4      1544394.06      6892328.69
      1541752.84      6892246.63
#Sta/Elev= 30
  2842.8 1724.15  2995.7 1723.94  3118.7 1723.95  3282.9  1723.9  3420.9 1723.57
  3497.6 1723.65  3521.7 1723.81  3542.9 1724.66  3622.4 1723.47  4689.3 1722.34
  4780.5 1721.87  4811.2 1723.56  5018.7 1720.26  5019.2 1719.76  5029.6 1720.26
  5034.4 1720.74  5084.2 1721.51  5094.2 1723.25  5134.2  1721.8  5734.5 1724.68
  5984.6 1724.55  6024.7 1726.79  6064.7 1725.12  6925.1 1727.34  6945.1 1728.86
  6995.1 1727.54  7395.3 1730.07  7585.4 1729.74  7625.4 1731.67  7657.6 1730.32
#Mann= 12 ,-1 , 0
  2842.8     .05       0  2995.7    .045       0  3118.7     .07       0
  3282.9     .05       0  3420.9    .035       0  3497.6    .045       0
  3521.7    .035       0  3622.4    .045       0  4689.3    .035       0
  5018.7    .035       0  5029.6    .035       0  5034.4    .045       0
Bank Sta=5018.7,5029.6
XS Rating Curve= 0 ,0
Exp/Cntr=0.3,0.1

Type RM Length L Ch R = 1 ,33987   ,426,426,426
BEGIN DESCRIPTION:
Mapping XS 085aa905
END DESCRIPTION:
XS GIS Cut Line= 3
      1545229.99      6893912.98      1544560.73      6891613.41
      1542365.32      6891982.52
#Sta/Elev= 30
    2599 1722.68  2791.7 1721.28  4033.3 1721.21  4624.7  1719.6  4681.2 1718.78
  4770.5 1718.47  4778.8 1718.66    4784 1720.09  4822.7  1720.3  4856.2 1718.96
  4994.3 1718.21  4994.8 1717.71  5005.2 1718.21  5070.8 1719.29  5109.2 1718.71
  5466.2 1720.02  5516.9 1721.14  5659.5 1721.24  5760.3 1722.65  5851.6 1722.32
  5942.8 1723.64  5983.4 1722.92  6133.9 1724.67  6358.6 1724.65  6381.3 1724.96
  6399.2 1726.91  6449.9 1725.36  7027.9 1727.75  7190.1 1727.56  7220.2 1728.35
#Mann= 4 ,-1 , 0
    2599    .045       0  4681.2    .035       0  4994.3    .035       0
  5005.2    .045       0
Bank Sta=4994.3,5005.2
XS Rating Curve= 0 ,0
Exp/Cntr=0.3,0.1

Type RM Length L Ch R = 1 ,33561   ,896,896,896
BEGIN DESCRIPTION:
Mapping XS c5c24787
END DESCRIPTION:
XS GIS Cut Line= 3
      1545435.16      6893561.09      1544793.37      6891302.65
      1543084.87       6891670.9
#Sta/Elev= 30
  2649.2 1719.78  3801.7 1719.56  4159.8    1718    4295 1718.43  4385.4 1717.21
  4609.5 1717.47    4690 1716.64  4755.4 1717.28  4762.8 1716.43  4789.3 1716.29
  4828.4 1717.13  4856.7 1716.23  4857.2 1715.73  4867.9 1716.23  5085.5 1716.44
  5159.1 1716.84  5210.2  1718.7  5235.9 1716.94  5292.1    1718  5376.1 1718.08
  5435.3 1719.44  5486.4 1718.76  5813.8 1719.86  5905.8 1721.16  6038.3 1721.08
  6274.1 1722.59  6323.9 1723.77  6373.2 1723.29  6499.2 1724.54  6744.8 1724.95
#Mann= 5 ,-1 , 0
  2649.2    .045       0  4856.7    .045       0  4867.9    .045       0
  5085.5    .035       0  5376.1    .045       0
Bank Sta=4856.7,4867.9
XS Rating Curve= 0 ,0
Exp/Cntr=0.3,0.1

Type RM Length L Ch R = 1 ,32665   ,531,531,531
BEGIN DESCRIPTION:
Mapping XS fdc704fd
END DESCRIPTION:
XS GIS Cut Line= 3
      1545579.43      6893012.56       1545298.3      6890894.33
      1543269.73      6891205.53
#Sta/Elev= 30
  2863.2 1718.22  3069.6 1718.54    3231 1717.03  3573.9  1717.1  3795.9 1715.88
  3844.1 1716.86  3937.1 1715.27  4179.2 1715.24  4209.5 1715.88  4225.8 1714.48
  4249.8 1714.36  4280.1 1715.58  4310.3 1714.88    4734 1714.18  4794.5 1714.91
  4910.2 1714.16  4910.7 1713.66  4921.4 1714.16  5737.3 1716.48  5873.4 1717.67
  5883.8 1716.83  5934.1 1716.45  5964.4 1718.56  6004.9 1717.57  6055.5 1717.64
  6248.5 1718.48  6328.7 1719.62  6642.1 1719.94    7020 1722.87  7052.3 1723.47
#Mann= 7 ,-1 , 0
  2863.2    .045       0  4910.2    .045       0  4921.4    .045       0
  5737.3    .035       0  5883.8    .045       0  6642.1    .035       0
    7020    .094       0
Bank Sta=4910.2,4921.4
XS Rating Curve= 0 ,0
Exp/Cntr=0.3,0.1

Type RM Length L Ch R = 1 ,32134   ,676,676,676
BEGIN DESCRIPTION:
Mapping XS 63a02176
END DESCRIPTION:
XS GIS Cut Line= 3
      1545599.77      6892030.01      1545698.73      6890605.49
      1543581.55      6890834.65
#Sta/Elev= 30
  3559.2 1715.56  3721.6 1714.31  3861.9 1715.36    3872 1714.06    3892 1713.25
  3932.1 1714.43  4262.9  1713.6  4363.1 1714.45  4413.3 1713.68  4977.7 1712.61
  4978.2 1712.11    4989 1712.61    5011 1713.28  5240.1 1713.98  5473.7 1713.95
  5715.1 1715.27  5745.3 1714.63  6057.1 1715.16  6239.6 1716.23  6360.9 1716.68
    6389 1717.48  6408.1 1715.74  6452.6 1715.98  6459.4 1716.35  6469.5 1718.59
  6529.8 1717.44  6650.5 1717.45  6811.5 1718.83  7002.6 1718.64  7116.7 1719.49
#Mann= 5 ,-1 , 0
  3559.2    .045       0  4977.7    .045       0    4989    .045       0
  6239.6    .035       0  6408.1    .045       0
Bank Sta=4977.7,4989
XS Rating Curve= 0 ,0
Exp/Cntr=0.3,0.1

Type RM Length L Ch R = 1 ,31458   ,1238,1238,1238
BEGIN DESCRIPTION:
Mapping XS 3cd6ea7b
END DESCRIPTION:
XS GIS Cut Line= 3
      1545797.91      6891733.54      1546251.67      6890396.02
      1544485.42      6890344.69
#Sta/Elev= 30
  3587.6 1712.45  3591.1  1712.9  3596.4 1712.38  3622.5 1713.71  3825.8 1712.77
  4174.2 1712.92  4237.6  1712.2  4459.4 1711.98  4648.3 1710.92  4691.7 1711.33
  4723.4 1710.63  4991.7 1710.07  4992.2 1709.57  5002.5 1709.57    5003 1710.07
  5176.7 1710.48  5326.8 1711.56  5346.8 1711.08  5406.8 1711.31  5456.9 1712.13
  5566.9 1712.04    5777 1713.38    5847 1712.85  6067.1 1713.69  6247.2 1713.28
  6287.2  1713.9  6337.2 1713.16  6537.3 1713.16  6687.4 1713.61    6767 1714.45
#Mann= 3 ,-1 , 0
  3587.6    .045       0  4991.7    .045       0    5003    .045       0
Bank Sta=4991.7,5003
XS Rating Curve= 0 ,0
Exp/Cntr=0.3,0.1

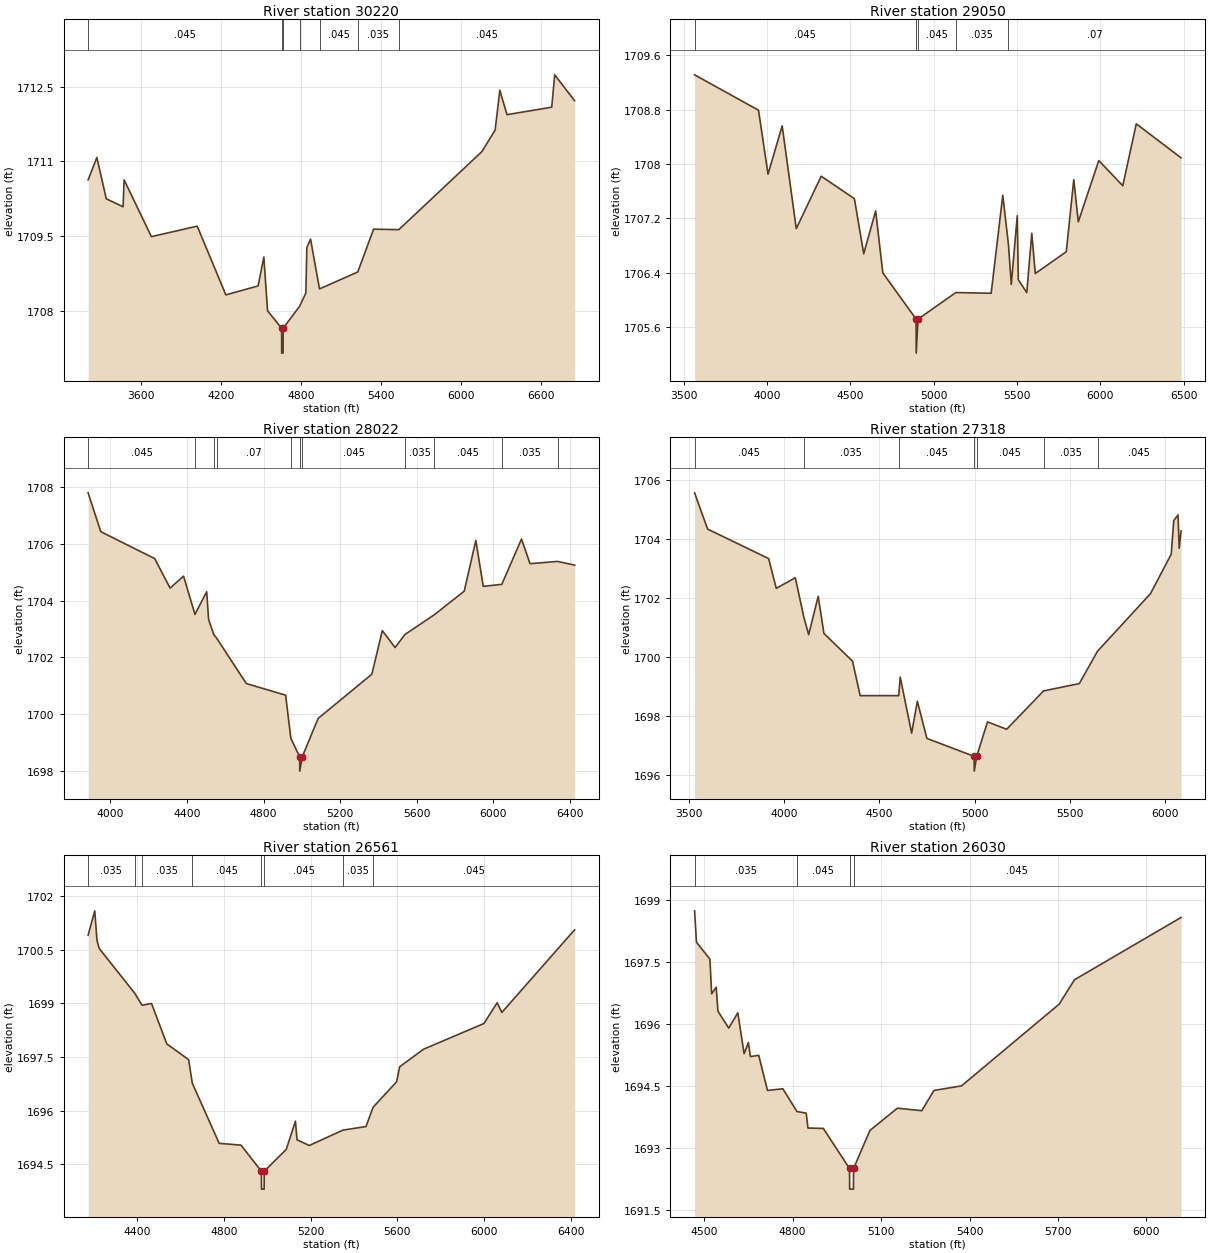
Type RM Length L Ch R = 1 ,30220   ,1170,1170,1170
BEGIN DESCRIPTION:
Mapping XS 13062094
END DESCRIPTION:
XS GIS Cut Line= 4
      1546324.86      6891285.41      1547049.31      6890020.22
      1546709.03      6889707.72      1545029.95      6890112.46
#Sta/Elev= 30
  3204.3 1710.63  3269.9 1711.08  3340.4 1710.25  3466.4 1710.09  3474.2 1710.63
  3678.5 1709.49  4022.4  1709.7  4236.8 1708.32  4478.6  1708.5  4521.7 1709.08
  4549.5    1708  4654.9 1707.65  4655.4 1707.15  4665.8 1707.15  4666.3 1707.65
  4789.7 1708.09  4836.7 1708.36    4844 1709.27  4871.8 1709.44  4938.9 1708.44
  5225.7 1708.78  5344.4 1709.64  5533.4 1709.63    6157  1711.2  6255.5 1711.63
  6290.7 1712.43  6344.5 1711.94  6679.7 1712.09  6702.2 1712.74  6851.4 1712.22
#Mann= 7 ,-1 , 0
  3204.3    .045       0  4654.9    .045       0  4666.3    .045       0
  4789.7    .035       0  4938.9    .045       0  5225.7    .035       0
  5533.4    .045       0
Bank Sta=4654.9,4666.3
XS Rating Curve= 0 ,0
Exp/Cntr=0.3,0.1

Type RM Length L Ch R = 1 ,29050   ,1028,1028,1028
BEGIN DESCRIPTION:
Mapping XS 52d36c91
END DESCRIPTION:
XS GIS Cut Line= 4
      1546532.92      6891346.09        1547480.        6890213.
      1547555.99      6889880.93      1546641.92      6889266.34
#Sta/Elev= 30
  3565.3 1709.31  3948.9 1708.79  4005.9 1707.85  4090.8 1708.56  4175.4 1707.05
    4325 1707.82  4524.1 1707.49  4580.1 1706.68  4651.7 1707.31  4694.6  1706.4
  4894.5 1705.72    4895 1705.22  4905.9 1705.72  5132.7 1706.11  5344.7  1706.1
  5414.4 1707.54  5448.3 1706.82  5465.4 1706.23  5501.4 1707.24  5507.5  1706.3
  5558.4 1706.11  5588.4 1706.98  5609.4 1706.39  5795.4 1706.71  5840.4 1707.77
  5867.4 1707.15  5990.4 1708.05  6134.4 1707.68  6215.4 1708.59  6484.2 1708.09
#Mann= 5 ,-1 , 0
  3565.3    .045       0  4894.5    .045       0  4905.9    .045       0
  5132.7    .035       0  5448.3     .07       0
Bank Sta=4894.5,4905.9
XS Rating Curve= 0 ,0
Exp/Cntr=0.3,0.1

Type RM Length L Ch R = 1 ,28022   ,704,704,704
BEGIN DESCRIPTION:
Mapping XS b3b4d158
END DESCRIPTION:
XS GIS Cut Line= 3
      1548074.16      6891793.64      1548203.45      6890684.25
       1547554.6      6889414.08
#Sta/Elev= 30
  3883.1 1707.81  3949.2 1706.44  4231.1 1705.49  4311.6 1704.45  4382.1 1704.87
  4441.6 1703.52  4502.9 1704.32    4513 1703.34  4539.9 1702.81  4555.1 1702.68
  4710.2 1701.08  4915.7 1700.67  4942.8 1699.15    4989 1698.49  4989.5 1697.99
  5002.1 1698.49  5085.6 1699.85  5366.4 1701.41  5421.1 1702.95  5487.7 1702.35
  5539.1 1702.81  5693.3 1703.51  5849.2 1704.34  5909.9 1706.13  5948.7 1704.51
  6045.6 1704.58  6148.7 1706.18  6193.2 1705.31  6337.2 1705.39  6426.3 1705.26
#Mann= 11 ,-1 , 0
  3883.1    .045       0  4441.6     .07       0  4539.9    .035       0
  4555.1     .07       0  4942.8    .045       0    4989    .045       0
  5002.1    .045       0  5539.1    .035       0  5693.3    .045       0
  6045.6    .035       0  6337.2     .07       0
Bank Sta=4989,5002.1
XS Rating Curve= 0 ,0
Exp/Cntr=0.3,0.1

Type RM Length L Ch R = 1 ,27318   ,757,757,757
BEGIN DESCRIPTION:
Mapping XS cfa27e93
END DESCRIPTION:
XS GIS Cut Line= 3
      1548875.07      6892006.39      1548860.18      6890537.56
      1547973.58      6889916.14
#Sta/Elev= 30
  3531.1 1705.56  3599.5 1704.33  3919.5 1703.33  3959.5 1702.32  4059.5 1702.68
  4103.8 1701.35  4129.5 1700.75  4179.5 1702.05  4209.5 1700.79  4359.5 1699.85
  4399.5 1698.68  4601.8 1698.68  4609.5 1699.31  4669.5 1697.41  4699.5 1698.49
  4749.5 1697.23  4997.5 1696.62    4998 1696.12  5010.6 1696.62  5067.4 1697.79
    5168 1697.54  5361.2 1698.84  5548.9 1699.09  5644.7 1700.19  5922.2 1702.14
    6031 1703.48  6044.3 1704.62  6066.7 1704.81  6072.8 1703.68  6082.7 1704.27
#Mann= 7 ,-1 , 0
  3531.1    .045       0  4103.8    .035       0  4601.8    .045       0
  4997.5    .045       0  5010.6    .045       0  5361.2    .035       0
  5644.7    .045       0
Bank Sta=4997.5,5010.6
XS Rating Curve= 0 ,0
Exp/Cntr=0.3,0.1

Type RM Length L Ch R = 1 ,26561   ,531,531,531
BEGIN DESCRIPTION:
Mapping XS e5eeddb5
END DESCRIPTION:
XS GIS Cut Line= 4
      1549598.61      6891558.51      1549501.39      6890742.55
      1549063.89      6890284.22      1548300.33      6890082.91
#Sta/Elev= 30
  4173.1 1700.91  4203.8 1701.59  4213.9 1700.77    4224 1700.54  4387.8 1699.29
    4422 1698.95  4465.7    1699  4536.2 1697.87  4636.9 1697.43  4653.9 1696.77
  4777.9 1695.09  4878.6 1695.04  4972.7 1694.31  4973.2 1693.81  4985.4 1693.81
  4985.9 1694.31  5087.4 1694.92  5129.8 1695.71  5137.1 1695.19  5193.7 1695.03
  5349.3 1695.46  5455.4 1695.56  5488.3  1696.1  5596.6 1696.81  5610.7 1697.23
  5720.4 1697.72  5999.6 1698.44  6060.6 1699.02  6082.3 1698.75  6418.1 1701.06
#Mann= 8 ,-1 , 0
  4173.1    .035       0  4387.8     .07       0    4422    .035       0
  4653.9    .045       0  4972.7    .045       0  4985.9    .045       0
  5349.3    .035       0  5488.3    .045       0
Bank Sta=4972.7,4985.9
XS Rating Curve= 0 ,0
Exp/Cntr=0.3,0.1

Type RM Length L Ch R = 1 ,26030   ,173,173,173
BEGIN DESCRIPTION:
Mapping XS 898c4343
END DESCRIPTION:
XS GIS Cut Line= 3
      1550310.46      6890742.57      1549869.45      6890471.72
      1548775.71      6890176.58
#Sta/Elev= 30
  4467.2 1698.74  4473.6 1697.98  4519.2 1697.57  4525.1 1696.73  4540.5 1696.89
  4546.4 1696.31  4583.1  1695.9  4613.9 1696.27  4635.2 1695.28  4649.6 1695.55
  4656.5 1695.21  4684.8 1695.24  4714.5 1694.39  4766.6 1694.43  4814.5 1693.88
  4845.9 1693.84  4851.8 1693.48  4903.9 1693.47  4992.8  1692.5  4993.3    1692
  5006.1    1692  5006.6  1692.5  5061.9 1693.42  5155.1 1693.96  5237.9  1693.9
  5279.4 1694.39  5372.6  1694.5    5704 1696.48  5755.8 1697.07  6117.6 1698.58
#Mann= 4 ,-1 , 0
  4467.2    .035       0  4814.5    .045       0  4992.8    .045       0
  5006.6    .045       0
Bank Sta=4992.8,5006.6
XS Rating Curve= 0 ,0
Exp/Cntr=0.3,0.1