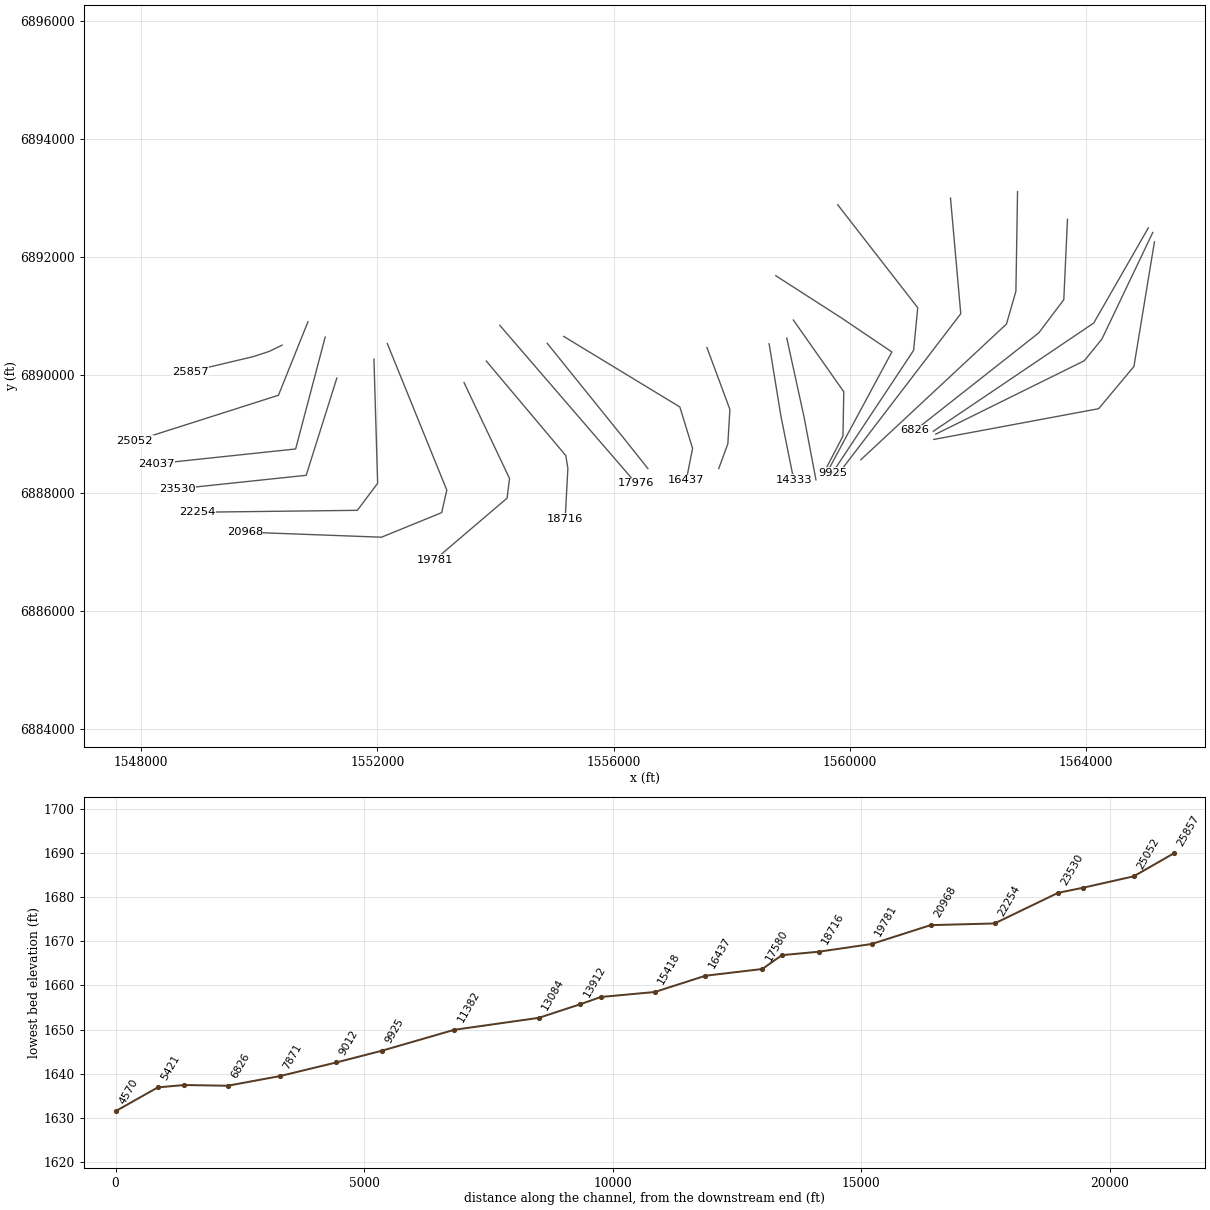
HEC-RAS study MULBERRY CREEK TRIBUTARY 6.prj: MULBERRY CREEK TRIBUTARY 6 Base Level Engineering

--- MULBERRY CREEK TRIBUTARY 6.g01 (geometry) --- (continued)

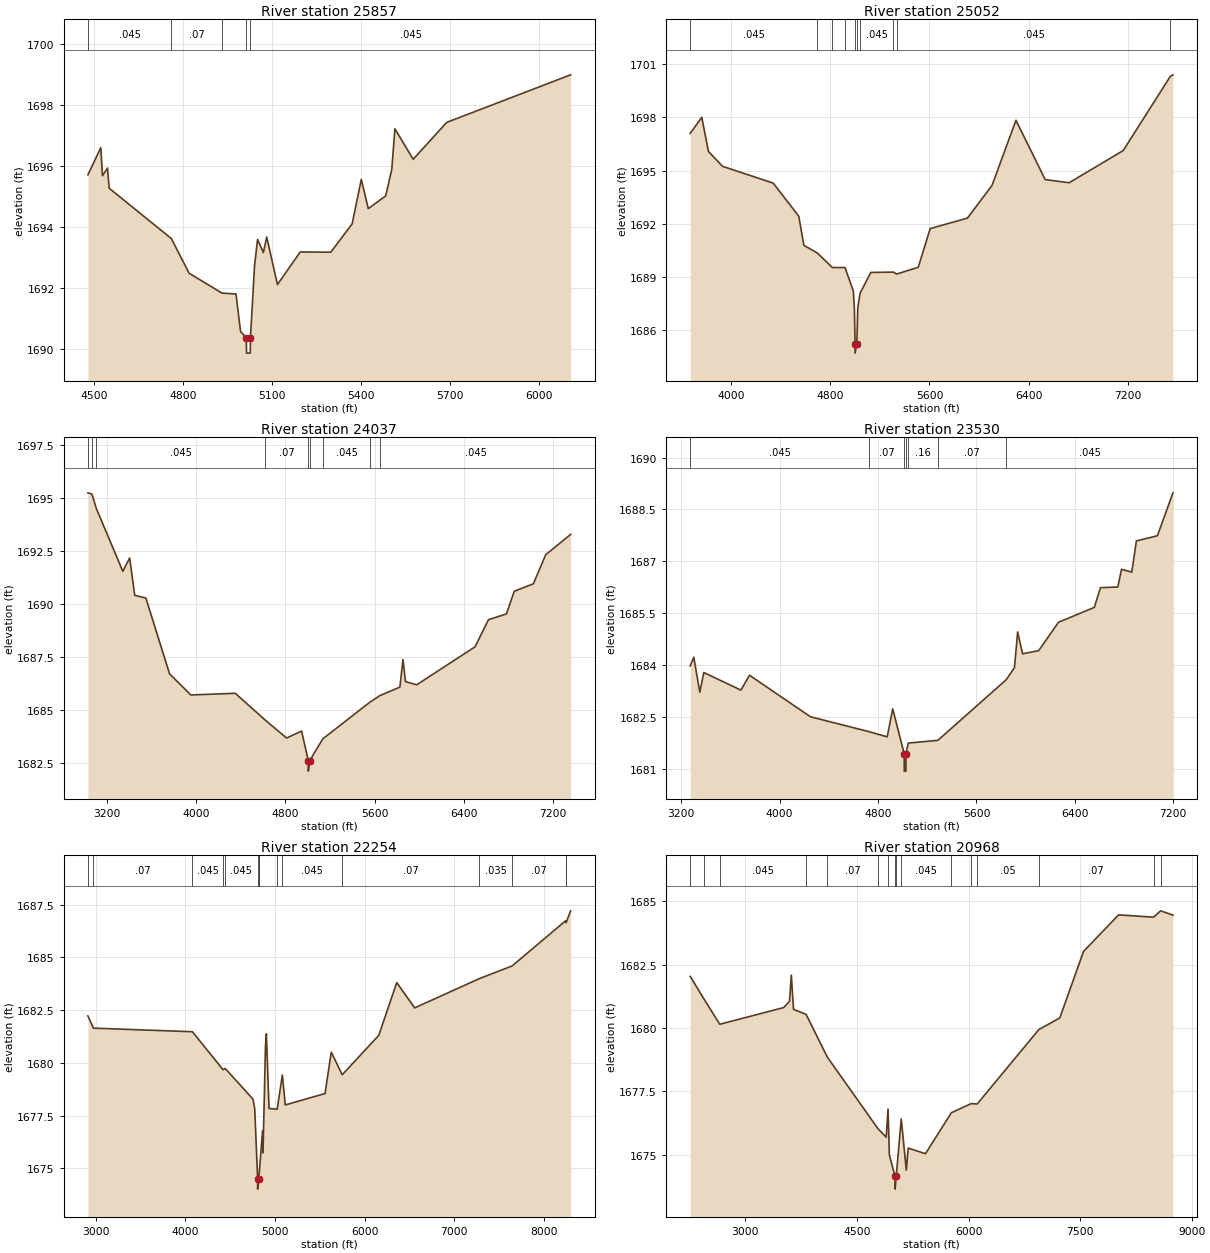
Type RM Length L Ch R = 1 ,25857   ,805,805,805
BEGIN DESCRIPTION:
Mapping XS 284755fd
END DESCRIPTION:
XS GIS Cut Line= 4
      1550386.83      6890502.98      1550171.53       6890398.8
      1549897.22      6890308.52      1548828.89      6890055.31
#Sta/Elev= 30
  4480.2 1695.72  4523.6 1696.61  4529.2 1695.69  4546.2 1695.94  4551.7 1695.28
    4761 1693.63    4821 1692.49  4931.8 1691.84  4978.9 1691.81  4994.3 1690.58
  5013.8 1690.37  5014.3 1689.87  5027.1 1689.87  5027.6 1690.37  5041.3 1692.72
  5051.6  1693.6  5071.2 1693.17  5082.4 1693.68  5118.6 1692.12  5195.4 1693.19
  5298.2 1693.18  5370.1 1694.11    5401 1695.57  5424.5 1694.61  5483.2 1695.03
  5503.7  1695.9  5514.1 1697.23  5575.7 1696.23  5688.7 1697.44  6106.1    1699
#Mann= 5 ,-1 , 0
  4480.2    .045       0    4761     .07       0  4931.8    .045       0
  5013.8    .045       0  5027.6    .045       0
Bank Sta=5013.8,5027.6
XS Rating Curve= 0 ,0
Exp/Cntr=0.3,0.1

Type RM Length L Ch R = 1 ,25052   ,1015,1015,1015
BEGIN DESCRIPTION:
Mapping XS 7be91d26
END DESCRIPTION:
XS GIS Cut Line= 3
       1550824.9      6890899.06      1550324.91      6889654.28
      1547892.65      6888878.25
#Sta/Elev= 30
  3669.7  1697.1  3762.9 1698.01  3816.7 1696.08  3929.6 1695.24    4339 1694.29
  4545.3 1692.42  4586.8 1690.77    4693 1690.35  4816.1 1689.52  4917.9 1689.52
  4985.6 1688.19  4994.2 1687.15  4999.5 1685.18    5000 1684.68  5013.4 1685.18
  5021.5 1687.26  5040.4 1688.07  5126.5 1689.24  5308.7 1689.26  5335.5 1689.15
  5509.2 1689.53  5605.8 1691.72  5906.1 1692.31  6104.5 1694.16  6297.6 1697.84
  6533.5 1694.49  6726.7 1694.31  7162.9 1696.13  7543.7 1700.33  7564.2 1700.41
#Mann= 10 ,-1 , 0
  3669.7    .045       0    4693     .07       0  4816.1    .045       0
  4917.9     .07       0  4999.5     .07       0  5013.4     .07       0
  5040.4    .045       0  5308.7     .07       0  5335.5    .045       0
  7543.7    .035       0
Bank Sta=4999.5,5013.4
XS Rating Curve= 0 ,0
Exp/Cntr=0.3,0.1

Type RM Length L Ch R = 1 ,24037   ,507,507,507
BEGIN DESCRIPTION:
Mapping XS 599ac3c0
END DESCRIPTION:
XS GIS Cut Line= 3
      1551116.56      6890640.35      1550616.58      6888744.56
      1548262.43      6888494.56
#Sta/Elev= 30
  3030.6 1695.23  3066.8 1695.17  3106.1 1694.49  3343.3 1691.53  3404.7 1692.16
  3450.2  1690.4  3550.1 1690.27  3762.2  1686.7  3953.3  1685.7    4351 1685.78
  4617.4 1684.53  4811.8 1683.67  4946.3    1684    5006 1682.61  5006.5 1682.11
  5019.9 1682.61  5136.3 1683.63  5560.6 1685.37  5651.9 1685.68  5827.5 1686.07
  5855.4 1687.37  5877.7 1686.33  5978.3 1686.18  6501.2 1687.97  6621.9 1689.25
  6782.8 1689.52  6853.2 1690.59  7024.2 1690.94  7134.8 1692.31  7358.6 1693.27
#Mann= 9 ,-1 , 0
  3030.6    .045       0  3066.8     .07       0  3106.1    .045       0
  4617.4     .07       0    5006     .07       0  5019.9     .07       0
  5136.3    .045       0  5560.6     .07       0  5651.9    .045       0
Bank Sta=5006,5019.9
XS Rating Curve= 0 ,0
Exp/Cntr=0.3,0.1

Type RM Length L Ch R = 1 ,23530   ,1276,1276,1276
BEGIN DESCRIPTION:
Mapping XS 7db01c75
END DESCRIPTION:
XS GIS Cut Line= 3
      1551313.89      6889945.68      1550794.82      6888298.32
      1548609.16      6888067.71
#Sta/Elev= 30
  3272.8 1683.98  3301.8 1684.23  3350.7 1683.22    3383 1683.79  3684.8 1683.28
  3754.8 1683.71  4250.7 1682.51    4727 1682.08  4874.5 1681.93    4919 1682.74
  5012.7 1681.44  5013.2 1680.94  5026.7 1680.94  5027.2 1681.44  5045.4 1681.75
  5286.4 1681.83  5841.8 1683.58  5909.1 1683.93    5935 1684.96  5975.2 1684.33
  6105.9 1684.42  6266.8 1685.24  6558.4 1685.67  6608.7 1686.24  6749.5 1686.26
  6779.6 1686.77  6863.3 1686.69  6900.3 1687.59  7071.3 1687.74  7197.8 1688.98
#Mann= 7 ,-1 , 0
  3272.8    .045       0    4727     .07       0  5012.7     .07       0
  5027.2     .07       0  5045.4     .16       0  5286.4     .07       0
  5841.8    .045       0
Bank Sta=5012.7,5027.2
XS Rating Curve= 0 ,0
Exp/Cntr=0.3,0.1

Type RM Length L Ch R = 1 ,22254   ,1286,1286,1286
BEGIN DESCRIPTION:
Mapping XS 52aee3df
END DESCRIPTION:
XS GIS Cut Line= 4
       1551942.1      6890267.14       1552004.6      6888162.96
      1551661.39      6887704.89      1548955.57      6887672.65
#Sta/Elev= 30
  2915.4 1682.23  2976.9 1681.65  4080.5 1681.48  4422.2 1679.68  4445.7 1679.74
  4755.4 1678.29  4775.4 1677.84    4808 1674.52  4808.5 1674.02  4822.8 1674.52
  4823.5 1674.65  4863.1 1676.79  4868.1 1675.74  4895.4 1680.81  4905.4 1681.38
  4935.4 1677.84  5026.2 1677.81  5083.7 1679.43    5116 1678.01  5559.8 1678.55
  5629.3 1680.51    5751 1679.44  6159.3 1681.31  6359.3 1683.81  6559.3 1682.61
  7277.2 1683.99  7646.8  1684.6  8243.5 1686.74  8248.2 1686.65  8298.9 1687.21
#Mann= 15 ,-1 , 0
  2915.4    .045       0  2976.9     .07       0  4080.5    .045       0
  4422.2    .035       0  4445.7    .045       0    4808     .07       0
  4822.8    .045       0  4823.5     .07       0  5026.2     .05       0
  5083.7    .045       0    5751     .07       0  7277.2    .035       0
  7646.8     .07       0  8243.5    .035       0  8248.2     .07       0
Bank Sta=4808,4822.8
XS Rating Curve= 0 ,0
Exp/Cntr=0.3,0.1

Type RM Length L Ch R = 1 ,20968   ,1187,1187,1187
BEGIN DESCRIPTION:
Mapping XS ad9e62e9
END DESCRIPTION:
XS GIS Cut Line= 5
      1552168.54      6890530.17      1553175.48      6888047.55
      1553088.68       6887665.6      1552069.65       6887249.6
      1549754.97      6887335.85
#Sta/Elev= 30
  2260.1 1682.04  2442.5 1681.16  2657.3 1680.15    3517 1680.81  3594.7 1681.06
  3618.8 1682.09  3648.3 1680.74  3817.7 1680.54  4103.4 1678.85  4782.6 1676.03
    4894 1675.69  4918.6  1676.8  4936.2 1674.99  5013.3 1674.14  5013.8 1673.64
  5028.1 1674.14  5096.3 1676.41  5164.3 1674.39  5189.7 1675.26  5421.9 1675.04
  5770.8 1676.66  6039.6 1677.02  6116.5    1677  6945.1 1679.94  7226.7  1680.4
  7546.9 1683.03  8017.3 1684.47  8487.1 1684.38  8581.4 1684.63  8747.8 1684.46
#Mann= 16 ,-1 , 0
  2260.1    .045       0  2442.5     .07       0  2657.3    .045       0
  3817.7    .035       0  4103.4     .07       0  4782.6    .045       0
  4918.6     .07       0  5013.3     .07       0  5028.1     .07       0
  5096.3    .045       0  5770.8     .05       0  6039.6    .045       0
  6116.5     .05       0  6945.1     .07       0  8487.1    .035       0
  8581.4     .07       0
Bank Sta=5013.3,5028.1
XS Rating Curve= 0 ,0
Exp/Cntr=0.3,0.1

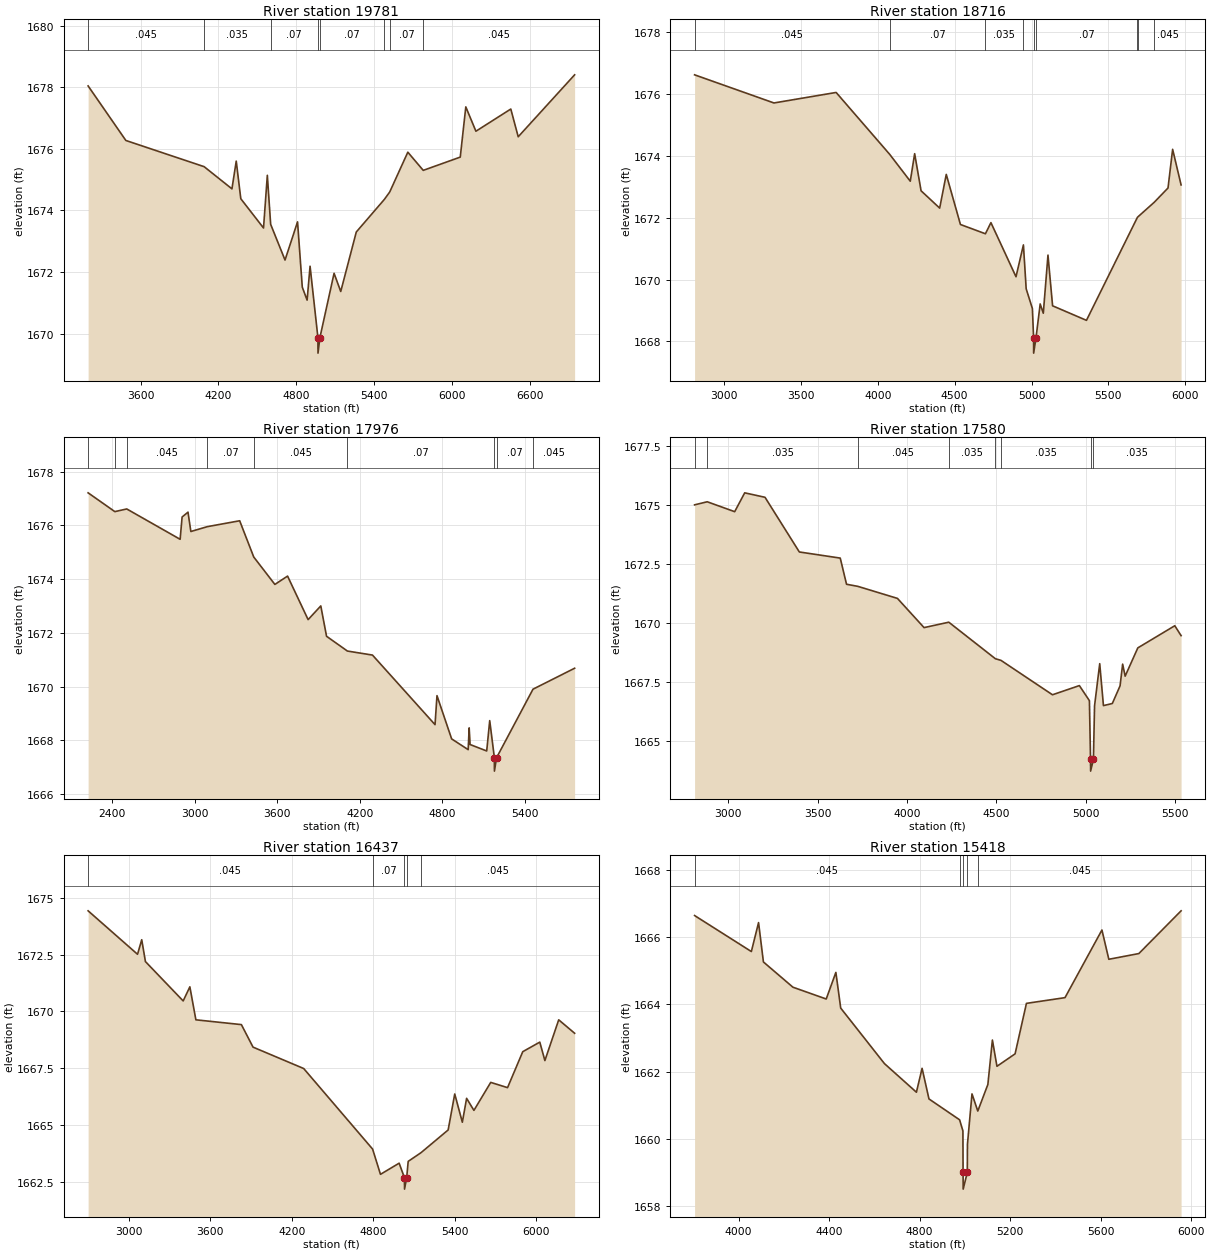
Type RM Length L Ch R = 1 ,19781   ,1065,1065,1065
BEGIN DESCRIPTION:
Mapping XS ae0953c3
END DESCRIPTION:
XS GIS Cut Line= 4
      1553467.15      6889869.59      1554237.98       6888244.6
      1554196.32      6887911.26      1552967.12      6886862.63
#Sta/Elev= 30
  3195.1 1678.04    3486 1676.27  4089.4 1675.42  4303.8  1674.7  4336.9  1675.6
    4372 1674.38  4547.2 1673.43  4576.6 1675.14  4602.2 1673.55    4713 1672.39
  4809.5 1673.63    4846 1671.51  4883.2 1671.09    4906 1672.19  4966.6 1669.87
  4967.1 1669.37  4981.7 1669.87    5091 1671.96  5142.5 1671.37  5262.3  1673.3
  5479.1 1674.36  5520.2  1674.6  5659.6 1675.89  5778.4  1675.3  6063.7 1675.73
  6106.5 1677.36  6184.4 1676.57  6453.4 1677.29  6510.5 1676.39  6945.3  1678.4
#Mann= 8 ,-1 , 0
  3195.1    .045       0  4089.4    .035       0  4602.2     .07       0
  4966.6     .07       0  4981.7     .07       0  5479.1    .045       0
  5520.2     .07       0  5778.4    .045       0
Bank Sta=4966.6,4981.7
XS Rating Curve= 0 ,0
Exp/Cntr=0.3,0.1

Type RM Length L Ch R = 1 ,18716   ,740,740,740
BEGIN DESCRIPTION:
Mapping XS 22206c55
END DESCRIPTION:
XS GIS Cut Line= 4
      1553844.19      6890234.45      1555190.79      6888632.14
      1555225.52      6888415.13        1555180.      6887563.04
#Sta/Elev= 30
  2807.3 1676.62  3323.9 1675.71  3728.5 1676.05  4076.8 1674.05    4211 1673.18
  4239.5 1674.07  4281.3 1672.87  4402.3 1672.31  4445.2  1673.4  4537.5 1671.78
    4700 1671.48  4735.9 1671.84  4899.1 1670.09  4947.3 1671.12  4965.3  1669.7
  5005.8 1669.06  5013.4 1668.12  5013.9 1667.62  5029.4 1668.12  5056.4 1669.21
  5076.7 1668.91  5107.1 1670.79  5137.2 1669.15  5357.6 1668.68  5689.1 1672.01
  5695.4 1672.04    5799  1672.5  5888.3 1672.96  5918.4 1674.21  5973.4 1673.06
#Mann= 9 ,-1 , 0
  2807.3    .045       0  4076.8     .07       0    4700    .035       0
  4947.3     .07       0  5013.4     .07       0  5029.4     .07       0
  5689.1    .045       0  5695.4     .07       0    5799    .045       0
Bank Sta=5013.4,5029.4
XS Rating Curve= 0 ,0
Exp/Cntr=0.3,0.1

Type RM Length L Ch R = 1 ,17976   ,396,396,396
BEGIN DESCRIPTION:
Mapping XS 65197112
END DESCRIPTION:
XS GIS Cut Line= 3
      1554073.34      6890838.64      1555802.51      6888831.69
      1556380.02      6888162.98
#Sta/Elev= 30
  2227.1 1677.21  2421.2 1676.51  2507.6 1676.61  2895.3 1675.48  2909.6 1676.31
  2952.3 1676.49  2973.2 1675.77  3092.5 1675.95  3327.6 1676.17  3429.9 1674.82
  3583.2  1673.8  3675.4 1674.11  3824.6 1672.49  3916.7    1673  3958.4 1671.87
    4110 1671.32    4292 1671.17  4746.2 1668.58  4760.4 1669.66  4866.8 1668.05
  4986.8 1667.65  4994.1 1668.46  5000.7 1667.84  5121.4  1667.6  5143.3 1668.73
    5177 1667.35  5177.5 1666.85  5193.1 1667.35  5457.6  1669.9  5759.8 1670.68
#Mann= 9 ,-1 , 0
  2227.1    .045       0  2421.2     .07       0  2507.6    .045       0
  3092.5     .07       0  3429.9    .045       0    4110     .07       0
    5177     .07       0  5193.1     .07       0  5457.6    .045       0
Bank Sta=5177,5193.1
XS Rating Curve= 0 ,0
Exp/Cntr=0.3,0.1

Type RM Length L Ch R = 1 ,17580   ,1143,1143,1143
BEGIN DESCRIPTION:
Mapping XS 2ffc67b9
END DESCRIPTION:
XS GIS Cut Line= 3
      1554876.29      6890533.95      1556230.46      6888853.39
        1556580.        6888413.
#Sta/Elev= 30
  2811.8 1675.01  2882.6 1675.14  3036.1 1674.72  3092.1 1675.52  3205.7 1675.33
  3397.6 1673.01  3626.3 1672.75  3661.5 1671.64  3725.2 1671.55  3946.2 1671.04
    4095  1669.8  4233.3 1670.03  4493.8 1668.48  4525.2 1668.41  4813.2 1666.95
  4963.5 1667.34  5019.6  1666.7  5025.9 1664.21  5026.4 1663.71  5042.1 1664.21
  5048.4 1666.48  5077.3 1668.27  5098.1 1666.49  5147.8 1666.58  5191.1 1667.33
  5205.5 1668.25  5219.5 1667.74  5290.4 1668.94  5497.1 1669.88  5532.3 1669.46
#Mann= 8 ,-1 , 0
  2811.8    .045       0  2882.6    .035       0  3725.2    .045       0
  4233.3    .035       0  4493.8     .07       0  4525.2    .035       0
  5025.9    .035       0  5042.1    .035       0
Bank Sta=5025.9,5042.1
XS Rating Curve= 0 ,0
Exp/Cntr=0.3,0.1

Type RM Length L Ch R = 1 ,16437   ,1019,1019,1019
BEGIN DESCRIPTION:
Mapping XS b5890c58
END DESCRIPTION:
XS GIS Cut Line= 4
      1555156.26      6890650.69      1557121.52      6889456.26
       1557336.8      6888754.87      1557230.01      6888213.03
#Sta/Elev= 30
  2698.7 1674.42    3063 1672.51  3093.9 1673.15  3121.1 1672.19  3399.3 1670.46
  3448.6 1671.08    3493 1669.63  3828.4 1669.42  3914.2 1668.43  4287.6 1667.49
  4795.4 1663.95  4853.5 1662.84  4991.1 1663.33  5030.3 1662.69  5030.8 1662.19
  5046.6 1662.69  5057.8 1663.41  5151.9 1663.79  5352.3 1664.79  5400.8 1666.37
  5456.9 1665.13  5488.3 1666.18  5542.2 1665.65  5666.1 1666.88  5790.1 1666.65
  5902.2 1668.23  6027.7 1668.65  6065.3 1667.84  6167.2 1669.63  6284.4 1669.04
#Mann= 5 ,-1 , 0
  2698.7    .045       0  4795.4     .07       0  5030.3     .07       0
  5046.6     .07       0  5151.9    .045       0
Bank Sta=5030.3,5046.6
XS Rating Curve= 0 ,0
Exp/Cntr=0.3,0.1

Type RM Length L Ch R = 1 ,15418   ,1085,1085,1085
BEGIN DESCRIPTION:
Mapping XS b4d6c93d
END DESCRIPTION:
XS GIS Cut Line= 4
      1557579.99      6890463.02      1557968.74      6889414.59
      1557934.02      6888831.26      1557779.98      6888412.96
#Sta/Elev= 30
    3806 1666.64  4056.7 1665.57  4088.5 1666.43    4110 1665.26  4240.4 1664.51
  4387.3 1664.16  4429.9 1664.95  4451.3 1663.89  4644.4 1662.24  4785.6 1661.39
  4810.6  1662.1    4841 1661.19  4976.3 1660.57  4990.9 1660.24  4991.6 1659.01
  4992.1 1658.51  5010.3 1659.01  5010.9 1659.84    5031 1661.34  5056.6 1660.83
  5101.1 1661.62  5121.1 1662.94  5141.2 1662.16  5221.3 1662.53  5271.4 1664.03
  5441.7  1664.2  5604.8 1666.21  5635.2 1665.34  5767.8 1665.51  5954.3 1666.78
#Mann= 5 ,-1 , 0
    3806    .045       0  4976.3     .07       0  4991.6     .07       0
  5010.3     .07       0  5056.6    .045       0
Bank Sta=4991.6,5010.3
XS Rating Curve= 0 ,0
Exp/Cntr=0.3,0.1

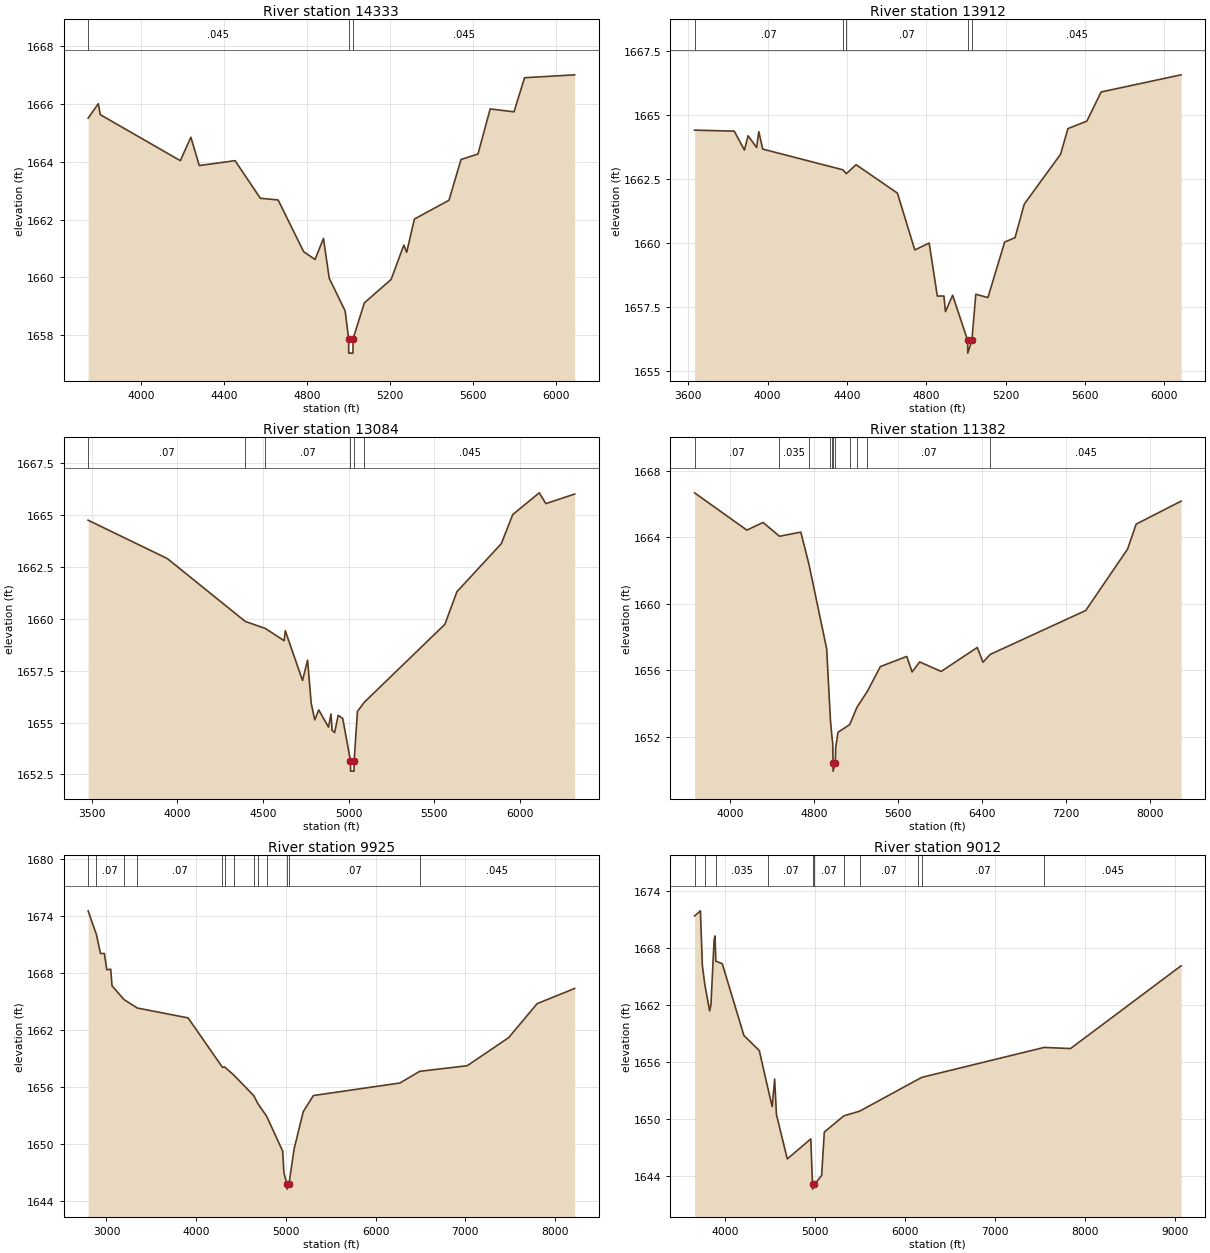
Type RM Length L Ch R = 1 ,14333   ,421,421,421
BEGIN DESCRIPTION:
Mapping XS 81ba1fd6
END DESCRIPTION:
XS GIS Cut Line= 3
      1558633.07      6890526.24      1558831.59      6889306.95
       1559049.5      6888221.86
#Sta/Elev= 30
  3745.6 1665.51  3794.5 1666.01  3804.6 1665.63  4189.6 1664.04  4240.3 1664.85
  4280.8 1663.87    4453 1664.04  4574.6 1662.74  4660.3 1662.68  4783.3 1660.89
    4838 1660.62  4878.6 1661.35  4906.4 1659.97    4983 1658.84  4999.8 1657.88
  5000.3 1657.38  5020.6 1657.38  5021.1 1657.88  5075.6 1659.12  5204.3 1659.93
  5265.5 1661.12  5279.2 1660.87  5316.5 1662.02  5482.8 1662.67  5540.9 1664.08
  5622.4 1664.27  5681.2 1665.83  5795.8 1665.73  5846.8 1666.91  6087.7 1667.01
#Mann= 3 ,-1 , 0
  3745.6    .045       0  4999.8    .045       0  5021.1    .045       0
Bank Sta=4999.8,5021.1
XS Rating Curve= 0 ,0
Exp/Cntr=0.3,0.1

Type RM Length L Ch R = 1 ,13912   ,828,828,828
BEGIN DESCRIPTION:
Mapping XS e4fd1739
END DESCRIPTION:
XS GIS Cut Line= 3
      1558931.68      6890623.46      1559223.08      6889292.19
      1559425.86      6888221.11
#Sta/Elev= 30
  3632.3 1664.42  3832.4 1664.38  3883.6 1663.64    3902  1664.2    3945 1663.74
  3956.1 1664.36  3975.7 1663.68  4380.1 1662.87  4397.3 1662.72  4446.6 1663.07
  4654.9 1661.96  4742.6 1659.74  4815.1 1660.01  4856.1 1657.94  4889.5 1657.94
    4897 1657.33  4933.4 1657.97  5009.1 1656.21  5009.6 1655.71  5030.4 1656.21
  5050.2 1658.01  5111.3 1657.88  5195.7 1660.05    5248 1660.22  5294.5 1661.53
  5477.7 1663.48  5514.7 1664.48    5610 1664.77  5681.9 1665.91  6085.2 1666.58
#Mann= 5 ,-1 , 0
  3632.3     .07       0  4380.1    .035       0  4397.3     .07       0
  5009.1     .07       0  5030.4    .045       0
Bank Sta=5009.1,5030.4
XS Rating Curve= 0 ,0
Exp/Cntr=0.3,0.1

Type RM Length L Ch R = 1 ,13084   ,1702,1702,1702
BEGIN DESCRIPTION:
Mapping XS 3e534ef1
END DESCRIPTION:
XS GIS Cut Line= 4
      1559042.79      6890929.02      1559896.96      6889713.74
      1559883.07      6888963.74       1559605.3      6888429.05
#Sta/Elev= 30
  3479.9 1664.76  3942.1 1662.91  4396.3 1659.88  4513.7 1659.54  4623.4 1658.95
  4630.1 1659.43  4730.6 1657.03  4760.2 1658.01  4781.1 1655.94    4802 1655.13
  4825.5 1655.61  4882.2 1654.78    4897 1655.42  4903.1 1654.63  4917.9 1654.52
  4938.8 1655.35  4965.3  1655.2  5010.4 1653.16  5010.9 1652.66  5031.3 1652.66
  5031.8 1653.16  5051.1 1655.54  5090.8 1655.98  5561.2 1659.74  5631.2 1661.31
  5890.5 1663.63  5956.8 1665.03  6111.6 1666.08  6150.1 1665.56    6318 1666.02
#Mann= 6 ,-1 , 0
  3479.9     .07       0  4396.3    .035       0  4513.7     .07       0
  5010.4     .07       0  5031.8     .07       0  5090.8    .045       0
Bank Sta=5010.4,5031.8
XS Rating Curve= 0 ,0
Exp/Cntr=0.3,0.1

Type RM Length L Ch R = 1 ,11382   ,1457,1457,1457
BEGIN DESCRIPTION:
Mapping XS 6958bbab
END DESCRIPTION:
XS GIS Cut Line= 4
      1558746.05       6891679.8       1559857.2       6890964.5
      1560711.36      6890388.11      1559628.03      6888374.23
#Sta/Elev= 30
  3661.3 1666.67  4159.8 1664.43  4314.2 1664.89  4470.5 1664.06  4674.2 1664.31
  4752.5 1662.36  4920.7  1657.3  4956.7 1653.01  4972.4 1651.93  4978.5 1651.64
  4981.4 1650.45  4981.9 1649.95    5003 1650.45  5006.8 1651.37  5028.4 1652.28
    5141 1652.75    5209 1653.78  5309.2 1654.75  5432.5 1656.23  5684.3 1656.84
  5735.2 1655.91  5807.2 1656.51  6012.4 1655.94  6356.8 1657.38  6410.8 1656.49
  6479.1 1656.96  7390.6  1659.6  7789.8 1663.29  7871.8 1664.79    8300 1666.17
#Mann= 11 ,-1 , 0
  3661.3     .07       0  4470.5    .035       0  4752.5     .07       0
  4956.7    .035       0  4972.4     .16       0  4981.4     .07       0
    5003     .16       0    5141     .07       0    5209    .035       0
  5309.2     .07       0  6479.1    .045       0
Bank Sta=4981.4,5003
XS Rating Curve= 0 ,0
Exp/Cntr=0.3,0.1

Type RM Length L Ch R = 1 ,9925    ,913,913,913
BEGIN DESCRIPTION:
Mapping XS a75f1569
END DESCRIPTION:
XS GIS Cut Line= 4
       1559794.7      6892881.16      1561148.86      6891138.11
      1561079.42      6890415.89      1559704.41       6888339.5
#Sta/Elev= 30
  2795.5 1674.53  2888.3 1672.02  2933.5 1670.04  2976.8 1670.03  3004.1 1668.32
  3047.5 1668.38    3062 1666.64  3194.5 1665.19  3343.9 1664.29    3910 1663.25
  4293.3 1658.04  4317.4 1658.08  4419.4 1657.23  4641.7 1655.06  4688.1 1654.22
  4785.9 1652.88  4964.9  1649.2    4978 1646.93  5012.1 1645.71  5012.6 1645.21
  5033.8 1645.71  5091.8 1649.44  5193.7 1653.37  5306.8 1655.07  6271.1 1656.39
  6491.3 1657.62  7021.1 1658.21  7483.5 1661.17  7800.7 1664.75  8218.7 1666.35
#Mann= 13 ,-1 , 0
  2795.5    .035       0  2888.3     .07       0  3194.5    .035       0
  3343.9     .07       0  4293.3    .035       0  4317.4     .07       0
  4419.4    .035       0  4641.7     .07       0  4688.1    .035       0
  4785.9     .07       0  5012.1     .07       0  5033.8     .07       0
  6491.3    .045       0
Bank Sta=5012.1,5033.8
XS Rating Curve= 0 ,0
Exp/Cntr=0.3,0.1

Type RM Length L Ch R = 1 ,9012    ,1141,1141,1141
BEGIN DESCRIPTION:
Mapping XS 5af55c60
END DESCRIPTION:
XS GIS Cut Line= 3
      1561703.99      6892994.41      1561877.59      6891036.12
      1559788.45      6888301.49
#Sta/Elev= 30
  3656.8 1671.35  3721.7 1671.89  3743.5 1666.11  3770.8 1664.11  3823.9 1661.35
  3838.5 1661.98  3874.1 1668.85  3884.1 1669.25  3892.8 1666.59  3964.4 1666.32
  4205.4 1658.75    4376 1657.17    4476 1653.02  4519.6 1651.26  4546.7 1654.16
  4566.8 1650.42  4687.2 1645.75  4948.3 1647.86  4967.5 1643.07    4968 1642.57
  4989.3 1643.07  5068.7 1644.01  5098.8 1648.58  5315.3 1650.29  5490.7 1650.78
    6140 1654.13  6184.1 1654.35  7542.5  1657.5  7835.2 1657.38  9064.1  1666.1
#Mann= 11 ,-1 , 0
  3656.8    .035       0  3770.8     .07       0  3892.8    .035       0
    4476     .07       0  4967.5     .07       0  4989.3     .07       0
  5315.3    .035       0  5490.7     .07       0    6140     .16       0
  6184.1     .07       0  7542.5    .045       0
Bank Sta=4967.5,4989.3
XS Rating Curve= 0 ,0
Exp/Cntr=0.3,0.1

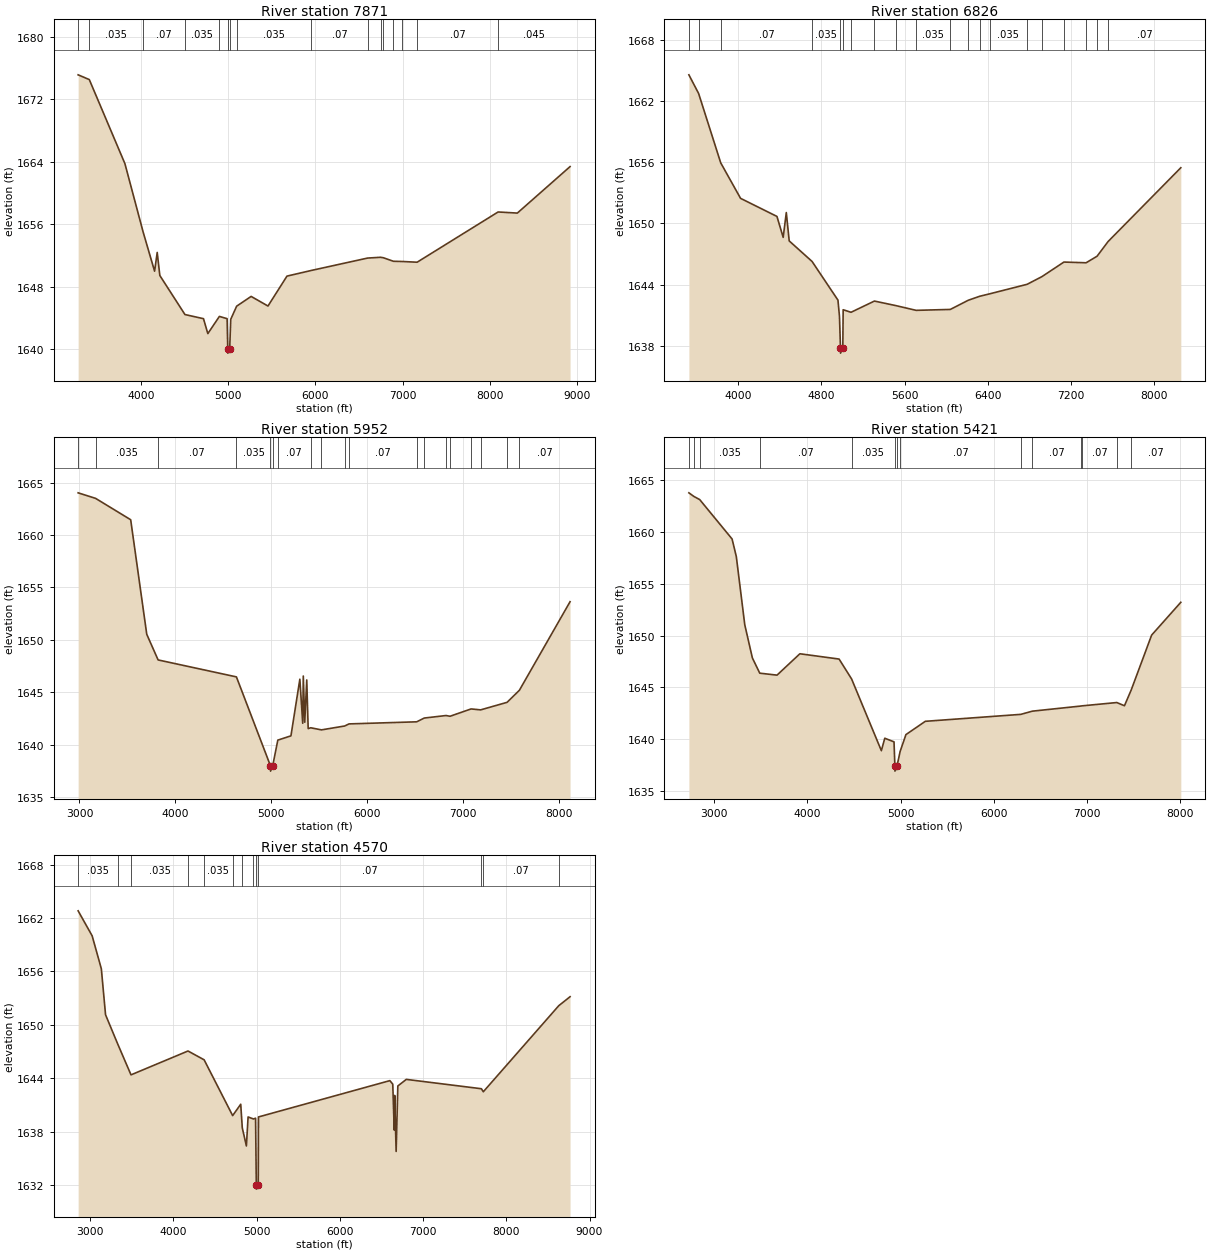
Type RM Length L Ch R = 1 ,7871    ,1045,1045,1045
BEGIN DESCRIPTION:
Mapping XS 6eddb46f
END DESCRIPTION:
XS GIS Cut Line= 4
      1562838.97      6893103.78      1562811.19      6891416.33
      1562651.47      6890860.77      1560186.62      6888562.56
#Sta/Elev= 30
  3282.3  1675.1  3410.2 1674.49  3818.2 1663.73  4026.6 1654.99  4158.2 1649.96
  4188.2 1652.36  4218.2 1649.41  4506.1 1644.41  4718.3 1643.88  4768.3 1641.97
  4900.6 1644.17  4989.1 1643.88  4996.7 1639.97  4997.2 1639.47  5018.5 1639.97
  5030.7  1643.8  5098.3 1645.48  5264.3 1646.73  5457.3  1645.5  5674.9 1649.33
  5952.2 1650.05  6598.6 1651.64  6746.5 1651.74  6779.4 1651.68  6894.4 1651.23
  6997.5  1651.2  7166.2 1651.11  8093.6 1657.54  8314.1  1657.4  8918.1 1663.35
#Mann= 16 ,-1 , 0
  3282.3     .07       0  3410.2    .035       0  4026.6     .07       0
  4506.1    .035       0  4900.6     .07       0  4996.7     .07       0
  5018.5     .07       0  5098.3    .035       0  5952.2     .07       0
  6598.6    .035       0  6746.5     .07       0  6779.4    .035       0
  6894.4     .07       0  6997.5    .035       0  7166.2     .07       0
  8093.6    .045       0
Bank Sta=4996.7,5018.5
XS Rating Curve= 0 ,0
Exp/Cntr=0.3,0.1

Type RM Length L Ch R = 1 ,6826    ,874,874,874
BEGIN DESCRIPTION:
Mapping XS 2078847a
END DESCRIPTION:
XS GIS Cut Line= 4
      1563684.45      6892635.04      1563621.95      6891273.97
      1563198.34      6890711.47       1561101.1      6889058.68
#Sta/Elev= 30
  3523.1 1664.56  3616.9 1662.73  3829.5 1655.94  4020.7 1652.46    4371 1650.69
  4431.1 1648.64  4461.1 1651.07  4489.1 1648.29  4709.2 1646.28  4958.6 1642.49
  4973.2 1640.88  4982.8  1637.8  4983.3  1637.3  5005.2  1637.8  5008.6 1641.55
  5084.5  1641.3  5309.5  1642.4  5518.2 1641.95  5711.3 1641.49  6040.5 1641.58
  6213.5 1642.48  6323.9 1642.87  6420.2 1643.11  6779.9 1644.04  6923.7  1644.8
  7134.2 1646.22  7347.8 1646.15  7453.4 1646.79  7560.6 1648.24    8260 1655.46
#Mann= 20 ,-1 , 0
  3523.1     .07       0  3616.9    .035       0  3829.5     .07       0
  4709.2    .035       0  4982.8    .035       0  5005.2    .035       0
  5084.5    .035       0  5309.5     .07       0  5518.2     .07       0
  5711.3    .035       0  6040.5    .035       0  6213.5     .07       0
  6323.9     .07       0  6420.2    .035       0  6779.9    .035       0
  6923.7     .07       0  7134.2    .035       0  7347.8     .07       0
  7453.4    .035       0  7560.6     .07       0
Bank Sta=4982.8,5005.2
XS Rating Curve= 0 ,0
Exp/Cntr=0.3,0.1

Type RM Length L Ch R = 1 ,5952    ,531,531,531
BEGIN DESCRIPTION:
Mapping XS 19a1390e
END DESCRIPTION:
XS GIS Cut Line= 3
       1565052.5      6892489.24       1564128.9      6890878.13
      1561413.64      6889044.81
#Sta/Elev= 30
  2986.6 1664.04    3169 1663.51    3535 1661.47  3702.7 1650.53  3821.1 1648.08
  4638.4 1646.46  4993.9 1637.96  4994.4 1637.46  5016.6 1637.96  5070.2 1640.42
  5207.3 1640.83  5300.2 1646.24  5330.2 1642.03  5336.2 1646.54  5351.2 1642.13
  5372.2 1646.17  5387.1 1641.52  5413.5  1641.6  5526.1  1641.4  5767.7 1641.77
  5813.7 1641.97  6519.7 1642.17  6598.6 1642.53  6825.5 1642.77  6867.4  1642.7
    7087  1643.4  7186.8 1643.31  7462.4 1644.03    7591 1645.18  8119.9 1653.64
#Mann= 19 ,-1 , 0
  2986.6     .07       0    3169    .035       0  3821.1     .07       0
  4638.4    .035       0  4993.9    .035       0  5016.6    .035       0
  5070.2     .07       0  5413.5    .035       0  5526.1     .07       0
  5767.7    .035       0  5813.7     .07       0  6519.7    .035       0
  6598.6     .07       0  6825.5    .035       0  6867.4     .07       0
    7087    .035       0  7186.8     .07       0  7462.4    .035       0
    7591     .07       0
Bank Sta=4993.9,5016.6
XS Rating Curve= 0 ,0
Exp/Cntr=0.3,0.1

Type RM Length L Ch R = 1 ,5421    ,851,851,851
BEGIN DESCRIPTION:
Mapping XS f0a9e8da
END DESCRIPTION:
XS GIS Cut Line= 4
      1565128.91      6892412.88      1564267.79       6890607.3
      1563969.17      6890239.24      1561455.28      6888996.19
#Sta/Elev= 30
  2728.8 1663.75  2782.6  1663.4  2844.7  1663.1  3192.4  1659.3  3237.8  1657.6
  3328.6 1651.03    3410 1647.84  3489.3 1646.37  3674.5 1646.18  3919.7 1648.24
  4340.7 1647.73  4474.9 1645.81  4794.2  1638.9  4830.8  1640.1    4930 1639.75
  4939.3 1637.43  4939.8 1636.93  4962.3 1637.43  4995.7 1638.83  5057.8 1640.45
  5265.8 1641.73  6290.5  1642.4  6415.3 1642.71  6932.7  1643.2    6948 1643.22
  7320.6 1643.54  7402.8 1643.23  7475.3 1644.75  7694.5 1650.04  8007.6  1653.2
#Mann= 14 ,-1 , 0
  2728.8    .035       0  2782.6     .07       0  2844.7    .035       0
  3489.3     .07       0  4474.9    .035       0  4939.3     .07       0
  4962.3    .035       0  4995.7     .07       0  6290.5    .035       0
  6415.3     .07       0  6932.7    .035       0    6948     .07       0
  7320.6    .035       0  7475.3     .07       0
Bank Sta=4939.3,4962.3
XS Rating Curve= 0 ,0
Exp/Cntr=0.3,0.1

Type RM Length L Ch R = 1 ,4570    ,0,0,0
BEGIN DESCRIPTION:
Mapping XS 94459531
END DESCRIPTION:
XS GIS Cut Line= 4
      1565156.67      6892253.13      1564809.45      6890142.02
      1564212.23      6889426.74       1561420.6      6888905.92
#Sta/Elev= 30
  2854.8  1662.8  3023.2 1659.99  3133.6 1656.29  3184.3 1651.12  3330.8 1647.83
  3490.1 1644.37    4175 1647.05  4368.8 1646.06  4711.6 1639.79  4808.5 1641.07
  4827.3 1638.41  4876.7 1636.38    4897 1639.64  4961.7 1639.41    4987  1639.5
  4995.8 1632.03  4996.3 1631.53  5019.3 1632.03  5021.8 1639.64  6600.3 1643.72
  6635.4 1643.33    6653 1638.17  6658.1 1642.06    6676 1635.77  6696.4 1643.12
  6798.1 1643.86  7700.5 1642.81  7723.5 1642.47  8630.2 1652.14  8765.9 1653.15
#Mann= 13 ,-1 , 0
  2854.8    .035       0  3330.8     .07       0  3490.1    .035       0
    4175     .07       0  4368.8    .035       0  4711.6     .07       0
  4827.3    .035       0  4961.7     .07       0  4995.8     .07       0
  5019.3     .07       0  7700.5    .035       0  7723.5     .07       0
  8630.2    .035       0
Bank Sta=4995.8,5019.3
XS Rating Curve= 0 ,0
Exp/Cntr=0.3,0.1

Chan Stop Cuts=-1
Use User Specified Reach Order=0
Composite Channel Slope=5