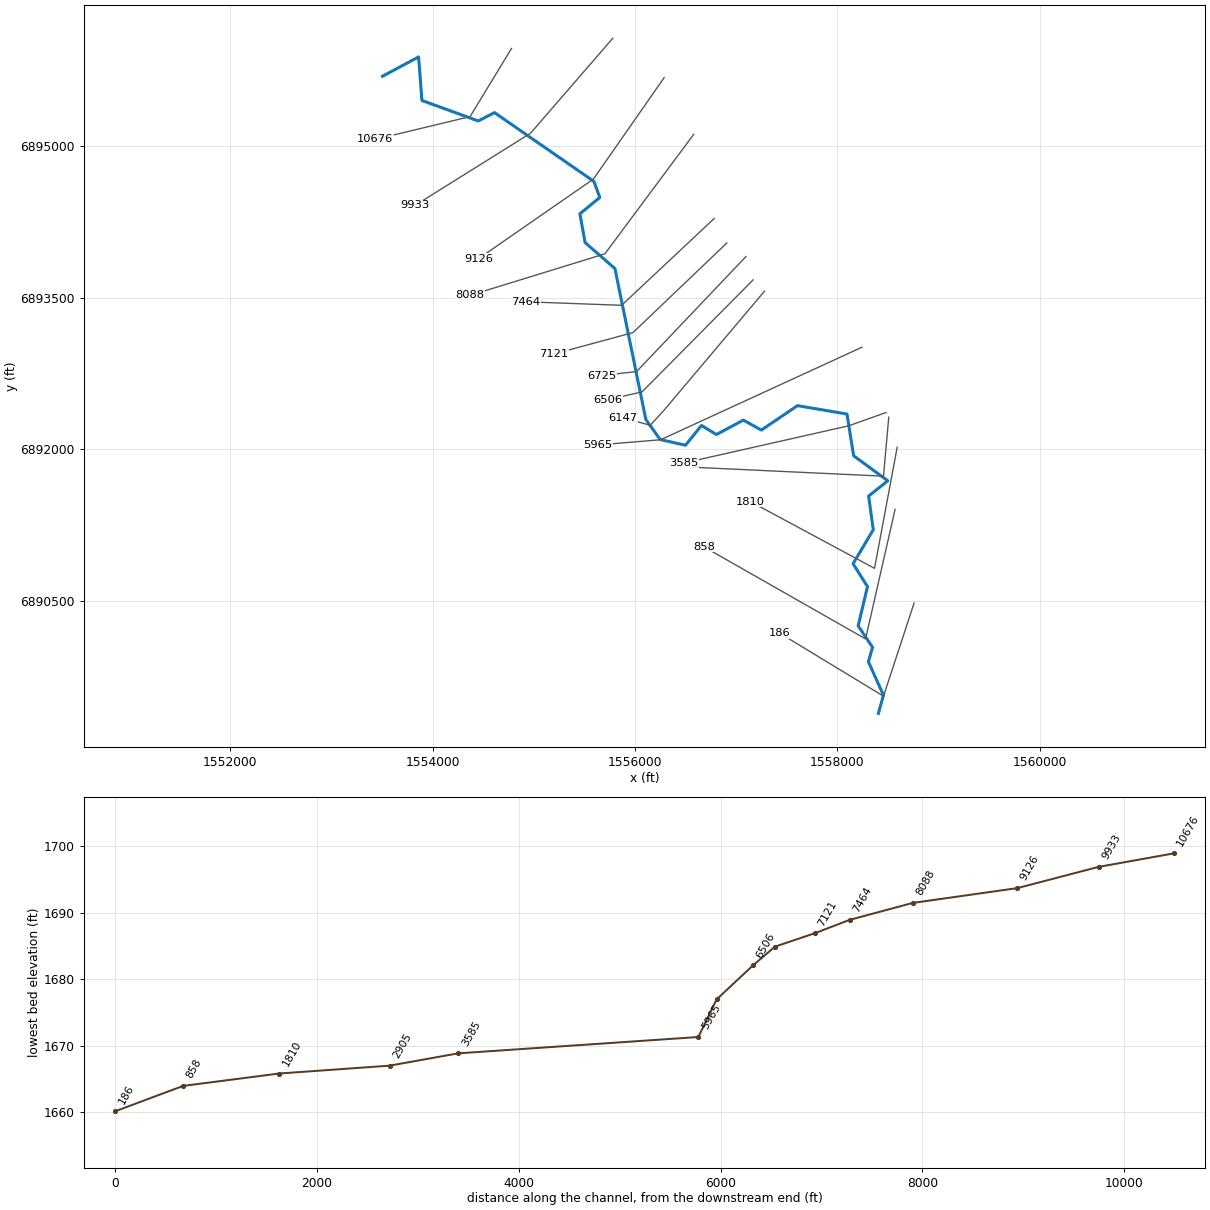
--- MULBERRY CREEK TRIBUTARY 6_1.prj (project) ---

Proj Title=MULBERRY CREEK TRIBUTARY 6_1 Base Level Engineering
Current Plan=p01
Default Exp/Contr=0.3,0.1
English Units
Geom File=g01
Flow File=f01
Plan File=p01
BEGIN DESCRIPTION:
MULBERRY CREEK TRIBUTARY 6_1
END DESCRIPTION:

--- MULBERRY CREEK TRIBUTARY 6_1.p01 (plan) ---

Plan Title=Multiple Run
Short Identifier=Multiple
Geom File=g01
Flow File=f01
Subcritical Flow
K Sum by GR= 0
Std Step Tol= 0.01
Critical Tol= 0.01
Num of Std Step Trials= 20
Max Error Tol= 0.3
Flow Tol Ratio= 0.001
Split Flow NTrial= 30
Split Flow Tol= 0.02
Split Flow Ratio= 0.02
Log Output Level= 0
Friction Slope Method= 1
Unsteady Friction Slope Method= 2
Unsteady Bridges Friction Slope Method= 1
Parabolic Critical Depth
Global Vel Dist=  1 , 1 , 1
Global Log Level= 0
CheckData=True
Encroach Param= -1, 0, 0, 0
BEGIN DESCRIPTION:
Multiple Run
END DESCRIPTION:

--- MULBERRY CREEK TRIBUTARY 6_1.f01 (steady flow) ---

Flow Title=Multiple
Number of Profiles=7
Profile Names=10-year,25-year,50-year,1pct_min,100-year,1pct_plu,500-year
River Rch & RM= MULBERRY CREEK T,Reach-1,10676
     183     245     293     175     349     697     501
River Rch & RM= MULBERRY CREEK T,Reach-1,3585
     266     364     442     267     534    1065     787
Boundary for River Rch & Prof#=MULBERRY CREEK T,Reach-1,1
Up Type=0
Dn Type=3
Dn Slope=0.005
Boundary for River Rch & Prof#=MULBERRY CREEK T,Reach-1,2
Up Type=0
Dn Type=3
Dn Slope=0.005
Boundary for River Rch & Prof#=MULBERRY CREEK T,Reach-1,3
Up Type=0
Dn Type=3
Dn Slope=0.005
Boundary for River Rch & Prof#=MULBERRY CREEK T,Reach-1,4
Up Type=0
Dn Type=3
Dn Slope=0.005
Boundary for River Rch & Prof#=MULBERRY CREEK T,Reach-1,5
Up Type=0
Dn Type=3
Dn Slope=0.005
Boundary for River Rch & Prof#=MULBERRY CREEK T,Reach-1,6
Up Type=0
Dn Type=3
Dn Slope=0.005
Boundary for River Rch & Prof#=MULBERRY CREEK T,Reach-1,7
Up Type=0
Dn Type=3
Dn Slope=0.005

--- MULBERRY CREEK TRIBUTARY 6_1.g01 (geometry) ---

Geom Title=Existing Conditions

River Reach=MULBERRY CREEK T,Reach-1
Reach XY= 30
      1553505.00      6895688.00      1553862.00      6895879.18
      1553894.57      6895448.75      1554451.69      6895246.02
      1554611.61      6895328.61      1555594.37      6894648.00
      1555651.88      6894489.62      1555455.53      6894327.53
      1555507.06      6894043.46      1555801.83      6893786.35
      1556107.24      6892293.93      1556248.79      6892095.81
      1556499.15      6892039.54      1556656.64      6892234.91
      1556804.92      6892145.30      1557070.41      6892287.98
      1557248.95      6892189.59      1557604.92      6892430.64
      1558094.62      6892348.11      1558160.36      6891935.30
      1558497.94      6891688.00      1558308.44      6891536.75
      1558354.68      6891204.04      1558154.59      6890867.87
      1558297.38      6890641.33      1558205.08      6890253.39
      1558347.19      6890041.41      1558306.09      6889898.55
      1558455.10      6889567.90      1558405.00      6889388.00

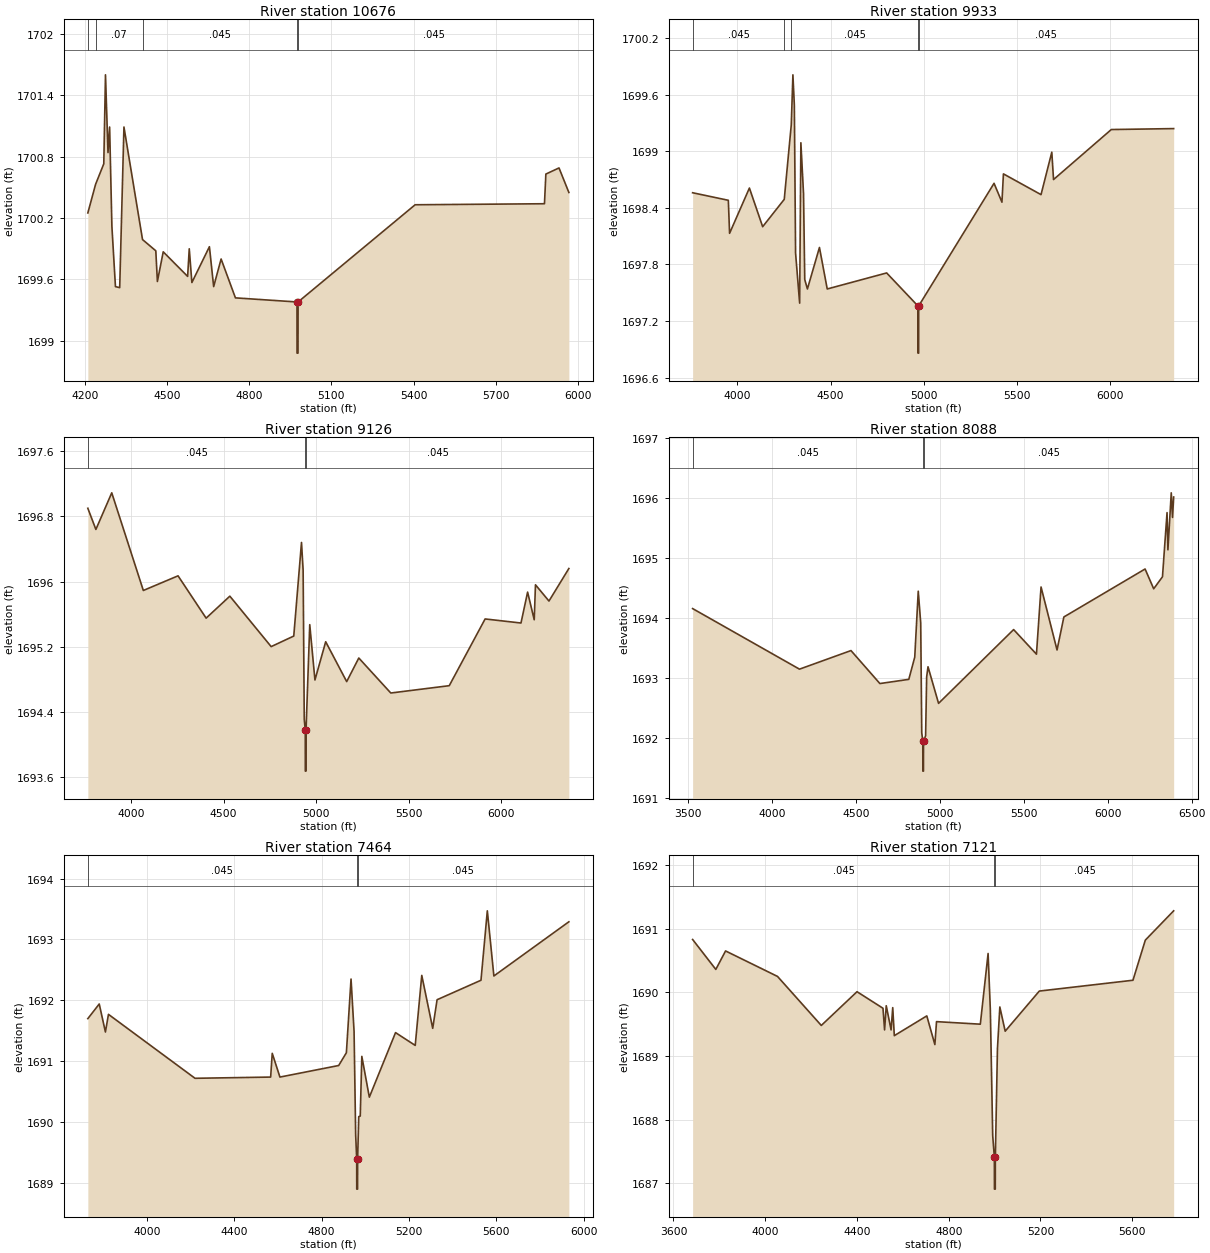
Type RM Length L Ch R = 1,10676,743,743,743
BEGIN DESCRIPTION:
MULBERRY CREEK TRIBUTARY 6_1 6.0
END DESCRIPTION:
XS GIS Cut Line= 3
      1554780.01      6895963.01      1554370.42      6895288.89
      1553429.97      6895062.99
#Sta/Elev= 30
  4211.2 1700.25  4239.5 1700.53  4269.4 1700.73  4275.6 1701.60  4284.8 1700.84
  4290.7 1701.09  4299.0 1700.12  4312.0 1699.53  4327.5 1699.52  4343.0 1701.09
  4410.8 1699.99  4459.3 1699.88  4465.1 1699.58  4486.4 1699.87  4575.5 1699.63
  4581.4 1699.90  4591.0 1699.57  4655.0 1699.92  4670.5 1699.53  4697.7 1699.80
  4750.0 1699.42  4974.7 1699.38  4974.9 1698.88  4978.4 1698.88  4978.7 1699.38
  5406.0 1700.33  5878.1 1700.34  5883.2 1700.63  5931.2 1700.69  5967.2 1700.45
#Mann=5,-1,0
  4211.2   0.045       0  4239.5    0.07       0  4410.8   0.045       0
  4974.7   0.045       0  4978.7   0.045       0
Bank Sta=4974.7,4978.7
Exp/Cntr=0.3,0.1

Type RM Length L Ch R = 1,9933,807,807,807
BEGIN DESCRIPTION:
MULBERRY CREEK TRIBUTARY 6_1 5.0
END DESCRIPTION:
XS GIS Cut Line= 3
      1555779.98      6896062.98      1554968.32      6895124.87
      1553829.99      6894412.99
#Sta/Elev= 30
  3759.5 1698.56  3951.2 1698.48  3958.0 1698.13  4064.4 1698.61  4135.6 1698.20
  4251.5 1698.49  4289.2 1699.28  4298.0 1699.81  4305.7 1699.49  4312.3 1697.92
  4334.2 1697.39  4340.8 1699.09  4355.0 1698.55  4361.6 1697.64  4375.9 1697.54
  4440.5 1697.98  4482.3 1697.54  4801.4 1697.71  4969.4 1697.36  4969.7 1696.86
  4973.2 1696.86  4973.4 1697.36  5378.1 1698.66  5420.5 1698.46  5428.5 1698.76
  5630.4 1698.54  5688.2 1698.99  5697.6 1698.70  6007.7 1699.23  6342.6 1699.24
#Mann=5,-1,0
  3759.5   0.045       0  4251.5    0.07       0  4289.2   0.045       0
  4969.4   0.045       0  4973.4   0.045       0
Bank Sta=4969.4,4973.4
Exp/Cntr=0.3,0.1

Type RM Length L Ch R = 1,9126,1038,1038,1038
BEGIN DESCRIPTION:
Mapping XS 75264bed
END DESCRIPTION:
XS GIS Cut Line= 3
      1556288.16      6895674.05      1555589.38      6894671.46
      1554456.60      6893885.89
#Sta/Elev= 30
  3765.8 1696.90  3809.3 1696.64  3895.1 1697.09  4065.8 1695.89  4253.5 1696.07
  4405.3 1695.55  4533.5 1695.82  4756.9 1695.20  4879.1 1695.33  4920.9 1696.48
  4929.7 1696.14  4935.8 1694.31  4941.3 1694.17  4941.5 1693.67  4945.1 1693.67
  4945.4 1694.17  4965.5 1695.47  4993.6 1694.79  5051.7 1695.26  5165.2 1694.77
  5230.7 1695.06  5403.6 1694.63  5719.7 1694.72  5913.6 1695.54  6107.5 1695.49
  6143.3 1695.87  6179.1 1695.53  6185.8 1695.96  6258.8 1695.76  6366.4 1696.16
#Mann=3,-1,0
  3765.8   0.045       0  4941.3   0.045       0  4945.4   0.045       0
Bank Sta=4941.3,4945.4
Exp/Cntr=0.3,0.1

Type RM Length L Ch R = 1,8088,624,624,624
BEGIN DESCRIPTION:
MULBERRY CREEK TRIBUTARY 6_1 4.0
END DESCRIPTION:
XS GIS Cut Line= 3
      1556580.02      6895113.03      1555702.47      6893931.97
      1554371.37      6893521.68
#Sta/Elev= 30
  3528.6 1694.15  4164.9 1693.14  4471.5 1693.45  4643.7 1692.90  4815.8 1692.97
  4851.2 1693.34  4872.1 1694.44  4886.7 1693.91  4892.9 1692.08  4899.2 1691.94
  4899.5 1691.44  4903.1 1691.44  4903.4 1691.94  4915.9 1692.03  4922.1 1693.01
  4930.2 1693.18  4993.0 1692.57  5440.0 1693.80  5575.9 1693.39  5603.3 1694.51
  5698.5 1693.46  5739.2 1694.01  6222.8 1694.81  6274.0 1694.48  6326.3 1694.68
  6353.5 1695.75  6358.7 1695.13  6378.6 1696.08  6386.1 1695.67  6392.9 1696.01
#Mann=3,-1,0
  3528.6   0.045       0  4899.2   0.045       0  4903.4   0.045       0
Bank Sta=4899.2,4903.4
Exp/Cntr=0.3,0.1

Type RM Length L Ch R = 1,7464,343,343,343
BEGIN DESCRIPTION:
Mapping XS 571fd288
END DESCRIPTION:
XS GIS Cut Line= 3
      1556783.86      6894282.60      1555868.03      6893423.19
      1554921.88      6893457.92
#Sta/Elev= 30
  3729.8 1691.70  3782.0 1691.94  3810.3 1691.48  3824.2 1691.77  4220.6 1690.72
  4566.9 1690.74  4574.2 1691.13  4609.4 1690.74  4878.5 1690.93  4913.7 1691.14
  4935.0 1692.35  4948.9 1691.49  4956.2 1689.79  4960.9 1689.40  4961.2 1688.90
  4964.9 1688.90  4965.2 1689.40  4970.3 1690.09  4977.2 1690.10  4984.4 1691.08
  5018.8 1690.41  5138.8 1691.47  5228.9 1691.26  5258.9 1692.41  5309.0 1691.54
  5329.0 1692.01  5530.0 1692.33  5559.1 1693.47  5589.1 1692.40  5932.5 1693.29
#Mann=3,-1,0
  3729.8   0.045       0  4960.9   0.045       0  4965.2   0.045       0
Bank Sta=4960.9,4965.2
Exp/Cntr=0.3,0.1

Type RM Length L Ch R = 1,7121,396,396,396
BEGIN DESCRIPTION:
Mapping XS ead132fa
END DESCRIPTION:
XS GIS Cut Line= 3
      1556907.31      6894038.83      1555980.21      6893153.39
      1555193.78      6892939.86
#Sta/Elev= 30
  3683.6 1690.83  3784.7 1690.36  3827.2 1690.65  4053.6 1690.25  4244.5 1689.48
  4400.2 1690.01  4513.4 1689.75  4520.4 1689.41  4527.6 1689.79  4548.7 1689.41
  4555.9 1689.76  4562.8 1689.32  4704.4 1689.63  4739.6 1689.18  4746.8 1689.54
  4937.7 1689.50  4971.6 1690.61  4981.4 1689.72  4991.7 1687.75  4998.9 1687.41
  4999.2 1686.91  5002.9 1686.91  5003.2 1687.41  5012.4 1689.12  5022.8 1689.77
  5046.1 1689.39  5194.9 1690.02  5603.1 1690.19  5657.0 1690.82  5780.5 1691.28
#Mann=3,-1,0
  3683.6   0.045       0  4998.9   0.045       0  5003.2   0.045       0
Bank Sta=4998.9,5003.2
Exp/Cntr=0.3,0.1

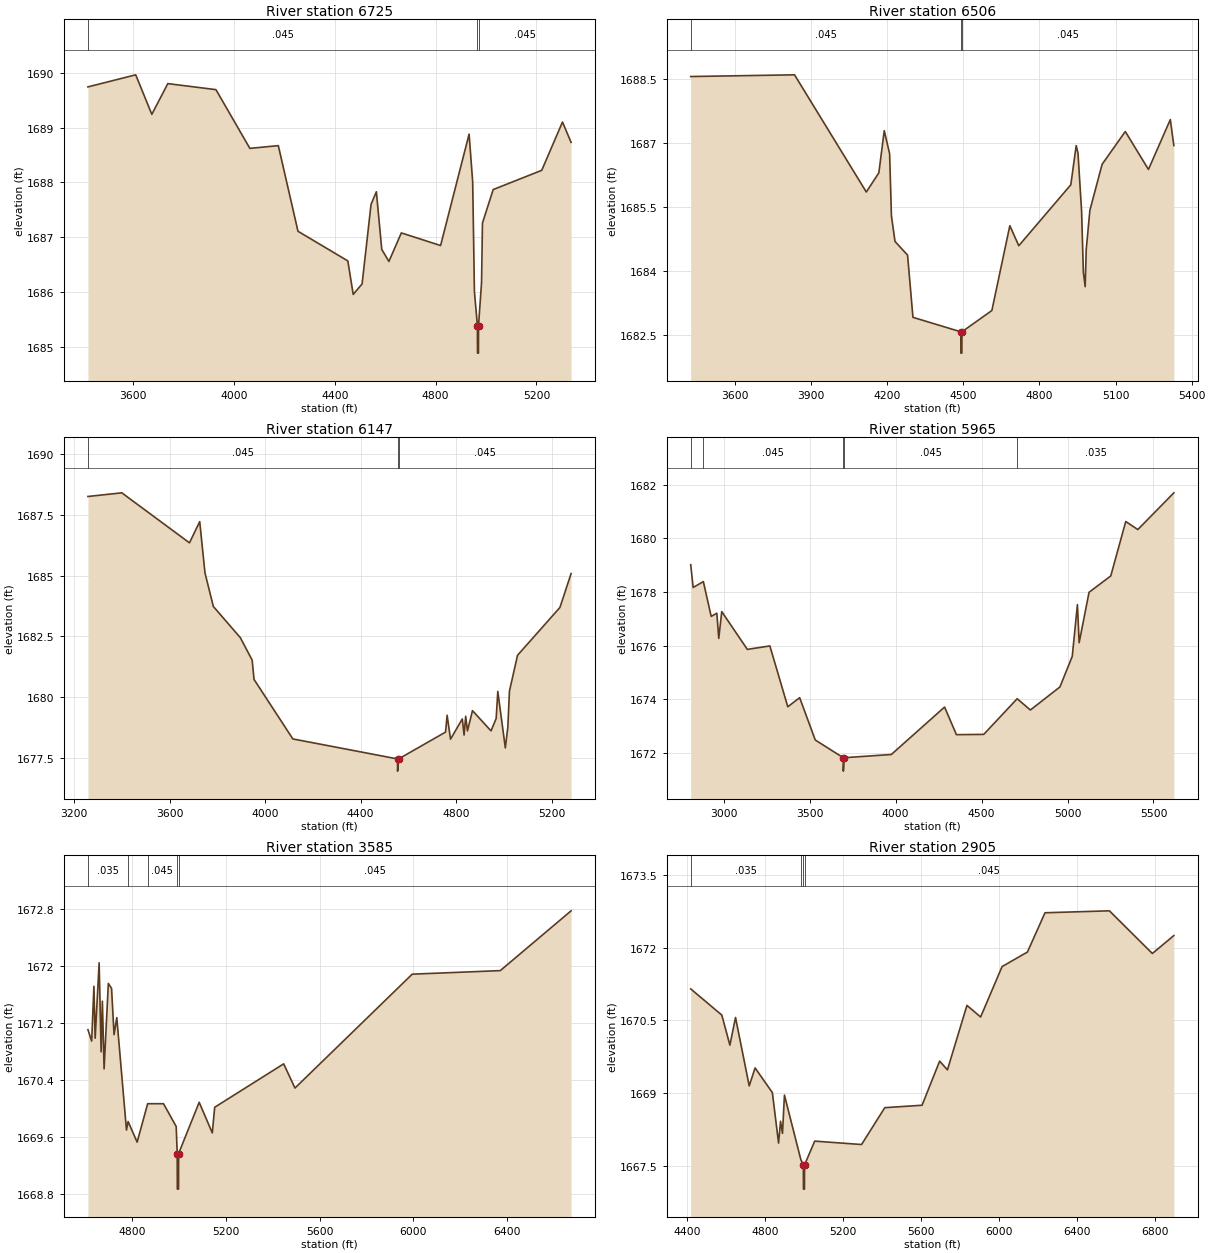
Type RM Length L Ch R = 1,6725,219,219,219
BEGIN DESCRIPTION:
Mapping XS c24b85dd
END DESCRIPTION:
XS GIS Cut Line= 3
      1557096.30      6893904.94      1556015.59      6892767.81
      1555669.23      6892728.85
#Sta/Elev= 30
  3420.3 1689.74  3609.9 1689.96  3673.8 1689.24  3737.3 1689.80  3928.2 1689.69
  4062.9 1688.62  4175.8 1688.67  4253.8 1687.11  4451.6 1686.57  4473.0 1685.96
  4508.2 1686.15  4543.8 1687.60  4564.9 1687.83  4586.3 1686.78  4614.6 1686.56
  4664.0 1687.08  4819.7 1686.85  4932.9 1688.88  4947.1 1688.01  4954.0 1686.01
  4965.9 1685.39  4966.2 1684.89  4970.0 1684.89  4970.3 1685.39  4982.3 1686.18
  4985.9 1687.26  5028.5 1687.87  5221.1 1688.22  5303.5 1689.10  5337.6 1688.73
#Mann=3,-1,0
  3420.3   0.045       0  4965.9   0.045       0  4970.3   0.045       0
Bank Sta=4965.9,4970.3
Exp/Cntr=0.3,0.1

Type RM Length L Ch R = 1,6506,359,359,359
BEGIN DESCRIPTION:
Mapping XS f6582dbc
END DESCRIPTION:
XS GIS Cut Line= 3
      1557167.16      6893674.68      1556069.97      6892567.07
      1555733.17      6892490.68
#Sta/Elev= 30
  3425.4 1688.56  3834.7 1688.60  4117.6 1685.85  4167.0 1686.30  4188.3 1687.29
  4209.4 1686.75  4216.6 1685.29  4230.7 1684.69  4280.2 1684.37  4301.4 1682.91
  4490.1 1682.57  4490.4 1682.07  4494.2 1682.07  4494.5 1682.57  4612.5 1683.07
  4683.3 1685.06  4718.6 1684.59  4923.7 1686.02  4944.9 1686.94  4952.0 1686.76
  4966.1 1685.41  4973.1 1683.97  4980.3 1683.63  4984.4 1684.50  4998.8 1685.42
  5047.0 1686.50  5138.4 1687.27  5229.7 1686.38  5315.9 1687.55  5329.8 1686.94
#Mann=3,-1,0
  3425.4   0.045       0  4490.1   0.045       0  4494.5   0.045       0
Bank Sta=4490.1,4494.5
Exp/Cntr=0.3,0.1

Type RM Length L Ch R = 1,6147,182,182,182
BEGIN DESCRIPTION:
Mapping XS 2fa8933e
END DESCRIPTION:
XS GIS Cut Line= 4
      1557280.02      6893563.02      1556287.77      6892386.77
      1556150.78      6892236.25      1555880.04      6892312.99
#Sta/Elev= 30
  3257.6 1688.24  3399.4 1688.39  3682.9 1686.34  3725.8 1687.21  3747.8 1685.11
  3782.9 1683.73  3896.1 1682.45  3945.5 1681.53  3953.3 1680.74  4115.9 1678.30
  4554.4 1677.48  4554.7 1676.98  4558.8 1677.48  4755.5 1678.58  4762.1 1679.27
  4776.4 1678.29  4825.7 1679.12  4833.2 1678.46  4839.9 1679.23  4847.4 1678.63
  4868.3 1679.46  4946.0 1678.63  4967.6 1679.14  4974.4 1680.25  5006.0 1677.93
  5016.4 1678.78  5023.2 1680.26  5057.1 1681.73  5234.7 1683.69  5281.4 1685.08
#Mann=3,-1,0
  3257.6   0.045       0  4554.4   0.045       0  4558.8   0.045       0
Bank Sta=4554.4,4558.8
Exp/Cntr=0.3,0.1

Type RM Length L Ch R = 1,5965,2380,2380,2380
BEGIN DESCRIPTION:
MULBERRY CREEK TRIBUTARY 6_1 2.0
END DESCRIPTION:
XS GIS Cut Line= 3
      1558243.18      6893008.79      1556252.54      6892093.46
      1555636.21      6892042.82
#Sta/Elev= 30
  2809.0 1679.02  2823.2 1678.17  2882.6 1678.39  2928.1 1677.09  2961.0 1677.21
  2972.1 1676.27  2989.5 1677.27  3138.4 1675.86  3269.3 1675.99  3373.6 1673.72
  3442.5 1674.06  3533.4 1672.48  3696.3 1671.82  3696.6 1671.32  3700.7 1671.82
  3975.5 1671.94  4285.2 1673.71  4354.1 1672.68  4513.0 1672.69  4707.3 1674.02
  4784.2 1673.60  4956.0 1674.46  5027.6 1675.60  5057.7 1677.53  5067.8 1676.11
  5125.3 1677.99  5251.6 1678.60  5338.7 1680.63  5408.9 1680.33  5618.4 1681.70
#Mann=5,-1,0
  2809.0    0.07       0  2882.6   0.045       0  3696.3   0.035       0
  3700.7   0.045       0  4707.3   0.035       0
Bank Sta=3696.3,3700.7
Exp/Cntr=0.3,0.1

Type RM Length L Ch R = 1,3585,680,680,680
BEGIN DESCRIPTION:
Mapping XS 097e1773
END DESCRIPTION:
XS GIS Cut Line= 3
      1558479.99      6892363.00      1558113.20      6892231.97
      1556479.96      6891862.99
#Sta/Elev= 30
  4610.5 1671.11  4626.4 1670.95  4636.0 1671.72  4641.3 1670.99  4658.3 1672.05
  4666.8 1670.80  4672.1 1671.51  4679.5 1670.56  4697.6 1671.76  4711.4 1671.69
  4722.0 1671.04  4733.7 1671.28  4775.1 1669.70  4782.0 1669.82  4820.7 1669.53
  4865.5 1670.07  4933.3 1670.07  4987.5 1669.75  4991.8 1669.37  4992.3 1668.87
  4997.4 1668.87  4997.9 1669.37  5085.7 1670.09  5141.7 1669.66  5151.9 1670.02
  5446.6 1670.63  5494.9 1670.29  5995.7 1671.89  6371.9 1671.94  6674.4 1672.78
#Mann=5,-1,0
  4610.5   0.035       0  4782.0    0.07       0  4865.5   0.045       0
  4991.8   0.045       0  4997.9   0.045       0
Bank Sta=4991.8,4997.9
Exp/Cntr=0.3,0.1

Type RM Length L Ch R = 1,2905,1095,1095,1095
BEGIN DESCRIPTION:
Mapping XS b0bfb776
END DESCRIPTION:
XS GIS Cut Line= 3
      1558507.55      6892316.94      1558455.46      6891733.63
      1556564.87      6891822.17
#Sta/Elev= 30
  4418.7 1671.15  4578.3 1670.61  4619.7 1669.99  4648.6 1670.56  4718.8 1669.15
  4749.0 1669.52  4837.6 1669.01  4869.4 1667.97  4879.5 1668.42  4889.5 1668.17
  4899.5 1668.96  4983.5 1667.63  4996.5 1667.52  4997.0 1667.02  5002.2 1667.02
  5002.7 1667.52  5054.8 1668.01  5295.1 1667.94  5414.3 1668.70  5605.5 1668.75
  5695.6 1669.66  5735.6 1669.48  5835.7 1670.81  5905.8 1670.57  6015.9 1671.61
  6146.0 1671.91  6236.1 1672.72  6566.5 1672.76  6786.7 1671.88  6897.0 1672.25
#Mann=4,-1,0
  4418.7   0.035       0  4983.5   0.045       0  4996.5   0.045       0
  5002.7   0.045       0
Bank Sta=4996.5,5002.7
Exp/Cntr=0.3,0.1

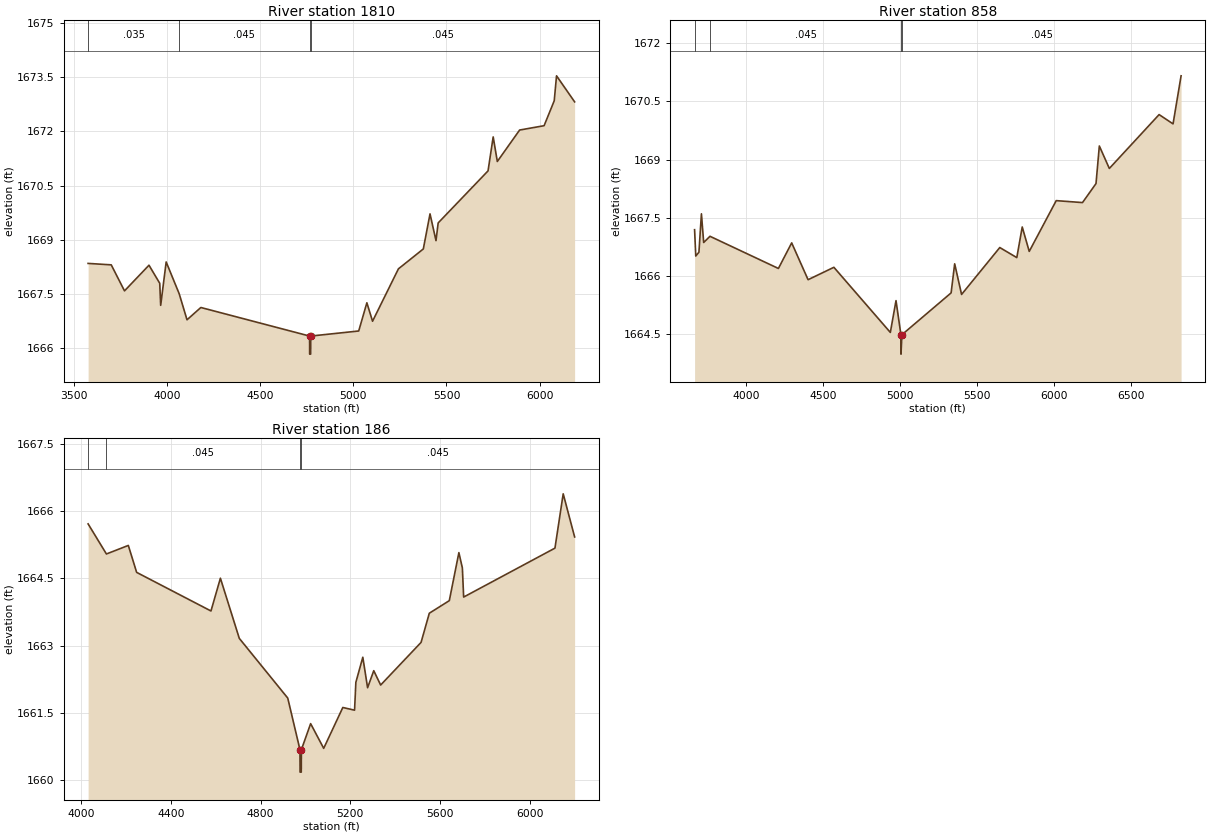
Type RM Length L Ch R = 1,1810,952,952,952
BEGIN DESCRIPTION:
Mapping XS 8ba5d0f8
END DESCRIPTION:
XS GIS Cut Line= 3
      1558590.87      6892020.05      1558366.92      6890822.18
      1557139.49      6891482.70
#Sta/Elev= 30
  3575.8 1668.35  3700.0 1668.31  3771.2 1667.59  3902.7 1668.30  3960.4 1667.80
  3965.5 1667.19  3995.0 1668.39  4064.9 1667.51  4106.9 1666.79  4181.2 1667.13
  4765.0 1666.34  4765.5 1665.84  4770.8 1665.84  4771.3 1666.34  5028.9 1666.48
  5072.7 1667.26  5103.2 1666.75  5242.2 1668.20  5375.8 1668.75  5411.8 1669.72
  5443.9 1668.98  5455.6 1669.47  5723.4 1670.91  5751.0 1671.85  5773.2 1671.17
  5893.0 1672.04  6024.4 1672.16  6078.8 1672.85  6091.2 1673.54  6188.3 1672.82
#Mann=4,-1,0
  3575.8   0.035       0  4064.9   0.045       0  4765.0   0.045       0
  4771.3   0.045       0
Bank Sta=4765,4771.3
Exp/Cntr=0.3,0.1

Type RM Length L Ch R = 1,858,672,672,672
BEGIN DESCRIPTION:
Mapping XS b85040b9
END DESCRIPTION:
XS GIS Cut Line= 3
      1558570.05      6891405.50      1558278.38      6890124.26
      1556679.70      6891035.56
#Sta/Elev= 30
  3667.4 1667.19  3675.1 1666.51  3695.6 1666.61  3711.8 1667.60  3726.4 1666.86
  3767.2 1667.02  4210.9 1666.19  4297.0 1666.85  4403.3 1665.90  4570.6 1666.22
  4936.6 1664.54  4973.3 1665.36  5005.2 1664.48  5005.7 1663.98  5011.5 1664.48
  5330.6 1665.56  5353.7 1666.31  5398.4 1665.52  5646.2 1666.73  5756.5 1666.47
  5791.7 1667.26  5837.1 1666.63  6012.1 1667.94  6182.4 1667.89  6270.0 1668.38
  6291.6 1669.35  6356.4 1668.77  6679.1 1670.16  6769.5 1669.92  6821.6 1671.16
#Mann=4,-1,0
  3667.4   0.035       0  3767.2   0.045       0  5005.2   0.045       0
  5011.5   0.045       0
Bank Sta=5005.2,5011.5
Exp/Cntr=0.3,0.1

Type RM Length L Ch R = 1,186,0,0,0
BEGIN DESCRIPTION:
MULBERRY CREEK TRIBUTARY 6_1 1.0
END DESCRIPTION:
XS GIS Cut Line= 3
      1558757.54      6890478.39      1558455.60      6889558.05
      1557429.72      6890181.37
#Sta/Elev= 30
  4031.4 1665.71  4113.0 1665.04  4210.7 1665.23  4247.8 1664.63  4579.1 1663.77
  4621.2 1664.50  4705.4 1663.16  4921.4 1661.83  4975.9 1660.68  4976.4 1660.18
  4981.7 1660.18  4982.2 1660.68  5023.5 1661.26  5081.7 1660.71  5167.0 1661.62
  5219.3 1661.56  5225.1 1662.18  5256.1 1662.74  5277.4 1662.06  5304.9 1662.44
  5335.6 1662.12  5515.8 1663.07  5552.6 1663.72  5641.7 1664.00  5684.4 1665.07
  5699.9 1664.73  5705.7 1664.08  6112.7 1665.17  6149.5 1666.38  6200.4 1665.42
#Mann=4,-1,0
  4031.4   0.035       0  4113.0   0.045       0  4975.9   0.045       0
  4982.2   0.045       0
Bank Sta=4975.9,4982.2
Exp/Cntr=0.3,0.1

Chan Stop Cuts=-1