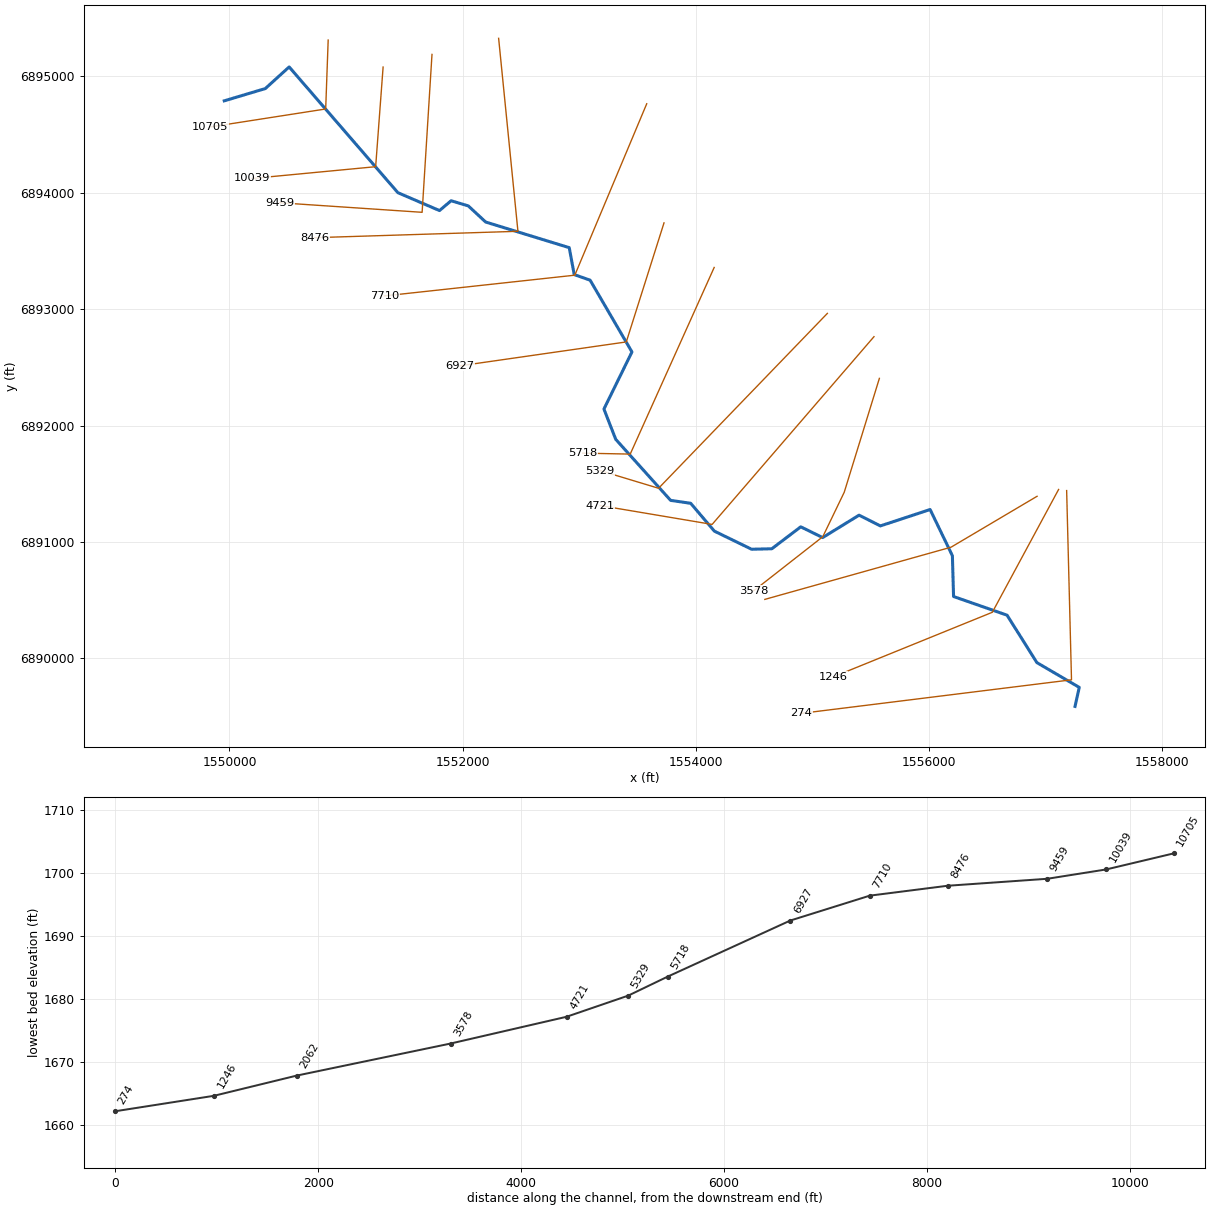
--- MULBERRY CREEK TRIBUTARY 6_2.prj (project) ---

Proj Title=MULBERRY CREEK TRIBUTARY 6_2 Base Level Engineering
Current Plan=p01
Default Exp/Contr=0.3,0.1
English Units
Geom File=g01
Flow File=f01
Plan File=p01
BEGIN DESCRIPTION:
MULBERRY CREEK TRIBUTARY 6_2
END DESCRIPTION:

--- MULBERRY CREEK TRIBUTARY 6_2.p01 (plan) ---

Plan Title=Multiple Run
Short Identifier=Multiple
Geom File=g01
Flow File=f01
Subcritical Flow
K Sum by GR= 0
Std Step Tol= 0.01
Critical Tol= 0.01
Num of Std Step Trials= 20
Max Error Tol= 0.3
Flow Tol Ratio= 0.001
Split Flow NTrial= 30
Split Flow Tol= 0.02
Split Flow Ratio= 0.02
Log Output Level= 0
Friction Slope Method= 1
Unsteady Friction Slope Method= 2
Unsteady Bridges Friction Slope Method= 1
Parabolic Critical Depth
Global Vel Dist=  1 , 1 , 1
Global Log Level= 0
CheckData=True
Encroach Param= -1, 0, 0, 0
BEGIN DESCRIPTION:
Multiple Run
END DESCRIPTION:

--- MULBERRY CREEK TRIBUTARY 6_2.f01 (steady flow) ---

Flow Title=Multiple
Number of Profiles=7
Profile Names=10-year,25-year,50-year,1pct_min,100-year,1pct_plu,500-year
River Rch & RM= MULBERRY CREEK T,Reach-1,10705
     130     170     201     118     236     470     329
River Rch & RM= MULBERRY CREEK T,Reach-1,10039
     224     304     368     221     442     882     646
Boundary for River Rch & Prof#=MULBERRY CREEK T,Reach-1,1
Up Type=0
Dn Type=3
Dn Slope=0.005
Boundary for River Rch & Prof#=MULBERRY CREEK T,Reach-1,2
Up Type=0
Dn Type=3
Dn Slope=0.005
Boundary for River Rch & Prof#=MULBERRY CREEK T,Reach-1,3
Up Type=0
Dn Type=3
Dn Slope=0.005
Boundary for River Rch & Prof#=MULBERRY CREEK T,Reach-1,4
Up Type=0
Dn Type=3
Dn Slope=0.005
Boundary for River Rch & Prof#=MULBERRY CREEK T,Reach-1,5
Up Type=0
Dn Type=3
Dn Slope=0.005
Boundary for River Rch & Prof#=MULBERRY CREEK T,Reach-1,6
Up Type=0
Dn Type=3
Dn Slope=0.005
Boundary for River Rch & Prof#=MULBERRY CREEK T,Reach-1,7
Up Type=0
Dn Type=3
Dn Slope=0.005

--- MULBERRY CREEK TRIBUTARY 6_2.g01 (geometry) ---

Geom Title=Existing Conditions

River Reach=MULBERRY CREEK T,Reach-1
Reach XY= 30
      1549955.00      6894788.00      1550307.45      6894893.47
      1550511.95      6895079.16      1551445.00      6893999.24
      1551801.78      6893845.89      1551901.58      6893930.18
      1552049.11      6893885.85      1552198.33      6893747.30
      1552915.06      6893527.39      1552957.94      6893295.97
      1553094.38      6893248.05      1553453.24      6892631.88
      1553212.80      6892141.41      1553314.30      6891881.33
      1553785.00      6891357.37      1553957.29      6891332.19
      1554160.44      6891093.19      1554479.88      6890937.70
      1554653.45      6890941.75      1554901.59      6891130.23
      1555089.66      6891037.95      1555401.94      6891230.21
      1555584.94      6891138.04      1556011.69      6891278.72
      1556202.74      6890882.06      1556212.80      6890531.79
      1556671.75      6890371.54      1556927.85      6889964.16
      1557291.50      6889751.41      1557255.00      6889588.00

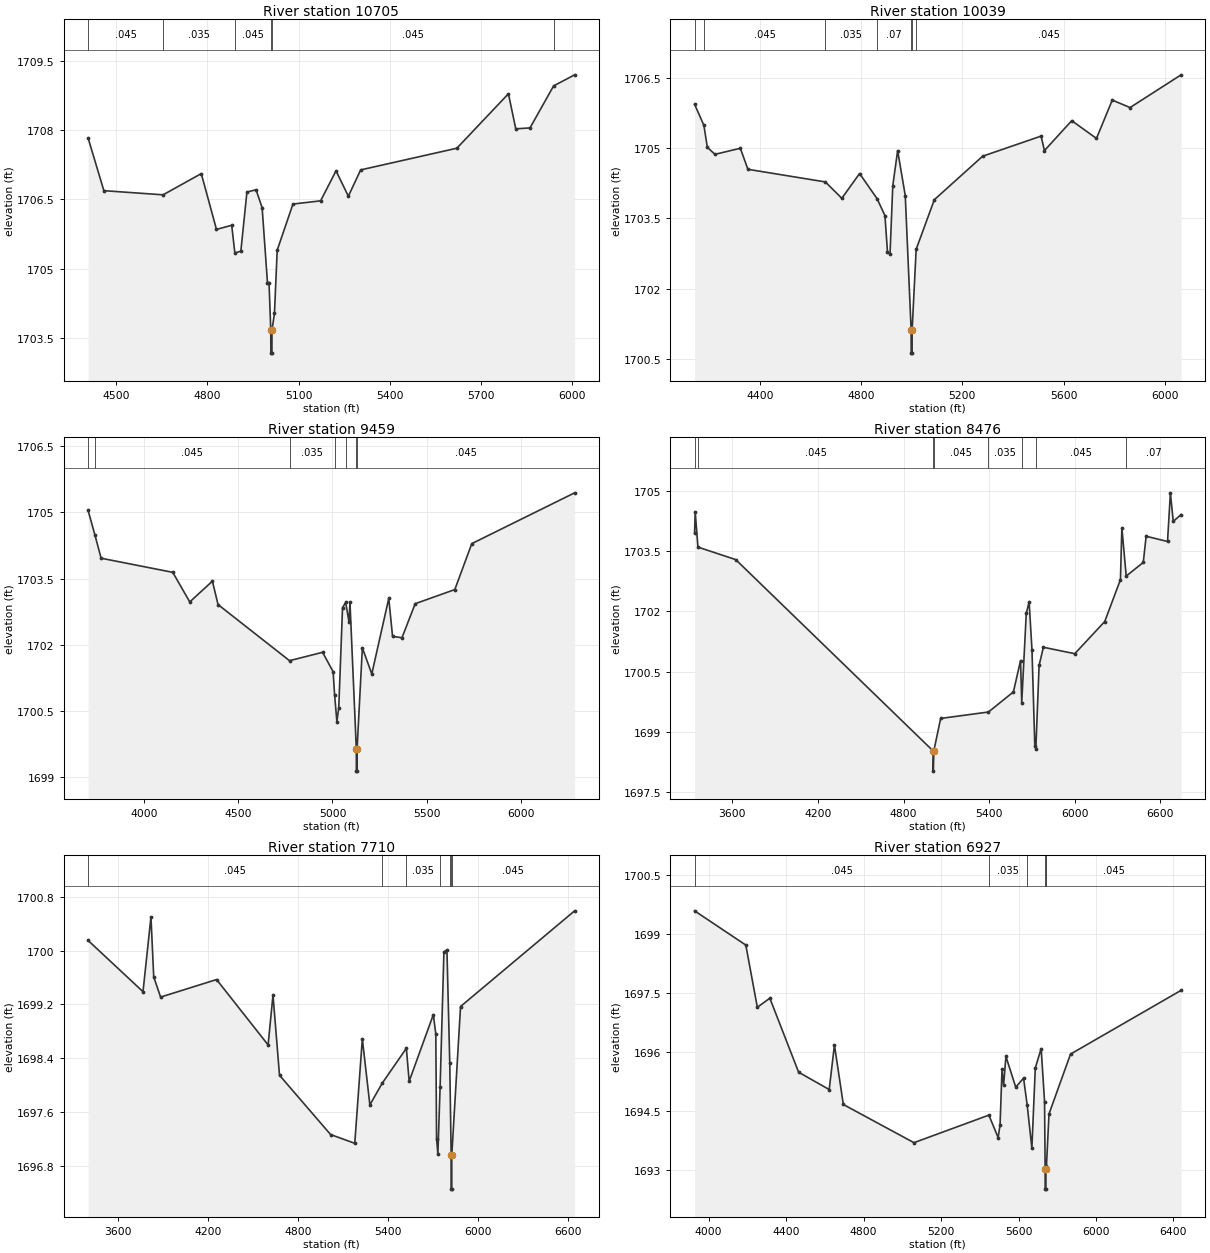
Type RM Length L Ch R = 1,10705,666,666,666
BEGIN DESCRIPTION:
MULBERRY CREEK TRIBUTARY 6_2 4.0
END DESCRIPTION:
XS GIS Cut Line= 3
      1550846.75      6895309.77      1550825.38      6894718.16
      1549830.01      6894563.00
#Sta/Elev= 30
  4408.0 1707.83  4459.8 1706.69  4654.5 1706.60  4780.0 1707.06  4830.0 1705.85
  4880.1 1705.94  4890.4 1705.34  4910.1 1705.38  4930.1 1706.66  4960.1 1706.71
  4980.1 1706.32  4997.6 1704.70  5002.7 1704.70  5008.5 1703.67  5008.8 1703.17
  5012.3 1703.17  5012.5 1703.67  5020.6 1704.03  5029.6 1705.40  5081.4 1706.40
  5172.4 1706.47  5223.0 1707.12  5263.5 1706.57  5304.0 1707.14  5620.3 1707.61
  5789.8 1708.79  5813.9 1708.03  5860.7 1708.05  5938.3 1708.96  6007.4 1709.20
#Mann=6,-1,0
  4408.0   0.045       0  4654.5   0.035       0  4890.4   0.045       0
  5008.5   0.045       0  5012.5   0.045       0  5938.3    0.07       0
Bank Sta=5008.5,5012.5
Exp/Cntr=0.3,0.1

Type RM Length L Ch R = 1,10039,580,580,580
BEGIN DESCRIPTION:
MULBERRY CREEK TRIBUTARY 6_2 3.0
END DESCRIPTION:
XS GIS Cut Line= 3
      1551318.07      6895078.25      1551254.13      6894222.64
      1550194.24      6894121.51
#Sta/Elev= 30
  4142.0 1705.94  4178.8 1705.49  4192.4 1705.02  4222.5 1704.87  4322.8 1705.00
  4352.8 1704.55  4659.0 1704.28  4723.9 1703.93  4794.1 1704.46  4863.4 1703.92
  4894.3 1703.56  4904.4 1702.78  4914.4 1702.74  4925.3 1704.20  4944.5 1704.95
  4974.6 1703.99  4997.8 1701.12  4998.1 1700.62  5001.6 1700.62  5001.8 1701.12
  5017.7 1702.84  5089.5 1703.90  5280.4 1704.83  5511.4 1705.26  5524.6 1704.95
  5632.5 1705.59  5730.3 1705.21  5792.7 1706.03  5863.0 1705.87  6064.7 1706.57
#Mann=7,-1,0
  4142.0    0.07       0  4178.8   0.045       0  4659.0   0.035       0
  4863.4    0.07       0  4997.8    0.07       0  5001.8    0.07       0
  5017.7   0.045       0
Bank Sta=4997.8,5001.8
Exp/Cntr=0.3,0.1

Type RM Length L Ch R = 1,9459,983,983,983
BEGIN DESCRIPTION:
Mapping XS 164aa74a
END DESCRIPTION:
XS GIS Cut Line= 3
      1551737.54      6895186.82      1551652.90      6893830.89
      1550430.03      6893913.00
#Sta/Elev= 30
  3702.2 1705.04  3738.1 1704.49  3771.2 1703.96  4151.9 1703.64  4242.1 1702.97
  4362.3 1703.44  4392.4 1702.91  4772.1 1701.64  4947.7 1701.83  5003.6 1701.39
  5011.6 1700.86  5023.6 1700.26  5033.6 1700.58  5053.6 1702.84  5070.1 1702.96
  5088.0 1702.52  5093.0 1702.97  5126.8 1699.64  5127.1 1699.14  5130.6 1699.14
  5130.8 1699.64  5158.9 1701.93  5209.0 1701.34  5299.2 1703.05  5319.3 1702.19
  5369.4 1702.16  5439.5 1702.93  5650.0 1703.25  5740.2 1704.29  6286.4 1705.44
#Mann=7,-1,0
  3702.2    0.07       0  3738.1   0.045       0  4772.1   0.035       0
  5011.6    0.07       0  5070.1   0.045       0  5126.8   0.035       0
  5130.8   0.045       0
Bank Sta=5126.8,5130.8
Exp/Cntr=0.3,0.1

Type RM Length L Ch R = 1,8476,766,766,766
BEGIN DESCRIPTION:
Mapping XS a9f75738
END DESCRIPTION:
XS GIS Cut Line= 3
      1552309.33      6895324.77      1552474.93      6893667.83
      1550729.99      6893613.00
#Sta/Elev= 30
  3334.8 1703.95  3339.1 1704.48  3358.4 1703.60  3623.0 1703.29  5007.9 1698.53
  5008.2 1698.03  5012.0 1698.53  5060.0 1699.34  5395.3 1699.50  5570.2 1700.00
  5620.2 1700.78  5628.5 1699.73  5660.3 1701.95  5680.3 1702.24  5700.3 1701.05
  5720.3 1698.65  5727.5 1698.59  5750.3 1700.66  5780.3 1701.11  6000.4 1700.95
  6210.5 1701.75  6320.6 1702.79  6330.6 1704.08  6361.0 1702.88  6480.7 1703.22
  6500.7 1703.87  6650.7 1703.74  6670.8 1704.95  6690.8 1704.24  6745.8 1704.41
#Mann=8,-1,0
  3334.8    0.07       0  3358.4   0.045       0  5007.9   0.045       0
  5012.0   0.045       0  5395.3   0.035       0  5628.5    0.07       0
  5727.5   0.045       0  6361.0    0.07       0
Bank Sta=5007.9,5012
Exp/Cntr=0.3,0.1

Type RM Length L Ch R = 1,7710,783,783,783
BEGIN DESCRIPTION:
MULBERRY CREEK TRIBUTARY 6_2 2.0
END DESCRIPTION:
XS GIS Cut Line= 3
      1553580.00      6894763.01      1552962.95      6893291.01
      1551330.03      6893113.00
#Sta/Elev= 30
  3403.9 1700.15  3769.3 1699.39  3822.3 1700.50  3840.6 1699.61  3886.4 1699.31
  4259.0 1699.57  4602.1 1698.60  4634.6 1699.34  4678.0 1698.15  5018.1 1697.27
  5179.0 1697.14  5229.3 1698.69  5279.6 1697.71  5361.1 1698.03  5522.5 1698.55
  5541.1 1698.06  5702.1 1699.05  5718.5 1698.76  5723.5 1697.21  5732.3 1696.98
  5747.0 1697.97  5772.5 1699.98  5792.6 1700.01  5811.4 1698.33  5820.7 1696.96
  5821.0 1696.46  5824.6 1696.46  5824.8 1696.96  5883.2 1699.17  6642.6 1700.59
#Mann=7,-1,0
  3403.9   0.045       0  5361.1    0.07       0  5522.5   0.035       0
  5747.0    0.07       0  5811.4   0.045       0  5820.7   0.045       0
  5824.8   0.045       0
Bank Sta=5820.7,5824.8
Exp/Cntr=0.3,0.1

Type RM Length L Ch R = 1,6927,1209,1209,1209
BEGIN DESCRIPTION:
Mapping XS e8a7825a
END DESCRIPTION:
XS GIS Cut Line= 3
      1553728.28      6893740.07      1553404.69      6892717.87
      1551980.05      6892513.01
#Sta/Elev= 30
  3927.8 1699.58  4192.3 1698.71  4251.7 1697.13  4316.3 1697.36  4464.9 1695.48
  4622.7 1695.04  4649.8 1696.17  4695.7 1694.66  5060.3 1693.69  5447.1 1694.39
  5494.7 1693.82  5504.8 1694.14  5514.9 1695.56  5523.0 1695.15  5535.1 1695.88
  5585.7 1695.10  5626.1 1695.33  5644.7 1694.65  5669.0 1693.55  5686.7 1695.59
  5717.0 1696.08  5734.5 1694.73  5737.5 1693.01  5737.7 1692.51  5741.3 1692.51
  5741.6 1693.01  5744.3 1693.10  5757.4 1694.42  5868.5 1695.94  6439.3 1697.56
#Mann=6,-1,0
  3927.8   0.045       0  5447.1   0.035       0  5644.7    0.07       0
  5737.5   0.045       0  5741.6    0.07       0  5744.3   0.045       0
Bank Sta=5737.5,5741.6
Exp/Cntr=0.3,0.1

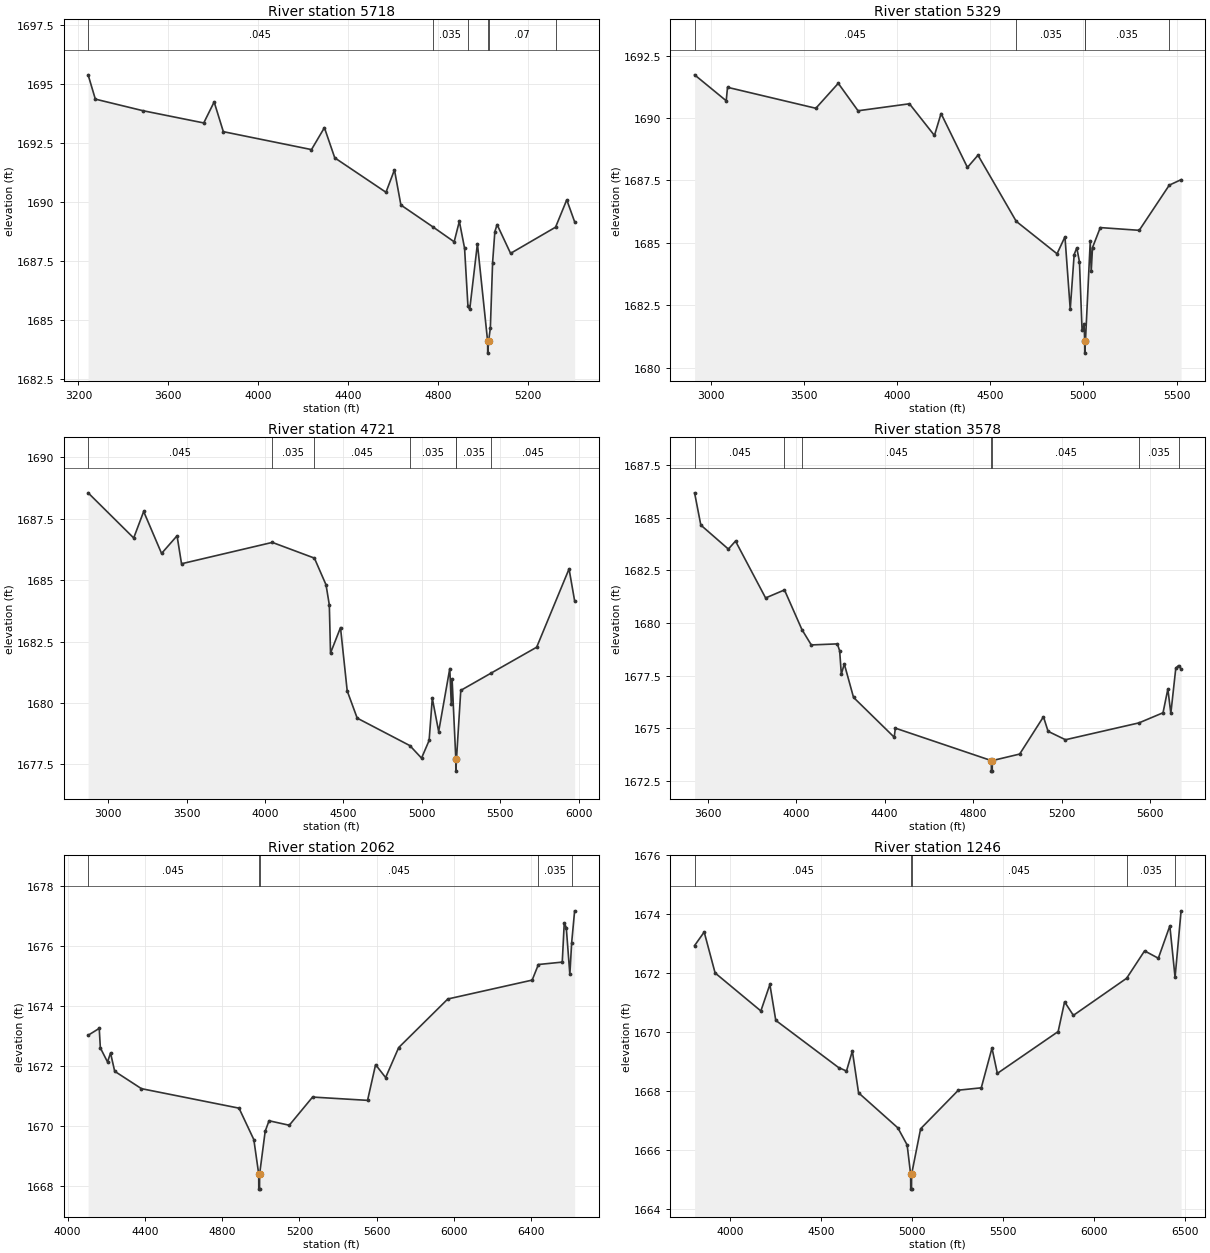
Type RM Length L Ch R = 1,5718,389,389,389
BEGIN DESCRIPTION:
Mapping XS 81875dab
END DESCRIPTION:
XS GIS Cut Line= 3
      1554158.86      6893357.32      1553438.42      6891754.70
      1553030.00      6891763.00
#Sta/Elev= 30
  3242.9 1695.40  3275.0 1694.37  3486.4 1693.88  3757.6 1693.36  3803.9 1694.25
  3844.8 1692.99  4237.2 1692.23  4294.7 1693.16  4340.8 1691.88  4568.8 1690.42
  4606.5 1691.37  4635.2 1689.88  4776.5 1688.96  4872.3 1688.32  4895.4 1689.19
  4918.6 1688.05  4933.7 1685.58  4941.6 1685.46  4975.8 1688.24  5021.3 1684.10
  5021.6 1683.60  5025.6 1684.10  5033.4 1684.67  5043.4 1687.44  5053.4 1688.75
  5063.4 1689.05  5123.4 1687.83  5323.7 1688.94  5373.5 1690.10  5408.5 1689.17
#Mann=6,-1,0
  3242.9   0.045       0  4776.5   0.035       0  4933.7    0.07       0
  5021.3    0.07       0  5025.6    0.07       0  5323.7   0.035       0
Bank Sta=5021.3,5025.6
Exp/Cntr=0.3,0.1

Type RM Length L Ch R = 1,5329,608,608,608
BEGIN DESCRIPTION:
Mapping XS d3302fde
END DESCRIPTION:
XS GIS Cut Line= 3
      1555129.99      6892962.99      1553681.67      6891461.33
      1553179.99      6891613.00
#Sta/Elev= 30
  2913.7 1691.73  3083.5 1690.69  3090.4 1691.23  3564.3 1690.39  3684.7 1691.39
  3790.7 1690.29  4066.5 1690.57  4200.7 1689.30  4236.2 1690.18  4377.7 1688.02
  4434.3 1688.51  4639.6 1685.86  4858.5 1684.56  4901.0 1685.24  4929.3 1682.34
  4950.4 1684.53  4964.5 1684.80  4978.7 1684.24  4992.8 1681.50  5003.8 1681.73
  5006.8 1681.08  5007.1 1680.58  5011.1 1681.08  5036.7 1685.06  5041.9 1683.86
  5048.8 1684.81  5090.5 1685.61  5299.5 1685.50  5460.7 1687.31  5524.1 1687.53
#Mann=5,-1,0
  2913.7   0.045       0  4639.6   0.035       0  5006.8   0.035       0
  5011.1   0.035       0  5460.7    0.07       0
Bank Sta=5006.8,5011.1
Exp/Cntr=0.3,0.1

Type RM Length L Ch R = 1,4721,1143,1143,1143
BEGIN DESCRIPTION:
Mapping XS 2b31b7a0
END DESCRIPTION:
XS GIS Cut Line= 3
      1555529.97      6892762.96      1554141.26      6891150.95
      1553180.02      6891313.00
#Sta/Elev= 30
  2872.3 1688.56  3163.0 1686.72  3226.6 1687.80  3340.7 1686.09  3439.5 1686.81
  3468.0 1685.67  4047.0 1686.54  4315.3 1685.90  4389.6 1684.81  4410.5 1683.99
  4418.1 1682.03  4481.8 1683.07  4524.5 1680.49  4588.2 1679.38  4924.1 1678.26
  4998.6 1677.75  5046.9 1678.47  5067.2 1680.19  5107.8 1678.83  5178.7 1681.40
  5188.3 1679.94  5193.4 1680.98  5217.1 1677.72  5217.4 1677.22  5221.5 1677.72
  5248.8 1680.51  5443.8 1681.22  5732.8 1682.27  5939.3 1685.46  5974.8 1684.16
#Mann=7,-1,0
  2872.3   0.045       0  4047.0   0.035       0  4315.3   0.045       0
  4924.1   0.035       0  5217.1   0.035       0  5221.5   0.035       0
  5443.8   0.045       0
Bank Sta=5217.1,5221.5
Exp/Cntr=0.3,0.1

Type RM Length L Ch R = 1,3578,1516,1516,1516
BEGIN DESCRIPTION:
Mapping XS d6777dc3
END DESCRIPTION:
XS GIS Cut Line= 4
      1555576.26      6892404.93      1555274.80      6891427.24
      1555090.76      6891045.29      1554497.88      6890580.88
#Sta/Elev= 30
  3540.3 1686.18  3568.5 1684.65  3693.1 1683.51  3725.4 1683.89  3861.5 1681.19
  3946.8 1681.57  4025.7 1679.69  4068.1 1678.96  4185.9 1679.01  4196.4 1678.68
  4204.0 1677.57  4217.3 1678.06  4259.1 1676.47  4443.1 1674.58  4448.3 1675.01
  4882.3 1673.47  4882.6 1672.97  4886.4 1672.97  4886.7 1673.47  5010.5 1673.78
  5118.1 1675.55  5138.9 1674.86  5217.6 1674.46  5550.0 1675.26  5658.8 1675.74
  5680.7 1676.87  5694.1 1675.71  5716.6 1677.86  5728.8 1677.98  5740.5 1677.83
#Mann=7,-1,0
  3540.3   0.045       0  3946.8   0.035       0  4025.7   0.045       0
  4882.3   0.045       0  4886.7   0.045       0  5550.0   0.035       0
  5728.8   0.045       0
Bank Sta=4882.3,4886.7
Exp/Cntr=0.3,0.1

Type RM Length L Ch R = 1,2062,816,816,816
BEGIN DESCRIPTION:
Mapping XS f6210e77
END DESCRIPTION:
XS GIS Cut Line= 3
      1556929.32      6891392.43      1556191.51      6890955.41
      1554593.42      6890507.11
#Sta/Elev= 30
  4106.6 1673.01  4164.1 1673.24  4169.9 1672.59  4207.0 1672.12  4222.6 1672.42
  4244.1 1671.81  4382.5 1671.23  4887.4 1670.58  4964.1 1669.53  4989.4 1668.38
  4989.7 1667.88  4993.6 1667.88  4994.0 1668.38  5022.8 1669.81  5042.7 1670.16
  5147.4 1670.01  5268.1 1670.95  5552.5 1670.84  5594.0 1672.03  5646.0 1671.60
  5713.5 1672.60  5967.7 1674.22  6404.2 1674.85  6436.5 1675.37  6559.9 1675.45
  6570.3 1676.76  6580.7 1676.60  6599.2 1675.04  6608.5 1676.09  6623.9 1677.16
#Mann=5,-1,0
  4106.6   0.045       0  4989.4   0.045       0  4994.0   0.045       0
  6436.5   0.035       0  6608.5    0.07       0
Bank Sta=4989.4,4994
Exp/Cntr=0.3,0.1

Type RM Length L Ch R = 1,1246,972,972,972
BEGIN DESCRIPTION:
Mapping XS ee46d0bc
END DESCRIPTION:
XS GIS Cut Line= 3
      1557114.13      6891451.11      1556545.53      6890396.39
      1555179.16      6889841.16
#Sta/Elev= 30
  3803.7 1672.94  3856.5 1673.40  3916.5 1672.01  4167.9 1670.72  4217.4 1671.62
  4249.8 1670.40  4594.5 1668.80  4638.3 1668.68  4670.6 1669.36  4704.7 1667.94
  4920.6 1666.75  4971.6 1666.17  4990.9 1665.17  4991.3 1664.67  4995.6 1664.67
  4996.0 1665.17  5045.7 1666.72  5253.1 1668.03  5378.9 1668.11  5437.8 1669.46
  5467.3 1668.60  5801.3 1670.02  5836.7 1671.03  5884.9 1670.57  6177.6 1671.83
  6276.2 1672.76  6351.8 1672.51  6415.0 1673.61  6443.7 1671.86  6476.8 1674.12
#Mann=5,-1,0
  3803.7   0.045       0  4990.9   0.045       0  4996.0   0.045       0
  6177.6   0.035       0  6443.7   0.045       0
Bank Sta=4990.9,4996
Exp/Cntr=0.3,0.1

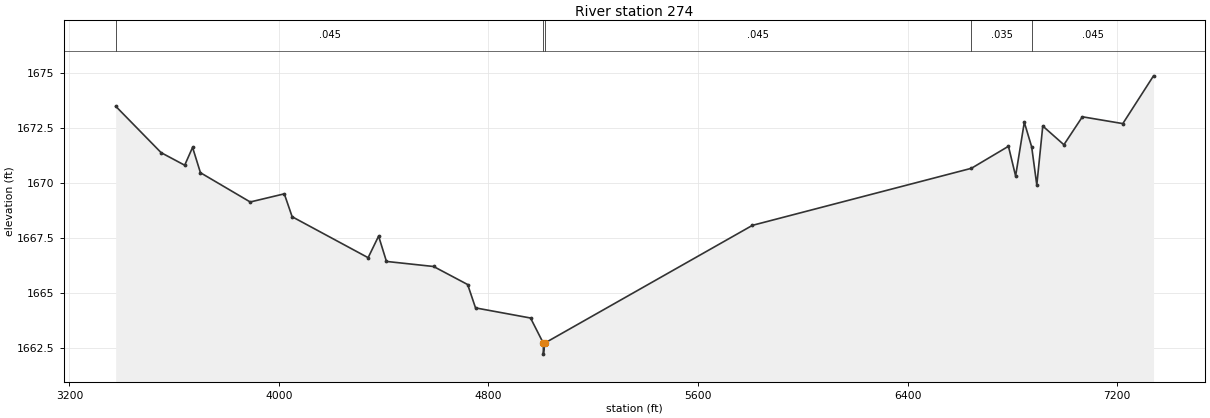
Type RM Length L Ch R = 1,274,0,0,0
BEGIN DESCRIPTION:
MULBERRY CREEK TRIBUTARY 6_2 1.0
END DESCRIPTION:
XS GIS Cut Line= 3
      1557183.12      6891441.54      1557224.79      6889816.52
      1554905.37      6889528.33
#Sta/Elev= 30
  3376.5 1673.48  3550.1 1671.37  3640.0 1670.80  3670.1 1671.61  3700.1 1670.46
  3890.2 1669.13  4020.3 1669.50  4050.3 1668.46  4340.4 1666.60  4380.4 1667.58
  4410.4 1666.43  4590.4 1666.20  4720.5 1665.38  4750.5 1664.32  4960.6 1663.86
  5009.3 1662.72  5009.7 1662.22  5014.5 1662.72  5808.0 1668.07  6643.9 1670.66
  6785.4 1671.66  6812.7 1670.31  6845.9 1672.75  6874.1 1671.63  6893.6 1669.90
  6916.4 1672.58  6997.1 1671.73  7067.6 1673.00  7222.1 1672.69  7339.3 1674.86
#Mann=5,-1,0
  3376.5   0.045       0  5009.3   0.045       0  5014.5   0.045       0
  6643.9   0.035       0  6874.1   0.045       0
Bank Sta=5009.3,5014.5
Exp/Cntr=0.3,0.1

Chan Stop Cuts=-1