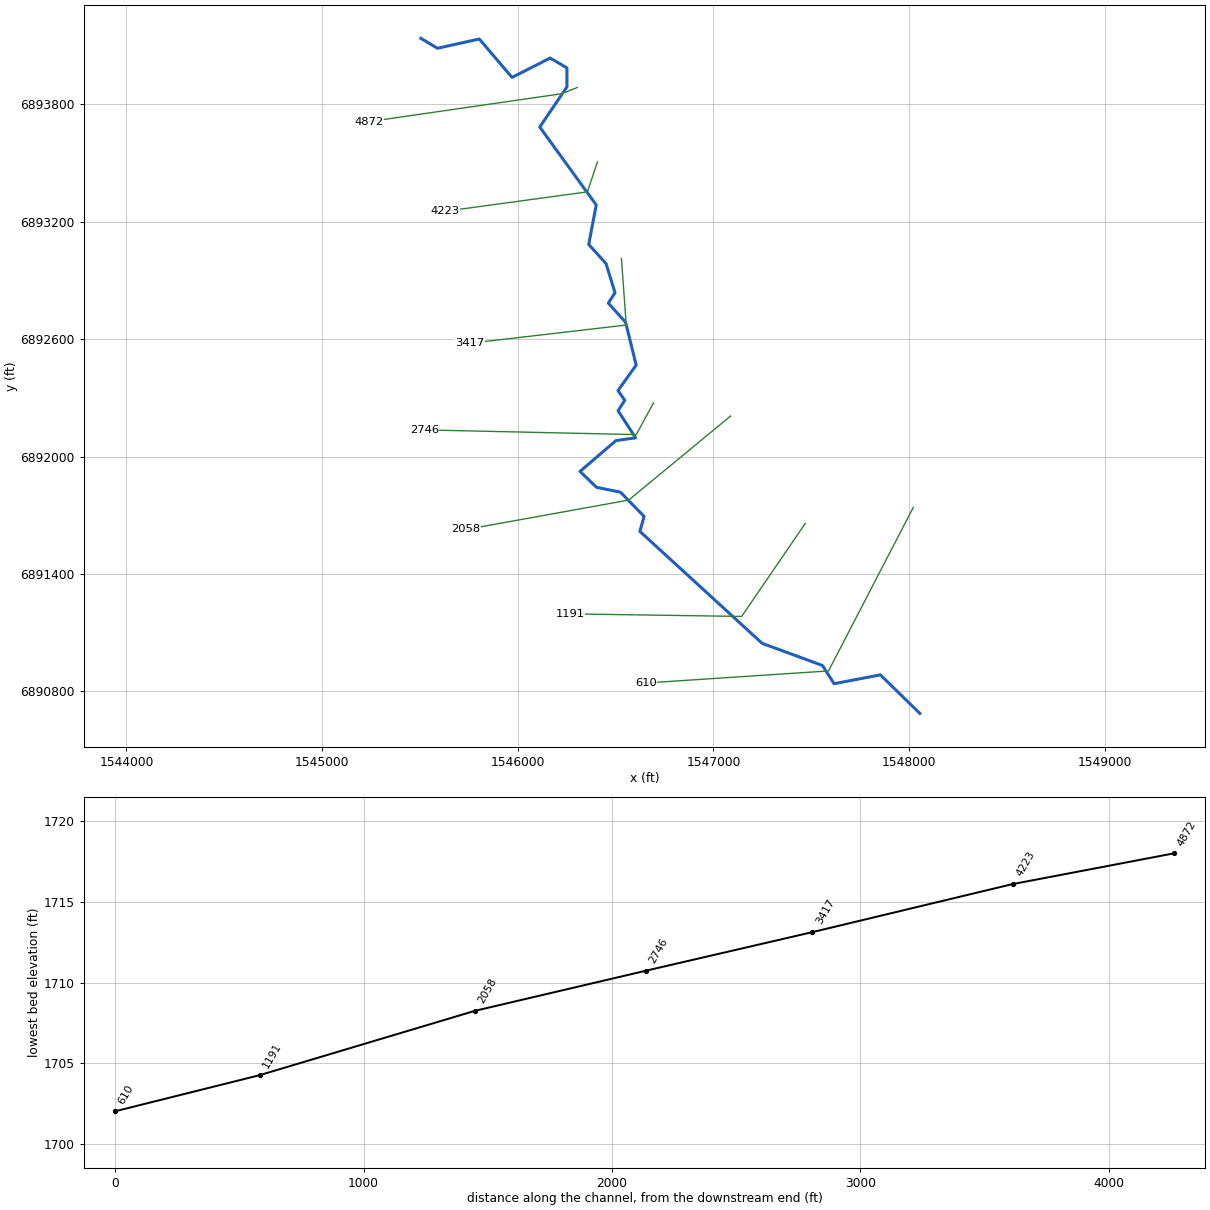
--- MULBERRY CREEK TRIBUTARY 6_3.prj (project) ---

Proj Title=MULBERRY CREEK TRIBUTARY 6_3 Base Level Engineering
Current Plan=p01
Default Exp/Contr=0.3,0.1
English Units
Geom File=g01
Flow File=f01
Plan File=p01
BEGIN DESCRIPTION:
MULBERRY CREEK TRIBUTARY 6_3
END DESCRIPTION:

--- MULBERRY CREEK TRIBUTARY 6_3.p01 (plan) ---

Plan Title=Multiple Run
Short Identifier=Multiple
Geom File=g01
Flow File=f01
Subcritical Flow
K Sum by GR= 0
Std Step Tol= 0.01
Critical Tol= 0.01
Num of Std Step Trials= 20
Max Error Tol= 0.3
Flow Tol Ratio= 0.001
Split Flow NTrial= 30
Split Flow Tol= 0.02
Split Flow Ratio= 0.02
Log Output Level= 0
Friction Slope Method= 1
Unsteady Friction Slope Method= 2
Unsteady Bridges Friction Slope Method= 1
Parabolic Critical Depth
Global Vel Dist=  1 , 1 , 1
Global Log Level= 0
CheckData=True
Encroach Param= -1, 0, 0, 0
BEGIN DESCRIPTION:
Multiple Run
END DESCRIPTION:

--- MULBERRY CREEK TRIBUTARY 6_3.f01 (steady flow) ---

Flow Title=Multiple
Number of Profiles=7
Profile Names=10-year,25-year,50-year,1pct_min,100-year,1pct_plu,500-year
River Rch & RM= MULBERRY CREEK T,Reach-1,4872
     139     183     217     128     255     509     358
Boundary for River Rch & Prof#=MULBERRY CREEK T,Reach-1,1
Up Type=0
Dn Type=3
Dn Slope=0.005
Boundary for River Rch & Prof#=MULBERRY CREEK T,Reach-1,2
Up Type=0
Dn Type=3
Dn Slope=0.005
Boundary for River Rch & Prof#=MULBERRY CREEK T,Reach-1,3
Up Type=0
Dn Type=3
Dn Slope=0.005
Boundary for River Rch & Prof#=MULBERRY CREEK T,Reach-1,4
Up Type=0
Dn Type=3
Dn Slope=0.005
Boundary for River Rch & Prof#=MULBERRY CREEK T,Reach-1,5
Up Type=0
Dn Type=3
Dn Slope=0.005
Boundary for River Rch & Prof#=MULBERRY CREEK T,Reach-1,6
Up Type=0
Dn Type=3
Dn Slope=0.005
Boundary for River Rch & Prof#=MULBERRY CREEK T,Reach-1,7
Up Type=0
Dn Type=3
Dn Slope=0.005

--- MULBERRY CREEK TRIBUTARY 6_3.g01 (geometry) ---

Geom Title=Existing Conditions

River Reach=MULBERRY CREEK T,Reach-1
Reach XY= 30
      1545505.00      6894138.00      1545589.96      6894087.27
      1545803.50      6894134.54      1545971.02      6893938.23
      1546165.75      6894037.32      1546251.63      6893986.78
      1546251.33      6893889.59      1546112.61      6893684.67
      1546401.26      6893286.44      1546362.81      6893084.59
      1546451.37      6892986.50      1546497.20      6892837.90
      1546463.01      6892784.67      1546551.43      6892686.53
      1546605.35      6892467.79      1546512.55      6892338.00
      1546546.95      6892288.00      1546513.00      6892234.67
      1546602.54      6892096.17      1546502.65      6892082.44
      1546318.35      6891924.75      1546402.54      6891843.52
      1546525.16      6891818.37      1546645.70      6891694.67
      1546624.37      6891618.00      1547248.94      6891046.14
      1547557.66      6890932.54      1547616.84      6890839.63
      1547853.37      6890884.87      1548055.00      6890688.00

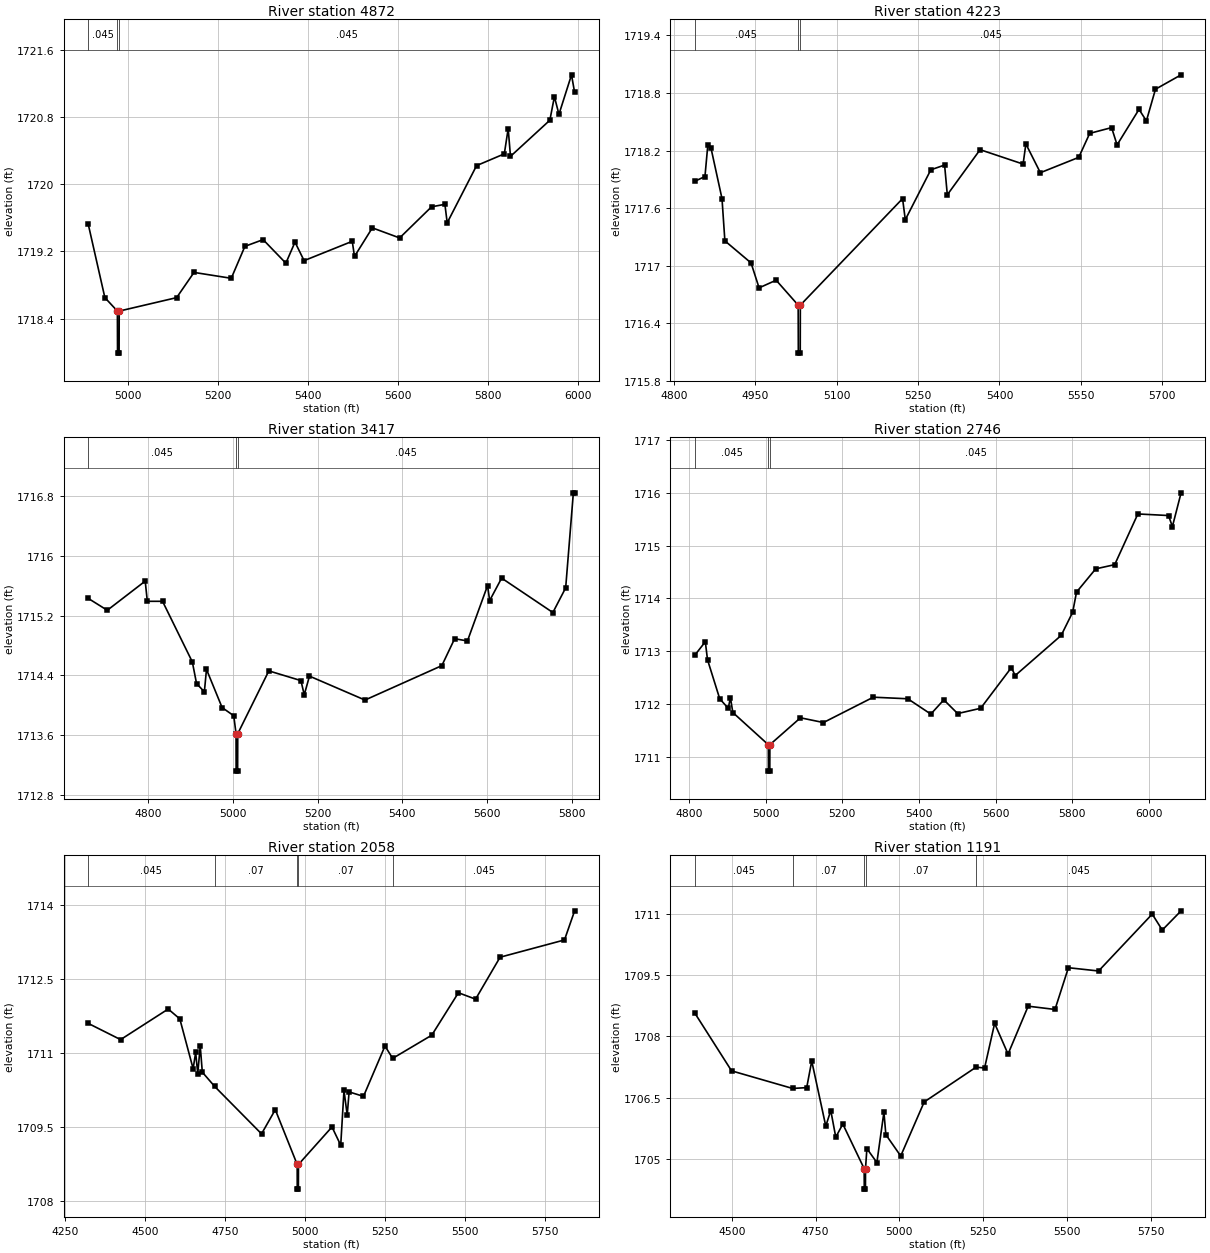
Type RM Length L Ch R = 1,4872,649,649,649
BEGIN DESCRIPTION:
MULBERRY CREEK TRIBUTARY 6_3 4.0
END DESCRIPTION:
XS GIS Cut Line= 3
      1546304.33      6893886.73      1546222.12      6893854.49
      1545240.56      6893712.38
#Sta/Elev= 30
  4911.7 1719.53  4948.9 1718.65  4976.7 1718.49  4977.0 1717.99  4980.5 1717.99
  4980.7 1718.49  5108.2 1718.65  5146.8 1718.95  5229.5 1718.88  5259.8 1719.26
  5300.2 1719.34  5350.7 1719.06  5371.0 1719.31  5391.2 1719.09  5498.1 1719.32
  5503.1 1719.14  5542.7 1719.48  5603.3 1719.36  5674.1 1719.73  5703.8 1719.76
  5708.9 1719.54  5774.1 1720.22  5835.7 1720.36  5844.3 1720.66  5849.4 1720.33
  5936.8 1720.76  5946.9 1721.04  5957.0 1720.83  5984.9 1721.30  5991.8 1721.09
#Mann=3,-1,0
  4911.7   0.045       0  4976.7   0.045       0  4980.7   0.045       0
Bank Sta=4976.7,4980.7
Exp/Cntr=0.3,0.1

Type RM Length L Ch R = 1,4223,806,806,806
BEGIN DESCRIPTION:
MULBERRY CREEK TRIBUTARY 6_3 3.0
END DESCRIPTION:
XS GIS Cut Line= 3
      1546407.64      6893506.51      1546355.96      6893353.40
      1545628.19      6893254.17
#Sta/Elev= 30
  4838.4 1717.88  4857.5 1717.93  4862.8 1718.26  4868.5 1718.23  4888.9 1717.70
  4894.2 1717.26  4942.4 1717.03  4957.2 1716.77  4988.6 1716.85  5029.2 1716.59
  5029.5 1716.09  5033.0 1716.09  5033.2 1716.59  5221.5 1717.70  5226.5 1717.48
  5273.5 1718.00  5298.9 1718.05  5303.9 1717.74  5364.3 1718.21  5443.5 1718.06
  5448.6 1718.27  5475.3 1717.97  5546.0 1718.13  5566.2 1718.38  5606.5 1718.44
  5616.6 1718.26  5657.0 1718.63  5670.6 1718.51  5687.3 1718.84  5734.5 1718.99
#Mann=3,-1,0
  4838.4   0.045       0  5029.2   0.045       0  5033.2   0.045       0
Bank Sta=5029.2,5033.2
Exp/Cntr=0.3,0.1

Type RM Length L Ch R = 1,3417,671,671,671
BEGIN DESCRIPTION:
MULBERRY CREEK TRIBUTARY 6_3 2.0
END DESCRIPTION:
XS GIS Cut Line= 3
      1546530.00      6893013.05      1546554.59      6892672.84
      1545754.02      6892579.45
#Sta/Elev= 30
  4658.9 1715.43  4704.1 1715.27  4793.5 1715.66  4798.5 1715.39  4834.4 1715.39
  4904.6 1714.58  4914.6 1714.29  4933.0 1714.18  4938.0 1714.48  4974.8 1713.97
  5002.3 1713.86  5007.7 1713.62  5007.9 1713.12  5011.4 1713.12  5011.7 1713.62
  5085.0 1714.46  5160.7 1714.33  5168.5 1714.14  5180.8 1714.39  5311.7 1714.07
  5492.9 1714.53  5523.1 1714.89  5553.3 1714.86  5600.7 1715.60  5605.7 1715.40
  5633.9 1715.70  5754.7 1715.24  5784.9 1715.57  5803.0 1716.84  5806.0 1716.84
#Mann=3,-1,0
  4658.9   0.045       0  5007.7   0.045       0  5011.7   0.045       0
Bank Sta=5007.7,5011.7
Exp/Cntr=0.3,0.1

Type RM Length L Ch R = 1,2746,688,688,688
BEGIN DESCRIPTION:
Mapping XS 31fb4dfa
END DESCRIPTION:
XS GIS Cut Line= 3
      1546694.52      6892275.58      1546605.70      6892112.73
      1545522.26      6892136.74
#Sta/Elev= 30
  4814.5 1712.92  4842.5 1713.18  4848.2 1712.84  4880.1 1712.10  4902.3 1711.92
  4908.0 1712.12  4914.3 1711.84  5006.9 1711.23  5007.2 1710.73  5010.7 1710.73
  5010.9 1711.23  5090.7 1711.74  5150.7 1711.65  5280.8 1712.13  5370.8 1712.10
  5430.8 1711.81  5464.7 1712.08  5500.8 1711.82  5560.8 1711.92  5640.9 1712.69
  5650.9 1712.54  5770.9 1713.30  5800.9 1713.74  5810.9 1714.12  5860.9 1714.56
  5910.5 1714.64  5970.9 1715.60  6051.0 1715.57  6061.0 1715.36  6083.7 1716.00
#Mann=3,-1,0
  4814.5   0.045       0  5006.9   0.045       0  5010.9   0.045       0
Bank Sta=5006.9,5010.9
Exp/Cntr=0.3,0.1

Type RM Length L Ch R = 1,2058,867,867,867
BEGIN DESCRIPTION:
Mapping XS b4142ead
END DESCRIPTION:
XS GIS Cut Line= 3
      1547087.96      6892207.81      1546567.19      6891778.06
      1545735.84      6891627.89
#Sta/Elev= 30
  4323.1 1711.61  4424.6 1711.28  4573.3 1711.90  4609.6 1711.70  4651.2 1710.69
  4659.1 1711.02  4665.6 1710.59  4673.4 1711.15  4679.9 1710.62  4718.6 1710.33
  4864.9 1709.37  4907.9 1709.86  4976.3 1708.75  4976.5 1708.25  4980.0 1708.25
  4980.3 1708.75  5085.0 1709.51  5112.3 1709.14  5122.5 1710.25  5132.6 1709.75
  5138.5 1710.22  5183.4 1710.13  5250.6 1711.15  5274.6 1710.90  5396.8 1711.37
  5480.0 1712.23  5533.6 1712.10  5610.2 1712.95  5811.4 1713.30  5843.1 1713.89
#Mann=5,-1,0
  4323.1   0.045       0  4718.6    0.07       0  4976.3    0.07       0
  4980.3    0.07       0  5274.6   0.045       0
Bank Sta=4976.3,4980.3
Exp/Cntr=0.3,0.1

Type RM Length L Ch R = 1,1191,581,581,581
BEGIN DESCRIPTION:
Mapping XS c7e98366
END DESCRIPTION:
XS GIS Cut Line= 3
      1547469.28      6891658.36      1547144.45      6891183.44
      1546268.93      6891196.53
#Sta/Elev= 30
  4389.2 1708.58  4499.5 1707.16  4681.4 1706.73  4723.6 1706.75  4738.6 1707.40
  4780.5 1705.81  4795.4 1706.19  4810.3 1705.54  4831.3 1705.86  4895.0 1704.77
  4895.3 1704.27  4898.8 1704.27  4899.0 1704.77  4903.1 1705.26  4932.9 1704.92
  4953.9 1706.15  4959.7 1705.60  5004.0 1705.08  5074.0 1706.40  5228.7 1707.25
  5254.1 1707.23  5284.1 1708.32  5324.1 1707.57  5384.1 1708.74  5464.1 1708.66
  5504.1 1709.68  5594.1 1709.60  5754.1 1710.99  5784.1 1710.60  5840.2 1711.07
#Mann=5,-1,0
  4389.2   0.045       0  4681.4    0.07       0  4895.0    0.07       0
  4899.0    0.07       0  5228.7   0.045       0
Bank Sta=4895,4899
Exp/Cntr=0.3,0.1

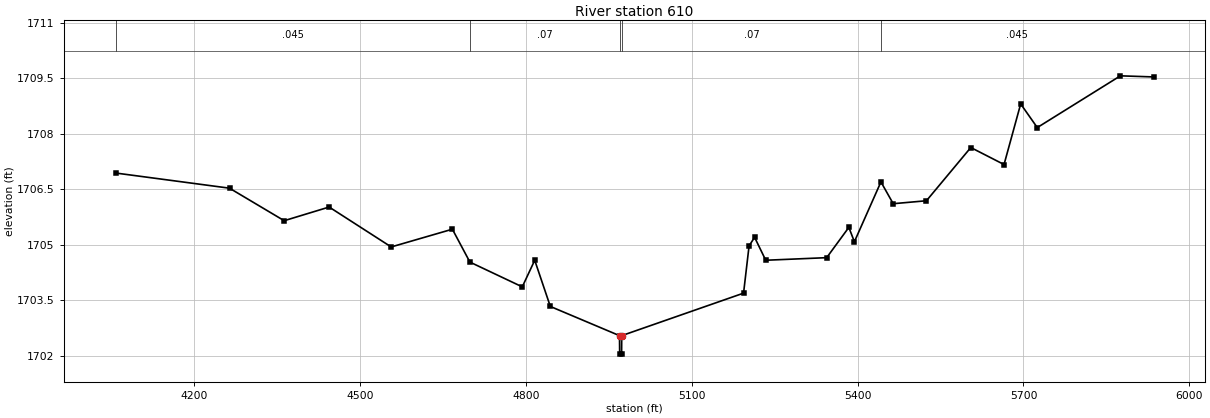
Type RM Length L Ch R = 1,610,0,0,0
BEGIN DESCRIPTION:
MULBERRY CREEK TRIBUTARY 6_3 1.0
END DESCRIPTION:
XS GIS Cut Line= 3
      1548021.62      6891740.72      1547588.44      6890904.91
      1546655.27      6890843.35
#Sta/Elev= 30
  4058.6 1706.94  4264.4 1706.53  4363.3 1705.65  4444.6 1706.02  4556.8 1704.94
  4667.4 1705.42  4699.1 1704.53  4793.8 1703.86  4816.3 1704.58  4844.5 1703.33
  4969.6 1702.54  4969.9 1702.04  4973.4 1702.04  4973.6 1702.54  5193.9 1703.69
  5203.9 1704.97  5213.9 1705.20  5234.0 1704.58  5344.2 1704.65  5384.3 1705.47
  5394.3 1705.08  5442.3 1706.70  5464.5 1706.11  5524.6 1706.19  5604.8 1707.63
  5664.9 1707.17  5695.0 1708.81  5725.0 1708.17  5875.3 1709.57  5935.2 1709.54
#Mann=5,-1,0
  4058.6   0.045       0  4699.1    0.07       0  4969.6    0.07       0
  4973.6    0.07       0  5442.3   0.045       0
Bank Sta=4969.6,4973.6
Exp/Cntr=0.3,0.1

Chan Stop Cuts=-1