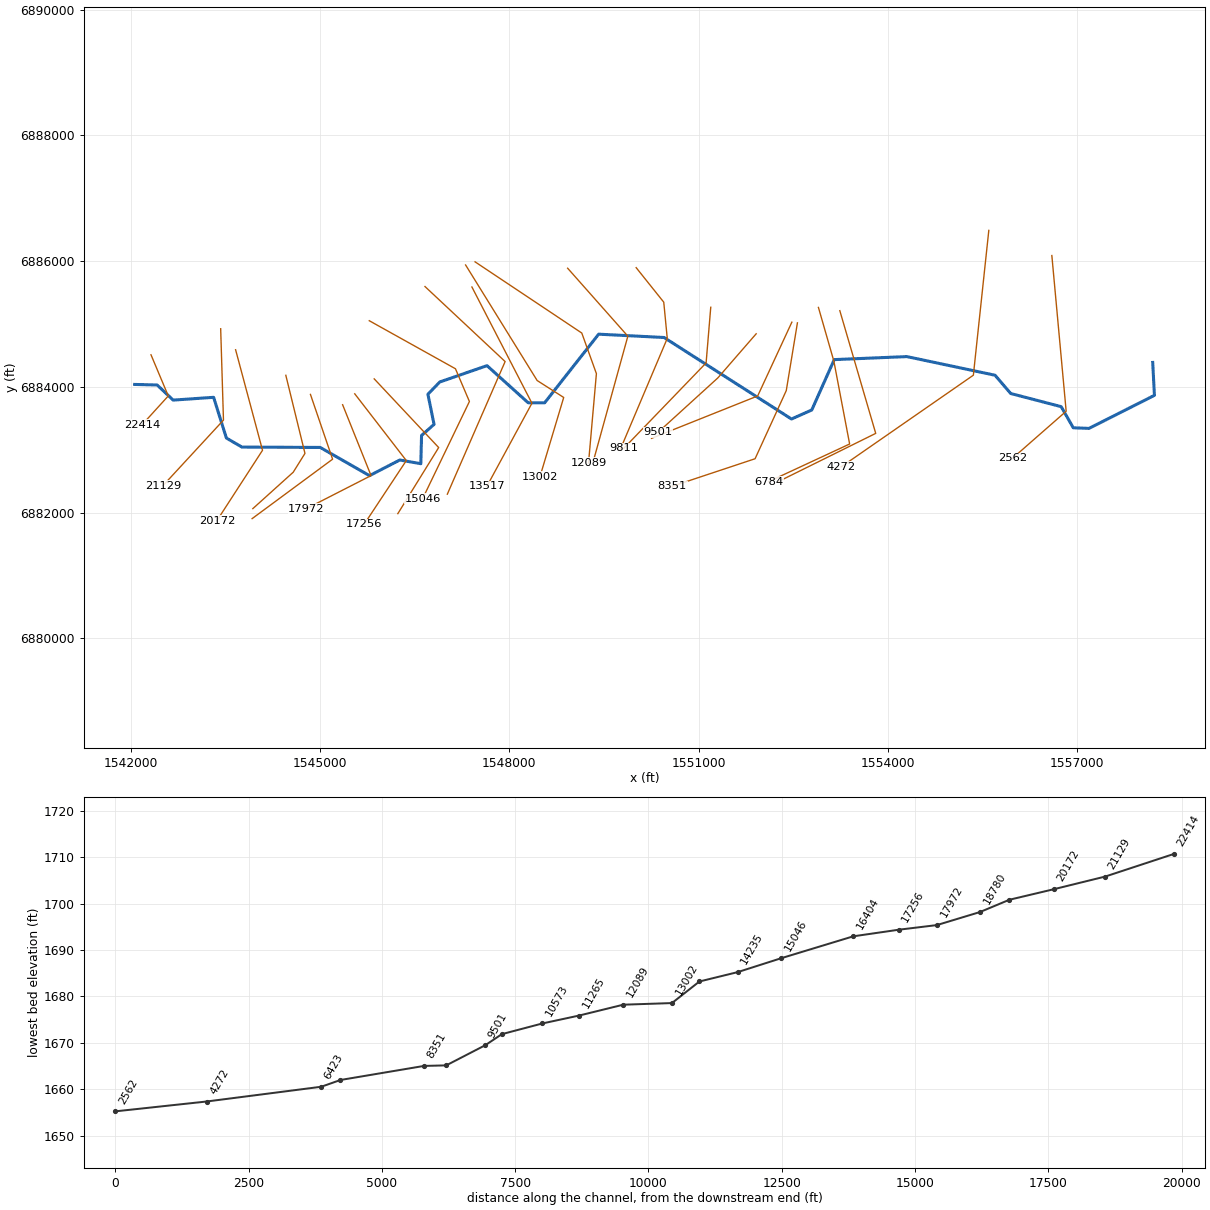
--- MULBERRY CREEK TRIBUTARY 7.prj (project) ---

Proj Title=MULBERRY CREEK TRIBUTARY 7 Base Level Engineering
Current Plan=p01
Default Exp/Contr=0.3,0.1
English Units
Geom File=g01
Flow File=f01
Plan File=p01
Y Axis Title=Elevation
X Axis Title(PF)=Main Channel Distance
X Axis Title(XS)=Station
BEGIN DESCRIPTION:
MULBERRY CREEK TRIBUTARY 7
END DESCRIPTION:
DSS Export Rating Curves= 0
DSS Export Rating Curve Sorted= 0
DSS Export Volume Flow Curves= 0
DXF OffsetX= 0
DXF OffsetY= 0
DXF ScaleX= 1
DXF ScaleY= 10

--- MULBERRY CREEK TRIBUTARY 7.p01 (plan) ---

Plan Title=Multiple Run
Short Identifier=Multiple
Geom File=g01
Flow File=f01
Subcritical Flow
K Sum by GR= 0
Std Step Tol= 0.01
Critical Tol= 0.01
Num of Std Step Trials= 20
Max Error Tol= 0.3
Flow Tol Ratio= 0.001
Split Flow NTrial= 30
Split Flow Tol= 0.02
Split Flow Ratio= 0.02
Log Output Level= 0
Friction Slope Method= 1
Unsteady Friction Slope Method= 2
Unsteady Bridges Friction Slope Method= 1
Parabolic Critical Depth
Global Vel Dist=  1 , 1 , 1
Global Log Level= 0
CheckData=True
Encroach Param= -1, 0, 0, 0
BEGIN DESCRIPTION:
Multiple Run
END DESCRIPTION:

--- MULBERRY CREEK TRIBUTARY 7.f01 (steady flow) ---

Flow Title=Multiple
Program Version=4.10
Number of Profiles= 7
Profile Names=10-year,25-year,50-year,1pct_min,100-year,1pct_plu,500-year
River Rch & RM=MULBERRY CREEK T,Reach-1         ,22414
     166     222     267     160     318     635     459
River Rch & RM=MULBERRY CREEK T,Reach-1         ,19332
     250     342     417     253     505    1007     748
River Rch & RM=MULBERRY CREEK T,Reach-1         ,14235
     285     393     482     293     585    1167     875
River Rch & RM=MULBERRY CREEK T,Reach-1         ,10573
     342     476     587     360     718    1432    1087
River Rch & RM=MULBERRY CREEK T,Reach-1         ,4272
     798    1145    1440     897    1790    3571    2806
Boundary for River Rch & Prof#=MULBERRY CREEK T,Reach-1         , 1
Up Type= 0
Dn Type= 3
Dn Slope=0.00139
Boundary for River Rch & Prof#=MULBERRY CREEK T,Reach-1         , 2
Up Type= 0
Dn Type= 3
Dn Slope=0.00139
Boundary for River Rch & Prof#=MULBERRY CREEK T,Reach-1         , 3
Up Type= 0
Dn Type= 3
Dn Slope=0.00139
Boundary for River Rch & Prof#=MULBERRY CREEK T,Reach-1         , 4
Up Type= 0
Dn Type= 3
Dn Slope=0.00139
Boundary for River Rch & Prof#=MULBERRY CREEK T,Reach-1         , 5
Up Type= 0
Dn Type= 3
Dn Slope=0.00139
Boundary for River Rch & Prof#=MULBERRY CREEK T,Reach-1         , 6
Up Type= 0
Dn Type= 3
Dn Slope=0.00139
Boundary for River Rch & Prof#=MULBERRY CREEK T,Reach-1         , 7
Up Type= 0
Dn Type= 3
Dn Slope=0.00139
DSS Import GetInterval= 0
DSS Import GetPeak= 0
DSS Import FillOption= 0

--- MULBERRY CREEK TRIBUTARY 7.g01 (geometry) ---

Geom Title=Existing Conditions
Program Version=4.10

River Reach=MULBERRY CREEK T,Reach-1
Reach XY= 30
        1542055.        6884038.      1542411.99      6884029.16
      1542665.49      6883788.95      1543307.55      6883833.01
      1543510.36       6883185.3      1543756.59      6883041.68
      1544999.11      6883036.04        1545780.      6882587.34
      1546260.89      6882836.04      1546594.53      6882777.47
      1546606.22      6883225.97      1546804.62      6883403.16
      1546707.05      6883882.14      1546894.94       6884076.9
       1547644.5       6884336.8      1548298.95      6883745.46
      1548558.35       6883745.6      1549415.61      6884837.41
       1550453.5      6884784.53      1552474.98      6883487.96
      1552796.86      6883631.94       1553152.7      6884432.91
        1554305.      6884480.91      1555703.55      6884184.47
       1555952.7      6883893.83      1556753.54      6883684.46
      1556945.17      6883348.47      1557194.57      6883339.05
      1558232.32      6883864.49        1558205.        6884388.

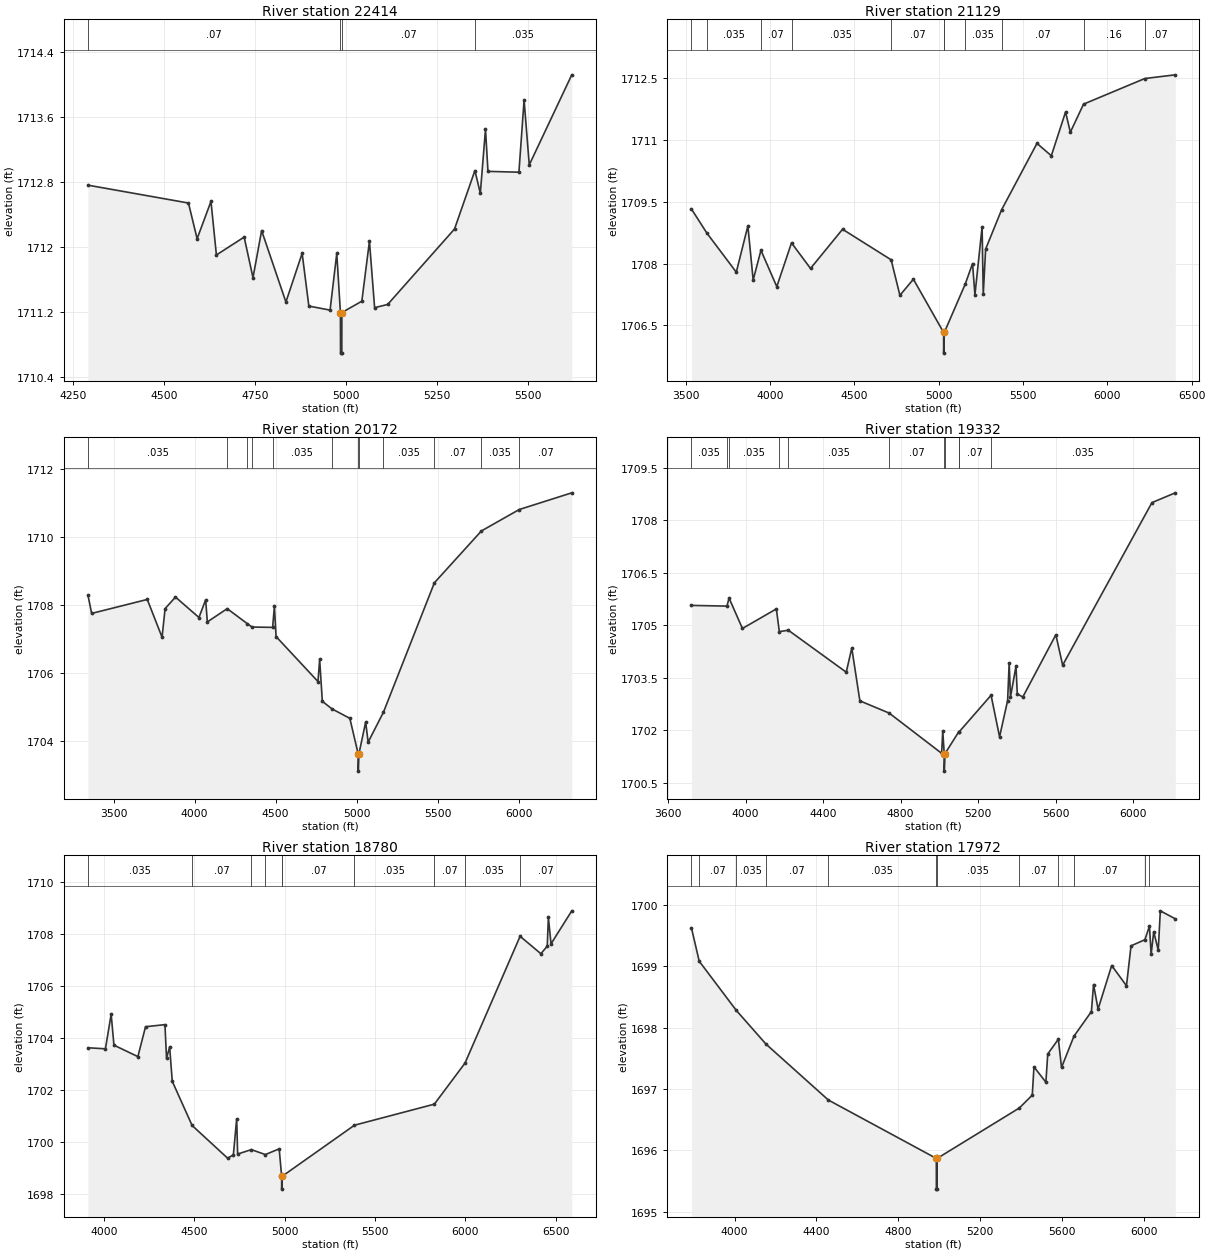
Type RM Length L Ch R = 1 ,22414   ,1285,1285,1285
BEGIN DESCRIPTION:
MULBERRY CREEK TRIBUTARY 7_1 11.0
END DESCRIPTION:
XS GIS Cut Line= 3
      1542314.14      6884509.87      1542588.47      6883855.02
      1542171.82      6883396.02
#Sta/Elev= 30
    4290 1712.76  4566.2 1712.54    4590  1712.1  4628.1 1712.56    4643  1711.9
  4719.3 1712.12  4743.6 1711.62  4767.3  1712.2  4834.1 1711.32  4878.7 1711.92
  4897.1 1711.27  4955.5 1711.22  4973.9 1711.92  4983.9 1711.19  4984.2 1710.69
  4987.7 1710.69  4987.9 1711.19  5042.8 1711.33  5063.7 1712.07  5077.9 1711.25
  5113.8 1711.29  5297.6 1712.22  5353.6 1712.94  5368.5 1712.66  5382.7 1713.45
  5389.5 1712.93  5474.6 1712.92  5488.8 1713.81    5503 1713.01  5619.9 1714.12
#Mann= 4 ,-1 , 0
    4290     .07       0  4983.9     .07       0  4987.9     .07       0
  5353.6    .035       0
Bank Sta=4983.9,4987.9
XS Rating Curve= 0 ,0
Exp/Cntr=0.3,0.1

Type RM Length L Ch R = 1 ,21129   ,957,957,957
BEGIN DESCRIPTION:
MULBERRY CREEK TRIBUTARY 7_1 10.0
END DESCRIPTION:
XS GIS Cut Line= 3
       1543419.7      6884923.82      1543463.97      6883470.68
       1542504.8      6882429.04
#Sta/Elev= 30
    3533 1709.32  3623.9 1708.74  3798.9 1707.79  3867.6 1708.91    3899  1707.6
  3945.1 1708.32  4039.1 1707.44  4126.4  1708.5  4239.1 1707.88  4429.2 1708.83
  4717.4 1708.09  4769.4 1707.23  4849.4 1707.62  5028.7 1706.33    5029 1705.83
  5032.7 1706.33  5156.7  1707.5  5200.3    1708  5214.4 1707.24    5257 1708.89
  5263.8 1707.25  5277.9 1708.35  5372.4  1709.3  5582.5 1710.91  5667.6 1710.61
    5752 1711.67  5780.4 1711.18  5858.7 1711.86  6221.8 1712.48  6402.8 1712.57
#Mann= 11 ,-1 , 0
    3533     .07       0  3623.9    .035       0  3945.1     .07       0
  4126.4    .035       0  4717.4     .07       0  5028.7     .07       0
  5032.7     .07       0  5156.7    .035       0  5372.4     .07       0
  5858.7     .16       0  6221.8     .07       0
Bank Sta=5028.7,5032.7
XS Rating Curve= 0 ,0
Exp/Cntr=0.3,0.1

Type RM Length L Ch R = 1 ,20172   ,840,840,840
BEGIN DESCRIPTION:
MULBERRY CREEK TRIBUTARY 7_1 9.0
END DESCRIPTION:
XS GIS Cut Line= 3
      1543656.39       6884589.9      1544083.47      6882990.93
      1543360.36      6881872.45
#Sta/Elev= 30
  3341.3 1708.28    3364 1707.75  3707.4 1708.16  3798.7 1707.05  3817.3 1707.89
  3881.5 1708.23  4026.4 1707.63  4067.8 1708.15  4078.2  1707.5  4200.9 1707.89
  4324.6 1707.45  4354.2 1707.35  4481.3 1707.34  4492.2 1707.96  4502.5 1707.07
  4761.3 1705.75  4771.6  1706.4  4788.1 1705.17  4846.6 1704.95    4958 1704.67
  5009.7 1703.62    5010 1703.12  5013.7 1703.62  5055.7 1704.56  5070.9 1703.97
  5165.5 1704.85    5480 1708.65    5770 1710.17  6003.8  1710.8  6328.2 1711.29
#Mann= 12 ,-1 , 0
  3341.3    .035       0  4200.9     .07       0  4324.6    .035       0
  4354.2     .07       0  4481.3    .035       0  4846.6     .07       0
  5009.7     .07       0  5013.7     .07       0  5165.5    .035       0
    5480     .07       0    5770    .035       0  6003.8     .07       0
Bank Sta=5009.7,5013.7
XS Rating Curve= 0 ,0
Exp/Cntr=0.3,0.1

Type RM Length L Ch R = 1 ,19332   ,552,552,552
BEGIN DESCRIPTION:
MULBERRY CREEK TRIBUTARY 7_1 7.0
END DESCRIPTION:
XS GIS Cut Line= 4
      1544453.12      6884183.16      1544756.65      6882941.11
      1544570.91      6882642.37      1543930.03      6882063.03
#Sta/Elev= 30
  3721.4 1705.57  3904.4 1705.55  3915.2 1705.78  3984.1 1704.91  4159.1 1705.47
  4174.3 1704.82  4220.8 1704.86  4519.4 1703.66  4547.9 1704.35  4589.6 1702.84
  4740.8 1702.49  5011.1 1701.34    5017 1701.98  5024.4 1701.33  5024.7 1700.83
  5028.4 1701.33  5100.1 1701.96    5101 1701.95  5266.1    1703  5309.8 1701.81
  5351.4 1702.85  5359.4 1703.93  5366.1 1702.95  5394.5 1703.83  5401.2 1703.04
  5429.6 1702.95    5600 1704.73  5635.1 1703.86  6095.4 1708.51  6215.7 1708.79
#Mann= 11 ,-1 , 0
  3721.4    .035       0  3904.4     .07       0  3915.2    .035       0
  4174.3     .07       0  4220.8    .035       0  4740.8     .07       0
  5024.4     .07       0  5028.4     .07       0  5100.1    .035       0
    5101     .07       0  5266.1    .035       0
Bank Sta=5024.4,5028.4
XS Rating Curve= 0 ,0
Exp/Cntr=0.3,0.1

Type RM Length L Ch R = 1 ,18780   ,808,808,808
BEGIN DESCRIPTION:
Mapping XS 2992d0fa
END DESCRIPTION:
XS GIS Cut Line= 3
      1544843.75      6883879.33        1545195.      6882848.96
      1543918.64      6881903.98
#Sta/Elev= 30
  3911.4 1703.62  4007.9 1703.58  4039.6 1704.91  4055.1 1703.72  4187.5 1703.28
  4229.8 1704.43  4337.2 1704.51    4346 1703.22  4363.2 1703.65  4377.7 1702.33
  4487.5 1700.63  4684.1 1699.37  4715.8  1699.5  4734.1 1700.89  4739.4 1699.53
  4815.3  1699.7  4892.8 1699.51  4969.3 1699.73  4982.8 1698.68  4983.1 1698.18
  4986.8 1698.68  5385.8 1700.64  5827.6 1701.45  5997.4 1703.03  6302.2 1707.91
    6417 1707.24  6452.4 1707.53  6458.6 1708.64  6473.3 1707.62  6588.1 1708.89
#Mann= 10 ,-1 , 0
  3911.4    .035       0  4487.5     .07       0  4815.3    .035       0
  4892.8     .07       0  4982.8     .07       0  4986.8     .07       0
  5385.8    .035       0  5827.6     .07       0  5997.4    .035       0
  6302.2     .07       0
Bank Sta=4982.8,4986.8
XS Rating Curve= 0 ,0
Exp/Cntr=0.3,0.1

Type RM Length L Ch R = 1 ,17972   ,716,716,716
BEGIN DESCRIPTION:
MULBERRY CREEK TRIBUTARY 7_1 6.0
END DESCRIPTION:
XS GIS Cut Line= 3
      1545354.04       6883715.4        1545805.        6882588.
      1544779.98      6882062.99
#Sta/Elev= 30
  3789.1 1699.62    3827 1699.08  4008.1 1698.28  4153.7 1697.73  4458.7 1696.82
  4986.5 1695.87  4986.8 1695.37  4990.3 1695.37  4990.5 1695.87  5392.2 1696.69
  5455.7  1696.9    5464 1697.36  5522.3 1697.11  5531.4 1697.57  5583.3 1697.81
  5598.8 1697.35  5659.6 1697.86  5744.9 1698.26  5755.3  1698.7  5777.5  1698.3
  5844.1 1699.01  5916.4 1698.68  5938.6 1699.33  6006.5 1699.43  6028.8 1699.65
    6037 1699.19  6049.6 1699.56  6071.8 1699.26  6081.9  1699.9    6155 1699.77
#Mann= 12 ,-1 , 0
  3789.1    .035       0    3827     .07       0  4008.1    .035       0
  4153.7     .07       0  4458.7    .035       0  4986.5    .035       0
  4990.5    .035       0  5392.2     .07       0  5583.3    .035       0
  5659.6     .07       0  6006.5    .035       0  6028.8     .07       0
Bank Sta=4986.5,4990.5
XS Rating Curve= 0 ,0
Exp/Cntr=0.3,0.1

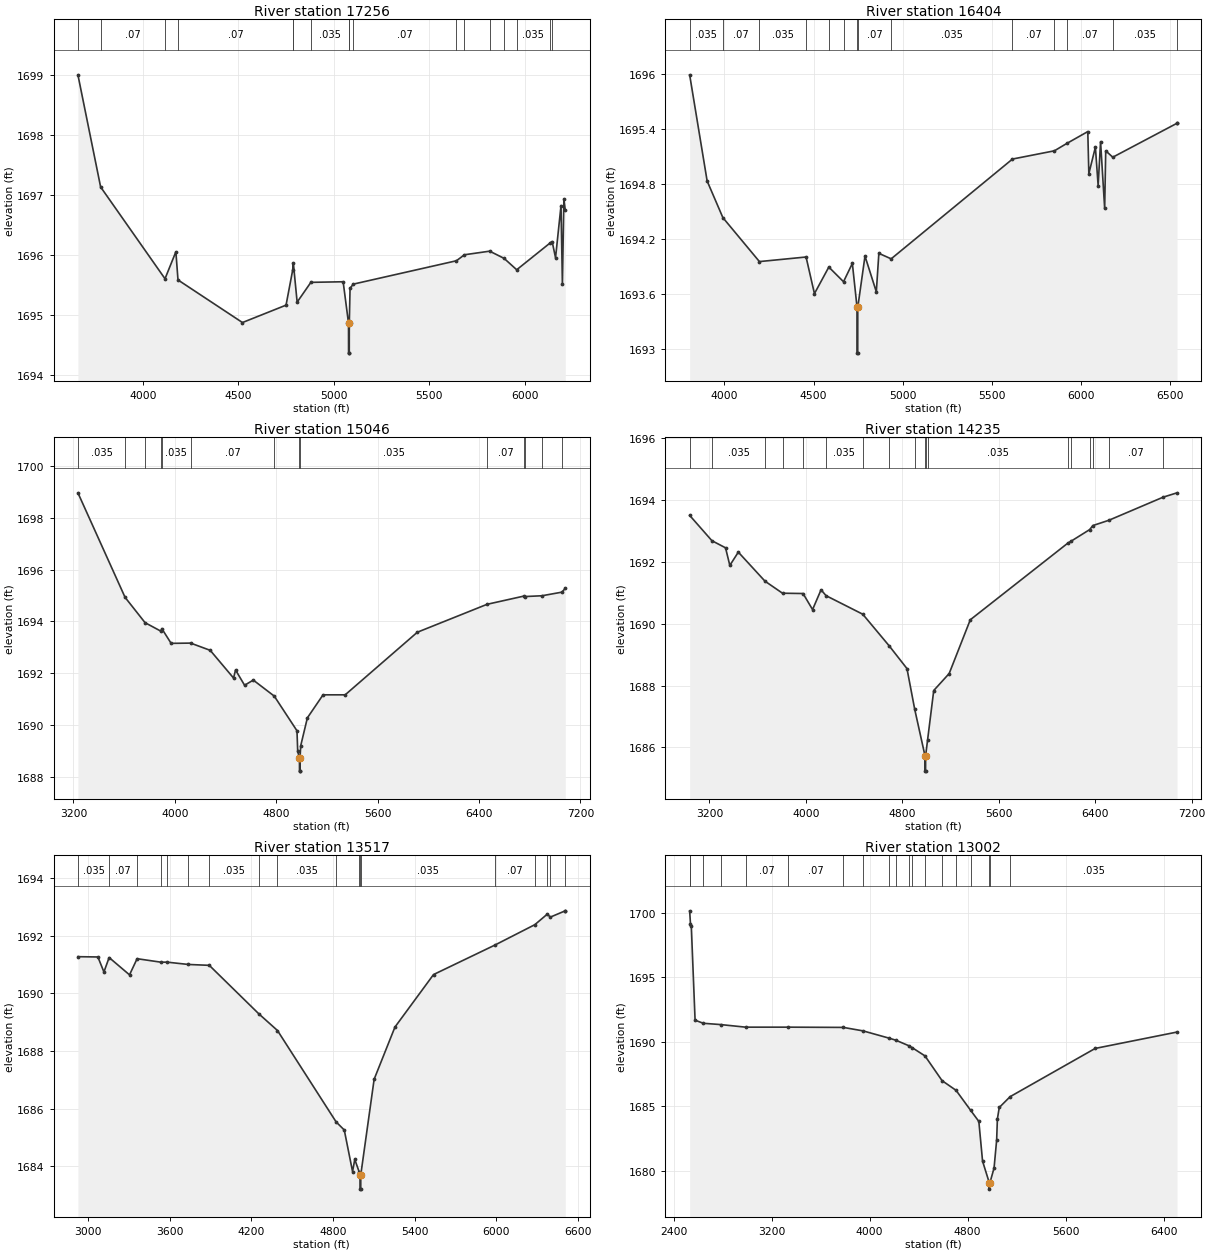
Type RM Length L Ch R = 1 ,17256   ,852,852,852
BEGIN DESCRIPTION:
Mapping XS 49e828e9
END DESCRIPTION:
XS GIS Cut Line= 3
      1545546.38      6883888.86      1546364.63      6882827.19
      1545696.97      6881815.32
#Sta/Elev= 30
  3659.6 1699.01  3778.6 1697.14  4115.8 1695.61  4172.7 1696.06  4183.8 1695.59
  4521.4 1694.88  4749.7 1695.17  4784.2 1695.75    4788 1695.87  4807.8 1695.22
  4879.7 1695.55  5048.8 1695.56  5076.9 1694.87  5077.2 1694.37  5080.8 1694.37
    5081 1694.87    5085 1695.45  5101.5 1695.52  5642.1 1695.91  5684.1 1696.01
  5816.2 1696.07  5891.7 1695.95  5957.8 1695.76  6130.2  1696.2  6143.4 1696.23
  6161.2 1695.96  6189.9 1696.83  6197.1 1695.52  6204.9 1696.94  6212.3 1696.75
#Mann= 17 ,-1 , 0
  3659.6    .035       0  3778.6     .07       0  4115.8    .035       0
  4183.8     .07       0  4784.2    .035       0    4788     .07       0
  4879.7    .035       0  5076.9    .035       0    5081    .035       0
  5101.5     .07       0  5642.1    .035       0  5684.1     .07       0
  5816.2    .035       0  5891.7     .07       0  5957.8    .035       0
  6130.2     .07       0  6143.4    .035       0
Bank Sta=5076.9,5081
XS Rating Curve= 0 ,0
Exp/Cntr=0.3,0.1

Type RM Length L Ch R = 1 ,16404   ,1358,1358,1358
BEGIN DESCRIPTION:
MULBERRY CREEK TRIBUTARY 7_1 5.0
END DESCRIPTION:
XS GIS Cut Line= 3
      1545855.04      6884126.71        1546878.       6883034.3
        1546230.      6881983.18
#Sta/Elev= 30
  3805.5 1695.99  3903.5 1694.83  3991.7 1694.43  4196.4 1693.95  4457.9    1694
  4504.8  1693.6  4585.4 1693.89  4667.8 1693.73  4717.3 1693.93  4743.6 1693.45
  4743.8 1692.95  4747.4 1692.95  4747.7 1693.45  4788.1 1694.01  4851.6 1693.62
  4865.8 1694.04  4934.8 1693.98  5614.7 1695.07  5849.5 1695.16  5918.7 1695.24
  6036.7 1695.37  6042.6 1694.91  6079.3  1695.2  6094.7 1694.78  6108.3 1695.26
  6131.3 1694.53  6137.2 1695.16  6176.7 1695.09  6535.7 1695.46  6536.9 1695.46
#Mann= 14 ,-1 , 0
  3805.5    .035       0  3991.7     .07       0  4196.4    .035       0
  4457.9     .07       0  4585.4    .035       0  4667.8     .07       0
  4743.6    .035       0  4747.7     .07       0  4934.8    .035       0
  5614.7     .07       0  5849.5    .035       0  5918.7     .07       0
  6176.7    .035       0  6535.7    .045       0
Bank Sta=4743.6,4747.7
XS Rating Curve= 0 ,0
Exp/Cntr=0.3,0.1

Type RM Length L Ch R = 1 ,15046   ,811,811,811
BEGIN DESCRIPTION:
Mapping XS c377bea3
END DESCRIPTION:
XS GIS Cut Line= 4
      1545777.04      6885051.28      1547144.24      6884287.39
      1547365.59      6883766.56      1546623.79      6882222.22
#Sta/Elev= 30
  3235.7 1698.97  3607.6 1694.93  3765.4 1693.95  3890.7 1693.62  3897.6 1693.72
  3971.2 1693.15  4125.1 1693.16  4279.6 1692.88  4463.5 1691.81  4479.5 1692.12
  4550.7 1691.53  4619.4 1691.73  4784.9 1691.11  4964.1 1689.77  4969.8 1688.98
  4983.7 1688.71    4984 1688.21  4987.8 1688.21  4988.1 1688.71  4993.4 1689.19
  5046.1 1690.27  5169.8 1691.16  5344.4 1691.16  5913.6 1693.58  6463.9 1694.66
  6756.4 1694.98  6763.1 1694.96  6896.3 1694.99  7054.6 1695.13    7081 1695.28
#Mann= 14 ,-1 , 0
  3235.7    .035       0  3607.6     .07       0  3765.4    .035       0
  3890.7     .07       0  3897.6    .035       0  4125.1     .07       0
  4784.9    .035       0  4983.7    .035       0  4988.1    .035       0
  6463.9     .07       0  6756.4    .035       0  6763.1     .07       0
  6896.3    .035       0  7054.6     .07       0
Bank Sta=4983.7,4988.1
XS Rating Curve= 0 ,0
Exp/Cntr=0.3,0.1

Type RM Length L Ch R = 1 ,14235   ,718,718,718
BEGIN DESCRIPTION:
Mapping XS fca1775d
END DESCRIPTION:
XS GIS Cut Line= 3
      1546661.05      6885594.79      1547931.89      6884402.08
       1547015.3      6882292.89
#Sta/Elev= 30
  3035.9 1693.51  3220.5 1692.69  3333.5 1692.46  3369.1 1691.89  3439.5 1692.32
  3660.7 1691.38    3806 1690.99  3976.5 1690.98  4055.4 1690.46  4125.7  1691.1
  4167.6 1690.91  4471.7 1690.31  4692.1 1689.28  4838.4 1688.55  4902.7 1687.23
  4987.7 1685.73  4988.1 1685.23  4992.7 1685.23  4993.1 1685.73  5009.1 1686.23
  5060.4 1687.84  5188.5 1688.39  5363.6 1690.13  6172.1 1692.61  6202.1 1692.68
    6354 1693.05  6379.9 1693.18    6512 1693.35  6963.4  1694.1  7078.5 1694.24
#Mann= 18 ,-1 , 0
  3035.9     .07       0  3220.5    .035       0  3660.7     .07       0
    3806    .035       0  3976.5     .07       0  4167.6    .035       0
  4471.7     .07       0  4692.1    .035       0  4902.7     .07       0
  4987.7     .07       0  4993.1     .07       0  5009.1    .035       0
  6172.1     .07       0  6202.1    .035       0    6354     .07       0
  6379.9    .035       0    6512     .07       0  6963.4    .035       0
Bank Sta=4987.7,4993.1
XS Rating Curve= 0 ,0
Exp/Cntr=0.3,0.1

Type RM Length L Ch R = 1 ,13517   ,515,515,515
BEGIN DESCRIPTION:
MULBERRY CREEK TRIBUTARY 7_1 4.0
END DESCRIPTION:
XS GIS Cut Line= 3
      1547404.98      6885588.03      1548357.23      6883739.32
      1547641.66      6882415.95
#Sta/Elev= 30
  2923.8 1691.27  3070.7 1691.26  3115.1 1690.74  3153.4 1691.24  3303.3 1690.64
  3359.1  1691.2    3533 1691.08  3580.4 1691.08  3736.6    1691  3889.9 1690.97
  4253.8 1689.29  4391.3 1688.71  4822.6 1685.54  4882.5 1685.26  4943.4 1683.82
  4959.8 1684.24  4991.8 1683.81  4998.5 1683.71    4999 1683.21  5003.6 1683.21
    5004 1683.71  5102.1 1687.02  5255.2 1688.83  5538.8 1690.65    5989 1691.67
  6283.8 1692.38  6376.5 1692.75  6396.8 1692.64  6502.3 1692.85  6507.8 1692.86
#Mann= 18 ,-1 , 0
  2923.8    .035       0  3153.4     .07       0  3359.1    .035       0
    3533     .07       0  3580.4    .035       0  3736.6     .07       0
  3889.9    .035       0  4253.8     .07       0  4391.3    .035       0
  4822.6     .07       0  4991.8    .035       0  4998.5    .035       0
    5004    .035       0    5989     .07       0  6283.8    .035       0
  6376.5     .07       0  6396.8    .035       0  6502.3     .07       0
Bank Sta=4998.5,5004
XS Rating Curve= 0 ,0
Exp/Cntr=0.3,0.1

Type RM Length L Ch R = 1 ,13002   ,913,913,913
BEGIN DESCRIPTION:
MULBERRY CREEK TRIBUTARY 7_1 3.0
END DESCRIPTION:
XS GIS Cut Line= 4
      1547305.02      6885937.97      1548440.28        6884100.
      1548861.29       6883830.9      1548483.69      6882567.91
#Sta/Elev= 30
  2530.8 1700.14  2537.4 1699.14  2544.3 1698.95  2575.1 1691.66  2642.2 1691.42
  2783.4 1691.32    2987 1691.12  3332.7 1691.12  3785.4  1691.1  3946.3 1690.83
  4161.3 1690.26    4213 1690.11  4319.7 1689.68  4345.5 1689.54  4451.6 1688.89
  4591.2 1686.97  4705.3 1686.22    4825 1684.66  4891.2 1683.81  4921.6 1680.73
  4976.3 1679.06  4976.8 1678.56  4981.9 1679.06  5015.5  1680.2  5036.6 1682.37
  5042.6    1684  5057.8 1684.89  5146.6 1685.73  5840.9 1689.47    6509 1690.74
#Mann= 19 ,-1 , 0
  2530.8     .07       0  2537.4    .035       0  2642.2     .07       0
  2783.4    .035       0    2987     .07       0  3332.7     .07       0
  3785.4    .035       0  3946.3     .07       0  4161.3    .035       0
    4213     .07       0  4319.7    .035       0  4345.5     .07       0
  4451.6    .035       0  4591.2     .07       0  4705.3    .035       0
    4825     .07       0  4976.3     .07       0  4981.9     .07       0
  5146.6    .035       0
Bank Sta=4976.3,4981.9
XS Rating Curve= 0 ,0
Exp/Cntr=0.3,0.1

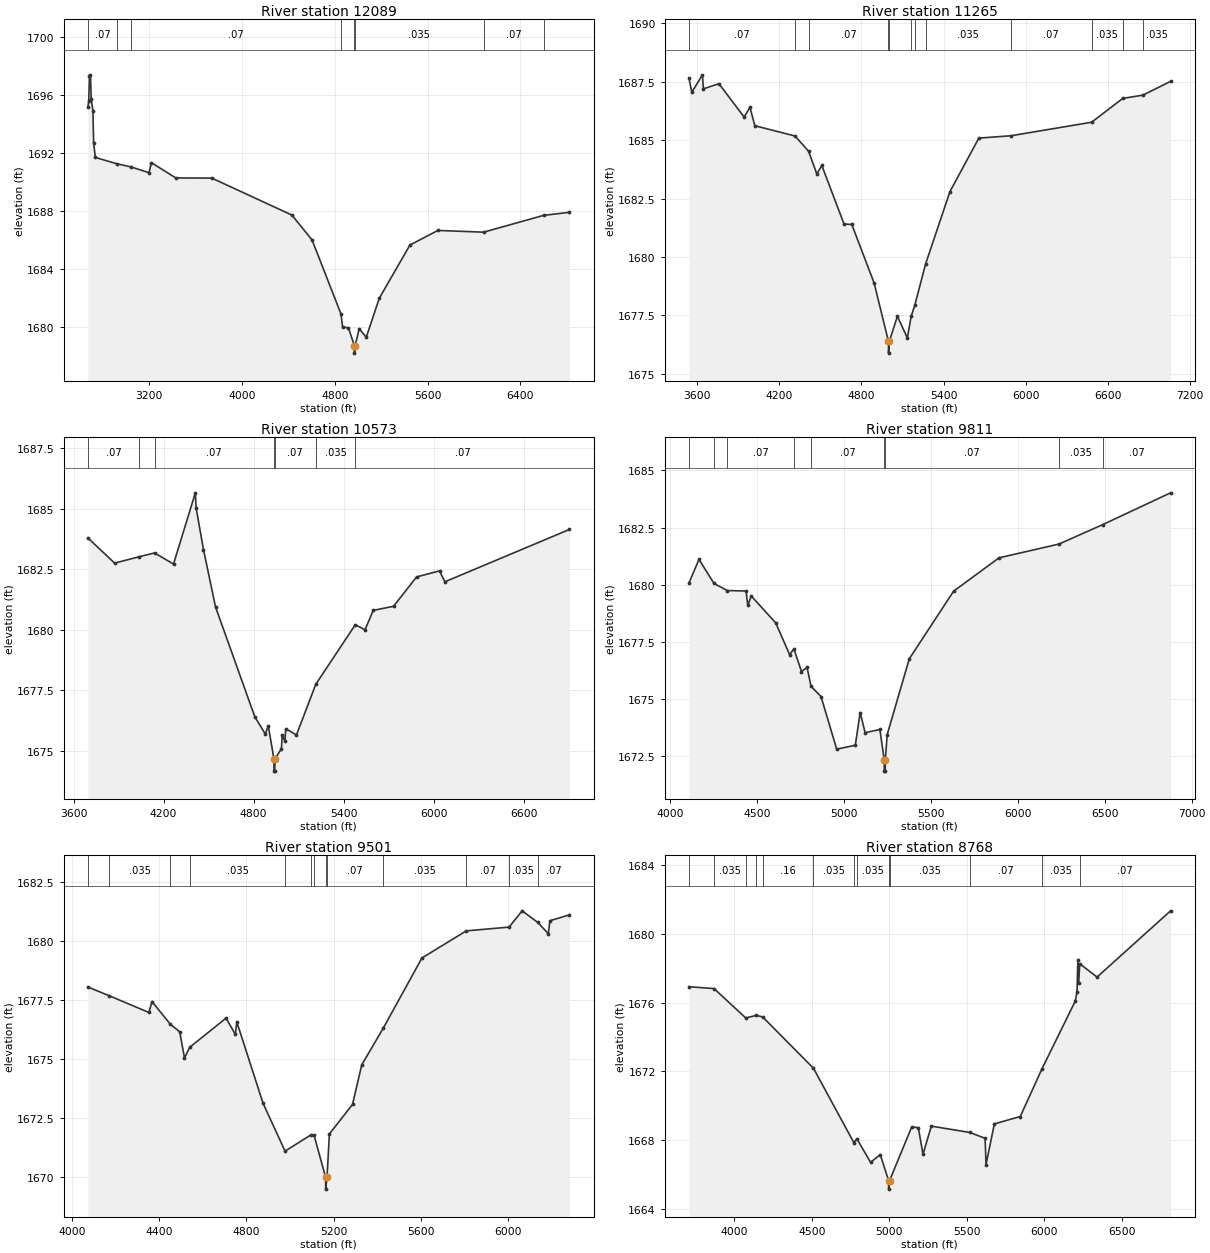
Type RM Length L Ch R = 1 ,12089   ,824,824,824
BEGIN DESCRIPTION:
MULBERRY CREEK TRIBUTARY 7_1 2.0
END DESCRIPTION:
XS GIS Cut Line= 4
      1547455.03      6885987.98      1549148.18      6884855.57
      1549379.95      6884209.73        1549255.      6882788.01
#Sta/Elev= 30
  2672.3 1695.17  2679.8 1695.57  2685.8  1697.3  2694.8  1697.4  2700.8 1695.75
  2715.8 1694.91  2721.8 1692.71  2736.8  1691.7  2925.6 1691.26  3044.3 1691.05
  3199.2 1690.65  3220.3 1691.34  3430.2 1690.29  3739.7 1690.28  4430.4 1687.73
  4604.5 1686.01    4854  1680.9    4867 1680.02  4917.8 1679.95  4969.4 1678.71
  4969.9 1678.21  4975.1 1678.71  5010.1 1679.89  5071.5 1679.31  5183.9    1682
  5447.3 1685.66  5688.3 1686.67    6082 1686.55  6600.4 1687.71  6822.6 1687.92
#Mann= 8 ,-1 , 0
  2672.3     .07       0  2925.6    .035       0  3044.3     .07       0
    4854    .035       0  4969.4    .035       0  4975.1    .035       0
    6082     .07       0  6600.4    .035       0
Bank Sta=4969.4,4975.1
XS Rating Curve= 0 ,0
Exp/Cntr=0.3,0.1

Type RM Length L Ch R = 1 ,11265   ,692,692,692
BEGIN DESCRIPTION:
Mapping XS d88aa218
END DESCRIPTION:
XS GIS Cut Line= 3
      1548924.06      6885886.19      1549878.94      6884805.43
      1549327.72      6882804.53
#Sta/Elev= 30
    3540 1687.66  3560.8 1687.05  3638.6  1687.8  3645.3  1687.2  3759.1 1687.42
  3943.1 1685.99  3985.8 1686.41  4020.9 1685.62  4314.6 1685.18  4413.3 1684.53
  4474.3 1683.55  4510.3 1683.92  4672.5 1681.41  4729.4 1681.39  4892.6 1678.88
  4997.3 1676.38  4997.8 1675.88  5003.1 1676.38  5062.5 1677.46  5135.1 1676.53
  5163.2 1677.46  5189.4 1677.93  5268.9 1679.71  5446.3  1682.8  5657.4 1685.09
  5891.5 1685.19    6481 1685.77  6708.5 1686.79  6855.7 1686.93  7057.6 1687.52
#Mann= 12 ,-1 , 0
    3540     .07       0  4314.6    .035       0  4413.3     .07       0
  4997.3     .07       0  5003.1     .07       0  5163.2    .035       0
  5189.4     .07       0  5268.9    .035       0  5891.5     .07       0
    6481    .035       0  6708.5     .07       0  6855.7    .035       0
Bank Sta=4997.3,5003.1
XS Rating Curve= 0 ,0
Exp/Cntr=0.3,0.1

Type RM Length L Ch R = 1 ,10573   ,762,762,762
BEGIN DESCRIPTION:
Mapping XS c8f2827a
END DESCRIPTION:
XS GIS Cut Line= 4
      1550010.96      6885895.12      1550448.48      6885346.48
      1550504.04      6884770.09      1549754.19      6882992.68
#Sta/Elev= 30
  3695.7 1683.79    3874 1682.75  4034.9 1683.01  4140.2 1683.17  4266.4 1682.71
  4412.1 1685.65  4417.1 1685.03  4466.2 1683.31  4546.6 1680.94  4807.8 1676.42
  4878.1  1675.7  4898.2 1676.04  4935.9 1674.67  4936.4 1674.17  4941.5 1674.17
    4942 1674.67  4985.5 1675.09    4991 1675.65  5009.2 1675.41  5014.7 1675.92
  5085.8 1675.66  5214.5 1677.75  5478.2 1680.21  5543.1    1680  5597.4  1680.8
    5733 1680.97  5886.2 1682.18  6039.3 1682.43    6075 1681.98  6905.6 1684.14
#Mann= 7 ,-1 , 0
  3695.7     .07       0  4034.9    .035       0  4140.2     .07       0
  4935.9     .07       0    4942     .07       0  5214.5    .035       0
  5478.2     .07       0
Bank Sta=4935.9,4942
XS Rating Curve= 0 ,0
Exp/Cntr=0.3,0.1

Type RM Length L Ch R = 1 ,9811    ,310,310,310
BEGIN DESCRIPTION:
Mapping XS 4232ce48
END DESCRIPTION:
XS GIS Cut Line= 3
      1551194.04      6885265.47      1551120.26      6884380.09
      1549814.53       6883022.3
#Sta/Elev= 30
  4106.4 1680.08  4164.1 1681.11  4250.5 1680.06  4327.7 1679.75    4435 1679.73
    4445 1679.11  4465.1 1679.51  4605.6 1678.34  4685.9 1676.95  4710.5  1677.2
  4754.1 1676.21  4786.2 1676.39    4809 1675.57  4866.5 1675.12  4956.8 1672.82
  5063.8 1672.99  5092.1 1674.42  5120.4 1673.54  5205.3 1673.68  5230.3 1672.36
  5230.8 1671.86  5236.3 1671.86  5236.8 1672.36  5247.5 1673.46  5374.8 1676.77
  5629.5 1679.72  5891.1 1681.18  6235.7 1681.78  6487.9 1682.63  6878.6 1684.02
#Mann= 9 ,-1 , 0
  4106.4     .07       0  4250.5    .035       0  4327.7     .07       0
  4710.5    .035       0    4809     .07       0  5230.3     .07       0
  5236.8     .07       0  6235.7    .035       0  6487.9     .07       0
Bank Sta=5230.3,5236.8
XS Rating Curve= 0 ,0
Exp/Cntr=0.3,0.1

Type RM Length L Ch R = 1 ,9501    ,733,733,733
BEGIN DESCRIPTION:
Mapping XS 04762a37
END DESCRIPTION:
XS GIS Cut Line= 3
      1551914.53      6884843.63      1551306.62      6884141.94
       1550358.6      6883277.16
#Sta/Elev= 30
  4071.6 1678.05  4169.6 1677.68  4351.9 1676.97  4366.1 1677.43  4450.6 1676.47
  4493.3 1676.15  4515.2 1675.05  4540.1  1675.5  4706.1 1676.73  4748.8 1676.04
  4755.5 1676.57  4876.1 1673.12  4977.1 1671.09    5094 1671.77  5110.3 1671.76
  5163.3 1669.98  5163.8 1669.48  5169.8 1669.98  5180.7 1671.82  5286.8 1673.07
  5329.3 1674.75  5428.9 1676.32  5605.7 1679.28  5809.2 1680.43  6005.9 1680.59
  6065.8 1681.28  6137.3 1680.79    6186 1680.31  6193.3 1680.86  6283.2 1681.11
#Mann= 13 ,-1 , 0
  4071.6     .07       0  4169.6    .035       0  4450.6     .07       0
  4540.1    .035       0  4977.1     .07       0    5094    .035       0
  5110.3     .07       0  5163.3     .07       0  5169.8     .07       0
  5428.9    .035       0  5809.2     .07       0  6005.9    .035       0
  6137.3     .07       0
Bank Sta=5163.3,5169.8
XS Rating Curve= 0 ,0
Exp/Cntr=0.3,0.1

Type RM Length L Ch R = 1 ,8768    ,417,417,417
BEGIN DESCRIPTION:
Mapping XS 6094d92a
END DESCRIPTION:
XS GIS Cut Line= 3
      1552480.43      6885028.09      1551938.34      6883854.66
      1550254.76      6883180.87
#Sta/Elev= 30
  3707.4 1676.92  3869.4 1676.81  4073.6  1675.1  4141.6 1675.25  4182.8 1675.16
  4510.5 1672.17  4770.7 1667.84  4790.5 1668.06  4878.7 1666.69  4941.2 1667.14
  4994.8 1665.63  4995.3 1665.13  5001.3 1665.63    5144 1668.75  5186.7 1668.71
  5216.7 1667.16  5270.5  1668.8  5519.1 1668.43  5617.5 1668.09  5623.2 1666.56
    5677 1668.93    5844 1669.36  5984.7 1672.15  6199.2 1676.09    6210 1676.63
  6215.5  1678.5  6220.8 1677.14  6227.5 1678.26  6339.2 1677.48  6813.4 1681.34
#Mann= 13 ,-1 , 0
  3707.4     .16       0  3869.4    .035       0  4073.6     .16       0
  4141.6    .035       0  4182.8     .16       0  4510.5    .035       0
  4770.7     .07       0  4790.5    .035       0  4994.8    .035       0
  5001.3    .035       0  5519.1     .07       0  5984.7    .035       0
  6227.5     .07       0
Bank Sta=4994.8,5001.3
XS Rating Curve= 0 ,0
Exp/Cntr=0.3,0.1

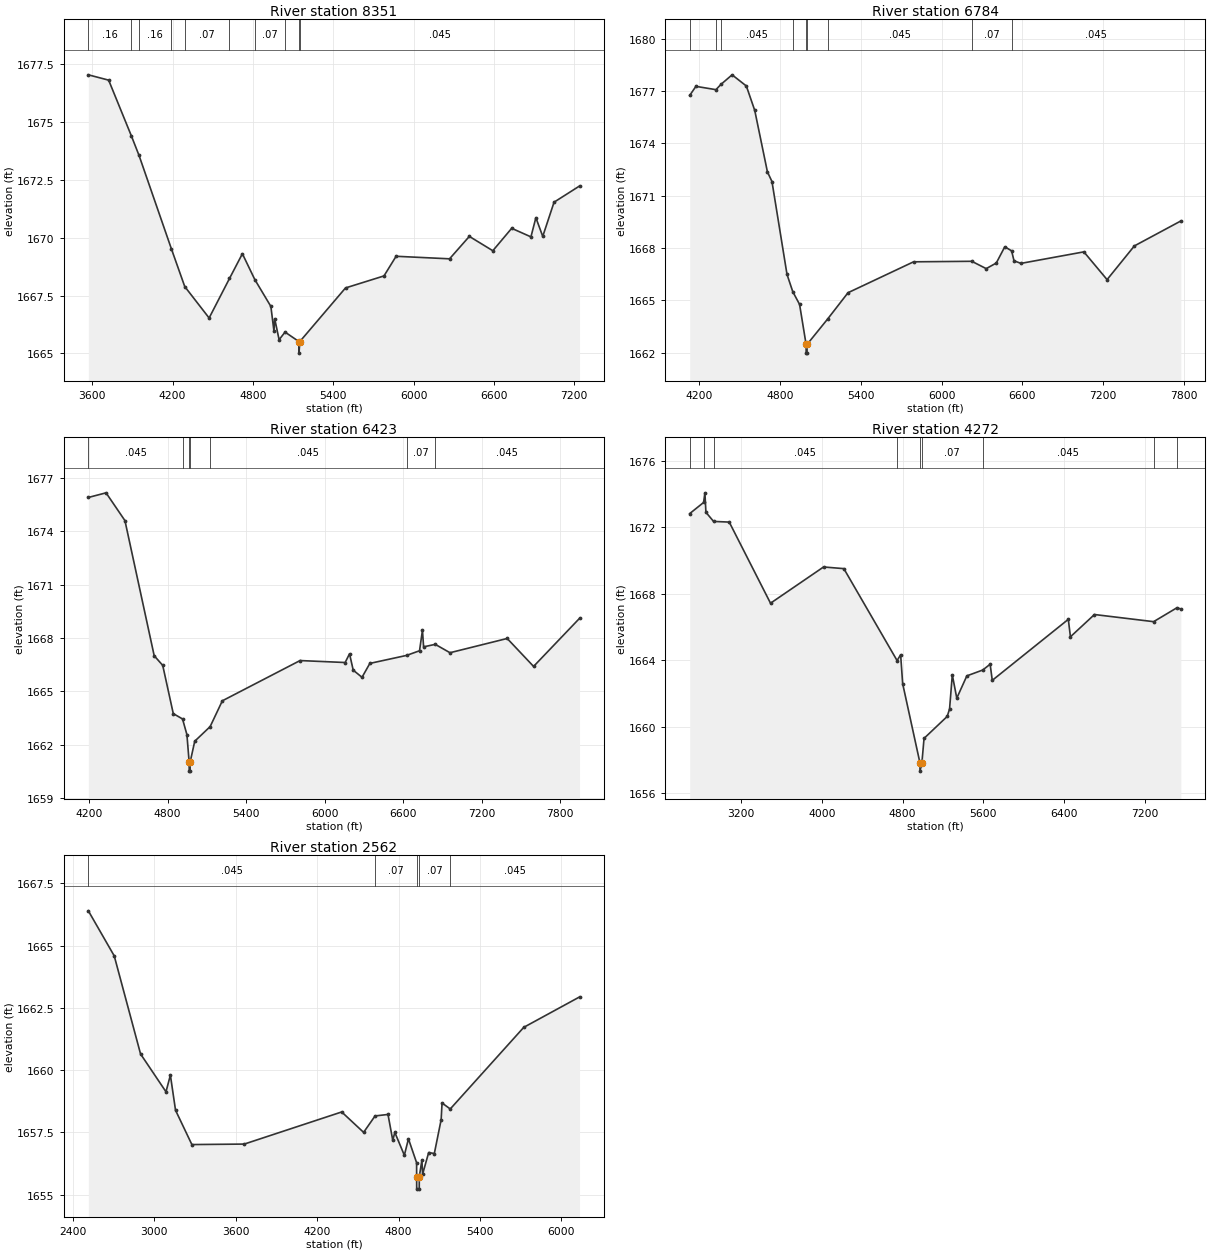
Type RM Length L Ch R = 1 ,8351    ,1567,1567,1567
BEGIN DESCRIPTION:
Mapping XS 3e7609e0
END DESCRIPTION:
XS GIS Cut Line= 4
      1552568.96      6885017.64      1552391.88      6883939.54
      1551897.09       6882856.2      1550584.62      6882418.71
#Sta/Elev= 30
  3571.7 1677.05  3723.3 1676.82  3892.8 1674.41  3950.3 1673.56  4191.8 1669.52
  4291.4 1667.89  4473.3 1666.53  4625.5 1668.24  4721.7 1669.31  4814.7 1668.19
  4934.4 1667.03  4957.5 1665.96  4962.9  1666.5  4995.8 1665.59  5040.3 1665.92
  5143.9 1665.51  5144.4 1665.01  5150.5 1665.51  5491.6 1667.83  5778.9 1668.35
  5869.3  1669.2  6268.5 1669.09  6416.1 1670.06  6591.4 1669.44  6732.3 1670.41
    6876 1670.04  6912.9 1670.87  6964.2 1670.06  7048.6 1671.54  7238.7 1672.24
#Mann= 10 ,-1 , 0
  3571.7     .16       0  3892.8    .035       0  3950.3     .16       0
  4191.8    .035       0  4291.4     .07       0  4625.5    .035       0
  4814.7     .07       0  5040.3    .045       0  5143.9     .07       0
  5150.5    .045       0
Bank Sta=5143.9,5150.5
XS Rating Curve= 0 ,0
Exp/Cntr=0.3,0.1

Type RM Length L Ch R = 1 ,6784    ,361,361,361
BEGIN DESCRIPTION:
Mapping XS 762a0abf
END DESCRIPTION:
XS GIS Cut Line= 4
       1552902.3      6885262.45      1553147.09      6884408.29
      1553397.09      6883090.58       1552112.1       6882492.3
#Sta/Elev= 30
  4129.1 1676.74  4175.3 1677.26  4324.1 1677.07  4360.9 1677.37    4444 1677.92
  4549.8 1677.28  4612.2 1675.88  4706.3 1672.36    4740 1671.81  4851.7 1666.49
  4894.6  1665.5  4945.1 1664.77  4993.5 1662.48    4994 1661.98  5000.3 1661.98
  5000.8 1662.48    5153 1663.93  5304.8 1665.44  5791.5 1667.21  6223.8 1667.24
  6330.9 1666.82  6405.7 1667.14  6468.8 1668.07  6519.4 1667.84  6537.4 1667.27
  6588.7 1667.12  7056.1 1667.78  7228.4 1666.19  7431.1 1668.12  7776.3 1669.55
#Mann= 9 ,-1 , 0
  4129.1    .045       0  4324.1     .07       0  4360.9    .045       0
  4894.6     .07       0  4993.5     .07       0  5000.8     .07       0
    5153    .045       0  6223.8     .07       0  6519.4    .045       0
Bank Sta=4993.5,5000.8
XS Rating Curve= 0 ,0
Exp/Cntr=0.3,0.1

Type RM Length L Ch R = 1 ,6423    ,2151,2151,2151
BEGIN DESCRIPTION:
MULBERRY CREEK TRIBUTARY 7_1 1.0
END DESCRIPTION:
XS GIS Cut Line= 3
      1553241.55      6885211.03      1553810.98      6883259.68
       1552269.9       6882494.8
#Sta/Elev= 30
  4194.6 1675.89  4329.9 1676.15  4474.2 1674.59  4697.8    1667  4762.9 1666.46
  4843.6 1663.75  4914.3 1663.45  4947.8 1662.57  4964.9 1661.02  4965.4 1660.52
  4971.8 1660.52  4972.3 1661.02  5007.6  1662.2  5125.2 1663.02  5218.6 1664.47
  5812.4 1666.73  6156.9 1666.62  6190.4 1667.11  6218.6 1666.19  6285.8 1665.79
  6345.7 1666.57  6626.7 1667.02  6725.2 1667.28  6747.6 1668.43  6756.4  1667.5
  6845.4 1667.64  6958.1 1667.17  7395.1 1667.97  7596.8  1666.4  7947.8  1669.1
#Mann= 7 ,-1 , 0
  4194.6    .045       0  4914.3     .07       0  4964.9     .07       0
  4972.3     .07       0  5125.2    .045       0  6626.7     .07       0
  6845.4    .045       0
Bank Sta=4964.9,4972.3
XS Rating Curve= 0 ,0
Exp/Cntr=0.3,0.1

Type RM Length L Ch R = 1 ,4272    ,1710,1710,1710
BEGIN DESCRIPTION:
MULBERRY CREEK TRIBUTARY 7 2.0
END DESCRIPTION:
XS GIS Cut Line= 3
        1555605.      6886488.02      1555359.99      6884185.02
       1553262.7      6882726.65
#Sta/Elev= 30
  2689.4 1672.83  2827.3  1673.5  2840.3 1674.08  2850.3 1672.91  2926.1 1672.36
  3081.6 1672.32  3490.9 1667.44  4016.9 1669.62    4218 1669.52    4746 1663.99
  4781.2 1664.34  4801.3  1662.6  4972.6 1657.84  4973.1 1657.34    4992 1657.84
  5013.3 1659.31  5242.9 1660.63  5266.4 1661.08  5293.5 1663.13    5338 1661.73
  5437.8 1663.07  5594.8 1663.42  5668.8 1663.77  5689.8  1662.8  6443.9 1666.47
  6464.9 1665.42  6703.2 1666.76  7289.8 1666.33  7521.9 1667.17  7559.9 1667.09
#Mann= 9 ,-1 , 0
  2689.4    .045       0  2827.3    .035       0  2926.1    .045       0
    4746     .07       0  4972.6     .07       0    4992     .07       0
  5594.8    .045       0  7289.8     .07       0  7521.9    .045       0
Bank Sta=4972.6,4992
XS Rating Curve= 0 ,0
Exp/Cntr=0.3,0.1

Type RM Length L Ch R = 1 ,2562    ,0,0,0
BEGIN DESCRIPTION:
MULBERRY CREEK TRIBUTARY 7 1.0
END DESCRIPTION:
XS GIS Cut Line= 3
        1556605.      6886087.99      1556832.16      6883611.58
      1555979.97      6882862.98
#Sta/Elev= 30
  2513.2  1666.4    2704 1664.59  2898.1 1660.65  3085.6 1659.13    3118  1659.8
  3155.9 1658.39  3276.4 1657.01  3662.8 1657.03    4381 1658.32  4542.6  1657.5
    4627 1658.16  4722.4 1658.22  4757.5 1657.18  4772.6  1657.5  4842.9 1656.58
  4873.1 1657.24  4933.3 1656.28  4933.5 1655.72    4934 1655.22  4952.6 1655.22
  4953.1 1655.72  4972.4 1656.39  4977.4 1655.82  5022.2 1656.69  5063.9 1656.65
  5114.2 1658.01  5120.9 1658.68  5181.3 1658.44  5723.4 1661.72  6134.3 1662.94
#Mann= 5 ,-1 , 0
  2513.2    .045       0    4627     .07       0  4933.5     .07       0
  4953.1     .07       0  5181.3    .045       0
Bank Sta=4933.5,4953.1
XS Rating Curve= 0 ,0
Exp/Cntr=0.3,0.1

Chan Stop Cuts=-1
Use User Specified Reach Order=0
Composite Channel Slope=5