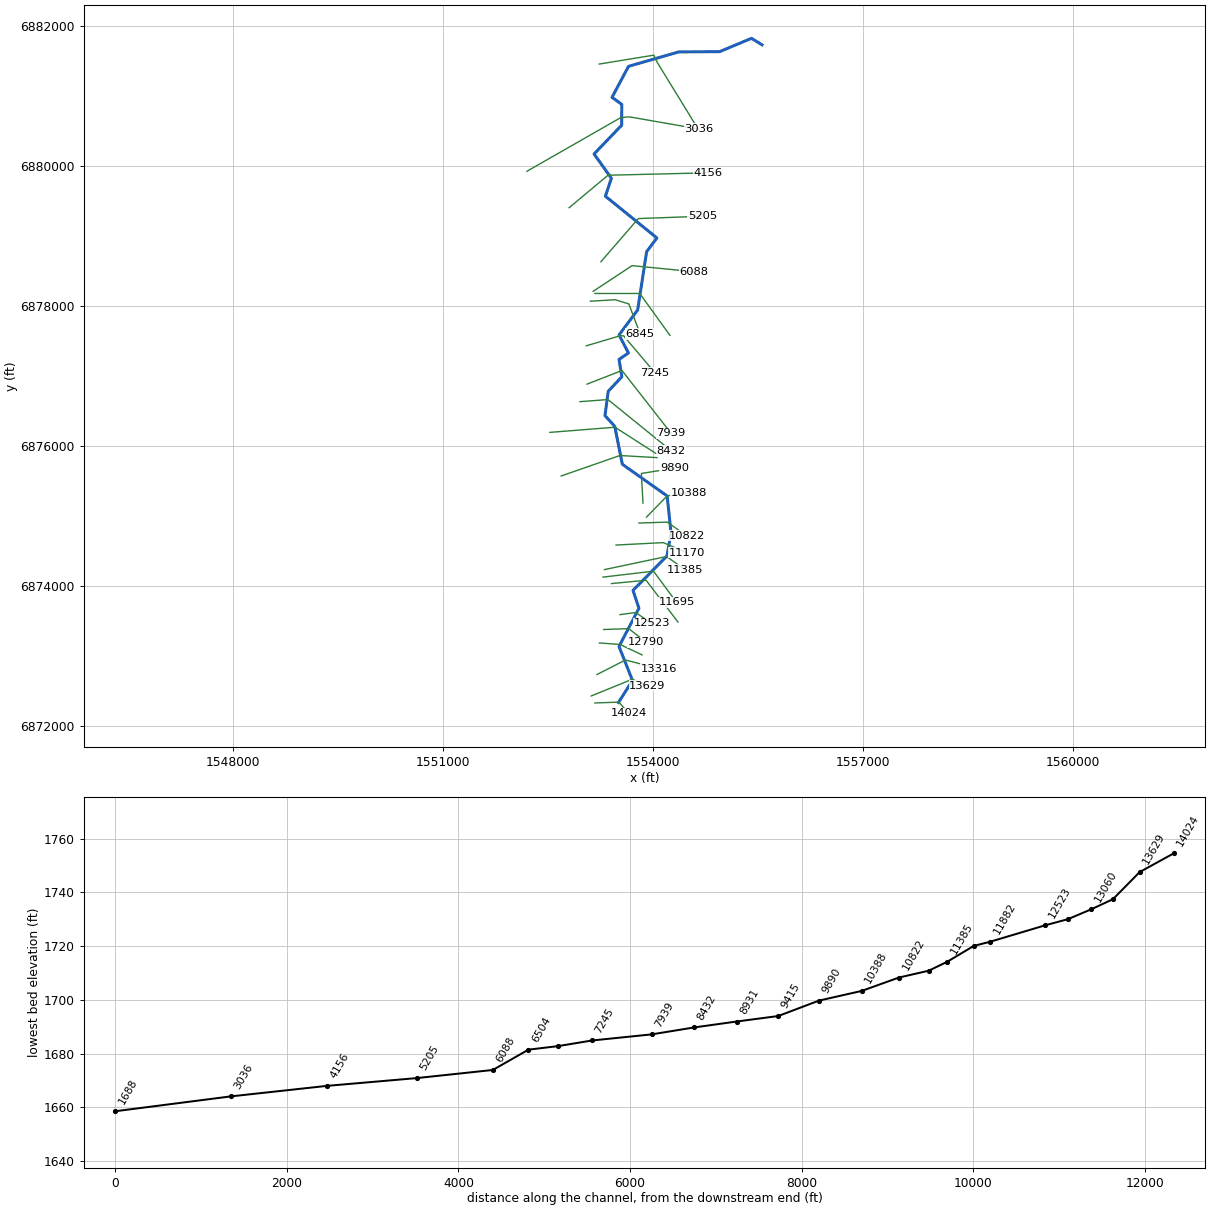
--- MULBERRY CREEK TRIBUTARY 8.prj (project) ---

Proj Title=MULBERRY CREEK TRIBUTARY 8 Base Level Engineering
Current Plan=p01
Default Exp/Contr=0.3,0.1
English Units
Geom File=g01
Flow File=f01
Plan File=p01
BEGIN DESCRIPTION:
MULBERRY CREEK TRIBUTARY 8
END DESCRIPTION:

--- MULBERRY CREEK TRIBUTARY 8.p01 (plan) ---

Plan Title=Multiple Run
Short Identifier=Multiple
Geom File=g01
Flow File=f01
Subcritical Flow
K Sum by GR= 0
Std Step Tol= 0.01
Critical Tol= 0.01
Num of Std Step Trials= 20
Max Error Tol= 0.3
Flow Tol Ratio= 0.001
Split Flow NTrial= 30
Split Flow Tol= 0.02
Split Flow Ratio= 0.02
Log Output Level= 0
Friction Slope Method= 1
Unsteady Friction Slope Method= 2
Unsteady Bridges Friction Slope Method= 1
Parabolic Critical Depth
Global Vel Dist=  1 , 1 , 1
Global Log Level= 0
CheckData=True
Encroach Param= -1, 0, 0, 0
BEGIN DESCRIPTION:
Multiple Run
END DESCRIPTION:

--- MULBERRY CREEK TRIBUTARY 8.f01 (steady flow) ---

Flow Title=Multiple
Number of Profiles=7
Profile Names=10-year,25-year,50-year,1pct_min,100-year,1pct_plu,500-year
River Rch & RM= MULBERRY CREEK T,Reach-1,14024
     235     327     404     249     496     990     759
River Rch & RM= MULBERRY CREEK T,Reach-1,1688
     401     576     724     454     905    1806    1434
Boundary for River Rch & Prof#=MULBERRY CREEK T,Reach-1,1
Up Type=0
Dn Type=3
Dn Slope=0.005
Boundary for River Rch & Prof#=MULBERRY CREEK T,Reach-1,2
Up Type=0
Dn Type=3
Dn Slope=0.005
Boundary for River Rch & Prof#=MULBERRY CREEK T,Reach-1,3
Up Type=0
Dn Type=3
Dn Slope=0.005
Boundary for River Rch & Prof#=MULBERRY CREEK T,Reach-1,4
Up Type=0
Dn Type=3
Dn Slope=0.005
Boundary for River Rch & Prof#=MULBERRY CREEK T,Reach-1,5
Up Type=0
Dn Type=3
Dn Slope=0.005
Boundary for River Rch & Prof#=MULBERRY CREEK T,Reach-1,6
Up Type=0
Dn Type=3
Dn Slope=0.005
Boundary for River Rch & Prof#=MULBERRY CREEK T,Reach-1,7
Up Type=0
Dn Type=3
Dn Slope=0.005

--- MULBERRY CREEK TRIBUTARY 8.g01 (geometry) ---

Geom Title=Existing Conditions

River Reach=MULBERRY CREEK T,Reach-1
Reach XY= 30
      1553505.00      6872338.00      1553704.98      6872653.41
      1553512.30      6873138.08      1553797.11      6873684.78
      1553712.81      6873941.42      1554197.25      6874431.81
      1554255.36      6874767.79      1554200.01      6875290.55
      1553560.11      6875743.11      1553451.54      6876286.50
      1553312.10      6876438.00      1553358.53      6876786.54
      1553552.94      6876993.85      1553512.69      6877241.67
      1553647.59      6877334.60      1553513.01      6877591.33
      1553778.77      6877948.19      1553907.05      6878782.16
      1554054.12      6878977.41      1553318.27      6879574.32
      1553403.35      6879831.95      1553156.03      6880177.56
      1553551.33      6880589.58      1553552.07      6880886.55
      1553412.78      6880987.91      1553648.52      6881430.31
      1554365.50      6881636.81      1554949.14      6881640.07
      1555405.10      6881830.69      1555555.00      6881738.00

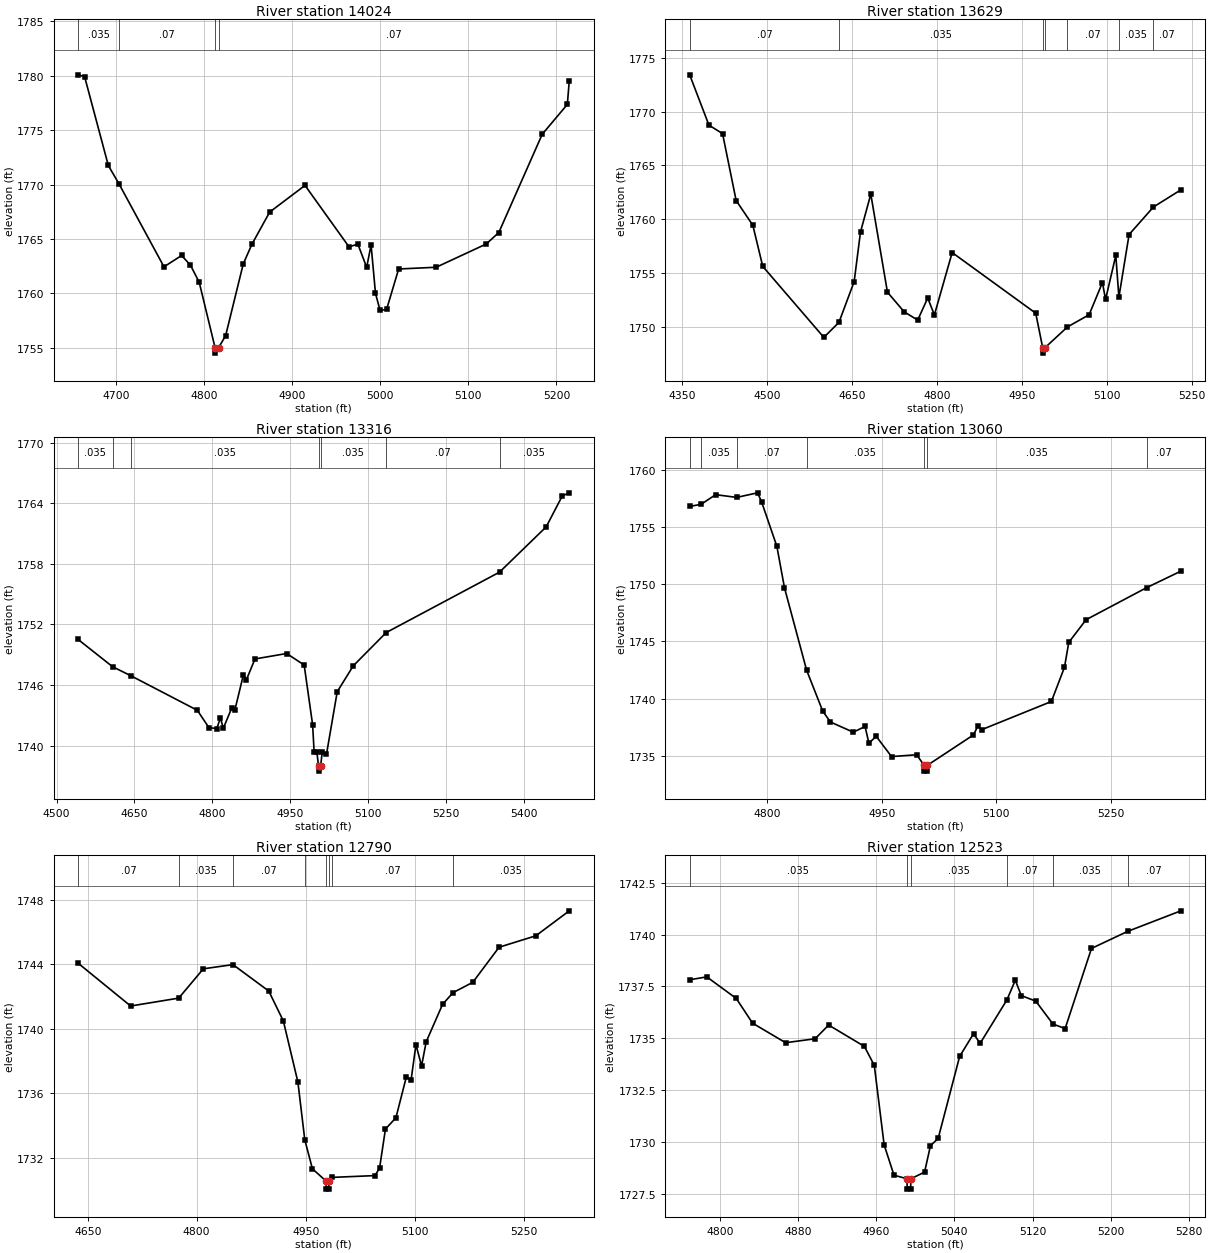
Type RM Length L Ch R = 1,14024,395,395,395
BEGIN DESCRIPTION:
MULBERRY CREEK TRIBUTARY 8 18.0
END DESCRIPTION:
XS GIS Cut Line= 3
      1553167.58      6872331.78      1553510.39      6872343.35
      1553652.90      6872182.90
#Sta/Elev= 30
  4657.0 1780.09  4664.4 1779.92  4691.3 1771.76  4703.5 1770.06  4754.5 1762.45
  4774.5 1763.49  4784.5 1762.61  4794.5 1761.03  4812.5 1755.02  4812.8 1754.52
  4816.5 1755.02  4824.5 1756.13  4844.5 1762.72  4854.5 1764.55  4874.5 1767.48
  4914.6 1769.93  4964.6 1764.28  4974.6 1764.54  4984.6 1762.40  4989.6 1764.46
  4994.6 1760.02  4999.8 1758.44  5007.2 1758.53  5020.9 1762.25  5063.5 1762.41
  5120.4 1764.55  5134.6 1765.60  5183.9 1774.63  5212.4 1777.37  5214.6 1779.54
#Mann=4,-1,0
  4657.0   0.035       0  4703.5    0.07       0  4812.5    0.07       0
  4816.5    0.07       0
Bank Sta=4812.5,4816.5
Exp/Cntr=0.3,0.1

Type RM Length L Ch R = 1,13629,313,313,313
BEGIN DESCRIPTION:
Mapping XS 386a798d
END DESCRIPTION:
XS GIS Cut Line= 3
      1553115.42      6872431.41      1553702.66      6872670.82
      1553917.55      6872578.35
#Sta/Elev= 30
  4363.0 1773.40  4397.0 1768.74  4421.1 1767.95  4445.1 1761.75  4474.6 1759.46
  4492.1 1755.65  4600.1 1749.07  4626.8 1750.46  4653.7 1754.24  4664.9 1758.84
  4683.1 1762.34  4712.5 1753.26  4742.0 1751.44  4766.0 1750.67  4783.7 1752.72
  4795.5 1751.15  4826.9 1756.93  4974.6 1751.31  4986.9 1748.11  4987.1 1747.61
  4990.9 1748.11  5030.5 1750.03  5069.0 1751.17  5092.5 1754.15  5098.0 1752.58
  5116.1 1756.66  5121.6 1752.80  5139.6 1758.60  5182.6 1761.15  5231.1 1762.74
#Mann=7,-1,0
  4363.0    0.07       0  4626.8   0.035       0  4986.9   0.035       0
  4990.9   0.035       0  5030.5    0.07       0  5121.6   0.035       0
  5182.6    0.07       0
Bank Sta=4986.9,4990.9
Exp/Cntr=0.3,0.1

Type RM Length L Ch R = 1,13316,256,256,256
BEGIN DESCRIPTION:
Mapping XS b5b974e5
END DESCRIPTION:
XS GIS Cut Line= 3
      1553197.08      6872737.65      1553604.14      6872945.56
      1554078.12      6872824.02
#Sta/Elev= 30
  4541.6 1750.51  4608.1 1747.81  4643.6 1746.91  4771.3 1743.50  4793.6 1741.79
  4808.8 1741.69  4815.8 1742.75  4821.4 1741.72  4838.0 1743.77  4843.6 1743.51
  4860.2 1747.03  4865.8 1746.51  4882.4 1748.58  4943.5 1749.12  4977.2 1747.98
  4993.5 1742.06  4996.4 1739.35  5001.7 1739.35  5004.9 1737.98  5005.1 1737.48
  5008.9 1737.98  5012.0 1739.38  5020.2 1739.14  5040.9 1745.34  5071.8 1747.90
  5135.2 1751.19  5353.6 1757.17  5443.5 1761.65  5474.5 1764.71  5488.0 1765.02
#Mann=7,-1,0
  4541.6   0.035       0  4608.1    0.07       0  4643.6   0.035       0
  5004.9   0.035       0  5008.9   0.035       0  5135.2    0.07       0
  5353.6   0.035       0
Bank Sta=5004.9,5008.9
Exp/Cntr=0.3,0.1

Type RM Length L Ch R = 1,13060,270,270,270
BEGIN DESCRIPTION:
Mapping XS 997a72b8
END DESCRIPTION:
XS GIS Cut Line= 3
      1553231.01      6873189.27      1553525.32      6873168.43
      1553840.82      6873019.12
#Sta/Elev= 30
  4698.0 1756.79  4713.0 1756.98  4732.1 1757.82  4759.6 1757.58  4787.0 1757.98
  4792.2 1757.21  4812.3 1753.31  4822.3 1749.69  4851.3 1742.50  4872.4 1738.93
  4882.5 1737.97  4912.5 1737.08  4928.0 1737.58  4933.0 1736.12  4942.6 1736.72
  4962.7 1734.95  4995.6 1735.11  5005.5 1734.18  5005.8 1733.68  5009.3 1733.68
  5009.5 1734.18  5070.1 1736.84  5075.8 1737.60  5081.3 1737.31  5172.3 1739.76
  5189.5 1742.75  5195.1 1744.92  5217.8 1746.90  5297.5 1749.71  5342.1 1751.14
#Mann=7,-1,0
  4698.0    0.07       0  4713.0   0.035       0  4759.6    0.07       0
  4851.3   0.035       0  5005.5   0.035       0  5009.5   0.035       0
  5297.5    0.07       0
Bank Sta=5005.5,5009.5
Exp/Cntr=0.3,0.1

Type RM Length L Ch R = 1,12790,267,267,267
BEGIN DESCRIPTION:
Mapping XS 80c5ff62
END DESCRIPTION:
XS GIS Cut Line= 3
      1553292.71      6873381.54      1553652.05      6873393.69
      1553901.01      6873198.33
#Sta/Elev= 30
  4636.8 1744.07  4709.1 1741.41  4775.3 1741.90  4809.2 1743.72  4849.9 1743.98
  4899.2 1742.34  4919.3 1740.48  4939.3 1736.69  4948.8 1733.10  4959.3 1731.30
  4978.1 1730.54  4978.3 1730.04  4981.8 1730.04  4982.1 1730.54  4986.9 1730.77
  5045.3 1730.88  5051.7 1731.34  5059.8 1733.77  5074.2 1734.47  5088.7 1737.03
  5095.0 1736.79  5101.8 1739.01  5109.5 1737.69  5115.9 1739.19  5138.4 1741.51
  5152.8 1742.24  5180.0 1742.88  5216.2 1745.06  5266.8 1745.77  5312.8 1747.32
#Mann=8,-1,0
  4636.8    0.07       0  4775.3   0.035       0  4849.9    0.07       0
  4948.8   0.035       0  4978.1    0.07       0  4982.1   0.035       0
  4986.9    0.07       0  5152.8   0.035       0
Bank Sta=4978.1,4982.1
Exp/Cntr=0.3,0.1

Type RM Length L Ch R = 1,12523,641,641,641
BEGIN DESCRIPTION:
Mapping XS 3a500028
END DESCRIPTION:
XS GIS Cut Line= 3
      1553527.70      6873594.21      1553750.36      6873624.16
      1553981.06      6873468.63
#Sta/Elev= 30
  4769.0 1737.82  4786.5 1737.96  4816.7 1736.92  4833.4 1735.73  4867.2 1734.79
  4897.4 1734.98  4911.3 1735.64  4947.9 1734.61  4958.0 1733.70  4968.1 1729.87
  4978.2 1728.41  4991.5 1728.24  4991.7 1727.74  4995.2 1727.74  4995.5 1728.24
  5009.5 1728.56  5015.5 1729.83  5023.4 1730.18  5045.4 1734.13  5059.6 1735.22
  5066.4 1734.76  5093.8 1736.85  5102.4 1737.80  5108.5 1737.06  5123.4 1736.79
  5140.9 1735.69  5153.4 1735.47  5180.4 1739.33  5217.4 1740.15  5271.9 1741.14
#Mann=6,-1,0
  4769.0   0.035       0  4991.5   0.035       0  4995.5   0.035       0
  5093.8    0.07       0  5140.9   0.035       0  5217.4    0.07       0
Bank Sta=4991.5,4995.5
Exp/Cntr=0.3,0.1

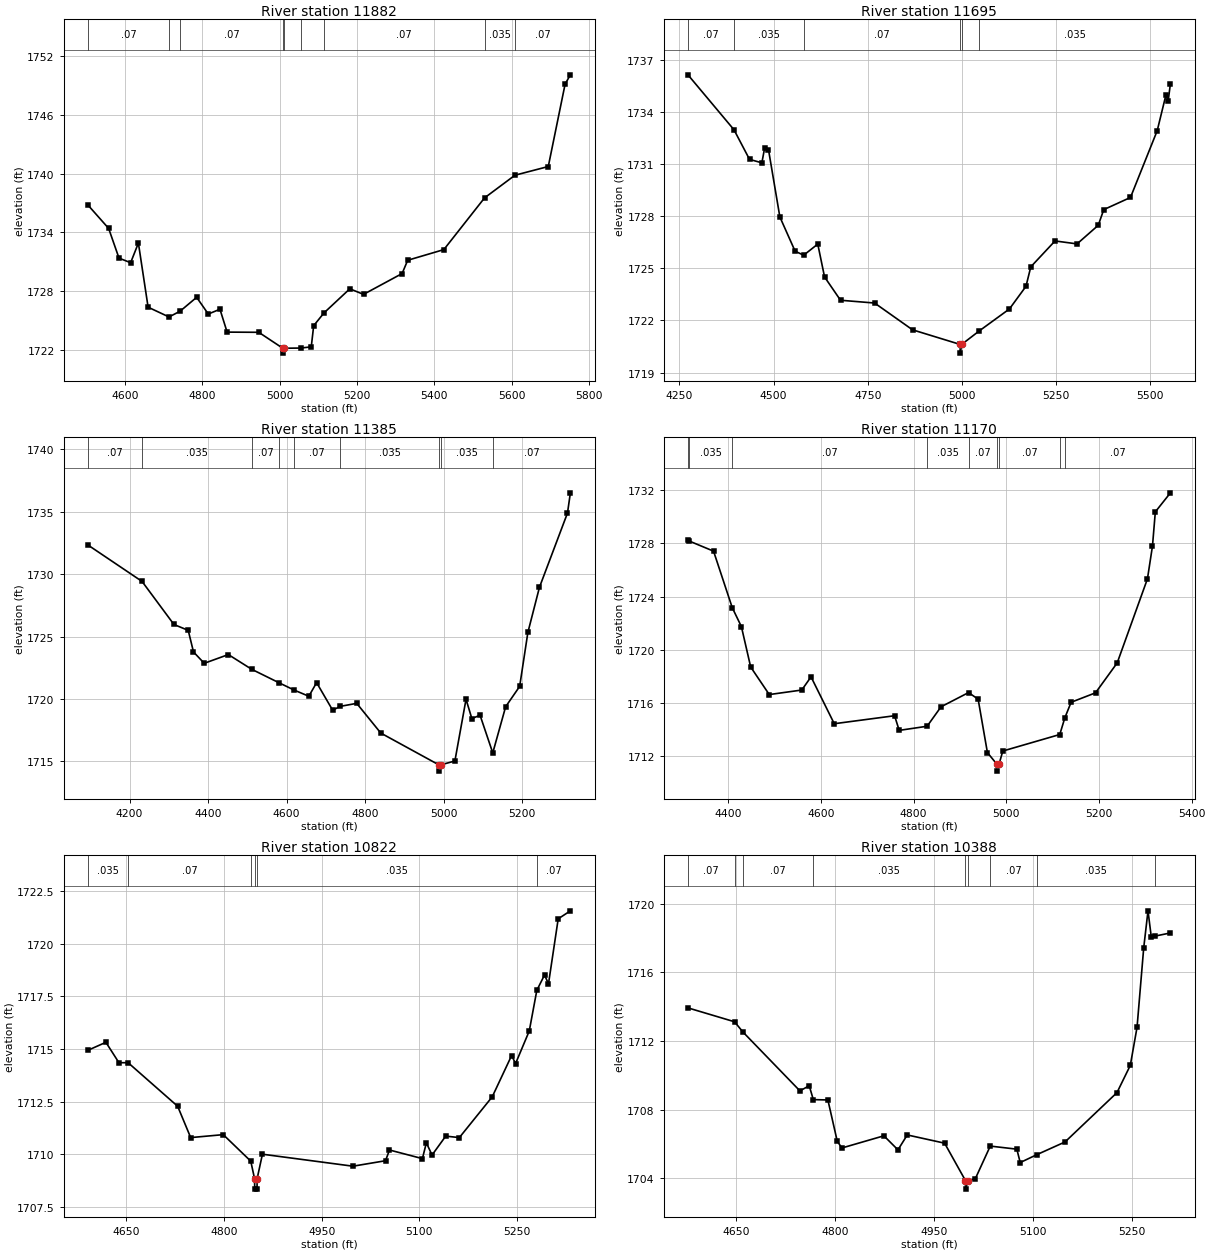
Type RM Length L Ch R = 1,11882,187,187,187
BEGIN DESCRIPTION:
MULBERRY CREEK TRIBUTARY 8 14.0
END DESCRIPTION:
XS GIS Cut Line= 3
      1553405.02      6874038.00      1553899.11      6874085.79
      1554355.00      6873487.99
#Sta/Elev= 30
  4503.6 1736.78  4557.2 1734.39  4584.0 1731.35  4614.1 1730.88  4634.2 1732.89
  4659.3 1726.33  4713.4 1725.33  4742.1 1725.92  4784.9 1727.34  4815.0 1725.63
  4845.2 1726.12  4863.7 1723.78  4945.6 1723.76  5007.8 1722.13  5008.1 1721.63
  5011.8 1722.13  5054.1 1722.15  5081.4 1722.27  5087.7 1724.44  5114.5 1725.75
  5181.2 1728.21  5216.6 1727.64  5316.4 1729.77  5330.9 1731.13  5424.4 1732.22
  5529.7 1737.51  5608.4 1739.83  5694.6 1740.72  5738.2 1749.16  5751.8 1750.10
#Mann=9,-1,0
  4503.6    0.07       0  4713.4   0.035       0  4742.1    0.07       0
  5007.8    0.07       0  5011.8    0.07       0  5054.1   0.035       0
  5114.5    0.07       0  5529.7   0.035       0  5608.4    0.07       0
Bank Sta=5007.8,5011.8
Exp/Cntr=0.3,0.1

Type RM Length L Ch R = 1,11695,310,310,310
BEGIN DESCRIPTION:
Mapping XS c6febcd8
END DESCRIPTION:
XS GIS Cut Line= 3
      1553282.59      6874130.45      1554005.24      6874215.09
      1554334.66      6873769.79
#Sta/Elev= 30
  4272.5 1736.12  4394.8 1732.96  4436.0 1731.26  4468.8 1731.06  4476.3 1731.93
  4486.4 1731.82  4516.6 1727.95  4557.1 1725.98  4579.9 1725.75  4617.3 1726.39
  4635.3 1724.50  4677.7 1723.16  4768.3 1723.00  4869.0 1721.46  4995.5 1720.62
  4995.7 1720.12  4999.5 1720.62  5046.4 1721.40  5126.4 1722.66  5170.3 1723.96
  5183.1 1725.08  5247.5 1726.57  5306.0 1726.40  5362.3 1727.47  5376.9 1728.37
  5447.9 1729.07  5518.9 1732.91  5541.9 1734.95  5548.1 1734.63  5554.0 1735.62
#Mann=6,-1,0
  4272.5    0.07       0  4394.8   0.035       0  4579.9    0.07       0
  4995.5    0.07       0  4999.5    0.07       0  5046.4   0.035       0
Bank Sta=4995.5,4999.5
Exp/Cntr=0.3,0.1

Type RM Length L Ch R = 1,11385,215,215,215
BEGIN DESCRIPTION:
MULBERRY CREEK TRIBUTARY 8 13.0
END DESCRIPTION:
XS GIS Cut Line= 3
      1553305.01      6874238.00      1554191.67      6874424.67
      1554455.02      6874237.99
#Sta/Elev= 30
  4093.9 1732.34  4231.8 1729.42  4313.0 1725.97  4349.4 1725.50  4362.8 1723.77
  4390.2 1722.86  4451.6 1723.56  4511.1 1722.38  4580.7 1721.30  4619.5 1720.71
  4656.6 1720.22  4676.4 1721.31  4717.3 1719.10  4736.5 1719.41  4778.6 1719.65
  4839.9 1717.27  4988.0 1714.72  4988.2 1714.22  4992.0 1714.72  5028.6 1715.03
  5057.0 1719.98  5071.8 1718.43  5092.7 1718.70  5125.1 1715.68  5157.9 1719.38
  5193.6 1721.01  5214.5 1725.33  5244.0 1728.95  5315.4 1734.90  5322.8 1736.52
#Mann=9,-1,0
  4093.9    0.07       0  4231.8   0.035       0  4511.1    0.07       0
  4580.7   0.035       0  4619.5    0.07       0  4736.5   0.035       0
  4988.0   0.035       0  4992.0   0.035       0  5125.1    0.07       0
Bank Sta=4988,4992
Exp/Cntr=0.3,0.1

Type RM Length L Ch R = 1,11170,348,348,348
BEGIN DESCRIPTION:
Mapping XS 91b05d9a
END DESCRIPTION:
XS GIS Cut Line= 3
      1553469.86      6874588.74      1554144.76      6874623.47
      1554480.59      6874480.47
#Sta/Elev= 30
  4313.4 1728.26  4315.4 1728.18  4368.6 1727.41  4408.9 1723.17  4428.7 1721.74
  4448.7 1718.71  4488.8 1716.64  4558.9 1716.98  4578.9 1717.97  4629.0 1714.45
  4759.1 1715.05  4769.1 1713.95  4829.3 1714.26  4859.3 1715.72  4918.8 1716.79
  4939.4 1716.29  4959.4 1712.28  4980.3 1711.39  4980.5 1710.89  4984.3 1711.39
  4992.6 1712.40  5115.5 1713.64  5126.3 1714.88  5139.9 1716.06  5192.6 1716.77
  5239.4 1719.02  5304.6 1725.33  5315.5 1727.80  5321.6 1730.36  5354.2 1731.79
#Mann=9,-1,0
  4313.4    0.07       0  4315.4   0.035       0  4408.9    0.07       0
  4829.3   0.035       0  4918.8    0.07       0  4980.3    0.07       0
  4984.3    0.07       0  5115.5   0.035       0  5126.3    0.07       0
Bank Sta=4980.3,4984.3
Exp/Cntr=0.3,0.1

Type RM Length L Ch R = 1,10822,434,434,434
BEGIN DESCRIPTION:
Mapping XS 0e7c5dcb
END DESCRIPTION:
XS GIS Cut Line= 3
      1553797.39      6874903.27      1554201.04      6874916.29
      1554476.64      6874723.15
#Sta/Elev= 30
  4591.3 1714.94  4618.9 1715.32  4638.9 1714.35  4653.0 1714.35  4729.0 1712.28
  4749.0 1710.79  4799.0 1710.93  4841.2 1709.67  4847.0 1708.84  4847.3 1708.34
  4850.8 1708.34  4851.0 1708.84  4859.1 1710.00  4998.0 1709.43  5048.0 1709.69
  5054.1 1710.20  5104.6 1709.79  5110.7 1710.54  5119.4 1709.96  5140.4 1710.86
  5161.3 1710.79  5211.8 1712.73  5241.5 1714.69  5247.6 1714.31  5268.6 1715.86
  5280.2 1717.79  5292.0 1718.52  5298.1 1718.10  5313.0 1721.19  5331.7 1721.57
#Mann=6,-1,0
  4591.3   0.035       0  4653.0    0.07       0  4841.2   0.035       0
  4847.0   0.035       0  4851.0   0.035       0  5280.2    0.07       0
Bank Sta=4847,4851
Exp/Cntr=0.3,0.1

Type RM Length L Ch R = 1,10388,498,498,498
BEGIN DESCRIPTION:
MULBERRY CREEK TRIBUTARY 8 11.0
END DESCRIPTION:
XS GIS Cut Line= 3
      1553904.98      6874987.98      1554200.01      6875290.55
      1554505.04      6875338.01
#Sta/Elev= 30
  4577.4 1713.93  4648.0 1713.12  4660.8 1712.52  4747.1 1709.09  4761.2 1709.39
  4767.4 1708.58  4789.5 1708.56  4803.7 1706.15  4810.8 1705.76  4874.4 1706.47
  4895.7 1705.65  4909.8 1706.52  4966.4 1706.04  4998.0 1703.86  4998.2 1703.36
  5002.0 1703.86  5013.0 1703.97  5035.6 1705.87  5075.9 1705.69  5081.0 1704.91
  5106.2 1705.37  5148.9 1706.11  5227.7 1708.99  5247.9 1710.58  5258.1 1712.80
  5268.2 1717.43  5274.7 1719.59  5279.7 1718.06  5285.8 1718.12  5308.7 1718.30
#Mann=9,-1,0
  4577.4    0.07       0  4648.0   0.035       0  4660.8    0.07       0
  4767.4   0.035       0  4998.0   0.035       0  5002.0   0.035       0
  5035.6    0.07       0  5106.2   0.035       0  5285.8    0.07       0
Bank Sta=4998,5002
Exp/Cntr=0.3,0.1

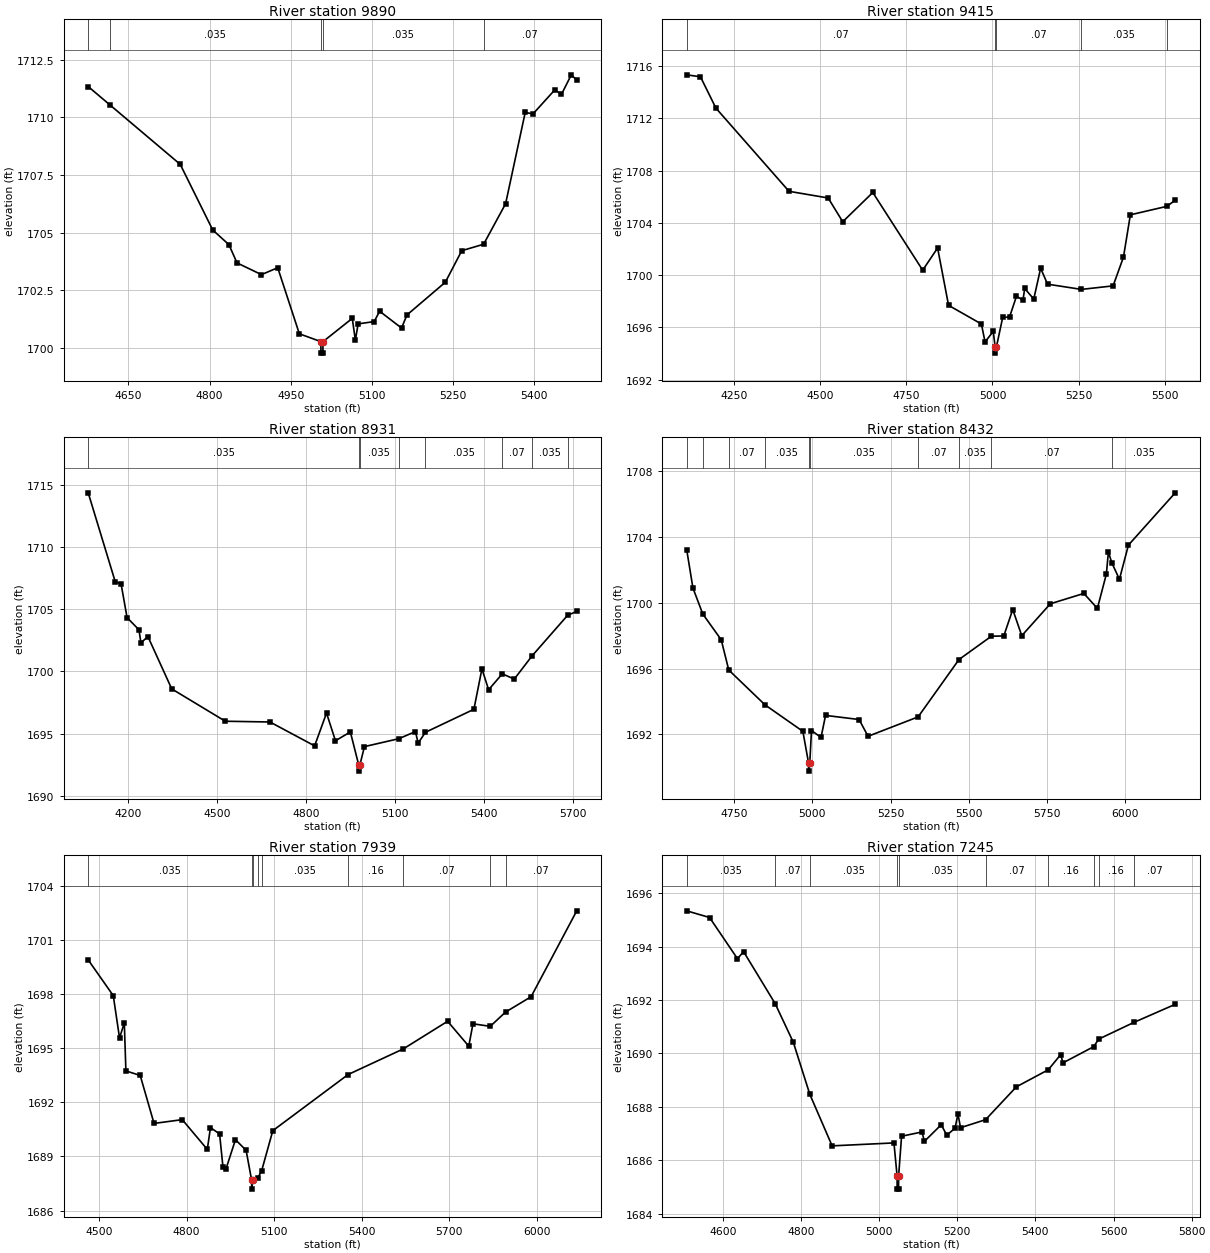
Type RM Length L Ch R = 1,9890,475,475,475
BEGIN DESCRIPTION:
MULBERRY CREEK TRIBUTARY 8 10.0
END DESCRIPTION:
XS GIS Cut Line= 3
      1553855.00      6875188.05      1553831.85      6875611.81
      1554304.96      6875687.99
#Sta/Elev= 30
  4575.6 1711.34  4615.9 1710.54  4745.8 1707.96  4805.9 1705.11  4835.9 1704.47
  4850.8 1703.68  4896.0 1703.17  4926.1 1703.47  4966.1 1700.60  5005.9 1700.26
  5006.1 1699.76  5009.6 1699.76  5009.9 1700.26  5064.0 1701.27  5069.7 1700.32
  5074.8 1701.03  5104.5 1701.13  5114.6 1701.58  5155.1 1700.85  5165.2 1701.42
  5236.1 1702.84  5266.5 1704.21  5306.9 1704.49  5347.6 1706.25  5383.9 1710.22
  5398.2 1710.15  5438.7 1711.20  5450.9 1711.00  5469.1 1711.85  5479.2 1711.62
#Mann=5,-1,0
  4575.6    0.07       0  4615.9   0.035       0  5005.9   0.035       0
  5009.9   0.035       0  5306.9    0.07       0
Bank Sta=5005.9,5009.9
Exp/Cntr=0.3,0.1

Type RM Length L Ch R = 1,9415,484,484,484
BEGIN DESCRIPTION:
MULBERRY CREEK TRIBUTARY 8 9.0
END DESCRIPTION:
XS GIS Cut Line= 3
      1552687.25      6875575.97      1553525.34      6875868.27
      1554054.97      6875838.00
#Sta/Elev= 30
  4112.4 1715.33  4152.4 1715.18  4197.3 1712.78  4409.5 1706.41  4523.1 1705.90
  4565.4 1704.08  4652.7 1706.32  4797.5 1700.37  4840.8 1702.07  4872.6 1697.68
  4967.9 1696.25  4978.5 1694.88  5002.3 1695.68  5007.7 1694.52  5007.9 1694.02
  5011.7 1694.52  5029.7 1696.75  5049.7 1696.79  5069.8 1698.38  5088.6 1698.07
  5093.6 1698.97  5119.9 1698.16  5139.9 1700.52  5159.9 1699.30  5258.3 1698.90
  5350.2 1699.17  5380.3 1701.37  5400.3 1704.61  5506.3 1705.26  5530.5 1705.73
#Mann=5,-1,0
  4112.4    0.07       0  5007.7    0.07       0  5011.7    0.07       0
  5258.3   0.035       0  5506.3    0.07       0
Bank Sta=5007.7,5011.7
Exp/Cntr=0.3,0.1

Type RM Length L Ch R = 1,8931,499,499,499
BEGIN DESCRIPTION:
MULBERRY CREEK TRIBUTARY 8 8.0
END DESCRIPTION:
XS GIS Cut Line= 3
      1552524.49      6876198.80      1553454.76      6876272.78
      1554055.01      6875887.99
#Sta/Elev= 30
  4066.8 1714.35  4157.6 1707.22  4177.7 1707.01  4197.7 1704.32  4237.8 1703.34
  4244.4 1702.29  4267.9 1702.80  4348.2 1698.59  4528.8 1695.99  4679.2 1695.93
  4829.7 1694.01  4869.8 1696.65  4899.9 1694.42  4950.1 1695.13  4978.2 1692.48
  4978.4 1691.98  4982.2 1692.48  4997.6 1693.95  5113.9 1694.59  5169.4 1695.16
  5178.5 1694.23  5203.0 1695.10  5366.4 1696.95  5393.5 1700.20  5416.0 1698.52
  5462.0 1699.80  5502.5 1699.38  5562.3 1701.24  5682.0 1704.50  5713.0 1704.82
#Mann=8,-1,0
  4066.8   0.035       0  4978.2   0.035       0  4982.2   0.035       0
  5113.9    0.07       0  5203.0   0.035       0  5462.0    0.07       0
  5562.3   0.035       0  5682.0    0.07       0
Bank Sta=4978.2,4982.2
Exp/Cntr=0.3,0.1

Type RM Length L Ch R = 1,8432,493,493,493
BEGIN DESCRIPTION:
MULBERRY CREEK TRIBUTARY 8 7.0
END DESCRIPTION:
XS GIS Cut Line= 3
      1552955.03      6876638.00      1553354.81      6876667.94
      1554254.96      6875938.03
#Sta/Elev= 30
  4599.1 1703.24  4619.1 1700.90  4650.5 1699.32  4709.4 1697.75  4733.5 1695.91
  4849.3 1693.79  4970.1 1692.18  4988.2 1690.26  4988.4 1689.76  4992.2 1690.26
  4997.6 1692.23  5028.1 1691.81  5042.5 1693.15  5149.5 1692.90  5178.3 1691.88
  5338.1 1693.06  5468.6 1696.55  5572.2 1697.97  5611.5 1697.98  5640.2 1699.59
  5669.0 1698.00  5760.2 1699.94  5867.2 1700.57  5910.4 1699.66  5939.1 1701.75
  5945.6 1703.10  5956.1 1702.45  5980.8 1701.43  6009.5 1703.51  6158.9 1706.69
#Mann=10,-1,0
  4599.1    0.07       0  4650.5   0.035       0  4733.5    0.07       0
  4849.3   0.035       0  4988.2   0.035       0  4992.2   0.035       0
  5338.1    0.07       0  5468.6   0.035       0  5572.2    0.07       0
  5956.1   0.035       0
Bank Sta=4988.2,4992.2
Exp/Cntr=0.3,0.1

Type RM Length L Ch R = 1,7939,694,694,694
BEGIN DESCRIPTION:
MULBERRY CREEK TRIBUTARY 8 6.0
END DESCRIPTION:
XS GIS Cut Line= 3
      1553055.02      6876888.01      1553555.16      6877082.99
      1554254.98      6876188.02
#Sta/Elev= 30
  4463.2 1699.89  4549.0 1697.91  4570.5 1695.56  4586.8 1696.41  4592.2 1693.74
  4641.2 1693.49  4688.6 1690.83  4785.2 1691.04  4871.0 1689.39  4881.8 1690.60
  4913.0 1690.25  4924.7 1688.40  4935.4 1688.33  4967.4 1689.93  5003.9 1689.34
  5022.7 1687.69  5023.0 1687.19  5026.7 1687.69  5044.4 1687.82  5057.1 1688.21
  5095.3 1690.43  5353.2 1693.54  5542.2 1694.96  5693.9 1696.49  5766.3 1695.11
  5780.7 1696.35  5839.9 1696.21  5892.3 1697.00  5979.7 1697.85  6136.1 1702.61
#Mann=9,-1,0
  4463.2   0.035       0  5022.7   0.035       0  5026.7   0.035       0
  5044.4    0.07       0  5057.1   0.035       0  5353.2    0.16       0
  5542.2    0.07       0  5839.9   0.035       0  5892.3    0.07       0
Bank Sta=5022.7,5026.7
Exp/Cntr=0.3,0.1

Type RM Length L Ch R = 1,7245,400,400,400
BEGIN DESCRIPTION:
Mapping XS d60c7ffb
END DESCRIPTION:
XS GIS Cut Line= 4
      1553045.26      6877435.83      1553524.83      6877579.05
      1553579.08      6877579.05      1554028.30      6877047.36
#Sta/Elev= 30
  4507.1 1695.34  4565.7 1695.09  4637.1 1693.55  4652.9 1693.81  4733.5 1691.87
  4780.1 1690.42  4822.4 1688.47  4879.5 1686.54  5037.8 1686.65  5045.8 1685.42
  5046.0 1684.92  5049.5 1684.92  5049.8 1685.42  5057.3 1686.90  5109.4 1687.06
  5115.9 1686.71  5158.8 1687.33  5173.1 1686.94  5194.1 1687.20  5201.7 1687.73
  5208.3 1687.22  5272.4 1687.52  5351.2 1688.75  5433.0 1689.39  5464.3 1689.95
  5470.9 1689.65  5548.7 1690.25  5562.5 1690.54  5651.8 1691.16  5757.9 1691.84
#Mann=10,-1,0
  4507.1   0.035       0  4733.5    0.07       0  4822.4   0.035       0
  5045.8   0.035       0  5049.8   0.035       0  5272.4    0.07       0
  5433.0    0.16       0  5548.7    0.07       0  5562.5    0.16       0
  5651.8    0.07       0
Bank Sta=5045.8,5049.8
Exp/Cntr=0.3,0.1

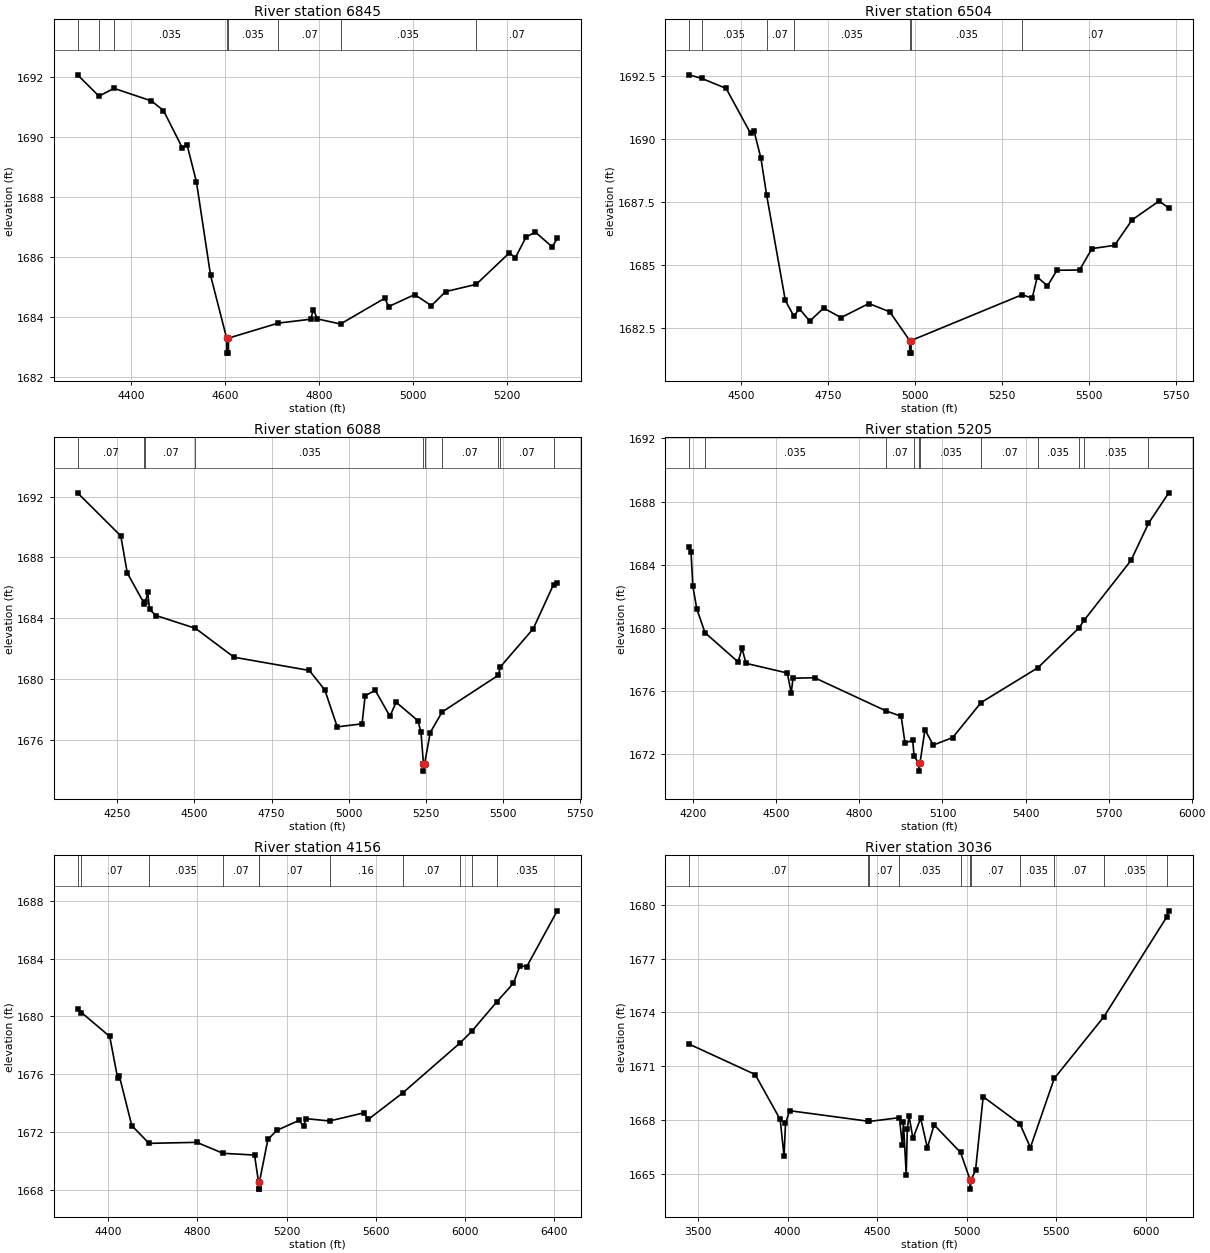
Type RM Length L Ch R = 1,6845,341,341,341
BEGIN DESCRIPTION:
Mapping XS b898c834
END DESCRIPTION:
XS GIS Cut Line= 4
      1553102.68      6878073.41      1553456.39      6878095.11
      1553653.88      6878034.35      1553814.46      6877604.67
#Sta/Elev= 30
  4286.7 1692.08  4332.2 1691.37  4364.3 1691.63  4443.8 1691.21  4469.4 1690.89
  4509.4 1689.65  4519.5 1689.75  4539.5 1688.51  4569.5 1685.40  4603.6 1683.31
  4603.9 1682.81  4607.4 1682.81  4607.6 1683.31  4713.4 1683.81  4782.6 1683.94
  4787.8 1684.26  4796.6 1683.95  4845.7 1683.78  4939.9 1684.64  4948.0 1684.36
  5003.3 1684.76  5038.9 1684.39  5069.2 1684.86  5134.1 1685.10  5204.7 1686.15
  5217.4 1685.99  5240.3 1686.68  5259.9 1686.84  5295.6 1686.35  5306.4 1686.63
#Mann=8,-1,0
  4286.7   0.035       0  4332.2    0.07       0  4364.3   0.035       0
  4603.6   0.035       0  4607.6   0.035       0  4713.4    0.07       0
  4845.7   0.035       0  5134.1    0.07       0
Bank Sta=4603.6,4607.6
Exp/Cntr=0.3,0.1

Type RM Length L Ch R = 1,6504,416,416,416
BEGIN DESCRIPTION:
Mapping XS b22099be
END DESCRIPTION:
XS GIS Cut Line= 3
      1553168.42      6878184.19      1553808.65      6878184.19
      1554240.25      6877585.59
#Sta/Elev= 30
  4351.2 1692.56  4387.3 1692.42  4457.8 1692.02  4527.8 1690.24  4537.8 1690.34
  4557.8 1689.24  4573.9 1687.80  4627.8 1683.60  4652.6 1682.97  4667.8 1683.28
  4697.8 1682.78  4737.8 1683.30  4787.8 1682.92  4867.8 1683.48  4927.8 1683.15
  4985.1 1682.01  4985.4 1681.51  4988.9 1681.51  4989.1 1682.01  5308.2 1683.83
  5336.9 1683.69  5351.6 1684.53  5381.0 1684.18  5408.1 1684.80  5473.1 1684.81
  5508.7 1685.66  5573.7 1685.79  5624.0 1686.80  5701.8 1687.55  5729.4 1687.27
#Mann=7,-1,0
  4351.2    0.07       0  4387.3   0.035       0  4573.9    0.07       0
  4652.6   0.035       0  4985.1   0.035       0  4989.1   0.035       0
  5308.2    0.07       0
Bank Sta=4985.1,4989.1
Exp/Cntr=0.3,0.1

Type RM Length L Ch R = 1,6088,883,883,883
BEGIN DESCRIPTION:
Mapping XS 6327dd2a
END DESCRIPTION:
XS GIS Cut Line= 3
      1553143.87      6878215.18      1553699.45      6878581.94
      1554584.89      6878495.14
#Sta/Elev= 30
  4120.8 1692.25  4261.0 1689.42  4282.1 1686.98  4336.9 1684.97  4340.9 1685.04
  4348.3 1685.71  4354.3 1684.58  4375.4 1684.18  4503.2 1683.34  4628.2 1681.44
  4872.5 1680.57  4922.7 1679.28  4962.9 1676.86  5043.3 1677.06  5053.3 1678.90
  5085.8 1679.27  5133.7 1677.56  5153.8 1678.48  5224.2 1677.27  5234.2 1676.54
  5242.3 1674.45  5242.5 1673.95  5246.3 1674.45  5264.3 1676.48  5302.9 1677.84
  5485.6 1680.26  5491.5 1680.80  5598.3 1683.31  5664.2 1686.22  5676.2 1686.30
#Mann=10,-1,0
  4120.8    0.07       0  4336.9   0.035       0  4340.9    0.07       0
  4503.2   0.035       0  5242.3   0.035       0  5246.3   0.035       0
  5302.9    0.07       0  5485.6   0.035       0  5491.5    0.07       0
  5664.2   0.035       0
Bank Sta=5242.3,5246.3
Exp/Cntr=0.3,0.1

Type RM Length L Ch R = 1,5205,1049,1049,1049
BEGIN DESCRIPTION:
MULBERRY CREEK TRIBUTARY 8 2.0
END DESCRIPTION:
XS GIS Cut Line= 3
      1553255.03      6878638.03      1553788.35      6879254.70
      1554705.04      6879288.00
#Sta/Elev= 30
  4184.7 1685.15  4191.8 1684.81  4198.4 1682.64  4212.6 1681.21  4242.3 1679.70
  4361.8 1677.85  4376.1 1678.71  4390.3 1677.76  4539.5 1677.15  4553.7 1675.89
  4560.3 1676.82  4638.2 1676.85  4894.9 1674.76  4950.8 1674.41  4964.7 1672.72
  4992.5 1672.89  4997.4 1671.89  5014.7 1671.44  5014.9 1670.94  5018.7 1671.44
  5036.7 1673.56  5066.7 1672.59  5136.7 1673.06  5239.4 1675.28  5444.5 1677.48
  5593.0 1680.00  5611.3 1680.48  5780.8 1684.27  5843.8 1686.61  5917.3 1688.55
#Mann=11,-1,0
  4184.7    0.07       0  4242.3   0.035       0  4894.9    0.07       0
  4997.4   0.035       0  5014.7   0.035       0  5018.7   0.035       0
  5239.4    0.07       0  5444.5   0.035       0  5593.0    0.07       0
  5611.3   0.035       0  5843.8    0.07       0
Bank Sta=5014.7,5018.7
Exp/Cntr=0.3,0.1

Type RM Length L Ch R = 1,4156,1120,1120,1120
BEGIN DESCRIPTION:
Mapping XS 052f6499
END DESCRIPTION:
XS GIS Cut Line= 3
      1552800.10      6879409.75      1553355.64      6879874.15
      1554781.84      6879908.83
#Sta/Elev= 30
  4262.4 1680.54  4279.9 1680.27  4406.7 1678.61  4441.9 1675.75  4449.7 1675.88
  4505.6 1672.44  4583.0 1671.21  4797.1 1671.28  4914.6 1670.52  5055.9 1670.40
  5073.9 1668.54  5074.1 1668.04  5077.6 1668.04  5077.9 1668.54  5115.9 1671.48
  5155.9 1672.11  5255.9 1672.80  5275.9 1672.38  5285.9 1672.92  5392.4 1672.76
  5546.0 1673.32  5566.0 1672.87  5721.0 1674.71  5976.5 1678.15  6029.4 1678.96
  6141.7 1681.00  6216.2 1682.29  6246.2 1683.51  6276.2 1683.44  6413.1 1687.31
#Mann=11,-1,0
  4262.4   0.035       0  4279.9    0.07       0  4583.0   0.035       0
  4914.6    0.07       0  5073.9    0.07       0  5077.9    0.07       0
  5392.4    0.16       0  5721.0    0.07       0  5976.5    0.16       0
  6029.4    0.07       0  6141.7   0.035       0
Bank Sta=5073.9,5077.9
Exp/Cntr=0.3,0.1

Type RM Length L Ch R = 1,3036,1348,1348,1348
BEGIN DESCRIPTION:
Mapping XS 9ff05f7b
END DESCRIPTION:
XS GIS Cut Line= 4
      1552197.73      6879930.71      1553538.04      6880698.08
      1553659.57      6880708.50      1554656.05      6880534.90
#Sta/Elev= 30
  3450.2 1672.23  3819.3 1670.53  3958.9 1668.02  3980.5 1665.96  3988.6 1667.80
  4011.7 1668.51  4451.3 1667.92  4456.2 1667.91  4624.3 1668.12  4641.0 1666.58
  4646.7 1667.86  4662.6 1664.94  4668.5 1667.50  4678.4 1668.21  4700.0 1666.96
  4743.1 1668.09  4780.6 1666.43  4818.0 1667.72  4965.8 1666.18  5019.7 1664.63
  5019.9 1664.13  5023.7 1664.63  5049.5 1665.18  5092.0 1669.29  5297.5 1667.77
  5355.6 1666.45  5488.8 1670.31  5766.2 1673.76  6117.0 1679.33  6128.1 1679.67
#Mann=11,-1,0
  3450.2    0.07       0  4451.3   0.035       0  4456.2    0.07       0
  4624.3   0.035       0  4965.8    0.07       0  5019.7    0.07       0
  5023.7    0.07       0  5297.5   0.035       0  5488.8    0.07       0
  5766.2   0.035       0  6117.0    0.07       0
Bank Sta=5019.7,5023.7
Exp/Cntr=0.3,0.1

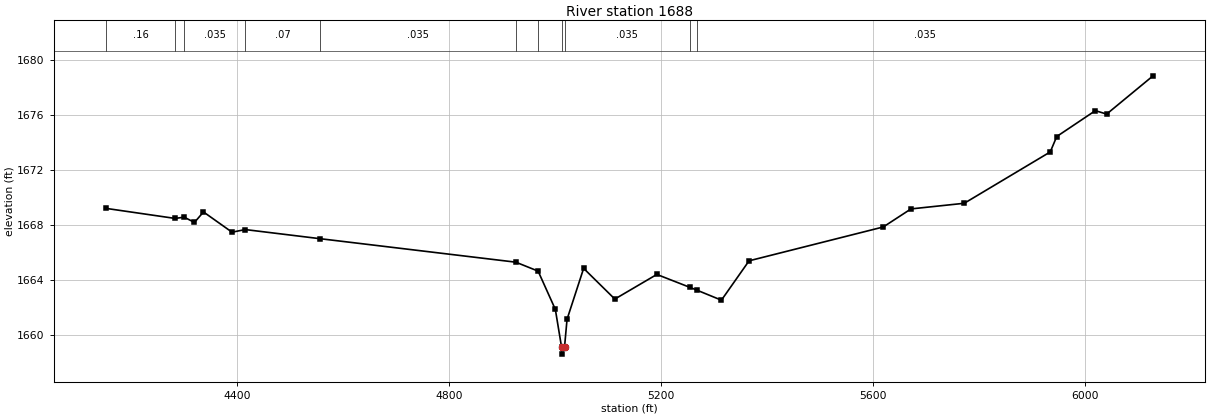
Type RM Length L Ch R = 1,1688,0,0,0
BEGIN DESCRIPTION:
MULBERRY CREEK TRIBUTARY 8 1.0
END DESCRIPTION:
XS GIS Cut Line= 4
      1553230.03      6881463.00      1554010.26      6881590.44
      1554058.87      6881486.28      1554618.63      6880572.99
#Sta/Elev= 30
  4151.9 1669.19  4282.5 1668.46  4299.6 1668.55  4319.1 1668.17  4336.1 1668.93
  4390.0 1667.46  4415.0 1667.65  4555.5 1666.99  4925.8 1665.28  4967.8 1664.63
  5000.3 1661.85  5012.1 1659.10  5012.5 1658.60  5017.6 1659.10  5022.4 1661.13
  5053.7 1664.83  5112.6 1662.60  5191.9 1664.39  5253.7 1663.46  5266.8 1663.26
  5313.8 1662.52  5366.0 1665.38  5619.4 1667.84  5671.6 1669.15  5772.2 1669.56
  5934.5 1673.29  5946.8 1674.41  6019.7 1676.29  6041.0 1676.04  6128.6 1678.82
#Mann=11,-1,0
  4151.9    0.16       0  4282.5    0.07       0  4299.6   0.035       0
  4415.0    0.07       0  4555.5   0.035       0  4925.8    0.07       0
  4967.8   0.035       0  5012.1   0.035       0  5017.6   0.035       0
  5253.7    0.07       0  5266.8   0.035       0
Bank Sta=5012.1,5017.6
Exp/Cntr=0.3,0.1

Chan Stop Cuts=-1