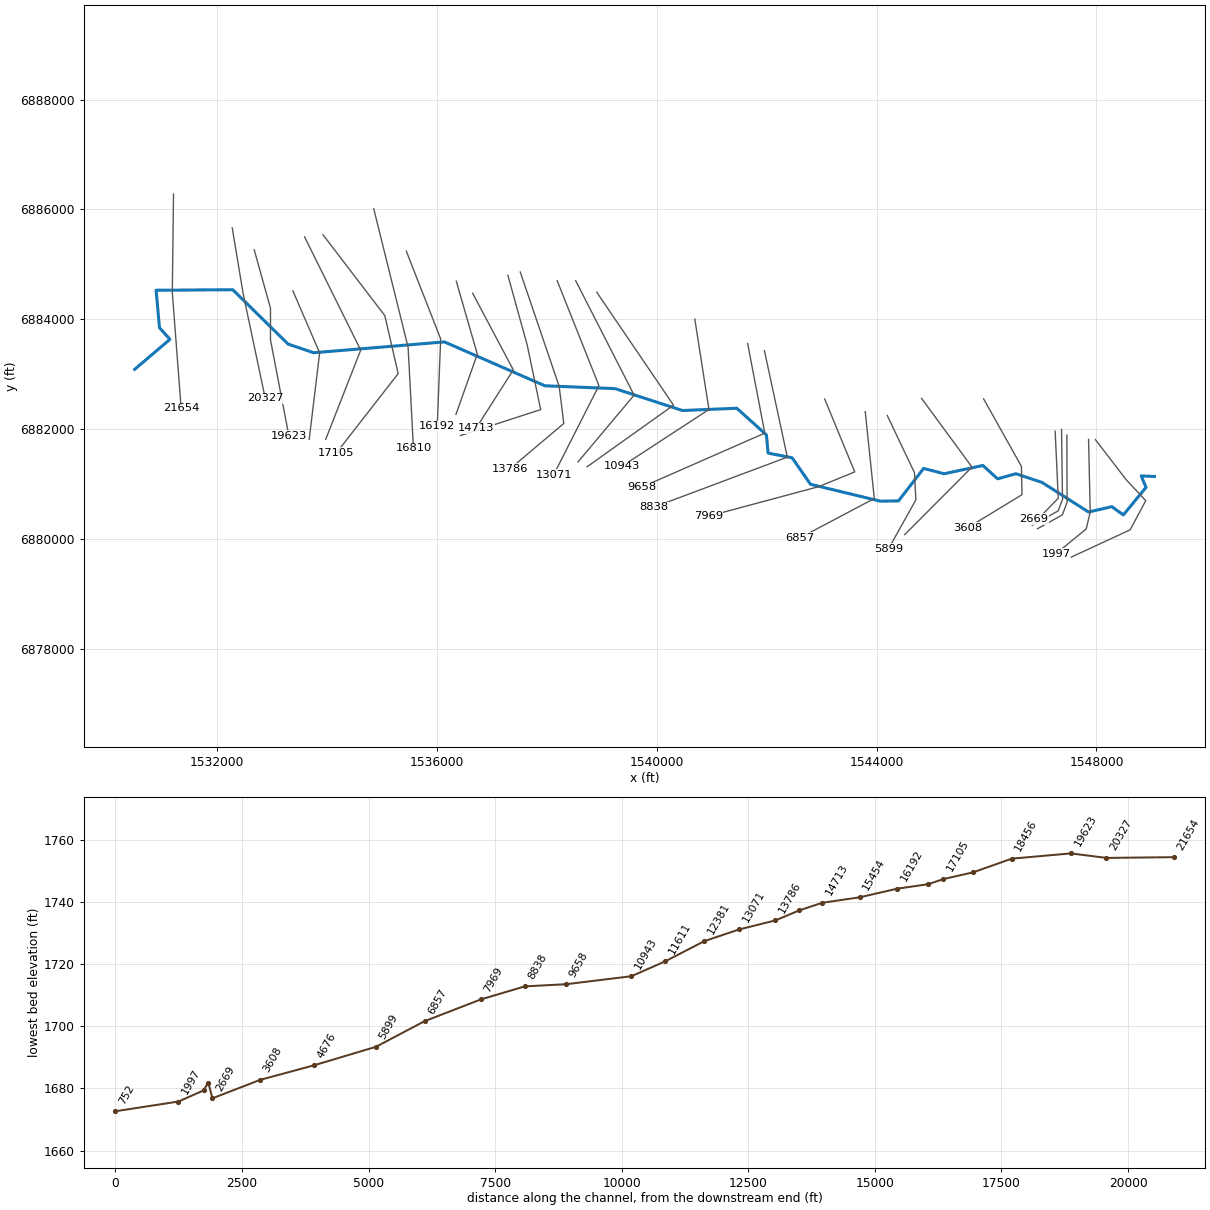
--- MULBERRY CREEK TRIBUTARY 9.prj (project) ---

Proj Title=MULBERRY CREEK TRIBUTARY 9 Base Level Engineering
Current Plan=p01
Default Exp/Contr=0.3,0.1
English Units
Geom File=g01
Flow File=f01
Plan File=p01
BEGIN DESCRIPTION:
MULBERRY CREEK TRIBUTARY 9
END DESCRIPTION:

--- MULBERRY CREEK TRIBUTARY 9.p01 (plan) ---

Plan Title=Multiple Run
Short Identifier=Multiple
Geom File=g01
Flow File=f01
Subcritical Flow
K Sum by GR= 0
Std Step Tol= 0.01
Critical Tol= 0.01
Num of Std Step Trials= 20
Max Error Tol= 0.3
Flow Tol Ratio= 0.001
Split Flow NTrial= 30
Split Flow Tol= 0.02
Split Flow Ratio= 0.02
Log Output Level= 0
Friction Slope Method= 1
Unsteady Friction Slope Method= 2
Unsteady Bridges Friction Slope Method= 1
Parabolic Critical Depth
Global Vel Dist=  1 , 1 , 1
Global Log Level= 0
CheckData=True
Encroach Param= -1, 0, 0, 0
BEGIN DESCRIPTION:
Multiple Run
END DESCRIPTION:

--- MULBERRY CREEK TRIBUTARY 9.f01 (steady flow) ---

Flow Title=Multiple
Number of Profiles=7
Profile Names=10-year,25-year,50-year,1pct_min,100-year,1pct_plu,500-year
River Rch & RM= MULBERRY CREEK T,Reach-1,21654
     315     438     539     330     658    1312     993
River Rch & RM= MULBERRY CREEK T,Reach-1,16810
     346     482     595     365     728    1453    1105
River Rch & RM= MULBERRY CREEK T,Reach-1,9658
     435     614     763     471     940    1876    1447
River Rch & RM= MULBERRY CREEK T,Reach-1,5899
     499     710     888     551    1100    2194    1711
Boundary for River Rch & Prof#=MULBERRY CREEK T,Reach-1,1
Up Type=0
Dn Type=3
Dn Slope=0.005
Boundary for River Rch & Prof#=MULBERRY CREEK T,Reach-1,2
Up Type=0
Dn Type=3
Dn Slope=0.005
Boundary for River Rch & Prof#=MULBERRY CREEK T,Reach-1,3
Up Type=0
Dn Type=3
Dn Slope=0.005
Boundary for River Rch & Prof#=MULBERRY CREEK T,Reach-1,4
Up Type=0
Dn Type=3
Dn Slope=0.005
Boundary for River Rch & Prof#=MULBERRY CREEK T,Reach-1,5
Up Type=0
Dn Type=3
Dn Slope=0.005
Boundary for River Rch & Prof#=MULBERRY CREEK T,Reach-1,6
Up Type=0
Dn Type=3
Dn Slope=0.005
Boundary for River Rch & Prof#=MULBERRY CREEK T,Reach-1,7
Up Type=0
Dn Type=3
Dn Slope=0.005

--- MULBERRY CREEK TRIBUTARY 9.g01 (geometry) ---

Geom Title=Existing Conditions

River Reach=MULBERRY CREEK T,Reach-1
Reach XY= 30
      1530505.00      6883088.00      1531147.42      6883634.68
      1530956.79      6883844.09      1530895.17      6884527.57
      1532289.78      6884537.48      1533295.19      6883548.51
      1533760.94      6883390.26      1536139.78      6883587.48
      1537965.50      6882789.20      1539244.50      6882736.78
      1540470.22      6882338.52      1541458.43      6882380.21
      1541997.14      6881894.17      1542027.25      6881564.12
      1542465.16      6881477.64      1542798.83      6880995.86
      1544065.50      6880689.22      1544399.59      6880693.17
      1544856.28      6881284.63      1545230.12      6881187.70
      1545935.02      6881338.04      1546201.58      6881095.79
      1546534.98      6881187.96      1547011.66      6881028.68
      1547856.64      6880491.14      1548280.19      6880588.35
      1548489.79      6880437.89      1548901.99      6880939.43
      1548815.04      6881148.00      1549055.00      6881138.00

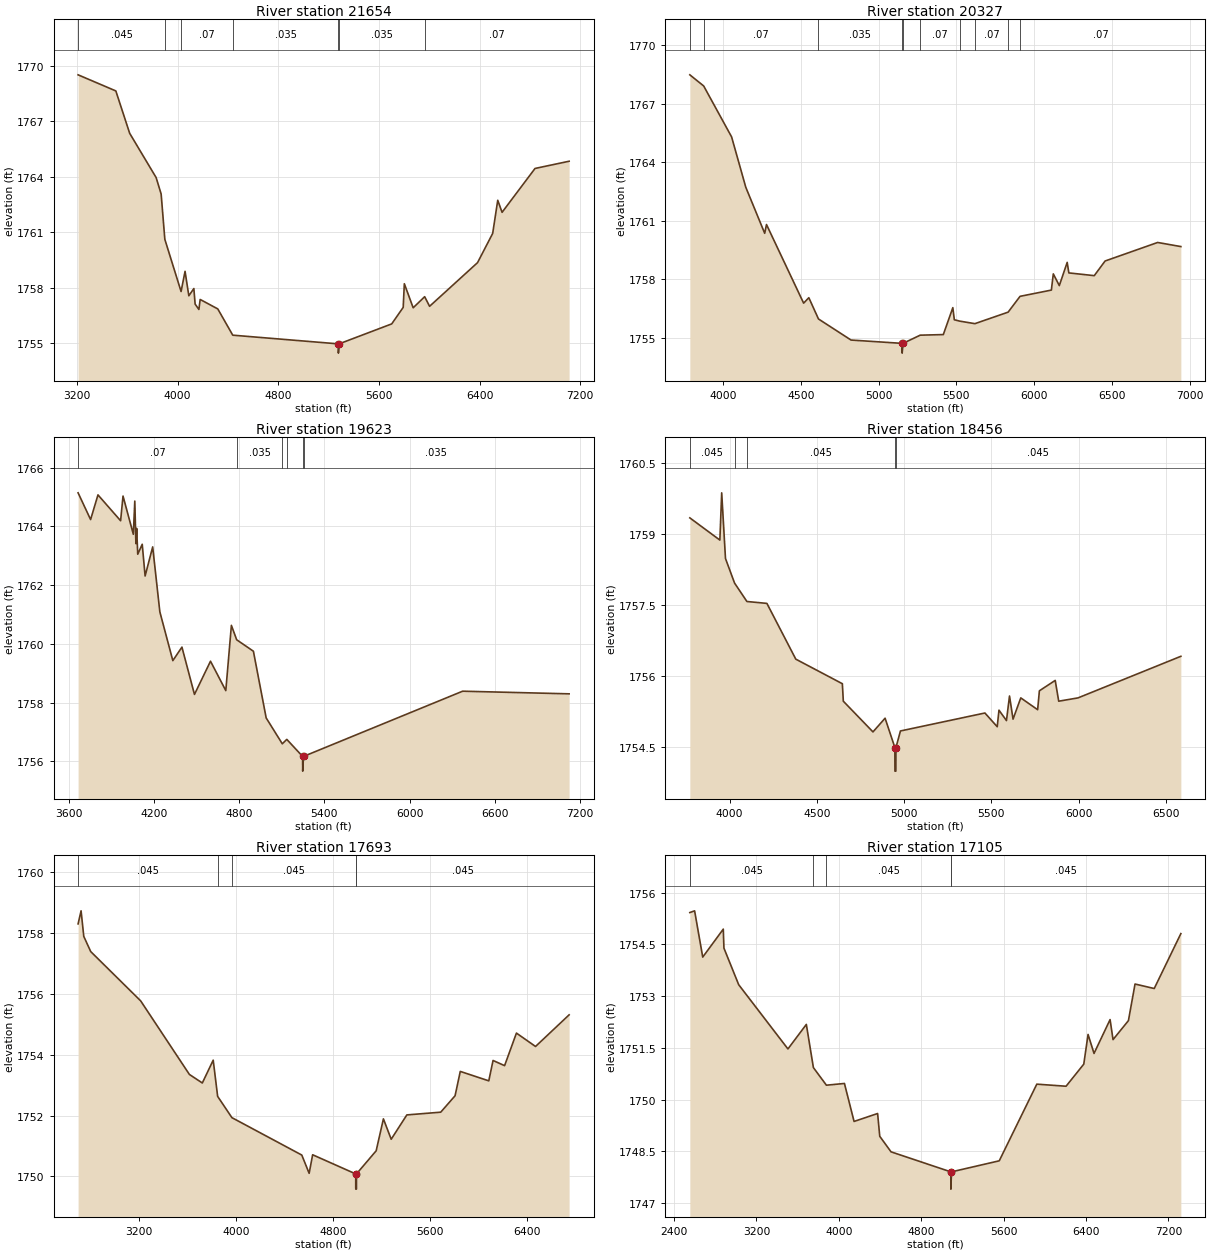
Type RM Length L Ch R = 1,21654,1327,1327,1327
BEGIN DESCRIPTION:
MULBERRY CREEK TRIBUTARY 9 20.0
END DESCRIPTION:
XS GIS Cut Line= 3
      1531211.71      6886277.85      1531189.99      6884487.98
      1531350.56      6882382.50
#Sta/Elev= 30
  3210.0 1769.50  3509.9 1768.63  3619.9 1766.34  3829.9 1763.95  3869.9 1763.06
  3899.3 1760.61  4028.3 1757.79  4059.9 1758.88  4089.9 1757.56  4129.9 1757.95
  4139.9 1757.11  4169.9 1756.82  4180.1 1757.36  4319.9 1756.85  4439.0 1755.43
  5278.0 1754.96  5278.4 1754.46  5283.6 1754.96  5702.0 1756.04  5793.2 1756.93
  5802.3 1758.21  5872.5 1756.91  5963.9 1757.51  6002.9 1756.99  6384.0 1759.35
  6504.3 1760.93  6544.5 1762.72  6578.9 1762.07  6840.8 1764.44  7111.6 1764.83
#Mann=7,-1,0
  3210.0   0.045       0  3899.3   0.035       0  4028.3    0.07       0
  4439.0   0.035       0  5278.0   0.035       0  5283.6   0.035       0
  5963.9    0.07       0
Bank Sta=5278,5283.6
Exp/Cntr=0.3,0.1

Type RM Length L Ch R = 1,20327,704,704,704
BEGIN DESCRIPTION:
Mapping XS 584f04f1
END DESCRIPTION:
XS GIS Cut Line= 3
      1532280.00      6885662.99      1532478.52      6884465.12
      1532879.99      6882563.03
#Sta/Elev= 30
  3785.8 1768.48  3874.8 1767.91  4054.4 1765.30  4145.6 1762.72  4267.3 1760.36
  4278.8 1760.81  4517.7 1756.78  4551.1 1757.06  4613.2 1755.97  4822.6 1754.89
  5150.9 1754.72  5151.4 1754.22  5156.9 1754.72  5267.5 1755.14  5416.1 1755.17
  5477.4 1756.55  5486.9 1755.93  5521.6 1755.86  5619.3 1755.73  5833.0 1756.32
  5909.7 1757.13  6111.1 1757.45  6123.6 1758.28  6162.2 1757.68  6212.9 1758.87
  6223.5 1758.33  6387.0 1758.19  6456.6 1758.94  6794.7 1759.89  6944.0 1759.68
#Mann=10,-1,0
  3785.8   0.035       0  3874.8    0.07       0  4613.2   0.035       0
  5150.9   0.035       0  5156.9   0.035       0  5267.5    0.07       0
  5521.6   0.035       0  5619.3    0.07       0  5833.0   0.035       0
  5909.7    0.07       0
Bank Sta=5150.9,5156.9
Exp/Cntr=0.3,0.1

Type RM Length L Ch R = 1,19623,1167,1167,1167
BEGIN DESCRIPTION:
Mapping XS 892e343d
END DESCRIPTION:
XS GIS Cut Line= 4
      1532680.00      6885263.00      1532975.60      6884201.42
      1532975.60      6883625.03      1533310.95      6881875.03
#Sta/Elev= 30
  3664.1 1765.14  3752.3 1764.23  3804.2 1765.07  3963.7 1764.19  3980.7 1765.03
  4053.4 1763.73  4063.7 1764.86  4071.6 1763.41  4076.7 1763.93  4084.5 1763.05
  4116.1 1763.39  4136.4 1762.31  4189.8 1763.30  4240.2 1761.09  4331.8 1759.43
  4395.9 1759.89  4484.2 1758.28  4597.2 1759.41  4705.0 1758.41  4744.4 1760.63
  4781.6 1760.14  4899.5 1759.75  4989.5 1757.48  5103.1 1756.60  5134.9 1756.75
  5246.4 1756.17  5246.9 1755.67  5252.6 1756.17  6374.1 1758.39  7124.3 1758.30
#Mann=6,-1,0
  3664.1    0.07       0  4781.6   0.035       0  5103.1   0.045       0
  5134.9   0.035       0  5246.4   0.035       0  5252.6   0.035       0
Bank Sta=5246.4,5252.6
Exp/Cntr=0.3,0.1

Type RM Length L Ch R = 1,18456,763,763,763
BEGIN DESCRIPTION:
Mapping XS a97ca77f
END DESCRIPTION:
XS GIS Cut Line= 3
      1533383.87      6884515.65      1533869.98      6883387.96
      1533680.00      6881812.98
#Sta/Elev= 30
  3772.0 1759.34  3944.1 1758.87  3954.6 1759.87  3976.3 1758.48  4028.4 1757.96
  4099.1 1757.57  4213.7 1757.53  4379.3 1756.35  4646.2 1755.83  4651.7 1755.46
  4821.7 1754.81  4891.1 1755.10  4947.1 1754.48  4947.6 1753.98  4952.9 1753.98
  4953.4 1754.48  4979.2 1754.83  5463.3 1755.21  5533.8 1754.92  5543.9 1755.27
  5586.8 1755.05  5604.3 1755.57  5624.5 1755.08  5668.8 1755.53  5765.5 1755.28
  5775.5 1755.68  5866.2 1755.90  5886.3 1755.46  5997.0 1755.53  6586.4 1756.41
#Mann=5,-1,0
  3772.0   0.045       0  4028.4   0.035       0  4099.1   0.045       0
  4947.1   0.045       0  4953.4   0.045       0
Bank Sta=4947.1,4953.4
Exp/Cntr=0.3,0.1

Type RM Length L Ch R = 1,17693,588,588,588
BEGIN DESCRIPTION:
Mapping XS f4a1233b
END DESCRIPTION:
XS GIS Cut Line= 3
      1533595.67      6885500.05      1534616.50      6883438.00
      1533980.00      6881813.01
#Sta/Elev= 30
  2699.1 1758.30  2723.7 1758.73  2746.0 1757.89  2803.2 1757.39  3214.7 1755.77
  3616.4 1753.35  3722.8 1753.07  3812.5 1753.82  3849.0 1752.63  3966.6 1751.93
  4542.5 1750.70  4603.0 1750.10  4631.8 1750.71  4986.7 1750.08  4987.2 1749.58
  4992.6 1749.58  4993.1 1750.08  5155.3 1750.84  5215.0 1751.89  5279.2 1751.22
  5408.1 1752.02  5687.3 1752.11  5805.5 1752.65  5848.4 1753.45  6083.3 1753.14
  6118.4 1753.81  6213.6 1753.64  6311.1 1754.71  6468.5 1754.27  6745.2 1755.31
#Mann=5,-1,0
  2699.1   0.045       0  3849.0   0.035       0  3966.6   0.045       0
  4986.7   0.045       0  4993.1   0.045       0
Bank Sta=4986.7,4993.1
Exp/Cntr=0.3,0.1

Type RM Length L Ch R = 1,17105,295,295,295
BEGIN DESCRIPTION:
Mapping XS da3cfca7
END DESCRIPTION:
XS GIS Cut Line= 4
      1533930.60      6885538.09      1535055.60      6884065.86
      1535298.66      6883010.30      1534173.66      6881565.86
#Sta/Elev= 30
  2554.1 1755.42  2600.4 1755.47  2679.3 1754.13  2878.8 1754.94  2885.1 1754.39
  3028.5 1753.33  3506.4 1751.47  3685.1 1752.18  3753.6 1750.93  3879.9 1750.42
  4055.0 1750.47  4148.5 1749.37  4377.0 1749.60  4397.9 1748.94  4507.4 1748.49
  5087.8 1747.91  5088.3 1747.41  5094.3 1747.91  5557.9 1748.23  5922.5 1750.45
  6206.6 1750.39  6378.5 1751.03  6420.1 1751.89  6478.0 1751.34  6633.8 1752.32
  6662.6 1751.74  6811.9 1752.29  6876.1 1753.35  7062.5 1753.22  7321.0 1754.81
#Mann=5,-1,0
  2554.1   0.045       0  3753.6   0.035       0  3879.9   0.045       0
  5087.8   0.045       0  5094.3   0.045       0
Bank Sta=5087.8,5094.3
Exp/Cntr=0.3,0.1

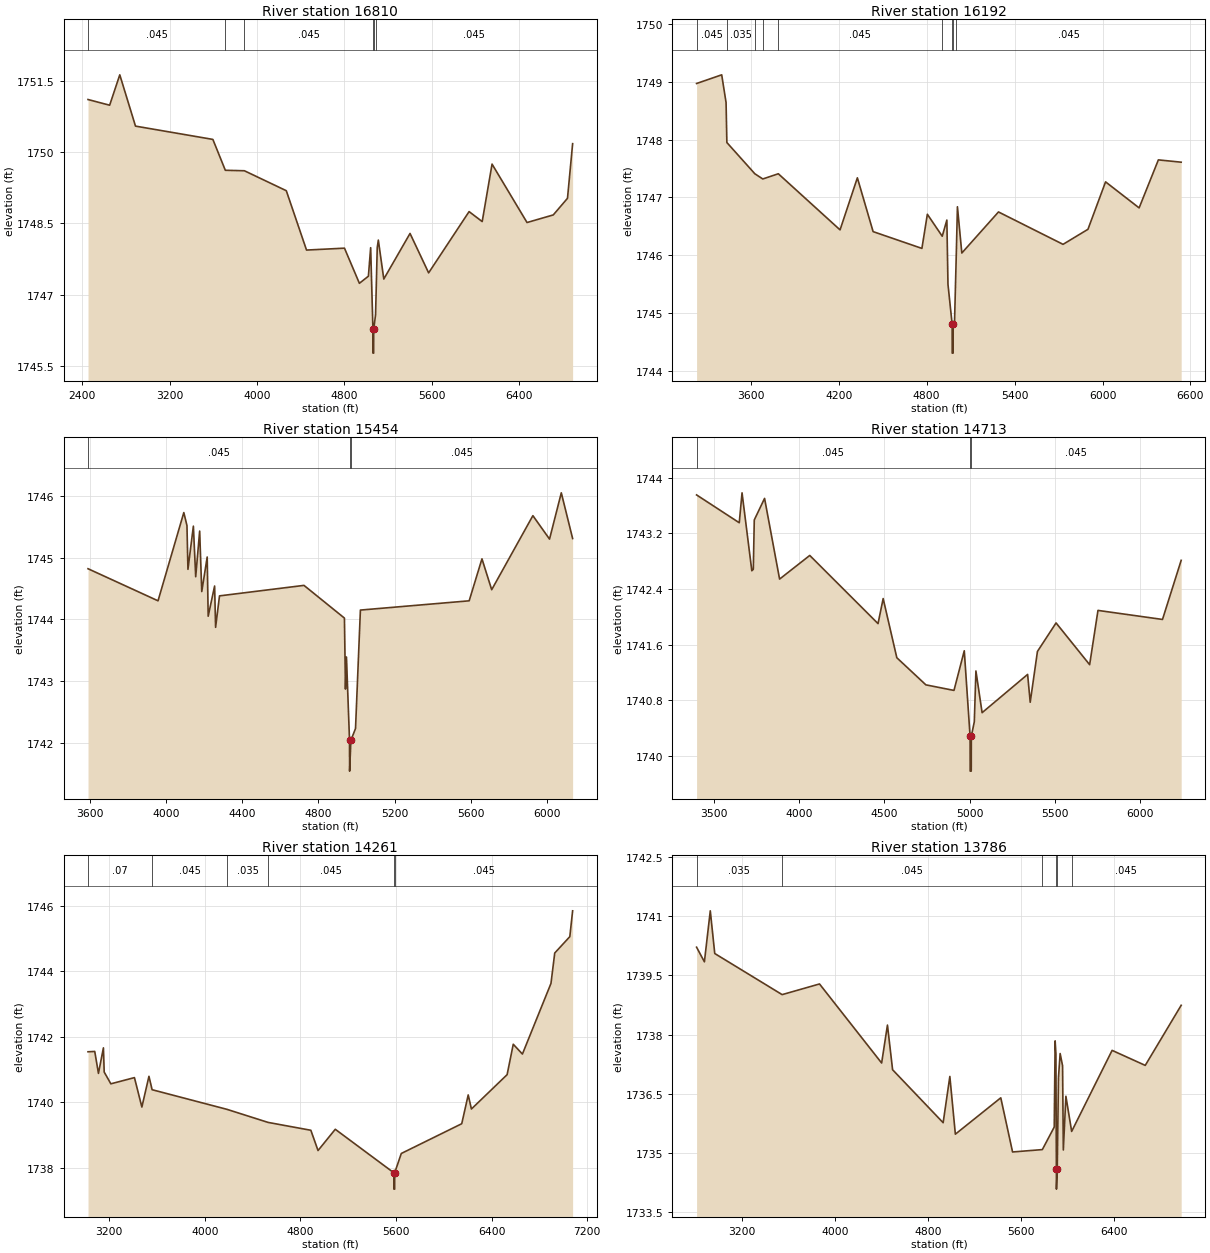
Type RM Length L Ch R = 1,16810,618,618,618
BEGIN DESCRIPTION:
Mapping XS 9f8df6a8
END DESCRIPTION:
XS GIS Cut Line= 3
      1534854.21      6886010.31      1535479.22      6883489.47
      1535576.34      6881651.09
#Sta/Elev= 30
  2452.9 1751.11  2651.0 1750.99  2743.8 1751.63  2887.7 1750.55  3596.3 1750.27
  3710.4 1749.62  3885.0 1749.61  4268.8 1749.19  4454.0 1747.94  4801.6 1747.98
  4938.2 1747.24  5020.7 1747.39  5041.3 1747.99  5062.2 1746.27  5062.7 1745.77
  5068.8 1745.77  5069.3 1746.27  5086.3 1746.58  5101.6 1747.99  5111.6 1748.15
  5161.7 1747.33  5402.0 1748.29  5572.3 1747.46  5942.8 1748.75  6062.9 1748.54
  6153.1 1749.75  6473.5 1748.52  6713.8 1748.68  6844.0 1749.03  6891.0 1750.18
#Mann=6,-1,0
  2452.9   0.045       0  3710.4   0.035       0  3885.0   0.045       0
  5062.2   0.045       0  5069.3   0.045       0  5086.3   0.045       0
Bank Sta=5062.2,5069.3
Exp/Cntr=0.3,0.1

Type RM Length L Ch R = 1,16192,738,738,738
BEGIN DESCRIPTION:
Mapping XS 6571f4fa
END DESCRIPTION:
XS GIS Cut Line= 3
      1535446.38      6885239.59      1536071.36      6883642.41
      1536008.88      6882052.54
#Sta/Elev= 30
  3230.6 1748.97  3402.0 1749.12  3431.8 1748.64  3437.2 1747.95  3628.1 1747.41
  3682.3 1747.32  3788.3 1747.41  4209.5 1746.44  4327.6 1747.34  4435.0 1746.41
  4767.9 1746.12  4805.1 1746.71  4906.6 1746.33  4938.1 1746.61  4945.7 1745.50
  4974.2 1744.81  4974.7 1744.31  4980.8 1744.31  4981.3 1744.81  4990.1 1744.81
  5002.8 1746.05  5010.2 1746.84  5040.2 1746.04  5290.4 1746.75  5730.7 1746.19
  5900.8 1746.45  6020.9 1747.27  6249.8 1746.82  6381.2 1747.65  6536.8 1747.61
#Mann=9,-1,0
  3230.6   0.045       0  3437.2   0.035       0  3628.1   0.045       0
  3682.3   0.035       0  3788.3   0.045       0  4906.6   0.035       0
  4974.2   0.035       0  4981.3   0.035       0  5002.8   0.045       0
Bank Sta=4974.2,4981.3
Exp/Cntr=0.3,0.1

Type RM Length L Ch R = 1,15454,741,741,741
BEGIN DESCRIPTION:
Mapping XS 14ab64d8
END DESCRIPTION:
XS GIS Cut Line= 3
      1536356.08      6884691.03      1536738.03      6883364.63
      1536349.57      6882268.63
#Sta/Elev= 30
  3591.6 1744.82  3959.0 1744.30  4094.3 1745.73  4110.8 1745.52  4116.0 1744.81
  4144.5 1745.51  4156.7 1744.69  4177.5 1745.43  4188.5 1744.45  4217.0 1745.01
  4222.2 1744.05  4255.9 1744.54  4261.1 1743.87  4281.6 1744.38  4724.9 1744.55
  4937.2 1744.02  4942.6 1742.87  4947.8 1743.39  4963.9 1742.04  4964.4 1741.54
  4971.1 1742.04  4995.4 1742.23  5021.0 1744.15  5591.8 1744.30  5658.9 1744.98
  5710.0 1744.48  5926.2 1745.68  6013.5 1745.30  6075.3 1746.05  6134.7 1745.31
#Mann=3,-1,0
  3591.6   0.045       0  4963.9   0.045       0  4971.1   0.045       0
Bank Sta=4963.9,4971.1
Exp/Cntr=0.3,0.1

Type RM Length L Ch R = 1,14713,452,452,452
BEGIN DESCRIPTION:
Mapping XS 2f990b78
END DESCRIPTION:
XS GIS Cut Line= 3
      1536652.95      6884474.03      1537392.54      6883078.17
      1536715.45      6882015.67
#Sta/Elev= 30
  3400.4 1743.75  3650.5 1743.35  3666.8 1743.78  3724.1 1742.66  3732.8 1742.68
  3738.5 1743.39  3798.8 1743.70  3886.8 1742.54  4063.6 1742.88  4463.7 1741.90
  4493.7 1742.26  4573.7 1741.41  4744.0 1741.02  4908.7 1740.94  4969.0 1741.51
  5003.1 1740.28  5003.6 1739.78  5009.8 1739.78  5010.3 1740.28  5027.8 1740.49
  5037.2 1741.22  5073.5 1740.62  5340.2 1741.17  5355.4 1740.77  5397.7 1741.50
  5506.9 1741.91  5703.6 1741.31  5752.4 1742.09  6130.5 1741.96  6240.0 1742.81
#Mann=3,-1,0
  3400.4   0.045       0  5003.1   0.045       0  5010.3   0.045       0
Bank Sta=5003.1,5010.3
Exp/Cntr=0.3,0.1

Type RM Length L Ch R = 1,14261,475,475,475
BEGIN DESCRIPTION:
Mapping XS 5ab1ed03
END DESCRIPTION:
XS GIS Cut Line= 4
      1537293.58      6884802.13      1537647.79      6883521.76
      1537890.85      6882355.09      1536432.67      6881882.92
#Sta/Elev= 30
  3024.2 1741.54  3080.4 1741.55  3111.5 1740.88  3153.0 1741.66  3159.5 1740.92
  3215.2 1740.56  3412.4 1740.75  3474.6 1739.85  3533.8 1740.79  3560.2 1740.38
  4185.9 1739.78  4530.2 1739.38  4887.7 1739.14  4947.9 1738.52  5092.0 1739.17
  5581.9 1737.84  5582.4 1737.34  5588.6 1737.34  5589.1 1737.84  5644.2 1738.43
  6149.7 1739.34  6203.9 1740.22  6230.7 1739.79  6529.2 1740.84  6580.6 1741.77
  6657.2 1741.47  6896.0 1743.63  6927.5 1744.56  7053.6 1745.06  7077.1 1745.85
#Mann=6,-1,0
  3024.2    0.07       0  3560.2   0.045       0  4185.9   0.035       0
  4530.2   0.045       0  5581.9   0.045       0  5589.1   0.045       0
Bank Sta=5581.9,5589.1
Exp/Cntr=0.3,0.1

Type RM Length L Ch R = 1,13786,715,715,715
BEGIN DESCRIPTION:
Mapping XS 14f9894a
END DESCRIPTION:
XS GIS Cut Line= 4
      1537519.32      6884859.43      1538227.65      6882776.10
      1538310.99      6882102.49      1537331.81      6881276.09
#Sta/Elev= 30
  2812.1 1740.21  2879.3 1739.84  2929.8 1741.13  2968.2 1740.05  3546.7 1739.01
  3867.5 1739.28  4400.9 1737.28  4450.8 1738.24  4495.0 1737.11  4929.0 1735.77
  4986.5 1736.94  5033.8 1735.48  5423.8 1736.40  5525.0 1735.03  5780.6 1735.09
  5882.7 1735.66  5890.5 1737.84  5897.0 1737.51  5901.2 1734.59  5901.7 1734.09
  5908.4 1734.59  5919.1 1736.91  5933.4 1737.52  5954.2 1737.21  5960.8 1735.08
  5982.8 1736.44  6032.3 1735.55  6379.6 1737.60  6664.1 1737.22  6972.6 1738.74
#Mann=6,-1,0
  2812.1   0.035       0  3546.7   0.045       0  5780.6   0.035       0
  5901.2   0.045       0  5908.4   0.035       0  6032.3   0.045       0
Bank Sta=5901.2,5908.4
Exp/Cntr=0.3,0.1

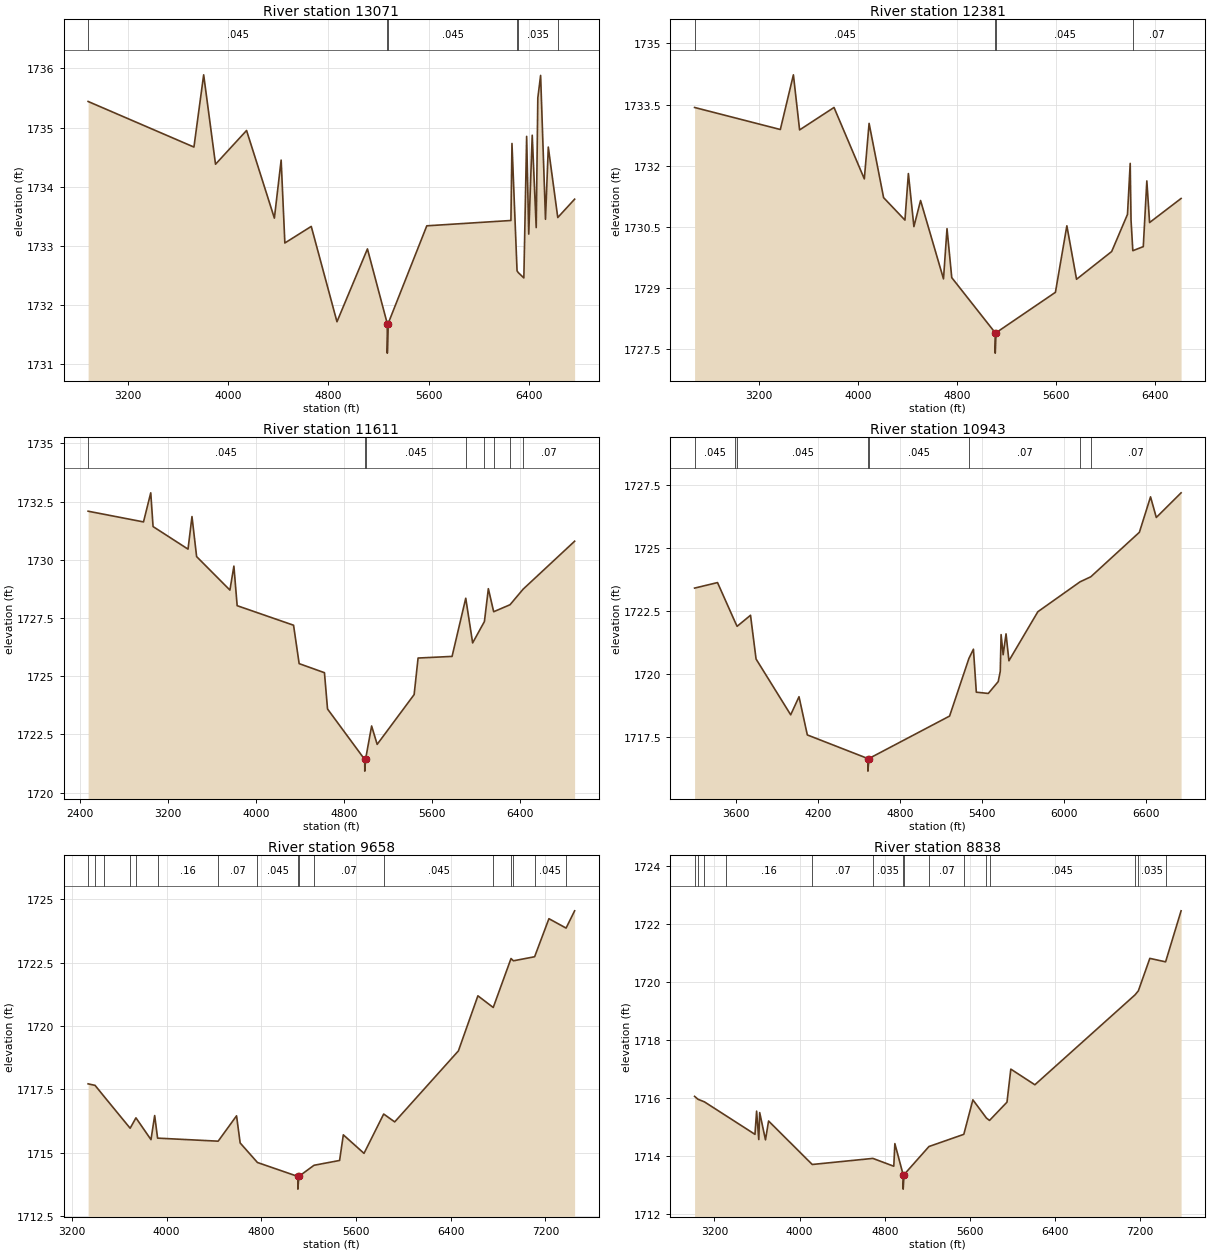
Type RM Length L Ch R = 1,13071,690,690,690
BEGIN DESCRIPTION:
Mapping XS 38ba8300
END DESCRIPTION:
XS GIS Cut Line= 3
      1538190.60      6884702.12      1538950.15      6882792.39
      1538125.51      6881164.81
#Sta/Elev= 30
  2883.8 1735.44  3727.7 1734.67  3805.3 1735.89  3899.8 1734.38  4147.4 1734.95
  4369.2 1733.47  4423.2 1734.45  4452.8 1733.05  4663.3 1733.33  4868.4 1731.72
  5111.4 1732.95  5269.4 1731.69  5269.9 1731.19  5276.6 1731.69  5584.8 1733.34
  6255.6 1733.43  6264.0 1734.73  6304.5 1732.58  6314.2 1732.55  6358.7 1732.46
  6381.0 1734.85  6397.7 1733.20  6425.5 1734.87  6457.3 1733.31  6470.1 1735.50
  6492.4 1735.88  6531.3 1733.45  6553.6 1734.67  6629.2 1733.48  6763.6 1733.79
#Mann=6,-1,0
  2883.8   0.045       0  5269.4   0.045       0  5276.6   0.045       0
  6304.5    0.07       0  6314.2   0.035       0  6629.2   0.045       0
Bank Sta=5269.4,5276.6
Exp/Cntr=0.3,0.1

Type RM Length L Ch R = 1,12381,770,770,770
BEGIN DESCRIPTION:
Mapping XS d390e4d6
END DESCRIPTION:
XS GIS Cut Line= 3
      1538526.96      6884702.14      1539590.34      6882618.78
      1538570.40      6881403.53
#Sta/Elev= 30
  2682.7 1733.43  3374.6 1732.89  3480.1 1734.23  3530.1 1732.88  3807.8 1733.43
  4052.3 1731.68  4090.8 1733.04  4207.9 1731.22  4380.1 1730.67  4407.9 1731.81
  4452.4 1730.51  4506.2 1731.15  4691.2 1729.23  4719.5 1730.46  4757.9 1729.26
  5108.0 1727.91  5108.5 1727.41  5115.3 1727.91  5594.3 1728.90  5686.6 1730.53
  5764.7 1729.22  6048.3 1729.90  6175.8 1730.81  6197.7 1732.06  6204.4 1730.67
  6218.9 1729.92  6303.3 1730.02  6331.9 1731.63  6354.0 1730.61  6608.3 1731.20
#Mann=4,-1,0
  2682.7   0.045       0  5108.0   0.045       0  5115.3   0.045       0
  6218.9    0.07       0
Bank Sta=5108,5115.3
Exp/Cntr=0.3,0.1

Type RM Length L Ch R = 1,11611,668,668,668
BEGIN DESCRIPTION:
Mapping XS 18e5a270
END DESCRIPTION:
XS GIS Cut Line= 3
      1538909.97      6884492.64      1540307.51      6882435.39
      1538736.37      6881315.62
#Sta/Elev= 30
  2477.1 1732.09  2979.9 1731.63  3045.7 1732.88  3066.7 1731.43  3384.1 1730.46
  3420.0 1731.86  3462.0 1730.14  3764.3 1728.70  3800.4 1729.73  3830.1 1728.03
  4342.1 1727.19  4392.8 1725.54  4622.5 1725.15  4650.5 1723.59  4988.1 1721.42
  4988.6 1720.92  4995.4 1721.42  5050.7 1722.86  5101.1 1722.07  5436.7 1724.21
  5472.4 1725.78  5781.0 1725.85  5905.2 1728.35  5967.8 1726.43  6074.7 1727.35
  6110.4 1728.76  6158.8 1727.77  6306.9 1728.07  6426.1 1728.74  6893.5 1730.80
#Mann=8,-1,0
  2477.1   0.045       0  4988.1   0.045       0  4995.4   0.045       0
  5905.2    0.07       0  6074.7   0.045       0  6158.8    0.07       0
  6306.9   0.035       0  6426.1    0.07       0
Bank Sta=4988.1,4995.4
Exp/Cntr=0.3,0.1

Type RM Length L Ch R = 1,10943,1285,1285,1285
BEGIN DESCRIPTION:
Mapping XS 56b33f67
END DESCRIPTION:
XS GIS Cut Line= 3
      1540694.62      6884001.82      1540951.57      6882357.69
      1539369.11      6881323.54
#Sta/Elev= 30
  3299.9 1723.41  3467.5 1723.63  3596.0 1722.06  3610.6 1721.89  3708.6 1722.33
  3749.1 1720.59  4002.1 1718.37  4062.9 1719.09  4123.6 1717.57  4565.9 1716.63
  4566.4 1716.13  4573.3 1716.63  5163.0 1718.32  5304.0 1720.61  5337.2 1720.98
  5358.3 1719.27  5445.8 1719.22  5518.2 1719.69  5533.3 1720.10  5539.3 1721.56
  5554.4 1720.76  5575.5 1721.59  5596.5 1720.52  5807.8 1722.47  6116.2 1723.66
  6194.7 1723.86  6549.7 1725.63  6631.2 1727.04  6673.4 1726.22  6854.4 1727.20
#Mann=8,-1,0
  3299.9   0.045       0  3596.0   0.035       0  3610.6   0.045       0
  4565.9   0.045       0  4573.3   0.045       0  5304.0    0.07       0
  6116.2   0.035       0  6194.7    0.07       0
Bank Sta=4565.9,4573.3
Exp/Cntr=0.3,0.1

Type RM Length L Ch R = 1,9658,820,820,820
BEGIN DESCRIPTION:
Mapping XS 2024e77d
END DESCRIPTION:
XS GIS Cut Line= 3
      1541655.09      6883559.59      1541967.60      6881927.61
      1539726.27      6880942.25
#Sta/Elev= 30
  3337.1 1717.72  3395.9 1717.66  3472.4 1717.22  3692.2 1715.97  3741.2 1716.38
  3868.2 1715.52  3899.4 1716.47  3924.0 1715.58  4435.7 1715.46  4591.1 1716.46
  4621.6 1715.39  4767.6 1714.62  5108.8 1714.07  5109.3 1713.57  5117.0 1714.07
  5245.4 1714.51  5461.6 1714.70  5493.1 1715.71  5667.9 1714.98  5834.1 1716.53
  5927.1 1716.22  6465.4 1719.02  6630.0 1721.19  6759.6 1720.73  6909.8 1722.66
  6930.4 1722.57  7109.2 1722.73  7230.0 1724.23  7375.0 1723.86  7447.1 1724.54
#Mann=17,-1,0
  3337.1    0.07       0  3395.9   0.035       0  3472.4    0.07       0
  3692.2    0.16       0  3741.2    0.07       0  3924.0    0.16       0
  4435.7    0.07       0  4767.6   0.045       0  5108.8   0.045       0
  5117.0   0.045       0  5245.4    0.07       0  5834.1   0.045       0
  6759.6    0.07       0  6909.8   0.045       0  6930.4    0.07       0
  7109.2   0.045       0  7375.0    0.07       0
Bank Sta=5108.8,5117
Exp/Cntr=0.3,0.1

Type RM Length L Ch R = 1,8838,869,869,869
BEGIN DESCRIPTION:
Mapping XS 6ca51e06
END DESCRIPTION:
XS GIS Cut Line= 3
      1541960.66      6883427.59      1542377.32      6881490.11
      1539953.71      6880580.38
#Sta/Elev= 30
  3013.2 1716.06  3045.0 1715.96  3105.9 1715.87  3305.0 1715.40  3580.6 1714.75
  3595.8 1715.55  3616.3 1714.57  3624.9 1715.50  3679.3 1714.56  3708.3 1715.21
  4118.6 1713.71  4688.3 1713.92  4884.6 1713.65  4894.8 1714.43  4972.4 1713.36
  4972.9 1712.86  4980.9 1713.36  5215.2 1714.33  5542.5 1714.75  5627.7 1715.94
  5755.5 1715.31  5784.1 1715.23  5948.1 1715.86  5984.1 1717.00  6210.1 1716.46
  7150.8 1719.56  7182.3 1719.70  7290.1 1720.82  7438.1 1720.70  7583.7 1722.46
#Mann=15,-1,0
  3013.2    0.07       0  3045.0   0.035       0  3105.9    0.07       0
  3305.0    0.16       0  4118.6    0.07       0  4688.3   0.035       0
  4972.4   0.035       0  4980.9   0.035       0  5215.2    0.07       0
  5542.5   0.045       0  5755.5    0.07       0  5784.1   0.045       0
  7150.8    0.07       0  7182.3   0.035       0  7438.1    0.07       0
Bank Sta=4972.4,4980.9
Exp/Cntr=0.3,0.1

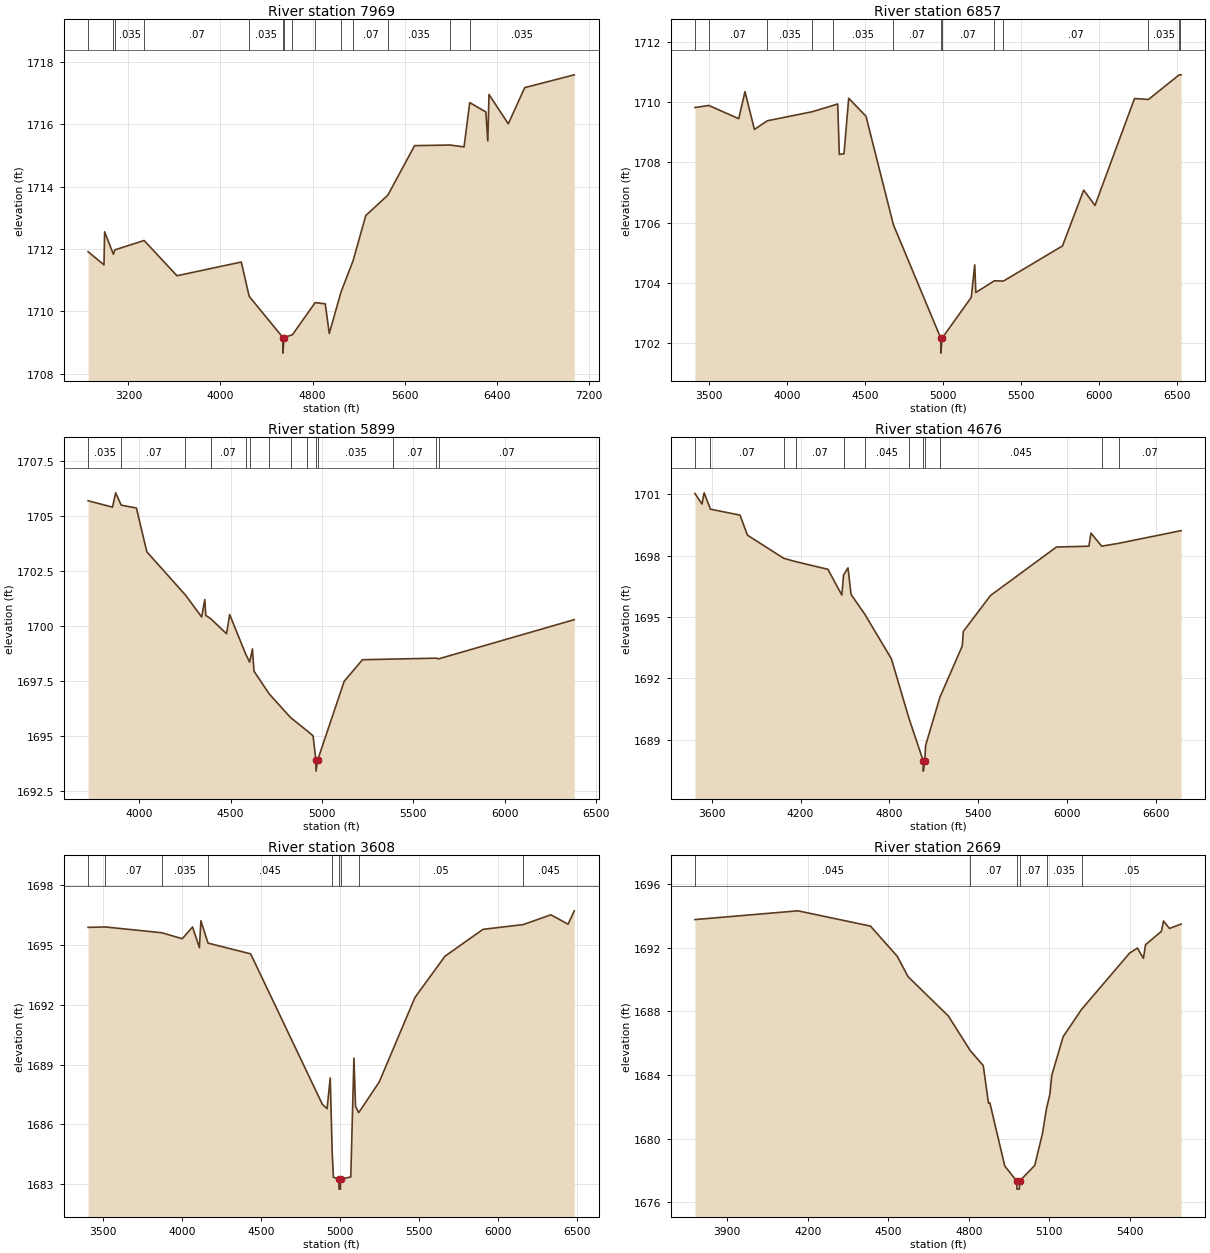
Type RM Length L Ch R = 1,7969,1112,1112,1112
BEGIN DESCRIPTION:
Mapping XS 4c68c799
END DESCRIPTION:
XS GIS Cut Line= 4
      1543056.72      6882548.77      1543603.58      6881220.68
      1542943.86      6880951.58      1540939.36      6880413.58
#Sta/Elev= 30
  2849.9 1711.91  2987.9 1711.49  2993.3 1712.55  3069.5 1711.83  3082.3 1711.97
  3336.7 1712.27  3622.1 1711.14  4180.9 1711.58  4249.5 1710.48  4542.7 1709.16
  4543.2 1708.66  4551.3 1709.16  4625.6 1709.25  4822.9 1710.28  4910.6 1710.24
  4945.4 1709.29  5046.6 1710.61  5153.0 1711.63  5262.4 1713.07  5453.6 1713.72
  5686.8 1715.31  5993.7 1715.33  6116.4 1715.27  6165.8 1716.69  6306.0 1716.39
  6322.8 1715.46  6333.1 1716.95  6500.8 1716.01  6643.8 1717.17  7074.1 1717.58
#Mann=14,-1,0
  2849.9   0.035       0  3069.5    0.07       0  3082.3   0.035       0
  3336.7    0.07       0  4249.5   0.035       0  4542.7    0.07       0
  4551.3   0.035       0  4625.6   0.035       0  4822.9    0.07       0
  5046.6   0.035       0  5153.0    0.07       0  5453.6   0.035       0
  5993.7    0.07       0  6165.8   0.035       0
Bank Sta=4542.7,4551.3
Exp/Cntr=0.3,0.1

Type RM Length L Ch R = 1,6857,958,958,958
BEGIN DESCRIPTION:
Mapping XS 5f75fe59
END DESCRIPTION:
XS GIS Cut Line= 3
      1543794.55      6882316.56      1543959.48      6880736.74
      1542613.98      6880024.93
#Sta/Elev= 30
  3412.9 1709.83  3501.6 1709.90  3693.0 1709.46  3733.2 1710.36  3793.5 1709.10
  3876.2 1709.39  4162.3 1709.69  4296.5 1709.90  4326.4 1709.95  4336.8 1708.27
  4366.6 1708.29  4396.8 1710.14  4507.4 1709.54  4682.5 1705.93  4985.6 1702.15
  4986.1 1701.65  4994.3 1702.15  5181.1 1703.51  5203.1 1704.59  5210.0 1703.67
  5329.1 1704.06  5386.7 1704.05  5764.4 1705.22  5900.1 1707.08  5972.6 1706.57
  6225.4 1710.13  6314.8 1710.10  6511.2 1710.92  6518.1 1710.92  6523.5 1710.92
#Mann=13,-1,0
  3412.9   0.035       0  3501.6    0.07       0  3876.2   0.035       0
  4162.3    0.07       0  4296.5   0.035       0  4682.5    0.07       0
  4985.6    0.07       0  4994.3    0.07       0  5329.1   0.035       0
  5386.7    0.07       0  6314.8   0.035       0  6511.2    0.07       0
  6518.1   0.035       0
Bank Sta=4985.6,4994.3
Exp/Cntr=0.3,0.1

Type RM Length L Ch R = 1,5899,1223,1223,1223
BEGIN DESCRIPTION:
Mapping XS d5ecd8d6
END DESCRIPTION:
XS GIS Cut Line= 4
      1544195.01      6882248.78      1544689.81      6881207.10
      1544715.85      6880712.31      1544221.05      6879826.88
#Sta/Elev= 30
  3719.0 1705.70  3852.7 1705.41  3869.9 1706.06  3900.5 1705.50  3983.5 1705.37
  4040.9 1703.38  4252.1 1701.42  4341.0 1700.42  4358.2 1701.21  4363.7 1700.49
  4389.8 1700.35  4477.3 1699.66  4494.5 1700.53  4583.1 1698.72  4603.8 1698.37
  4619.2 1698.97  4627.7 1697.96  4710.8 1696.93  4828.4 1695.85  4920.3 1695.24
  4951.4 1695.02  4966.6 1693.92  4967.1 1693.42  4976.3 1693.92  5121.7 1697.50
  5221.8 1698.48  5390.8 1698.51  5624.9 1698.55  5639.3 1698.52  6382.0 1700.30
#Mann=14,-1,0
  3719.0   0.035       0  3900.5    0.07       0  4252.1   0.035       0
  4389.8    0.07       0  4583.1   0.035       0  4603.8    0.07       0
  4710.8   0.045       0  4828.4    0.07       0  4920.3   0.035       0
  4966.6   0.035       0  4976.3   0.035       0  5390.8    0.07       0
  5624.9   0.035       0  5639.3    0.07       0
Bank Sta=4966.6,4976.3
Exp/Cntr=0.3,0.1

Type RM Length L Ch R = 1,4676,1068,1068,1068
BEGIN DESCRIPTION:
Mapping XS f3b6767a
END DESCRIPTION:
XS GIS Cut Line= 3
      1544819.80      6882558.66      1545736.48      6881308.65
      1544512.54      6880079.50
#Sta/Elev= 30
  3486.3 1701.04  3533.9 1700.52  3548.6 1701.07  3591.0 1700.27  3791.0 1699.98
  3841.1 1699.00  4085.7 1697.87  4169.8 1697.70  4384.5 1697.33  4478.7 1696.07
  4490.6 1697.05  4520.4 1697.40  4541.2 1696.10  4633.4 1695.14  4814.0 1692.95
  4932.0 1690.05  5028.8 1687.96  5029.3 1687.46  5038.7 1687.96  5045.0 1688.72
  5141.7 1691.08  5292.5 1693.58  5299.5 1694.29  5483.4 1696.05  5928.9 1698.42
  6148.1 1698.46  6162.2 1699.10  6234.4 1698.46  6348.2 1698.60  6771.0 1699.22
#Mann=12,-1,0
  3486.3   0.035       0  3591.0    0.07       0  4085.7   0.035       0
  4169.8    0.07       0  4490.6   0.035       0  4633.4   0.045       0
  4932.0    0.05       0  5028.8    0.05       0  5038.7    0.05       0
  5141.7   0.045       0  6234.4   0.035       0  6348.2    0.07       0
Bank Sta=5028.8,5038.7
Exp/Cntr=0.3,0.1

Type RM Length L Ch R = 1,3608,939,939,939
BEGIN DESCRIPTION:
Mapping XS bbbe33c9
END DESCRIPTION:
XS GIS Cut Line= 4
      1545948.00      6882550.98      1546635.49      6881321.82
      1546645.91      6880806.19      1545661.51      6880207.22
#Sta/Elev= 30
  3406.6 1695.89  3515.8 1695.91  3872.5 1695.62  4002.4 1695.32  4067.5 1695.91
  4110.9 1694.87  4120.4 1696.22  4165.4 1695.10  4435.2 1694.56  4888.8 1687.01
  4918.8 1686.79  4938.8 1688.33  4951.1 1684.63  4958.8 1683.35  4993.8 1683.25
  4994.3 1682.75  5003.4 1682.75  5003.9 1683.25  5068.8 1683.36  5088.8 1689.33
  5098.8 1686.91  5119.0 1686.59  5248.9 1688.13  5474.8 1692.37  5664.6 1694.44
  5905.3 1695.79  6160.2 1696.03  6334.9 1696.52  6443.8 1696.05  6483.0 1696.72
#Mann=9,-1,0
  3406.6   0.035       0  3515.8    0.07       0  3872.5   0.035       0
  4165.4   0.045       0  4951.1   0.035       0  4993.8   0.035       0
  5003.9   0.035       0  5119.0    0.05       0  6160.2   0.045       0
Bank Sta=4993.8,5003.9
Exp/Cntr=0.3,0.1

Type RM Length L Ch R = 1,2669,83,83,83
BEGIN DESCRIPTION:
Mapping XS 4dc91cf4
END DESCRIPTION:
XS GIS Cut Line= 4
      1547249.21      6881961.53      1547305.63      6880741.96
      1547014.83      6880442.48      1546859.30      6880364.71
#Sta/Elev= 30
  3779.4 1693.78  4163.3 1694.33  4433.6 1693.37  4533.7 1691.47  4573.8 1690.19
  4723.9 1687.72  4805.7 1685.54  4854.1 1684.60  4873.7 1682.23  4878.7 1682.26
  4934.2 1678.29  4979.1 1677.33  4979.6 1676.83  4988.8 1676.83  4989.3 1677.33
  5046.0 1678.32  5074.3 1680.29  5090.1 1681.92  5102.6 1682.80  5109.6 1683.99
  5152.0 1686.42  5220.5 1688.13  5399.5 1691.67  5428.7 1691.99  5451.1 1691.34
  5459.0 1692.20  5518.2 1693.04  5526.0 1693.69  5548.4 1693.22  5591.6 1693.50
#Mann=6,-1,0
  3779.4   0.045       0  4805.7    0.07       0  4979.1    0.07       0
  4989.3    0.07       0  5090.1   0.035       0  5220.5    0.05       0
Bank Sta=4979.1,4989.3
Exp/Cntr=0.3,0.1

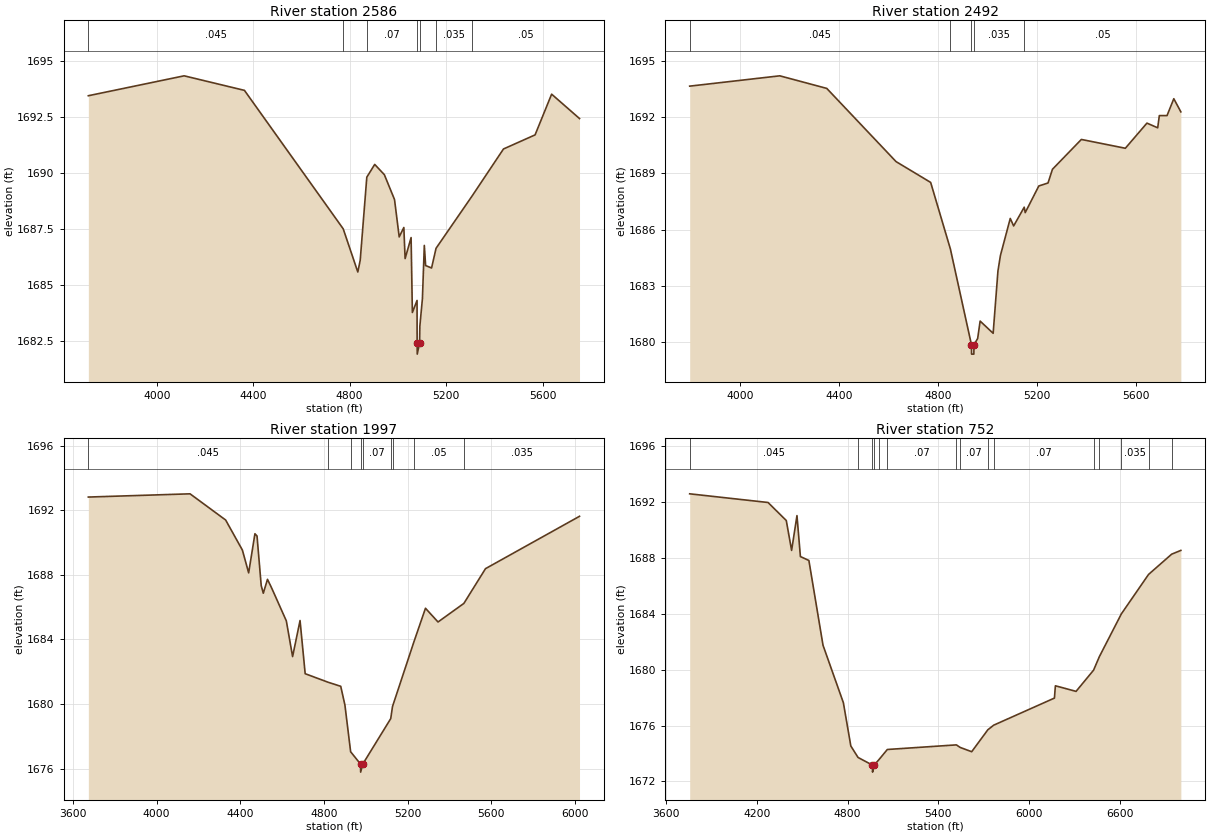
Type RM Length L Ch R = 1,2586,94,94,94
BEGIN DESCRIPTION:
Mapping XS 07a9c207
END DESCRIPTION:
XS GIS Cut Line= 5
      1547365.22      6881995.02      1547380.85      6880854.36
      1547386.06      6880729.36      1547302.72      6880510.61
      1546833.97      6880250.19
#Sta/Elev= 30
  3716.6 1693.45  4113.7 1694.34  4363.7 1693.69  4773.2 1687.50  4833.7 1685.57
  4843.7 1686.10  4871.0 1689.81  4903.8 1690.38  4943.8 1689.92  4985.9 1688.81
  5005.3 1687.14  5024.5 1687.56  5029.8 1686.17  5054.6 1687.11  5059.9 1683.76
  5079.3 1684.30  5079.6 1682.40  5080.1 1681.90  5089.8 1682.40  5090.9 1683.15
  5101.6 1684.39  5109.4 1686.76  5114.8 1685.86  5139.5 1685.75  5158.0 1686.63
  5307.6 1688.97  5437.6 1691.07  5568.6 1691.70  5637.2 1693.52  5752.8 1692.43
#Mann=7,-1,0
  3716.6   0.045       0  4773.2   0.035       0  4871.0    0.07       0
  5079.6    0.07       0  5089.8    0.07       0  5158.0   0.035       0
  5307.6    0.05       0
Bank Sta=5079.6,5089.8
Exp/Cntr=0.3,0.1

Type RM Length L Ch R = 1,2492,495,495,495
BEGIN DESCRIPTION:
Mapping XS 67eb5f4c
END DESCRIPTION:
XS GIS Cut Line= 4
      1547461.88      6881892.08      1547466.22      6880668.17
      1547379.42      6880438.14      1546929.01      6880186.95
#Sta/Elev= 30
  3795.6 1693.64  4159.7 1694.19  4349.7 1693.52  4629.7 1689.62  4769.7 1688.51
  4849.5 1684.96  4934.6 1679.86  4935.1 1679.36  4944.3 1679.36  4944.8 1679.86
  4959.7 1680.19  4969.7 1681.12  5022.3 1680.47  5041.8 1683.80  5051.8 1684.62
  5091.5 1686.59  5105.2 1686.19  5147.9 1687.19  5151.9 1686.90  5206.9 1688.32
  5244.2 1688.48  5262.0 1689.21  5378.9 1690.80  5556.7 1690.33  5644.0 1691.67
  5687.5 1691.42  5694.1 1692.07  5725.2 1692.07  5752.6 1692.97  5781.1 1692.27
#Mann=5,-1,0
  3795.6   0.045       0  4849.5   0.035       0  4934.6   0.035       0
  4944.8   0.035       0  5147.9    0.05       0
Bank Sta=4934.6,4944.8
Exp/Cntr=0.3,0.1

Type RM Length L Ch R = 1,1997,1245,1245,1245
BEGIN DESCRIPTION:
Mapping XS 1200cd76
END DESCRIPTION:
XS GIS Cut Line= 4
      1547856.85      6881813.99      1547887.23      6880485.88
      1547813.45      6880182.06      1547266.54      6879734.98
#Sta/Elev= 30
  3673.5 1692.81  4159.6 1693.01  4329.7 1691.39  4409.7 1689.53  4439.7 1688.12
  4469.7 1690.54  4479.7 1690.40  4499.7 1687.33  4509.7 1686.86  4529.7 1687.72
  4549.7 1687.18  4619.7 1685.15  4649.7 1682.94  4685.3 1685.17  4709.8 1681.88
  4819.7 1681.35  4879.8 1681.10  4899.8 1679.94  4927.1 1677.05  4974.4 1676.29
  4974.9 1675.79  4985.2 1676.29  5118.7 1679.10  5127.2 1679.85  5228.7 1683.82
  5284.8 1685.93  5344.8 1685.08  5468.3 1686.23  5571.7 1688.38  6021.0 1691.62
#Mann=9,-1,0
  3673.5   0.045       0  4819.7   0.035       0  4927.1    0.07       0
  4974.4    0.07       0  4985.2    0.07       0  5118.7    0.05       0
  5127.2    0.07       0  5228.7    0.05       0  5468.3   0.035       0
Bank Sta=4974.4,4985.2
Exp/Cntr=0.3,0.1

Type RM Length L Ch R = 1,752,0,0,0
BEGIN DESCRIPTION:
MULBERRY CREEK TRIBUTARY 9 1.0
END DESCRIPTION:
XS GIS Cut Line= 5
      1547981.00      6881809.06      1548543.48      6881076.45
      1548897.65      6880697.97      1548612.92      6880166.72
      1547522.62      6879661.22
#Sta/Elev= 30
  3756.4 1692.59  4274.3 1691.97  4394.8 1690.68  4430.1 1688.54  4465.5 1691.03
  4488.2 1688.10  4544.3 1687.82  4637.7 1681.75  4772.2 1677.64  4821.5 1674.54
  4869.2 1673.72  4964.6 1673.17  4965.1 1672.67  4975.5 1673.17  5006.3 1673.55
  5062.7 1674.29  5519.2 1674.62  5543.8 1674.44  5620.3 1674.13  5727.1 1675.70
  5765.6 1676.03  6167.3 1677.97  6173.6 1678.85  6310.3 1678.45  6426.1 1679.97
  6464.0 1680.93  6609.8 1684.00  6789.4 1686.82  6942.1 1688.27  7002.9 1688.54
#Mann=15,-1,0
  3756.4   0.045       0  4869.2    0.07       0  4964.6    0.07       0
  4975.5    0.07       0  5006.3   0.045       0  5062.7    0.07       0
  5519.2   0.035       0  5543.8    0.07       0  5727.1   0.035       0
  5765.6    0.07       0  6426.1   0.035       0  6464.0    0.07       0
  6609.8   0.035       0  6789.4    0.07       0  6942.1   0.035       0
Bank Sta=4964.6,4975.5
Exp/Cntr=0.3,0.1

Chan Stop Cuts=-1