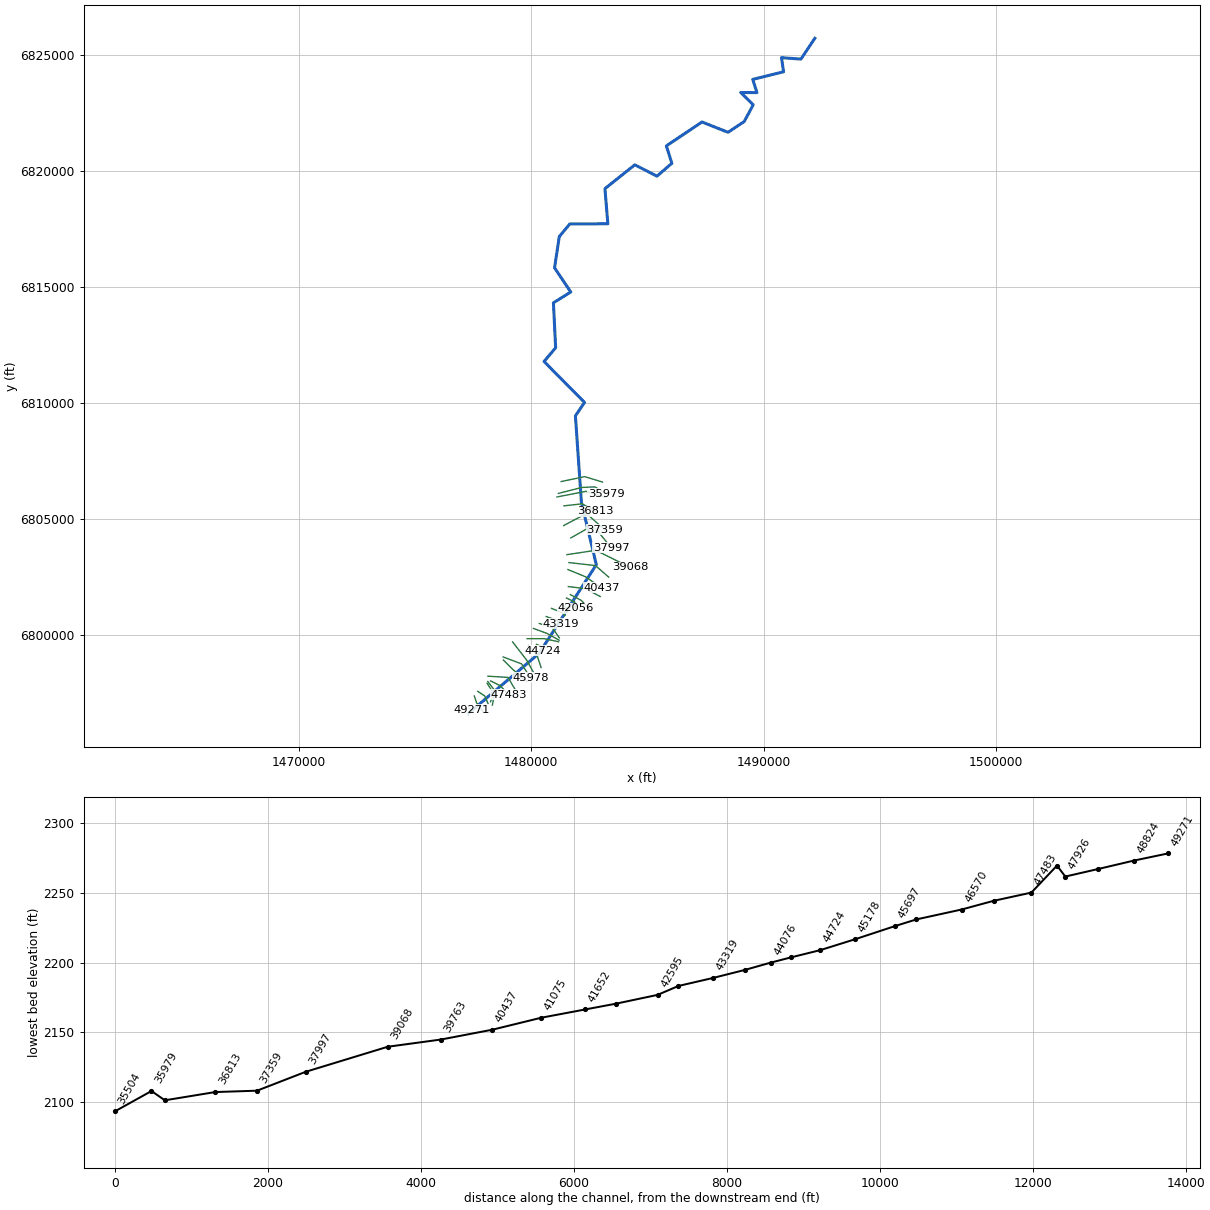
--- NUBIA CREEK.prj (project) ---

Proj Title=NUBIA CREEK Base Level Engineering
Current Plan=p01
Default Exp/Contr=0.3,0.1
English Units
Geom File=g01
Flow File=f01
Plan File=p01
Y Axis Title=Elevation
X Axis Title(PF)=Main Channel Distance
X Axis Title(XS)=Station
BEGIN DESCRIPTION:
NUBIA CREEK
END DESCRIPTION:
DSS Export Rating Curves= 0
DSS Export Rating Curve Sorted= 0
DSS Export Volume Flow Curves= 0
DXF OffsetX= 0
DXF OffsetY= 0
DXF ScaleX= 1
DXF ScaleY= 10

--- NUBIA CREEK.p01 (plan) ---

Plan Title=Multiple Run
Short Identifier=Multiple
Geom File=g01
Flow File=f01
Subcritical Flow
K Sum by GR= 0
Std Step Tol= 0.01
Critical Tol= 0.01
Num of Std Step Trials= 20
Max Error Tol= 0.3
Flow Tol Ratio= 0.001
Split Flow NTrial= 30
Split Flow Tol= 0.02
Split Flow Ratio= 0.02
Log Output Level= 0
Friction Slope Method= 1
Unsteady Friction Slope Method= 2
Unsteady Bridges Friction Slope Method= 1
Parabolic Critical Depth
Global Vel Dist=  1 , 1 , 1
Global Log Level= 0
CheckData=True
Encroach Param= -1, 0, 0, 0
BEGIN DESCRIPTION:
Multiple Run
END DESCRIPTION:

--- NUBIA CREEK.f01 (steady flow) ---

Flow Title=Multiple
Program Version=4.10
Number of Profiles= 7
Profile Names=10-year,25-year,50-year,1pct_min,100-year,1pct_plu,500-year
River Rch & RM=NUBIA CREEK,Reach-1         ,49271
     323     457     570     354     706    1409    1095
River Rch & RM=NUBIA CREEK,Reach-1         ,48824
     485     702     890     561    1120    2235    1792
River Rch & RM=NUBIA CREEK,Reach-1         ,44345
     685    1011    1299     828    1652    3297    2707
River Rch & RM=NUBIA CREEK,Reach-1         ,41652
     824    1228    1586    1017    2029    4049    3362
River Rch & RM=NUBIA CREEK,Reach-1         ,36154
     969    1453    1885    1213    2419    4827    4036
River Rch & RM=NUBIA CREEK,Reach-1         ,29491
    1035    1563    2034    1313    2620    5228    4404
River Rch & RM=NUBIA CREEK,Reach-1         ,22628
    1729    2661    3510    2292    4573    9125    7866
River Rch & RM=NUBIA CREEK,Reach-1         ,13992
    2071    3202    4237    2774    5536   11045    9571
River Rch & RM=NUBIA CREEK,Reach-1         ,5747
    2095    3236    4278    2799    5585   11143    9639
River Rch & RM=NUBIA CREEK,Reach-1         ,842
    3236    5073    6777    4476    8930   17818   15704
Boundary for River Rch & Prof#=NUBIA CREEK,Reach-1         , 1
Up Type= 0
Dn Type= 3
Dn Slope=0.00313
Boundary for River Rch & Prof#=NUBIA CREEK,Reach-1         , 2
Up Type= 0
Dn Type= 3
Dn Slope=0.00313
Boundary for River Rch & Prof#=NUBIA CREEK,Reach-1         , 3
Up Type= 0
Dn Type= 3
Dn Slope=0.00313
Boundary for River Rch & Prof#=NUBIA CREEK,Reach-1         , 4
Up Type= 0
Dn Type= 3
Dn Slope=0.00313
Boundary for River Rch & Prof#=NUBIA CREEK,Reach-1         , 5
Up Type= 0
Dn Type= 3
Dn Slope=0.00313
Boundary for River Rch & Prof#=NUBIA CREEK,Reach-1         , 6
Up Type= 0
Dn Type= 3
Dn Slope=0.00313
Boundary for River Rch & Prof#=NUBIA CREEK,Reach-1         , 7
Up Type= 0
Dn Type= 3
Dn Slope=0.00313
DSS Import GetInterval= 0
DSS Import GetPeak= 0
DSS Import FillOption= 0

--- NUBIA CREEK.g01 (geometry) ---

Geom Title=Existing Conditions
Program Version=4.10

River Reach=NUBIA CREEK     ,Reach-1
Reach XY= 30
        1477305.        6796638.      1480341.61      6799224.67
      1482804.23      6803048.69      1482162.53      6805738.01
      1481904.68      6809463.11      1482296.95      6810041.32
      1480555.01      6811808.21      1481053.78       6812398.5
      1480958.36      6814336.75       1481704.5      6814803.22
      1481006.95      6815844.26      1481210.46      6817190.45
      1481660.89      6817736.03      1483300.26      6817743.62
      1483174.77      6819258.13      1484460.89      6820286.04
      1485411.17      6819795.86      1486053.08      6820349.95
      1485818.37      6821101.32      1487352.55      6822132.54
      1488470.19      6821687.47      1489165.05      6822148.63
      1489554.62      6822872.84      1489018.35      6823401.34
      1489715.24      6823398.34      1489534.79      6823968.41
      1490861.17      6824295.86       1490771.4      6824904.83
      1491607.55      6824843.05        1492205.        6825738.

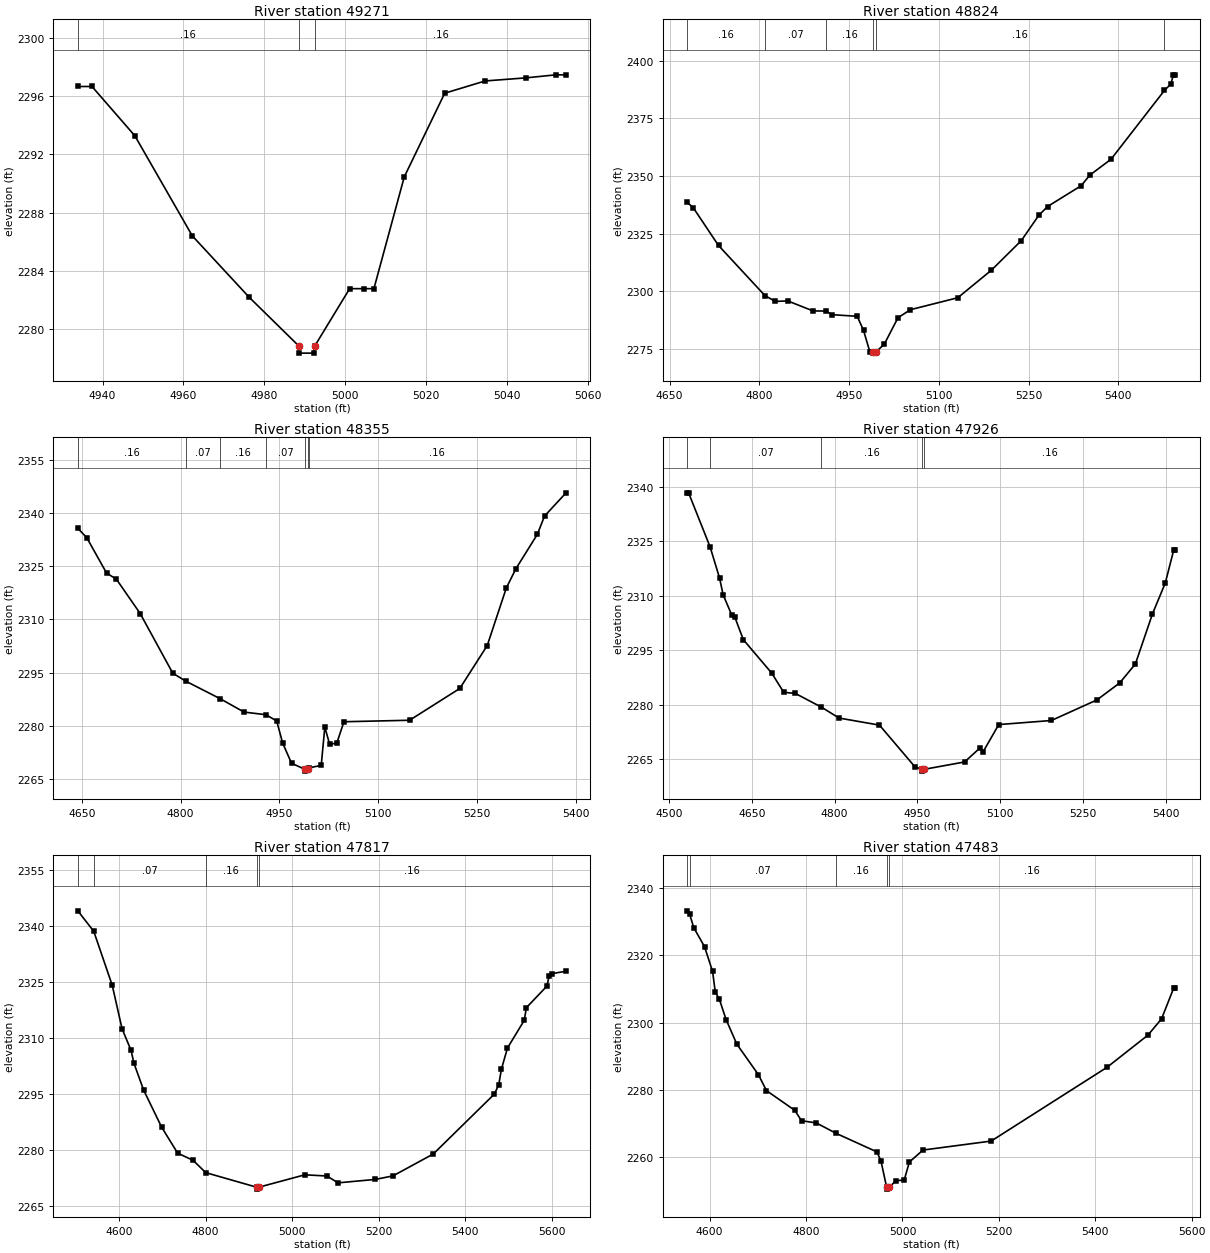
Type RM Length L Ch R = 1 ,49271   ,447,447,447
BEGIN DESCRIPTION:
NUBIA CREEK 81.0
END DESCRIPTION:
XS GIS Cut Line= 3
      1477355.01      6796837.99        1477405.        6796788.
      1477455.01        6796788.
#Sta/Elev= 18
  4933.9 2296.66  4937.4 2296.66    4948 2293.28  4962.2 2286.42  4976.3  2282.2
  4988.5 2278.88  4988.7 2278.38  4992.2 2278.38  4992.5 2278.88  5001.1  2282.8
  5004.6  2282.8  5007.1  2282.8  5014.6 2290.46  5024.6  2296.2  5034.6 2297.04
  5044.6 2297.25  5052.1 2297.46  5054.6 2297.46
#Mann= 3 ,-1 , 0
  4933.9     .16       0  4988.5     .07       0  4992.5     .16       0
Bank Sta=4988.5,4992.5
XS Rating Curve= 0 ,0
Exp/Cntr=0.3,0.1

Type RM Length L Ch R = 1 ,48824   ,469,469,469
BEGIN DESCRIPTION:
NUBIA CREEK 80.0
END DESCRIPTION:
XS GIS Cut Line= 3
      1477555.01      6797387.98        1477655.        6797088.
        1477955.        6796688.
#Sta/Elev= 30
    4679 2338.66  4689.5 2336.25  4731.7 2319.89  4809.2 2298.21  4826.5 2295.67
  4847.6 2295.86  4889.8 2291.53  4911.5 2291.49  4921.4 2289.92  4963.6  2289.2
  4974.1 2283.13  4984.7 2273.83  4990.6 2273.75  4990.8 2273.25  4994.6 2273.75
  5008.7 2277.05  5031.7 2288.58  5052.5 2292.07  5131.7 2297.25  5187.9 2309.19
  5237.9 2322.01  5267.1 2332.95  5281.7 2336.76  5337.9 2345.79  5352.5  2350.4
  5387.9 2357.27  5477.2 2387.09  5487.9 2389.87  5492.1 2393.85  5495.2 2393.85
#Mann= 6 ,-1 , 0
    4679     .16       0  4809.2     .07       0  4911.5     .16       0
  4990.6     .07       0  4994.6     .16       0  5477.2     .07       0
Bank Sta=4990.6,4994.6
XS Rating Curve= 0 ,0
Exp/Cntr=0.3,0.1

Type RM Length L Ch R = 1 ,48355   ,429,429,429
BEGIN DESCRIPTION:
NUBIA CREEK 79.0
END DESCRIPTION:
XS GIS Cut Line= 3
      1477704.98      6797588.01        1478005.        6797388.
      1478155.01      6797037.97
#Sta/Elev= 30
  4643.9 2335.67  4657.4 2333.06  4687.5 2323.07  4702.5 2321.32  4738.6 2311.64
  4788.1 2294.81  4808.3 2292.52  4859.8 2287.64  4896.3 2283.85  4929.6  2283.1
  4945.9 2281.34  4954.9 2275.13  4968.4 2269.42  4988.9 2267.69  4989.2 2267.19
    4993 2267.69  4994.2 2268.09  5013.5 2268.81    5019 2279.64  5026.2 2274.81
  5037.1 2275.05    5048 2281.12  5147.7 2281.54  5223.9  2290.5  5265.6 2302.61
  5294.6 2318.86  5309.1 2324.26  5341.7 2333.98  5352.6 2339.13  5385.3 2345.69
#Mann= 7 ,-1 , 0
  4643.9     .16       0  4808.3     .07       0  4859.8     .16       0
  4929.6     .07       0  4988.9     .07       0    4993     .07       0
  4994.2     .16       0
Bank Sta=4988.9,4993
XS Rating Curve= 0 ,0
Exp/Cntr=0.3,0.1

Type RM Length L Ch R = 1 ,47926   ,109,109,109
BEGIN DESCRIPTION:
NUBIA CREEK 78.0
END DESCRIPTION:
XS GIS Cut Line= 3
        1478105.        6797938.        1478355.        6797538.
        1478255.      6797138.01
#Sta/Elev= 30
  4532.7 2338.29  4535.6 2338.29  4574.6 2323.39  4591.7 2314.85  4598.1 2310.28
  4613.5 2304.78  4619.4 2304.08  4634.7 2297.92    4686 2288.75  4707.8 2283.46
    4729 2283.13  4776.2 2279.36  4808.1 2276.37  4881.2 2274.43  4945.4 2262.97
  4958.1 2262.28  4958.4 2261.78  4962.2 2262.28  5035.3  2264.3  5063.7 2268.22
  5068.8 2267.07  5097.2 2274.58  5192.5  2275.7    5275 2281.36  5316.2 2286.03
  5344.6 2291.24  5375.5 2305.01  5398.7 2313.49  5414.1 2322.63  5416.7 2322.63
#Mann= 5 ,-1 , 0
  4532.7     .16       0  4574.6     .07       0  4776.2     .16       0
  4958.1     .07       0  4962.2     .16       0
Bank Sta=4958.1,4962.2
XS Rating Curve= 0 ,0
Exp/Cntr=0.3,0.1

Type RM Length L Ch R = 1 ,47817   ,334,334,334
BEGIN DESCRIPTION:
Mapping XS 167f0333
END DESCRIPTION:
XS GIS Cut Line= 4
      1478135.18       6798010.7      1478425.98      6797633.09
      1478443.34      6797583.18      1478332.66      6796995.06
#Sta/Elev= 30
  4504.7 2344.08  4541.5  2338.6  4584.2 2324.16  4606.9 2312.52  4627.7 2306.75
  4634.3 2303.32  4656.7 2296.14  4698.3 2286.22  4735.3 2279.26  4770.8 2277.36
  4800.2 2274.05  4918.3 2270.14  4918.5 2269.64  4922.4 2270.14  5029.1 2273.47
  5080.1 2273.15  5105.9 2271.32  5192.1 2272.24  5232.8 2273.18    5326 2279.05
  5466.8 2295.04    5477 2297.51  5483.4 2301.77  5497.3  2307.4  5535.9 2314.76
    5541 2318.18  5588.4 2323.95  5593.5 2326.66  5599.1 2327.26  5632.6 2327.93
#Mann= 5 ,-1 , 0
  4504.7     .16       0  4541.5     .07       0  4800.2     .16       0
  4918.3     .07       0  4922.4     .16       0
Bank Sta=4918.3,4922.4
XS Rating Curve= 0 ,0
Exp/Cntr=0.3,0.1

Type RM Length L Ch R = 1 ,47483   ,495,495,495
BEGIN DESCRIPTION:
NUBIA CREEK 77.0
END DESCRIPTION:
XS GIS Cut Line= 3
      1478254.99      6798038.01        1478655.        6797838.
      1479054.99      6797438.01
#Sta/Elev= 30
    4553 2333.32  4558.4 2332.38    4567 2328.31  4589.4 2322.62  4606.1 2315.23
  4611.7 2309.02  4620.1 2306.97  4634.1 2300.88  4656.4 2293.55  4701.2 2284.42
  4717.9 2279.68  4776.6  2273.8  4790.6  2270.7  4821.3 2270.04  4862.1 2266.95
  4947.1 2261.39  4955.5 2258.63  4967.3 2250.79  4967.6 2250.29  4971.7 2250.79
  4986.3 2252.73  5003.8 2253.07  5014.4 2258.38  5042.7 2261.95  5184.1 2264.63
  5424.5 2286.64  5509.3 2296.24  5537.6  2301.1  5562.4 2310.15  5565.9 2310.15
#Mann= 5 ,-1 , 0
    4553     .16       0  4558.4     .07       0  4862.1     .16       0
  4967.3     .07       0  4971.7     .16       0
Bank Sta=4967.3,4971.7
XS Rating Curve= 0 ,0
Exp/Cntr=0.3,0.1

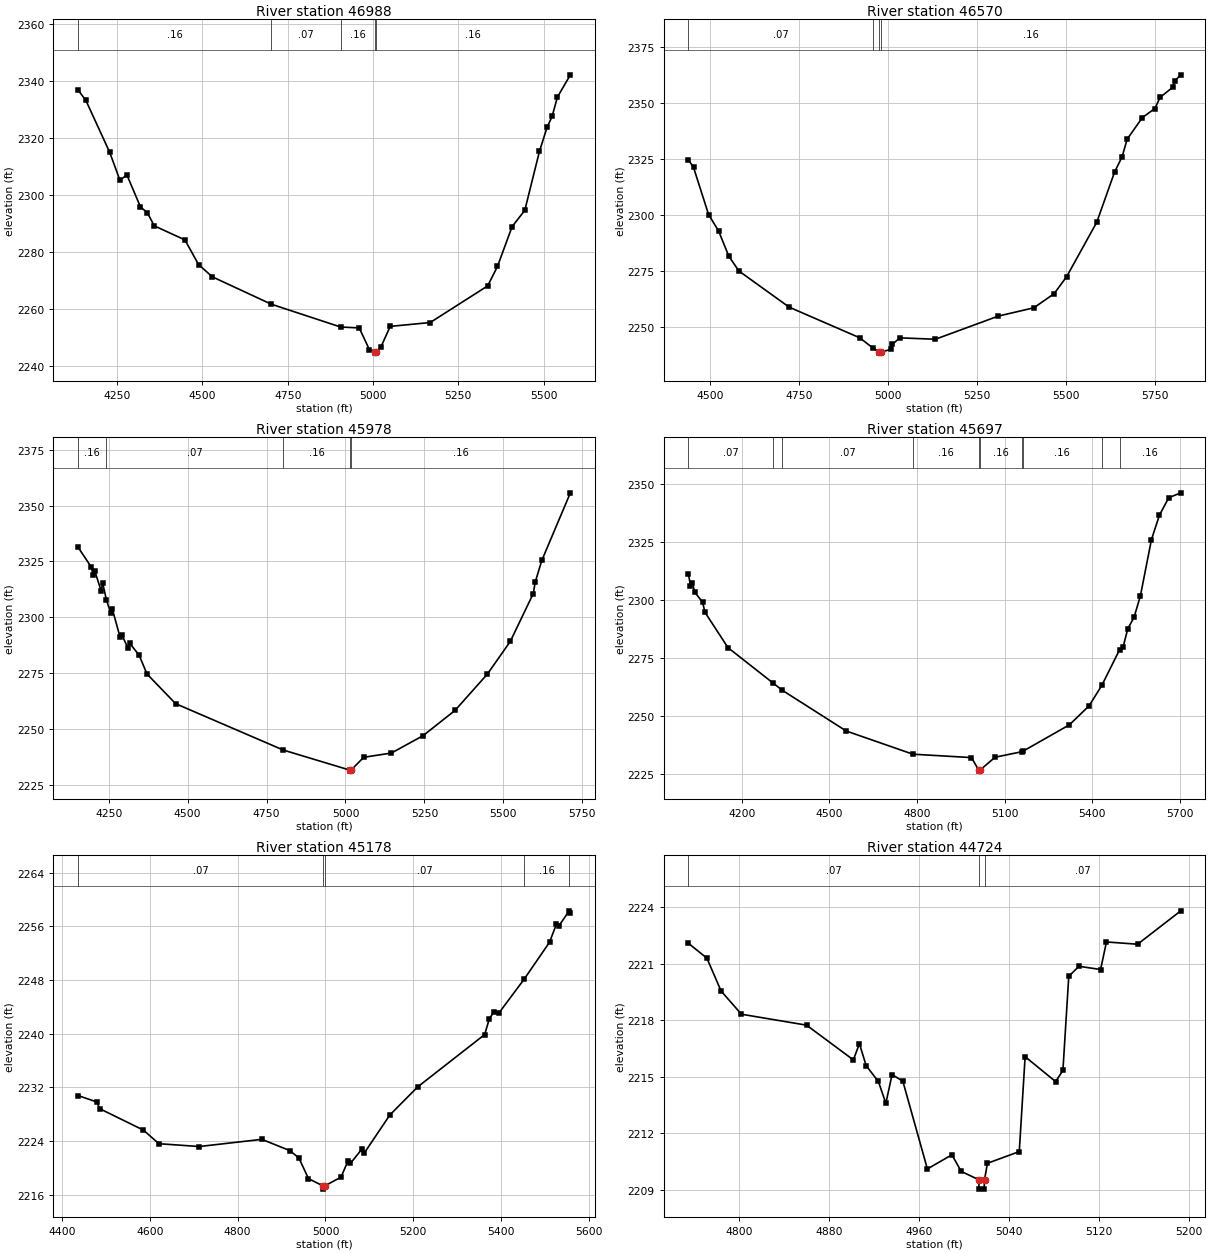
Type RM Length L Ch R = 1 ,46988   ,418,418,418
BEGIN DESCRIPTION:
NUBIA CREEK 76.0
END DESCRIPTION:
XS GIS Cut Line= 3
      1478142.25      6798241.02        1479005.        6798188.
      1479298.46      6797688.97
#Sta/Elev= 30
  4135.4 2336.74  4158.2 2333.14  4228.3 2314.85  4258.4    2305  4278.4 2306.99
  4318.5 2295.68  4338.5 2293.72  4358.6 2289.08  4448.7 2284.12  4488.8 2275.47
  4528.9 2271.17  4701.7 2261.56  4905.4 2253.53  4959.7 2253.22  4989.8 2245.54
  5005.4 2244.87  5005.7 2244.37  5009.8 2244.87    5023 2246.44  5050.5 2253.76
  5167.7 2255.11  5336.2 2267.97    5365 2274.81  5407.9  2288.8    5445 2294.48
    5488 2315.18  5510.2  2323.6  5525.1 2327.46  5540.8 2334.29  5578.7 2342.08
#Mann= 5 ,-1 , 0
  4135.4     .16       0  4701.7     .07       0  4905.4     .16       0
  5005.4     .07       0  5009.8     .16       0
Bank Sta=5005.4,5009.8
XS Rating Curve= 0 ,0
Exp/Cntr=0.3,0.1

Type RM Length L Ch R = 1 ,46570   ,592,592,592
BEGIN DESCRIPTION:
NUBIA CREEK 75.0
END DESCRIPTION:
XS GIS Cut Line= 3
      1478804.98      6798938.02        1479205.        6798538.
      1479824.54      6798005.12
#Sta/Elev= 30
  4438.8 2324.66    4453 2321.28  4495.4 2300.15  4523.7 2292.73    4552 2281.58
  4580.3 2274.93  4721.7 2258.72  4919.7 2245.03  4957.6 2240.36  4973.7 2238.65
  4974.1 2238.15  4978.8 2238.65  5007.8  2239.8  5011.6  2242.1  5032.5 2244.99
  5132.3 2244.36    5309 2254.72  5408.9 2258.43  5465.9 2264.75    5501 2272.36
  5585.5 2296.67    5636 2319.31  5656.8 2325.98  5671.1 2333.92  5713.9 2343.59
    5749 2347.62  5763.3 2352.56  5798.4 2357.05  5806.1 2360.15  5821.7 2362.69
#Mann= 4 ,-1 , 0
  4438.8     .07       0  4957.6     .16       0  4973.7     .07       0
  4978.8     .16       0
Bank Sta=4973.7,4978.8
XS Rating Curve= 0 ,0
Exp/Cntr=0.3,0.1

Type RM Length L Ch R = 1 ,45978   ,281,281,281
BEGIN DESCRIPTION:
NUBIA CREEK 74.0
END DESCRIPTION:
XS GIS Cut Line= 3
      1478795.84      6799070.24      1479588.45      6798771.04
       1479970.2      6798169.44
#Sta/Elev= 30
  4152.8 2331.38  4194.7 2322.54  4200.8 2318.75  4206.2 2320.58  4225.7 2311.98
    4231 2315.17  4242.9 2307.66  4255.8 2302.09  4261.2  2303.8    4286 2291.04
  4291.4 2292.16  4310.9 2286.19  4316.2  2288.4  4346.4 2282.97  4371.3 2274.56
  4461.9 2261.27  4803.1 2240.48  5012.8 2231.54  5013.2 2231.04    5018 2231.54
  5057.9 2237.24  5145.7 2239.15    5246 2246.95  5347.1 2258.25  5449.3 2274.48
  5522.1 2289.15    5595 2310.64  5600.9 2315.63  5622.1  2325.5  5712.5 2355.76
#Mann= 5 ,-1 , 0
  4152.8     .16       0  4242.9     .07       0  4803.1     .16       0
  5012.8     .07       0    5018     .16       0
Bank Sta=5012.8,5018
XS Rating Curve= 0 ,0
Exp/Cntr=0.3,0.1

Type RM Length L Ch R = 1 ,45697   ,519,519,519
BEGIN DESCRIPTION:
NUBIA CREEK 73.0
END DESCRIPTION:
XS GIS Cut Line= 3
      1479203.89      6799716.03        1479805.        6798938.
       1480148.3      6798323.72
#Sta/Elev= 30
  4016.8 2311.15  4023.7 2306.05    4030 2307.35  4038.2 2303.32  4065.3 2298.88
  4073.5 2294.58  4152.3 2279.39  4305.2  2264.3  4338.7 2261.01  4557.7 2243.49
  4785.8 2233.52  4986.4 2232.06  5011.1 2226.73  5011.5 2226.23  5016.3 2226.73
  5067.4 2232.22  5160.3 2234.61  5162.2 2234.75  5322.1 2246.17  5389.5 2254.35
    5433 2263.13  5493.7 2278.42    5506 2279.65    5522 2287.53  5543.7 2292.47
  5565.4 2301.77  5603.1 2325.89  5630.5 2336.43  5662.4 2343.94  5703.7 2346.05
#Mann= 10 ,-1 , 0
  4016.8     .07       0  4305.2     .16       0  4338.7     .07       0
  4785.8     .16       0  5011.1     .07       0  5016.3     .16       0
  5160.3     .07       0  5162.2     .16       0    5433     .07       0
  5493.7     .16       0
Bank Sta=5011.1,5016.3
XS Rating Curve= 0 ,0
Exp/Cntr=0.3,0.1

Type RM Length L Ch R = 1 ,45178   ,454,454,454
BEGIN DESCRIPTION:
NUBIA CREEK 72.0
END DESCRIPTION:
XS GIS Cut Line= 3
        1479880.        6799563.      1480253.52      6799141.61
        1480430.      6798612.99
#Sta/Elev= 30
  4436.9 2230.79  4479.6 2229.83  4486.2 2228.83  4585.8 2225.63  4620.9 2223.61
  4712.9 2223.19  4855.1 2224.26  4918.6 2222.59  4939.5 2221.49  4961.3  2218.4
  4993.8 2217.34  4994.2 2216.84    4999 2217.34  5035.4 2218.63  5051.6  2221.1
  5056.9 2220.69  5083.3 2222.84  5088.5 2222.24  5146.5 2227.89  5209.7 2232.07
  5362.3 2239.88  5372.9 2242.24  5383.3 2243.26  5393.9 2243.02  5452.4 2248.16
  5509.8 2253.63  5525.7 2256.36    5531 2256.06  5554.7 2258.32  5557.3 2258.05
#Mann= 5 ,-1 , 0
  4436.9     .07       0  4993.8     .07       0    4999     .07       0
  5452.4     .16       0  5554.7     .07       0
Bank Sta=4993.8,4999
XS Rating Curve= 0 ,0
Exp/Cntr=0.3,0.1

Type RM Length L Ch R = 1 ,44724   ,379,379,379
BEGIN DESCRIPTION:
Mapping XS d144507b
END DESCRIPTION:
XS GIS Cut Line= 3
      1480229.96      6799613.02       1480455.2      6799515.84
      1480508.87      6799331.08
#Sta/Elev= 30
  4754.7 2222.08  4771.1 2221.29  4783.7 2219.55  4801.8 2218.32  4859.7 2217.74
  4901.3  2215.9  4906.7 2216.76  4912.7 2215.59  4923.5 2214.76  4930.2  2213.6
  4935.7 2215.12  4945.3 2214.77  4967.1 2210.12  4988.9 2210.87  4997.2 2209.99
  5012.7 2209.55  5013.1 2209.05  5017.5 2209.05  5017.9 2209.55  5020.5 2210.42
  5048.8 2211.04    5054 2216.07  5081.1 2214.75  5087.6 2215.34  5092.8 2220.33
  5101.9 2220.86  5121.1 2220.69  5126.3 2222.15    5154 2222.03  5192.4  2223.8
#Mann= 3 ,-1 , 0
  4754.7     .07       0  5012.7     .07       0  5017.9     .07       0
Bank Sta=5012.7,5017.9
XS Rating Curve= 0 ,0
Exp/Cntr=0.3,0.1

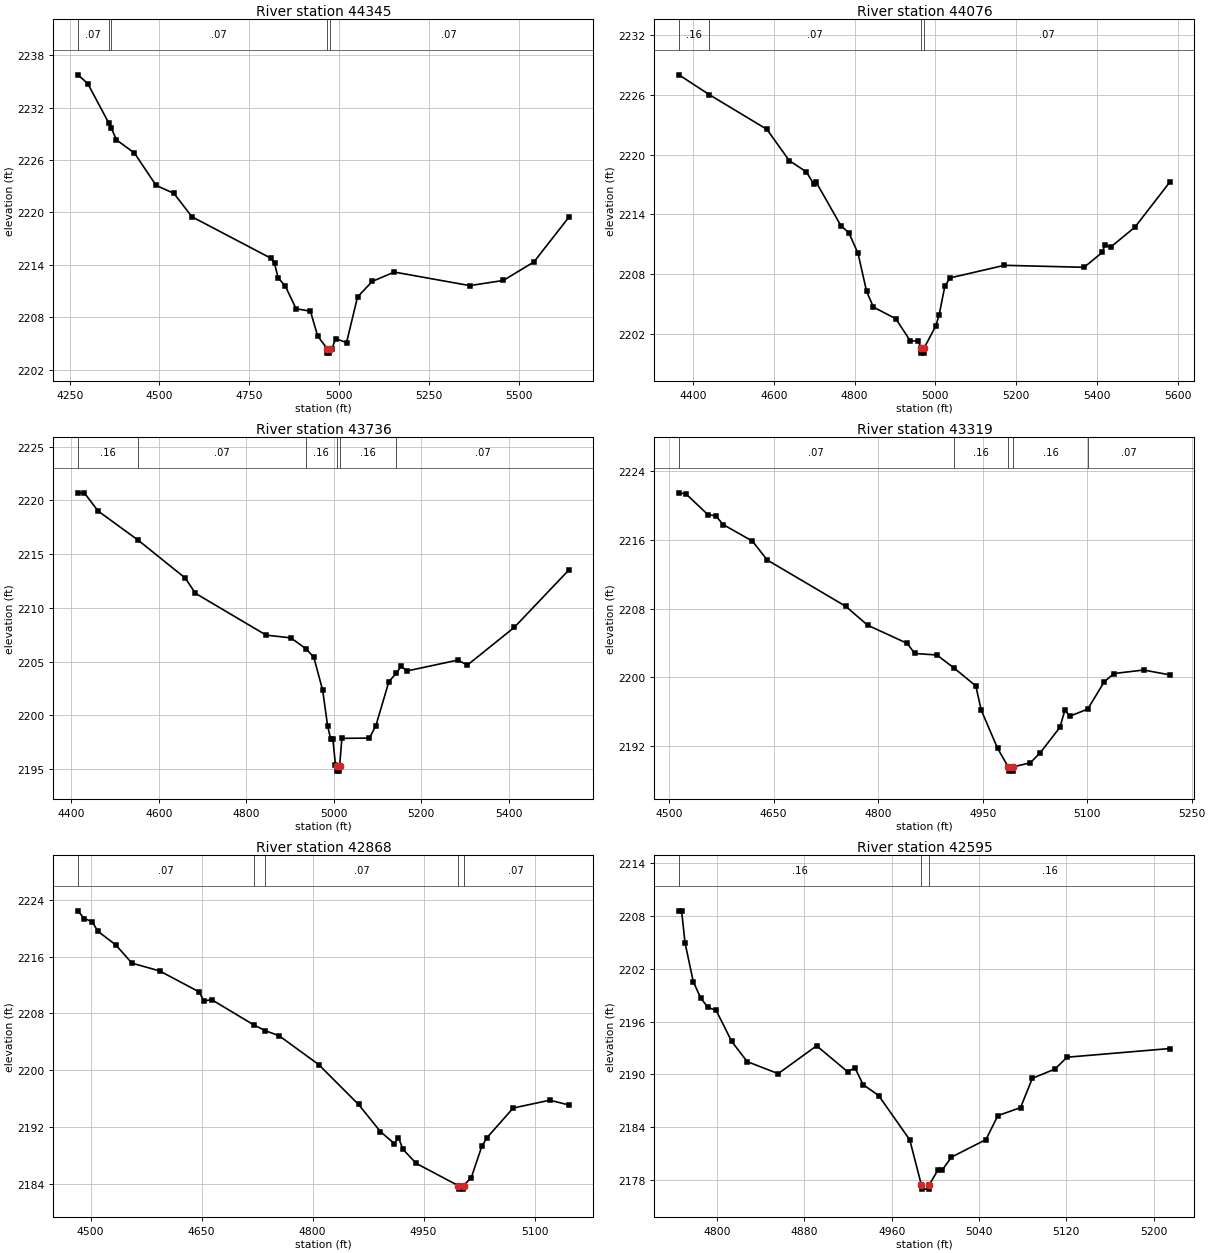
Type RM Length L Ch R = 1 ,44345   ,269,269,269
BEGIN DESCRIPTION:
Mapping XS fa433fd0
END DESCRIPTION:
XS GIS Cut Line= 3
      1479827.75      6799858.32      1480555.22      6799860.06
      1481180.15      6799724.66
#Sta/Elev= 30
  4273.2 2235.76  4300.4 2234.76  4358.4 2230.29  4365.4 2229.72  4380.4 2228.31
  4430.4 2226.81  4490.5 2223.11  4540.5 2222.18  4590.5 2219.51  4810.5 2214.76
  4820.5 2214.17  4830.5 2212.52  4850.5 2211.57  4880.5 2208.98  4920.5  2208.7
  4940.5 2205.86  4967.3  2204.4  4967.8  2203.9  4973.2  2203.9  4973.7  2204.4
  4980.5 2204.41  4990.5 2205.57  5020.9  2205.1  5051.6 2210.33  5092.5 2212.11
  5153.9 2213.18  5364.1 2211.63  5457.4 2212.22  5542.7 2214.34  5640.1 2219.47
#Mann= 5 ,-1 , 0
  4273.2     .07       0  4358.4     .16       0  4365.4     .07       0
  4967.3     .07       0  4973.7     .07       0
Bank Sta=4967.3,4973.7
XS Rating Curve= 0 ,0
Exp/Cntr=0.3,0.1

Type RM Length L Ch R = 1 ,44076   ,340,340,340
BEGIN DESCRIPTION:
Mapping XS e0dc7c76
END DESCRIPTION:
XS GIS Cut Line= 3
      1480098.66      6800299.28      1480687.16      6800083.15
      1481200.06      6799793.02
#Sta/Elev= 30
  4364.8 2228.01    4440 2226.02  4582.7 2222.54  4637.9 2219.41  4680.5 2218.27
  4699.3 2217.01  4704.6 2217.25  4765.7 2212.89  4785.4 2212.18  4808.3 2210.11
  4829.6 2206.29  4846.4 2204.71    4902 2203.54  4937.8 2201.32  4957.5  2201.3
  4964.8 2200.59  4965.3 2200.09  4971.4 2200.09  4971.9 2200.59  5000.7 2202.79
  5009.4 2203.93  5023.7 2206.87  5036.8 2207.64  5171.1  2208.9  5368.4  2208.7
  5413.6  2210.2  5419.3 2210.89  5435.2 2210.76  5494.4 2212.73    5581 2217.26
#Mann= 4 ,-1 , 0
  4364.8     .16       0    4440     .07       0  4964.8     .07       0
  4971.9     .07       0
Bank Sta=4964.8,4971.9
XS Rating Curve= 0 ,0
Exp/Cntr=0.3,0.1

Type RM Length L Ch R = 1 ,43736   ,417,417,417
BEGIN DESCRIPTION:
Mapping XS 017ce6a3
END DESCRIPTION:
XS GIS Cut Line= 3
      1480351.24      6800512.83      1480903.31      6800338.36
       1481213.2      6799893.05
#Sta/Elev= 30
  4415.6 2220.68    4430  2220.7  4461.5 2219.01    4553  2216.3  4660.8 2212.77
  4683.7 2211.36  4845.4 2207.47    4902 2207.21  4936.5  2206.2  4954.4  2205.4
  4974.7 2202.32  4985.9    2199  4992.8 2197.83  4997.8 2197.83  5003.7 2195.42
  5006.2 2195.32  5006.7 2194.82  5012.8 2194.82  5013.3 2195.32  5018.5 2197.87
  5081.4 2197.89  5096.2 2199.06  5125.9 2203.15  5142.5 2203.91  5153.4 2204.56
  5167.8 2204.14  5283.9 2205.15  5304.8 2204.67  5412.1 2208.18  5537.1 2213.53
#Mann= 6 ,-1 , 0
  4415.6     .16       0    4553     .07       0  4936.5     .16       0
  5006.2     .07       0  5013.3     .16       0  5142.5     .07       0
Bank Sta=5006.2,5013.3
XS Rating Curve= 0 ,0
Exp/Cntr=0.3,0.1

Type RM Length L Ch R = 1 ,43319   ,451,451,451
BEGIN DESCRIPTION:
Mapping XS 688efb05
END DESCRIPTION:
XS GIS Cut Line= 3
      1480645.46      6800812.33      1481109.04      6800650.86
      1481262.66      6800502.44
#Sta/Elev= 30
  4514.2 2221.51  4524.3 2221.38  4556.1 2218.94  4566.7 2218.85  4577.8  2217.8
  4619.6 2215.88  4640.8 2213.68  4753.7 2208.27  4784.8 2206.08  4841.6 2203.96
  4852.6 2202.78  4884.3  2202.6  4908.4 2201.12  4940.2 2198.99  4947.9 2196.18
  4971.3 2191.74  4986.6 2189.56  4987.1 2189.06  4993.3 2189.06  4993.8 2189.56
  5018.4 2190.03  5032.5 2191.19  5060.8 2194.16    5068 2196.17    5075 2195.46
  5100.8  2196.3  5124.6 2199.49  5138.5 2200.44    5181 2200.85  5218.7 2200.28
#Mann= 5 ,-1 , 0
  4514.2     .07       0  4908.4     .16       0  4986.6     .07       0
  4993.8     .16       0  5100.8     .07       0
Bank Sta=4986.6,4993.8
XS Rating Curve= 0 ,0
Exp/Cntr=0.3,0.1

Type RM Length L Ch R = 1 ,42868   ,273,273,273
BEGIN DESCRIPTION:
Mapping XS ee8db3b6
END DESCRIPTION:
XS GIS Cut Line= 3
      1480877.27      6801163.88      1481351.22      6800973.78
      1481457.99      6800864.41
#Sta/Elev= 30
    4483 2222.42  4491.3 2221.33  4502.1 2220.91  4509.9 2219.55  4534.1 2217.63
    4556 2215.07  4593.3 2213.98    4647 2211.02  4652.9 2209.76  4663.7 2209.94
  4720.4 2206.41  4736.4 2205.57  4754.6 2204.89  4808.4 2200.82  4862.2 2195.22
  4891.8 2191.41  4910.7 2189.71    4916 2190.58  4922.3 2188.91  4940.2 2186.94
  4996.8 2183.83  4997.3 2183.33  5003.6 2183.33  5004.1 2183.83  5014.6 2184.96
  5028.8 2189.35  5035.8 2190.57  5071.2 2194.72  5120.6 2195.82  5146.5 2195.15
#Mann= 5 ,-1 , 0
    4483     .07       0  4720.4     .16       0  4736.4     .07       0
  4996.8     .07       0  5004.1     .07       0
Bank Sta=4996.8,5004.1
XS Rating Curve= 0 ,0
Exp/Cntr=0.3,0.1

Type RM Length L Ch R = 1 ,42595   ,539,539,539
BEGIN DESCRIPTION:
Mapping XS f2da9fd0
END DESCRIPTION:
XS GIS Cut Line= 3
      1481325.19      6801346.17      1481505.74      6801186.45
      1481571.72      6800988.51
#Sta/Elev= 30
  4765.2  2208.6  4767.6  2208.6  4770.8 2204.94  4778.3 2200.55    4785 2198.71
  4791.7  2197.6  4799.2 2197.29  4813.5 2193.74  4827.7 2191.44  4856.1 2190.07
  4891.3 2193.24  4919.7 2190.29  4926.4 2190.73  4933.9 2188.82  4948.1 2187.58
  4976.6 2182.54  4987.2 2177.43  4987.7 2176.93    4994 2176.93  4994.5 2177.43
  5002.4  2179.1  5006.3  2179.1  5014.8 2180.57  5046.4 2182.57  5057.3 2185.29
  5078.1 2186.21  5088.9 2189.54  5109.7  2190.6  5120.6 2191.94  5214.9 2192.93
#Mann= 3 ,-1 , 0
  4765.2     .16       0  4987.2     .07       0  4994.5     .16       0
Bank Sta=4987.2,4994.5
XS Rating Curve= 0 ,0
Exp/Cntr=0.3,0.1

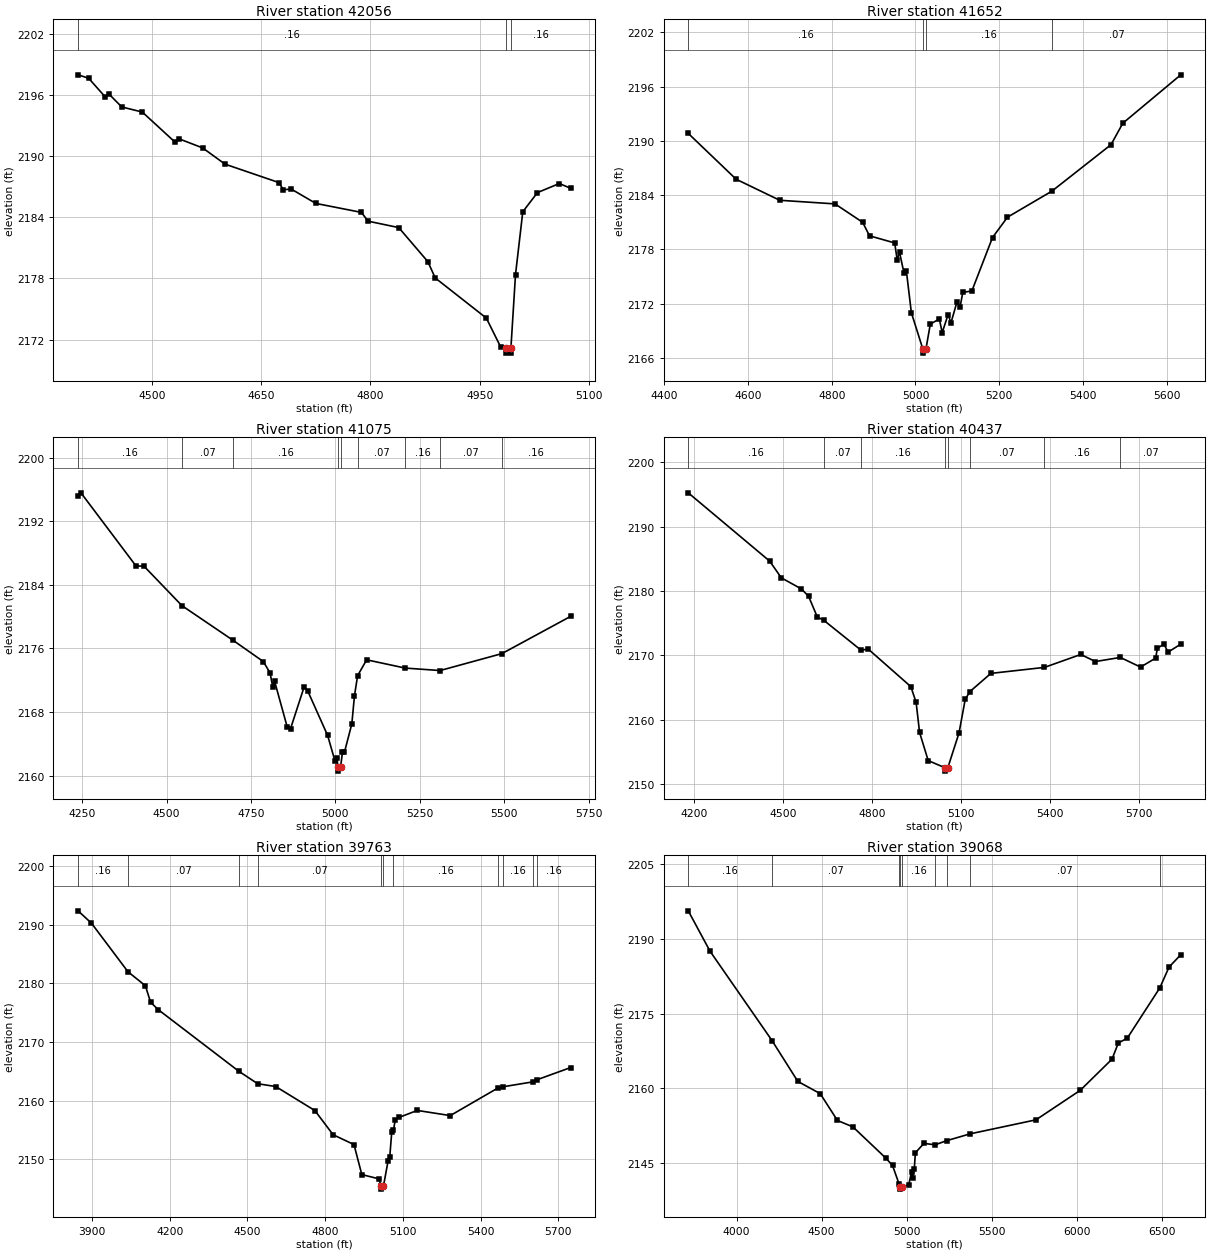
Type RM Length L Ch R = 1 ,42056   ,404,404,404
BEGIN DESCRIPTION:
Mapping XS 9776cbb3
END DESCRIPTION:
XS GIS Cut Line= 3
      1481520.46      6801610.94        1481880.      6801439.92
      1481898.07      6801162.55
#Sta/Elev= 30
  4398.7 2197.97  4413.2 2197.64  4435.9 2195.81  4441.5 2196.06  4458.7 2194.82
  4486.9 2194.32  4532.3 2191.34  4537.9 2191.68  4569.8  2190.8  4600.5 2189.21
  4674.2 2187.41  4680.6  2186.7  4691.3 2186.77  4725.1 2185.36  4787.7 2184.48
  4796.8 2183.62  4838.9 2182.99  4878.9 2179.65    4889 2178.05  4959.1 2174.12
  4979.1 2171.25  4985.5 2171.18    4986 2170.68  4992.4 2170.68  4992.9 2171.18
  4999.2 2178.38  5009.2 2184.54  5029.3 2186.42  5059.3 2187.31  5074.8 2186.85
#Mann= 3 ,-1 , 0
  4398.7     .16       0  4985.5     .07       0  4992.9     .16       0
Bank Sta=4985.5,4992.9
XS Rating Curve= 0 ,0
Exp/Cntr=0.3,0.1

Type RM Length L Ch R = 1 ,41652   ,577,577,577
BEGIN DESCRIPTION:
Mapping XS 8938710c
END DESCRIPTION:
XS GIS Cut Line= 3
      1481689.27      6801756.67      1482160.18      6801507.11
      1482596.34      6801034.05
#Sta/Elev= 30
  4457.3 2190.83  4571.6 2185.76  4675.9 2183.43  4807.9 2183.03  4873.9 2180.99
  4890.2  2179.5  4950.4 2178.71  4956.2 2176.86  4961.9 2177.68  4972.5 2175.39
  4978.2 2175.64  4990.2 2170.99  5017.3 2167.02  5017.8 2166.52  5025.2 2167.02
  5035.4 2169.73    5057  2170.3  5063.8 2168.79    5078 2170.79  5084.8 2169.87
    5099 2172.17  5106.3 2171.58  5113.1 2173.24  5134.7  2173.4    5184 2179.31
  5219.8 2181.56  5325.8 2184.44    5467 2189.58  5495.3 2191.96  5633.7 2197.31
#Mann= 4 ,-1 , 0
  4457.3     .16       0  5017.3     .07       0  5025.2     .16       0
  5325.8     .07       0
Bank Sta=5017.3,5025.2
XS Rating Curve= 0 ,0
Exp/Cntr=0.3,0.1

Type RM Length L Ch R = 1 ,41075   ,638,638,638
BEGIN DESCRIPTION:
Mapping XS 2758cef8
END DESCRIPTION:
XS GIS Cut Line= 3
      1481600.24       6802103.9       1482340.3      6802012.75
       1482969.6       6801676.4
#Sta/Elev= 30
  4237.5 2195.21  4246.1 2195.56  4408.5  2186.4  4433.7  2186.3  4545.3 2181.37
  4696.8 2177.01  4786.4 2174.34  4806.5  2172.9  4814.5 2171.09  4819.6 2171.89
  4856.9 2166.16    4867 2165.89  4907.3 2171.15  4917.4  2170.7  4976.9 2165.05
    4999 2161.79  5004.7 2162.25  5007.2 2161.06  5007.7 2160.56  5015.2 2161.06
  5020.9 2162.92  5026.6 2162.91  5048.6  2166.5  5056.5 2170.06  5065.8 2172.57
  5092.5 2174.56  5206.7 2173.52    5310 2173.21  5493.3 2175.34  5696.7 2180.02
#Mann= 9 ,-1 , 0
  4237.5     .16       0  4545.3     .07       0  4696.8     .16       0
  5007.2     .07       0  5015.2     .16       0  5065.8     .07       0
  5206.7     .16       0    5310     .07       0  5493.3     .16       0
Bank Sta=5007.2,5015.2
XS Rating Curve= 0 ,0
Exp/Cntr=0.3,0.1

Type RM Length L Ch R = 1 ,40437   ,674,674,674
BEGIN DESCRIPTION:
Mapping XS ce781d39
END DESCRIPTION:
XS GIS Cut Line= 3
       1481585.1      6802836.53      1482335.09      6802529.24
       1483031.5      6802045.92
#Sta/Elev= 30
  4181.5 2195.24  4455.8 2184.62  4494.8 2182.03  4562.6  2180.3  4586.6 2179.16
  4615.9 2175.95    4637 2175.46  4763.9 2170.76  4786.6 2170.99  4930.9 2165.12
  4948.7 2162.66  4960.3    2158  4989.3 2153.63    5047 2152.49  5047.5 2151.99
  5055.2 2152.49    5093 2157.91  5113.9 2163.13  5129.9 2164.36  5200.4 2167.18
  5380.6 2168.11  5503.1 2170.12  5552.3 2169.02  5636.1 2169.66  5704.2 2168.16
  5754.9 2169.55    5761 2171.08  5783.1 2171.74  5796.8 2170.48  5839.7 2171.73
#Mann= 8 ,-1 , 0
  4181.5     .16       0    4637     .07       0  4763.9     .16       0
    5047     .07       0  5055.2     .16       0  5129.9     .07       0
  5380.6     .16       0  5636.1     .07       0
Bank Sta=5047,5055.2
XS Rating Curve= 0 ,0
Exp/Cntr=0.3,0.1

Type RM Length L Ch R = 1 ,39763   ,695,695,695
BEGIN DESCRIPTION:
Mapping XS 3779ea9d
END DESCRIPTION:
XS GIS Cut Line= 3
       1481626.8      6803138.61      1482767.38      6803008.41
      1483335.13      6802513.59
#Sta/Elev= 30
    3846 2192.34  3897.5 2190.25  4038.7 2181.96  4105.9 2179.58    4126 2176.76
  4155.6  2175.5    4467 2164.99  4539.3 2162.88  4609.1  2162.4  4760.1 2158.31
  4830.5 2154.19  4911.1 2152.51  4941.3  2147.4  5006.5 2146.68  5016.6 2145.42
  5017.1 2144.92  5024.8 2145.42  5042.6  2149.7  5049.2 2150.42  5056.8 2154.63
  5063.6    2155  5070.4 2156.75  5084.3 2157.13  5155.5 2158.33  5282.7 2157.45
  5466.6 2162.15  5486.3 2162.36  5600.6 2163.19    5617 2163.55  5747.1 2165.63
#Mann= 11 ,-1 , 0
    3846     .16       0  4038.7     .07       0    4467     .16       0
  4539.3     .07       0  5016.6     .07       0  5024.8     .07       0
  5063.6     .16       0  5466.6     .07       0  5486.3     .16       0
  5600.6     .07       0    5617     .16       0
Bank Sta=5016.6,5024.8
XS Rating Curve= 0 ,0
Exp/Cntr=0.3,0.1

Type RM Length L Ch R = 1 ,39068   ,1071,1071,1071
BEGIN DESCRIPTION:
Mapping XS 6a11743c
END DESCRIPTION:
XS GIS Cut Line= 3
      1481538.33      6803480.28      1482781.35      6803667.77
      1484246.66      6802938.59
#Sta/Elev= 30
  3716.5 2195.65  3844.6 2187.53  4208.8 2169.58  4360.4 2161.38  4491.8 2158.93
    4593 2153.54    4684 2152.25  4877.9 2145.96  4916.6  2144.5  4955.8 2140.72
  4962.8 2140.25  4963.3 2139.75  4971.5 2140.25  5011.7 2140.58  5028.6 2143.26
  5034.1 2142.08  5044.7 2143.86  5050.9 2147.05  5101.3 2148.94  5166.5 2148.65
  5234.5 2149.48  5372.1 2150.85  5759.5 2153.67  6019.4 2159.59  6206.3 2165.86
  6243.3 2169.11  6295.7 2170.06  6486.9 2180.16  6541.4 2184.36  6610.3 2186.83
#Mann= 9 ,-1 , 0
  3716.5     .16       0  4208.8     .07       0  4955.8     .16       0
  4962.8     .07       0  4971.5     .16       0  5166.5     .07       0
  5234.5     .16       0  5372.1     .07       0  6486.9    .035       0
Bank Sta=4962.8,4971.5
XS Rating Curve= 0 ,0
Exp/Cntr=0.3,0.1

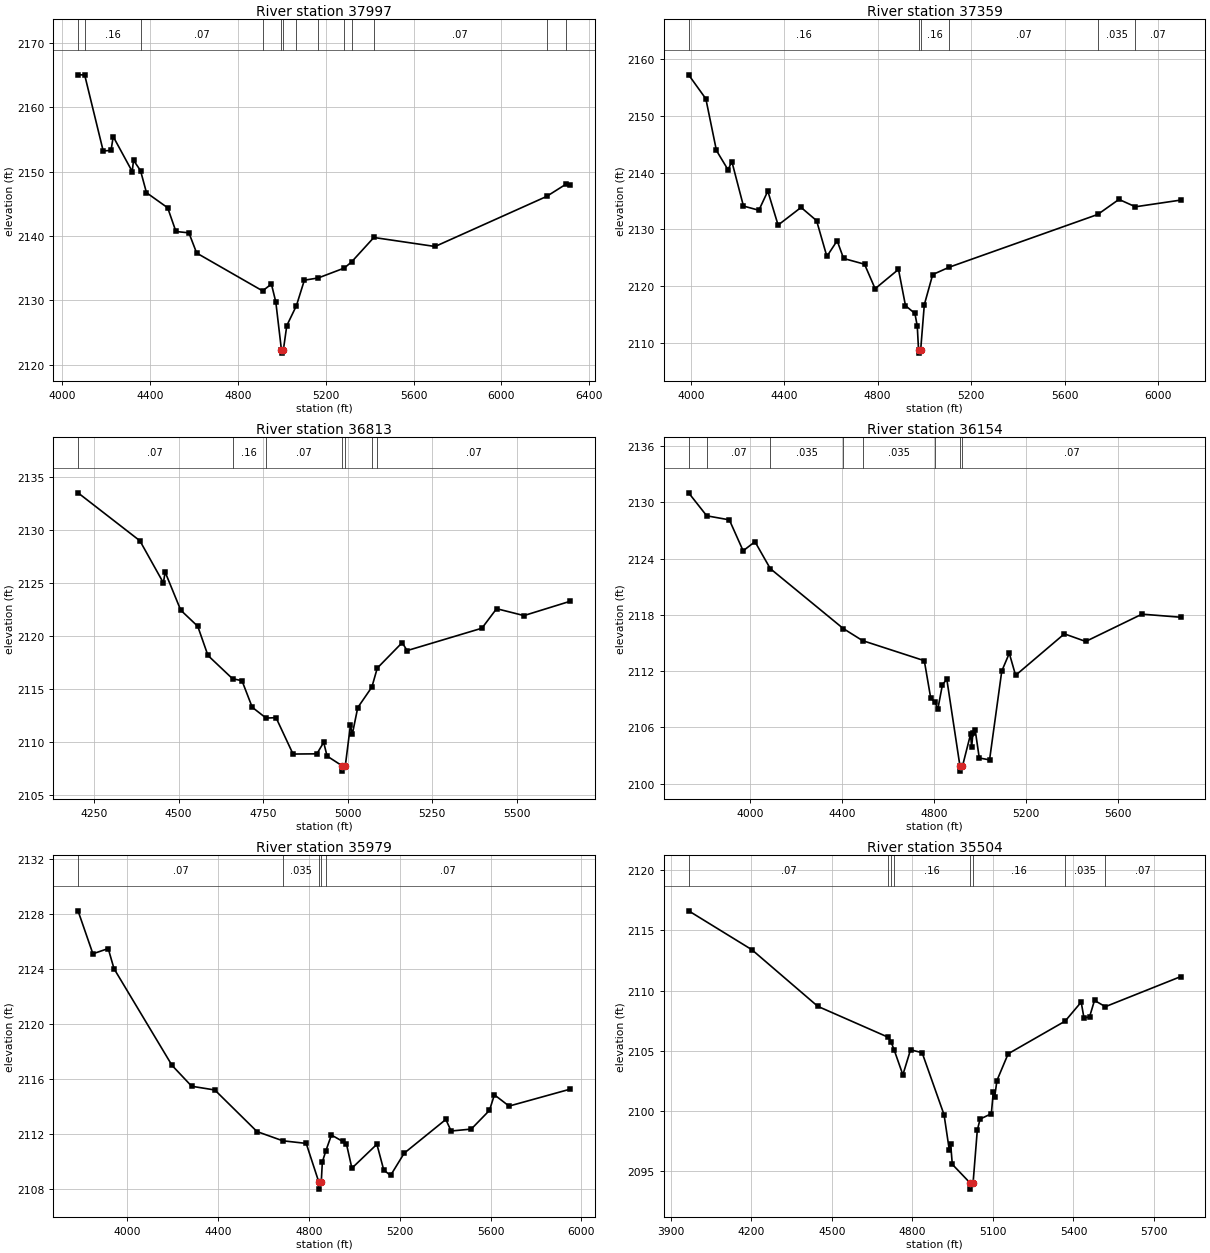
Type RM Length L Ch R = 1 ,37997   ,638,638,638
BEGIN DESCRIPTION:
Mapping XS bee05d1d
END DESCRIPTION:
XS GIS Cut Line= 4
      1481705.43      6804200.99      1482442.38      6804620.24
      1482754.88      6804622.85      1483441.17      6803788.38
#Sta/Elev= 30
  4072.1 2165.04  4102.3 2165.03  4186.7 2153.22  4222.3  2153.3  4232.4 2155.44
  4318.9 2150.02  4324.7 2151.77  4356.6 2150.17  4383.7 2146.74  4480.3 2144.39
  4517.8 2140.71  4576.9  2140.5  4612.3 2137.36  4912.3 2131.49  4952.6 2132.54
  4972.6 2129.76  4998.2 2122.32  4998.7 2121.82    5007 2122.32  5022.6 2126.09
  5066.3 2129.18  5102.6 2133.15  5165.3 2133.49  5284.3 2135.03  5317.4 2135.98
    5419 2139.78  5697.7 2138.38  6205.2 2146.15  6291.5 2148.01  6312.9 2147.99
#Mann= 13 ,-1 , 0
  4072.1     .07       0  4102.3     .16       0  4356.6     .07       0
  4912.3     .16       0  4998.2     .07       0    5007     .16       0
  5066.3     .07       0  5165.3     .16       0  5284.3    .035       0
  5317.4     .16       0    5419     .07       0  6205.2     .16       0
  6291.5     .07       0
Bank Sta=4998.2,5007
XS Rating Curve= 0 ,0
Exp/Cntr=0.3,0.1

Type RM Length L Ch R = 1 ,37359   ,546,546,546
BEGIN DESCRIPTION:
Mapping XS 66cde4c0
END DESCRIPTION:
XS GIS Cut Line= 4
      1481399.86      6804734.62      1482181.09      6805148.67
      1482472.76      6805174.72      1483162.86      6804552.33
#Sta/Elev= 30
  3991.1  2157.2  4064.8 2152.98  4110.1 2143.89  4159.7  2140.5  4176.1 2141.94
  4225.7 2134.12  4291.7 2133.38    4330 2136.75    4374 2130.77  4472.3 2133.88
  4538.7 2131.55  4582.7 2125.26  4626.7 2128.02  4654.3  2124.9  4743.9 2123.89
  4789.2 2119.58  4889.2 2122.98  4919.1  2116.6  4959.5 2115.23  4969.6    2113
  4975.1 2108.75  4975.6 2108.25    4984 2108.75  4999.7 2116.76  5035.6 2122.07
  5106.6 2123.37  5741.9 2132.64  5832.7 2135.29    5903 2133.99  6097.4 2135.17
#Mann= 6 ,-1 , 0
  3991.1     .16       0  4975.1     .07       0    4984     .16       0
  5106.6     .07       0  5741.9    .035       0    5903     .07       0
Bank Sta=4975.1,4984
XS Rating Curve= 0 ,0
Exp/Cntr=0.3,0.1

Type RM Length L Ch R = 1 ,36813   ,659,659,659
BEGIN DESCRIPTION:
Mapping XS 1f65b468
END DESCRIPTION:
XS GIS Cut Line= 3
      1481413.24       6805584.8      1482197.94      6805671.61
       1482777.8      6805345.22
#Sta/Elev= 30
  4202.6 2133.49  4385.5 2128.97    4455    2125    4460 2126.03  4506.2 2122.43
  4556.5 2120.91  4586.7 2118.16  4659.3 2115.97  4687.3 2115.78  4717.5 2113.28
  4758.5 2112.26  4787.9  2112.3  4838.2 2108.87  4908.6 2108.89  4928.8 2109.97
  4938.8 2108.68  4983.4 2107.76  4983.9 2107.26  4992.7 2107.76  5007.8 2111.57
  5013.5 2110.75  5029.5 2113.25  5071.2 2115.18  5087.2 2116.97  5160.8 2119.37
  5175.4 2118.62  5396.5 2120.73  5439.9 2122.57  5520.8 2121.92  5657.5 2123.27
#Mann= 7 ,-1 , 0
  4202.6     .07       0  4659.3     .16       0  4758.5     .07       0
  4983.4     .07       0  4992.7     .07       0  5071.2     .16       0
  5087.2     .07       0
Bank Sta=4983.4,4992.7
XS Rating Curve= 0 ,0
Exp/Cntr=0.3,0.1

Type RM Length L Ch R = 1 ,36154   ,175,175,175
BEGIN DESCRIPTION:
Mapping XS dea6b016
END DESCRIPTION:
XS GIS Cut Line= 3
      1481111.18      6805966.75      1482354.19       6806209.8
      1483190.31      6805953.07
#Sta/Elev= 30
  3732.6 2131.01  3811.3 2128.56  3909.7 2128.13  3969.7 2124.83  4021.2  2125.8
  4087.9 2122.93  4405.1 2116.55  4489.1 2115.26  4757.9 2113.12    4786 2109.11
  4803.6 2108.76  4816.6 2107.95  4836.9 2110.58  4855.9 2111.13  4913.2 2101.85
  4913.7 2101.35  4923.7 2101.85  4958.9 2105.26    4964 2103.94  4969.4 2105.44
  4979.6 2105.68    4997 2102.75  5041.8 2102.55  5094.9 2112.01  5127.6 2113.91
  5155.1 2111.56  5367.2 2115.98  5460.1 2115.17  5704.9 2118.08  5873.8 2117.75
#Mann= 8 ,-1 , 0
  3732.6    .035       0  3811.3     .07       0  4087.9    .035       0
  4405.1     .07       0  4489.1    .035       0  4803.6     .07       0
  4913.2     .07       0  4923.7     .07       0
Bank Sta=4913.2,4923.7
XS Rating Curve= 0 ,0
Exp/Cntr=0.3,0.1

Type RM Length L Ch R = 1 ,35979   ,475,475,475
BEGIN DESCRIPTION:
Mapping XS b497ea58
END DESCRIPTION:
XS GIS Cut Line= 4
      1481171.55      6806120.03      1482174.15       6806376.1
      1482734.04      6806402.15      1483228.83      6806115.69
#Sta/Elev= 30
  3783.8 2128.21  3849.3 2125.09  3916.7 2125.47  3942.2 2124.01  4197.5 2116.99
  4284.3 2115.47    4386  2115.2  4571.8 2112.18  4685.3 2111.51  4788.5 2111.32
  4844.2  2108.5  4844.7    2108  4854.7  2108.5  4859.5 2109.97  4874.7 2110.77
  4899.5 2111.93  4949.6 2111.46  4965.8 2111.27  4989.6 2109.52  5099.7 2111.26
  5129.8 2109.39  5159.8 2108.99  5219.9 2110.61  5403.3 2113.06  5426.4 2112.22
  5515.1 2112.36  5595.4 2113.72    5617 2114.85  5681.6 2114.03  5950.8 2115.26
#Mann= 5 ,-1 , 0
  3783.8     .07       0  4685.3    .035       0  4844.2     .07       0
  4854.7    .035       0  4874.7     .07       0
Bank Sta=4844.2,4854.7
XS Rating Curve= 0 ,0
Exp/Cntr=0.3,0.1

Type RM Length L Ch R = 1 ,35504   ,305,305,305
BEGIN DESCRIPTION:
Mapping XS 849a6c8e
END DESCRIPTION:
XS GIS Cut Line= 3
      1481294.58      6806631.68      1482301.53      6806844.35
      1483069.71      6806609.99
#Sta/Elev= 30
  3967.2 2116.62  4202.7 2113.39    4448 2108.69  4710.4 2106.12    4721 2105.72
  4732.8 2105.04  4764.8    2103  4793.3 2105.08  4836.4 2104.84  4918.1 2099.69
  4937.5 2096.78  4942.6 2097.27  4948.8 2095.57  5015.6 2094.01  5016.1 2093.51
  5026.1 2094.01  5041.8 2098.39  5052.3 2099.33  5094.1 2099.77  5101.5 2101.58
  5106.8  2101.2    5115 2102.53  5156.8 2104.75  5368.8 2107.46  5428.6 2109.04
  5439.1 2107.71    5460 2107.83  5478.2 2109.18  5518.6 2108.66  5799.5 2111.16
#Mann= 8 ,-1 , 0
  3967.2     .07       0  4710.4     .16       0    4721     .07       0
  4732.8     .16       0  5015.6     .07       0  5026.1     .16       0
  5368.8    .035       0  5518.6     .07       0
Bank Sta=5015.6,5026.1
XS Rating Curve= 0 ,0
Exp/Cntr=0.3,0.1