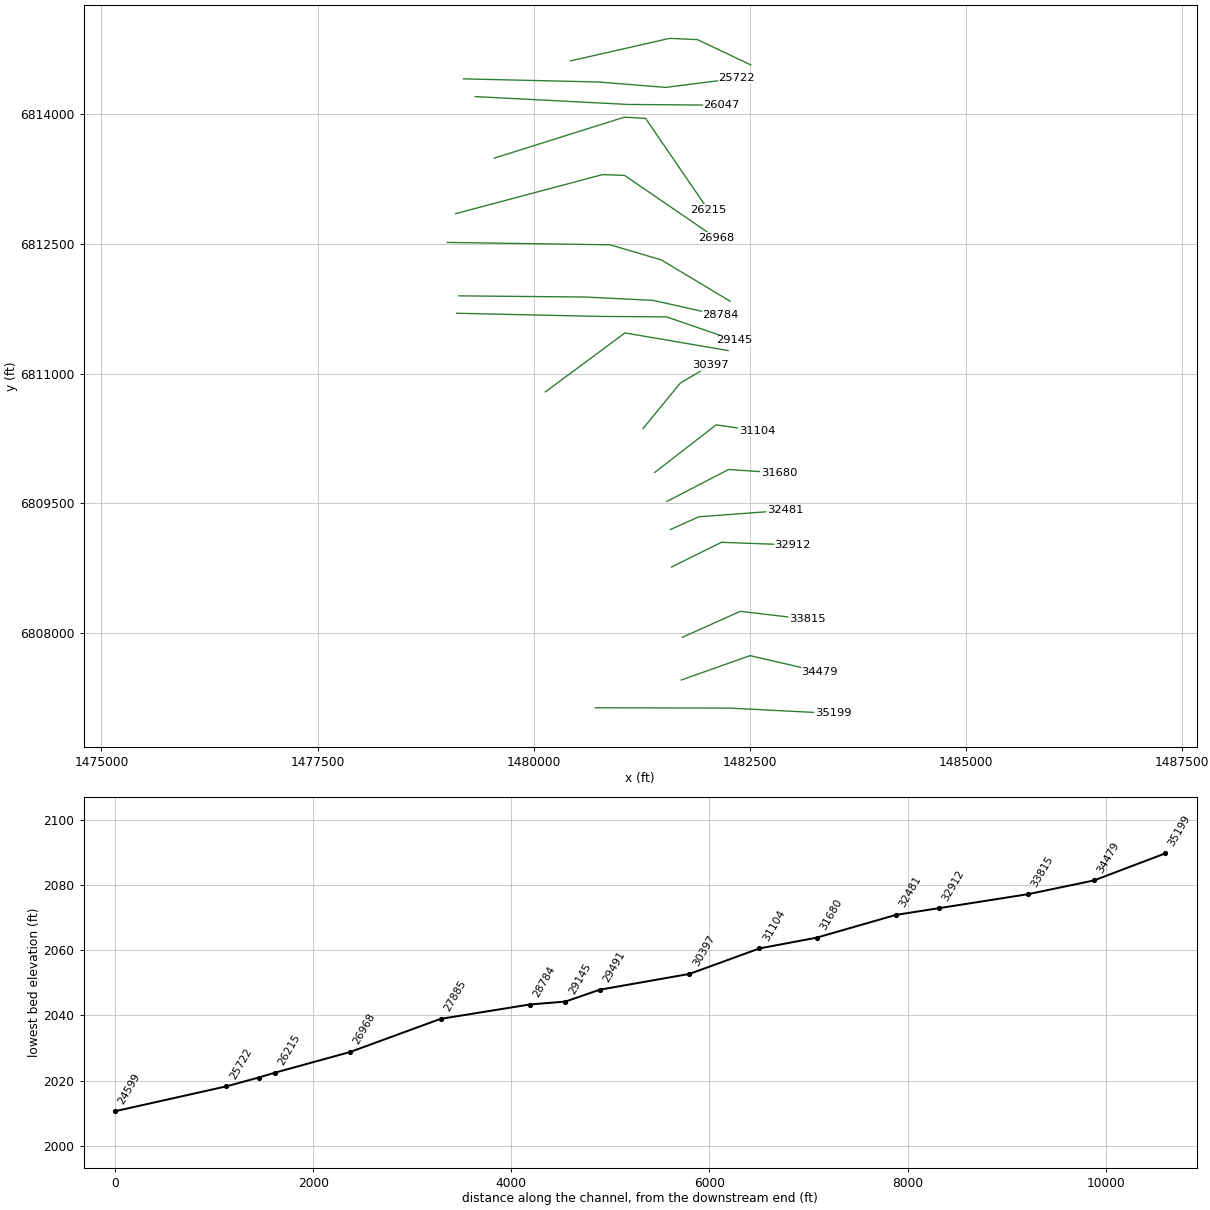
HEC-RAS study NUBIA CREEK.prj: NUBIA CREEK Base Level Engineering

--- NUBIA CREEK.g01 (geometry) --- (continued)

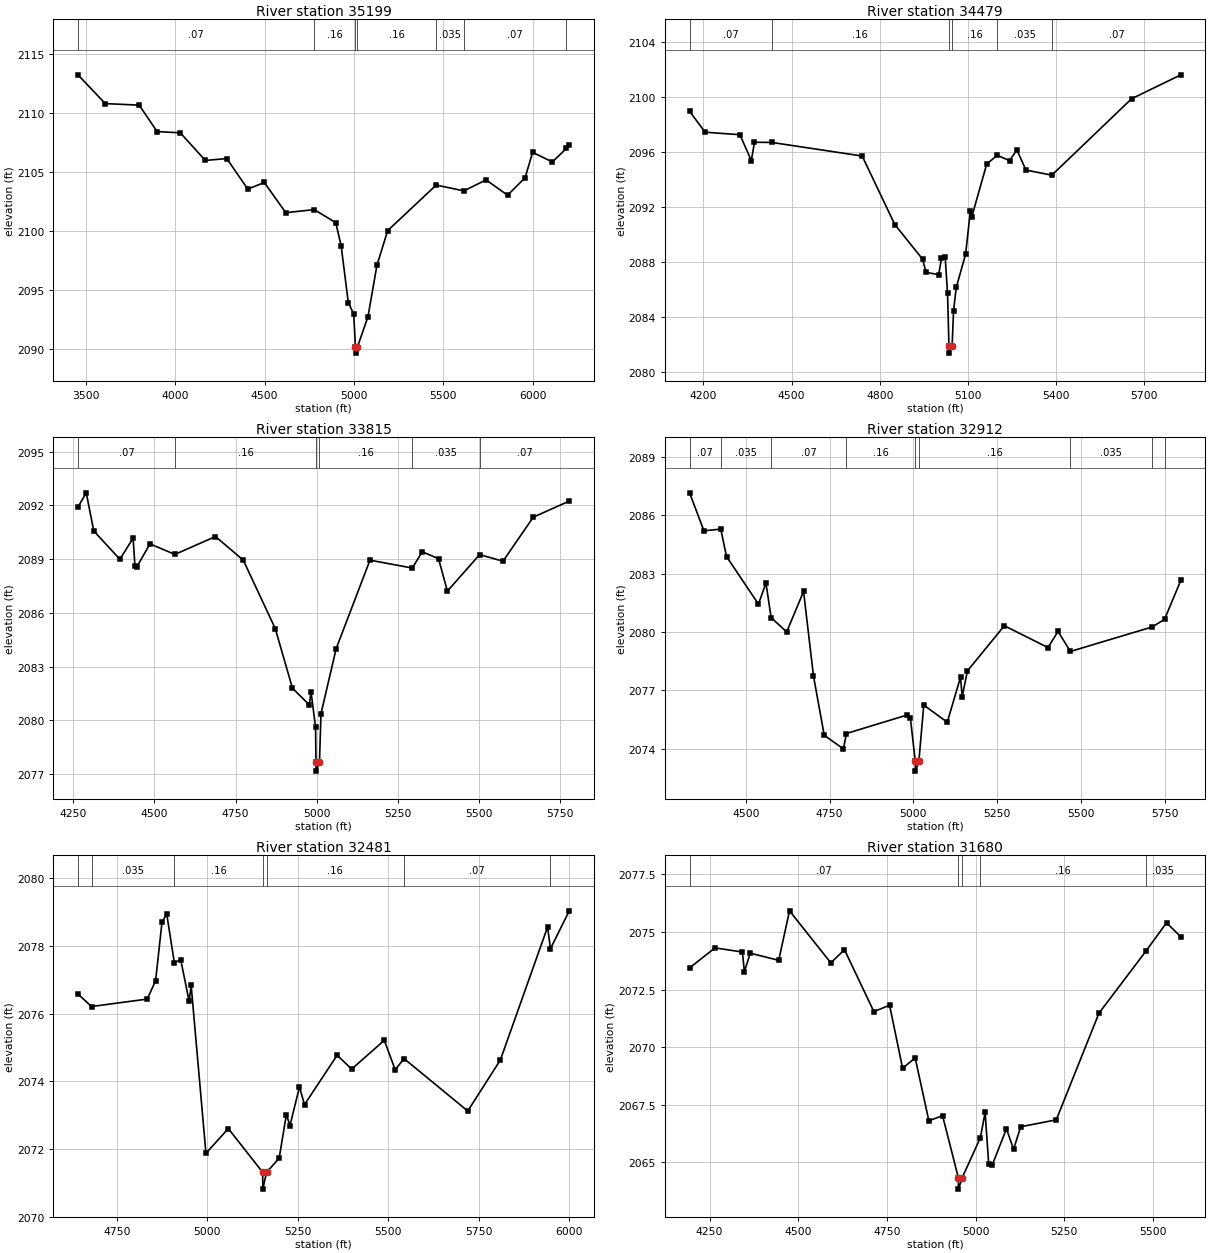
Type RM Length L Ch R = 1 ,35199   ,720,720,720
BEGIN DESCRIPTION:
Mapping XS b812197b
END DESCRIPTION:
XS GIS Cut Line= 3
      1480712.38      6807135.65       1482270.5      6807131.31
      1483459.72      6807070.55
#Sta/Elev= 30
  3455.7 2113.25  3608.3 2110.81  3798.3 2110.68  3898.3 2108.44  4028.3 2108.33
  4168.3 2105.99  4288.3 2106.15  4405.7 2103.56  4498.3 2104.12  4618.3 2101.56
  4777.9 2101.82  4898.3 2100.71  4928.3 2098.74  4968.3 2093.93  4998.3 2092.98
  5008.3 2090.15  5008.8 2089.65  5018.9 2090.15  5078.4 2092.74  5128.5  2097.1
  5188.6 2100.04  5460.1  2103.9  5614.9 2103.41  5739.3 2104.34  5859.4 2103.04
  5957.6 2104.53  5999.6 2106.68  6109.8 2105.86  6188.8 2107.01  6204.6 2107.29
#Mann= 7 ,-1 , 0
  3455.7     .07       0  4777.9     .16       0  5008.3     .07       0
  5018.9     .16       0  5460.1    .035       0  5614.9     .07       0
  6188.8    .035       0
Bank Sta=5008.3,5018.9
XS Rating Curve= 0 ,0
Exp/Cntr=0.3,0.1

Type RM Length L Ch R = 1 ,34479   ,664,664,664
BEGIN DESCRIPTION:
Mapping XS 052d120a
END DESCRIPTION:
XS GIS Cut Line= 3
      1481706.94      6807456.34      1482501.18      6807738.45
      1483308.44      6807551.82
#Sta/Elev= 30
  4152.7 2098.93  4205.7 2097.41  4323.9 2097.23  4362.9 2095.35  4373.5 2096.68
  4431.7 2096.67  4739.9 2095.68    4851  2090.7  4945.3 2088.19  4957.2 2087.23
  5000.1 2087.06  5009.7 2088.25  5022.4 2088.31  5030.3 2085.72  5035.2 2081.86
  5035.7 2081.36  5045.9 2081.86  5050.8 2084.44    5060 2086.14  5091.8 2088.54
  5107.9 2091.67    5113 2091.28  5163.7  2095.1  5199.2 2095.73  5241.2 2095.35
  5266.3 2096.12  5297.1 2094.66  5385.2 2094.29  5656.4 2099.84  5824.1 2101.58
#Mann= 6 ,-1 , 0
  4152.7     .07       0  4431.7     .16       0  5035.2     .07       0
  5045.9     .16       0  5199.2    .035       0  5385.2     .07       0
Bank Sta=5035.2,5045.9
XS Rating Curve= 0 ,0
Exp/Cntr=0.3,0.1

Type RM Length L Ch R = 1 ,33815   ,903,903,903
BEGIN DESCRIPTION:
Mapping XS 92e89fb0
END DESCRIPTION:
XS GIS Cut Line= 3
      1481719.96      6807951.13      1482388.33       6808250.6
      1483165.21      6808159.46
#Sta/Elev= 30
  4264.1 2091.91  4289.6  2092.7  4312.8 2090.57  4393.3 2088.99    4434 2090.17
  4439.7 2088.62  4445.1 2088.55    4486 2089.85  4562.8 2089.26    4688 2090.26
  4773.7 2088.94  4872.3 2085.12  4925.3 2081.79  4977.2 2080.86  4982.6 2081.58
  4996.5 2079.62  4997.9 2077.66  4998.4 2077.16  5008.6 2077.66  5013.3 2080.37
  5060.1    2084  5164.3 2088.94    5295  2088.5  5325.4 2089.41  5375.7 2089.02
    5403 2087.21  5502.3 2089.25  5574.4 2088.88  5667.7 2091.34  5778.7 2092.24
#Mann= 6 ,-1 , 0
  4264.1     .07       0  4562.8     .16       0  4997.9     .07       0
  5008.6     .16       0    5295    .035       0  5502.3     .07       0
Bank Sta=4997.9,5008.6
XS Rating Curve= 0 ,0
Exp/Cntr=0.3,0.1

Type RM Length L Ch R = 1 ,32912   ,431,431,431
BEGIN DESCRIPTION:
Mapping XS fea6073b
END DESCRIPTION:
XS GIS Cut Line= 3
      1481594.07      6808762.76      1482171.32      6809049.21
      1482990.84      6809018.86
#Sta/Elev= 30
  4332.7 2087.14  4375.5 2085.19  4425.7 2085.28  4442.8 2083.87    4538 2081.43
  4560.4 2082.51  4575.8 2080.74  4622.1    2080  4672.5 2082.08  4702.1 2077.74
  4734.1  2074.7  4791.4    2074  4800.1 2074.79  4981.5 2075.74  4990.8 2075.61
  5005.5 2073.36    5006 2072.86  5016.2 2073.36  5030.8 2076.25  5100.9 2075.37
  5140.4 2077.68  5145.4 2076.68  5160.9    2078    5271 2080.32  5401.1  2079.2
  5431.1 2080.03  5467.8    2079  5712.1 2080.26  5748.6 2080.65  5797.2 2082.65
#Mann= 9 ,-1 , 0
  4332.7     .07       0  4425.7    .035       0  4575.8     .07       0
  4800.1     .16       0  5005.5     .07       0  5016.2     .16       0
  5467.8    .035       0  5712.1     .07       0  5748.6    .035       0
Bank Sta=5005.5,5016.2
XS Rating Curve= 0 ,0
Exp/Cntr=0.3,0.1

Type RM Length L Ch R = 1 ,32481   ,801,801,801
BEGIN DESCRIPTION:
Mapping XS 4a67fcf1
END DESCRIPTION:
XS GIS Cut Line= 3
      1481581.07      6809196.79       1481910.9      6809344.35
      1482904.83      6809418.13
#Sta/Elev= 30
  4642.5 2076.58  4679.9 2076.21  4833.8 2076.43    4857 2076.97  4874.7  2078.7
  4887.8 2078.95  4908.8 2077.51  4926.6 2077.59  4949.8 2076.36  4955.3 2076.84
  4996.2 2071.87  5058.1  2072.6  5152.9 2071.31  5153.4 2070.81  5163.8 2071.31
  5198.5 2071.72  5218.5 2073.01  5228.5 2072.69  5254.7 2073.83  5268.7 2073.31
  5358.9 2074.77    5399 2074.36  5489.3 2075.21  5519.3 2074.34  5543.8 2074.67
  5719.9 2073.12  5810.1 2074.63  5940.5 2078.56  5948.6 2077.92  6000.5 2079.04
#Mann= 7 ,-1 , 0
  4642.5     .07       0  4679.9    .035       0  4908.8     .16       0
  5152.9     .07       0  5163.8     .16       0  5543.8     .07       0
  5948.6    .035       0
Bank Sta=5152.9,5163.8
XS Rating Curve= 0 ,0
Exp/Cntr=0.3,0.1

Type RM Length L Ch R = 1 ,31680   ,576,576,576
BEGIN DESCRIPTION:
Mapping XS 0843eb7a
END DESCRIPTION:
XS GIS Cut Line= 3
      1481541.98       6809522.3      1482253.78      6809891.22
      1482835.35      6809852.16
#Sta/Elev= 30
  4193.8 2073.44  4265.5 2074.31  4342.7 2074.13  4348.3 2073.28  4364.8 2074.08
    4445 2073.77  4475.5 2075.92  4591.8 2073.66  4630.4 2074.23  4713.3 2071.54
  4757.5 2071.82  4794.2 2069.08  4829.6 2069.53  4868.2  2066.8  4906.8 2067.02
  4951.2 2064.33  4951.7 2063.83  4962.2 2064.33  5013.3 2066.06  5026.8 2067.16
  5036.8 2064.93  5046.9 2064.88  5086.9 2066.45    5107 2065.56    5127 2066.54
  5227.3 2066.84  5347.5 2071.47    5480 2074.17    5538  2075.4  5578.4 2074.79
#Mann= 5 ,-1 , 0
  4193.8     .07       0  4951.2     .07       0  4962.2     .07       0
  5013.3     .16       0    5480    .035       0
Bank Sta=4951.2,4962.2
XS Rating Curve= 0 ,0
Exp/Cntr=0.3,0.1

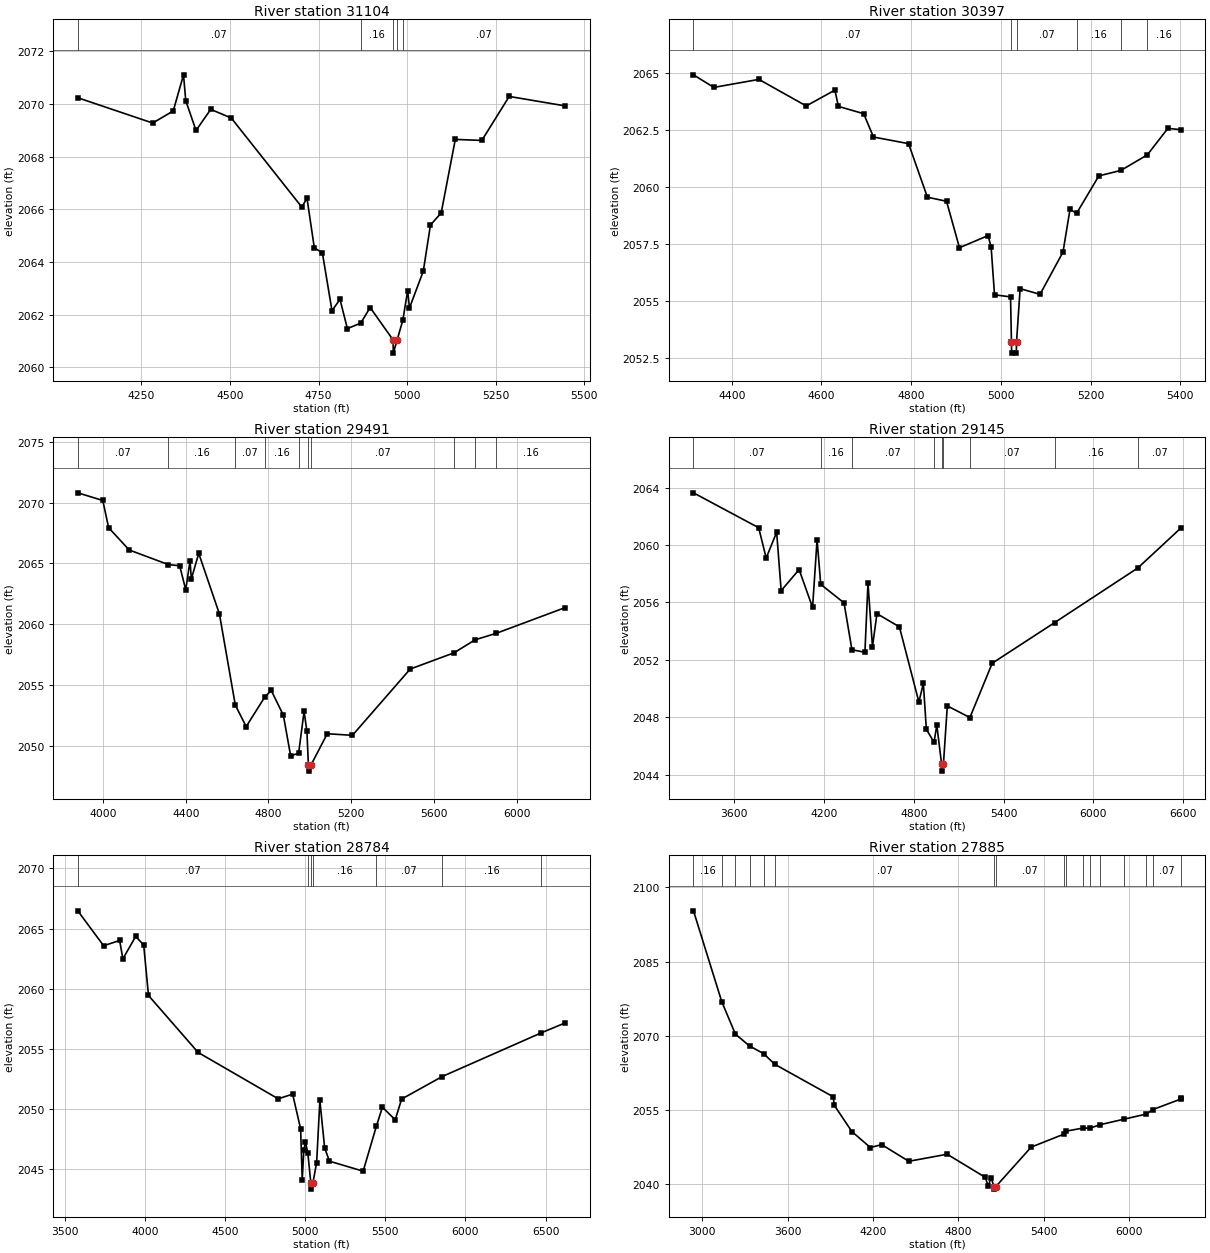
Type RM Length L Ch R = 1 ,31104   ,707,707,707
BEGIN DESCRIPTION:
Mapping XS 27926248
END DESCRIPTION:
XS GIS Cut Line= 3
      1481398.79      6809856.53      1482110.56      6810407.72
      1482581.87      6810338.53
#Sta/Elev= 30
  4070.3 2070.23  4281.9 2069.27  4339.8 2069.73  4368.8  2071.1  4375.1 2070.12
  4404.1 2068.99  4445.7 2069.79  4503.7 2069.46  4702.9 2066.08  4717.4 2066.42
  4738.2 2064.53  4760.8 2064.35    4788 2062.15  4810.6 2062.58  4831.4 2061.47
  4869.3 2061.68  4895.7 2062.27  4960.6 2061.04  4961.1 2060.54    4972 2061.04
    4988 2061.79  5001.7 2062.91  5006.7 2062.25  5045.8 2063.65    5066  2065.4
  5096.3 2065.86  5136.2 2068.65  5211.1 2068.61  5288.4 2070.28  5446.9 2069.92
#Mann= 5 ,-1 , 0
  4070.3     .07       0  4869.3     .16       0  4960.6     .07       0
    4972     .16       0    4988     .07       0
Bank Sta=4960.6,4972
XS Rating Curve= 0 ,0
Exp/Cntr=0.3,0.1

Type RM Length L Ch R = 1 ,30397   ,906,906,906
BEGIN DESCRIPTION:
Mapping XS 807ad138
END DESCRIPTION:
XS GIS Cut Line= 3
       1481264.2      6810364.31      1481693.89      6810889.49
      1482045.44      6811097.81
#Sta/Elev= 30
  4314.6  2064.9    4360 2064.35  4460.5  2064.7    4566 2063.54  4629.9 2064.23
  4637.8 2063.52  4694.1  2063.2    4716 2062.18  4794.2 2061.89  4836.2 2059.55
  4878.9 2059.37  4907.7 2057.34  4971.5 2057.87  4978.3 2057.37  4985.9 2055.28
  5021.6 2055.19  5023.6 2053.23  5024.1 2052.73  5034.5 2052.73    5035 2053.23
    5043 2055.55  5087.4  2055.3  5138.6 2057.15  5154.2 2059.02  5168.8 2058.84
  5218.5 2060.48  5267.7 2060.72  5326.6  2061.4  5372.5 2062.56  5401.8  2062.5
#Mann= 6 ,-1 , 0
  4314.6     .07       0  5023.6     .07       0    5035     .07       0
  5168.8     .16       0  5267.7     .07       0  5326.6     .16       0
Bank Sta=5023.6,5035
XS Rating Curve= 0 ,0
Exp/Cntr=0.3,0.1

Type RM Length L Ch R = 1 ,29491   ,346,346,346
BEGIN DESCRIPTION:
Mapping XS 0b971c28
END DESCRIPTION:
XS GIS Cut Line= 3
      1480135.34      6810789.27      1481055.51      6811470.72
      1482249.08      6811266.73
#Sta/Elev= 30
  3878.6 2070.82  3999.4 2070.19  4027.5 2067.95  4127.1 2066.11  4315.9 2064.91
  4370.9 2064.81  4400.2 2062.83    4421 2065.23  4427.2 2063.72    4463 2065.83
  4562.9 2060.84  4639.7 2053.33  4692.3 2051.56  4782.7 2054.01  4813.3 2054.54
  4871.8  2052.5  4907.3 2049.13  4945.8 2049.38    4972 2052.81  4985.7 2051.18
  4992.9 2048.39  4993.4 2047.89  5005.3 2048.39    5084 2050.97  5205.7 2050.84
  5484.8  2056.3  5696.9 2057.64  5798.4 2058.71  5901.5 2059.25  6234.5 2061.37
#Mann= 10 ,-1 , 0
  3878.6     .07       0  4315.9     .16       0  4639.7     .07       0
  4782.7     .16       0  4945.8     .07       0  4992.9     .07       0
  5005.3     .07       0  5696.9     .16       0  5798.4     .07       0
  5901.5     .16       0
Bank Sta=4992.9,5005.3
XS Rating Curve= 0 ,0
Exp/Cntr=0.3,0.1

Type RM Length L Ch R = 1 ,29145   ,361,361,361
BEGIN DESCRIPTION:
Mapping XS d2edec92
END DESCRIPTION:
XS GIS Cut Line= 4
      1479109.36      6811698.15        1480776.      6811661.69
      1481536.42      6811656.49       1482321.4      6811386.16
#Sta/Elev= 30
  3327.8 2063.63  3763.5  2061.2  3813.6 2059.09  3883.6 2060.89  3913.6 2056.82
  4033.6 2058.29  4123.6 2055.65  4153.6 2060.37    4178 2057.26  4333.7 2055.97
  4386.5 2052.71  4473.3 2052.53  4493.7 2057.36  4523.7 2052.92  4553.7 2055.22
  4703.8  2054.3  4833.8 2049.07  4863.8 2050.36  4883.8 2047.17  4934.9 2046.27
  4953.8 2047.46  4985.6 2044.76  4986.1 2044.26    4998 2044.76  5023.8  2048.8
  5174.8 2047.99  5323.9 2051.77  5741.1  2054.6  6296.9  2058.4  6585.5 2061.19
#Mann= 9 ,-1 , 0
  3327.8     .07       0    4178     .16       0  4386.5     .07       0
  4934.9     .16       0  4985.6     .07       0    4998     .16       0
  5174.8     .07       0  5741.1     .16       0  6296.9     .07       0
Bank Sta=4985.6,4998
XS Rating Curve= 0 ,0
Exp/Cntr=0.3,0.1

Type RM Length L Ch R = 1 ,28784   ,899,899,899
BEGIN DESCRIPTION:
Mapping XS f17a2f0a
END DESCRIPTION:
XS GIS Cut Line= 4
      1479133.65      6811899.54      1480605.86      6811885.65
      1481380.17      6811847.46      1482157.91      6811673.86
#Sta/Elev= 30
  3579.3 2066.47  3740.7 2063.57  3840.7 2064.01  3860.7 2062.48  3940.7 2064.34
  3990.7 2063.64  4020.7 2059.44  4330.7 2054.71  4830.7 2050.86  4920.7 2051.25
  4970.7 2048.36  4980.7 2044.15  4990.7 2046.59  5000.7 2047.25  5015.7 2046.37
  5034.4 2043.86  5034.9 2043.36  5047.1 2043.86  5070.7 2045.56  5090.8 2050.72
  5120.8 2046.78  5150.8 2045.68  5361.1 2044.85  5443.8 2048.59  5481.2 2050.16
  5561.3 2049.12  5601.4 2050.84  5854.8 2052.71    6472 2056.33  6623.7 2057.17
#Mann= 7 ,-1 , 0
  3579.3     .07       0  5015.7     .16       0  5034.4     .07       0
  5047.1     .16       0  5443.8     .07       0  5854.8     .16       0
    6472     .07       0
Bank Sta=5034.4,5047.1
XS Rating Curve= 0 ,0
Exp/Cntr=0.3,0.1

Type RM Length L Ch R = 1 ,27885   ,917,917,917
BEGIN DESCRIPTION:
Mapping XS 4d8b53e1
END DESCRIPTION:
XS GIS Cut Line= 4
      1479001.65       6812517.6      1480883.64      6812489.82
      1481473.92      6812316.21      1482271.24      6811837.81
#Sta/Elev= 30
  2938.8 2095.26  3137.9 2076.85  3233.7 2070.32  3332.7 2067.92  3431.8 2066.37
  3510.5 2064.21  3922.3 2057.62  3927.6 2055.96  4052.3  2050.6  4182.3 2047.38
  4262.3 2047.96  4452.3 2044.59  4722.3 2046.02  4990.7 2041.33    5010 2039.54
  5030.9 2041.31    5051 2039.46  5051.5 2038.96  5063.8 2039.46  5312.3 2047.45
    5545 2050.11  5560.6  2050.7    5678 2051.32    5727  2051.3  5795.5 2051.98
  5961.8 2053.09  6122.9 2054.15  6165.9 2055.03  6363.9 2057.18  6366.1 2057.33
#Mann= 17 ,-1 , 0
  2938.8     .16       0  3137.9     .07       0  3233.7    .035       0
  3332.7     .07       0  3431.8     .16       0  3510.5     .07       0
    5051     .07       0  5063.8     .07       0    5545     .16       0
  5560.6     .07       0    5678     .16       0    5727     .07       0
  5795.5     .16       0  5961.8     .07       0  6122.9     .16       0
  6165.9     .07       0  6363.9    .035       0
Bank Sta=5051,5063.8
XS Rating Curve= 0 ,0
Exp/Cntr=0.3,0.1

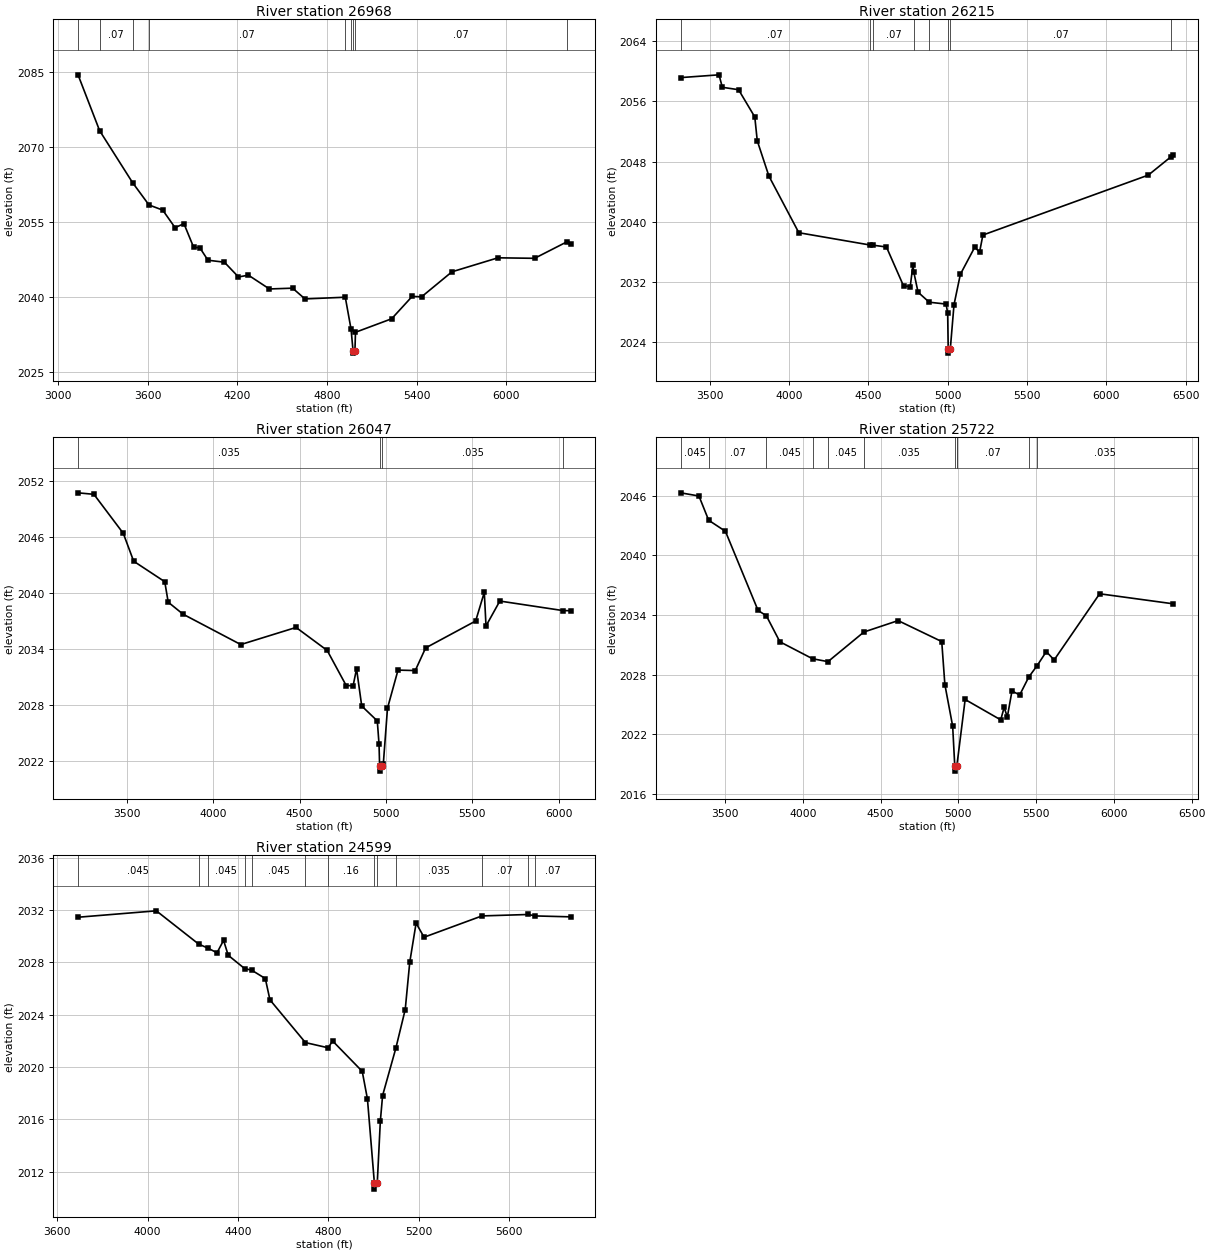
Type RM Length L Ch R = 1 ,26968   ,753,753,753
BEGIN DESCRIPTION:
Mapping XS 9084476c
END DESCRIPTION:
XS GIS Cut Line= 4
      1479097.43       6812850.2      1480794.52       6813301.6
      1481050.59      6813292.92      1482109.59      6812568.11
#Sta/Elev= 30
  3134.2 2084.42  3278.7 2073.25  3499.2 2062.86  3608.9  2058.4  3700.8 2057.37
  3783.6 2053.86  3842.9 2054.66  3907.8 2049.93  3949.2 2049.84  4003.5 2047.35
  4113.6 2046.95  4207.8    2044  4274.2 2044.36  4414.8  2041.6    4570 2041.76
  4652.8 2039.61  4922.6 2039.95  4961.4 2033.52  4974.4 2029.27  4974.9 2028.77
  4987.2 2029.27  4990.8 2032.94  5232.8 2035.64    5370 2040.11  5433.1 2040.03
  5636.3 2045.03  5944.3 2047.83  6189.5 2047.73  6405.3 2051.02  6429.8 2050.57
#Mann= 9 ,-1 , 0
  3134.2     .16       0  3278.7     .07       0  3499.2     .16       0
  3608.9     .07       0  4922.6    .035       0  4961.4     .07       0
  4974.4     .07       0  4987.2     .07       0  6405.3    .035       0
Bank Sta=4974.4,4987.2
XS Rating Curve= 0 ,0
Exp/Cntr=0.3,0.1

Type RM Length L Ch R = 1 ,26215   ,168,168,168
BEGIN DESCRIPTION:
Mapping XS 51d02de3
END DESCRIPTION:
XS GIS Cut Line= 4
      1479544.51      6813492.57      1481046.25      6813965.66
      1481293.65      6813952.64       1482018.5      6812893.58
#Sta/Elev= 30
  3316.4 2059.17  3558.1 2059.54  3578.9 2057.88  3681.3 2057.56  3783.6 2053.93
  3799.2 2050.76  3872.6 2046.06  4061.3 2038.52  4508.7 2036.89  4529.3 2036.86
  4613.8 2036.62  4721.8 2031.43  4763.8 2031.35  4780.9  2034.2  4786.1  2033.3
  4813.2  2030.6  4883.6 2029.27  4989.8 2029.02  4999.8 2027.86  5003.4 2022.99
  5003.9 2022.49  5016.3 2022.99  5039.9 2028.94  5079.9 2032.98  5171.1 2036.61
  5200.9  2035.9  5221.9 2038.21  6265.2 2046.19  6409.3 2048.65    6422 2048.81
#Mann= 8 ,-1 , 0
  3316.4     .07       0  4508.7    .035       0  4529.3     .07       0
  4786.1    .035       0  4883.6     .07       0  5003.4     .07       0
  5016.3     .07       0  6409.3    .035       0
Bank Sta=5003.4,5016.3
XS Rating Curve= 0 ,0
Exp/Cntr=0.3,0.1

Type RM Length L Ch R = 1 ,26047   ,325,325,325
BEGIN DESCRIPTION:
Mapping XS 4d2c6229
END DESCRIPTION:
XS GIS Cut Line= 3
      1479323.16      6814204.37      1481089.66      6814113.23
      1482174.68      6814104.55
#Sta/Elev= 30
  3215.7 2050.72  3307.7 2050.56  3477.9 2046.39    3538 2043.41  3718.2 2041.22
  3738.2 2039.03    3824 2037.75  4158.8  2034.5  4479.2 2036.33  4659.5 2033.87
  4769.6 2030.12  4809.7  2030.1  4829.7  2031.9  4859.7 2027.93  4949.8 2026.34
  4959.9 2023.87  4963.4 2021.47  4963.9 2020.97  4976.3 2021.47  4984.5 2021.68
    5009  2027.7  5069.9 2031.77  5169.9 2031.72  5229.9 2034.14  5519.9 2037.02
  5569.9 2040.08  5579.9 2036.49  5659.9 2039.15  6026.6 2038.13  6069.6 2038.12
#Mann= 4 ,-1 , 0
  3215.7    .035       0  4963.4    .035       0  4976.3    .035       0
  6026.6    .045       0
Bank Sta=4963.4,4976.3
XS Rating Curve= 0 ,0
Exp/Cntr=0.3,0.1

Type RM Length L Ch R = 1 ,25722   ,1123,1123,1123
BEGIN DESCRIPTION:
Mapping XS 603ceac5
END DESCRIPTION:
XS GIS Cut Line= 4
       1479187.7      6814409.24      1480755.45      6814372.78
      1481526.29      6814310.28      1482344.04      6814414.45
#Sta/Elev= 30
  3215.3 2046.29  3332.6 2045.97  3395.1 2043.53  3502.7 2042.42  3712.7 2034.45
  3765.8 2033.92  3852.8  2031.3    4063 2029.59  4162.1  2029.3    4393 2032.28
    4613 2033.43  4893.4 2031.32  4913.5 2026.99  4963.6 2022.81  4977.2 2018.78
  4977.7 2018.28  4990.1 2018.78  4990.4 2018.79  5043.9 2025.49  5272.6 2023.44
  5294.7  2024.7  5314.8 2023.72  5344.9 2026.34  5394.7 2025.95  5453.2 2027.76
  5505.9 2028.88  5565.6 2030.31    5616 2029.47  5908.4 2036.13  6381.2 2035.12
#Mann= 11 ,-1 , 0
  3215.3    .045       0  3395.1     .07       0  3765.8    .045       0
    4063     .07       0  4162.1    .045       0    4393    .035       0
  4977.2     .07       0  4990.1    .035       0  4990.4     .07       0
  5453.2     .16       0  5505.9    .035       0
Bank Sta=4977.2,4990.1
XS Rating Curve= 0 ,0
Exp/Cntr=0.3,0.1

Type RM Length L Ch R = 1 ,24599   ,718,718,718
BEGIN DESCRIPTION:
Mapping XS 3d2c5ed0
END DESCRIPTION:
XS GIS Cut Line= 4
      1480427.32      6814617.57      1481573.16      6814877.99
      1481896.08      6814862.36      1482510.36      6814570.84
#Sta/Elev= 30
  3692.5 2031.46  4038.8 2031.95  4225.7 2029.41  4267.6 2029.09  4307.1 2028.74
  4336.2 2029.69  4356.7 2028.55  4429.5 2027.53  4460.5 2027.41  4520.8 2026.77
  4541.3 2025.14  4698.3 2021.87  4799.2 2021.47  4818.2    2022  4949.5 2019.67
  4972.6 2017.55  5003.1 2011.16  5003.6 2010.66  5016.1 2011.16  5029.6 2015.86
  5039.6 2017.82    5098 2021.43  5139.7  2024.4  5159.7 2028.02  5187.8 2031.01
  5222.9 2029.93    5479 2031.56    5684 2031.67  5714.5 2031.56  5870.8 2031.49
#Mann= 13 ,-1 , 0
  3692.5    .045       0  4225.7    .035       0  4267.6    .045       0
  4429.5    .035       0  4460.5    .045       0  4698.3    .035       0
  4799.2     .16       0  5003.1     .07       0  5016.1     .16       0
    5098    .035       0    5479     .07       0    5684    .035       0
  5714.5     .07       0
Bank Sta=5003.1,5016.1
XS Rating Curve= 0 ,0
Exp/Cntr=0.3,0.1