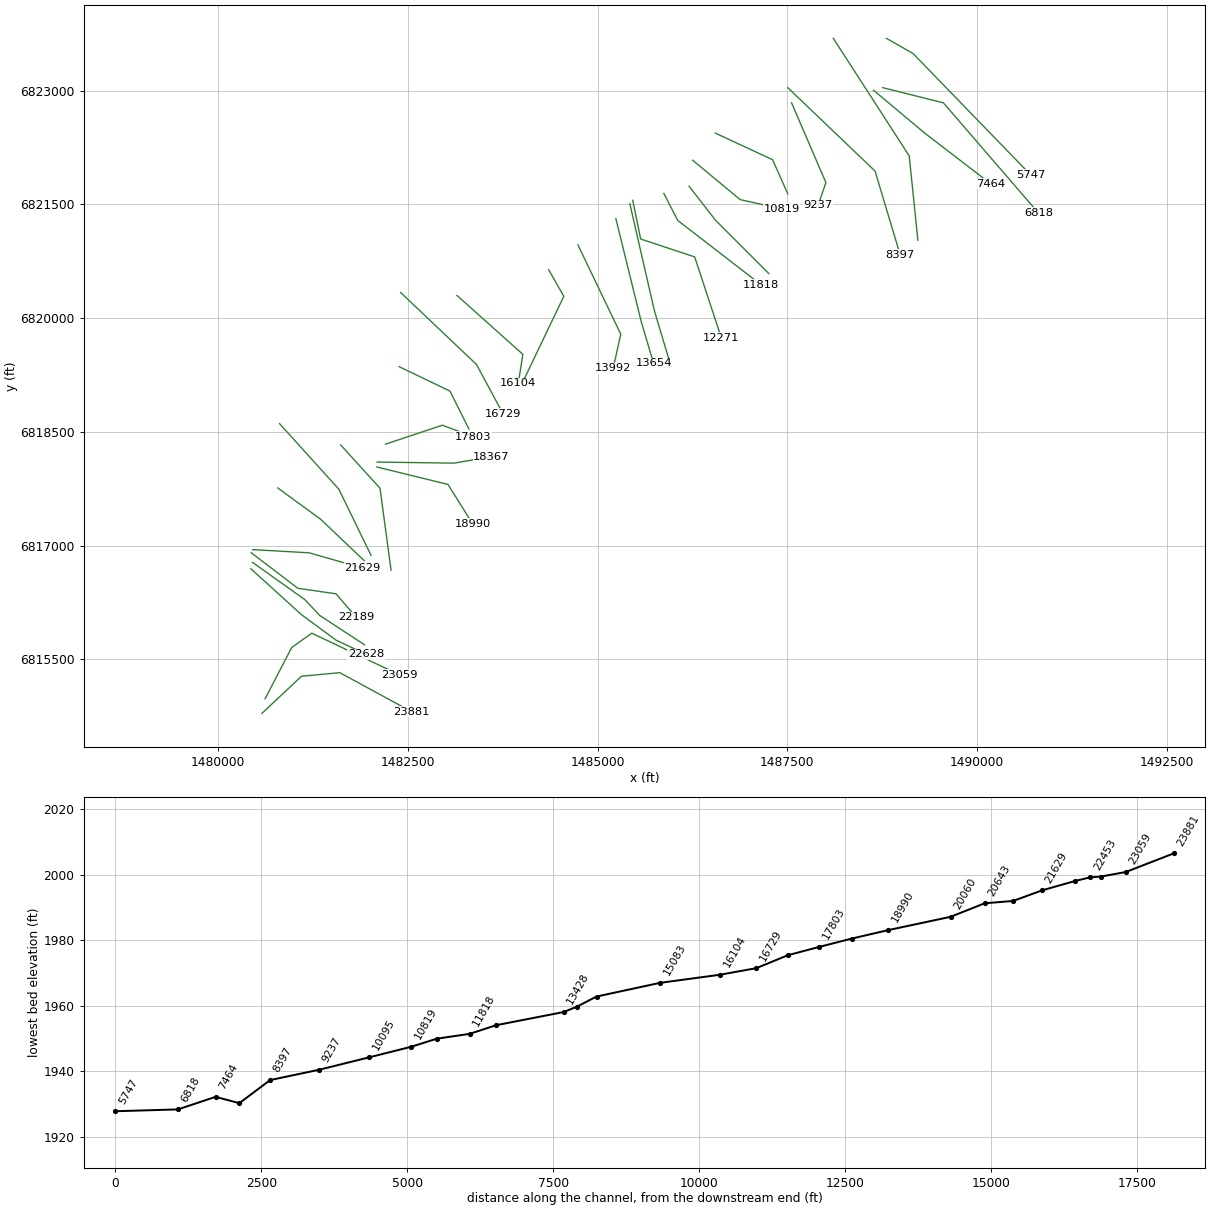
HEC-RAS study NUBIA CREEK.prj: NUBIA CREEK Base Level Engineering

--- NUBIA CREEK.g01 (geometry) --- (continued)

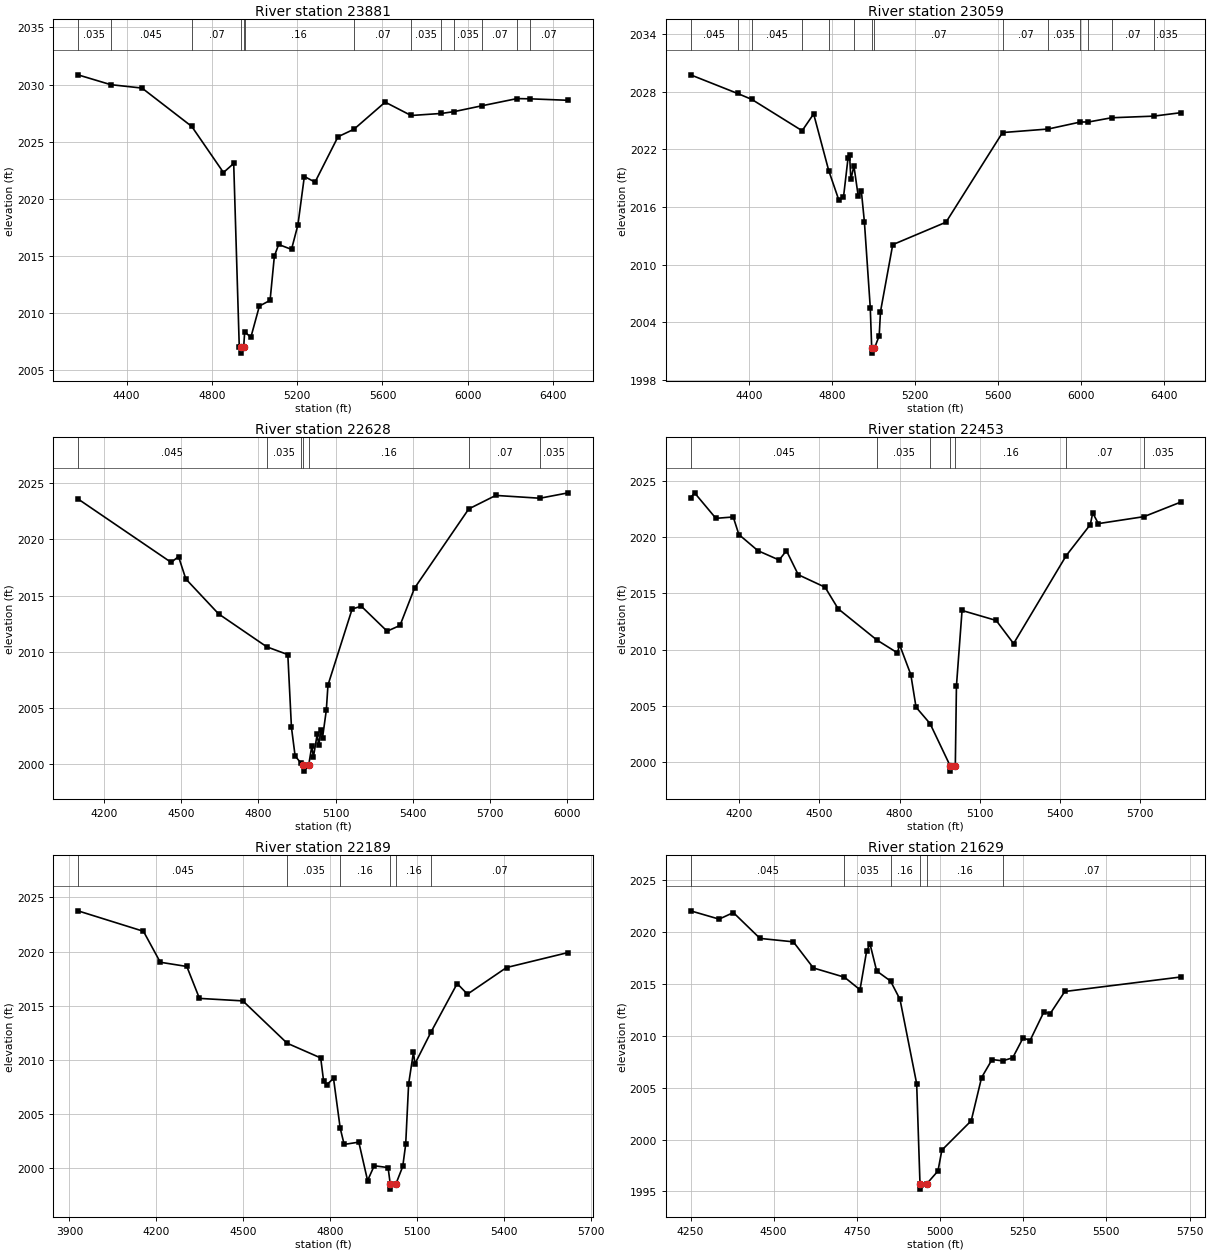
Type RM Length L Ch R = 1 ,23881   ,822,822,822
BEGIN DESCRIPTION:
Mapping XS 22b398c2
END DESCRIPTION:
XS GIS Cut Line= 4
      1480578.36      6814789.43       1481099.2      6815279.03
      1481604.41       6815325.9       1482551.2      6814810.89
#Sta/Elev= 30
  4171.4 2030.85  4325.1 2029.99  4472.1 2029.69  4705.4 2026.33    4854  2022.3
  4902.1 2023.09  4928.2 2007.06  4935.8 2006.99  4936.3 2006.49  4948.8 2006.99
  4953.7 2008.37  4982.4 2007.86  5022.6 2010.61  5072.8 2011.11  5092.9 2014.98
    5113    2016  5173.3 2015.57  5203.4 2017.72  5233.5 2021.95  5283.7 2021.46
  5391.4 2025.43  5466.5 2026.09  5612.6 2028.46  5734.3 2027.29  5876.8 2027.47
  5936.2 2027.63  6066.3 2028.14  6231.1 2028.77  6291.1 2028.75  6471.4 2028.62
#Mann= 13 ,-1 , 0
  4171.4    .035       0  4325.1    .045       0  4705.4     .07       0
  4935.8     .07       0  4948.8     .07       0  4953.7     .16       0
  5466.5     .07       0  5734.3    .035       0  5876.8     .07       0
  5936.2    .035       0  6066.3     .07       0  6231.1    .035       0
  6291.1     .07       0
Bank Sta=4935.8,4948.8
XS Rating Curve= 0 ,0
Exp/Cntr=0.3,0.1

Type RM Length L Ch R = 1 ,23059   ,431,431,431
BEGIN DESCRIPTION:
NUBIA CREEK 32.0
END DESCRIPTION:
XS GIS Cut Line= 4
      1480620.05      6814982.18      1480969.57      6815656.84
      1481234.62      6815846.74      1482385.64      6815299.87
#Sta/Elev= 30
  4119.9 2029.77  4346.1 2027.83  4414.6 2027.21  4656.8 2023.95  4712.2  2025.7
  4784.7 2019.81  4833.8 2016.71  4855.9 2017.04  4877.6 2021.07  4885.3 2021.39
  4891.4 2018.88  4906.1 2020.28    4927 2017.11  4941.8 2017.68  4956.5 2014.47
  4984.8 2005.53  4991.7  2001.3  4992.2  2000.8  5004.8  2001.3  5027.8 2002.61
    5034 2005.12  5092.9 2012.09  5349.4 2014.43  5621.5 2023.76  5841.5 2024.13
  5996.7 2024.86    6035 2024.86  6146.1  2025.3    6349 2025.47  6480.1 2025.83
#Mann= 14 ,-1 , 0
  4119.9    .045       0  4346.1    .035       0  4414.6    .045       0
  4656.8     .07       0  4784.7     .16       0  4906.1     .07       0
  4991.7     .07       0  5004.8     .07       0  5621.5     .07       0
  5841.5    .035       0  5996.7     .07       0    6035    .035       0
  6146.1     .07       0    6349    .035       0
Bank Sta=4991.7,5004.8
XS Rating Curve= 0 ,0
Exp/Cntr=0.3,0.1

Type RM Length L Ch R = 1 ,22628   ,175,175,175
BEGIN DESCRIPTION:
NUBIA CREEK 31.0
END DESCRIPTION:
XS GIS Cut Line= 4
       1480431.5      6816696.22      1481098.56       6816090.7
      1481556.53      6815753.49      1481949.71      6815568.62
#Sta/Elev= 30
  4099.1 2023.58  4461.3 2017.94  4489.7 2018.46  4518.1 2016.47  4645.2 2013.37
  4832.5 2010.44  4914.2 2009.75  4928.3 2003.29  4942.5 2000.75  4966.3 2000.08
  4975.1  1999.9  4975.6  1999.4    4995  1999.9  5007.4 2001.62  5013.6 2000.65
  5028.2 2002.67  5034.4 2001.69  5042.9 2003.09  5049.1 2002.38  5063.7 2004.81
  5070.1 2007.04    5164  2013.8  5199.5 2014.05  5299.8 2011.83  5349.9 2012.34
  5406.2 2015.65  5616.9 2022.69  5721.7 2023.89  5893.1 2023.64  6003.2 2024.12
#Mann= 7 ,-1 , 0
  4099.1    .045       0  4832.5    .035       0  4966.3     .16       0
  4975.1     .07       0    4995     .16       0  5616.9     .07       0
  5893.1    .035       0
Bank Sta=4975.1,4995
XS Rating Curve= 0 ,0
Exp/Cntr=0.3,0.1

Type RM Length L Ch R = 1 ,22453   ,264,264,264
BEGIN DESCRIPTION:
Mapping XS 5500045f
END DESCRIPTION:
XS GIS Cut Line= 4
        1480455.      6816779.51      1481145.07      6816287.35
      1481337.78      6816081.62      1481928.92       6815693.6
#Sta/Elev= 30
  4017.2 2023.52    4032 2023.96  4111.9 2021.69  4176.9 2021.81    4198 2020.25
  4269.3 2018.81  4348.8 2017.98  4376.2 2018.81  4420.5 2016.67  4520.8 2015.56
  4569.9 2013.64    4715 2010.86  4791.7 2009.72  4800.3 2010.42  4842.1 2007.78
  4861.7 2004.88  4914.2 2003.42  4988.9 1999.69  4989.4 1999.19  5008.8 1999.69
    5013 2006.77    5034 2013.49  5161.9  2012.6  5227.1 2010.54  5424.2 2018.37
  5514.4 2021.13  5523.5 2022.17  5544.6 2021.22  5715.5 2021.84  5853.8 2023.14
#Mann= 7 ,-1 , 0
  4017.2    .045       0    4715    .035       0  4914.2     .16       0
  4988.9     .07       0  5008.8     .16       0  5424.2     .07       0
  5715.5    .035       0
Bank Sta=4988.9,5008.8
XS Rating Curve= 0 ,0
Exp/Cntr=0.3,0.1

Type RM Length L Ch R = 1 ,22189   ,560,560,560
BEGIN DESCRIPTION:
Mapping XS c91ed950
END DESCRIPTION:
XS GIS Cut Line= 4
       1480436.7      6816907.16      1481051.32      6816438.39
      1481553.92      6816365.47      1481821.06      6816054.24
#Sta/Elev= 30
  3929.1 2023.76    4155 2021.87  4213.1 2019.01  4304.6 2018.62  4348.2 2015.67
  4497.9 2015.44  4650.6 2011.53  4766.4 2010.17  4776.5 2008.01  4786.6 2007.68
  4810.6 2008.28  4833.6 2003.69  4847.3 2002.18  4897.8 2002.39  4928.1 1998.84
    4951 2000.21  4998.8 2000.04  5006.1 1998.55  5006.6 1998.05  5026.1 1998.55
  5049.4 2000.15  5059.5 2002.19  5069.6 2007.76  5086.3 2010.71  5091.3 2009.62
  5146.4 2012.54  5237.1 2017.04  5272.5 2016.06  5407.2 2018.52  5620.1 2019.91
#Mann= 6 ,-1 , 0
  3929.1    .045       0  4650.6    .035       0  4833.6     .16       0
  5006.1     .07       0  5026.1     .16       0  5146.4     .07       0
Bank Sta=5006.1,5026.1
XS Rating Curve= 0 ,0
Exp/Cntr=0.3,0.1

Type RM Length L Ch R = 1 ,21629   ,500,500,500
BEGIN DESCRIPTION:
Mapping XS 40a6904e
END DESCRIPTION:
XS GIS Cut Line= 3
       1480456.7      6816947.94      1481198.89      6816906.27
      1481901.03      6816706.03
#Sta/Elev= 30
  4250.3 2022.06    4336 2021.26  4378.8 2021.89  4458.9  2019.4  4559.1 2019.07
  4619.2 2016.55  4712.6 2015.66  4759.4 2014.45  4779.4 2018.19  4789.5 2018.86
  4809.5 2016.26  4851.1 2015.29  4879.6 2013.52  4929.7 2005.39  4939.7 1995.72
  4940.2 1995.22  4959.7 1995.72  4993.7 1996.97  5005.4 1998.98  5093.6 2001.81
  5124.8 2005.98  5156.3 2007.72    5188 2007.59  5218.4 2007.89  5249.6 2009.81
  5270.4 2009.55    5312 2012.31  5330.7 2012.13  5374.9 2014.28  5723.8 2015.68
#Mann= 6 ,-1 , 0
  4250.3    .045       0  4712.6    .035       0  4851.1     .16       0
  4939.7     .07       0  4959.7     .16       0    5188     .07       0
Bank Sta=4939.7,4959.7
XS Rating Curve= 0 ,0
Exp/Cntr=0.3,0.1

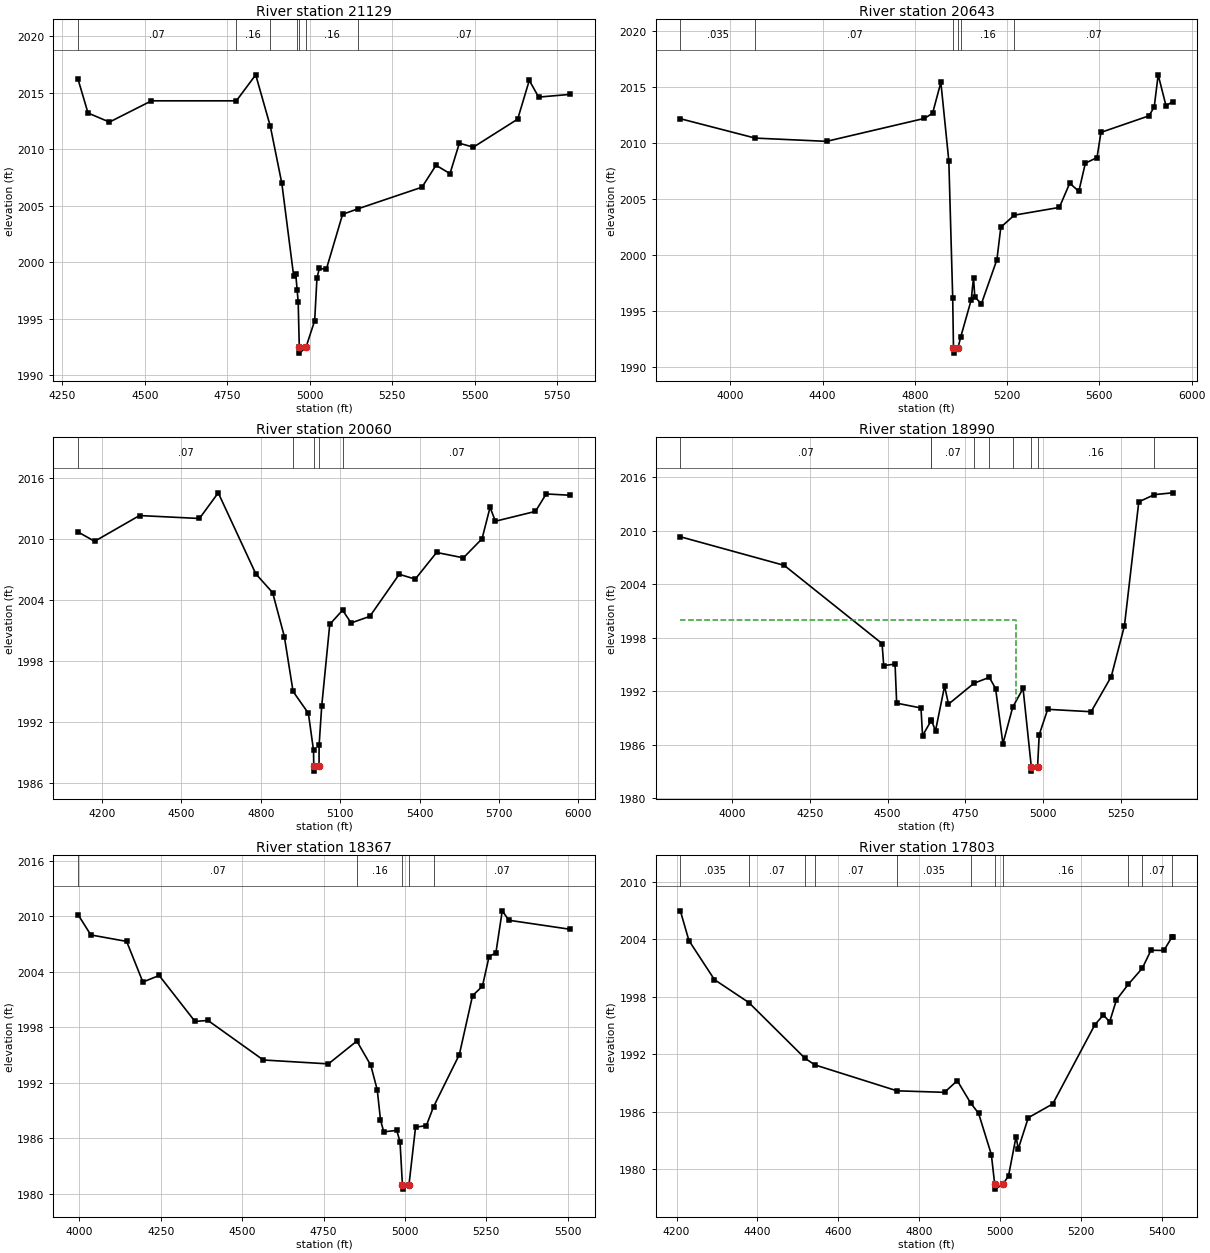
Type RM Length L Ch R = 1 ,21129   ,486,486,486
BEGIN DESCRIPTION:
Mapping XS 21ce0234
END DESCRIPTION:
XS GIS Cut Line= 3
      1480786.12      6817761.31       1481352.1      6817348.11
      1481925.02      6816802.96
#Sta/Elev= 30
  4297.4 2016.19  4327.7  2013.2  4392.6  2012.4    4520 2014.28  4777.3 2014.28
  4835.9 2016.58  4880.3 2012.01  4915.1 2006.97    4951 1998.77  4957.2 1998.96
  4961.4 1997.56  4964.6  1996.5    4968 1992.46  4968.5 1991.96    4988 1992.46
  5014.6 1994.83  5021.5  1998.6  5028.7 1999.45  5049.8 1999.37  5099.2 2004.24
    5147 2004.74  5339.8 2006.64  5382.3 2008.58  5424.7 2007.84    5453 2010.53
  5495.5 2010.18  5629.8 2012.66    5665 2016.09  5693.3 2014.61    5789 2014.85
#Mann= 7 ,-1 , 0
  4297.4     .07       0  4777.3     .16       0  4880.3     .07       0
  4961.4     .16       0    4968     .07       0    4988     .16       0
    5147     .07       0
Bank Sta=4968,4988
XS Rating Curve= 0 ,0
Exp/Cntr=0.3,0.1

Type RM Length L Ch R = 1 ,20643   ,583,583,583
BEGIN DESCRIPTION:
Mapping XS 463c9a45
END DESCRIPTION:
XS GIS Cut Line= 3
      1480810.46      6818608.49      1481591.68      6817743.94
      1482015.14      6816872.73
#Sta/Elev= 30
  3783.2 2012.19  4107.7 2010.46  4417.2 2010.17  4841.7 2012.22  4876.8 2012.68
  4912.7 2015.44  4947.2 2008.41    4964  1996.2  4967.3 1991.76  4967.8 1991.26
  4987.3 1991.76    4999 1992.72    5044 1995.99  5054.3    1998  5059.8 1996.27
  5088.5 1995.67  5155.6  1999.6  5172.6  2002.5  5231.1 2003.58  5426.3 2004.27
  5471.4 2006.43  5510.9 2005.71  5539.1 2008.22  5589.7 2008.72  5606.7 2010.97
  5815.3 2012.45  5837.8 2013.25  5854.8 2016.11    5889 2013.33  5917.1 2013.72
#Mann= 6 ,-1 , 0
  3783.2    .035       0  4107.7     .07       0  4967.3     .07       0
  4987.3     .07       0    4999     .16       0  5231.1     .07       0
Bank Sta=4967.3,4987.3
XS Rating Curve= 0 ,0
Exp/Cntr=0.3,0.1

Type RM Length L Ch R = 1 ,20060   ,1070,1070,1070
BEGIN DESCRIPTION:
Mapping XS 1d0b0654
END DESCRIPTION:
XS GIS Cut Line= 3
        1481616.      6818327.26      1482133.35      6817757.83
      1482279.18      6816677.98
#Sta/Elev= 30
  4109.8 2010.71  4172.4 2009.79    4342 2012.33  4568.4 2012.04  4639.4 2014.57
  4781.3 2006.58  4844.8 2004.73  4889.1  2000.4    4922 1994.99  4979.9 1992.83
  4999.3 1989.18  5000.2 1987.63  5000.7 1987.13  5020.2 1987.63  5020.3 1989.66
  5030.3 1993.56  5060.6  2001.6    5109    2003  5141.3 2001.74    5212 2002.39
    5323 2006.54  5383.5 2006.06  5464.2 2008.69  5565.2 2008.16  5635.8 2010.04
  5666.1 2013.14  5686.2 2011.77  5837.6 2012.74    5878 2014.46  5968.8 2014.33
#Mann= 5 ,-1 , 0
  4109.8     .07       0    4922     .16       0  5000.2     .07       0
  5020.2     .16       0    5109     .07       0
Bank Sta=5000.2,5020.2
XS Rating Curve= 0 ,0
Exp/Cntr=0.3,0.1

Type RM Length L Ch R = 1 ,18990   ,623,623,623
BEGIN DESCRIPTION:
NUBIA CREEK 27.0
END DESCRIPTION:
XS GIS Cut Line= 3
      1482091.42      6818037.34      1483028.89      6817807.31
      1483354.43      6817286.45
#Sta/Elev= 30
    3835  2009.3  4168.2  2006.1  4482.4 1997.34  4487.6 1994.87    4524 1995.05
  4529.2 1990.67  4607.2 1990.13  4612.3 1987.03  4639.9 1988.72  4640.4 1988.76
  4653.9 1987.59    4683 1992.59  4695.5 1990.56  4777.3  1992.9  4826.5 1993.56
  4846.6 1992.31  4870.2 1986.13  4901.6 1990.22  4934.8 1992.32  4961.2 1983.56
  4961.7 1983.06  4981.4 1983.56  4986.6 1987.13  5013.8 1989.98  5153.2 1989.71
  5217.8 1993.64  5260.2 1999.34  5306.2 2013.21  5356.4 2014.02  5414.5 2014.22
#Mann= 9 ,-1 , 0
    3835     .07       0  4639.9     .16       0  4640.4     .07       0
  4777.3    .035       0  4826.5     .07       0  4901.6     .16       0
  4961.2     .07       0  4981.4     .16       0  5356.4     .07       0
#XS Ineff= 2 , 0
       0  4913.5    2000               0
Permanent Ineff=
       F       F
Bank Sta=4961.2,4981.4
XS Rating Curve= 0 ,0
Exp/Cntr=0.3,0.1

Type RM Length L Ch R = 1 ,18367   ,564,564,564
BEGIN DESCRIPTION:
NUBIA CREEK 26.0
END DESCRIPTION:
XS GIS Cut Line= 3
      1482095.73      6818102.45        1483105.        6818088.
       1483600.9      6818171.74
#Sta/Elev= 30
  3995.7  2010.2    4035    2008    4145  2007.3    4195  2002.9    4245 2003.61
    4355 1998.64    4395 1998.74    4565 1994.46  4765.1 1994.04  4852.4 1996.51
  4895.1  1993.9  4915.1 1991.23  4925.1 1987.97  4935.1 1986.68  4975.1 1986.84
  4985.1  1985.6  4992.4 1980.98  4992.9 1980.48  5012.7 1980.98  5032.8 1987.19
  5065.9 1987.35    5088 1989.39  5167.3 1995.04  5207.9 2001.42  5238.3 2002.45
  5258.6 2005.64  5279.7 2006.07  5299.2 2010.61  5319.5 2009.59    5508 2008.61
#Mann= 5 ,-1 , 0
  3995.7     .07       0  4852.4     .16       0  4992.4     .07       0
  5012.7     .16       0    5088     .07       0
Bank Sta=4992.4,5012.7
XS Rating Curve= 0 ,0
Exp/Cntr=0.3,0.1

Type RM Length L Ch R = 1 ,17803   ,533,533,533
BEGIN DESCRIPTION:
NUBIA CREEK 25.0
END DESCRIPTION:
XS GIS Cut Line= 3
      1482204.97      6818337.99        1482955.        6818588.
        1483355.        6818438.
#Sta/Elev= 30
  4209.4 2006.98  4230.5 2003.88  4293.8 1999.79  4378.8  1997.4  4517.5 1991.59
    4542 1990.89  4745.3 1988.18    4863 1988.02  4894.6 1989.24  4927.6 1986.91
  4947.3 1985.83  4978.9 1981.52  4987.2 1978.41  4987.7 1977.91  5007.5 1978.41
  5021.4  1979.3  5040.1  1983.4  5045.4  1982.1  5070.3 1985.37  5130.8 1986.81
    5235 1995.08  5256.3 1996.11  5271.5 1995.37  5288.4 1997.68  5317.9 1999.31
  5352.5 2000.99  5373.8 2002.86  5405.8 2002.84    5426 2004.25  5427.2 2004.25
#Mann= 11 ,-1 , 0
  4209.4    .035       0  4378.8     .07       0  4517.5    .035       0
    4542     .07       0  4745.3    .035       0  4927.6     .16       0
  4987.2     .07       0  5007.5     .16       0  5317.9    .035       0
  5352.5     .07       0    5426    .035       0
Bank Sta=4987.2,5007.5
XS Rating Curve= 0 ,0
Exp/Cntr=0.3,0.1

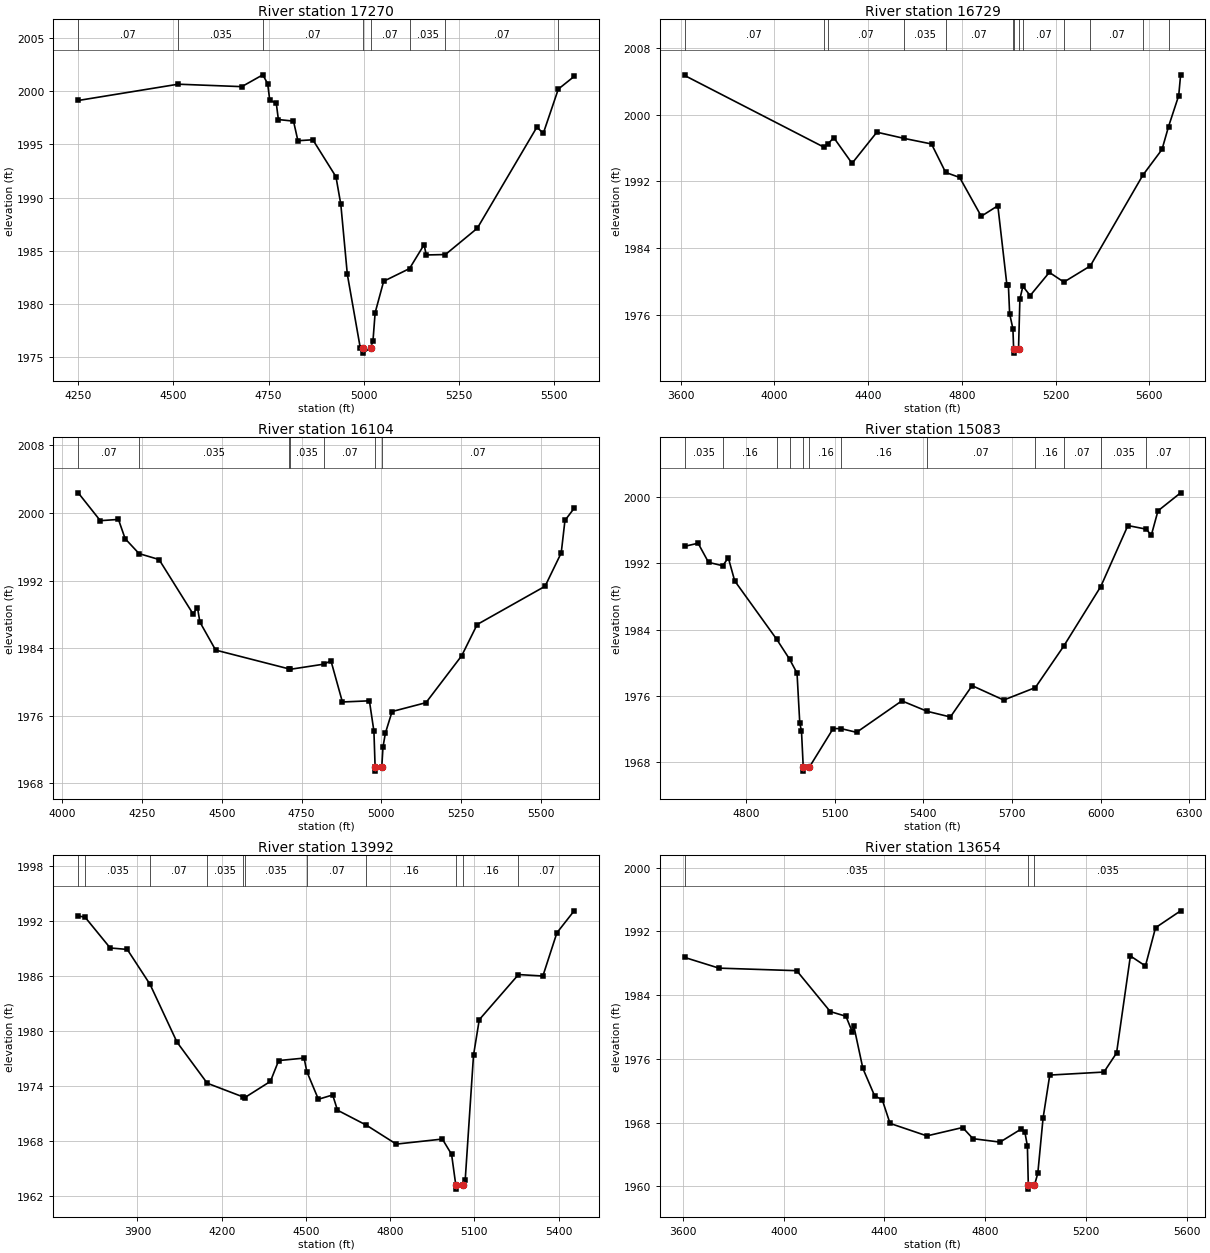
Type RM Length L Ch R = 1 ,17270   ,541,541,541
BEGIN DESCRIPTION:
NUBIA CREEK 24.0
END DESCRIPTION:
XS GIS Cut Line= 3
      1482384.96      6819360.21        1483055.        6819038.
        1483305.        6818538.
#Sta/Elev= 30
  4250.1 1999.12  4512.7 2000.65  4679.7 2000.42  4734.9 2001.53  4747.6  2000.7
  4753.2 1999.13  4770.2 1998.88  4775.8 1997.33  4815.5 1997.18  4827.1 1995.34
  4866.3 1995.43    4927 1991.96  4939.8 1989.36  4956.9 1982.79  4990.8  1975.9
  4997.1 1975.89  4997.6 1975.39    5018 1975.89  5024.3 1976.56  5029.9 1979.18
  5052.3 1982.14  5120.2 1983.33  5158.5 1985.58  5164.1 1984.61  5214.5 1984.65
  5298.2 1987.12  5454.8 1996.62  5471.5 1996.03    5511 2000.19  5552.6 2001.38
#Mann= 8 ,-1 , 0
  4250.1     .07       0  4512.7    .035       0  4734.9     .07       0
  4997.1     .07       0    5018     .07       0  5120.2    .035       0
  5214.5     .07       0    5511    .035       0
Bank Sta=4997.1,5018
XS Rating Curve= 0 ,0
Exp/Cntr=0.3,0.1

Type RM Length L Ch R = 1 ,16729   ,625,625,625
BEGIN DESCRIPTION:
NUBIA CREEK 23.0
END DESCRIPTION:
XS GIS Cut Line= 3
      1482404.97      6820338.03        1483405.        6819388.
        1483755.        6818738.
#Sta/Elev= 30
  3616.5 2004.68  4210.1 1996.11  4227.5 1996.45    4253 1997.24  4331.1 1994.16
  4437.1 1997.89  4554.3 1997.14  4670.4 1996.48  4730.8 1993.07  4790.6 1992.47
  4882.8 1987.82  4953.6 1989.08  4992.4 1979.59  4998.7 1979.59    5004 1976.15
    5018 1974.35  5021.1 1971.93  5021.6 1971.43    5042 1971.93  5047.8 1977.91
  5060.6 1979.44  5091.6 1978.32  5173.5  1981.1  5235.6 1979.94  5348.4 1981.87
    5573 1992.75  5654.6 1995.82  5682.6 1998.57    5726 2002.28  5734.1 2004.76
#Mann= 13 ,-1 , 0
  3616.5     .07       0  4210.1    .035       0  4227.5     .07       0
  4554.3    .035       0  4730.8     .07       0    5018     .16       0
  5021.1     .07       0    5042     .16       0  5060.6     .07       0
  5235.6     .16       0  5348.4     .07       0    5573    .035       0
  5682.6     .07       0
Bank Sta=5021.1,5042
XS Rating Curve= 0 ,0
Exp/Cntr=0.3,0.1

Type RM Length L Ch R = 1 ,16104   ,1021,1021,1021
BEGIN DESCRIPTION:
NUBIA CREEK 22.0
END DESCRIPTION:
XS GIS Cut Line= 3
      1483147.84      6820298.61      1484015.28      6819522.02
        1483955.        6819138.
#Sta/Elev= 30
  4050.7 2002.39  4119.9 1999.09  4176.7 1999.24  4197.6 1996.96  4241.2 1995.19
  4303.8 1994.49    4410 1988.06  4424.2 1988.79  4431.7 1987.08    4481 1983.76
  4711.9 1981.52  4714.2 1981.48  4821.1  1982.1  4842.1  1982.5    4878 1977.61
  4962.5 1977.75  4976.7 1974.14  4980.4 1969.92  4980.9 1969.42  5001.3 1969.92
  5005.1 1972.28  5012.6 1973.92  5033.5 1976.48  5139.7 1977.53  5251.7  1983.1
    5300 1986.79  5512.6 1991.32  5563.2 1995.27  5574.9 1999.12  5603.7 2000.56
#Mann= 7 ,-1 , 0
  4050.7     .07       0  4241.2    .035       0  4711.9     .07       0
  4714.2    .035       0  4821.1     .07       0  4980.4     .07       0
  5001.3     .07       0
Bank Sta=4980.4,5001.3
XS Rating Curve= 0 ,0
Exp/Cntr=0.3,0.1

Type RM Length L Ch R = 1 ,15083   ,1091,1091,1091
BEGIN DESCRIPTION:
NUBIA CREEK 21.0
END DESCRIPTION:
XS GIS Cut Line= 3
        1484355.      6820638.01        1484555.        6820288.
      1484004.99      6819137.98
#Sta/Elev= 30
  4593.1 1994.03  4638.5  1994.4  4673.7  1992.1  4721.8 1991.69  4740.7 1992.65
  4762.3 1989.87  4904.7 1982.82  4947.8 1980.45  4973.2 1978.76  4982.5 1972.73
  4988.3 1971.79  4994.2 1967.46  4994.7 1966.96  5015.3 1967.46  5095.5 1972.09
  5123.3 1972.07  5174.6 1971.63  5327.8 1975.42  5413.7 1974.16    5492 1973.48
  5565.6 1977.25  5672.4 1975.52  5779.5 1977.02  5875.1 1981.99  6000.9 1989.19
  6092.6 1996.53  6155.3 1996.09  6171.7 1995.34  6194.4  1998.3    6271 2000.47
#Mann= 12 ,-1 , 0
  4593.1    .035       0  4721.8     .16       0  4904.7     .07       0
  4947.8     .16       0  4994.2     .07       0  5015.3     .16       0
  5123.3     .16       0  5413.7     .07       0  5779.5     .16       0
  5875.1     .07       0  6000.9    .035       0  6155.3     .07       0
Bank Sta=4994.2,5015.3
XS Rating Curve= 0 ,0
Exp/Cntr=0.3,0.1

Type RM Length L Ch R = 1 ,13992   ,338,338,338
BEGIN DESCRIPTION:
NUBIA CREEK 20.0
END DESCRIPTION:
XS GIS Cut Line= 3
       1484740.7       6820965.5        1485305.        6819788.
        1485205.      6819338.01
#Sta/Elev= 30
  3688.9 1992.56  3713.2 1992.43  3802.8 1989.07  3863.6 1988.91  3944.8  1985.1
    4041 1978.79  4148.5 1974.32  4274.9 1972.84  4282.7 1972.76  4373.6 1974.52
    4403 1976.79  4493.6 1977.06  4503.3 1975.59  4544.5 1972.57  4595.4 1973.04
  4612.4 1971.38  4715.7 1969.74  4821.9 1967.68  4986.1 1968.23    5019 1966.56
  5033.7 1963.27  5034.2 1962.77    5058 1963.27  5067.6 1963.81  5097.1 1977.37
  5117.6 1981.25  5257.3 1986.17  5344.2 1986.01  5394.1 1990.72  5455.6 1993.12
#Mann= 11 ,-1 , 0
  3688.9     .07       0  3713.2    .035       0  3944.8     .07       0
  4148.5    .035       0  4274.9     .07       0  4282.7    .035       0
  4503.3     .07       0  4715.7     .16       0  5033.7     .07       0
    5058     .16       0  5257.3     .07       0
Bank Sta=5033.7,5058
XS Rating Curve= 0 ,0
Exp/Cntr=0.3,0.1

Type RM Length L Ch R = 1 ,13654   ,226,226,226
BEGIN DESCRIPTION:
Mapping XS f96c07d8
END DESCRIPTION:
XS GIS Cut Line= 3
      1485240.69      6821310.17      1485574.03      6819955.97
      1485737.22      6819403.91
#Sta/Elev= 30
  3606.3 1988.74  3742.4  1987.4  4051.4 1987.08  4184.6 1981.95    4247 1981.36
  4272.8 1979.35    4278 1980.17  4314.3 1974.81    4361 1971.37  4391.2 1970.88
  4422.1 1967.92  4568.6 1966.35  4710.5  1967.4  4751.7    1966  4859.2 1965.57
  4942.2 1967.19  4957.6 1966.87  4967.9 1965.07  4971.5 1960.17    4972 1959.67
  4995.9 1960.17  5009.2 1961.65  5030.1 1968.57  5056.7 1973.98    5272 1974.36
  5322.1 1976.75  5377.1 1988.93  5436.8 1987.67  5476.9 1992.47  5576.6 1994.59
#Mann= 3 ,-1 , 0
  3606.3    .035       0  4971.5    .035       0  4995.9    .035       0
Bank Sta=4971.5,4995.9
XS Rating Curve= 0 ,0
Exp/Cntr=0.3,0.1

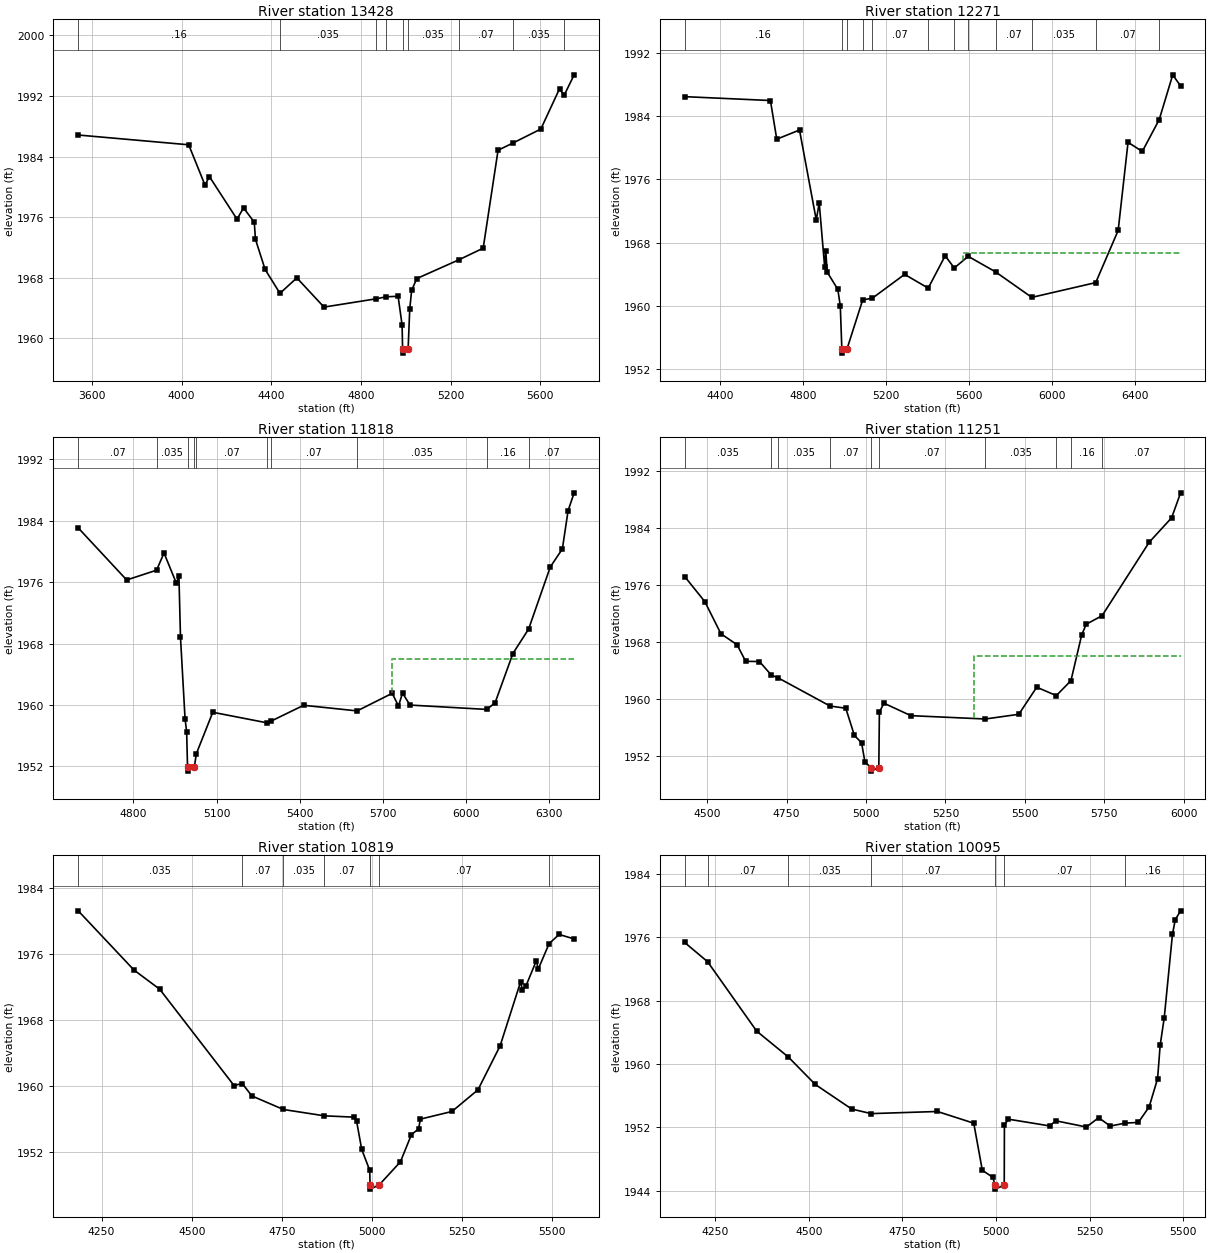
Type RM Length L Ch R = 1 ,13428   ,1157,1157,1157
BEGIN DESCRIPTION:
Mapping XS a331247b
END DESCRIPTION:
XS GIS Cut Line= 3
      1485424.73      6821508.04      1485747.64      6820098.33
      1485966.39      6819365.71
#Sta/Elev= 30
  3539.5 1986.84    4032 1985.55  4104.7 1980.22  4124.3 1981.35  4247.4 1975.72
  4276.4 1977.21  4324.4 1975.33  4329.5 1973.08  4372.5 1969.09  4438.8 1965.93
  4514.1 1967.97  4635.1 1964.11  4866.7  1965.2  4912.3 1965.47  4965.5 1965.54
  4983.3 1961.73  4985.6 1958.53  4986.1 1958.03  5010.1 1958.53  5017.4 1963.86
  5025.8 1966.31  5048.7 1967.88  5235.8 1970.35  5344.8 1971.89  5411.1 1984.83
  5478.7  1985.8  5601.8 1987.63  5685.3 1992.96  5705.2 1992.06  5750.3 1994.79
#Mann= 9 ,-1 , 0
  3539.5     .16       0  4438.8    .035       0  4866.7     .07       0
  4912.3    .035       0  4985.6    .035       0  5010.1    .035       0
  5235.8     .07       0  5478.7    .035       0  5705.2     .07       0
Bank Sta=4985.6,5010.1
XS Rating Curve= 0 ,0
Exp/Cntr=0.3,0.1

Type RM Length L Ch R = 1 ,12271   ,453,453,453
BEGIN DESCRIPTION:
Mapping XS 0149319c
END DESCRIPTION:
XS GIS Cut Line= 4
      1485462.92      6821553.16      1485567.09      6821042.77
      1486278.89      6820806.66       1486629.2      6819741.86
#Sta/Elev= 30
  4228.8 1986.45  4642.3 1985.96  4672.9 1981.07  4782.6 1982.23  4863.4 1970.85
  4877.6 1973.01    4904 1964.87  4909.3 1966.94  4916.1 1964.26  4967.4 1962.07
  4979.3 1959.97  4986.8 1954.51  4987.3 1954.01  5011.3 1954.51  5087.4 1960.75
    5134 1960.96  5289.5 1963.97  5403.3 1962.23    5485 1966.32  5528.9 1964.78
  5596.4 1966.25  5727.9 1964.29  5902.9 1961.06  6211.2 1962.93  6319.4 1969.53
    6367 1980.67  6435.8 1979.52  6517.3 1983.54  6582.6 1989.21  6620.6 1987.79
#Mann= 12 ,-1 , 0
  4228.8     .16       0  4986.8     .07       0  5011.3     .16       0
  5087.4    .035       0    5134     .07       0  5403.3    .035       0
  5528.9     .07       0  5596.4    .035       0  5727.9     .07       0
  5902.9    .035       0  6211.2     .07       0  6517.3    .035       0
#XS Ineff= 2 , 0
       0                  5572.2       0 1966.64
Permanent Ineff=
       F       F
Bank Sta=4986.8,5011.3
XS Rating Curve= 0 ,0
Exp/Cntr=0.3,0.1

Type RM Length L Ch R = 1 ,11818   ,567,567,567
BEGIN DESCRIPTION:
NUBIA CREEK 16.0
END DESCRIPTION:
XS GIS Cut Line= 3
      1485872.63       6821643.5        1486055.        6821288.
      1487155.01      6820437.99
#Sta/Elev= 30
  4600.5 1983.07  4775.4 1976.28  4883.3 1977.56  4910.1  1979.8  4955.1 1975.83
  4963.9 1976.84  4969.6 1968.79  4986.1 1958.17  4991.8 1956.52    4995 1951.87
  4995.5 1951.37  5019.5 1951.87  5026.7 1953.63  5086.1 1959.04  5282.5 1957.66
  5297.8 1957.91  5413.9 1959.95  5607.1 1959.22  5733.6 1961.51  5756.3 1959.86
  5770.8 1961.54  5797.9 1959.98    6075 1959.41  6104.9 1960.28  6169.2  1966.7
  6225.8 1969.88  6304.1 1977.98  6347.6 1980.32  6368.4 1985.33  6390.2 1987.64
#Mann= 10 ,-1 , 0
  4600.5     .07       0  4883.3    .035       0    4995    .035       0
  5019.5    .035       0  5026.7     .07       0  5282.5    .035       0
  5297.8     .07       0  5607.1    .035       0    6075     .16       0
  6225.8     .07       0
#XS Ineff= 2 , 0
       0                  5733.6       0    1966
Permanent Ineff=
       F       F
Bank Sta=4995,5019.5
XS Rating Curve= 0 ,0
Exp/Cntr=0.3,0.1

Type RM Length L Ch R = 1 ,11251   ,432,432,432
BEGIN DESCRIPTION:
NUBIA CREEK 15.0
END DESCRIPTION:
XS GIS Cut Line= 3
      1486204.98      6821738.03        1486555.        6821288.
      1487255.02      6820587.98
#Sta/Elev= 30
  4429.6 1977.17    4493 1973.65  4543.7 1969.14  4594.3 1967.61  4621.5 1965.28
  4664.9 1965.25  4702.3 1963.34    4724 1962.95  4886.9 1959.01  4936.4  1958.7
  4963.5 1954.89  4986.1 1953.85  4996.6 1951.16  5015.8 1950.38  5016.3 1949.88
  5040.3 1950.38  5042.1 1958.14  5056.3 1959.41  5141.1 1957.66  5375.1 1957.19
  5480.6 1957.85  5537.1 1961.65  5598.7 1960.47  5644.7 1962.57  5678.5 1968.98
  5692.7 1970.48  5742.7 1971.68  5890.7 1981.97  5961.4 1985.41  5989.7 1988.91
#Mann= 10 ,-1 , 0
  4429.6    .035       0  4702.3     .07       0    4724    .035       0
  4886.9     .07       0  5015.8     .07       0  5040.3     .07       0
  5375.1    .035       0  5598.7     .07       0  5644.7     .16       0
  5742.7     .07       0
#XS Ineff= 2 , 0
       0                  5339.1       0    1966
Permanent Ineff=
       F       F
Bank Sta=5015.8,5040.3
XS Rating Curve= 0 ,0
Exp/Cntr=0.3,0.1

Type RM Length L Ch R = 1 ,10819   ,724,724,724
BEGIN DESCRIPTION:
NUBIA CREEK 14.0
END DESCRIPTION:
XS GIS Cut Line= 3
      1486251.09      6822081.86       1486878.2      6821561.64
      1487425.61       6821441.2
#Sta/Elev= 30
  4185.2 1981.27  4339.9 1974.07  4411.2 1971.74  4617.3 1960.03  4640.1 1960.28
  4666.7 1958.77  4754.3 1957.12  4868.1 1956.35  4950.6 1956.19  4957.1 1955.72
  4971.4 1952.26  4993.6 1949.73  4994.5 1947.94    4995 1947.44  5019.5 1947.94
  5078.6 1950.75  5109.3 1954.07    5129 1954.76  5134.1 1955.95  5221.6 1956.88
  5293.7 1959.51  5355.1 1964.85    5412 1972.64  5417.1 1971.66  5426.8 1972.14
  5455.7 1975.21  5460.8 1974.17    5491 1977.28  5518.9  1978.4  5560.5 1977.85
#Mann= 7 ,-1 , 0
  4185.2    .035       0  4640.1     .07       0  4754.3    .035       0
  4868.1     .07       0  4994.5     .07       0  5019.5     .07       0
    5491    .035       0
Bank Sta=4994.5,5019.5
XS Rating Curve= 0 ,0
Exp/Cntr=0.3,0.1

Type RM Length L Ch R = 1 ,10095   ,858,858,858
BEGIN DESCRIPTION:
NUBIA CREEK 13.0
END DESCRIPTION:
XS GIS Cut Line= 3
       1486550.6       6822438.6        1487305.        6822088.
      1487504.98      6821638.03
#Sta/Elev= 30
  4168.4 1975.35  4229.6 1972.92  4360.7 1964.15  4445.2 1960.88  4517.2 1957.41
  4614.3 1954.31  4666.3 1953.73  4843.2    1954  4940.3 1952.52  4963.2 1946.57
  4991.6 1945.67  4996.7 1944.69  4997.2 1944.19  5021.7 1944.69  5022.2 1952.25
  5032.4 1953.03  5142.6 1952.18  5159.7 1952.82    5241 1952.04  5273.9 1953.21
  5304.7 1952.16  5345.2 1952.53  5379.9 1952.62  5408.6 1954.58  5431.2 1958.14
    5438 1962.34    5449 1965.86  5470.9 1976.38  5478.4 1978.24  5492.7 1979.35
#Mann= 7 ,-1 , 0
  4168.4    .035       0  4229.6     .07       0  4445.2    .035       0
  4666.3     .07       0  4996.7     .07       0  5021.7     .07       0
  5345.2     .16       0
Bank Sta=4996.7,5021.7
XS Rating Curve= 0 ,0
Exp/Cntr=0.3,0.1

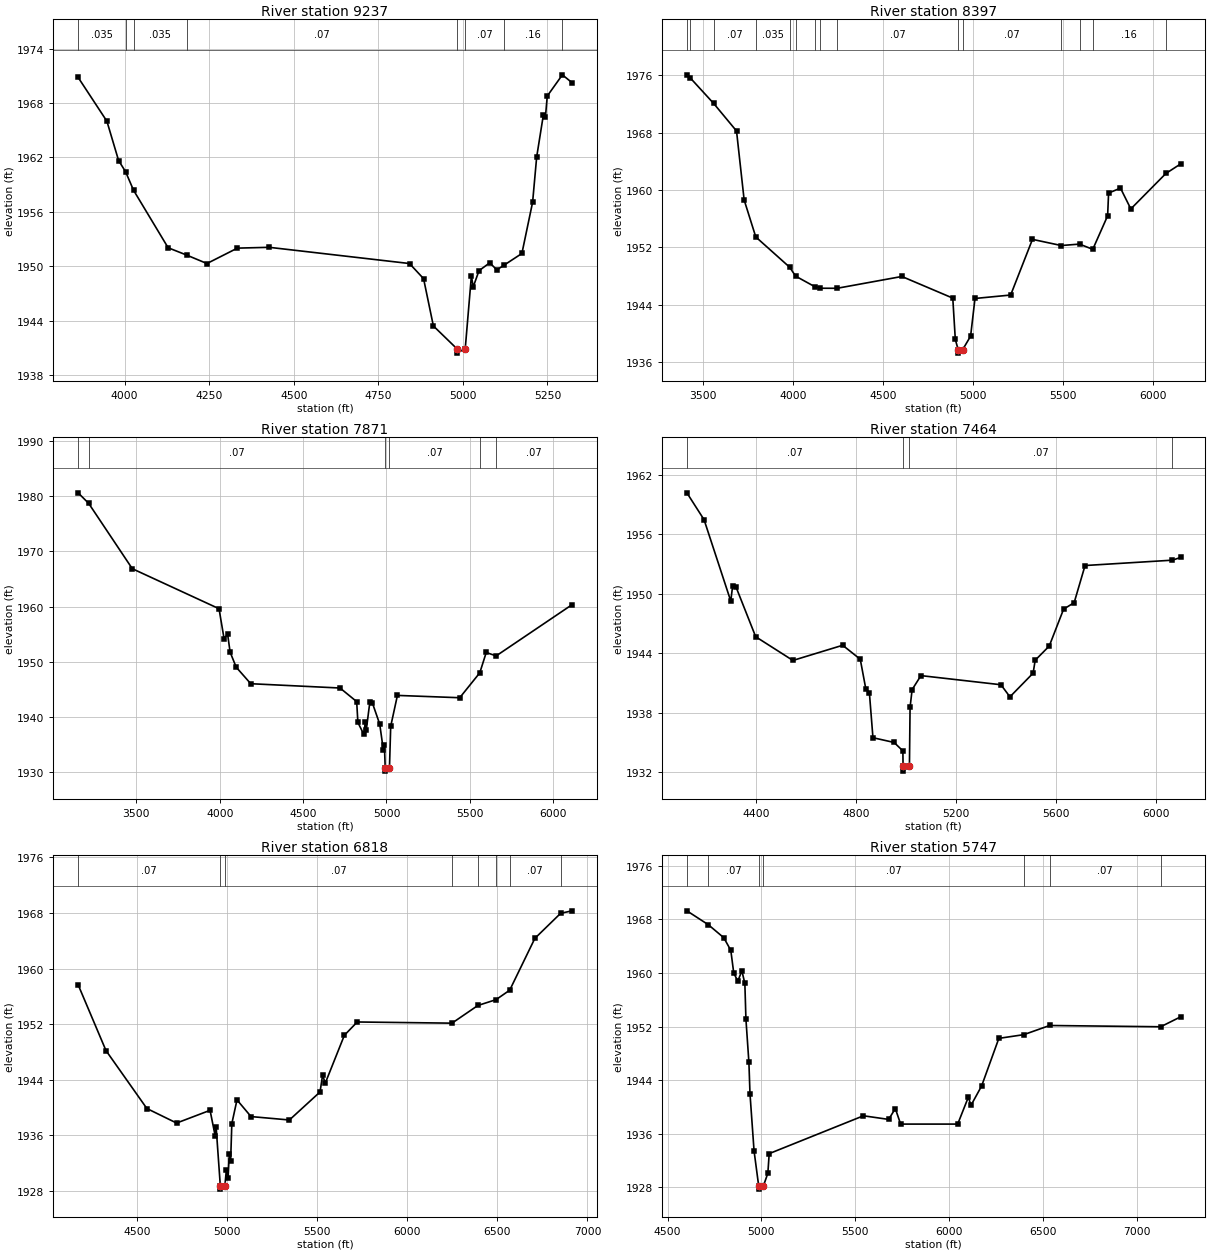
Type RM Length L Ch R = 1 ,9237    ,840,840,840
BEGIN DESCRIPTION:
NUBIA CREEK 12.0
END DESCRIPTION:
XS GIS Cut Line= 3
      1487555.02      6822837.96      1488007.19      6821786.48
      1487904.99      6821487.98
#Sta/Elev= 30
  3862.4 1970.84  3947.5    1966  3982.1 1961.66  4002.7 1960.43  4026.3 1958.38
  4128.6 1952.03  4182.9 1951.23  4243.3 1950.29  4333.3 1951.99  4427.4 1952.08
  4842.2 1950.29  4883.8 1948.62  4912.8  1943.4  4981.9  1940.9  4982.4  1940.4
    5007  1940.9  5025.2 1948.94  5030.5  1947.7  5047.7  1949.5  5079.4 1950.37
  5100.5 1949.59  5120.9 1950.09  5174.5  1951.4  5206.2 1957.06  5218.2 1962.05
  5237.9 1966.67  5244.2  1966.5  5249.5 1968.78  5294.2 1971.12  5322.5 1970.26
#Mann= 8 ,-1 , 0
  3862.4    .035       0  4002.7     .07       0  4026.3    .035       0
  4182.9     .07       0  4981.9     .07       0    5007     .07       0
  5120.9     .16       0  5294.2     .07       0
Bank Sta=4981.9,5007
XS Rating Curve= 0 ,0
Exp/Cntr=0.3,0.1

Type RM Length L Ch R = 1 ,8397    ,526,526,526
BEGIN DESCRIPTION:
NUBIA CREEK 11.0
END DESCRIPTION:
XS GIS Cut Line= 3
      1487505.02      6823037.98        1488655.        6821938.
      1488986.16      6820832.28
#Sta/Elev= 30
  3408.9 1976.09  3426.2  1975.7    3558 1972.09  3684.9 1968.25  3727.2 1958.63
  3791.9 1953.46  3980.4 1949.23  4013.3 1947.99  4121.2  1946.5    4151  1946.3
  4243.8 1946.29  4604.1 1947.94  4887.2 1944.92  4901.3 1939.15    4917 1937.74
  4917.5 1937.24  4942.4 1937.74  4986.3 1939.61  5010.7 1944.87    5209 1945.35
  5330.2 1953.12  5490.4 1952.26  5591.8 1952.46  5665.5 1951.73  5748.1 1956.41
  5753.4 1959.58  5819.5 1960.28  5877.1 1957.37  6072.1 1962.32  6154.5 1963.66
#Mann= 15 ,-1 , 0
  3408.9     .07       0  3426.2    .035       0    3558     .07       0
  3791.9    .035       0  3980.4     .07       0  4013.3    .035       0
  4121.2     .07       0    4151    .035       0  4243.8     .07       0
    4917     .07       0  4942.4     .07       0  5490.4    .035       0
  5591.8     .07       0  5665.5     .16       0  6072.1     .07       0
Bank Sta=4917,4942.4
XS Rating Curve= 0 ,0
Exp/Cntr=0.3,0.1

Type RM Length L Ch R = 1 ,7871    ,407,407,407
BEGIN DESCRIPTION:
NUBIA CREEK 10.0
END DESCRIPTION:
XS GIS Cut Line= 3
        1488105.      6823688.01        1489105.        6822138.
      1489218.96      6821026.62
#Sta/Elev= 30
  3150.8 1980.62  3213.9 1978.72  3475.8 1966.87  3995.9 1959.62  4026.2  1954.2
  4047.4 1955.01  4062.5 1951.75  4098.8 1949.03  4186.2 1946.03  4721.7 1945.25
  4821.5 1942.79  4828.8 1939.01  4864.5 1936.83    4873 1939.07  4878.9 1937.61
  4900.2 1942.64  4915.2 1942.59  4959.7 1938.71  4981.9 1933.94  4987.8 1934.98
  4992.7 1930.69  4993.2 1930.19  5018.1 1930.69  5025.6 1938.31  5065.8 1943.91
  5439.6 1943.49  5559.9 1948.01  5598.5 1951.69  5658.1 1951.07  6112.6 1960.34
#Mann= 6 ,-1 , 0
  3150.8    .035       0  3213.9     .07       0  4992.7     .07       0
  5018.1     .07       0  5559.9    .035       0  5658.1     .07       0
Bank Sta=4992.7,5018.1
XS Rating Curve= 0 ,0
Exp/Cntr=0.3,0.1

Type RM Length L Ch R = 1 ,7464    ,646,646,646
BEGIN DESCRIPTION:
NUBIA CREEK 9.0
END DESCRIPTION:
XS GIS Cut Line= 3
      1488634.11      6823004.39      1489308.62      6822439.26
       1490176.3      6821772.22
#Sta/Elev= 30
  4123.7 1960.19  4192.4 1957.48  4299.1 1949.28  4306.8 1950.83  4320.5 1950.67
  4398.8 1945.68  4547.6 1943.29  4746.6 1944.82  4816.9 1943.41    4839 1940.43
  4853.3 1940.05  4867.6  1935.5  4952.2 1935.02  4987.3 1934.17    4988 1932.63
  4988.5 1932.13  5013.5 1932.63    5016 1938.55  5024.2 1940.35  5059.5 1941.76
  5379.3 1940.84  5415.3 1939.62    5508 1942.01  5516.2 1943.31  5572.4 1944.74
  5629.8 1948.46  5672.1 1949.12  5715.6 1952.86  6064.9  1953.4  6098.1 1953.68
#Mann= 4 ,-1 , 0
  4123.7     .07       0    4988     .07       0  5013.5     .07       0
  6064.9    .035       0
Bank Sta=4988,5013.5
XS Rating Curve= 0 ,0
Exp/Cntr=0.3,0.1

Type RM Length L Ch R = 1 ,6818    ,1071,1071,1071
BEGIN DESCRIPTION:
NUBIA CREEK 8.0
END DESCRIPTION:
XS GIS Cut Line= 3
      1488754.97      6823038.01        1489555.        6822838.
      1490805.02      6821387.98
#Sta/Elev= 30
  4174.7 1957.68  4329.3 1948.21  4556.1 1939.88    4721 1937.79  4906.6 1939.62
  4934.9 1935.95  4940.1 1937.27  4963.4 1928.79  4963.9 1928.29  4988.9 1928.79
  4996.8 1931.01  5006.5 1929.93  5013.1  1933.3  5020.7 1932.33  5027.3  1937.7
  5055.9 1941.12  5133.8 1938.72  5346.6 1938.23  5516.6 1942.26  5530.9 1944.71
  5545.2  1943.5  5651.6 1950.41  5722.9 1952.32  6248.4 1952.15  6391.9 1954.69
  6492.7 1955.53  6568.5 1956.89  6708.1 1964.34  6850.9 1967.94  6913.8  1968.3
#Mann= 8 ,-1 , 0
  4174.7     .07       0  4963.4     .07       0  4988.9     .07       0
  6248.4    .035       0  6391.9     .07       0  6492.7    .035       0
  6568.5     .07       0  6850.9    .035       0
Bank Sta=4963.4,4988.9
XS Rating Curve= 0 ,0
Exp/Cntr=0.3,0.1

Type RM Length L Ch R = 1 ,5747    ,628,628,628
BEGIN DESCRIPTION:
NUBIA CREEK 7.0
END DESCRIPTION:
XS GIS Cut Line= 3
        1488805.        6823688.        1489155.        6823488.
      1490705.01      6821887.99
#Sta/Elev= 30
  4603.2 1969.28  4717.2 1967.21  4799.7 1965.27  4837.2 1963.38    4853 1959.96
  4874.6  1958.8  4896.2 1960.31    4912 1958.45  4917.8 1953.08  4933.6 1946.65
  4939.4 1941.97    4961 1933.45  4985.6 1928.23  4986.1 1927.73  5011.1 1928.23
  5034.5  1930.1  5041.7 1933.03  5543.8 1938.68  5678.1 1938.14  5713.6 1939.76
  5741.9 1937.44  6045.9 1937.44  6102.5 1941.45  6116.7 1940.24  6173.3 1943.13
  6265.1 1950.24  6397.7 1950.79  6535.7 1952.16  7127.2 1951.97    7234 1953.46
#Mann= 7 ,-1 , 0
  4603.2    .035       0  4717.2     .07       0  4985.6     .07       0
  5011.1     .07       0  6397.7    .035       0  6535.7     .07       0
  7127.2    .035       0
Bank Sta=4985.6,5011.1
XS Rating Curve= 0 ,0
Exp/Cntr=0.3,0.1