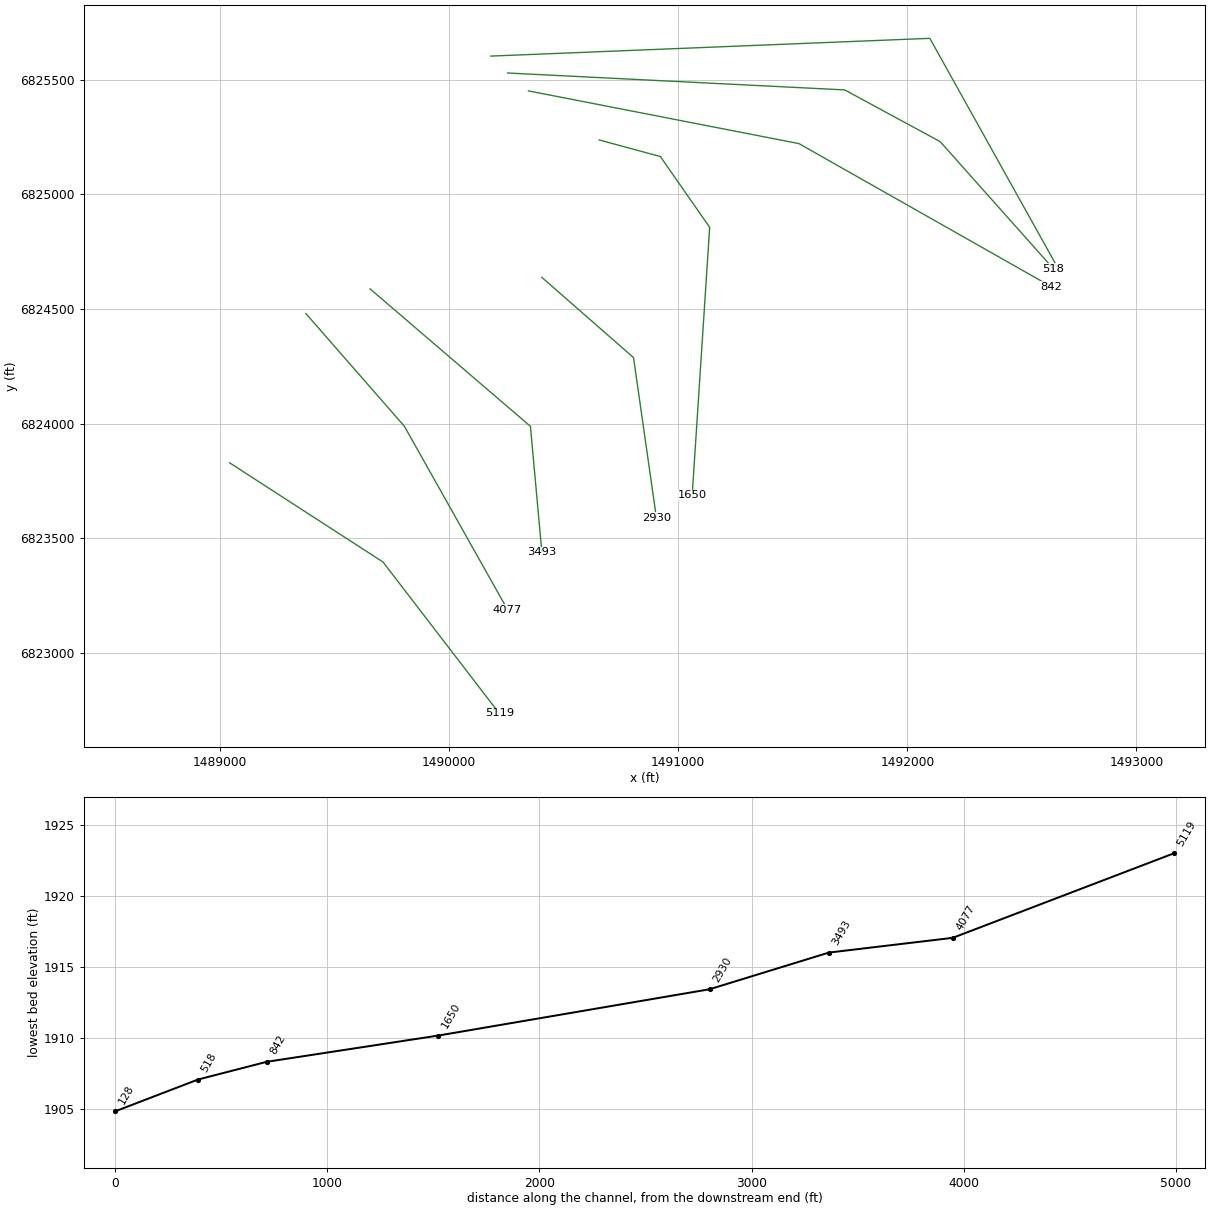
HEC-RAS study NUBIA CREEK.prj: NUBIA CREEK Base Level Engineering

--- NUBIA CREEK.g01 (geometry) --- (continued)

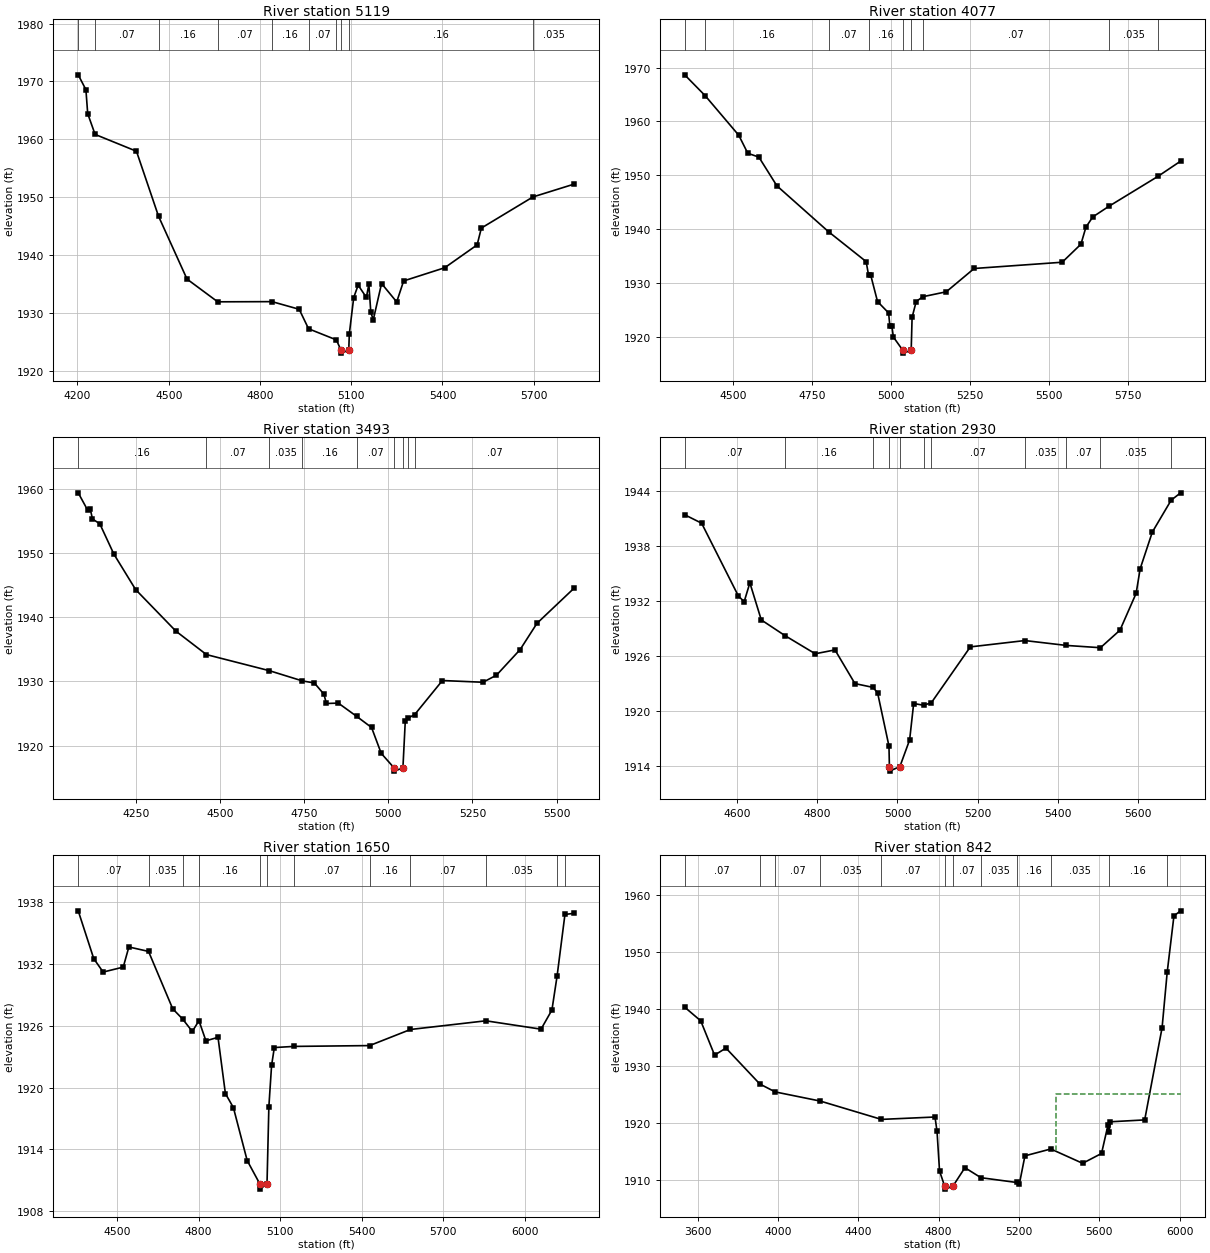
Type RM Length L Ch R = 1 ,5119    ,1042,1042,1042
BEGIN DESCRIPTION:
NUBIA CREEK 6.0
END DESCRIPTION:
XS GIS Cut Line= 3
      1489041.89      6823828.74      1489711.57      6823395.69
      1490218.93      6822735.03
#Sta/Elev= 30
  4202.5 1971.13  4227.8 1968.56  4233.7 1964.42    4258 1960.83    4394 1957.92
  4466.5 1946.69  4560.2 1935.82  4661.1 1931.89  4839.7 1931.92    4929  1930.6
  4959.8 1927.23  5051.2 1925.31  5066.5 1923.52    5067 1923.02    5092 1923.52
  5093.8 1926.35  5108.3 1932.63  5122.8 1934.77  5149.9 1932.65  5158.1 1934.92
  5164.5 1930.05  5172.7  1928.8  5199.8 1935.05  5249.6 1931.87  5272.4  1935.5
  5407.4 1937.78    5514 1941.73  5527.9 1944.64  5697.5 1950.02    5833 1952.24
#Mann= 10 ,-1 , 0
  4202.5    .035       0    4258     .07       0  4466.5     .16       0
  4661.1     .07       0  4839.7     .16       0  4959.8     .07       0
  5051.2     .16       0  5066.5     .07       0    5092     .16       0
  5697.5    .035       0
Bank Sta=5066.5,5092
XS Rating Curve= 0 ,0
Exp/Cntr=0.3,0.1

Type RM Length L Ch R = 1 ,4077    ,584,584,584
BEGIN DESCRIPTION:
NUBIA CREEK 5.0
END DESCRIPTION:
XS GIS Cut Line= 3
      1489375.21      6824479.79        1489805.        6823988.
        1490255.        6823188.
#Sta/Elev= 30
    4347 1968.65  4411.8 1964.79  4518.4 1957.44  4546.9 1954.11    4582  1953.4
    4639 1948.08  4802.6 1939.57  4921.8 1934.03  4929.6 1931.49  4936.1 1931.56
  4957.9 1926.62    4993 1924.51  4996.8 1922.18    5003 1922.18  5008.1 1920.04
  5038.3 1917.56  5038.8 1917.06  5064.5 1917.56  5067.4  1923.7  5080.4 1926.63
  5101.6 1927.52  5175.7 1928.43    5264 1932.75  5542.9 1933.91  5602.2 1937.25
  5618.1 1940.42  5639.8 1942.31  5691.4  1944.3  5845.7 1949.81    5918 1952.65
#Mann= 9 ,-1 , 0
    4347     .07       0  4411.8     .16       0  4802.6     .07       0
  4929.6     .16       0  5038.3     .07       0  5064.5     .16       0
  5101.6     .07       0  5691.4    .035       0  5845.7     .07       0
Bank Sta=5038.3,5064.5
XS Rating Curve= 0 ,0
Exp/Cntr=0.3,0.1

Type RM Length L Ch R = 1 ,3493    ,563,563,563
BEGIN DESCRIPTION:
NUBIA CREEK 4.0
END DESCRIPTION:
XS GIS Cut Line= 3
        1489655.        6824588.        1490355.        6823988.
        1490405.      6823438.03
#Sta/Elev= 30
    4078 1959.39    4106  1956.7  4113.7 1956.91  4120.3 1955.32  4142.2 1954.56
  4183.9 1949.85  4248.7 1944.31  4368.3 1937.84  4459.2 1934.18  4646.4 1931.67
  4744.2 1930.08  4779.9 1929.76  4808.4 1928.01  4815.6 1926.56  4851.2 1926.62
  4905.3 1924.57    4950 1922.82  4978.6  1918.8    5017 1916.52  5017.5 1916.02
  5043.2 1916.52  5050.2 1923.81  5057.2 1924.24  5078.3 1924.84  5160.6 1930.14
  5281.1 1929.87  5321.3 1930.97  5391.6 1934.96  5441.8 1939.06  5552.2 1944.54
#Mann= 9 ,-1 , 0
    4078     .16       0  4459.2     .07       0  4646.4    .035       0
  4744.2     .16       0  4905.3     .07       0    5017     .07       0
  5043.2     .07       0  5057.2     .16       0  5078.3     .07       0
Bank Sta=5017,5043.2
XS Rating Curve= 0 ,0
Exp/Cntr=0.3,0.1

Type RM Length L Ch R = 1 ,2930    ,1280,1280,1280
BEGIN DESCRIPTION:
NUBIA CREEK 3.0
END DESCRIPTION:
XS GIS Cut Line= 3
      1490404.99      6824638.01        1490805.        6824288.
        1490905.      6823588.03
#Sta/Elev= 30
  4468.5 1941.37  4510.8 1940.45  4602.8  1932.5  4617.1  1931.9  4631.3 1933.95
  4659.8 1929.91  4718.6 1928.21  4794.5 1926.22  4843.9 1926.64  4893.7 1922.97
  4938.4 1922.56  4950.2 1921.98  4978.7 1916.16  4979.8 1913.93  4980.3 1913.43
    5006 1913.93  5030.3 1916.83  5040.4  1920.8  5065.1 1920.61  5084.5 1920.88
  5181.9 1926.97  5318.1 1927.66  5421.3 1927.13  5506.9 1926.88  5555.6 1928.79
    5596 1932.81  5606.1 1935.49  5636.4 1939.48  5683.5 1942.96  5707.1 1943.76
#Mann= 11 ,-1 , 0
  4468.5     .07       0  4718.6     .16       0  4938.4     .07       0
  4979.8     .07       0    5006     .07       0  5065.1     .16       0
  5084.5     .07       0  5318.1    .035       0  5421.3     .07       0
  5506.9    .035       0  5683.5     .07       0
Bank Sta=4979.8,5006
XS Rating Curve= 0 ,0
Exp/Cntr=0.3,0.1

Type RM Length L Ch R = 1 ,1650    ,808,808,808
BEGIN DESCRIPTION:
NUBIA CREEK 2.0
END DESCRIPTION:
XS GIS Cut Line= 4
      1490654.97      6825238.01      1490922.08      6825165.56
      1491137.36      6824856.53      1491060.97       6823686.4
#Sta/Elev= 30
  4356.5 1937.11  4413.7 1932.48  4448.3 1931.18  4522.3 1931.66    4543 1933.61
  4615.4 1933.18  4704.5 1927.62  4740.7 1926.64  4776.5 1925.43  4801.1 1926.47
  4826.7 1924.52  4871.2 1924.86  4898.4 1919.42  4927.9 1918.05  4978.6 1912.93
  5025.3 1910.66  5025.8 1910.16  5051.6 1910.66  5058.5 1918.16  5068.5 1922.15
  5078.6 1923.87  5150.4 1923.98  5429.4 1924.06  5579.8 1925.62  5857.5 1926.46
  6060.6 1925.65  6100.7 1927.51  6119.7  1930.8  6148.6 1936.76  6182.5 1936.87
#Mann= 12 ,-1 , 0
  4356.5     .07       0  4615.4    .035       0  4740.7     .07       0
  4801.1     .16       0  5025.3     .07       0  5051.6     .16       0
  5150.4     .07       0  5429.4     .16       0  5579.8     .07       0
  5857.5    .035       0  6119.7     .07       0  6148.6    .035       0
Bank Sta=5025.3,5051.6
XS Rating Curve= 0 ,0
Exp/Cntr=0.3,0.1

Type RM Length L Ch R = 1 ,842     ,324,324,324
BEGIN DESCRIPTION:
Mapping XS 8456b640
END DESCRIPTION:
XS GIS Cut Line= 3
      1490346.56      6825452.02      1491527.11      6825221.98
      1492629.52        6824597.
#Sta/Elev= 30
  3535.3  1940.3  3615.2  1937.9  3684.2 1931.87  3740.9 1933.11  3909.6 1926.79
  3986.3  1925.4  4210.9 1923.79  4515.1 1920.57    4782 1920.99  4792.1 1918.48
  4804.6  1911.5  4830.3 1908.81  4831.3 1908.31  4870.9 1908.81    4931 1912.08
  5010.8 1910.32  5188.4 1909.48  5201.8 1909.15  5229.9 1914.16  5358.8 1915.37
  5517.3 1912.85  5611.4 1914.58  5643.2 1919.52  5648.5 1918.28  5655.2 1920.15
  5826.4 1920.48    5913 1936.69  5938.4 1946.43  5972.1 1956.36  6005.3 1957.24
#Mann= 12 ,-1 , 0
  3535.3     .07       0  3909.6    .035       0  3986.3     .07       0
  4210.9    .035       0  4515.1     .07       0  4830.3     .07       0
  4870.9     .07       0  5010.8    .035       0  5188.4     .16       0
  5358.8    .035       0  5648.5     .16       0  5938.4     .07       0
#XS Ineff= 2 , 0
       0                    5385       0    1925
Permanent Ineff=
       F       F
Bank Sta=4830.3,4870.9
XS Rating Curve= 0 ,0
Exp/Cntr=0.3,0.1

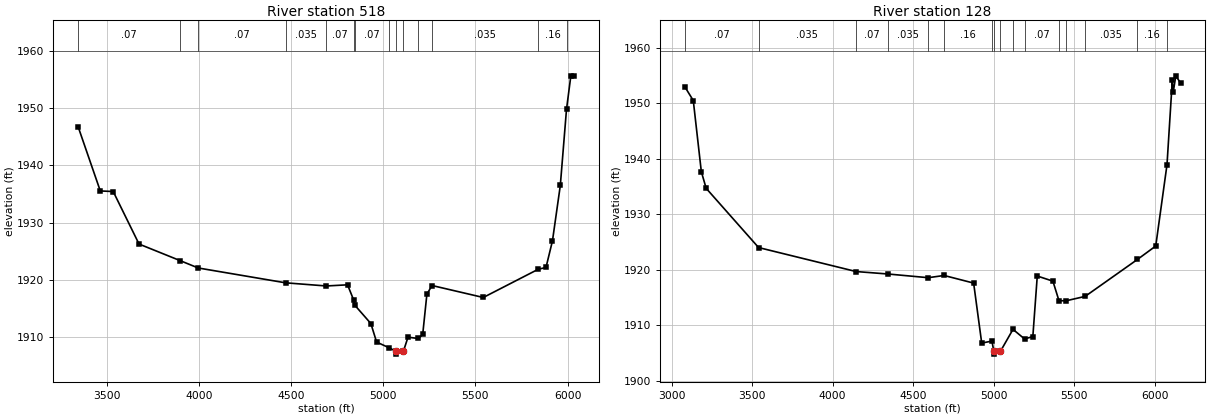
Type RM Length L Ch R = 1 ,518     ,390,390,390
BEGIN DESCRIPTION:
Mapping XS fd5cb675
END DESCRIPTION:
XS GIS Cut Line= 4
      1490255.37      6825530.14      1491726.77      6825456.36
      1492143.43      6825230.66      1492638.25      6824675.08
#Sta/Elev= 30
  3344.8 1946.72  3464.6 1935.55  3534.7 1935.45  3674.8 1926.28  3896.7  1923.4
    3996  1922.1  4470.1 1919.51  4690.8 1918.96  4806.3 1919.16  4839.7 1916.49
  4844.9 1915.63  4932.8  1912.4  4963.9 1909.17  5032.9 1908.15  5068.6 1907.56
  5069.6 1907.06  5109.3 1907.56  5134.4 1910.02  5190.1 1909.79  5214.1 1910.49
  5236.8 1917.52  5264.7 1919.04  5542.8 1916.95  5841.1 1921.88  5883.1 1922.19
  5918.2 1926.84  5960.8 1936.51  5994.4  1949.8  6017.7 1955.58  6035.9 1955.65
#Mann= 14 ,-1 , 0
  3344.8     .07       0  3896.7    .035       0    3996     .07       0
  4470.1    .035       0  4690.8     .07       0  4839.7    .035       0
  4844.9     .07       0  5032.9    .035       0  5068.6     .07       0
  5109.3    .035       0  5190.1     .16       0  5264.7    .035       0
  5841.1     .16       0  5994.4     .07       0
Bank Sta=5068.6,5109.3
XS Rating Curve= 0 ,0
Exp/Cntr=0.3,0.1

Type RM Length L Ch R = 1 ,128     ,0,0,0
BEGIN DESCRIPTION:
NUBIA CREEK 1.0
END DESCRIPTION:
XS GIS Cut Line= 3
      1490181.63      6825603.93      1492098.27      6825681.46
      1492664.28       6824666.4
#Sta/Elev= 30
  3081.8 1953.03  3135.2 1950.51  3185.2 1937.69  3215.3 1934.69  3540.9 1924.02
  4146.3  1919.7  4346.7 1919.25  4594.3 1918.59  4693.2 1918.99  4876.6 1917.62
  4926.7 1906.81  4990.1 1907.17  5002.3 1905.32  5003.3 1904.82    5043 1905.32
    5121 1909.28  5192.7 1907.56  5244.3 1907.98  5271.8 1918.89  5368.9 1917.97
  5406.8 1914.43  5452.3 1914.44  5569.1 1915.22  5894.1 1921.88  6007.7  1924.3
  6077.6 1938.95  6110.6 1954.17  6116.3 1952.03  6132.3 1954.96  6162.2 1953.65
#Mann= 16 ,-1 , 0
  3081.8     .07       0  3540.9    .035       0  4146.3     .07       0
  4346.7    .035       0  4594.3     .07       0  4693.2     .16       0
  4990.1     .07       0  5002.3     .07       0    5043     .07       0
    5121     .16       0  5192.7     .07       0  5406.8     .16       0
  5452.3     .07       0  5569.1    .035       0  5894.1     .16       0
  6077.6     .07       0
Bank Sta=5002.3,5043
XS Rating Curve= 0 ,0
Exp/Cntr=0.3,0.1

Chan Stop Cuts=-1
Use User Specified Reach Order=0
Composite Channel Slope=5