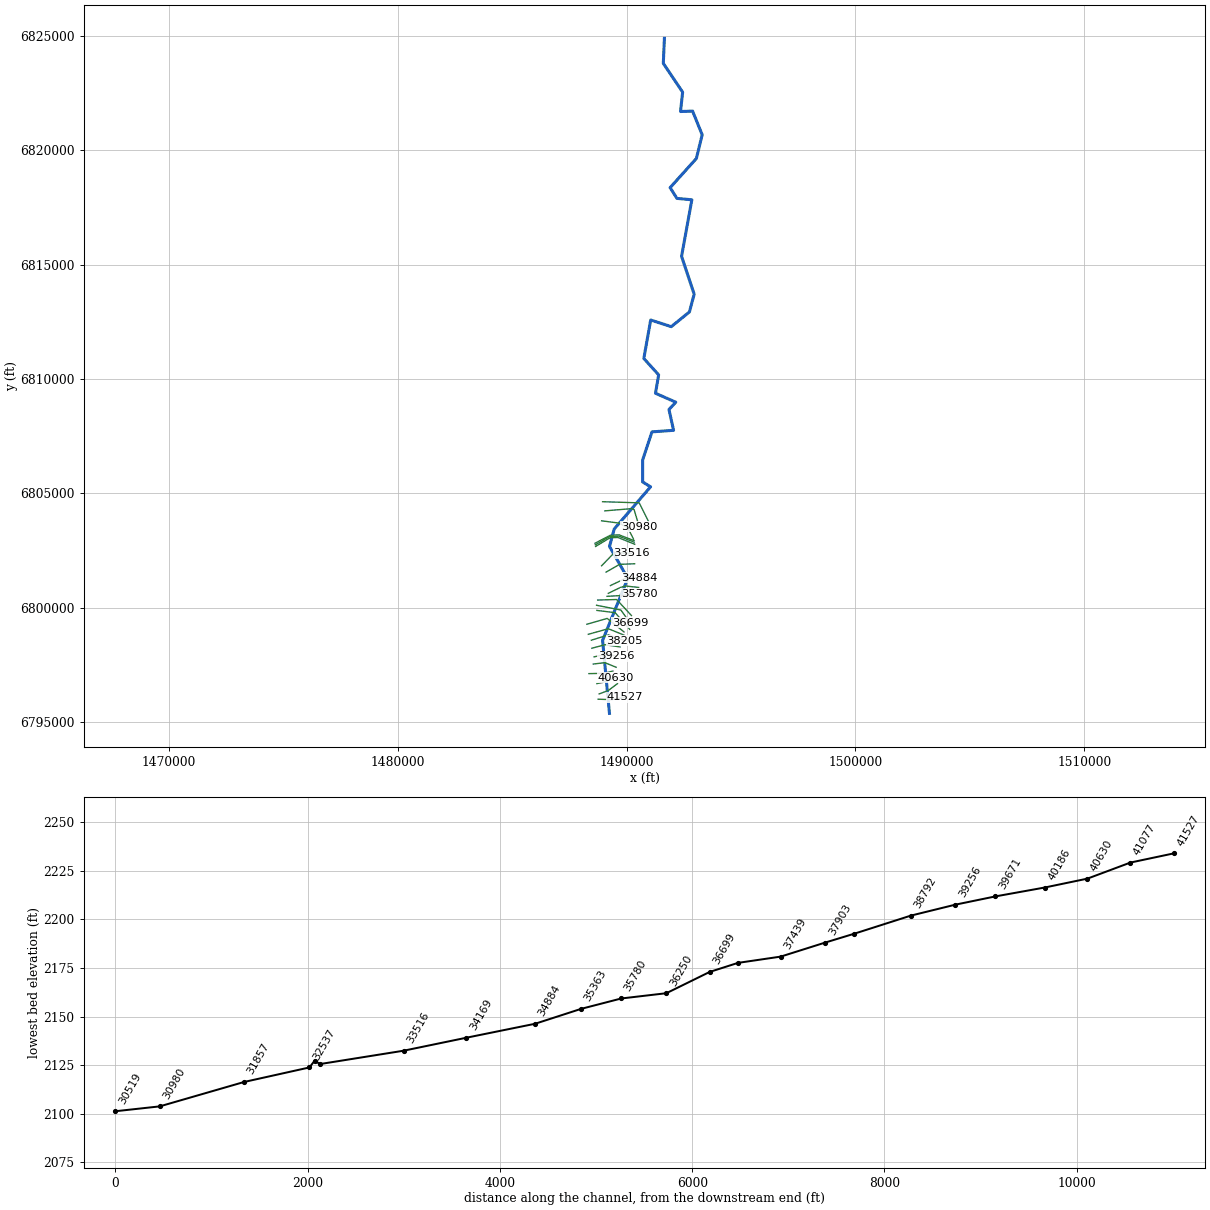
--- NUBIA CREEK TRIBUTARY 1.prj (project) ---

Proj Title=NUBIA CREEK TRIBUTARY 1 Base Level Engineering
Current Plan=p01
Default Exp/Contr=0.3,0.1
English Units
Geom File=g01
Flow File=f01
Plan File=p01
Y Axis Title=Elevation
X Axis Title(PF)=Main Channel Distance
X Axis Title(XS)=Station
BEGIN DESCRIPTION:
NUBIA CREEK TRIBUTARY 1
END DESCRIPTION:
DSS Export Rating Curves= 0
DSS Export Rating Curve Sorted= 0
DSS Export Volume Flow Curves= 0
DXF OffsetX= 0
DXF OffsetY= 0
DXF ScaleX= 1
DXF ScaleY= 10

--- NUBIA CREEK TRIBUTARY 1.p01 (plan) ---

Plan Title=Multiple Run
Short Identifier=Multiple
Geom File=g01
Flow File=f01
Subcritical Flow
K Sum by GR= 0
Std Step Tol= 0.01
Critical Tol= 0.01
Num of Std Step Trials= 20
Max Error Tol= 0.3
Flow Tol Ratio= 0.001
Split Flow NTrial= 30
Split Flow Tol= 0.02
Split Flow Ratio= 0.02
Log Output Level= 0
Friction Slope Method= 1
Unsteady Friction Slope Method= 2
Unsteady Bridges Friction Slope Method= 1
Parabolic Critical Depth
Global Vel Dist=  1 , 1 , 1
Global Log Level= 0
CheckData=True
Encroach Param= -1, 0, 0, 0
BEGIN DESCRIPTION:
Multiple Run
END DESCRIPTION:

--- NUBIA CREEK TRIBUTARY 1.f01 (steady flow) ---

Flow Title=Multiple
Program Version=4.10
Number of Profiles= 7
Profile Names=10-year,25-year,50-year,1pct_min,100-year,1pct_plu,500-year
River Rch & RM=NUBIA CREEK TRIB,Reach-1         ,41527
     641     953    1229     788    1572    3137    2604
River Rch & RM=NUBIA CREEK TRIB,Reach-1         ,35780
     787    1178    1528     984    1963    3918    3282
River Rch & RM=NUBIA CREEK TRIB,Reach-1         ,30519
     864    1291    1671    1074    2142    4275    3563
River Rch & RM=NUBIA CREEK TRIB,Reach-1         ,16901
    1451    2220    2917    1900    3792    7566    6486
River Rch & RM=NUBIA CREEK TRIB,Reach-1         ,12357
    1614    2486    3282    2147    4283    8546    7387
River Rch & RM=NUBIA CREEK TRIB,Reach-1         ,6682
    1941    3005    3980    2609    5206   10387    9025
Boundary for River Rch & Prof#=NUBIA CREEK TRIB,Reach-1         , 1
Up Type= 0
Dn Type= 3
Dn Slope=0.00378
Boundary for River Rch & Prof#=NUBIA CREEK TRIB,Reach-1         , 2
Up Type= 0
Dn Type= 3
Dn Slope=0.00378
Boundary for River Rch & Prof#=NUBIA CREEK TRIB,Reach-1         , 3
Up Type= 0
Dn Type= 3
Dn Slope=0.00378
Boundary for River Rch & Prof#=NUBIA CREEK TRIB,Reach-1         , 4
Up Type= 0
Dn Type= 3
Dn Slope=0.00378
Boundary for River Rch & Prof#=NUBIA CREEK TRIB,Reach-1         , 5
Up Type= 0
Dn Type= 3
Dn Slope=0.00378
Boundary for River Rch & Prof#=NUBIA CREEK TRIB,Reach-1         , 6
Up Type= 0
Dn Type= 3
Dn Slope=0.00378
Boundary for River Rch & Prof#=NUBIA CREEK TRIB,Reach-1         , 7
Up Type= 0
Dn Type= 3
Dn Slope=0.00378
DSS Import GetInterval= 0
DSS Import GetPeak= 0
DSS Import FillOption= 0

--- NUBIA CREEK TRIBUTARY 1.g01 (geometry) ---

Geom Title=Existing Conditions
Program Version=4.10

River Reach=NUBIA CREEK TRIB,Reach-1
Reach XY= 30
        1489255.        6795388.      1488955.59      6798577.38
      1490055.88        6801288.      1489256.58      6802681.95
      1489462.67      6803444.52      1491051.66      6805289.72
      1490706.37      6805499.53      1490704.29      6806458.14
      1491110.44      6807690.62      1492055.49      6807758.12
      1491854.96      6808668.02      1492151.36      6808986.34
       1491265.3       6809377.9      1491403.04      6810182.11
      1490756.03      6810898.43      1491056.05      6812577.57
        1491955.        6812288.      1492747.18      6812931.81
      1492954.94      6813708.01      1492404.79      6815362.91
      1492853.39      6817831.98      1492202.33       6817893.3
       1491904.7      6818363.12      1493049.16      6819635.71
      1493304.48      6820672.78       1492885.6      6821708.67
      1492358.52      6821689.46      1492451.25      6822536.45
      1491606.97      6823793.67        1491655.        6824888.

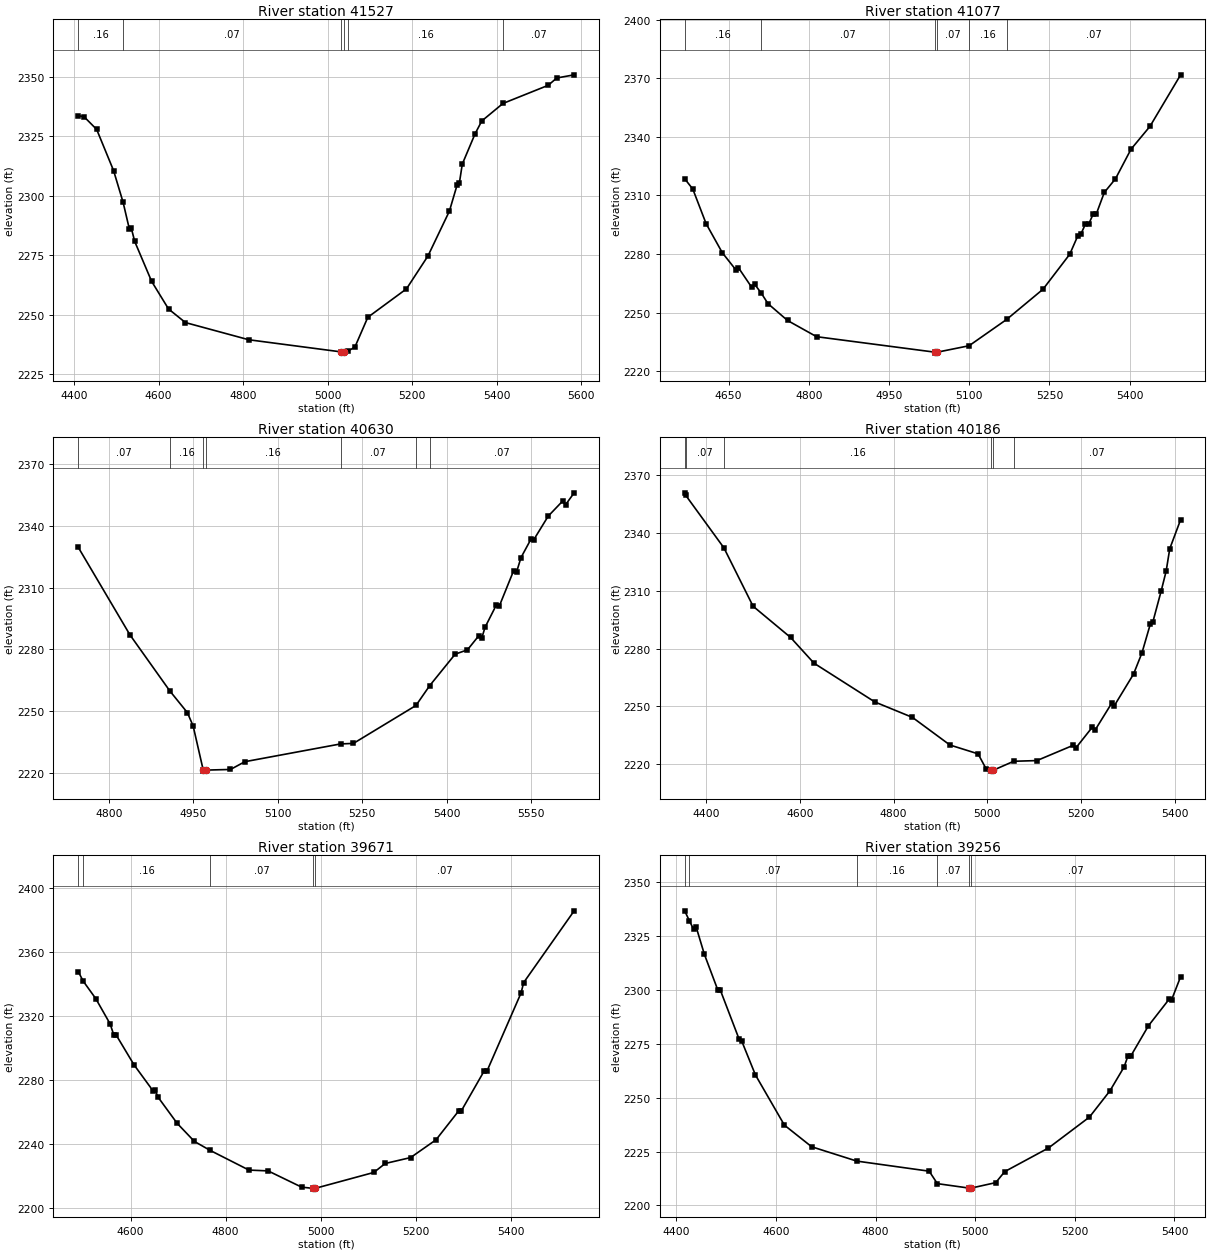
Type RM Length L Ch R = 1 ,41527   ,450,450,450
BEGIN DESCRIPTION:
NUBIA CREEK TRIBUTARY 1 72.0
END DESCRIPTION:
XS GIS Cut Line= 3
      1488761.32      6796006.92        1489355.        6795988.
      1489925.48      6796092.19
#Sta/Elev= 30
  4409.9 2333.62  4423.6 2333.21  4453.6 2327.86  4493.6 2310.57  4516.2 2297.22
  4530.8 2286.14  4535.8 2286.27  4543.6 2280.82  4583.7 2264.04  4623.7 2252.45
  4663.7 2246.74  4813.8 2239.52  5033.1 2234.41  5033.5 2233.91    5038 2234.41
  5048.3 2234.72  5064.9 2236.49  5095.4 2248.96  5186.9  2260.9  5237.7  2274.7
  5288.5 2293.55  5306.9 2304.63    5312 2305.21    5319 2313.29  5349.5 2326.11
  5365.2 2331.42  5415.3 2338.77  5522.3 2346.38  5542.6 2349.46  5583.8 2350.79
#Mann= 6 ,-1 , 0
  4409.9     .16       0  4516.2     .07       0  5033.1     .07       0
    5038     .07       0  5048.3     .16       0  5415.3     .07       0
Bank Sta=5033.1,5038
XS Rating Curve= 0 ,0
Exp/Cntr=0.3,0.1

Type RM Length L Ch R = 1 ,41077   ,447,447,447
BEGIN DESCRIPTION:
NUBIA CREEK TRIBUTARY 1 71.0
END DESCRIPTION:
XS GIS Cut Line= 3
      1488804.97      6796237.99        1489205.        6796388.
      1489604.97      6796687.98
#Sta/Elev= 30
    4568 2318.51  4583.2 2313.23  4608.1 2295.49  4638.3 2280.65  4663.3 2271.98
  4668.6 2272.91  4693.5 2262.84  4698.9 2264.45  4711.2 2259.92  4723.8 2254.53
  4760.3 2245.92  4814.6 2237.62  5035.5  2229.7  5035.8  2229.2  5040.4  2229.7
  5099.7 2232.98  5169.9 2246.44  5237.9 2261.92  5287.9 2279.84  5302.5 2288.99
  5308.8 2290.22  5317.1 2295.21  5323.4 2295.38  5331.7 2300.37  5337.9 2300.71
  5352.5  2311.5  5373.4 2318.49  5402.5 2333.67  5437.9 2345.35  5495.2 2371.75
#Mann= 6 ,-1 , 0
    4568     .16       0  4711.2     .07       0  5035.5     .07       0
  5040.4     .07       0  5099.7     .16       0  5169.9     .07       0
Bank Sta=5035.5,5040.4
XS Rating Curve= 0 ,0
Exp/Cntr=0.3,0.1

Type RM Length L Ch R = 1 ,40630   ,444,444,444
BEGIN DESCRIPTION:
NUBIA CREEK TRIBUTARY 1 70.0
END DESCRIPTION:
XS GIS Cut Line= 3
        1488705.        6796688.        1488955.        6796738.
      1489543.95      6796948.26
#Sta/Elev= 30
  4745.9 2329.62  4837.7  2287.1  4908.6 2259.84  4939.7 2249.33  4949.9 2242.86
  4967.8 2221.44  4968.2 2220.94  4972.8 2221.44  5016.2 2221.75  5041.7 2225.52
  5211.5 2234.14  5234.4  2234.4  5345.4 2252.81  5369.9 2262.48    5415 2277.72
  5436.8 2279.82    5457 2286.68  5462.3  2285.6    5468 2290.74  5487.8 2301.45
  5493.1 2300.89  5518.6 2318.13  5523.9 2317.49  5531.8 2324.58  5549.4 2333.49
  5554.7 2333.36  5580.2 2344.74  5605.7 2352.02    5611 2350.27  5626.2 2356.04
#Mann= 7 ,-1 , 0
  4745.9     .07       0  4908.6     .16       0  4967.8     .07       0
  4972.8     .16       0  5211.5     .07       0  5345.4     .16       0
  5369.9     .07       0
Bank Sta=4967.8,4972.8
XS Rating Curve= 0 ,0
Exp/Cntr=0.3,0.1

Type RM Length L Ch R = 1 ,40186   ,515,515,515
BEGIN DESCRIPTION:
NUBIA CREEK TRIBUTARY 1 69.0
END DESCRIPTION:
XS GIS Cut Line= 3
      1488359.06      6797125.36        1489005.        6797138.
      1489405.02      6797238.01
#Sta/Elev= 30
  4354.3 2360.91  4356.4 2359.66  4438.1  2332.3  4500.3    2302  4580.3  2285.8
  4630.3 2272.43  4760.3 2252.27  4840.3 2244.29  4920.3 2229.94  4980.4 2225.35
  4997.9 2217.43  5008.2 2216.87  5008.5 2216.37  5013.2 2216.87  5056.5 2221.49
    5106 2221.85  5183.3 2229.77  5188.5 2228.22  5224.6  2239.3  5229.7  2237.5
  5265.8 2251.72  5270.9 2250.23  5312.2 2266.75  5330.2 2277.78  5348.3 2292.97
  5353.4  2293.8  5371.4 2310.12  5381.8 2320.21  5389.5 2331.87  5412.7 2346.96
#Mann= 6 ,-1 , 0
  4354.3     .16       0  4356.4     .07       0  4438.1     .16       0
  5008.2     .07       0  5013.2     .16       0  5056.5     .07       0
Bank Sta=5008.2,5013.2
XS Rating Curve= 0 ,0
Exp/Cntr=0.3,0.1

Type RM Length L Ch R = 1 ,39671   ,415,415,415
BEGIN DESCRIPTION:
NUBIA CREEK TRIBUTARY 1 68.0
END DESCRIPTION:
XS GIS Cut Line= 3
      1488548.36      6797543.77      1489054.73      6797604.54
      1489548.42      6797402.85
#Sta/Elev= 30
    4490 2347.73  4500.6  2341.7  4526.9 2330.83  4557.1 2315.04  4564.8 2308.15
  4569.9 2308.05  4607.5 2289.41  4647.1 2273.32  4652.1 2273.54  4657.8 2269.31
  4698.1 2252.91  4734.4 2241.59  4767.5 2235.99  4849.2 2223.68  4889.5 2223.17
    4960 2213.02  4983.6 2212.28    4984 2211.78  4988.7 2212.28  5111.8  2222.2
  5135.8  2227.8  5189.2 2231.49  5242.7  2242.6  5290.7 2260.77  5296.1 2260.77
  5344.2 2285.72  5349.6 2285.34  5421.6 2334.34  5427.1 2340.85  5533.3 2385.68
#Mann= 5 ,-1 , 0
    4490     .07       0  4500.6     .16       0  4767.5     .07       0
  4983.6     .07       0  4988.7     .07       0
Bank Sta=4983.6,4988.7
XS Rating Curve= 0 ,0
Exp/Cntr=0.3,0.1

Type RM Length L Ch R = 1 ,39256   ,464,464,464
BEGIN DESCRIPTION:
NUBIA CREEK TRIBUTARY 1 67.0
END DESCRIPTION:
XS GIS Cut Line= 3
      1488586.52        6797858.        1489155.        6797988.
      1489555.03      6797887.99
#Sta/Elev= 30
  4416.8 2336.79  4426.3 2332.13  4434.9 2328.14  4440.1 2329.08  4456.3 2316.62
    4483  2300.2  4488.1 2300.13    4526 2277.23  4531.1 2276.43  4558.9 2260.54
    4617 2237.26  4671.7 2227.22  4762.2 2220.57  4907.6 2215.88    4924  2210.1
  4987.1 2208.05  4987.5 2207.55  4992.2 2208.05  5041.2 2210.57  5059.2 2215.68
  5146.8 2226.62  5229.3 2241.01  5270.5 2253.22  5298.9 2264.32  5306.6 2269.41
  5311.8 2269.17  5347.8 2283.44  5389.1 2295.71  5394.2 2295.47  5412.3 2306.19
#Mann= 6 ,-1 , 0
  4416.8     .16       0  4426.3     .07       0  4762.2     .16       0
    4924     .07       0  4987.1     .07       0  4992.2     .07       0
Bank Sta=4987.1,4992.2
XS Rating Curve= 0 ,0
Exp/Cntr=0.3,0.1

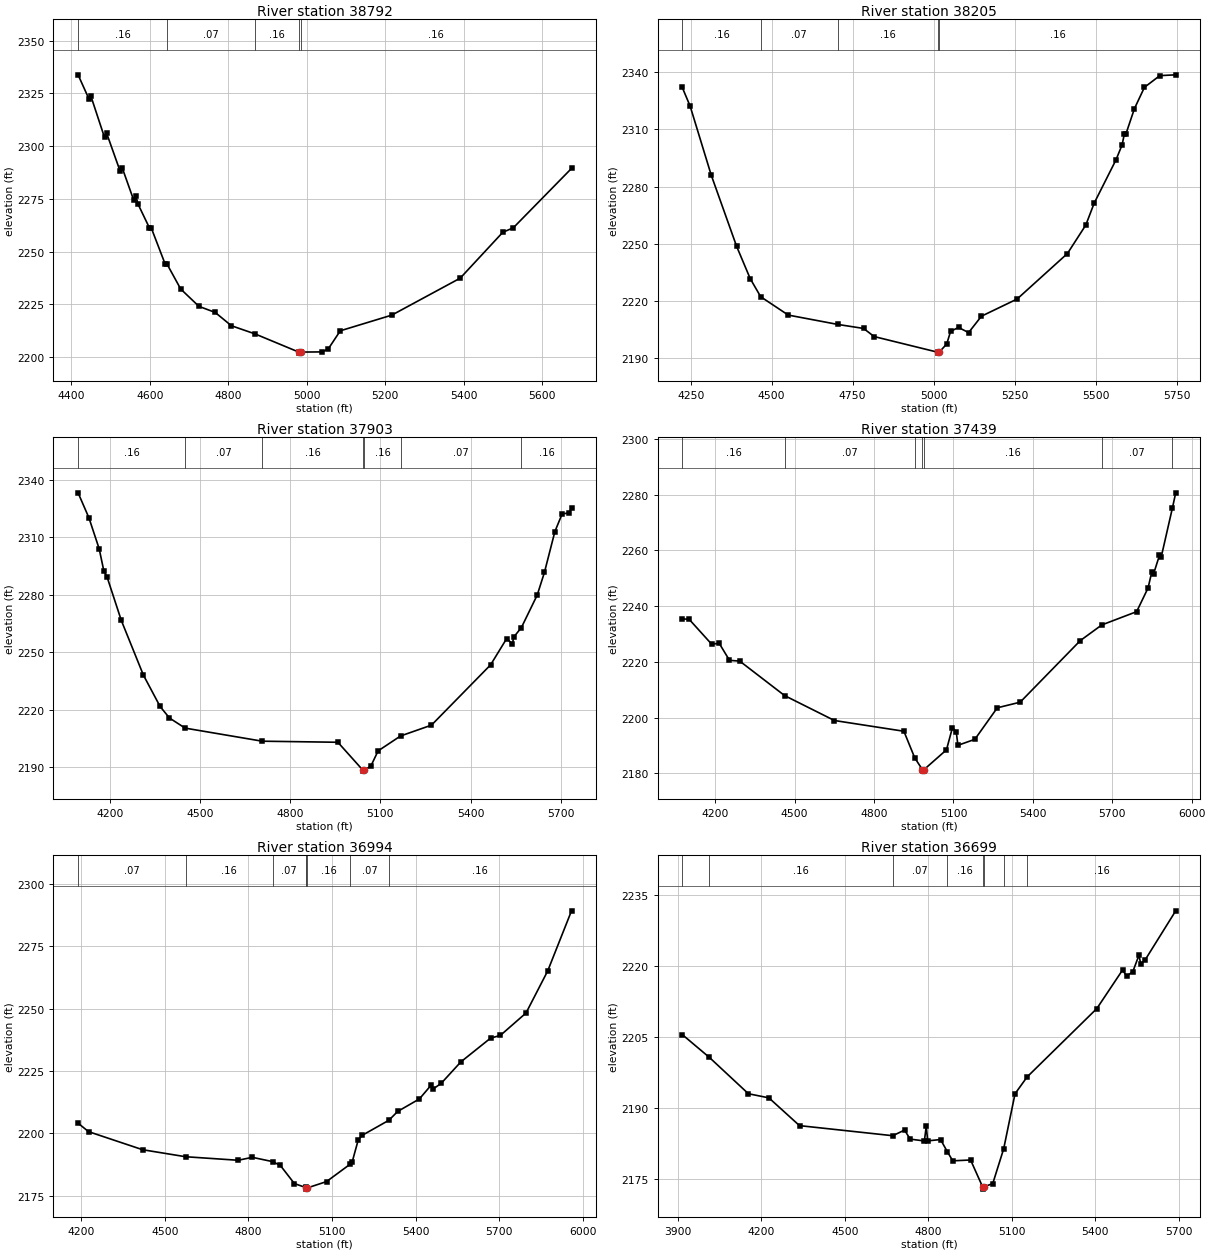
Type RM Length L Ch R = 1 ,38792   ,587,587,587
BEGIN DESCRIPTION:
NUBIA CREEK TRIBUTARY 1 66.0
END DESCRIPTION:
XS GIS Cut Line= 3
      1488487.53      6798234.72        1489055.        6798388.
      1489718.49      6798292.02
#Sta/Elev= 30
  4416.8 2333.74  4444.3 2322.39  4449.5 2323.63  4484.2 2304.07  4489.4 2306.18
  4524.1 2288.04  4529.3  2289.7  4558.8 2274.27    4564 2276.51  4569.6 2272.51
  4598.7 2261.24  4603.9 2260.98  4638.6 2244.19  4643.9 2243.97  4678.5 2232.26
  4724.9 2224.06  4766.4 2221.18  4807.8 2214.87  4867.8 2211.02  4979.5  2202.4
  4979.9  2201.9  4984.7  2202.4  5039.8 2202.48  5055.1    2204  5085.4 2212.48
  5216.8 2219.91  5391.2 2237.42  5499.7 2259.13  5526.7 2261.29    5675  2289.4
#Mann= 5 ,-1 , 0
  4416.8     .16       0  4643.9     .07       0  4867.8     .16       0
  4979.5     .07       0  4984.7     .16       0
Bank Sta=4979.5,4984.7
XS Rating Curve= 0 ,0
Exp/Cntr=0.3,0.1

Type RM Length L Ch R = 1 ,38205   ,302,302,302
BEGIN DESCRIPTION:
NUBIA CREEK TRIBUTARY 1 65.0
END DESCRIPTION:
XS GIS Cut Line= 3
      1488464.84      6798586.36      1489205.55      6798817.73
      1489911.34      6798571.22
#Sta/Elev= 30
    4224 2332.04  4248.3 2322.21  4313.3 2286.07  4391.8 2248.63  4433.7 2231.72
  4466.1 2222.21  4551.2 2212.59  4703.5  2207.7  4783.8 2205.57  4816.3 2201.32
  5012.2 2193.12  5012.6 2192.62  5017.4 2193.12  5040.6 2197.46  5052.4 2204.04
  5076.9 2206.11    5108 2203.39  5147.7    2212  5257.9 2221.02  5413.2  2244.9
    5470 2259.86  5495.8 2271.33  5563.2 2294.08    5582 2301.92  5588.9 2307.59
  5594.2 2307.83    5620  2320.9    5651 2332.13  5698.5 2338.27  5747.6 2338.69
#Mann= 5 ,-1 , 0
    4224     .16       0  4466.1     .07       0  4703.5     .16       0
  5012.2     .07       0  5017.4     .16       0
Bank Sta=5012.2,5017.4
XS Rating Curve= 0 ,0
Exp/Cntr=0.3,0.1

Type RM Length L Ch R = 1 ,37903   ,464,464,464
BEGIN DESCRIPTION:
NUBIA CREEK TRIBUTARY 1 64.0
END DESCRIPTION:
XS GIS Cut Line= 3
      1488332.03      6798844.17        1489205.        6799088.
      1489886.73       6798810.3
#Sta/Elev= 30
  4093.7  2333.2  4129.8 2320.16    4164 2303.95  4179.8 2292.18  4190.2 2289.31
  4237.5 2266.68    4311 2238.18  4366.7 2221.78  4397.9 2215.77    4450  2210.5
  4706.6 2203.68  4958.5 2203.12  5041.7 2188.57  5042.1 2188.07  5046.9 2188.57
  5068.3 2190.71  5092.4 2198.63    5167 2206.39    5270 2212.05  5466.9  2243.5
  5520.4 2257.21    5539 2254.42  5544.4 2258.07  5569.4 2262.95    5622 2279.88
    5646 2291.67  5680.9 2313.03  5704.9 2322.16    5729 2322.79  5736.2 2325.45
#Mann= 7 ,-1 , 0
  4093.7     .16       0    4450     .07       0  4706.6     .16       0
  5041.7     .07       0  5046.9     .16       0    5167     .07       0
  5569.4     .16       0
Bank Sta=5041.7,5046.9
XS Rating Curve= 0 ,0
Exp/Cntr=0.3,0.1

Type RM Length L Ch R = 1 ,37439   ,445,445,445
BEGIN DESCRIPTION:
NUBIA CREEK TRIBUTARY 1 63.0
END DESCRIPTION:
XS GIS Cut Line= 3
      1488270.39      6799283.15        1489155.        6799538.
      1489890.95      6798947.11
#Sta/Elev= 30
  4075.5  2235.4  4101.1  2235.3  4186.5 2226.34  4214.9 2226.67  4253.8 2220.56
  4292.7 2220.27  4462.2 2207.91  4650.2 2198.98  4912.8 2195.13  4953.7  2185.6
    4983 2181.33  4983.4 2180.83  4988.3 2181.33  5073.7 2188.47  5096.1 2196.37
  5110.5 2195.02  5116.9 2190.09  5180.9 2192.23  5265.7 2203.54  5352.1 2205.55
  5579.3 2227.63  5660.5 2233.25  5792.2 2238.01  5835.4 2246.51  5849.8 2252.38
  5856.2 2251.52  5878.6 2258.27    5885 2257.57  5927.2 2275.11  5939.9 2280.62
#Mann= 7 ,-1 , 0
  4075.5     .16       0  4462.2     .07       0  4953.7     .16       0
    4983     .07       0  4988.3     .16       0  5660.5     .07       0
  5927.2     .16       0
Bank Sta=4983,4988.3
XS Rating Curve= 0 ,0
Exp/Cntr=0.3,0.1

Type RM Length L Ch R = 1 ,36994   ,295,295,295
BEGIN DESCRIPTION:
NUBIA CREEK TRIBUTARY 1 62.0
END DESCRIPTION:
XS GIS Cut Line= 3
      1488705.05      6799887.99        1489505.        6799788.
       1490139.7      6799062.67
#Sta/Elev= 30
  4189.2 2204.06  4226.9 2200.66  4420.9 2193.41  4575.1  2190.6  4763.6 2189.18
    4814 2190.37    4887 2188.64  4914.8  2187.1  4965.1 2179.83    5005 2178.27
  5006.5  2178.1  5006.9  2177.6  5011.8  2178.1  5080.3 2180.62    5165  2187.6
  5172.4 2188.49  5194.2 2197.38    5208 2199.17  5304.1 2205.24  5335.6 2208.78
  5413.5  2213.8  5456.2  2219.4  5462.8  2217.8  5491.3 2220.01  5562.5 2228.69
  5668.8  2238.2  5703.9 2239.29    5796 2248.29  5873.8 2265.18  5959.2  2289.3
#Mann= 8 ,-1 , 0
  4189.2     .07       0  4575.1     .16       0    4887     .07       0
    5005     .16       0  5006.5     .07       0  5011.8     .16       0
    5165     .07       0  5304.1     .16       0
Bank Sta=5006.5,5011.8
XS Rating Curve= 0 ,0
Exp/Cntr=0.3,0.1

Type RM Length L Ch R = 1 ,36699   ,449,449,449
BEGIN DESCRIPTION:
NUBIA CREEK TRIBUTARY 1 61.0
END DESCRIPTION:
XS GIS Cut Line= 3
      1488692.07      6800112.48      1489755.17      6799903.22
      1490154.44      6799342.56
#Sta/Elev= 30
  3916.5 2205.58  4013.9 2200.75  4153.9 2193.08  4227.4 2192.21  4337.4 2186.34
  4672.2 2184.21  4714.5  2185.4  4734.8 2183.49  4785.8  2183.1  4792.5 2186.23
  4797.6 2183.12  4843.8  2183.4  4868.4 2180.81  4887.7  2178.9  4951.7 2179.08
  4994.7 2173.42  4995.1 2172.92    5000 2173.42  5031.3 2174.09  5070.5 2181.44
  5111.3 2193.08  5154.8 2196.64  5405.1 2211.09  5497.5 2219.24  5512.1 2217.93
  5534.3  2218.9  5556.3 2222.36  5562.5 2220.57  5577.2 2221.25  5688.3 2231.74
#Mann= 8 ,-1 , 0
  3916.5     .07       0  4013.9     .16       0  4672.2     .07       0
  4868.4     .16       0  4994.7     .07       0    5000     .16       0
  5070.5     .07       0  5154.8     .16       0
Bank Sta=4994.7,5000
XS Rating Curve= 0 ,0
Exp/Cntr=0.3,0.1

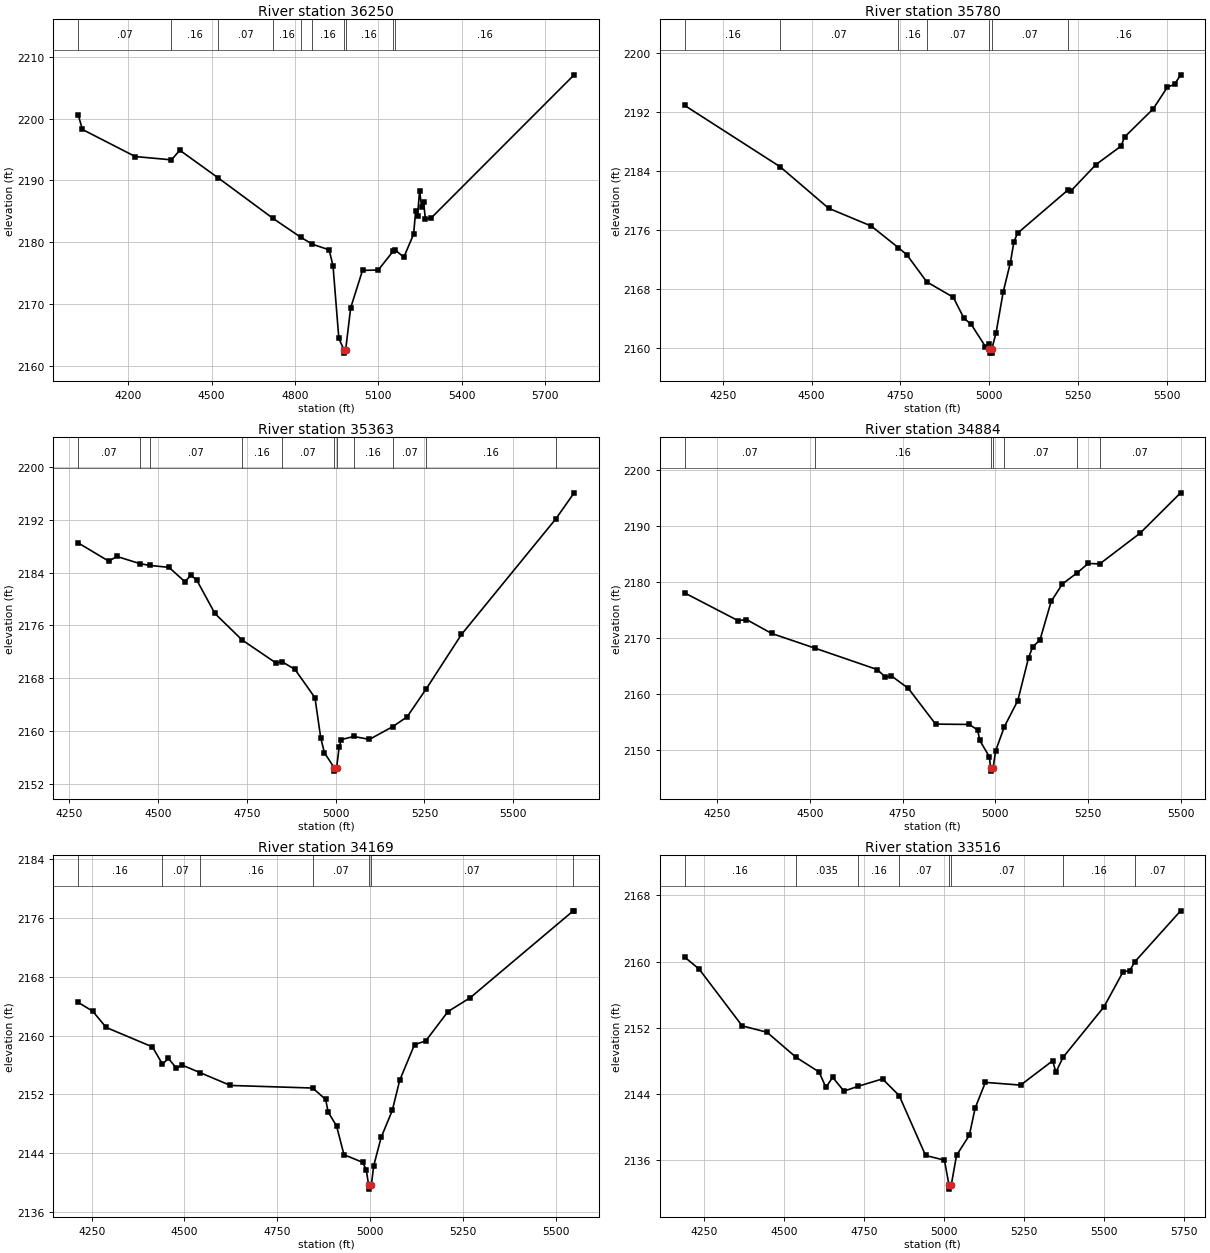
Type RM Length L Ch R = 1 ,36250   ,470,470,470
BEGIN DESCRIPTION:
Mapping XS 7fe037d1
END DESCRIPTION:
XS GIS Cut Line= 3
      1488739.87      6800340.33      1489568.85      6800364.21
      1490215.53      6799663.27
#Sta/Elev= 30
  4020.7  2200.6  4035.8 2198.24  4225.9 2193.85  4355.8 2193.32    4386 2194.87
  4523.3 2190.42  4721.2 2183.83  4820.1  2180.8    4863 2179.64  4922.6 2178.75
  4936.7 2176.19  4957.7  2164.4  4976.4 2162.51  4976.9 2162.01  4982.1 2162.51
  5000.3 2169.35  5042.8 2175.41  5099.5 2175.47  5152.2 2178.48  5159.6 2178.73
  5191.4 2177.55  5226.5 2181.28  5233.9 2185.03  5240.7 2184.28  5248.1 2188.35
  5254.9 2185.75  5262.2 2186.52    5269 2183.68  5290.6 2183.94  5803.7 2207.09
#Mann= 10 ,-1 , 0
  4020.7     .07       0  4355.8     .16       0  4523.3     .07       0
  4721.2     .16       0  4820.1     .07       0    4863     .16       0
  4976.4     .07       0  4982.1     .16       0  5152.2     .07       0
  5159.6     .16       0
Bank Sta=4976.4,4982.1
XS Rating Curve= 0 ,0
Exp/Cntr=0.3,0.1

Type RM Length L Ch R = 1 ,35780   ,417,417,417
BEGIN DESCRIPTION:
Mapping XS 4b03df25
END DESCRIPTION:
XS GIS Cut Line= 3
      1489150.41      6800503.53       1489749.4      6800536.08
      1490541.87      6800618.36
#Sta/Elev= 30
  4142.8 2192.93    4412 2184.59    4548 2178.97  4668.2 2176.55  4744.1 2173.63
  4768.4 2172.65  4824.5 2168.97  4899.1 2166.88  4929.3 2164.02  4949.4 2163.22
  4989.6 2160.19    4999 2160.55  5000.7 2159.79  5001.2 2159.29  5006.9 2159.29
  5007.4 2159.79  5019.8 2162.08  5039.9 2167.62    5060 2171.58    5070 2174.43
  5080.1 2175.57  5221.4 2181.42  5230.9 2181.34  5301.3 2184.91  5371.6 2187.41
  5381.7 2188.65  5462.1 2192.46  5502.3 2195.43  5522.4 2195.79  5539.4 2197.09
#Mann= 7 ,-1 , 0
  4142.8     .16       0    4412     .07       0  4744.1     .16       0
  4824.5     .07       0  5000.7     .07       0  5007.4     .07       0
  5221.4     .16       0
Bank Sta=5000.7,5007.4
XS Rating Curve= 0 ,0
Exp/Cntr=0.3,0.1

Type RM Length L Ch R = 1 ,35363   ,479,479,479
BEGIN DESCRIPTION:
Mapping XS 3f27fe65
END DESCRIPTION:
XS GIS Cut Line= 4
       1489205.1      6800634.15      1489741.59      6800894.59
      1489960.34      6800954.48      1490530.36      6800892.01
#Sta/Elev= 30
    4275 2188.47  4361.1 2185.71  4383.7 2186.43  4449.5 2185.33  4476.7 2185.07
  4530.6 2184.78  4575.3 2182.61  4592.3 2183.57  4608.4 2182.89    4660  2177.8
  4736.2 2173.81  4830.7 2170.36  4849.8 2170.48  4885.3 2169.35  4941.7 2165.06
  4957.8 2159.04  4968.2 2156.75    4996 2154.46  4996.5 2153.96  5002.7 2154.46
  5009.7 2157.54  5015.8 2158.73  5050.9  2159.2  5095.2 2158.76  5160.4 2160.68
    5201 2162.16  5255.3 2166.42  5354.3 2174.63  5620.1 2192.12  5671.6 2196.05
#Mann= 11 ,-1 , 0
    4275     .07       0  4449.5     .16       0  4476.7     .07       0
  4736.2     .16       0  4849.8     .07       0    4996     .07       0
  5002.7     .07       0  5050.9     .16       0  5160.4     .07       0
  5255.3     .16       0  5620.1     .07       0
Bank Sta=4996,5002.7
XS Rating Curve= 0 ,0
Exp/Cntr=0.3,0.1

Type RM Length L Ch R = 1 ,34884   ,715,715,715
BEGIN DESCRIPTION:
Mapping XS dbc16a09
END DESCRIPTION:
XS GIS Cut Line= 3
      1489296.23      6800972.69      1490038.46      6801326.88
      1490554.13      6801308.65
#Sta/Elev= 30
  4161.8 2178.09  4305.9 2173.14  4328.6 2173.34  4396.7 2170.85  4513.5 2168.23
  4681.2 2164.42  4703.4 2163.08  4719.9 2163.27  4765.3 2161.06  4838.9 2154.68
  4929.6 2154.62  4952.3 2153.65  4958.2 2151.77  4984.2 2148.84  4987.3 2146.79
  4987.8 2146.29  4994.1 2146.79  5000.8 2149.88  5024.7 2154.24  5060.8 2158.88
  5089.9 2166.54  5100.8 2168.43  5120.8 2169.73  5150.8 2176.57  5180.9 2179.67
  5221.5  2181.7  5250.9 2183.35  5281.8 2183.26    5391 2188.76  5500.2 2195.95
#Mann= 7 ,-1 , 0
  4161.8     .07       0  4513.5     .16       0  4987.3     .07       0
  4994.1     .16       0  5024.7     .07       0  5221.5     .16       0
  5281.8     .07       0
Bank Sta=4987.3,4994.1
XS Rating Curve= 0 ,0
Exp/Cntr=0.3,0.1

Type RM Length L Ch R = 1 ,34169   ,653,653,653
BEGIN DESCRIPTION:
Mapping XS f70d41ac
END DESCRIPTION:
XS GIS Cut Line= 3
      1489109.82      6801561.23       1489695.8       6801899.8
      1490354.63      6801925.84
#Sta/Elev= 30
  4213.8 2164.51    4253  2163.3  4289.1  2161.1  4413.8 2158.45  4440.7 2156.12
  4456.9 2156.88  4478.4 2155.56  4494.2 2155.97  4541.8 2154.96    4624 2153.21
  4845.5 2152.86  4880.4 2151.31  4887.2 2149.59  4909.8  2147.7  4929.8 2143.79
  4979.8 2142.76  4989.8 2141.77  4996.3 2139.61  4996.8 2139.11  5003.4 2139.61
  5009.9 2142.29  5029.9 2146.14  5059.9 2149.81  5079.9 2153.91  5119.9 2158.77
    5150 2159.26    5210 2163.26  5270.1 2165.15  5547.1 2176.94  5549.9 2176.96
#Mann= 7 ,-1 , 0
  4213.8     .16       0  4440.7     .07       0  4541.8     .16       0
  4845.5     .07       0  4996.3     .07       0  5003.4     .07       0
  5547.1     .16       0
Bank Sta=4996.3,5003.4
XS Rating Curve= 0 ,0
Exp/Cntr=0.3,0.1

Type RM Length L Ch R = 1 ,33516   ,868,868,868
BEGIN DESCRIPTION:
Mapping XS 25853dd8
END DESCRIPTION:
XS GIS Cut Line= 3
      1488911.96      6801837.31      1489474.45      6802418.02
      1490214.08      6802381.56
#Sta/Elev= 30
  4190.4 2160.53  4235.4 2159.09  4369.9 2152.21  4447.6 2151.43  4537.9 2148.41
  4610.2 2146.62  4631.5 2144.75  4652.6 2145.97  4688.1  2144.3  4731.3 2144.88
  4808.3 2145.78  4860.4 2143.76  4942.8 2136.51  5001.7 2135.94  5015.9 2132.93
  5016.4 2132.43    5023 2132.93  5039.5 2136.52  5079.5 2138.96  5097.7 2142.26
  5129.6 2145.36  5239.7 2145.03  5339.8 2147.98  5349.9 2146.59  5371.9 2148.38
    5500 2154.51  5560.1 2158.78  5580.1 2158.87  5596.2 2159.96  5739.4 2166.14
#Mann= 8 ,-1 , 0
  4190.4     .16       0  4537.9    .035       0  4731.3     .16       0
  4860.4     .07       0  5015.9     .07       0    5023     .07       0
  5371.9     .16       0  5596.2     .07       0
Bank Sta=5015.9,5023
XS Rating Curve= 0 ,0
Exp/Cntr=0.3,0.1

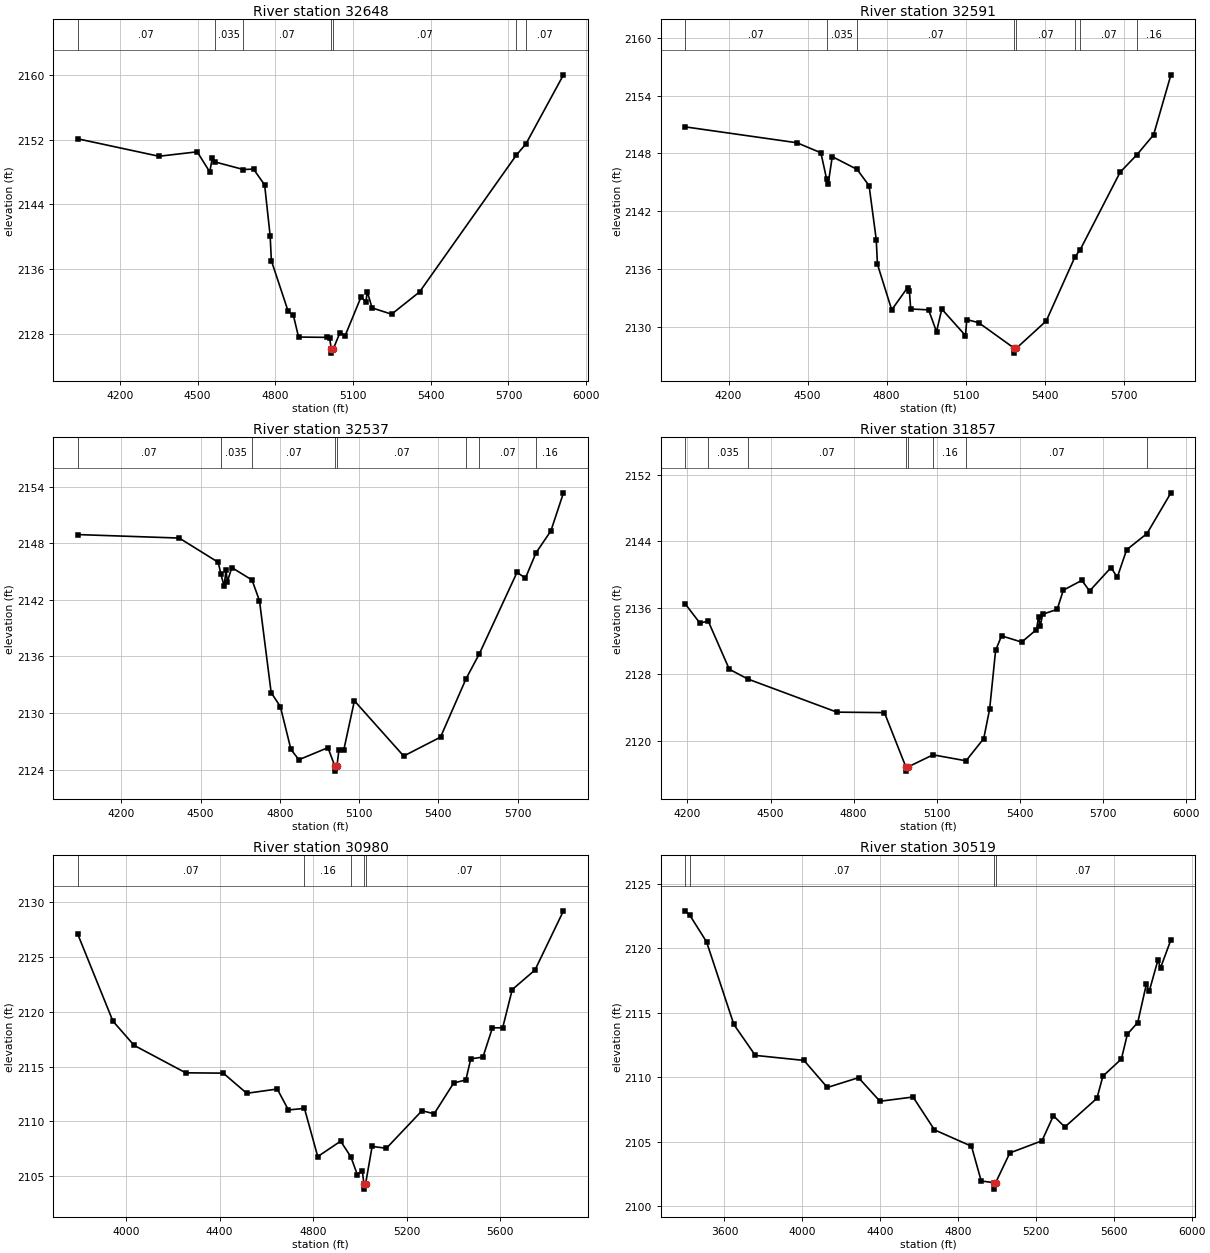
Type RM Length L Ch R = 1 ,32648   ,57,57,57
BEGIN DESCRIPTION:
Mapping XS e2c883f1
END DESCRIPTION:
XS GIS Cut Line= 4
      1488649.49      6802682.46      1489290.07      6803067.85
      1489631.22      6803073.06      1490360.22      6802778.85
#Sta/Elev= 30
  4037.4 2152.11    4351 2149.95  4498.6  2150.5  4547.1 2148.01  4556.8 2149.69
  4565.6 2149.26  4676.6 2148.31  4716.1 2148.36  4758.9  2146.4  4780.2  2140.1
  4784.9 2137.02  4849.9 2130.74  4869.9 2130.25  4889.9 2127.57  4999.9 2127.53
  5009.9 2127.41  5016.2 2126.08  5016.7 2125.58  5023.6 2126.08  5049.9 2128.13
  5069.9 2127.76    5131 2132.53  5149.7 2131.91  5155.1  2133.2  5173.4 2131.18
  5248.9  2130.4  5356.7 2133.15  5730.8 2150.11  5767.2 2151.47  5912.3 2160.03
#Mann= 7 ,-1 , 0
  4037.4     .07       0  4565.6    .035       0  4676.6     .07       0
  5016.2     .07       0  5023.6     .07       0  5730.8     .16       0
  5767.2     .07       0
#XS Ineff= 2 , 0
       0                  5155.1       0  2133.2
Permanent Ineff=
       F       F
Bank Sta=5016.2,5023.6
XS Rating Curve= 0 ,0
Exp/Cntr=0.3,0.1

Type RM Length L Ch R = 1 ,32591   ,54,54,54
BEGIN DESCRIPTION:
Mapping XS 7a8e4a5d
END DESCRIPTION:
XS GIS Cut Line= 4
      1488636.44      6802755.36      1489271.84      6803117.33
      1489665.07      6803135.56      1490334.36      6802869.93
#Sta/Elev= 30
    4035 2150.75  4459.7  2149.1  4550.5 2148.06  4571.9 2145.38  4577.9 2144.78
  4593.7 2147.66  4687.8 2146.34  4733.5 2144.65  4760.8 2139.05  4765.2  2136.5
  4819.5 2131.76  4879.5 2134.06  4886.6 2133.73  4891.6 2131.85  4959.6 2131.76
  4989.7 2129.49  5009.7 2131.84  5099.7 2129.09  5104.7 2130.75  5149.8 2130.43
  5285.3 2127.77  5285.8 2127.27  5292.7 2127.77  5406.4 2130.61  5515.9 2137.28
  5535.2 2137.99  5687.2 2146.05  5750.6 2147.85  5814.1 2149.92    5880 2156.15
#Mann= 8 ,-1 , 0
    4035     .07       0  4571.9    .035       0  4687.8     .07       0
  5285.3     .07       0  5292.7     .07       0  5515.9     .16       0
  5535.2     .07       0  5750.6     .16       0
#XS Ineff= 2 , 0
       0  5104.7 2130.75               0
Permanent Ineff=
       F       F
Bank Sta=5285.3,5292.7
XS Rating Curve= 0 ,0
Exp/Cntr=0.3,0.1

Type RM Length L Ch R = 1 ,32537   ,680,680,680
BEGIN DESCRIPTION:
Mapping XS 70d7822d
END DESCRIPTION:
XS GIS Cut Line= 4
       1488623.4      6802823.06      1489292.67      6803172.02
      1489675.49      6803190.25      1490329.14      6802937.64
#Sta/Elev= 30
  4034.9 2148.93  4419.3 2148.56  4566.8 2145.99  4576.6 2144.78  4589.3 2143.44
    4596 2145.13  4601.7 2143.95  4618.1 2145.43  4694.7 2144.11    4723 2141.91
  4767.2 2132.16    4802 2130.68  4842.1 2126.13  4872.1 2125.04  4982.2 2126.32
  5008.6 2124.33  5009.1 2123.83    5016 2124.33  5023.9  2126.1  5042.3  2126.1
  5082.3 2131.29  5268.9 2125.43  5408.3 2127.44  5505.1 2133.64  5555.1 2136.27
  5697.7 2144.91  5729.9 2144.32  5769.7 2146.99  5826.1 2149.32  5873.7 2153.36
#Mann= 8 ,-1 , 0
  4034.9     .07       0  4576.6    .035       0  4694.7     .07       0
  5008.6     .07       0    5016     .07       0  5505.1     .16       0
  5555.1     .07       0  5769.7     .16       0
#XS Ineff= 2 , 0
       0                  5082.3       0 2131.29
Permanent Ineff=
       F       F
Bank Sta=5008.6,5016
XS Rating Curve= 0 ,0
Exp/Cntr=0.3,0.1

Type RM Length L Ch R = 1 ,31857   ,877,877,877
BEGIN DESCRIPTION:
Mapping XS b03326cf
END DESCRIPTION:
XS GIS Cut Line= 4
      1488912.45      6803803.96      1489697.19       6803699.8
      1490061.77      6803484.52      1490304.83      6803005.35
#Sta/Elev= 30
  4192.1 2136.46  4245.1 2134.15  4275.3 2134.38  4351.2  2128.6  4418.2 2127.42
  4739.4 2123.44  4910.9 2123.38  4988.3 2116.85  4988.8 2116.35  4995.8 2116.85
  5086.1 2118.31  5205.2 2117.59  5269.1 2120.26  5290.5 2123.82    5312 2130.86
  5333.4 2132.61  5406.1 2131.86  5459.3 2133.36  5467.2 2134.92  5472.8 2133.76
  5481.7 2135.21    5534 2135.79  5556.3  2138.1  5623.1 2139.28  5650.9    2138
  5728.4 2140.82  5750.8 2139.64  5784.5 2142.95  5857.9  2144.9  5944.4  2149.8
#Mann= 8 ,-1 , 0
  4192.1     .07       0  4275.3    .035       0  4418.2     .07       0
  4988.3     .07       0  4995.8     .07       0  5086.1     .16       0
  5205.2     .07       0  5857.9     .16       0
Bank Sta=4988.3,4995.8
XS Rating Curve= 0 ,0
Exp/Cntr=0.3,0.1

Type RM Length L Ch R = 1 ,30980   ,461,461,461
BEGIN DESCRIPTION:
NUBIA CREEK TRIBUTARY 1 49.0
END DESCRIPTION:
XS GIS Cut Line= 4
      1489054.98        6804238.      1490214.29      6804334.61
      1490330.72      6804295.86        1490555.      6803537.99
#Sta/Elev= 30
  3793.4  2127.1  3943.9 2119.15  4034.3 2116.94    4255 2114.43  4415.6  2114.4
  4515.9 2112.56  4646.4 2112.95    4694 2111.04  4762.6 2111.18  4819.5 2106.78
  4917.3 2108.19    4961 2106.76  4988.7 2105.13  5010.2 2105.48  5016.5 2104.31
    5017 2103.81  5024.1 2104.31  5051.9 2107.71  5112.9 2107.54  5264.9 2110.97
  5317.1 2110.69  5400.5  2113.5  5452.6 2113.78  5473.5  2115.7  5525.6 2115.87
  5566.2 2118.54  5609.9 2118.54  5650.8 2122.03  5748.2 2123.82  5869.8 2129.22
#Mann= 5 ,-1 , 0
  3793.4     .07       0  4762.6     .16       0    4961     .07       0
  5016.5     .07       0  5024.1     .07       0
Bank Sta=5016.5,5024.1
XS Rating Curve= 0 ,0
Exp/Cntr=0.3,0.1

Type RM Length L Ch R = 1 ,30519   ,409,409,409
BEGIN DESCRIPTION:
NUBIA CREEK TRIBUTARY 1 48.0
END DESCRIPTION:
XS GIS Cut Line= 3
      1488955.01        6804638.        1490555.        6804588.
        1490955.      6803787.99
#Sta/Elev= 30
  3398.3 2122.91    3423 2122.55  3508.3  2120.5  3648.4 2114.09  3758.5 2111.69
  4008.6  2111.3  4128.6  2109.2  4288.7 2109.96  4398.8 2108.13  4568.9 2108.46
  4678.9 2105.91    4869 2104.64    4919 2101.94  4985.1 2101.81  4985.6 2101.31
  4993.1 2101.81  5066.1 2104.12  5231.1 2105.06  5289.8 2107.01  5348.5 2106.13
  5513.4 2108.36  5544.1 2110.08  5639.1 2111.41  5669.9 2113.34    5723 2114.24
  5767.7 2117.24  5781.7 2116.65  5826.4 2119.07  5840.4  2118.5  5893.5 2120.66
#Mann= 4 ,-1 , 0
  3398.3    .035       0    3423     .07       0  4985.1     .07       0
  4993.1     .07       0
Bank Sta=4985.1,4993.1
XS Rating Curve= 0 ,0
Exp/Cntr=0.3,0.1