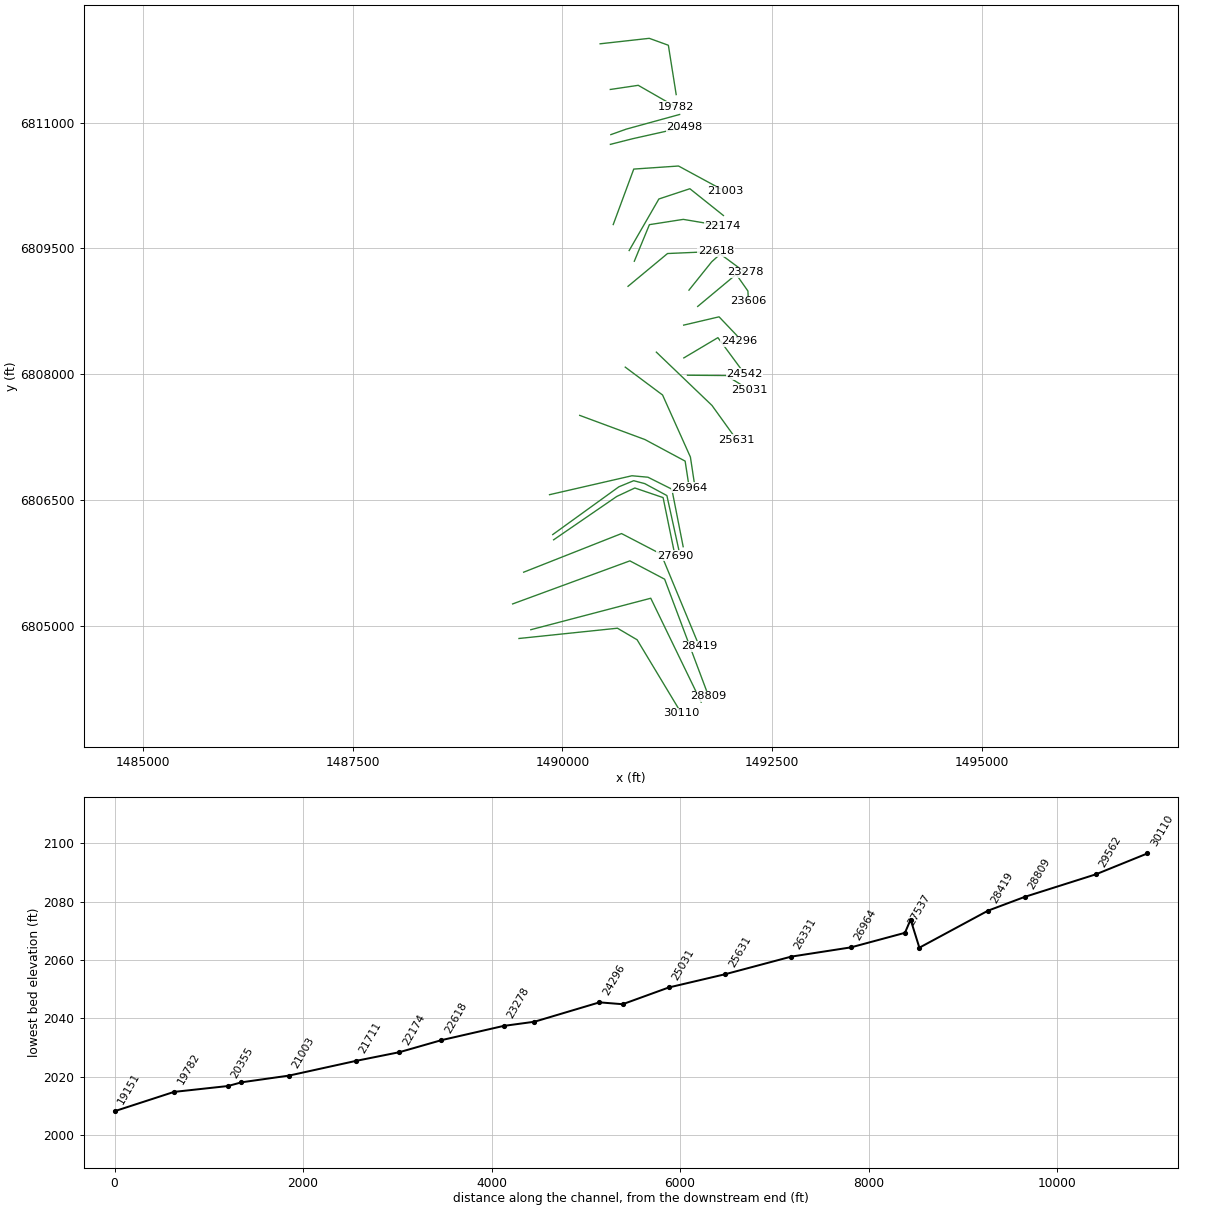
HEC-RAS study NUBIA CREEK TRIBUTARY 1.prj: NUBIA CREEK TRIBUTARY 1 Base Level Engineering

--- NUBIA CREEK TRIBUTARY 1.g01 (geometry) --- (continued)

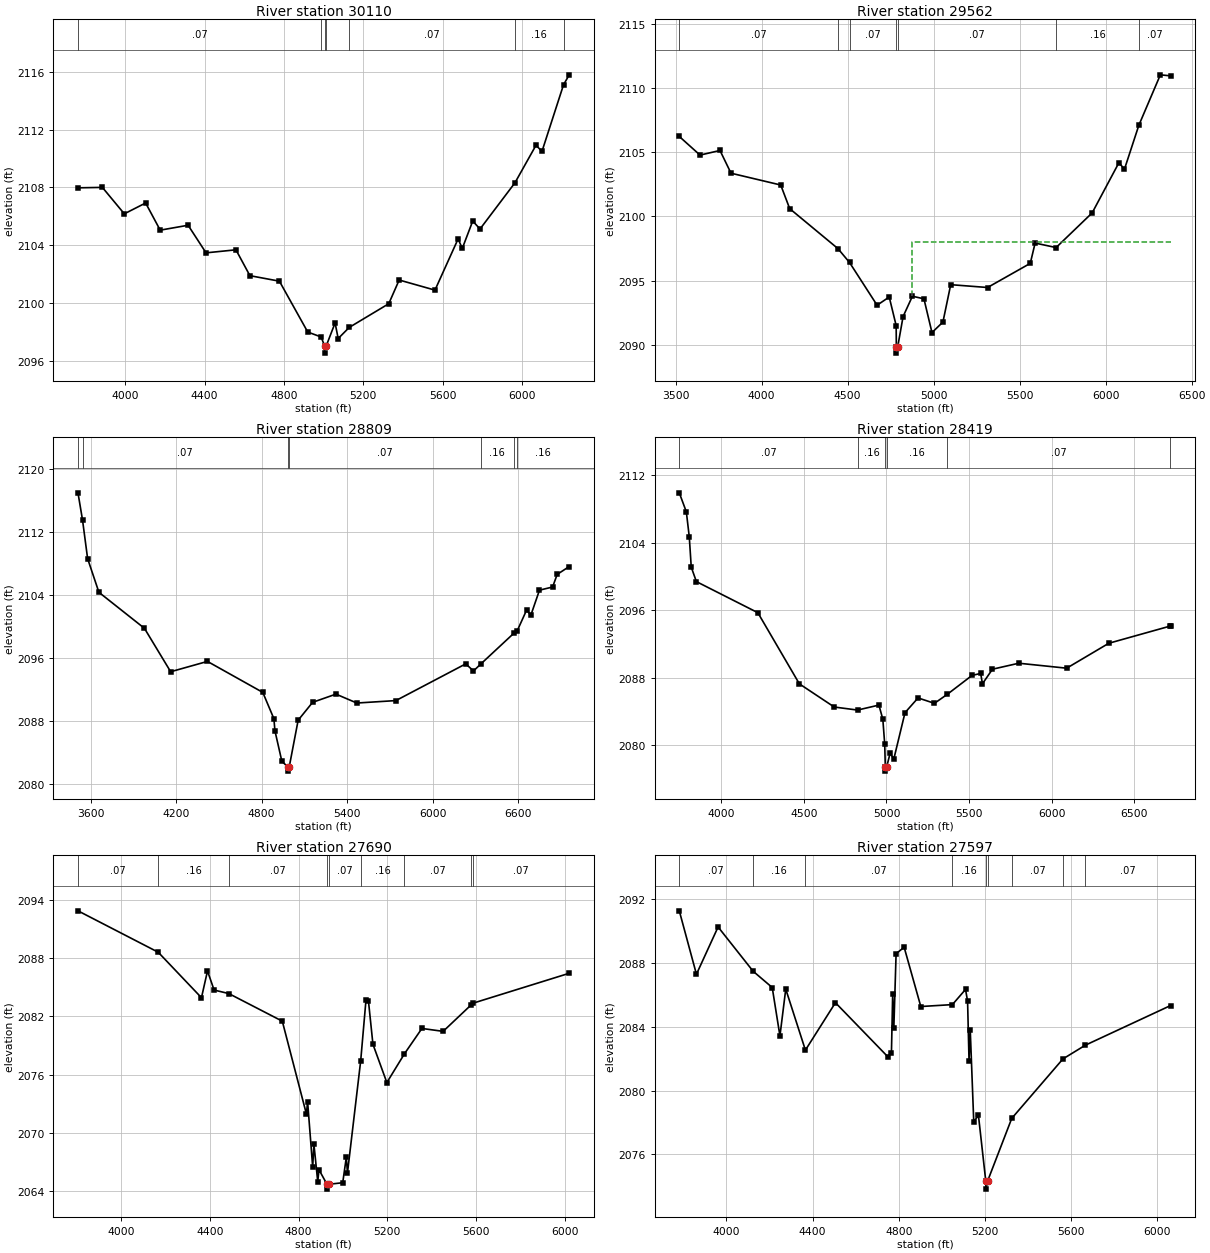
Type RM Length L Ch R = 1 ,30110   ,548,548,548
BEGIN DESCRIPTION:
Mapping XS ffce8ee6
END DESCRIPTION:
XS GIS Cut Line= 4
      1489482.68      6804847.42      1490657.14      6804969.81
      1490891.51      6804831.79      1491420.08      6803954.31
#Sta/Elev= 30
  3761.2 2107.97  3884.2    2108  3994.8 2106.17  4102.4 2106.92  4175.8 2105.04
  4316.5 2105.38    4407 2103.47  4557.8 2103.68  4628.2 2101.89  4776.9 2101.51
  4919.8 2097.99    4987 2097.65    5005 2097.03  5005.5 2096.53    5013 2097.03
  5057.7 2098.62  5073.3 2097.54  5129.1 2098.31  5328.4 2099.95  5380.8 2101.59
  5561.4 2100.89  5677.9 2104.43  5699.3 2103.78  5751.7 2105.67  5788.6 2105.12
  5964.8 2108.32  6070.6 2110.91  6101.2  2110.5  6209.6  2115.1  6238.4 2115.79
#Mann= 7 ,-1 , 0
  3761.2     .07       0    4987     .16       0    5005     .07       0
    5013     .16       0  5129.1     .07       0  5964.8     .16       0
  6209.6     .07       0
Bank Sta=5005,5013
XS Rating Curve= 0 ,0
Exp/Cntr=0.3,0.1

Type RM Length L Ch R = 1 ,29562   ,753,753,753
BEGIN DESCRIPTION:
NUBIA CREEK TRIBUTARY 1 47.0
END DESCRIPTION:
XS GIS Cut Line= 3
      1489624.25      6804952.14      1491054.26      6805327.32
      1491654.98      6804088.04
#Sta/Elev= 30
  3521.6 2106.22  3642.2 2104.77  3758.2 2105.13  3822.2 2103.36  4111.3 2102.44
  4163.4  2100.6  4443.7 2097.49  4511.1 2096.41  4671.4 2093.08  4741.9 2093.72
  4782.2  2091.5  4783.4 2089.85  4783.9 2089.35  4791.4 2089.85  4822.6  2092.2
  4876.7 2093.78  4943.7 2093.58  4990.4 2090.95  5054.1 2091.77  5099.3 2094.68
  5313.6 2094.46  5561.9 2096.34    5590 2097.92    5712 2097.57  5921.6 2100.27
  6077.2 2104.18  6109.3 2103.67  6192.9 2107.09    6318 2111.02  6377.2 2110.94
#Mann= 7 ,-1 , 0
  3521.6     .07       0  4443.7    .035       0  4511.1     .07       0
  4783.4     .07       0  4791.4     .07       0    5712     .16       0
  6192.9     .07       0
#XS Ineff= 2 , 0
       0                  4876.7       0    2098
Permanent Ineff=
       F       F
Bank Sta=4783.4,4791.4
XS Rating Curve= 0 ,0
Exp/Cntr=0.3,0.1

Type RM Length L Ch R = 1 ,28809   ,390,390,390
BEGIN DESCRIPTION:
NUBIA CREEK TRIBUTARY 1 46.0
END DESCRIPTION:
XS GIS Cut Line= 4
      1489407.08      6805259.48      1490805.17      6805772.94
      1491219.61      6805554.63      1491743.92      6804158.78
#Sta/Elev= 30
  3510.6 2116.94  3542.6 2113.48  3578.2  2108.6  3657.5 2104.32  3977.1 2099.75
  4161.3 2094.24  4419.6 2095.55  4808.1 2091.62  4886.1 2088.28  4893.3 2086.75
  4941.7  2082.9  4985.1 2082.13  4985.6 2081.63  4993.3 2082.13  5056.3 2088.09
    5158 2090.36  5321.8  2091.4  5468.4 2090.27  5742.6 2090.58    6233 2095.24
  6287.4 2094.34  6337.4  2095.2  6569.3  2099.1  6594.2 2099.43  6659.9 2102.05
  6690.2 2101.42  6750.6 2104.59  6842.8 2104.99  6874.9 2106.59  6959.5 2107.59
#Mann= 7 ,-1 , 0
  3510.6    .035       0  3542.6     .07       0  4985.1     .07       0
  4993.3     .07       0  6337.4     .16       0  6569.3     .07       0
  6594.2     .16       0
Bank Sta=4985.1,4993.3
XS Rating Curve= 0 ,0
Exp/Cntr=0.3,0.1

Type RM Length L Ch R = 1 ,28419   ,729,729,729
BEGIN DESCRIPTION:
NUBIA CREEK TRIBUTARY 1 44.0
END DESCRIPTION:
XS GIS Cut Line= 4
      1489538.71      6805637.96      1490705.56      6806098.64
       1491177.6      6805853.24      1491632.46      6804756.01
#Sta/Elev= 30
  3745.5 2109.94  3788.2 2107.68    3806 2104.71  3817.9 2101.12    3849  2099.4
  4221.1 2095.71  4472.6 2087.26  4683.7 2084.51  4824.6 2084.15  4954.2 2084.74
  4977.9 2083.05  4989.3 2080.09  4992.9  2077.4  4993.4  2076.9  5001.1  2077.4
  5021.9 2079.02  5044.5 2078.35  5112.1 2083.84  5191.1 2085.59  5290.4 2084.95
  5368.9 2086.03  5517.8 2088.26  5570.2  2088.5    5581 2087.27  5641.6    2089
  5801.2 2089.71  6090.9 2089.12    6346 2092.08  6717.6 2094.12  6719.8 2094.12
#Mann= 6 ,-1 , 0
  3745.5     .07       0  4824.6     .16       0  4992.9     .07       0
  5001.1     .16       0  5368.9     .07       0  6717.6     .16       0
Bank Sta=4992.9,5001.1
XS Rating Curve= 0 ,0
Exp/Cntr=0.3,0.1

Type RM Length L Ch R = 1 ,27690   ,93,93,93
BEGIN DESCRIPTION:
Mapping XS 71c43dc7
END DESCRIPTION:
XS GIS Cut Line= 5
      1489895.77      6806024.02      1490649.24      6806541.38
      1490864.52      6806642.07      1491201.33      6806527.49
      1491343.69      6805833.04
#Sta/Elev= 30
  3804.9 2092.89  4166.9 2088.62    4362 2083.93  4389.2 2086.69    4419 2084.72
  4485.1 2084.36  4726.7 2081.51  4835.4 2071.94  4840.9  2073.2  4863.8 2066.46
  4869.3 2068.83  4886.6 2064.96  4892.2 2066.19  4928.2 2064.69  4928.7 2064.19
  4936.5 2064.69  4999.3 2064.85  5015.5 2067.47  5020.7 2065.86  5080.4 2077.43
  5104.3 2083.71  5115.5 2083.57  5135.6 2079.13  5198.4 2075.18  5277.9 2078.15
  5356.6 2080.76  5452.3 2080.46  5578.7 2083.19  5586.3 2083.36  6021.2 2086.45
#Mann= 9 ,-1 , 0
  3804.9     .07       0  4166.9     .16       0  4485.1     .07       0
  4928.2     .07       0  4936.5     .07       0  5080.4     .16       0
  5277.9     .07       0  5578.7     .16       0  5586.3     .07       0
Bank Sta=4928.2,4936.5
XS Rating Curve= 0 ,0
Exp/Cntr=0.3,0.1

Type RM Length L Ch R = 1 ,27597   ,60,60,60
BEGIN DESCRIPTION:
Mapping XS 0d5c963a
END DESCRIPTION:
XS GIS Cut Line= 6
      1489885.35      6806086.51      1490673.55      6806655.96
      1490850.63      6806728.88      1490982.58      6806694.15
      1491246.46      6806551.79      1491392.31      6805888.56
#Sta/Elev= 30
  3781.1 2091.25  3860.7 2087.28  3961.2 2090.24  4123.7 2087.47  4212.5 2086.45
  4248.3 2083.42  4275.3 2086.35  4366.5 2082.53  4505.9  2085.5  4748.8 2082.12
  4765.9 2082.38  4771.6 2086.02    4777 2083.91  4787.5 2088.57  4824.9 2088.97
  4902.2 2085.26  5048.8 2085.38  5109.8 2086.33  5119.3  2085.6    5126 2081.87
  5131.7 2083.79  5147.9 2078.06  5169.8 2078.44  5203.8 2074.33  5204.3 2073.83
  5212.1 2074.33  5324.4 2078.26  5561.9 2081.98    5666 2082.84  6061.4 2085.32
#Mann= 9 ,-1 , 0
  3781.1     .07       0  4123.7     .16       0  4366.5     .07       0
  5048.8     .16       0  5203.8     .07       0  5212.1     .16       0
  5324.4     .07       0  5561.9     .16       0    5666     .07       0
Bank Sta=5203.8,5212.1
XS Rating Curve= 0 ,0
Exp/Cntr=0.3,0.1

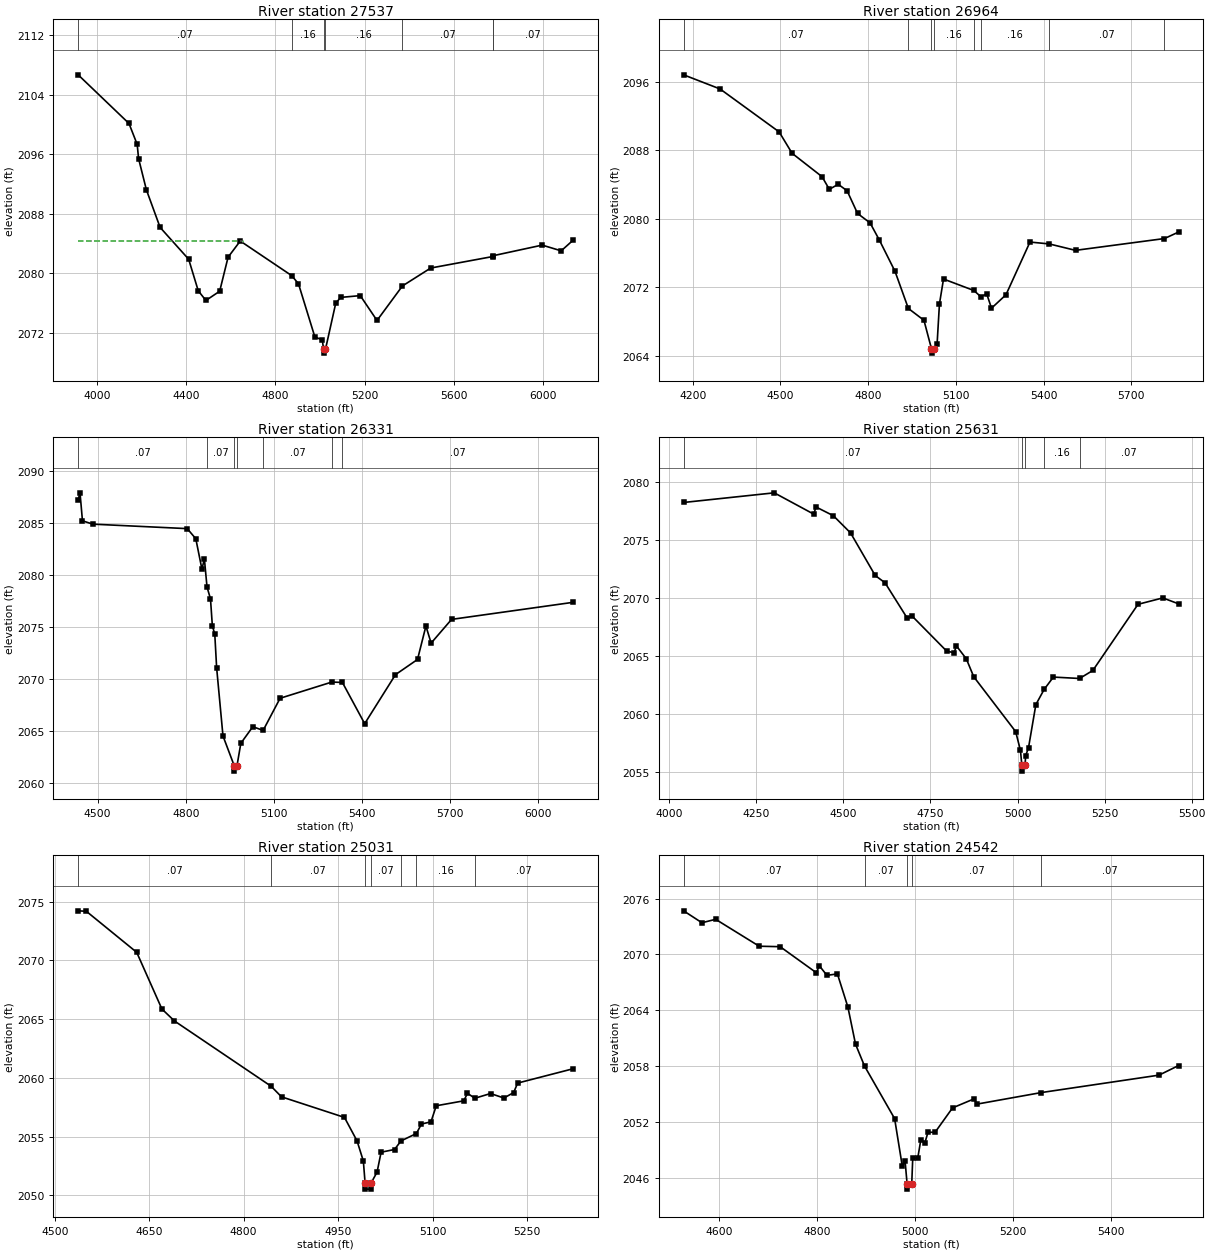
Type RM Length L Ch R = 1 ,27537   ,573,573,573
BEGIN DESCRIPTION:
Mapping XS 57da01f2
END DESCRIPTION:
XS GIS Cut Line= 5
      1489847.18      6806562.21       1490829.8       6806787.9
      1491020.77      6806770.54      1491305.49      6806628.18
      1491440.68      6805941.86
#Sta/Elev= 30
  3915.9  2106.7  4143.6 2100.16  4180.4 2097.34  4186.5 2095.45  4221.5 2091.25
    4283 2086.19    4411 2081.91  4453.9 2077.67  4488.2 2076.37  4549.9 2077.61
  4587.6 2082.19  4642.1 2084.36  4872.5 2079.71    4903 2078.61  4976.4 2071.46
  5009.7 2071.07  5015.5 2069.79    5016 2069.29  5023.8 2069.79  5069.9    2076
  5091.9 2076.78  5179.8 2077.02  5254.8 2073.68  5368.7 2078.32  5495.5 2080.73
  5772.7 2082.27  5774.4 2082.38  5994.9 2083.81    6080 2083.04  6133.7 2084.48
#Mann= 7 ,-1 , 0
  3915.9     .07       0  4872.5     .16       0  5015.5     .07       0
  5023.8     .16       0  5368.7     .07       0  5772.7     .16       0
  5774.4     .07       0
#XS Ineff= 2 , 0
       0  4652.4  2084.3               0
Permanent Ineff=
       F       F
Bank Sta=5015.5,5023.8
XS Rating Curve= 0 ,0
Exp/Cntr=0.3,0.1

Type RM Length L Ch R = 1 ,26964   ,633,633,633
BEGIN DESCRIPTION:
Mapping XS 8a1b3e4d
END DESCRIPTION:
XS GIS Cut Line= 4
      1490207.14       6807507.8      1490984.89      6807219.62
      1491464.06      6806962.67      1491512.66      6806646.72
#Sta/Elev= 30
  4168.9 2096.82  4293.5 2095.17  4495.6 2090.15  4539.9 2087.65  4642.2 2084.92
  4667.3 2083.44  4697.6 2084.03    4728 2083.27  4763.8 2080.62  4806.5 2079.52
  4838.5  2077.5  4891.8 2073.86  4937.5 2069.52  4990.8 2068.14  5016.6  2064.8
  5017.1  2064.3  5025.7  2064.8  5035.8 2065.39  5043.8 2070.05  5057.7 2072.96
  5161.4 2071.62  5185.2  2070.9  5205.6 2071.21  5221.8 2069.55  5271.3 2071.12
  5353.4 2077.28  5419.3 2077.06  5509.1 2076.31  5813.4 2077.69  5861.7 2078.45
#Mann= 8 ,-1 , 0
  4168.9     .07       0  4937.5     .16       0  5016.6     .07       0
  5025.7     .16       0  5161.4     .07       0  5185.2     .16       0
  5419.3     .07       0  5813.4     .16       0
Bank Sta=5016.6,5025.7
XS Rating Curve= 0 ,0
Exp/Cntr=0.3,0.1

Type RM Length L Ch R = 1 ,26331   ,700,700,700
BEGIN DESCRIPTION:
Mapping XS 0fb714ee
END DESCRIPTION:
XS GIS Cut Line= 4
      1490750.05      6808083.06      1491194.96      6807751.01
      1491526.99      6807010.99      1491574.73      6806696.35
#Sta/Elev= 30
    4434 2087.21  4440.3 2087.87  4448.6 2085.18  4484.1 2084.86  4805.1 2084.43
  4834.3 2083.46  4855.1 2080.54  4863.5 2081.51  4872.5 2078.82  4884.3 2077.68
  4890.6  2075.1  4898.9 2074.29  4905.2 2071.06  4926.8 2064.51  4965.3 2061.63
  4965.8 2061.13  4974.4 2061.63  4987.5  2063.8  5028.4  2065.4  5063.4 2065.04
  5121.1 2068.13  5297.4 2069.69  5333.2 2069.65    5409 2065.69  5513.8  2070.4
  5588.8 2071.86  5617.4 2075.07  5635.1 2073.43  5704.7 2075.71  6118.5 2077.35
#Mann= 7 ,-1 , 0
    4434     .07       0  4872.5     .07       0  4965.3     .07       0
  4974.4     .07       0  5063.4     .07       0  5297.4     .16       0
  5333.2     .07       0
Bank Sta=4965.3,4974.4
XS Rating Curve= 0 ,0
Exp/Cntr=0.3,0.1

Type RM Length L Ch R = 1 ,25631   ,600,600,600
BEGIN DESCRIPTION:
Mapping XS 0cf20df9
END DESCRIPTION:
XS GIS Cut Line= 3
      1491120.91      6808261.92      1491784.13      6807626.47
      1492077.94      6807218.09
#Sta/Elev= 30
    4041 2078.21  4301.3 2079.04  4414.5 2077.21  4421.4 2077.82  4471.1 2077.07
  4520.5 2075.59  4591.2 2071.93  4619.5  2071.3  4683.4 2068.25  4697.5 2068.43
  4796.3 2065.43  4817.6 2065.28  4824.6 2065.87  4852.9 2064.76  4874.2 2063.22
  4994.6  2058.5  5008.4 2056.88  5012.4  2055.6  5012.9  2055.1  5021.6  2055.6
  5023.2 2056.42  5031.5 2057.11  5052.6 2060.82  5076.4 2062.13  5102.9 2063.19
  5178.1 2063.07  5216.3 2063.76    5346 2069.45  5417.2    2070  5462.6 2069.49
#Mann= 5 ,-1 , 0
    4041     .07       0  5012.4     .07       0  5021.6     .07       0
  5076.4     .16       0  5178.1     .07       0
Bank Sta=5012.4,5021.6
XS Rating Curve= 0 ,0
Exp/Cntr=0.3,0.1

Type RM Length L Ch R = 1 ,25031   ,489,489,489
BEGIN DESCRIPTION:
Mapping XS a290c3dd
END DESCRIPTION:
XS GIS Cut Line= 3
      1491492.02      6807986.69       1491954.9      6807982.96
      1492230.03      6807812.98
#Sta/Elev= 30
  4537.1 2074.21  4550.1 2074.17  4630.1 2070.68  4670.1 2065.86  4690.1 2064.84
  4843.6 2059.29  4860.1 2058.39  4960.1 2056.64  4980.1 2054.64  4990.1 2052.93
  4992.9 2051.04  4993.4 2050.54  5001.7 2050.54  5002.2 2051.04  5011.9 2051.99
  5018.3 2053.68  5039.6 2053.91  5049.9 2054.64  5074.4 2055.27  5082.4 2056.08
  5097.5 2056.26  5105.9 2057.63  5149.6 2058.05  5155.5 2058.69  5167.2 2058.27
  5192.1 2058.67  5213.4 2058.29  5228.8 2058.75  5235.2 2059.56  5323.4 2060.78
#Mann= 7 ,-1 , 0
  4537.1     .07       0  4843.6     .07       0  4992.9     .07       0
  5002.2     .07       0  5049.9     .07       0  5074.4     .16       0
  5167.2     .07       0
Bank Sta=4992.9,5002.2
XS Rating Curve= 0 ,0
Exp/Cntr=0.3,0.1

Type RM Length L Ch R = 1 ,24542   ,246,246,246
BEGIN DESCRIPTION:
Mapping XS 74ec3856
END DESCRIPTION:
XS GIS Cut Line= 3
       1491448.8      6808193.28      1491854.96      6808434.92
      1492174.56      6808002.13
#Sta/Elev= 30
  4527.4 2074.68  4564.8  2073.4  4592.8 2073.77  4681.7 2070.88  4724.5 2070.83
  4798.5 2068.03  4804.4 2068.79    4820 2067.75  4841.4 2067.91  4862.8 2064.35
  4878.4 2060.36  4896.8 2058.01  4958.2 2052.37  4973.8 2047.28  4979.6 2047.78
  4983.8  2045.3  4984.3  2044.8  4993.1  2045.3  4995.2 2048.13  5005.4 2048.13
  5011.6 2050.06  5020.1 2049.79  5026.3  2050.9  5040.9 2050.91  5076.4 2053.52
  5120.3 2054.49  5126.5 2053.93  5257.9 2055.17  5498.1 2057.04    5538 2058.07
#Mann= 5 ,-1 , 0
  4527.4     .07       0  4896.8     .07       0  4983.8     .05       0
  4993.1     .07       0  5257.9     .07       0
Bank Sta=4983.8,4993.1
XS Rating Curve= 0 ,0
Exp/Cntr=0.3,0.1

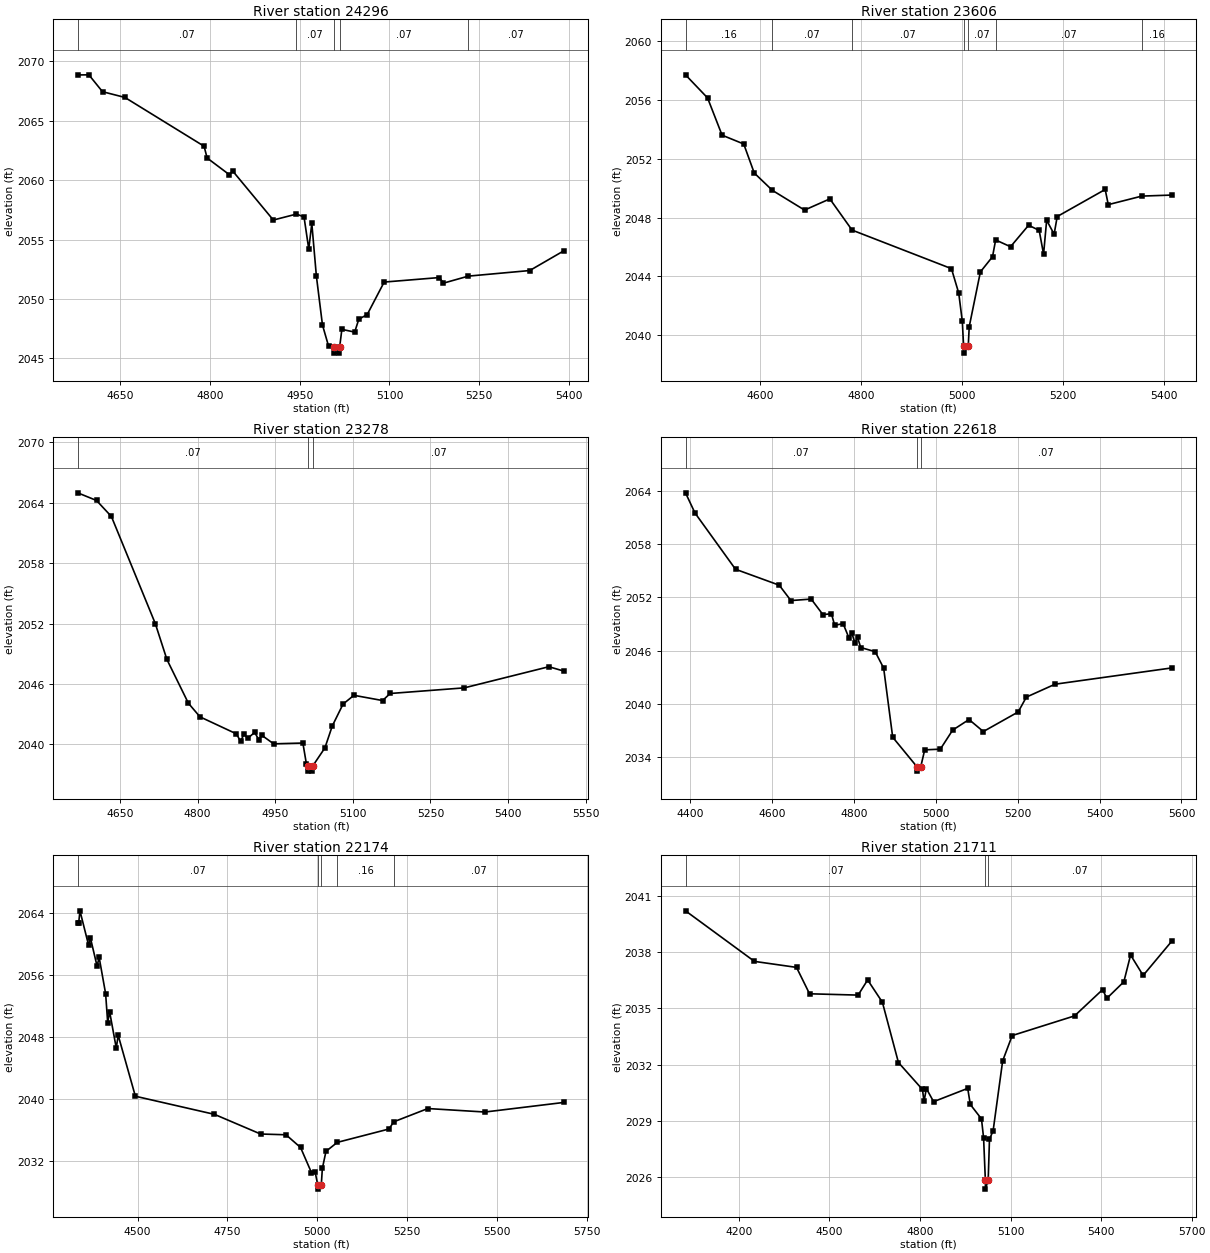
Type RM Length L Ch R = 1 ,24296   ,690,690,690
BEGIN DESCRIPTION:
Mapping XS 99b525dc
END DESCRIPTION:
XS GIS Cut Line= 4
      1491446.88      6808584.22      1491868.73      6808683.18
      1492084.01      6808457.48      1492104.86       6808393.5
#Sta/Elev= 30
  4579.1 2068.85  4597.7 2068.86  4620.5 2067.44  4657.8 2066.96  4790.2 2062.85
  4795.3 2061.86  4832.6 2060.45  4837.8 2060.78  4905.9 2056.64  4944.5 2057.14
  4957.2  2056.9  4965.1  2054.2  4970.2 2056.35  4977.8 2051.94    4988 2047.81
  4998.3 2046.01  5007.4 2045.94  5007.9 2045.44  5016.2 2045.44  5016.7 2045.94
  5020.4 2047.44  5041.8 2047.21  5048.7 2048.29  5062.8 2048.69  5091.1 2051.42
  5183.3  2051.8  5190.2 2051.33  5231.7 2051.92  5334.3 2052.39  5391.6 2054.06
#Mann= 5 ,-1 , 0
  4579.1     .07       0  4944.5     .07       0  5007.4     .05       0
  5016.7     .07       0  5231.7     .07       0
Bank Sta=5007.4,5016.7
XS Rating Curve= 0 ,0
Exp/Cntr=0.3,0.1

Type RM Length L Ch R = 1 ,23606   ,328,328,328
BEGIN DESCRIPTION:
Mapping XS a3115b79
END DESCRIPTION:
XS GIS Cut Line= 4
      1491613.99      6808807.03      1492073.15      6809189.81
      1492212.51      6808991.34      1492219.46      6808868.94
#Sta/Elev= 30
  4451.8  2057.7  4495.5 2056.13  4524.2  2053.6  4567.1    2053  4587.9 2051.03
  4623.8 2049.85  4687.5 2048.51  4737.6 2049.27  4781.6 2047.15  4978.4 2044.53
  4992.8 2042.87  4999.9 2040.95  5002.4 2039.29  5002.9 2038.79  5011.7 2039.29
  5013.6 2040.59  5035.7 2044.31  5059.7 2045.34  5065.9 2046.48  5095.4 2046.02
  5131.2 2047.48  5152.1 2047.13  5160.8 2045.51  5166.9 2047.82  5181.7 2046.87
  5187.8 2048.07  5282.8 2049.91  5288.9 2048.88  5355.4 2049.46  5414.7 2049.53
#Mann= 7 ,-1 , 0
  4451.8     .16       0  4623.8     .07       0  4781.6     .07       0
  5002.4     .07       0  5011.7     .07       0  5065.9     .07       0
  5355.4     .16       0
Bank Sta=5002.4,5011.7
XS Rating Curve= 0 ,0
Exp/Cntr=0.3,0.1

Type RM Length L Ch R = 1 ,23278   ,660,660,660
BEGIN DESCRIPTION:
Mapping XS e0932d70
END DESCRIPTION:
XS GIS Cut Line= 4
      1491509.81      6809001.46        1491780.      6809338.41
      1491883.49      6809432.09      1492180.03      6809212.98
#Sta/Elev= 30
  4568.1 2064.99  4604.4 2064.23  4633.2 2062.64  4718.1    2052  4740.5 2048.44
  4782.1 2044.09  4804.5 2042.74  4874.9 2041.05  4882.9 2040.31  4889.3 2040.99
  4896.9 2040.62  4910.1 2041.19  4918.1 2040.49  4924.5 2040.89  4946.9 2040.06
  5003.4 2040.14  5010.2 2038.07    5013 2037.85  5013.5 2037.35  5021.8 2037.35
  5022.3 2037.85    5046 2039.66  5060.2 2041.83  5081.1 2044.01  5102.1 2044.88
  5157.5 2044.36  5172.1 2045.06  5315.5 2045.62    5479 2047.72  5508.3 2047.28
#Mann= 3 ,-1 , 0
  4568.1     .07       0    5013     .07       0  5022.3     .07       0
Bank Sta=5013,5022.3
XS Rating Curve= 0 ,0
Exp/Cntr=0.3,0.1

Type RM Length L Ch R = 1 ,22618   ,444,444,444
BEGIN DESCRIPTION:
Mapping XS b730e67a
END DESCRIPTION:
XS GIS Cut Line= 3
      1490783.31      6809047.19      1491254.17      6809437.97
      1491830.03        6809463.
#Sta/Elev= 30
  4388.1 2063.74  4411.3 2061.47  4510.3 2055.15  4617.1 2053.36  4645.7 2051.63
  4695.2  2051.8  4723.9 2050.05  4744.7 2050.15  4752.5 2048.86  4773.3 2049.03
  4787.7 2047.41  4794.2 2048.03    4802 2046.88  4808.5 2047.49  4816.3 2046.35
  4851.5 2045.89  4872.3 2044.04  4894.4 2036.27  4953.5 2032.96    4954 2032.46
    4963 2032.96  4972.6 2034.85  5010.8 2034.93  5040.9 2037.07  5080.9 2038.26
  5115.9 2036.91    5201 2039.11    5221 2040.78  5291.1 2042.23  5576.4 2044.06
#Mann= 3 ,-1 , 0
  4388.1     .07       0  4953.5     .07       0    4963     .07       0
Bank Sta=4953.5,4963
XS Rating Curve= 0 ,0
Exp/Cntr=0.3,0.1

Type RM Length L Ch R = 1 ,22174   ,463,463,463
BEGIN DESCRIPTION:
Mapping XS c5282535
END DESCRIPTION:
XS GIS Cut Line= 4
      1490858.09      6809346.15      1491038.22      6809782.37
      1491441.86       6809845.3      1491909.06      6809766.87
#Sta/Elev= 30
  4333.2 2062.67  4335.7 2062.67  4339.4  2064.3  4363.3 2059.89  4368.7 2060.77
  4387.2 2057.13  4392.7 2058.32  4410.9 2053.59  4416.6 2049.87    4422 2051.27
  4440.5 2046.58  4445.9 2048.22  4493.7 2040.35  4713.9 2038.01  4842.4 2035.47
  4913.2 2035.37  4953.7 2033.73  4984.1 2030.48  4994.2 2030.56  5001.9 2028.85
  5002.4 2028.35  5011.4 2028.85  5014.4 2031.02  5024.5 2033.23    5056 2034.39
  5200.2 2036.12  5212.9 2037.04  5308.1 2038.76  5467.2 2038.31  5687.4 2039.55
#Mann= 5 ,-1 , 0
  4333.2     .07       0  5001.9     .07       0  5011.4     .07       0
    5056     .16       0  5212.9     .07       0
Bank Sta=5001.9,5011.4
XS Rating Curve= 0 ,0
Exp/Cntr=0.3,0.1

Type RM Length L Ch R = 1 ,21711   ,708,708,708
BEGIN DESCRIPTION:
Mapping XS 099ac85e
END DESCRIPTION:
XS GIS Cut Line= 4
      1490796.73      6809473.74      1491150.92      6810088.36
      1491520.71      6810210.75      1491920.85      6809891.16
#Sta/Elev= 30
  4023.2 2040.21  4251.6 2037.51    4391 2037.19  4434.1 2035.78    4595 2035.71
  4626.6 2036.52  4675.4 2035.33  4728.6 2032.11  4808.2 2030.67  4813.4 2030.03
  4821.1 2030.72  4845.1 2030.02  4958.1 2030.73  4966.7 2029.87  5003.7  2029.1
  5010.7 2028.09  5016.5 2025.85    5017 2025.35    5026 2025.85  5030.2 2028.01
  5042.3 2028.47  5073.9  2032.2  5105.5 2033.55    5312  2034.6  5404.8    2036
  5419.2 2035.54  5475.3 2036.42  5497.7 2037.85  5539.3 2036.76  5634.2 2038.59
#Mann= 3 ,-1 , 0
  4023.2     .07       0  5016.5     .07       0    5026     .07       0
Bank Sta=5016.5,5026
XS Rating Curve= 0 ,0
Exp/Cntr=0.3,0.1

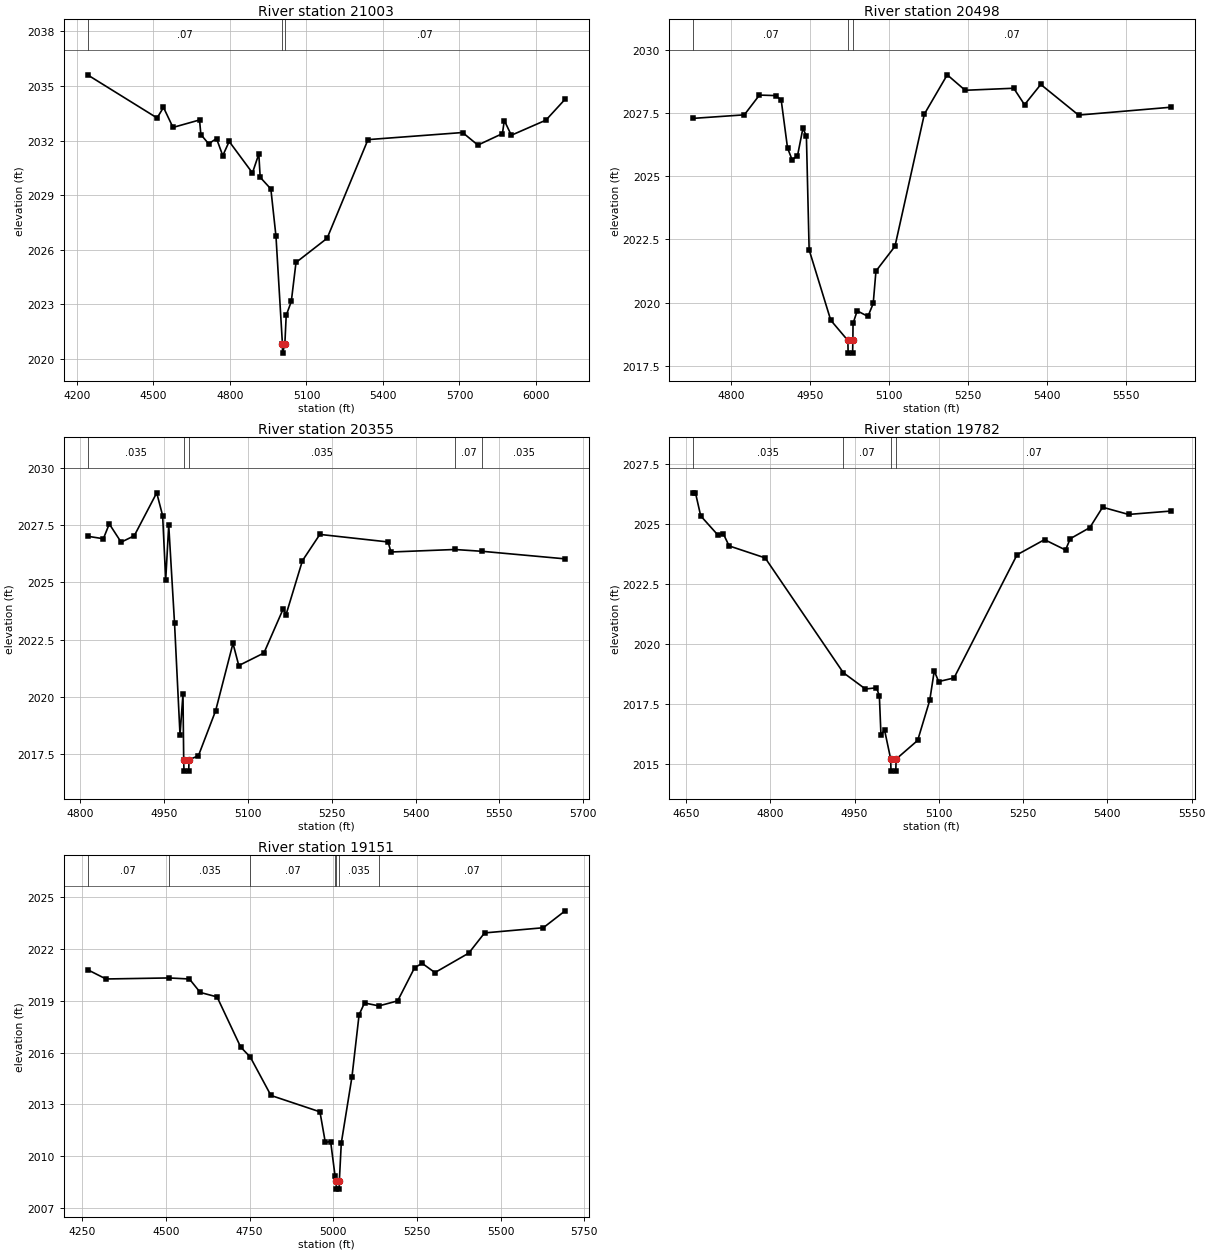
Type RM Length L Ch R = 1 ,21003   ,505,505,505
BEGIN DESCRIPTION:
Mapping XS abb56b05
END DESCRIPTION:
XS GIS Cut Line= 4
      1490606.67      6809783.72      1490851.44      6810445.13
       1491385.3      6810481.59      1491941.31       6810180.2
#Sta/Elev= 30
  4241.5 2035.61  4514.2 2033.24  4539.3 2033.82  4576.6 2032.72  4680.6 2033.13
  4685.9 2032.33  4716.3 2031.82  4747.2 2032.11  4771.8 2031.17  4796.9 2031.95
  4888.1 2030.22  4913.1 2031.26  4918.5 2029.98  4960.3 2029.34  4980.4 2026.74
  5005.7 2020.82  5006.2 2020.32  5015.2 2020.82  5020.5 2022.39  5040.5 2023.16
  5058.9  2025.3  5180.9 2026.63  5341.2 2032.05  5712.2 2032.44  5772.1 2031.75
  5868.3 2032.38  5875.8  2033.1  5903.3 2032.29  6038.9 2033.12  6114.3 2034.27
#Mann= 3 ,-1 , 0
  4241.5     .07       0  5005.7     .07       0  5015.2     .07       0
Bank Sta=5005.7,5015.2
XS Rating Curve= 0 ,0
Exp/Cntr=0.3,0.1

Type RM Length L Ch R = 1 ,20498   ,143,143,143
BEGIN DESCRIPTION:
Mapping XS ec118f3e
END DESCRIPTION:
XS GIS Cut Line= 3
      1490572.85      6810739.81      1490838.42      6810807.11
      1491455.61      6810945.13
#Sta/Elev= 30
  4728.5 2027.28  4825.8 2027.42  4854.5  2028.2  4885.5 2028.18  4895.8    2028
  4907.8 2026.11  4916.4 2025.65  4926.7  2025.8    4937 2026.89  4943.6 2026.58
  4948.8 2022.09  4989.8 2019.31  5022.3 2018.51  5022.8 2018.01  5031.3 2018.01
  5031.8 2018.51  5032.1 2019.18    5040 2019.68  5060.4 2019.46  5070.4 2019.97
  5075.6 2021.25  5111.7 2022.23  5167.5 2027.45  5210.9    2029  5244.9 2028.39
  5337.1 2028.47  5357.6 2027.82  5388.4 2028.62  5460.1 2027.41  5634.9 2027.72
#Mann= 3 ,-1 , 0
  4728.5     .07       0  5022.3     .07       0  5031.8     .07       0
Bank Sta=5022.3,5031.8
XS Rating Curve= 0 ,0
Exp/Cntr=0.3,0.1

Type RM Length L Ch R = 1 ,20355   ,573,573,573
BEGIN DESCRIPTION:
Mapping XS f49ad305
END DESCRIPTION:
XS GIS Cut Line= 3
      1490578.36      6810855.99       1490762.9      6810921.69
      1491398.29      6811096.16
#Sta/Elev= 30
    4813 2027.02  4841.3 2026.91  4851.9 2027.56  4873.1 2026.76  4896.6 2027.04
  4936.8 2028.92  4947.4 2027.92  4952.9 2025.11  4958.3 2027.51  4968.7 2023.21
  4978.5 2018.33  4983.8 2020.11  4985.1 2017.24  4985.6 2016.74  4994.1 2016.74
  4994.6 2017.24  5011.4 2017.41  5042.2 2019.38  5073.3 2022.33  5083.7 2021.36
  5128.7 2021.91  5163.2 2023.84  5168.3 2023.59  5197.6 2025.95  5228.8  2027.1
  5350.9 2026.77  5356.1 2026.33  5470.3 2026.44  5519.7 2026.36  5667.8 2026.03
#Mann= 5 ,-1 , 0
    4813    .035       0  4985.1    .035       0  4994.6    .035       0
  5470.3     .07       0  5519.7    .035       0
Bank Sta=4985.1,4994.6
XS Rating Curve= 0 ,0
Exp/Cntr=0.3,0.1

Type RM Length L Ch R = 1 ,19782   ,631,631,631
BEGIN DESCRIPTION:
Mapping XS 6426f2f2
END DESCRIPTION:
XS GIS Cut Line= 3
      1490571.57      6811394.38      1490904.88      6811443.85
      1491350.08      6811188.71
#Sta/Elev= 30
  4662.5 2026.31  4666.8 2026.31  4676.1 2025.35  4706.4 2024.56  4716.3 2024.61
  4726.6  2024.1  4790.8  2023.6  4929.9 2018.82  4969.3 2018.14    4989 2018.19
  4994.1 2017.86    4997 2016.21  5003.3 2016.44  5014.3 2015.22  5014.8 2014.72
  5023.4 2014.72  5023.9 2015.22  5062.3    2016  5083.8 2017.67  5091.8 2018.89
  5099.7 2018.45    5127  2018.6  5239.2 2023.73  5288.1 2024.36  5325.5 2023.93
  5333.9  2024.4  5368.7 2024.86  5391.5 2025.71  5437.6 2025.41  5512.6 2025.55
#Mann= 4 ,-1 , 0
  4662.5    .035       0  4929.9     .07       0  5014.3     .07       0
  5023.9     .07       0
Bank Sta=5014.3,5023.9
XS Rating Curve= 0 ,0
Exp/Cntr=0.3,0.1

Type RM Length L Ch R = 1 ,19151   ,547,547,547
BEGIN DESCRIPTION:
Mapping XS 150329fa
END DESCRIPTION:
XS GIS Cut Line= 4
      1490450.28      6811939.07      1491036.25      6812004.18
      1491264.12      6811921.72      1491357.44      6811333.58
#Sta/Elev= 30
  4265.5 2020.81  4320.6 2020.27  4508.2 2020.33  4569.9 2020.27  4602.3 2019.49
  4652.6 2019.23    4723 2016.33    4752 2015.74  4813.6 2013.52  4960.1 2012.57
  4976.1  2010.8    4992 2010.85  5005.4 2008.83  5008.5 2008.59    5009 2008.09
  5017.6 2008.09  5018.1 2008.59  5023.9 2010.76  5055.8  2014.6  5077.1  2018.2
  5093.3 2018.88  5136.3 2018.71  5192.3    2019  5242.9 2020.92  5265.4 2021.18
  5303.7 2020.64  5404.9 2021.77  5452.2 2022.94  5627.7 2023.24  5692.9 2024.22
#Mann= 7 ,-1 , 0
  4265.5     .07       0  4508.2    .035       0    4752     .07       0
  5005.4    .035       0  5008.5     .07       0  5018.1    .035       0
  5136.3     .07       0
Bank Sta=5008.5,5018.1
XS Rating Curve= 0 ,0
Exp/Cntr=0.3,0.1