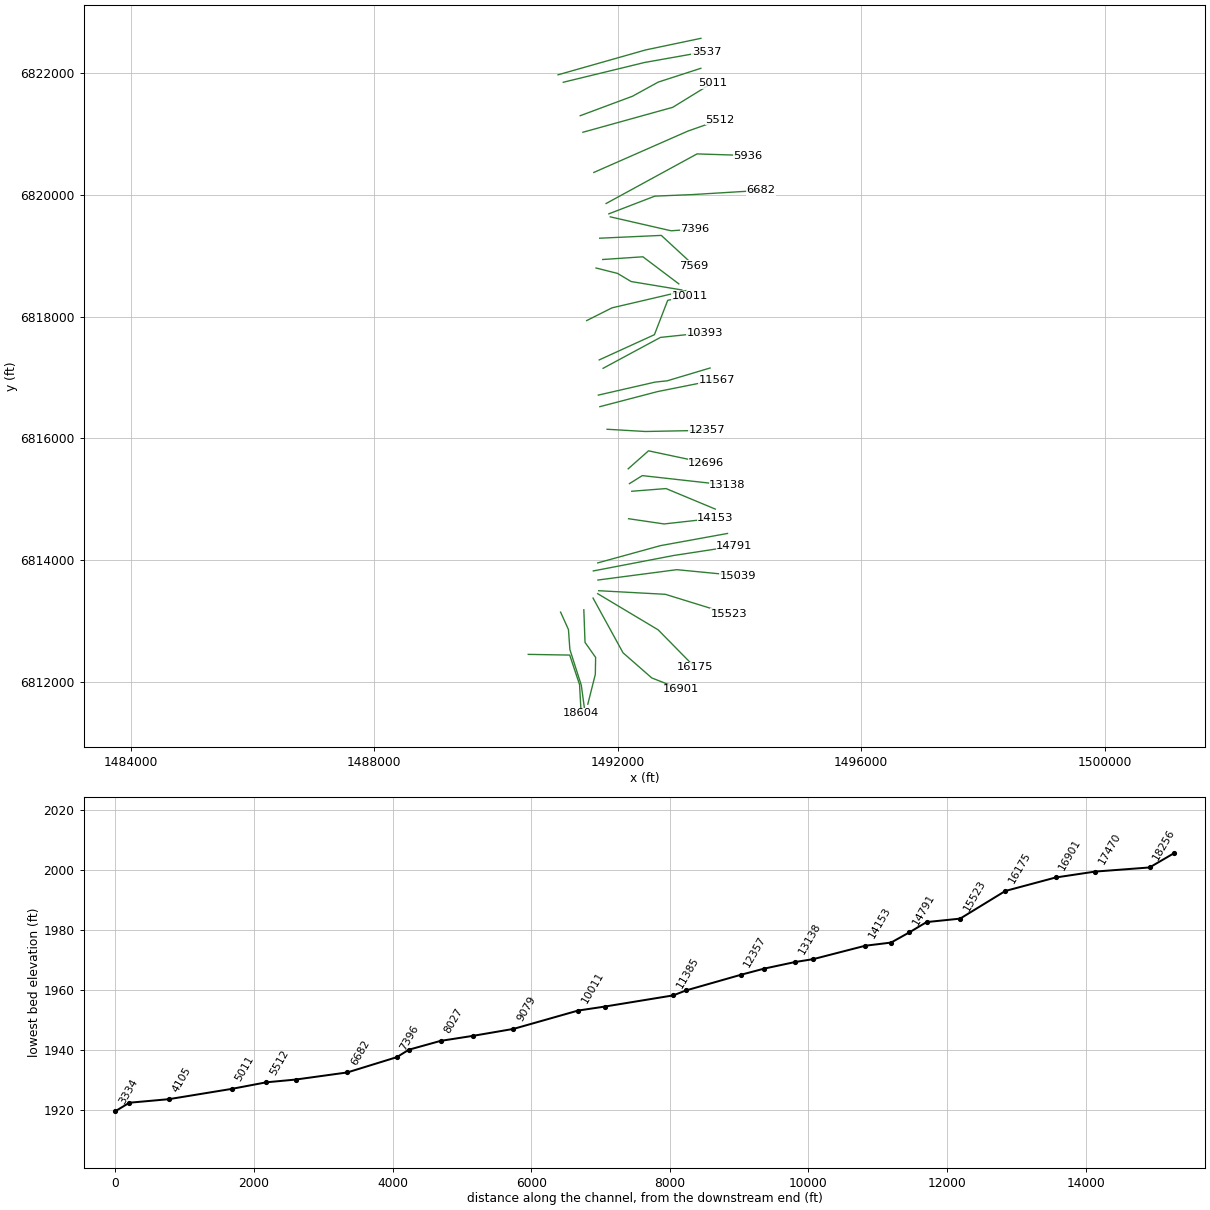
HEC-RAS study NUBIA CREEK TRIBUTARY 1.prj: NUBIA CREEK TRIBUTARY 1 Base Level Engineering

--- NUBIA CREEK TRIBUTARY 1.g01 (geometry) --- (continued)

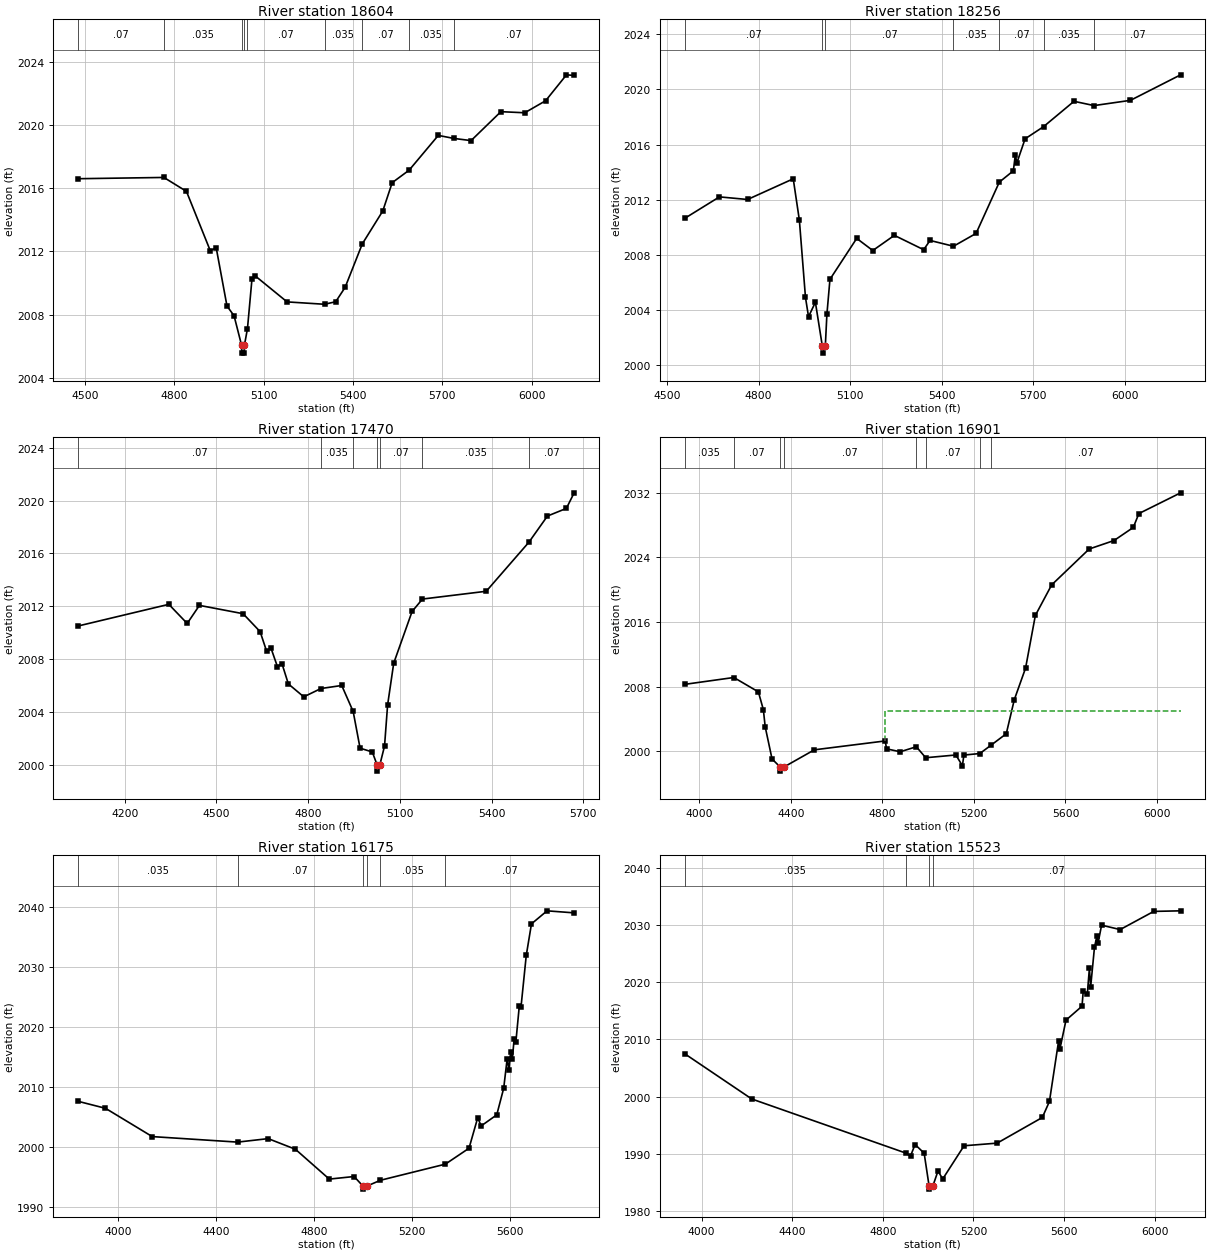
Type RM Length L Ch R = 1 ,18604   ,348,348,348
BEGIN DESCRIPTION:
Mapping XS 41327bf0
END DESCRIPTION:
XS GIS Cut Line= 4
       1490531.5      6812451.47       1491212.9      6812439.95
      1491374.36      6811955.57      1491400.36      6811482.26
#Sta/Elev= 30
  4476.8  2016.6  4764.6 2016.68  4840.4  2015.8  4920.4 2012.05  4940.4 2012.23
  4976.6 2008.55  5000.4 2007.93  5025.6 2006.07  5026.1 2005.57  5034.7 2005.57
  5035.2 2006.07  5045.4 2007.12  5060.4 2010.23  5070.4 2010.47  5178.5 2008.81
  5304.3 2008.66  5341.8 2008.82  5373.5 2009.73  5431.2 2012.48    5500 2014.56
  5531.6 2016.35  5588.5 2017.14  5686.5 2019.34    5738 2019.15  5796.6 2019.01
  5896.8 2020.84  5976.9 2020.77    6047 2021.53  6117.1 2023.17  6142.9 2023.13
#Mann= 9 ,-1 , 0
  4476.8     .07       0  4764.6    .035       0  5025.6    .035       0
  5035.2    .035       0  5045.4     .07       0  5304.3    .035       0
  5431.2     .07       0  5588.5    .035       0    5738     .07       0
Bank Sta=5025.6,5035.2
XS Rating Curve= 0 ,0
Exp/Cntr=0.3,0.1

Type RM Length L Ch R = 1 ,18256   ,786,786,786
BEGIN DESCRIPTION:
Mapping XS f0436b42
END DESCRIPTION:
XS GIS Cut Line= 5
      1491062.73      6813145.89      1491192.07      6812859.22
       1491215.5      6812531.09        1491403.      6811945.15
      1491452.32      6811581.75
#Sta/Elev= 30
  4557.9 2010.65  4671.8 2012.21    4764 2012.02  4913.7 2013.52  4933.8 2010.52
  4953.8 2004.92  4963.8 2003.52  4986.3 2004.57  5009.1 2001.38  5009.6 2000.88
  5018.8 2001.38    5024 2003.69    5034 2006.23  5121.7  2009.2  5174.4 2008.32
  5245.1 2009.42  5341.1 2008.38  5362.1 2009.05  5438.9 2008.63  5512.9 2009.56
  5589.1 2013.28  5635.1  2014.1  5641.5 2015.25  5646.7 2014.68  5673.6 2016.42
    5734  2017.3  5833.9 2019.14  5899.5 2018.83  6018.9 2019.21  6183.3 2021.06
#Mann= 7 ,-1 , 0
  4557.9     .07       0  5009.1     .07       0  5018.8     .07       0
  5438.9    .035       0  5589.1     .07       0    5734    .035       0
  5899.5     .07       0
Bank Sta=5009.1,5018.8
XS Rating Curve= 0 ,0
Exp/Cntr=0.3,0.1

Type RM Length L Ch R = 1 ,17470   ,569,569,569
BEGIN DESCRIPTION:
Mapping XS c7fe071c
END DESCRIPTION:
XS GIS Cut Line= 5
      1491444.66      6813184.12      1491464.11      6812648.72
      1491638.58      6812401.33      1491633.38      6812122.68
      1491509.93      6811633.28
#Sta/Elev= 30
    4048  2010.5  4344.3 2012.14  4404.4 2010.69  4444.4 2012.06  4587.2 2011.43
  4642.9 2010.07  4663.8 2008.61  4678.6 2008.81  4699.5 2007.42  4714.3 2007.65
  4735.2 2006.11  4785.7 2005.13  4841.8 2005.76  4909.8 2005.99  4947.2 2004.02
  4969.8 2001.24  5009.8 2000.95    5025    2000  5025.5  1999.5  5034.7    2000
  5049.8  2001.4  5059.8 2004.51  5079.8 2007.68  5139.9  2011.6  5173.8 2012.54
  5382.4 2013.13    5522 2016.85  5582.5 2018.83  5644.4 2019.41  5669.9 2020.59
#Mann= 7 ,-1 , 0
    4048     .07       0  4841.8    .035       0  4947.2     .07       0
    5025     .07       0  5034.7     .07       0  5173.8    .035       0
    5522     .07       0
Bank Sta=5025,5034.7
XS Rating Curve= 0 ,0
Exp/Cntr=0.3,0.1

Type RM Length L Ch R = 1 ,16901   ,726,726,726
BEGIN DESCRIPTION:
Mapping XS 0b6851b6
END DESCRIPTION:
XS GIS Cut Line= 4
      1491595.74      6813376.54      1492088.77      6812477.27
      1492560.99      6812064.08      1493040.09       6811876.6
#Sta/Elev= 30
  3935.8 2008.28  4150.6 2009.13  4257.9 2007.35  4279.7 2005.14  4287.7 2003.02
  4317.6 1999.04  4353.4 1998.03  4353.9 1997.53    4369 1998.03  4502.5 2000.17
  4812.3 2001.27  4818.1 2000.29  4877.9 1999.93  4948.3 2000.55  4989.2 1999.19
  5121.1 1999.53  5149.5  1998.2  5156.2 1999.52  5225.7 1999.71  5274.6 2000.74
  5341.3 2002.16  5376.4 2006.38  5425.7  2010.3  5468.4 2016.82  5539.6  2020.6
  5703.7 2025.05  5812.3  2026.1  5896.4 2027.72  5920.9 2029.44  6103.3 2032.01
#Mann= 8 ,-1 , 0
  3935.8    .035       0  4150.6     .07       0  4353.4     .07       0
    4369     .07       0  4948.3     .16       0  4989.2     .07       0
  5225.7     .16       0  5274.6     .07       0
#XS Ineff= 2 , 0
       0                  4812.3       0    2005
Permanent Ineff=
       F       F
Bank Sta=4353.4,4369
XS Rating Curve= 0 ,0
Exp/Cntr=0.3,0.1

Type RM Length L Ch R = 1 ,16175   ,652,652,652
BEGIN DESCRIPTION:
Mapping XS 6236bb60
END DESCRIPTION:
XS GIS Cut Line= 3
      1491672.12      6813448.62      1492665.16      6812854.88
      1493271.38      6812238.27
#Sta/Elev= 30
  3838.2 2007.65  3949.4 2006.49    4140 2001.78  4487.9 2000.86  4612.7 2001.44
  4723.6 1999.67  4861.7  1994.7  4962.9 1995.13  4999.1 1993.53  4999.6 1993.03
  5014.8 1993.53  5069.7  1994.5  5334.9 1997.19  5431.3 1999.84  5466.7 2004.91
  5480.9 2003.56  5544.4  2005.4  5572.7 2009.84  5586.9 2014.77  5593.9 2012.85
    5601 2015.89    5608 2014.71  5615.2 2018.03  5622.2  2017.5  5636.3 2023.53
  5643.4 2023.42  5664.6 2031.94  5685.9 2037.21  5749.5 2039.38  5859.9 2039.04
#Mann= 6 ,-1 , 0
  3838.2    .035       0  4487.9     .07       0  4999.1     .07       0
  5014.8     .07       0  5069.7    .035       0  5334.9     .07       0
Bank Sta=4999.1,5014.8
XS Rating Curve= 0 ,0
Exp/Cntr=0.3,0.1

Type RM Length L Ch R = 1 ,15523   ,484,484,484
BEGIN DESCRIPTION:
Mapping XS a3b83044
END DESCRIPTION:
XS GIS Cut Line= 3
      1491689.47      6813497.24      1492783.21      6813438.21
      1493828.33       6813115.3
#Sta/Elev= 30
  3925.4  2007.5  4221.4 1999.58  4900.9 1990.12  4922.4  1989.6  4942.4 1991.61
  4982.5 1990.09  5004.5  1984.3    5005  1983.8  5020.5  1984.3  5043.6 1986.97
  5064.5 1985.58  5158.7 1991.39  5304.7 1991.85  5504.1 1996.34  5535.5 1999.14
  5576.2 2009.78  5581.5 2008.29  5608.7 2013.38  5679.4 2015.82  5684.6  2018.4
  5702.9 2018.03    5712 2022.48  5717.3 2019.13  5734.3 2026.11  5744.7 2028.03
  5749.9 2026.81  5765.7    2030  5847.8 2029.23    5996 2032.41  6114.6 2032.51
#Mann= 4 ,-1 , 0
  3925.4    .035       0  4900.9     .07       0  5004.5     .07       0
  5020.5     .07       0
Bank Sta=5004.5,5020.5
XS Rating Curve= 0 ,0
Exp/Cntr=0.3,0.1

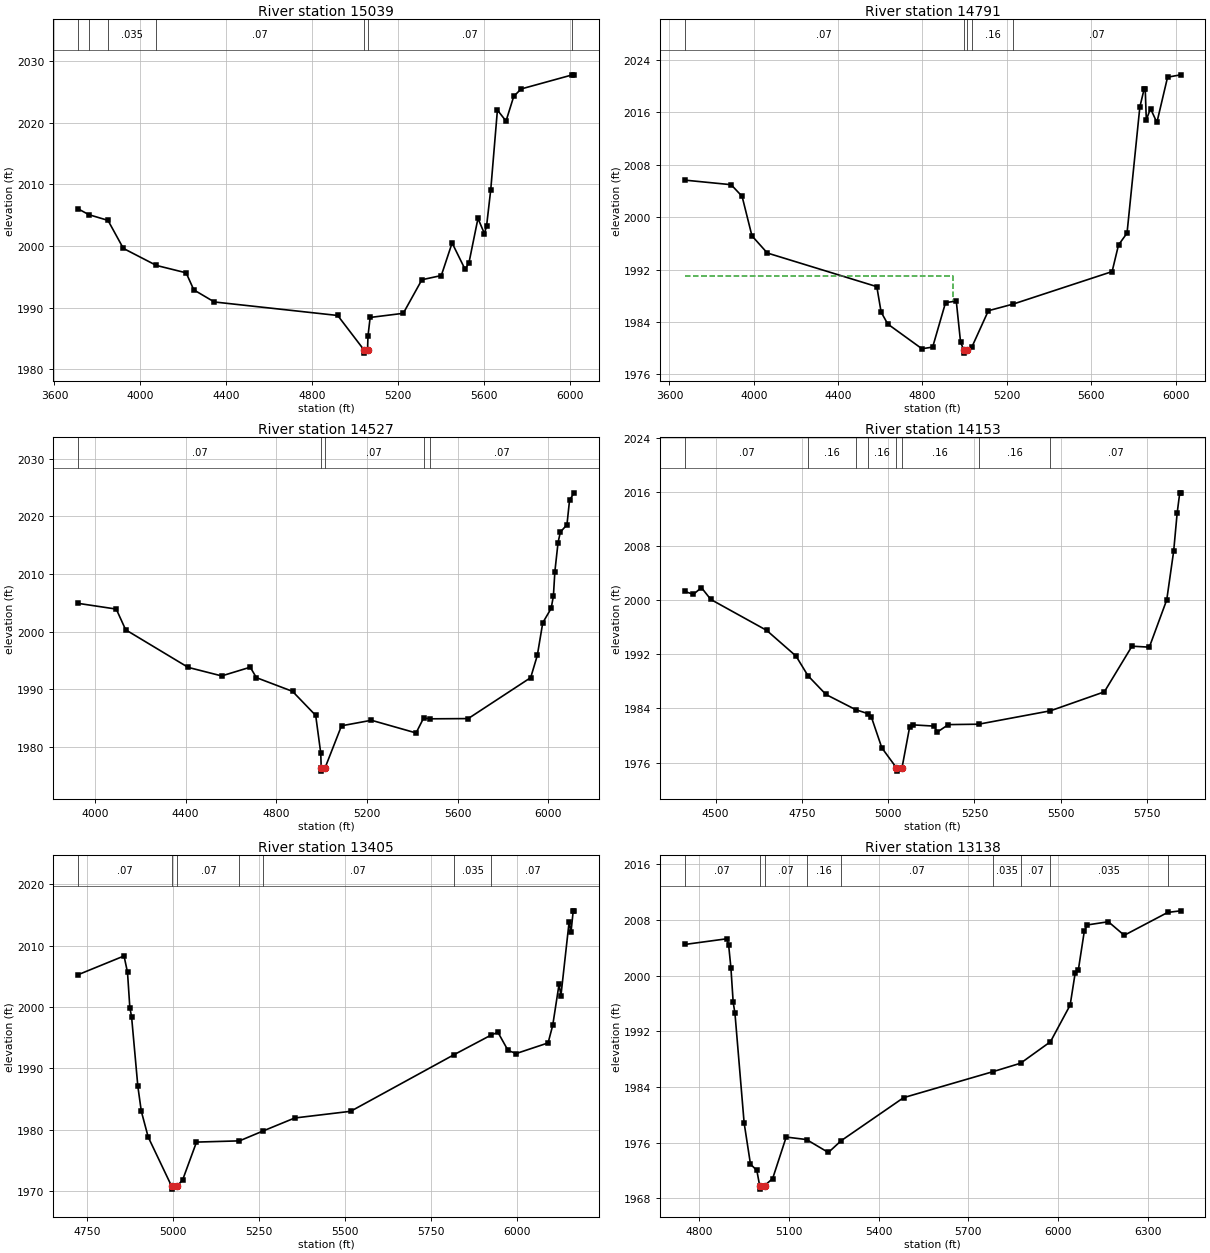
Type RM Length L Ch R = 1 ,15039   ,248,248,248
BEGIN DESCRIPTION:
Mapping XS cfc97111
END DESCRIPTION:
XS GIS Cut Line= 3
      1491676.59      6813672.83      1492971.75      6813842.97
      1493970.85      6813745.84
#Sta/Elev= 30
  3710.5 2006.02  3760.2 2005.08  3849.1 2004.16  3920.7 1999.62  4074.4 1996.86
  4213.2 1995.66  4248.9  1992.9  4344.3 1990.94  4919.2 1988.75  5042.1 1983.15
  5042.6 1982.65  5058.2 1983.15  5060.2 1985.39  5070.3 1988.43  5224.6  1989.1
  5311.4 1994.54  5401.8 1995.22  5452.1  2000.5  5512.4 1996.24  5530.3 1997.24
  5572.6 2004.48  5602.8    2002  5612.8 2003.29  5632.2 2009.16  5663.1 2022.03
  5703.3 2020.25  5739.2 2024.25  5773.6 2025.45  6008.5  2027.7  6020.6 2027.74
#Mann= 7 ,-1 , 0
  3710.5    .035       0  3760.2     .07       0  3849.1    .035       0
  4074.4     .07       0  5042.1     .07       0  5058.2     .07       0
  6008.5    .045       0
Bank Sta=5042.1,5058.2
XS Rating Curve= 0 ,0
Exp/Cntr=0.3,0.1

Type RM Length L Ch R = 1 ,14791   ,264,264,264
BEGIN DESCRIPTION:
Mapping XS a3e27479
END DESCRIPTION:
XS GIS Cut Line= 3
      1491600.22      6813822.14      1492919.67      6814075.61
      1493916.15      6814228.38
#Sta/Elev= 30
  3672.3 2005.66  3892.5 2004.96  3944.5 2003.18  3991.3 1997.14  4064.1 1994.52
  4583.4 1989.38  4603.8 1985.49  4635.2 1983.67  4797.3 1979.89  4848.2 1980.14
  4909.3 1986.94  4960.2 1987.17  4980.6 1980.87  4995.9 1979.72  4996.4 1979.22
  5012.1 1979.72  5034.3 1980.16  5112.3  1985.7  5230.3 1986.72  5699.1 1991.68
  5729.5 1995.75  5769.9 1997.56  5830.6 2016.82  5850.8 2019.56  5856.2 2019.55
  5861.3 2014.88  5881.2 2016.59  5911.5 2014.47  5962.1 2021.39    6024 2021.75
#Mann= 5 ,-1 , 0
  3672.3     .07       0  4995.9     .07       0  5012.1     .07       0
  5034.3     .16       0  5230.3     .07       0
#XS Ineff= 2 , 0
       0    4947    1991               0
Permanent Ineff=
       F       F
Bank Sta=4995.9,5012.1
XS Rating Curve= 0 ,0
Exp/Cntr=0.3,0.1

Type RM Length L Ch R = 1 ,14527   ,374,374,374
BEGIN DESCRIPTION:
NUBIA CREEK TRIBUTARY 1 24.0
END DESCRIPTION:
XS GIS Cut Line= 3
      1491673.16      6813954.09        1492705.        6814238.
      1493804.98        6814438.
#Sta/Elev= 30
  3925.9  2004.9  4093.8 2003.91  4135.2 2000.32    4411  1993.8  4558.9 1992.32
  4684.9 1993.83  4712.1 1992.02  4871.6 1989.64  4973.7 1985.47  4996.1 1978.91
  4998.1 1976.31  4998.6 1975.81  5014.4 1976.31  5087.6 1983.67  5219.7 1984.63
  5416.6 1982.43  5450.1 1985.03  5477.4 1984.88  5646.6 1984.92  5922.3 1992.02
  5951.5 1995.87  5975.6 2001.54  6012.5 2004.02  6022.6 2006.18    6029 2010.41
    6043 2015.43  6053.1 2017.25  6082.4 2018.55  6093.8  2022.8  6114.1 2024.07
#Mann= 5 ,-1 , 0
  3925.9     .07       0  4998.1     .07       0  5014.4     .07       0
  5450.1     .16       0  5477.4     .07       0
Bank Sta=4998.1,5014.4
XS Rating Curve= 0 ,0
Exp/Cntr=0.3,0.1

Type RM Length L Ch R = 1 ,14153   ,748,748,748
BEGIN DESCRIPTION:
NUBIA CREEK TRIBUTARY 1 23.0
END DESCRIPTION:
XS GIS Cut Line= 3
      1492180.11      6814679.78      1492763.14      6814594.06
      1493605.02        6814688.
#Sta/Elev= 30
  4410.7 2001.29  4435.9 2000.86  4459.2 2001.85  4486.4  2000.1  4648.1 1995.54
  4733.2 1991.74  4767.8 1988.84  4819.9 1986.07  4906.7 1983.81  4940.9 1983.25
  4951.3 1982.76  4981.7 1978.19  5023.9 1975.25  5024.4 1974.75  5040.2 1975.25
  5062.2 1981.25  5072.3 1981.58  5132.7  1981.4  5142.7 1980.53  5174.4 1981.62
  5262.1 1981.68  5470.1 1983.66  5626.2 1986.46  5706.2  1993.2  5756.5 1993.06
  5806.9 2000.04    5827 2007.25    5837 2012.83  5844.6 2015.85  5847.1 2015.85
#Mann= 8 ,-1 , 0
  4410.7     .07       0  4767.8     .16       0  4906.7     .07       0
  4940.9     .16       0  5023.9     .07       0  5040.2     .16       0
  5262.1     .16       0  5470.1     .07       0
Bank Sta=5023.9,5040.2
XS Rating Curve= 0 ,0
Exp/Cntr=0.3,0.1

Type RM Length L Ch R = 1 ,13405   ,267,267,267
BEGIN DESCRIPTION:
NUBIA CREEK TRIBUTARY 1 22.0
END DESCRIPTION:
XS GIS Cut Line= 3
      1492232.17      6815131.17      1492795.17      6815175.16
      1493604.98      6814838.01
#Sta/Elev= 30
  4724.6 2005.26  4857.8 2008.31  4867.9 2005.65  4874.7 1999.88  4879.7 1998.43
    4898 1987.04    4908    1983    4928 1978.79  4995.9 1970.79  4996.4 1970.29
  5012.3 1970.79  5028.3 1971.81  5068.5 1977.96  5193.5 1978.16  5260.7 1979.74
  5354.1 1981.89  5516.6 1982.98  5817.2 1992.21  5925.7 1995.43  5944.9 1995.86
  5974.2 1992.91    5998  1992.4  6090.7 1994.13  6104.2    1997  6122.6  2003.7
  6128.1 2001.86  6151.9 2013.89  6157.3 2012.18  6163.8 2015.67  6166.5 2015.67
#Mann= 7 ,-1 , 0
  4724.6     .07       0  4995.9     .07       0  5012.3     .07       0
  5193.5     .16       0  5260.7     .07       0  5817.2    .035       0
  5925.7     .07       0
Bank Sta=4995.9,5012.3
XS Rating Curve= 0 ,0
Exp/Cntr=0.3,0.1

Type RM Length L Ch R = 1 ,13138   ,442,442,442
BEGIN DESCRIPTION:
NUBIA CREEK TRIBUTARY 1 21.0
END DESCRIPTION:
XS GIS Cut Line= 3
      1492194.01      6815256.19        1492405.        6815388.
      1493805.04      6815231.87
#Sta/Elev= 30
  4751.7 2004.49  4892.6 2005.31  4898.5 2004.46  4906.2 2001.14  4913.8 1996.17
  4919.7  1994.6  4950.4 1978.82  4971.6 1972.89  4992.8    1972  5002.3  1969.8
  5002.8  1969.3  5018.7  1969.8  5045.7 1970.82    5091 1976.79    5159 1976.43
  5231.9 1974.57  5274.8 1976.27  5483.5 1982.46  5781.6 1986.19  5874.3 1987.41
  5974.2  1990.5    6040 1995.77    6057 2000.44  6067.1 2000.75  6087.2 2006.37
  6097.2  2007.3  6167.7 2007.76  6220.8 2005.81    6366  2009.1  6409.2 2009.33
#Mann= 9 ,-1 , 0
  4751.7     .07       0  5002.3     .07       0  5018.7     .07       0
    5159     .16       0  5274.8     .07       0  5781.6    .035       0
  5874.3     .07       0  5974.2    .035       0    6366     .07       0
Bank Sta=5002.3,5018.7
XS Rating Curve= 0 ,0
Exp/Cntr=0.3,0.1

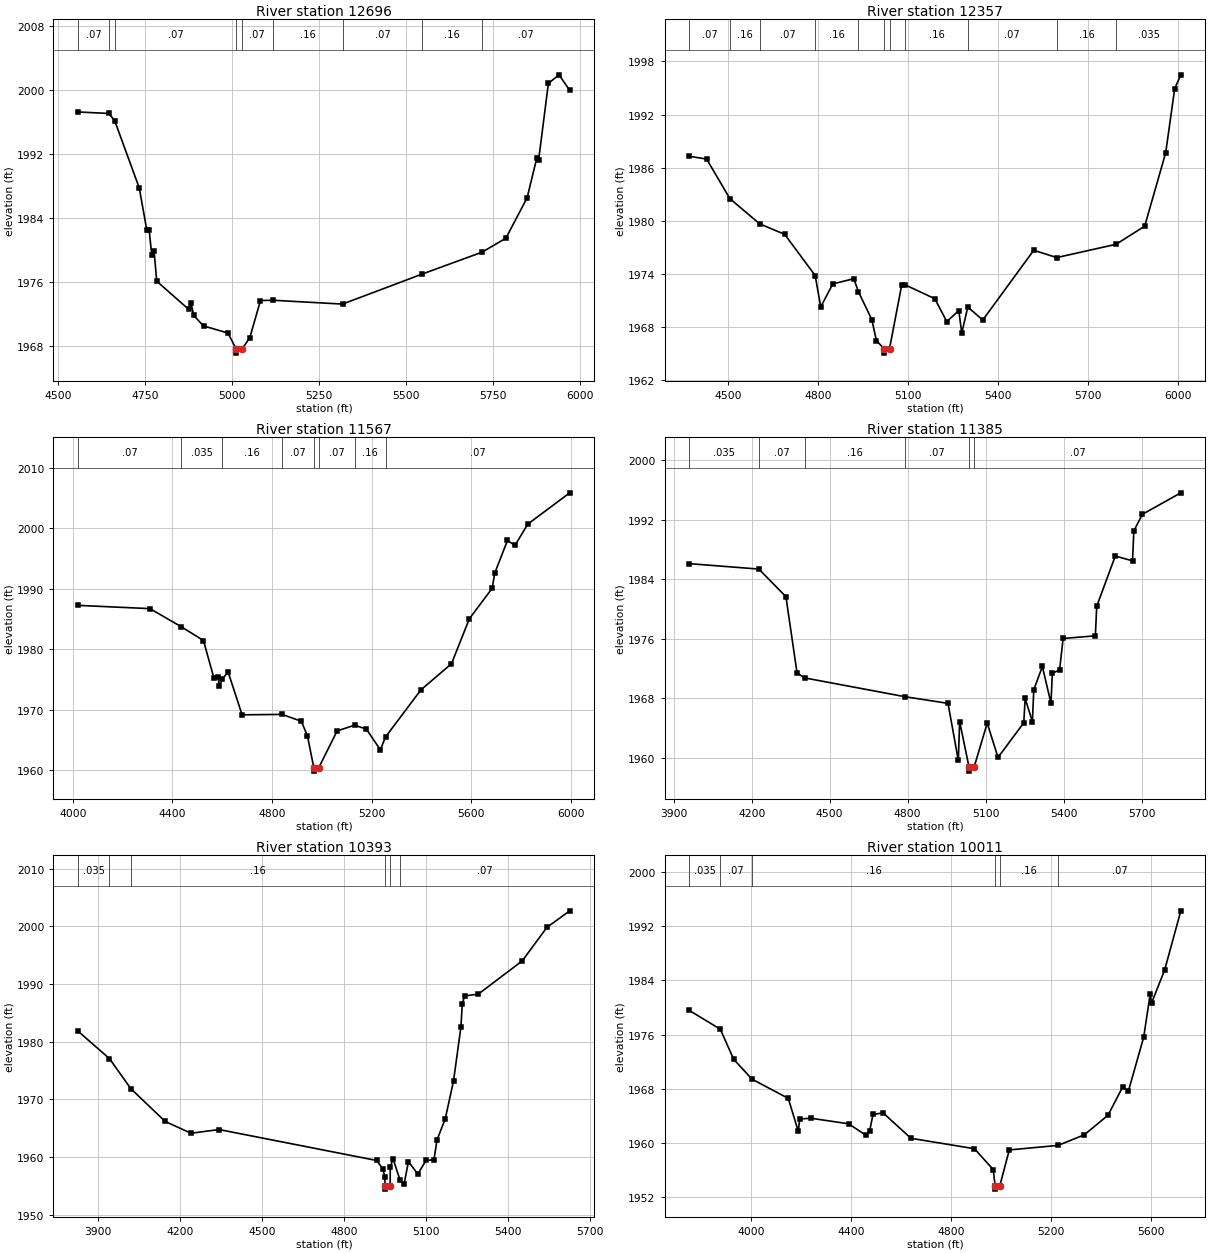
Type RM Length L Ch R = 1 ,12696   ,339,339,339
BEGIN DESCRIPTION:
NUBIA CREEK TRIBUTARY 1 20.0
END DESCRIPTION:
XS GIS Cut Line= 3
      1492173.79      6815500.06      1492507.16      6815795.22
      1493455.04      6815593.84
#Sta/Elev= 30
  4557.5 1997.26  4646.4 1997.07    4663 1996.17  4733.6 1987.77  4755.4  1982.5
  4762.1 1982.56  4769.6 1979.33  4776.3 1979.88  4783.9 1976.11  4875.9 1972.59
  4882.5 1973.41  4890.1 1971.84  4918.5 1970.52  4988.8 1969.63  5012.7 1967.62
  5013.2 1967.12  5029.2 1967.62  5051.7 1969.06  5082.3 1973.69  5116.9 1973.73
  5318.4 1973.25  5547.9 1977.01  5719.8 1979.74  5788.1 1981.48  5849.1 1986.52
  5877.1 1991.51  5882.2 1991.22  5910.4 2000.84  5941.1  2001.9  5971.8 1999.95
#Mann= 9 ,-1 , 0
  4557.5     .07       0  4646.4     .16       0    4663     .07       0
  5012.7     .07       0  5029.2     .07       0  5116.9     .16       0
  5318.4     .07       0  5547.9     .16       0  5719.8     .07       0
Bank Sta=5012.7,5029.2
XS Rating Curve= 0 ,0
Exp/Cntr=0.3,0.1

Type RM Length L Ch R = 1 ,12357   ,790,790,790
BEGIN DESCRIPTION:
NUBIA CREEK TRIBUTARY 1 19.0
END DESCRIPTION:
XS GIS Cut Line= 3
      1491826.65      6816149.39      1492454.98      6816112.76
       1493465.5      6816132.03
#Sta/Elev= 30
  4370.6 1987.29  4429.1 1986.97  4506.8 1982.49  4606.1 1979.65  4689.5 1978.46
  4791.2 1973.81  4809.7 1970.26  4849.8 1972.86  4919.9 1973.45  4935.4 1971.98
    4980 1968.83  4995.5 1966.45  5020.9 1965.54  5021.4 1965.04  5039.1 1965.54
    5080 1972.78  5092.3 1972.74  5190.1 1971.19  5230.1 1968.61  5270.1 1969.84
  5280.1 1967.31  5300.2 1970.25  5350.1 1968.78  5520.1 1976.66    5597 1975.84
  5794.9 1977.34  5890.2 1979.39  5960.2 1987.68  5990.2 1994.92  6010.7 1996.49
#Mann= 11 ,-1 , 0
  4370.6     .07       0  4506.8     .16       0  4606.1     .07       0
  4791.2     .16       0  4935.4     .07       0  5020.9     .07       0
  5039.1     .07       0  5092.3     .16       0  5300.2     .07       0
    5597     .16       0  5794.9    .035       0
Bank Sta=5020.9,5039.1
XS Rating Curve= 0 ,0
Exp/Cntr=0.3,0.1

Type RM Length L Ch R = 1 ,11567   ,182,182,182
BEGIN DESCRIPTION:
NUBIA CREEK TRIBUTARY 1 18.0
END DESCRIPTION:
XS GIS Cut Line= 3
      1491707.83      6816520.74       1492654.8      6816767.94
      1493630.41       6816962.9
#Sta/Elev= 30
  4021.3 1987.24  4310.1  1986.7  4434.4 1983.74  4524.8 1981.43  4566.1 1975.31
  4583.1 1975.45  4588.2 1973.89  4600.4 1975.01  4623.5 1976.27  4679.8 1969.14
  4840.3 1969.21  4917.5 1968.08  4942.1 1965.67    4968 1960.33  4968.5 1959.83
  4986.7 1960.33  5061.4 1966.48  5131.5 1967.43  5178.8 1966.77  5234.9 1963.35
  5255.6 1965.49  5397.9 1973.28  5520.3 1977.59    5592 1985.03  5683.5 1990.06
    5694 1992.58    5745 1997.98  5775.2 1997.15  5826.2 2000.67  5994.9 2005.85
#Mann= 8 ,-1 , 0
  4021.3     .07       0  4434.4    .035       0  4600.4     .16       0
  4840.3     .07       0    4968     .07       0  4986.7     .07       0
  5131.5     .16       0  5255.6     .07       0
Bank Sta=4968,4986.7
XS Rating Curve= 0 ,0
Exp/Cntr=0.3,0.1

Type RM Length L Ch R = 1 ,11385   ,992,992,992
BEGIN DESCRIPTION:
Mapping XS 81083743
END DESCRIPTION:
XS GIS Cut Line= 4
      1491683.06      6816710.69      1492615.33      6816924.22
      1492813.25      6816945.06      1493518.97      6817155.99
#Sta/Elev= 30
  3959.1 1986.08  4227.6 1985.35  4331.7 1981.64  4374.6 1971.37    4404 1970.72
  4790.3 1968.19  4955.4  1967.3    4995 1959.62    5000 1964.86  5036.5 1958.69
    5037 1958.19  5055.3 1958.69  5106.2 1964.64  5147.7 1960.03  5246.9 1964.69
  5252.1 1967.96    5280 1964.83  5285.3 1969.13  5318.4 1972.26  5351.5 1967.32
  5356.7 1971.34  5384.6  1971.8  5398.2 1976.02  5522.3 1976.38  5527.5 1980.35
  5598.9  1987.1  5665.2 1986.46  5670.4  1990.5  5703.5 1992.72  5851.1  1995.6
#Mann= 6 ,-1 , 0
  3959.1    .035       0  4227.6     .07       0    4404     .16       0
  4790.3     .07       0  5036.5     .07       0  5055.3     .07       0
Bank Sta=5036.5,5055.3
XS Rating Curve= 0 ,0
Exp/Cntr=0.3,0.1

Type RM Length L Ch R = 1 ,10393   ,382,382,382
BEGIN DESCRIPTION:
Mapping XS 16ab7e5c
END DESCRIPTION:
XS GIS Cut Line= 3
      1491761.12      6817150.76      1492703.87       6817658.6
      1493427.82      6817734.12
#Sta/Elev= 30
  3827.9 1981.83  3942.9 1977.07  4021.3 1971.85  4146.8 1966.17  4241.2 1964.13
  4343.9 1964.77    4920 1959.41  4943.1 1957.96  4950.1 1956.57  4950.8 1954.94
  4951.3 1954.44  4969.6 1954.94  4970.2 1958.33  4980.3 1959.68  5005.6 1956.05
  5020.5 1955.28  5036.6 1959.21  5070.8 1957.06  5100.9 1959.41    5130 1959.54
  5141.2 1962.99  5171.3 1966.64  5201.5  1973.2  5228.5 1982.53  5233.5 1986.51
  5241.7 1987.94    5292 1988.24  5452.8 1994.01  5543.3 1999.83  5626.6 2002.69
#Mann= 6 ,-1 , 0
  3827.9    .035       0  3942.9     .07       0  4021.3     .16       0
  4950.8     .07       0  4969.6     .16       0  5005.6     .07       0
Bank Sta=4950.8,4969.6
XS Rating Curve= 0 ,0
Exp/Cntr=0.3,0.1

Type RM Length L Ch R = 1 ,10011   ,932,932,932
BEGIN DESCRIPTION:
Mapping XS c1aea7a2
END DESCRIPTION:
XS GIS Cut Line= 4
      1491697.77       6817288.8      1492604.05      6817702.87
       1492822.8      6818267.97      1493181.04      6818335.47
#Sta/Elev= 30
  3751.1 1979.58    3876 1976.78  3929.6 1972.32  4003.3 1969.38  4147.8 1966.55
  4187.8 1961.69  4193.8 1963.51  4239.9  1963.6    4389 1962.79  4458.1  1961.1
  4473.7 1961.78  4486.6 1964.17  4527.2  1964.4  4638.6 1960.64  4892.4  1959.1
  4967.5 1956.02  4975.2 1953.62  4975.7 1953.12    4994 1953.62  5031.8 1958.92
  5226.9 1959.59    5332 1961.16  5426.9 1964.06  5485.8 1968.27  5508.3 1967.63
  5569.4 1975.59  5595.7 1982.05  5600.8 1980.64  5653.3 1985.55    5718  1994.3
#Mann= 6 ,-1 , 0
  3751.1    .035       0    3876     .07       0  4003.3     .16       0
  4975.2     .07       0    4994     .16       0  5226.9     .07       0
Bank Sta=4975.2,4994
XS Rating Curve= 0 ,0
Exp/Cntr=0.3,0.1

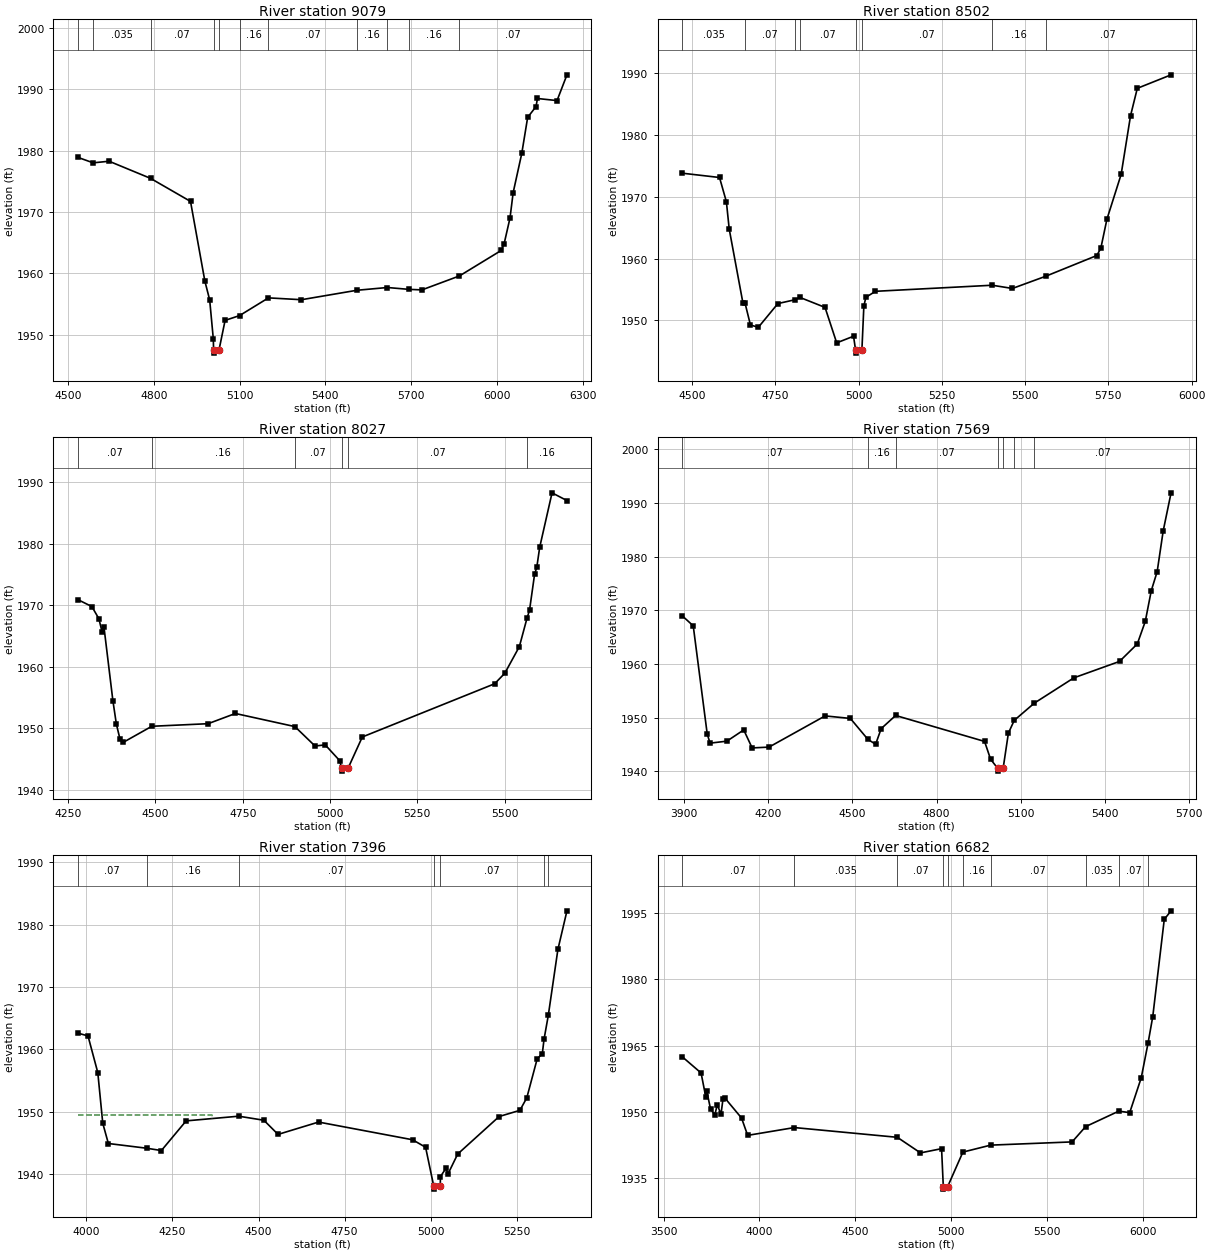
Type RM Length L Ch R = 1 ,9079    ,577,577,577
BEGIN DESCRIPTION:
NUBIA CREEK TRIBUTARY 1 14.0
END DESCRIPTION:
XS GIS Cut Line= 3
      1491491.15      6817934.62      1491906.97      6818143.65
      1493118.82      6818426.83
#Sta/Elev= 30
  4534.6 1978.92  4588.1 1978.03  4643.8 1978.29  4788.6  1975.5  4928.4 1971.74
  4978.6 1958.74  4995.4 1955.68  5008.2 1949.28    5009  1947.5  5009.5    1947
    5028  1947.5  5049.3 1952.34  5099.9 1953.12  5200.9 1956.01  5316.3 1955.71
  5510.2 1957.25  5616.7  1957.7  5691.3  1957.4  5737.4 1957.31  5868.7 1959.59
  6014.6 1963.74  6024.9 1964.85  6045.5 1969.06  6056.4 1973.17  6086.5 1979.56
  6107.1 1985.44  6136.3  1987.2  6141.4 1988.52  6209.8 1988.18  6244.5 1992.38
#Mann= 11 ,-1 , 0
  4534.6     .07       0  4588.1    .035       0  4788.6     .07       0
    5009     .07       0    5028     .07       0  5099.9     .16       0
  5200.9     .07       0  5510.2     .16       0  5616.7     .07       0
  5691.3     .16       0  5868.7     .07       0
Bank Sta=5009,5028
XS Rating Curve= 0 ,0
Exp/Cntr=0.3,0.1

Type RM Length L Ch R = 1 ,8502    ,475,475,475
BEGIN DESCRIPTION:
NUBIA CREEK TRIBUTARY 1 13.0
END DESCRIPTION:
XS GIS Cut Line= 4
      1491645.71      6818798.36      1491998.14      6818709.81
       1492222.1      6818576.13      1493055.02        6818438.
#Sta/Elev= 30
  4469.7 1973.79  4582.4 1973.09    4603 1969.17  4611.5 1964.76  4652.6 1952.83
  4658.7 1952.86  4675.2 1949.26  4698.9 1948.88  4757.7 1952.72  4809.4 1953.34
  4823.4 1953.72  4899.2  1952.1  4934.2 1946.37  4984.8 1947.44  4990.9 1945.21
  4991.4 1944.71  5009.9 1945.21  5015.8 1952.33  5021.8 1953.73  5050.7  1954.7
  5401.1 1955.68  5461.8 1955.16  5561.2 1957.12  5715.2 1960.48  5727.3 1961.67
  5745.6 1966.35  5788.3  1973.6  5816.5 1983.08  5836.8  1987.5  5938.2 1989.68
#Mann= 8 ,-1 , 0
  4469.7    .035       0  4658.7     .07       0  4809.4     .16       0
  4823.4     .07       0  4990.9     .07       0  5009.9     .07       0
  5401.1     .16       0  5561.2     .07       0
Bank Sta=4990.9,5009.9
XS Rating Curve= 0 ,0
Exp/Cntr=0.3,0.1

Type RM Length L Ch R = 1 ,8027    ,458,458,458
BEGIN DESCRIPTION:
NUBIA CREEK TRIBUTARY 1 12.0
END DESCRIPTION:
XS GIS Cut Line= 3
      1491754.98        6818938.      1492415.16      6818982.73
        1493005.        6818538.
#Sta/Elev= 30
  4277.9 1970.88    4318 1969.75  4338.1 1967.77  4347.5 1965.55  4352.5 1966.48
  4378.1 1954.48  4388.2 1950.62  4398.2 1948.28  4408.2 1947.69  4489.6 1950.29
  4650.8 1950.71  4728.9 1952.37  4899.3 1950.24    4957 1947.08  4986.1 1947.27
  5027.8 1944.69  5032.8  1943.5  5033.3    1943  5051.8  1943.5  5092.3 1948.55
  5471.2  1957.2  5500.3 1958.91    5542 1963.24  5564.1  1967.9  5571.1 1969.14
  5585.7 1975.04  5591.9 1976.12  5600.2 1979.38  5635.6 1988.24  5678.3 1986.98
#Mann= 6 ,-1 , 0
  4277.9     .07       0  4489.6     .16       0  4899.3     .07       0
  5032.8     .07       0  5051.8     .07       0  5564.1     .16       0
Bank Sta=5032.8,5051.8
XS Rating Curve= 0 ,0
Exp/Cntr=0.3,0.1

Type RM Length L Ch R = 1 ,7569    ,173,173,173
BEGIN DESCRIPTION:
NUBIA CREEK TRIBUTARY 1 11.0
END DESCRIPTION:
XS GIS Cut Line= 3
      1491704.95        6819288.      1492717.24        6819334.
      1493254.99      6818838.01
#Sta/Elev= 30
  3891.9 1969.01    3932  1967.1    3982 1946.93  3992.1 1945.26  4052.1 1945.63
  4112.2 1947.72  4142.2 1944.37  4202.3 1944.52  4402.5 1950.33  4492.6 1949.86
  4555.2 1945.96  4582.7 1945.05  4602.7 1947.97  4654.1 1950.41  4971.4 1945.58
  4992.9 1942.26  5018.6 1940.55  5019.1 1940.05  5037.6 1940.55  5056.4 1947.13
  5077.3  1949.5  5149.2 1952.72  5290.1 1957.42  5452.8 1960.47  5516.3 1963.73
  5544.7 1967.91  5566.2 1973.65  5587.2 1977.19  5608.7 1984.78  5636.8 1991.86
#Mann= 7 ,-1 , 0
  3891.9     .07       0  4555.2     .16       0  4654.1     .07       0
  5018.6     .07       0  5037.6     .07       0  5077.3    .035       0
  5149.2     .07       0
#XS Ineff= 2 , 0
       0  4402.5 1950.33               0
Permanent Ineff=
       F       F
Bank Sta=5018.6,5037.6
XS Rating Curve= 0 ,0
Exp/Cntr=0.3,0.1

Type RM Length L Ch R = 1 ,7396    ,714,714,714
BEGIN DESCRIPTION:
Mapping XS 08619e49
END DESCRIPTION:
XS GIS Cut Line= 3
       1491878.7      6819638.97      1492878.68      6819409.81
      1493271.25      6819438.15
#Sta/Elev= 30
  3975.7  1962.6  4005.1 1962.15  4033.5 1956.27    4048 1948.13  4064.2 1944.89
  4175.6 1944.13  4218.1 1943.76  4289.9 1948.52  4442.5 1949.27  4515.6 1948.62
  4556.7 1946.35  4674.3 1948.33  4947.1 1945.49  4984.9 1944.29  5008.5 1938.07
    5009 1937.57  5027.5 1938.07    5028 1939.59  5044.5 1940.94  5049.5 1939.96
  5078.1  1943.2  5198.4 1949.22  5258.6 1950.21  5278.6 1952.21  5308.7 1958.45
  5323.7 1959.31  5328.7 1961.62    5341 1965.43  5368.9 1976.02  5395.2 1982.22
#Mann= 7 ,-1 , 0
  3975.7     .07       0  4175.6     .16       0  4442.5     .07       0
  5008.5     .07       0  5027.5     .07       0  5328.7     .16       0
    5341     .07       0
#XS Ineff= 2 , 0
       0  4363.7  1949.4               0
Permanent Ineff=
       F       F
Bank Sta=5008.5,5027.5
XS Rating Curve= 0 ,0
Exp/Cntr=0.3,0.1

Type RM Length L Ch R = 1 ,6682    ,746,746,746
BEGIN DESCRIPTION:
NUBIA CREEK TRIBUTARY 1 9.0
END DESCRIPTION:
XS GIS Cut Line= 4
      1491855.01        6819688.      1492611.32      6819979.25
      1493208.55      6820003.56      1494350.46      6820072.97
#Sta/Elev= 30
    3596 1962.51  3695.6 1958.79  3720.2 1953.35  3725.6 1954.64  3744.8 1950.65
  3767.4 1949.31  3780.2 1951.59  3799.5 1949.44  3810.3 1952.98    3821 1953.05
  3906.8 1948.58  3938.7 1944.65  4182.5 1946.42  4719.8 1944.21  4840.5 1940.68
  4950.6 1941.64  4959.7 1932.97  4960.2 1932.47  4981.6 1932.97  5061.8 1940.86
  5206.8 1942.44  5631.8 1943.17  5702.2 1946.63  5875.4 1950.14  5932.3  1949.8
  5992.4 1957.68    6028 1965.54  6052.6 1971.55  6112.7  1993.6  6148.2 1995.53
#Mann= 10 ,-1 , 0
    3596     .07       0  4182.5    .035       0  4719.8     .07       0
  4959.7     .07       0  4981.6     .07       0  5061.8     .16       0
  5206.8     .07       0  5702.2    .035       0  5875.4     .07       0
    6028     .16       0
Bank Sta=4959.7,4981.6
XS Rating Curve= 0 ,0
Exp/Cntr=0.3,0.1

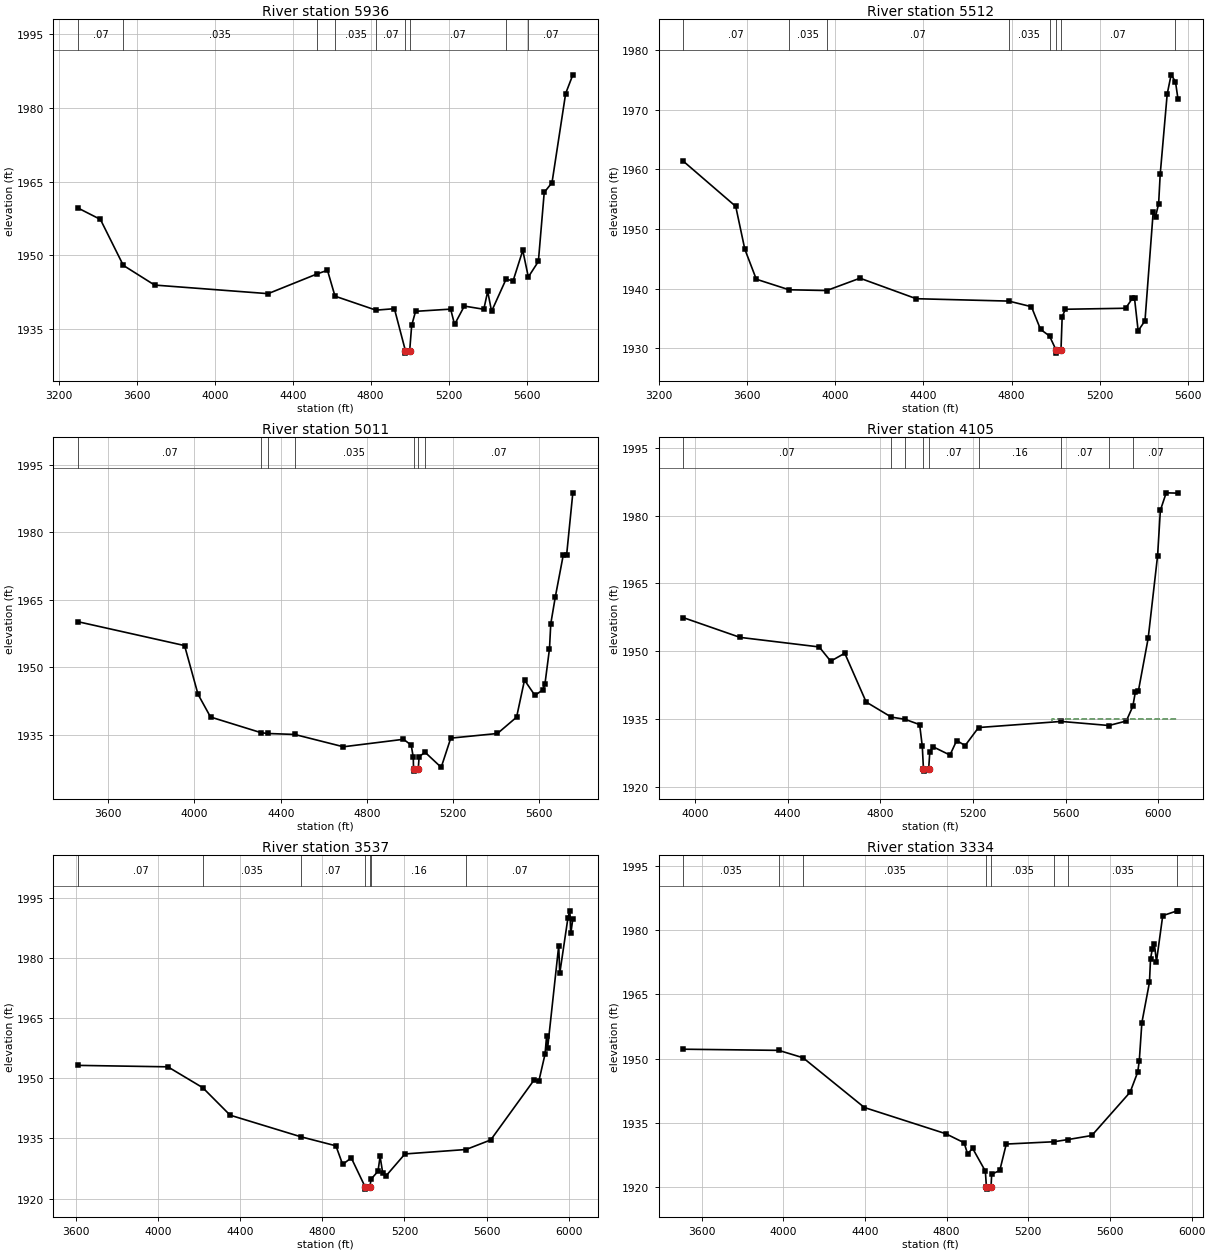
Type RM Length L Ch R = 1 ,5936    ,424,424,424
BEGIN DESCRIPTION:
Mapping XS bb50b576
END DESCRIPTION:
XS GIS Cut Line= 3
      1491810.41      6819857.99      1493304.48      6820672.78
      1494141.86      6820646.24
#Sta/Elev= 30
  3298.2 1959.62  3412.4 1957.32    3530 1947.96  3690.7 1943.95  4273.4  1942.2
  4526.2 1946.24  4578.1 1946.96  4616.8 1941.69  4827.3 1938.84  4921.7 1939.14
  4978.2 1930.59  4978.7 1930.09  5000.2 1930.59  5010.5 1935.75  5030.5  1938.6
  5210.6 1939.05  5230.6 1935.92  5280.7 1939.67  5380.7 1939.02  5400.7 1942.66
  5420.7 1938.61  5495.4 1945.18  5530.8 1944.77  5580.8 1951.01  5609.3 1945.59
  5660.9 1948.76  5690.9 1962.81  5730.9 1964.81  5800.9 1982.95  5837.8 1986.76
#Mann= 9 ,-1 , 0
  3298.2     .07       0    3530    .035       0  4526.2     .07       0
  4616.8    .035       0  4827.3     .07       0  4978.2     .07       0
  5000.2     .07       0  5495.4    .035       0  5609.3     .07       0
Bank Sta=4978.2,5000.2
XS Rating Curve= 0 ,0
Exp/Cntr=0.3,0.1

Type RM Length L Ch R = 1 ,5512    ,501,501,501
BEGIN DESCRIPTION:
Mapping XS 373b5b6c
END DESCRIPTION:
XS GIS Cut Line= 3
      1491608.97      6820368.39      1493156.65      6821048.69
      1493680.92      6821232.63
#Sta/Elev= 30
  3309.4 1961.38  3547.7 1953.79  3588.9 1946.62  3641.1 1941.57  3789.8  1939.8
  3960.8 1939.67    4112 1941.74  4367.3  1938.3  4787.7  1937.9  4890.4 1936.96
  4931.7 1933.16  4972.6 1932.04  5002.6 1929.67  5003.1 1929.17  5024.6 1929.67
    5030 1935.27  5044.6 1936.53  5318.3  1936.7  5349.3 1938.39  5358.6 1938.34
    5375 1932.92    5406 1934.59  5443.3 1952.85  5453.9 1952.06    5468 1954.23
  5475.1 1959.15  5506.9 1972.64  5524.7 1975.86  5544.4 1974.73  5555.6 1971.87
#Mann= 8 ,-1 , 0
  3309.4     .07       0  3789.8    .035       0  3960.8     .07       0
  4787.7    .035       0  4972.6     .07       0  5002.6     .07       0
  5024.6     .07       0  5544.4    .035       0
Bank Sta=5002.6,5024.6
XS Rating Curve= 0 ,0
Exp/Cntr=0.3,0.1

Type RM Length L Ch R = 1 ,5011    ,906,906,906
BEGIN DESCRIPTION:
NUBIA CREEK TRIBUTARY 1 7.0
END DESCRIPTION:
XS GIS Cut Line= 3
      1491429.39      6821028.52        1492905.        6821438.
      1493555.01      6821838.01
#Sta/Elev= 30
  3460.5 1960.15  3954.1 1954.86  4016.4 1944.05  4074.5 1938.99  4308.9 1935.51
  4339.5 1935.33  4464.4 1935.12  4690.9 1932.38  4969.6 1934.04  5005.4 1932.75
    5015 1930.02  5016.1 1927.47  5016.6 1926.97  5038.1 1927.47  5042.1 1930.18
  5069.6 1931.16  5144.5 1927.81  5188.9  1934.3  5405.4 1935.33  5494.2 1938.96
  5530.9 1947.19  5579.3 1943.79    5616 1945.03  5625.6 1946.27  5646.8 1954.15
  5652.7 1959.69    5674 1965.71  5710.7 1974.97  5726.1  1974.9  5755.1 1988.79
#Mann= 7 ,-1 , 0
  3460.5     .07       0  4308.9    .035       0  4339.5     .07       0
  4464.4    .035       0  5016.1    .035       0  5038.1    .035       0
  5069.6     .07       0
Bank Sta=5016.1,5038.1
XS Rating Curve= 0 ,0
Exp/Cntr=0.3,0.1

Type RM Length L Ch R = 1 ,4105    ,568,568,568
BEGIN DESCRIPTION:
Mapping XS b36d4d37
END DESCRIPTION:
XS GIS Cut Line= 4
      1491385.27      6821300.21      1492244.69      6821620.53
      1492666.56      6821852.31      1493367.11      6822078.88
#Sta/Elev= 30
    3950 1957.46  4195.2 1953.09  4536.7 1950.98  4586.3 1947.83    4647 1949.59
  4739.4 1938.81  4847.8 1935.48  4906.9 1934.99  4970.2 1933.82  4981.7 1928.99
  4986.6 1924.04  4987.1 1923.54  5009.1 1924.04  5013.9 1927.66  5027.3 1928.94
  5101.1 1927.09    5130  1930.3  5166.5 1929.19  5224.4 1933.17  5580.9 1934.52
  5787.1 1933.62  5861.9 1934.61  5890.2 1937.86  5900.9 1940.96  5914.4 1941.31
  5956.5 1952.92    5997 1971.11    6009 1981.15  6034.2 1985.03  6084.8 1984.96
#Mann= 9 ,-1 , 0
    3950     .07       0  4847.8    .035       0  4906.9     .07       0
  4986.6     .07       0  5009.1     .07       0  5224.4     .16       0
  5580.9     .07       0  5787.1     .16       0  5890.2     .07       0
#XS Ineff= 2 , 0
       0                  5543.5       0  1935.1
Permanent Ineff=
       F       F
Bank Sta=4986.6,5009.1
XS Rating Curve= 0 ,0
Exp/Cntr=0.3,0.1

Type RM Length L Ch R = 1 ,3537    ,203,203,203
BEGIN DESCRIPTION:
Mapping XS 0a38c4de
END DESCRIPTION:
XS GIS Cut Line= 3
      1491106.64       6821849.7      1492445.21      6822175.22
      1493458.22      6822354.91
#Sta/Elev= 30
  3612.6 1953.25    4049 1952.89  4218.7 1947.68  4351.9 1940.82  4695.9 1935.43
  4866.5 1933.17  4899.3 1928.52  4941.1 1930.17  5009.2 1922.86  5009.7 1922.36
  5031.7 1922.86  5037.3 1924.83  5071.2 1926.82  5081.4 1930.53  5094.3 1926.36
  5111.8 1925.76  5202.3 1931.14  5499.6 1932.25  5619.6 1934.64  5832.1 1949.72
  5853.2 1949.23  5883.7 1956.03  5891.2  1960.5  5896.2  1957.5  5950.3 1983.11
  5955.3 1976.19  5995.4 1990.15  6004.3 1991.83  6009.4 1986.28    6019 1989.84
#Mann= 7 ,-1 , 0
  3612.6     .07       0  4218.7    .035       0  4695.9     .07       0
  5009.2     .07       0  5031.7     .07       0  5037.3     .16       0
  5499.6     .07       0
Bank Sta=5009.2,5031.7
XS Rating Curve= 0 ,0
Exp/Cntr=0.3,0.1

Type RM Length L Ch R = 1 ,3334    ,558,558,558
BEGIN DESCRIPTION:
Mapping XS e1f44ed1
END DESCRIPTION:
XS GIS Cut Line= 3
      1491021.49      6821972.35      1492461.61      6822381.21
      1493367.85      6822571.31
#Sta/Elev= 30
  3509.8 1952.21  3977.4 1951.94  4096.3 1950.22    4397 1938.59  4795.5 1932.47
  4885.6 1930.35  4902.4 1927.77  4927.2 1929.05  4989.6 1923.72  4994.8 1920.02
  4995.3 1919.52  5017.3 1920.02  5020.6    1923  5060.3 1923.89    5092 1930.05
  5325.9 1930.59  5394.1  1931.1    5511 1932.05  5698.7 1942.17  5735.8 1946.85
  5743.5 1949.48  5756.2 1958.41  5793.4 1967.83  5798.5 1973.25  5807.3 1975.65
  5817.5 1976.83  5827.7 1972.69  5858.4 1983.41  5929.2 1984.54  5932.8 1984.54
#Mann= 8 ,-1 , 0
  3509.8    .035       0  3977.4     .07       0  4096.3    .035       0
  4994.8    .035       0  5017.3    .035       0  5325.9     .07       0
  5394.1    .035       0  5929.2     .07       0
Bank Sta=4994.8,5017.3
XS Rating Curve= 0 ,0
Exp/Cntr=0.3,0.1