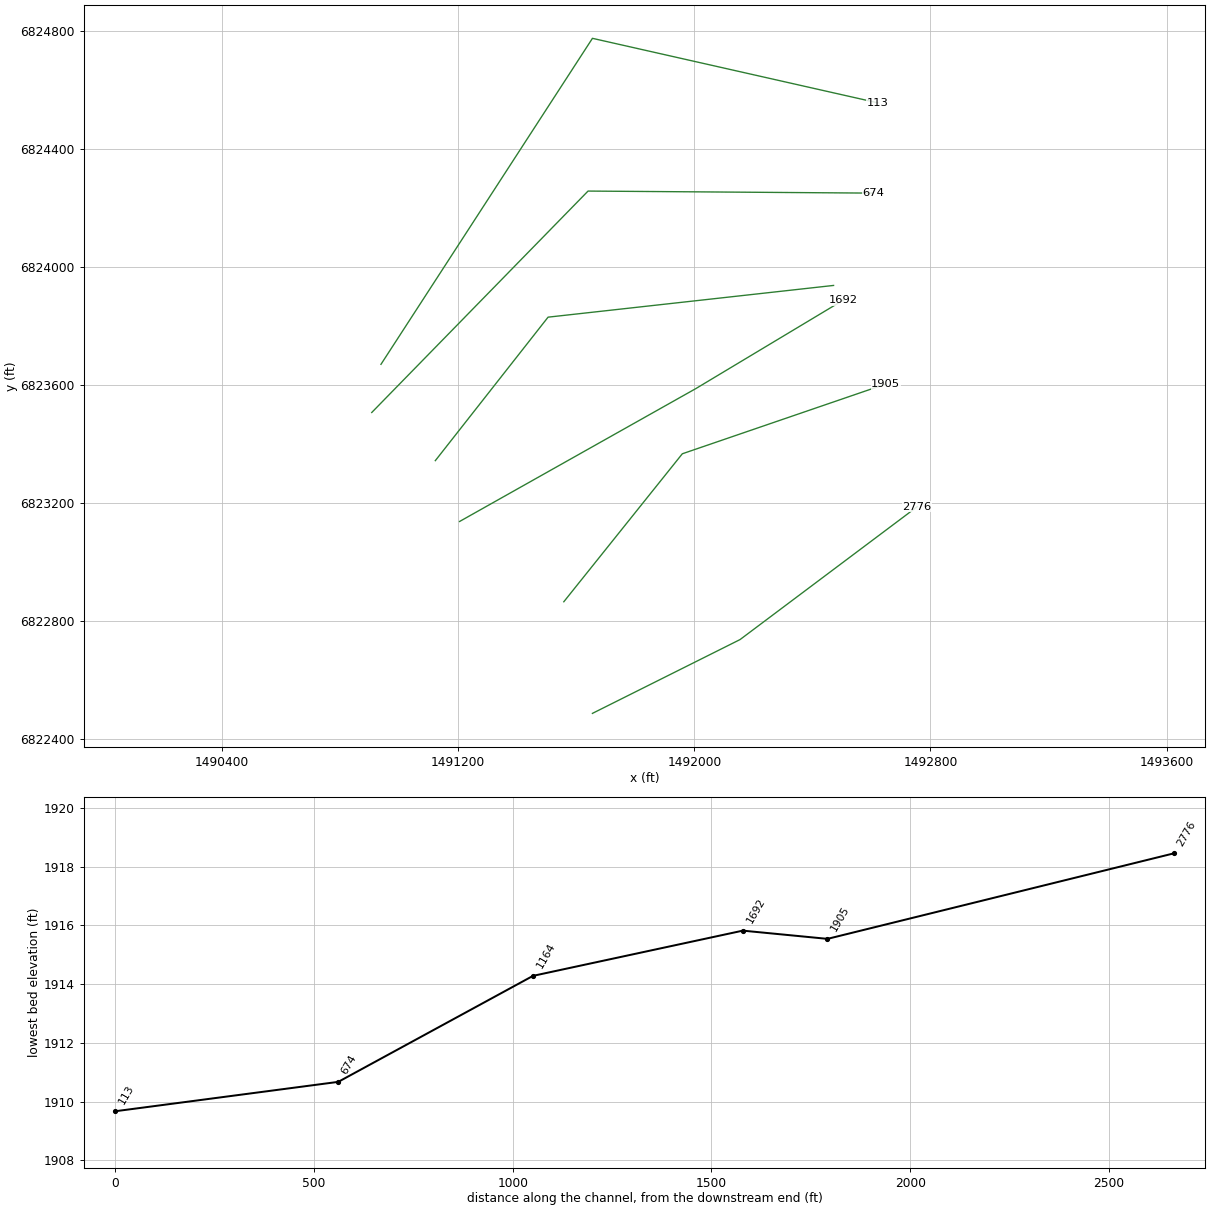
HEC-RAS study NUBIA CREEK TRIBUTARY 1.prj: NUBIA CREEK TRIBUTARY 1 Base Level Engineering

--- NUBIA CREEK TRIBUTARY 1.g01 (geometry) --- (continued)

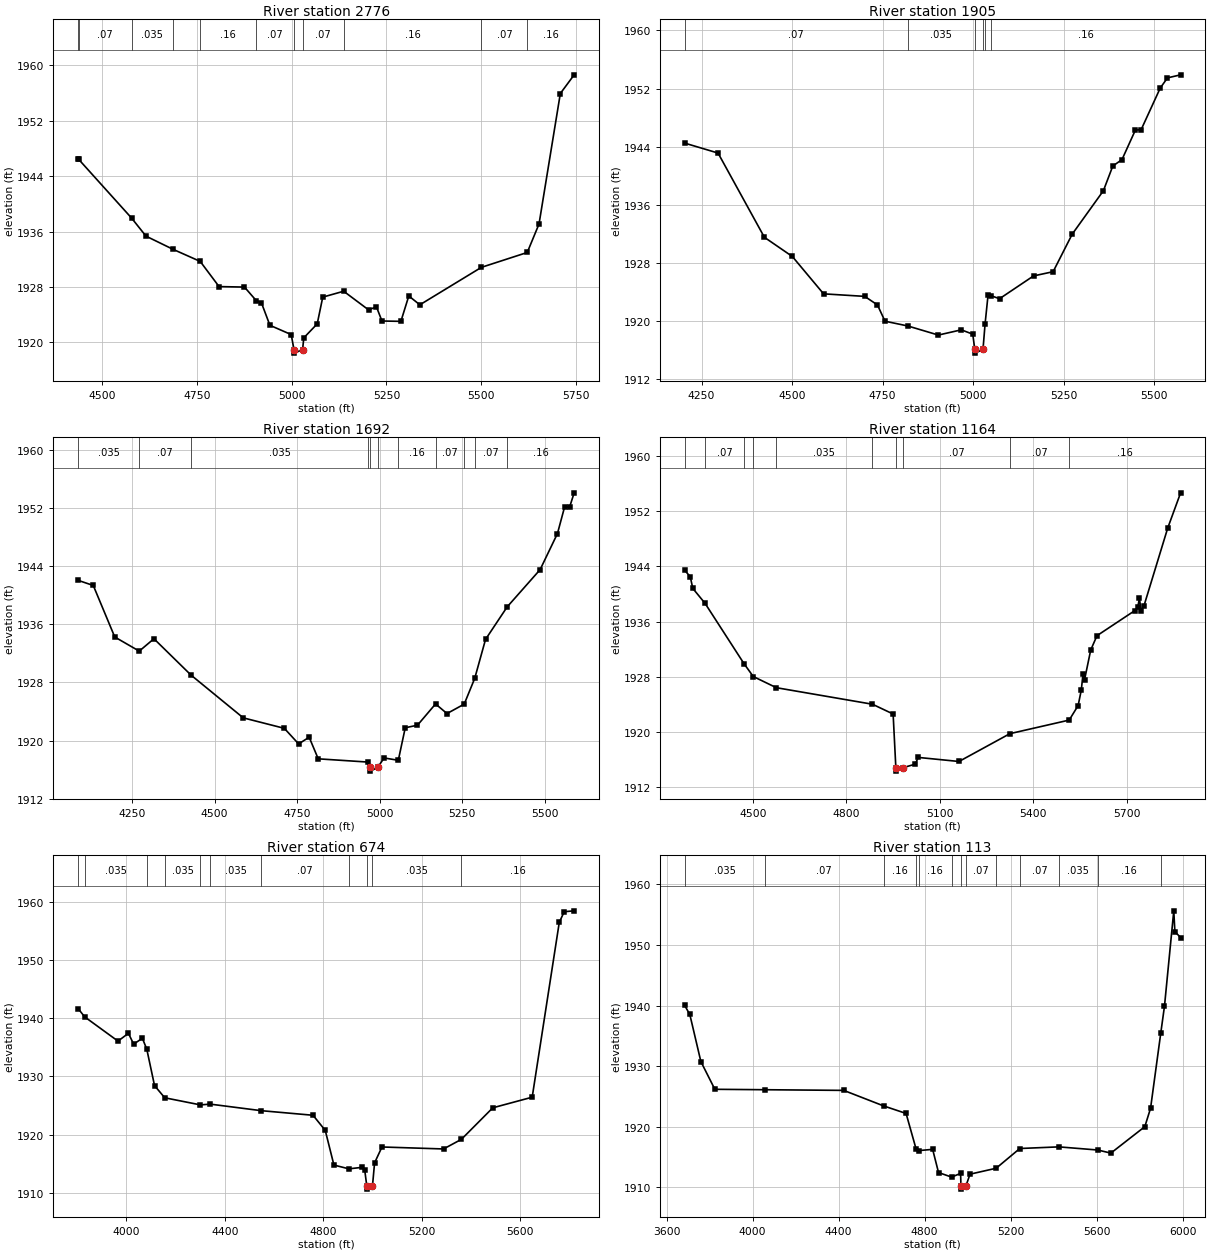
Type RM Length L Ch R = 1 ,2776    ,871,871,871
BEGIN DESCRIPTION:
NUBIA CREEK TRIBUTARY 1 4.0
END DESCRIPTION:
XS GIS Cut Line= 3
      1491654.96      6822487.98        1492155.        6822738.
      1492755.03      6823188.02
#Sta/Elev= 30
  4436.3 1946.43  4437.7 1946.43  4577.3 1937.95  4615.2 1935.35  4686.4 1933.45
  4758.3  1931.7  4808.1 1928.06  4875.2 1927.99  4906.5 1926.02  4919.9 1925.72
  4942.3 1922.47  4998.5 1921.13  5005.9 1918.95  5006.4 1918.45  5028.5 1918.95
  5031.8 1920.66  5067.2 1922.68  5081.8 1926.54    5137 1927.39  5202.7  1924.7
  5223.5 1925.14  5238.1 1923.09  5288.1 1923.04  5308.9 1926.71  5338.1 1925.43
  5500.5 1930.84  5621.6 1932.99  5652.7 1937.11  5708.9 1955.95  5745.4 1958.65
#Mann= 11 ,-1 , 0
  4436.3    .035       0  4437.7     .07       0  4577.3    .035       0
  4686.4     .07       0  4758.3     .16       0  4906.5     .07       0
  5005.9     .07       0  5028.5     .07       0    5137     .16       0
  5500.5     .07       0  5621.6     .16       0
Bank Sta=5005.9,5028.5
XS Rating Curve= 0 ,0
Exp/Cntr=0.3,0.1

Type RM Length L Ch R = 1 ,1905    ,213,213,213
BEGIN DESCRIPTION:
Mapping XS 50a61e78
END DESCRIPTION:
XS GIS Cut Line= 3
      1491557.98      6822866.04      1491959.44      6823367.32
      1492648.27      6823603.43
#Sta/Elev= 30
  4203.2 1944.48  4295.4 1943.11  4423.5  1931.5  4500.6 1928.86    4587 1923.71
  4700.7 1923.36  4735.9 1922.18  4756.7 1919.94  4819.9 1919.28  4904.2 1918.03
  4967.6 1918.75  4999.3 1918.15  5004.8 1916.04  5005.3 1915.54  5027.5 1916.04
  5033.3 1919.58  5041.6  1923.6    5049 1923.46  5073.3 1923.04  5167.2 1926.18
  5221.3 1926.76  5274.1 1931.94  5360.2 1937.92  5386.2 1941.32  5411.6 1942.21
  5448.7 1946.29  5464.4 1946.32  5517.3 1952.07  5537.3 1953.47  5573.6 1953.89
#Mann= 6 ,-1 , 0
  4203.2     .07       0  4819.9    .035       0  5004.8    .035       0
  5027.5    .035       0  5033.3     .07       0    5049     .16       0
Bank Sta=5004.8,5027.5
XS Rating Curve= 0 ,0
Exp/Cntr=0.3,0.1

Type RM Length L Ch R = 1 ,1692    ,528,528,528
BEGIN DESCRIPTION:
NUBIA CREEK TRIBUTARY 1 2.0
END DESCRIPTION:
XS GIS Cut Line= 3
      1491204.96      6823137.98        1492005.        6823588.
      1492504.98      6823887.99
#Sta/Elev= 30
  4087.4 1942.03    4133 1941.33    4198 1934.25  4272.1 1932.31  4316.6 1934.01
    4429 1929.01  4586.9 1923.14  4711.2  1921.7  4754.5 1919.56  4786.4 1920.48
  4813.8 1917.51  4965.8 1917.06    4971 1916.32  4971.5 1915.82  4993.7 1916.32
  5013.1 1917.63  5056.2 1917.31  5077.2 1921.78  5114.2 1922.13  5168.9 1925.05
  5203.6 1923.73  5255.7 1925.03  5287.5 1928.57  5320.2 1933.92  5385.7 1938.39
  5485.4 1943.51  5537.9 1948.47  5559.3 1952.09  5574.8 1952.12  5588.4 1954.06
#Mann= 11 ,-1 , 0
  4087.4    .035       0  4272.1     .07       0    4429    .035       0
  4965.8     .07       0    4971     .07       0  4993.7     .07       0
  5056.2     .16       0  5168.9     .07       0  5255.7     .16       0
  5287.5     .07       0  5385.7     .16       0
Bank Sta=4971,4993.7
XS Rating Curve= 0 ,0
Exp/Cntr=0.3,0.1

Type RM Length L Ch R = 1 ,1164    ,490,490,490
BEGIN DESCRIPTION:
Mapping XS 0c5f4098
END DESCRIPTION:
XS GIS Cut Line= 3
      1491122.75      6823344.01      1491504.67      6823830.08
      1492471.75      6823937.54
#Sta/Elev= 30
  4281.4 1943.44  4299.3  1942.5  4307.4 1940.81  4346.9 1938.63  4472.3 1929.84
  4501.6 1928.01  4575.7 1926.39  4883.9 1923.99  4950.2 1922.57  4958.9 1914.78
  4959.4 1914.28  4981.7 1914.78  5021.1 1915.29  5030.7 1916.27  5161.5 1915.68
  5324.9 1919.72  5515.1 1921.69  5543.8  1923.8  5553.9 1926.05  5559.4 1928.36
  5564.4 1927.56  5584.1 1931.85  5604.2 1933.94  5724.9 1937.56    5735 1938.07
  5740.5 1939.37  5745.5 1937.57  5755.1 1938.29  5831.1 1949.55  5872.6 1954.68
#Mann= 10 ,-1 , 0
  4281.4    .035       0  4346.9     .07       0  4472.3    .035       0
  4501.6     .07       0  4575.7    .035       0  4883.9     .07       0
  4958.9    .035       0  4981.7     .07       0  5324.9     .07       0
  5515.1     .16       0
Bank Sta=4958.9,4981.7
XS Rating Curve= 0 ,0
Exp/Cntr=0.3,0.1

Type RM Length L Ch R = 1 ,674     ,561,561,561
BEGIN DESCRIPTION:
Mapping XS 555c1fd9
END DESCRIPTION:
XS GIS Cut Line= 3
      1490907.44      6823507.16      1491640.08      6824257.17
       1492605.4      6824250.22
#Sta/Elev= 30
  3804.7 1941.63  3830.6 1940.23  3966.2 1936.06  4008.6  1937.4  4029.8 1935.54
  4065.2 1936.55  4083.2 1934.67  4114.6 1928.43    4156 1926.34    4301 1925.12
  4340.8 1925.25  4547.5 1924.13  4758.2 1923.34  4807.8 1920.75    4843  1914.8
  4903.8 1914.15  4958.1 1914.41  4968.1 1913.94  4976.6 1911.17  4977.1 1910.67
  4999.5 1911.17  5008.1 1915.17  5038.1  1917.9  5288.1 1917.56  5360.6 1919.21
  5488.1 1924.62  5648.1 1926.44  5758.1 1956.43  5778.1 1958.26  5818.5 1958.41
#Mann= 11 ,-1 , 0
  3804.7     .07       0  3830.6    .035       0  4083.2     .07       0
    4156    .035       0    4301     .07       0  4340.8    .035       0
  4547.5     .07       0  4903.8    .035       0  4976.6    .035       0
  4999.5    .035       0  5360.6     .16       0
Bank Sta=4976.6,4999.5
XS Rating Curve= 0 ,0
Exp/Cntr=0.3,0.1

Type RM Length L Ch R = 1 ,113     ,0,0,0
BEGIN DESCRIPTION:
NUBIA CREEK TRIBUTARY 1 1.0
END DESCRIPTION:
XS GIS Cut Line= 3
      1490938.67      6823670.32      1491654.98      6824774.53
       1492621.4      6824556.08
#Sta/Elev= 30
  3683.8 1940.01  3707.7 1938.52  3759.1 1930.74  3824.1 1926.16    4057 1926.09
  4423.6 1925.98  4608.9 1923.42  4713.7 1922.17  4760.9 1916.22  4771.7 1916.03
  4837.3 1916.24  4864.6 1912.41  4925.3 1911.66  4967.4 1912.27  4968.9 1910.17
  4969.4 1909.67  4991.8 1910.17  5011.2 1912.14  5132.7 1913.12  5242.8 1916.38
  5424.5 1916.65  5605.4 1916.13  5666.4 1915.62  5824.3 1919.99    5851 1923.03
  5898.2 1935.38  5915.8 1939.91    5959 1955.64  5964.1 1952.21  5990.8 1951.22
#Mann= 13 ,-1 , 0
  3683.8    .035       0    4057     .07       0  4608.9     .16       0
  4760.9     .07       0  4771.7     .16       0  4925.3     .07       0
  4968.9    .035       0  4991.8     .07       0  5132.7     .16       0
  5242.8     .07       0  5424.5    .035       0  5605.4     .16       0
  5898.2     .07       0
Bank Sta=4968.9,4991.8
XS Rating Curve= 0 ,0
Exp/Cntr=0.3,0.1

Chan Stop Cuts=-1
Use User Specified Reach Order=0
Composite Channel Slope=5