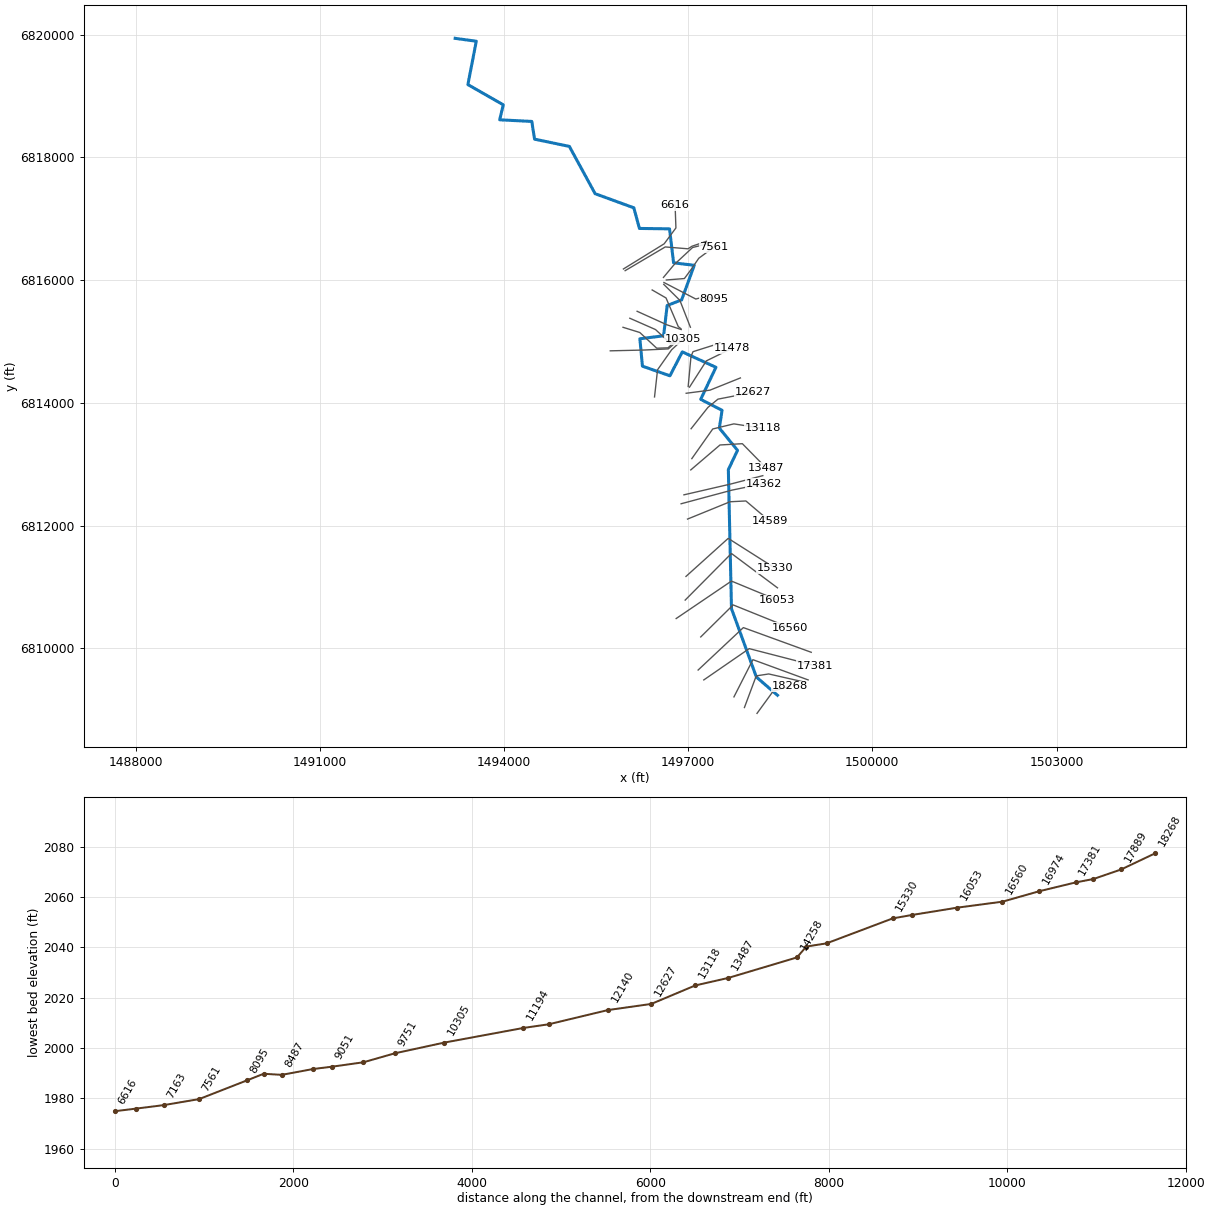
--- NUBIA CREEK TRIBUTARY 1_1.prj (project) ---

Proj Title=NUBIA CREEK TRIBUTARY 1_1 Base Level Engineering
Current Plan=p01
Default Exp/Contr=0.3,0.1
English Units
Geom File=g01
Flow File=f01
Plan File=p01
Y Axis Title=Elevation
X Axis Title(PF)=Main Channel Distance
X Axis Title(XS)=Station
BEGIN DESCRIPTION:
NUBIA CREEK TRIBUTARY 1_1
END DESCRIPTION:
DSS Export Rating Curves= 0
DSS Export Rating Curve Sorted= 0
DSS Export Volume Flow Curves= 0
DXF OffsetX= 0
DXF OffsetY= 0
DXF ScaleX= 1
DXF ScaleY= 10

--- NUBIA CREEK TRIBUTARY 1_1.p01 (plan) ---

Plan Title=Multiple Run
Short Identifier=Multiple
Geom File=g01
Flow File=f01
Subcritical Flow
K Sum by GR= 0
Std Step Tol= 0.01
Critical Tol= 0.01
Num of Std Step Trials= 20
Max Error Tol= 0.3
Flow Tol Ratio= 0.001
Split Flow NTrial= 30
Split Flow Tol= 0.02
Split Flow Ratio= 0.02
Log Output Level= 0
Friction Slope Method= 1
Unsteady Friction Slope Method= 2
Unsteady Bridges Friction Slope Method= 1
Parabolic Critical Depth
Global Vel Dist=  1 , 1 , 1
Global Log Level= 0
CheckData=True
Encroach Param= -1, 0, 0, 0
BEGIN DESCRIPTION:
Multiple Run
END DESCRIPTION:

--- NUBIA CREEK TRIBUTARY 1_1.f01 (steady flow) ---

Flow Title=Multiple
Program Version=4.10
Number of Profiles= 7
Profile Names=10-year,25-year,50-year,1pct_min,100-year,1pct_plu,500-year
River Rch & RM=NUBIA CREEK TRIB,Reach-1         ,18268
     362     524     664     420     838    1672    1348
River Rch & RM=NUBIA CREEK TRIB,Reach-1         ,13487
     596     885    1141     732    1460    2913    2419
River Rch & RM=NUBIA CREEK TRIB,Reach-1         ,8487
     753    1126    1457     938    1871    3733    3120
Boundary for River Rch & Prof#=NUBIA CREEK TRIB,Reach-1         , 1
Up Type= 0
Dn Type= 3
Dn Slope=0.00578
Boundary for River Rch & Prof#=NUBIA CREEK TRIB,Reach-1         , 2
Up Type= 0
Dn Type= 3
Dn Slope=0.00578
Boundary for River Rch & Prof#=NUBIA CREEK TRIB,Reach-1         , 3
Up Type= 0
Dn Type= 3
Dn Slope=0.00578
Boundary for River Rch & Prof#=NUBIA CREEK TRIB,Reach-1         , 4
Up Type= 0
Dn Type= 3
Dn Slope=0.00578
Boundary for River Rch & Prof#=NUBIA CREEK TRIB,Reach-1         , 5
Up Type= 0
Dn Type= 3
Dn Slope=0.00578
Boundary for River Rch & Prof#=NUBIA CREEK TRIB,Reach-1         , 6
Up Type= 0
Dn Type= 3
Dn Slope=0.00578
Boundary for River Rch & Prof#=NUBIA CREEK TRIB,Reach-1         , 7
Up Type= 0
Dn Type= 3
Dn Slope=0.00578
DSS Import GetInterval= 0
DSS Import GetPeak= 0
DSS Import FillOption= 0

--- NUBIA CREEK TRIBUTARY 1_1.g01 (geometry) ---

Geom Title=Existing Conditions

River Reach=NUBIA CREEK TRIB,Reach-1
Reach XY= 30
      1498455.00      6809238.00      1498110.80      6809535.70
      1497705.93      6810648.49      1497654.71      6812913.12
      1497804.11      6813227.66      1497508.46      6813589.49
      1497551.94      6813879.70      1497204.45      6814058.12
      1497452.54      6814579.83      1496904.75      6814831.02
      1496703.50      6814441.46      1496255.53      6814598.45
      1496213.88      6815044.53      1496599.92      6815093.03
      1496658.43      6815586.78      1496893.91      6815677.62
      1497099.64      6816240.78      1496762.85      6816281.81
      1496696.69      6816835.03      1496206.50      6816841.61
      1496115.24      6817177.65      1495484.80      6817407.61
      1495065.17      6818177.68      1494498.56      6818296.02
      1494453.56      6818584.47      1493930.53      6818611.01
      1493988.78      6818855.21      1493412.59      6819184.65
      1493549.29      6819890.59      1493205.00      6819938.00

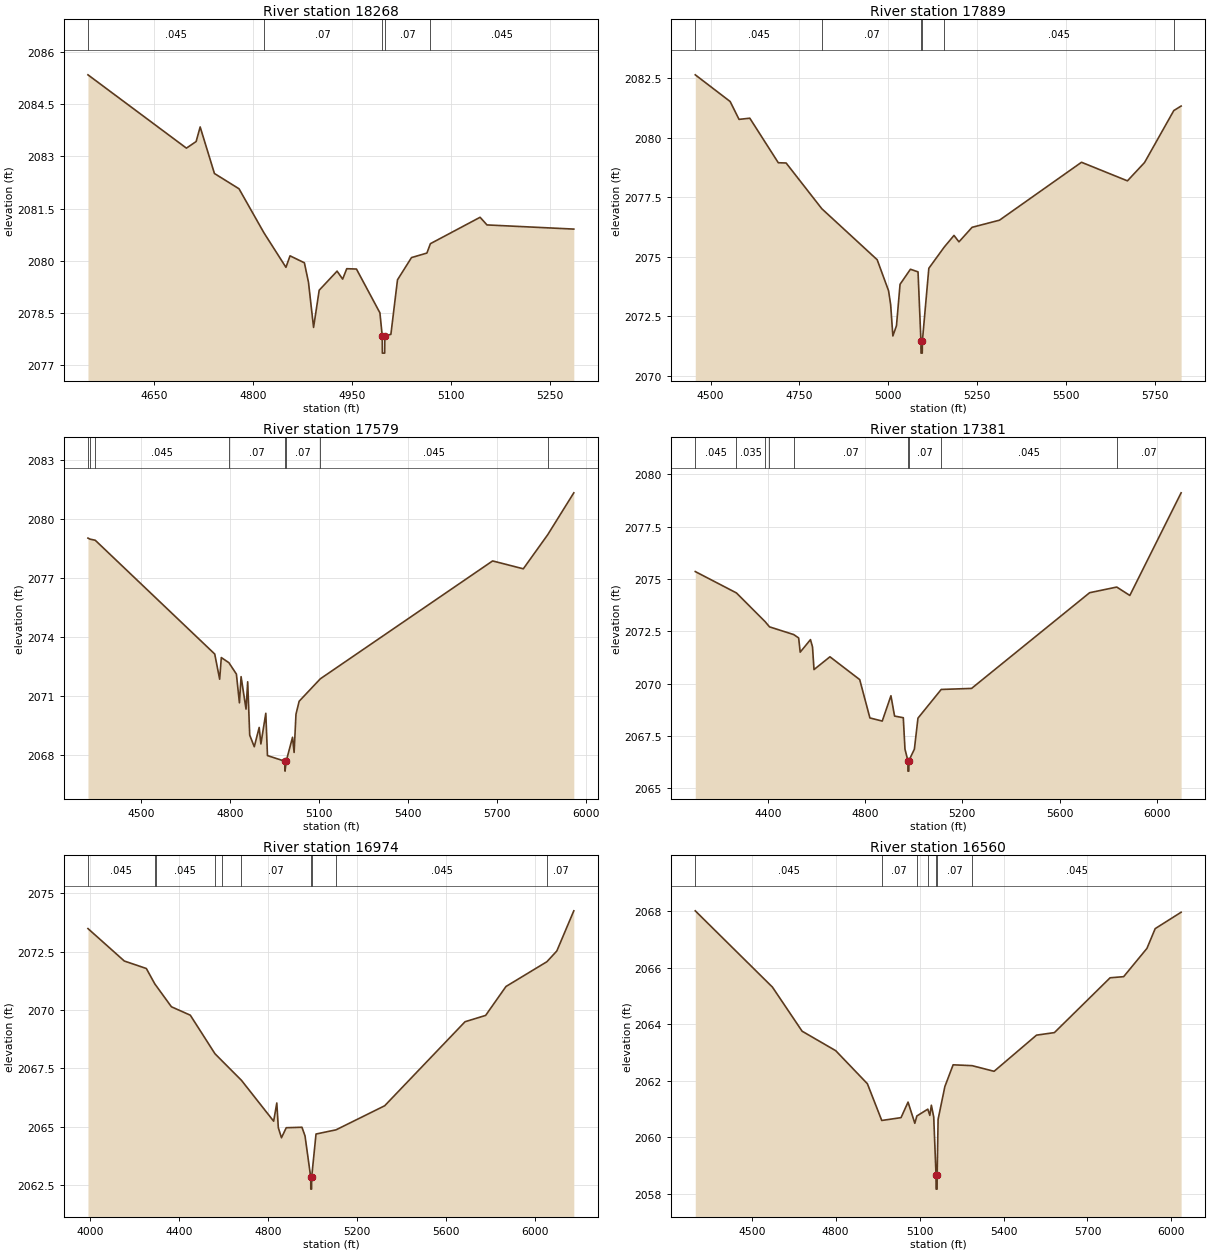
Type RM Length L Ch R = 1,18268,379,379,379
BEGIN DESCRIPTION:
NUBIA CREEK TRIBUTARY 1_1 32.0
END DESCRIPTION:
XS GIS Cut Line= 3
      1498121.81      6808943.24      1498386.43      6809306.60
      1498661.50      6809383.80
#Sta/Elev= 30
  4550.5 2085.35  4699.5 2083.24  4714.2 2083.43  4720.3 2083.85  4741.9 2082.51
  4779.1 2082.07  4816.9 2080.80  4850.1 2079.81  4856.3 2080.14  4878.0 2079.94
  4884.2 2079.38  4891.9 2078.08  4900.4 2079.15  4927.5 2079.70  4935.9 2079.47
  4942.1 2079.77  4956.8 2079.76  4992.3 2078.50  4995.8 2077.84  4996.0 2077.34
  4999.5 2077.34  4999.8 2077.84  5008.9 2077.88  5018.9 2079.45  5040.1 2080.09
  5063.4 2080.22  5068.7 2080.49  5143.9 2081.25  5154.3 2081.03  5285.7 2080.91
#Mann=5,-1,0
  4550.5   0.045       0  4816.9    0.07       0  4995.8    0.07       0
  4999.8    0.07       0  5068.7   0.045       0
Bank Sta=4995.8,4999.8
Exp/Cntr=0.3,0.1

Type RM Length L Ch R = 1,17889,310,310,310
BEGIN DESCRIPTION:
Mapping XS b5628829
END DESCRIPTION:
XS GIS Cut Line= 4
      1497916.58      6809038.44      1498109.28      6809554.03
      1498312.40      6809585.28      1498908.79      6809449.85
#Sta/Elev= 30
  4456.8 2082.64  4555.0 2081.52  4580.0 2080.77  4610.3 2080.82  4690.5 2078.95
  4712.5 2078.94  4813.0 2077.02  4968.8 2074.88  5000.8 2073.58  5006.7 2073.00
  5013.0 2071.68  5023.1 2072.11  5033.2 2073.85  5062.4 2074.48  5083.8 2074.37
  5092.0 2071.46  5092.2 2070.96  5095.7 2070.96  5096.0 2071.46  5114.2 2074.52
  5157.5 2075.41  5185.0 2075.90  5199.0 2075.63  5235.9 2076.24  5313.1 2076.54
  5543.9 2078.97  5673.2 2078.19  5721.4 2078.96  5803.7 2081.14  5824.3 2081.33
#Mann=6,-1,0
  4456.8   0.045       0  4813.0    0.07       0  5092.0    0.07       0
  5096.0    0.07       0  5157.5   0.045       0  5803.7    0.07       0
Bank Sta=5092,5096
Exp/Cntr=0.3,0.1

Type RM Length L Ch R = 1,17579,198,198,198
BEGIN DESCRIPTION:
NUBIA CREEK TRIBUTARY 1_1 31.0
END DESCRIPTION:
XS GIS Cut Line= 3
      1497745.93      6809211.74      1498054.77      6809817.90
      1498955.02      6809487.99
#Sta/Elev= 30
  4319.7 2079.01  4326.1 2078.96  4344.3 2078.90  4747.4 2073.12  4764.0 2071.84
  4769.6 2072.94  4795.1 2072.68  4820.5 2072.10  4830.7 2070.64  4836.3 2071.97
  4853.0 2070.32  4858.6 2071.71  4865.4 2069.00  4880.8 2068.41  4897.4 2069.39
  4903.1 2068.55  4919.7 2070.11  4925.3 2067.96  4984.4 2067.67  4984.6 2067.17
  4988.4 2067.67  5009.9 2068.89  5015.2 2068.12  5021.5 2070.06  5032.2 2070.72
  5103.6 2071.86  5684.9 2077.85  5788.4 2077.45  5870.7 2079.18  5958.8 2081.31
#Mann=8,-1,0
  4319.7   0.045       0  4326.1    0.07       0  4344.3   0.045       0
  4795.1    0.07       0  4984.4    0.07       0  4988.4    0.07       0
  5103.6   0.045       0  5870.7    0.07       0
Bank Sta=4984.4,4988.4
Exp/Cntr=0.3,0.1

Type RM Length L Ch R = 1,17381,407,407,407
BEGIN DESCRIPTION:
NUBIA CREEK TRIBUTARY 1_1 30.0
END DESCRIPTION:
XS GIS Cut Line= 3
      1497255.03      6809488.02      1497994.44      6809997.79
      1499059.20      6809722.81
#Sta/Elev= 30
  4101.9 2075.35  4271.1 2074.33  4389.0 2072.96  4407.1 2072.71  4506.9 2072.34
  4527.0 2072.18  4533.3 2071.50  4575.6 2072.10  4584.0 2071.75  4590.1 2070.67
  4655.7 2071.28  4778.1 2070.19  4820.0 2068.36  4870.7 2068.21  4906.5 2069.42
  4921.4 2068.45  4957.3 2068.37  4964.2 2066.87  4976.2 2066.32  4976.5 2065.82
  4980.0 2065.82  4980.2 2066.32  5002.9 2066.87  5017.6 2068.35  5113.2 2069.72
  5238.1 2069.77  5723.5 2074.34  5835.0 2074.61  5888.8 2074.21  6099.7 2079.11
#Mann=9,-1,0
  4101.9   0.045       0  4271.1   0.035       0  4389.0    0.07       0
  4407.1   0.035       0  4506.9    0.07       0  4976.2    0.07       0
  4980.2    0.07       0  5113.2   0.045       0  5835.0    0.07       0
Bank Sta=4976.2,4980.2
Exp/Cntr=0.3,0.1

Type RM Length L Ch R = 1,16974,414,414,414
BEGIN DESCRIPTION:
NUBIA CREEK TRIBUTARY 1_1 29.0
END DESCRIPTION:
XS GIS Cut Line= 3
      1497162.55      6809649.18      1497899.20      6810340.31
      1499004.99      6809938.01
#Sta/Elev= 30
  3989.9 2073.49  4153.6 2072.10  4252.7 2071.78  4290.8 2071.12  4295.4 2071.06
  4365.6 2070.14  4450.6 2069.78  4561.5 2068.13  4593.8 2067.82  4680.8 2066.99
  4825.7 2065.24  4839.9 2066.02  4846.7 2064.96  4860.9 2064.53  4882.4 2064.96
  4953.1 2064.98  4966.9 2064.61  4992.7 2062.83  4992.9 2062.33  4996.4 2062.33
  4996.7 2062.83  5016.4 2064.69  5106.6 2064.87  5325.4 2065.90  5687.2 2069.50
  5779.8 2069.77  5871.5 2071.01  6055.6 2072.07  6100.2 2072.53  6176.7 2074.25
#Mann=10,-1,0
  3989.9   0.045       0  4290.8   0.035       0  4295.4   0.045       0
  4561.5    0.07       0  4593.8   0.045       0  4680.8    0.07       0
  4992.7    0.07       0  4996.7    0.07       0  5106.6   0.045       0
  6055.6    0.07       0
Bank Sta=4992.7,4996.7
Exp/Cntr=0.3,0.1

Type RM Length L Ch R = 1,16560,507,507,507
BEGIN DESCRIPTION:
NUBIA CREEK TRIBUTARY 1_1 28.0
END DESCRIPTION:
XS GIS Cut Line= 3
      1497205.02      6810188.02      1497732.89      6810709.80
      1498655.03      6810337.99
#Sta/Elev= 30
  4298.2 2068.01  4574.0 2065.31  4680.0 2063.75  4800.2 2063.06  4913.4 2061.89
  4964.7 2060.59  5033.6 2060.69  5058.7 2061.24  5082.9 2060.49  5090.2 2060.75
  5129.3 2060.99  5136.6 2060.77  5142.0 2061.13  5150.5 2060.71  5158.7 2058.66
  5159.0 2058.16  5162.5 2058.16  5162.7 2058.66  5166.1 2060.63  5190.3 2061.79
  5219.8 2062.56  5287.7 2062.53  5366.2 2062.33  5517.9 2063.61  5581.8 2063.70
  5780.9 2065.64  5829.3 2065.68  5912.5 2066.68  5942.0 2067.38  6034.7 2067.96
#Mann=7,-1,0
  4298.2   0.045       0  4964.7    0.07       0  5090.2   0.045       0
  5129.3    0.07       0  5158.7    0.07       0  5162.7    0.07       0
  5287.7   0.045       0
Bank Sta=5158.7,5162.7
Exp/Cntr=0.3,0.1

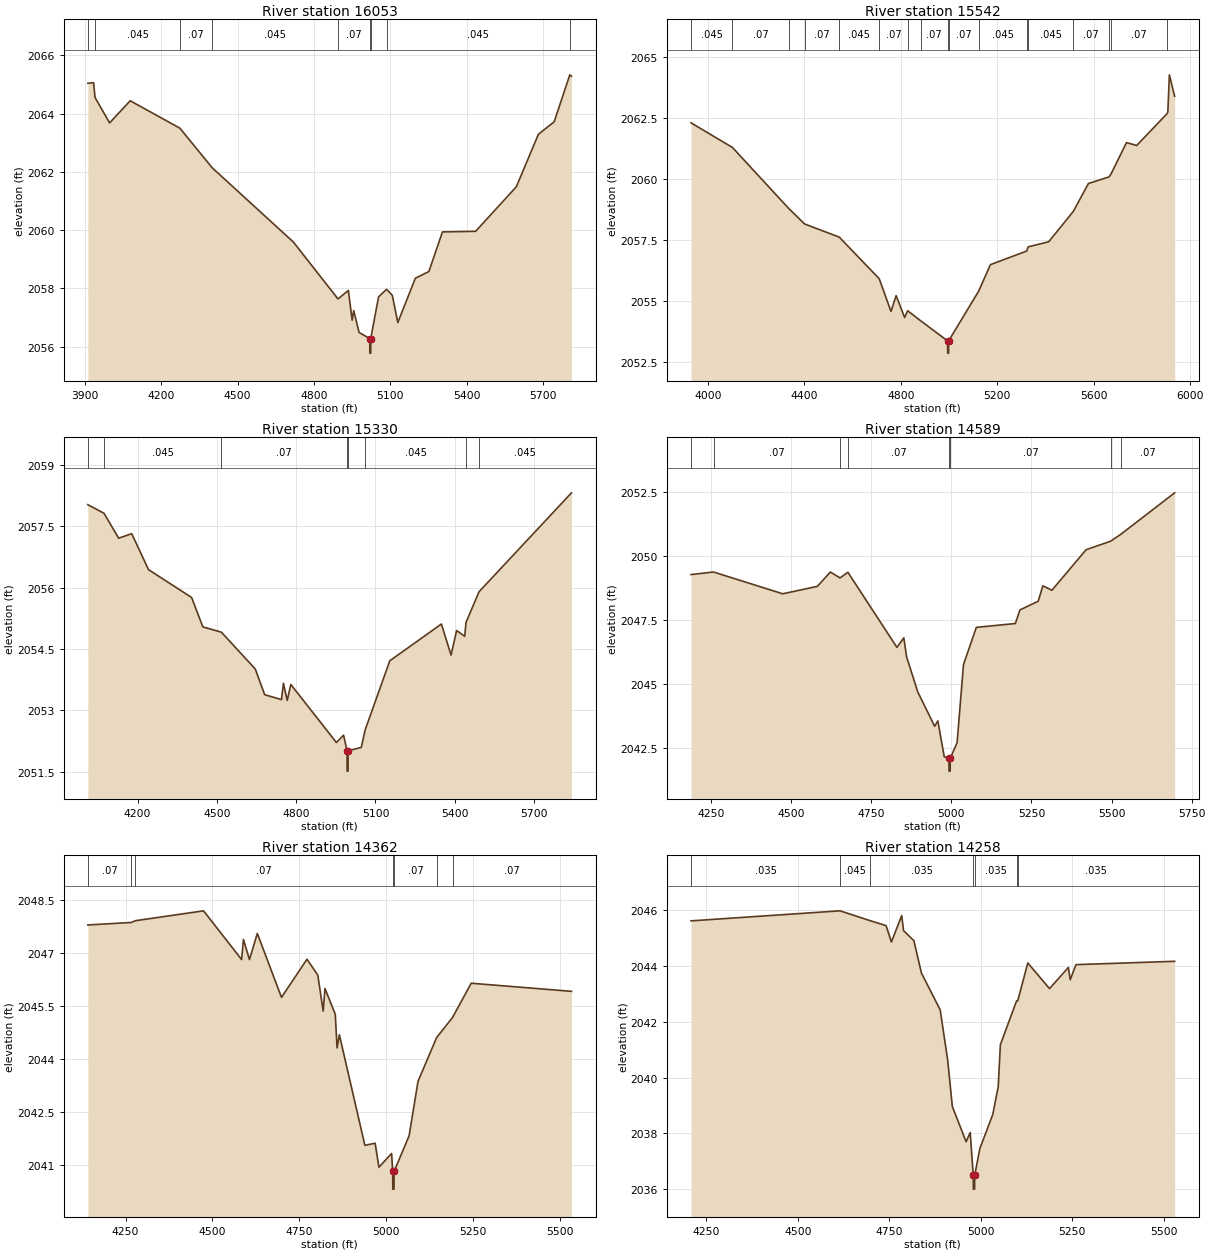
Type RM Length L Ch R = 1,16053,511,511,511
BEGIN DESCRIPTION:
NUBIA CREEK TRIBUTARY 1_1 27.0
END DESCRIPTION:
XS GIS Cut Line= 3
      1496804.97      6810487.98      1497705.40      6811098.17
      1498454.96      6810788.02
#Sta/Elev= 30
  3912.3 2065.04  3934.8 2065.06  3940.7 2064.55  3997.7 2063.68  4078.5 2064.44
  4273.6 2063.50  4400.6 2062.14  4719.5 2059.59  4894.5 2057.64  4935.2 2057.93
  4950.1 2056.91  4956.2 2057.24  4977.2 2056.49  5019.2 2056.28  5019.5 2055.78
  5023.0 2055.78  5023.2 2056.28  5053.7 2057.71  5085.2 2057.97  5107.8 2057.76
  5129.4 2056.83  5198.2 2058.35  5251.4 2058.58  5304.6 2059.94  5434.9 2059.96
  5594.8 2061.49  5681.4 2063.29  5743.4 2063.72  5804.7 2065.33  5811.2 2065.28
#Mann=9,-1,0
  3912.3    0.07       0  3940.7   0.045       0  4273.6    0.07       0
  4400.6   0.045       0  4894.5    0.07       0  5019.2    0.07       0
  5023.2    0.07       0  5085.2   0.045       0  5804.7    0.07       0
Bank Sta=5019.2,5023.2
Exp/Cntr=0.3,0.1

Type RM Length L Ch R = 1,15542,212,212,212
BEGIN DESCRIPTION:
NUBIA CREEK TRIBUTARY 1_1 26.0
END DESCRIPTION:
XS GIS Cut Line= 3
      1496951.63      6810788.35      1497705.05      6811547.98
      1498455.04      6810987.97
#Sta/Elev= 30
  3930.1 2062.30  4101.8 2061.29  4336.0 2058.78  4401.2 2058.15  4545.0 2057.61
  4710.9 2055.90  4759.6 2054.56  4780.8 2055.21  4816.2 2054.31  4828.6 2054.59
  4883.6 2054.17  4994.5 2053.35  4994.7 2052.85  4998.2 2052.85  4998.5 2053.35
  5123.0 2055.39  5171.9 2056.48  5322.6 2057.04  5328.2 2057.21  5413.7 2057.42
  5516.0 2058.67  5578.4 2059.81  5663.4 2060.08  5671.6 2060.19  5736.3 2061.49
  5778.6 2061.37  5904.0 2062.67  5907.8 2062.74  5914.1 2064.27  5936.0 2063.39
#Mann=17,-1,0
  3930.1   0.045       0  4101.8    0.07       0  4336.0   0.045       0
  4401.2    0.07       0  4545.0   0.045       0  4710.9    0.07       0
  4828.6   0.045       0  4883.6    0.07       0  4994.5    0.07       0
  4998.5    0.07       0  5123.0   0.045       0  5322.6    0.07       0
  5328.2   0.045       0  5516.0    0.07       0  5663.4   0.045       0
  5671.6    0.07       0  5904.0   0.045       0
Bank Sta=4994.5,4998.5
Exp/Cntr=0.3,0.1

Type RM Length L Ch R = 1,15330,741,741,741
BEGIN DESCRIPTION:
Mapping XS 3bbf3a50
END DESCRIPTION:
XS GIS Cut Line= 3
      1496964.64      6811173.76      1497652.16      6811793.56
      1498415.15      6811309.21
#Sta/Elev= 30
  4012.1 2058.03  4073.2 2057.82  4128.7 2057.21  4178.1 2057.32  4241.6 2056.44
  4404.5 2055.76  4447.1 2055.04  4517.2 2054.91  4645.4 2054.01  4681.0 2053.38
  4744.6 2053.26  4752.0 2053.66  4766.2 2053.24  4780.0 2053.63  4952.3 2052.21
  4979.4 2052.39  4992.6 2052.01  4992.9 2051.51  4996.4 2051.51  4996.6 2052.01
  5046.3 2052.09  5061.1 2052.52  5154.3 2054.21  5349.5 2055.11  5386.0 2054.35
  5407.1 2054.95  5437.6 2054.81  5442.6 2055.15  5492.0 2055.90  5841.5 2058.32
#Mann=8,-1,0
  4012.1    0.07       0  4073.2   0.045       0  4517.2    0.07       0
  4992.6    0.07       0  4996.6    0.07       0  5061.1   0.045       0
  5442.6    0.07       0  5492.0   0.045       0
Bank Sta=4992.6,4996.6
Exp/Cntr=0.3,0.1

Type RM Length L Ch R = 1,14589,227,227,227
BEGIN DESCRIPTION:
Mapping XS c6971c0d
END DESCRIPTION:
XS GIS Cut Line= 4
      1496989.79      6812107.78      1497682.11      6812389.92
      1497940.35      6812402.94      1498324.49      6812077.40
#Sta/Elev= 30
  4187.2 2049.26  4257.4 2049.36  4473.6 2048.51  4581.6 2048.80  4622.2 2049.36
  4652.3 2049.13  4676.9 2049.35  4829.9 2046.42  4851.5 2046.79  4860.2 2046.05
  4895.0 2044.68  4947.7 2043.34  4957.7 2043.55  4977.7 2042.15  4992.4 2042.09
  4992.6 2041.59  4996.1 2041.59  4996.4 2042.09  5017.8 2042.70  5037.8 2045.75
  5077.9 2047.20  5199.7 2047.35  5213.9 2047.88  5271.1 2048.22  5285.4 2048.82
  5313.9 2048.65  5420.5 2050.23  5496.7 2050.56  5529.8 2050.84  5696.9 2052.45
#Mann=8,-1,0
  4187.2   0.045       0  4257.4    0.07       0  4652.3   0.045       0
  4676.9    0.07       0  4992.4    0.07       0  4996.4    0.07       0
  5496.7   0.045       0  5529.8    0.07       0
Bank Sta=4992.4,4996.4
Exp/Cntr=0.3,0.1

Type RM Length L Ch R = 1,14362,104,104,104
BEGIN DESCRIPTION:
Mapping XS a54ef988
END DESCRIPTION:
XS GIS Cut Line= 3
      1496885.64      6812357.36      1497710.32      6812578.72
      1498237.70      6812687.24
#Sta/Elev= 30
  4141.4 2047.80  4266.5 2047.87  4278.3 2047.92  4474.5 2048.20  4584.1 2046.82
  4589.3 2047.39  4606.7 2046.82  4629.3 2047.56  4698.9 2045.75  4772.3 2046.83
  4803.4 2046.38  4818.9 2045.36  4824.1 2046.00  4853.7 2045.27  4858.9 2044.32
  4865.5 2044.69  4938.9 2041.56  4968.5 2041.62  4979.4 2040.94  5015.9 2041.33
  5019.0 2040.82  5019.3 2040.32  5022.8 2040.32  5023.0 2040.82  5066.3 2041.83
  5091.9 2043.37  5145.4 2044.61  5191.3 2045.18  5245.1 2046.15  5533.7 2045.92
#Mann=7,-1,0
  4141.4    0.07       0  4266.5   0.045       0  4278.3    0.07       0
  5019.0    0.07       0  5023.0    0.07       0  5145.4   0.035       0
  5191.3    0.07       0
Bank Sta=5019,5023
Exp/Cntr=0.3,0.1

Type RM Length L Ch R = 1,14258,771,771,771
BEGIN DESCRIPTION:
Mapping XS dc2f1c7b
END DESCRIPTION:
XS GIS Cut Line= 3
      1496931.19      6812502.76      1497701.64      6812680.72
      1498216.00      6812815.28
#Sta/Elev= 30
  4208.0 2045.62  4615.6 2045.98  4697.0 2045.63  4741.4 2045.45  4755.9 2044.86
  4784.1 2045.81  4789.2 2045.27  4817.4 2044.91  4838.0 2043.75  4889.3 2042.43
  4909.8 2040.63  4922.6 2038.96  4960.2 2037.70  4971.4 2038.03  4979.7 2036.50
  4979.9 2036.00  4983.4 2036.00  4983.7 2036.50  4997.9 2037.46  5033.2 2038.68
  5048.0 2039.67  5053.9 2041.18  5098.2 2042.75  5101.3 2042.75  5128.9 2044.11
  5188.3 2043.19  5239.8 2043.95  5245.0 2043.51  5260.6 2044.05  5530.4 2044.17
#Mann=7,-1,0
  4208.0   0.035       0  4615.6   0.045       0  4697.0   0.035       0
  4979.7   0.035       0  4983.7   0.035       0  5098.2    0.07       0
  5101.3   0.035       0
Bank Sta=4979.7,4983.7
Exp/Cntr=0.3,0.1

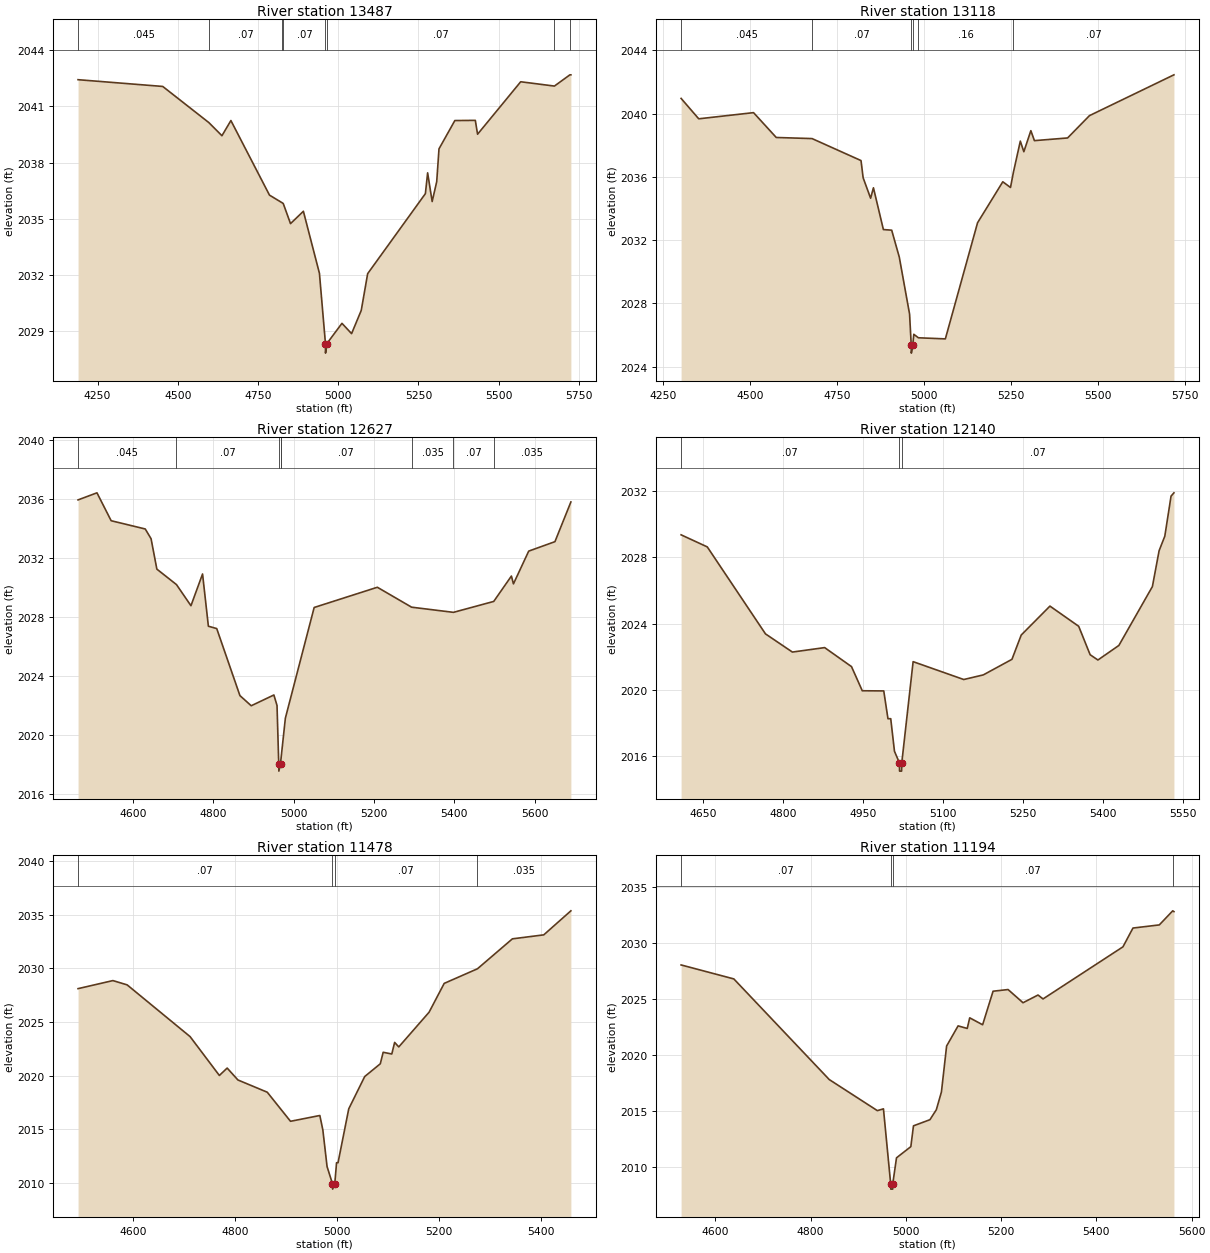
Type RM Length L Ch R = 1,13487,369,369,369
BEGIN DESCRIPTION:
Mapping XS 5d69c823
END DESCRIPTION:
XS GIS Cut Line= 4
      1497042.82      6812908.61      1497518.48      6813314.83
      1497883.06      6813335.67      1498265.02      6812946.76
#Sta/Elev= 30
  4189.3 2042.43  4453.2 2042.07  4597.0 2040.14  4637.7 2039.44  4665.6 2040.25
  4785.9 2036.27  4825.6 2035.86  4828.8 2035.82  4851.4 2034.75  4891.5 2035.41
  4941.5 2032.10  4960.3 2028.34  4960.5 2027.84  4964.3 2028.34  5011.7 2029.43
  5041.7 2028.88  5071.8 2030.12  5091.8 2032.08  5271.7 2036.35  5278.7 2037.46
  5292.8 2035.93  5307.0 2036.99  5314.1 2038.74  5363.5 2040.25  5427.3 2040.26
  5434.3 2039.52  5568.7 2042.32  5673.8 2042.09  5722.1 2042.69  5725.1 2042.69
#Mann=8,-1,0
  4189.3   0.045       0  4597.0    0.07       0  4825.6   0.035       0
  4828.8    0.07       0  4960.3    0.07       0  4964.3    0.07       0
  5673.8   0.035       0  5722.1    0.07       0
Bank Sta=4960.3,4964.3
Exp/Cntr=0.3,0.1

Type RM Length L Ch R = 1,13118,491,491,491
BEGIN DESCRIPTION:
Mapping XS 83879813
END DESCRIPTION:
XS GIS Cut Line= 4
      1497060.12      6813092.57      1497400.42      6813575.25
      1497744.17      6813658.58      1498211.47      6813585.89
#Sta/Elev= 30
  4301.2 2040.96  4351.9 2039.67  4509.5 2040.06  4574.8 2038.49  4677.8 2038.42
  4818.6 2037.03  4824.7 2035.94  4846.2 2034.65  4854.3 2035.31  4882.9 2032.67
  4906.8 2032.63  4928.6 2030.93  4958.2 2027.33  4963.0 2025.36  4963.3 2024.86
  4967.4 2025.36  4970.4 2026.05  4983.5 2025.83  5061.1 2025.76  5153.7 2033.10
  5226.3 2035.69  5248.4 2035.33  5256.8 2036.29  5276.7 2038.26  5286.8 2037.59
  5307.0 2038.92  5317.2 2038.29  5412.6 2038.46  5475.5 2039.87  5718.4 2042.45
#Mann=6,-1,0
  4301.2   0.045       0  4677.8    0.07       0  4963.0    0.07       0
  4967.4    0.07       0  4983.5    0.16       0  5256.8    0.07       0
Bank Sta=4963,4967.4
Exp/Cntr=0.3,0.1

Type RM Length L Ch R = 1,12627,487,487,487
BEGIN DESCRIPTION:
Mapping XS 994126a0
END DESCRIPTION:
XS GIS Cut Line= 4
      1497047.98      6813579.58      1497321.43      6813925.94
      1497485.49      6814061.36      1498048.03      6814170.74
#Sta/Elev= 30
  4463.1 2035.91  4510.2 2036.39  4545.5 2034.50  4630.4 2033.94  4644.9 2033.28
  4659.3 2031.22  4708.2 2030.17  4744.2 2028.74  4773.1 2030.89  4787.6 2027.35
  4808.4 2027.19  4866.1 2022.65  4894.3 2021.96  4950.7 2022.69  4958.5 2021.98
  4962.8 2018.03  4963.1 2017.53  4967.2 2018.03  4968.0 2018.26  4979.3 2021.12
  5051.0 2028.62  5208.3 2029.99  5293.6 2028.64  5397.8 2028.29  5498.1 2029.03
  5542.1 2030.75  5547.2 2030.22  5585.2 2032.44  5650.5 2033.08  5690.2 2035.77
#Mann=8,-1,0
  4463.1   0.045       0  4708.2    0.07       0  4962.8    0.07       0
  4967.2    0.07       0  4968.0    0.07       0  5293.6   0.035       0
  5397.8    0.07       0  5498.1   0.035       0
Bank Sta=4962.8,4967.2
Exp/Cntr=0.3,0.1

Type RM Length L Ch R = 1,12140,662,662,662
BEGIN DESCRIPTION:
NUBIA CREEK TRIBUTARY 1_1 20.0
END DESCRIPTION:
XS GIS Cut Line= 3
      1496968.01      6814157.06      1497355.71      6814207.80
      1497850.84      6814406.73
#Sta/Elev= 30
  4609.0 2029.37  4658.1 2028.64  4767.3 2023.38  4817.8 2022.28  4878.3 2022.55
  4928.7 2021.40  4948.9 2019.94  4989.2 2019.93  4997.1 2018.25  5002.3 2018.25
  5009.3 2016.28  5018.6 2015.58  5018.9 2015.08  5022.7 2015.08  5023.0 2015.58
  5044.3 2021.70  5139.3 2020.62  5176.0 2020.90  5229.7 2021.84  5247.1 2023.31
  5301.0 2025.06  5354.9 2023.84  5376.4 2022.12  5391.0 2021.80  5430.3 2022.68
  5493.2 2026.24  5505.8 2028.41  5516.5 2029.29  5528.2 2031.71  5533.6 2031.91
#Mann=3,-1,0
  4609.0    0.07       0  5018.6    0.07       0  5023.0    0.07       0
Bank Sta=5018.6,5023
Exp/Cntr=0.3,0.1

Type RM Length L Ch R = 1,11478,284,284,284
BEGIN DESCRIPTION:
NUBIA CREEK TRIBUTARY 1_1 19.0
END DESCRIPTION:
XS GIS Cut Line= 3
      1497022.25      6814256.88      1497296.15      6814684.36
      1497708.04      6814886.24
#Sta/Elev= 30
  4492.3 2028.12  4560.6 2028.87  4588.6 2028.47  4712.0 2023.65  4769.4 2020.03
  4784.7 2020.72  4805.8 2019.61  4863.3 2018.47  4908.9 2015.76  4966.4 2016.30
  4972.3 2014.96  4980.6 2011.54  4991.2 2009.94  4991.5 2009.44  4995.7 2009.94
  4999.2 2011.90  5002.1 2011.90  5023.1 2016.92  5054.4 2019.93  5085.0 2021.12
  5090.6 2022.19  5107.5 2022.03  5113.1 2023.11  5121.2 2022.69  5180.6 2025.92
  5210.3 2028.61  5275.5 2029.97  5344.0 2032.76  5405.5 2033.13  5458.7 2035.37
#Mann=4,-1,0
  4492.3    0.07       0  4991.2    0.07       0  4995.7    0.07       0
  5275.5   0.035       0
Bank Sta=4991.2,4995.7
Exp/Cntr=0.3,0.1

Type RM Length L Ch R = 1,11194,889,889,889
BEGIN DESCRIPTION:
Mapping XS d6557384
END DESCRIPTION:
XS GIS Cut Line= 4
      1497000.56      6814267.78      1497046.13      6814753.85
      1497078.68      6814834.15      1497516.96      6814973.01
#Sta/Elev= 30
  4528.2 2028.03  4638.9 2026.78  4839.2 2017.78  4940.2 2015.00  4953.0 2015.16
  4968.1 2008.48  4968.4 2007.98  4972.3 2007.98  4972.6 2008.48  4980.4 2010.78
  5010.5 2011.78  5016.0 2013.64  5050.6 2014.19  5064.0 2015.08  5074.7 2016.67
  5085.6 2020.78  5109.7 2022.58  5128.9 2022.35  5134.1 2023.30  5161.2 2022.68
  5183.1 2025.68  5214.6 2025.83  5246.0 2024.65  5277.5 2025.34  5288.0 2024.99
  5455.8 2029.65  5476.8 2031.33  5532.1 2031.61  5560.3 2032.87  5562.8 2032.80
#Mann=4,-1,0
  4528.2    0.07       0  4968.1    0.07       0  4972.6    0.07       0
  5560.3   0.035       0
Bank Sta=4968.1,4972.6
Exp/Cntr=0.3,0.1

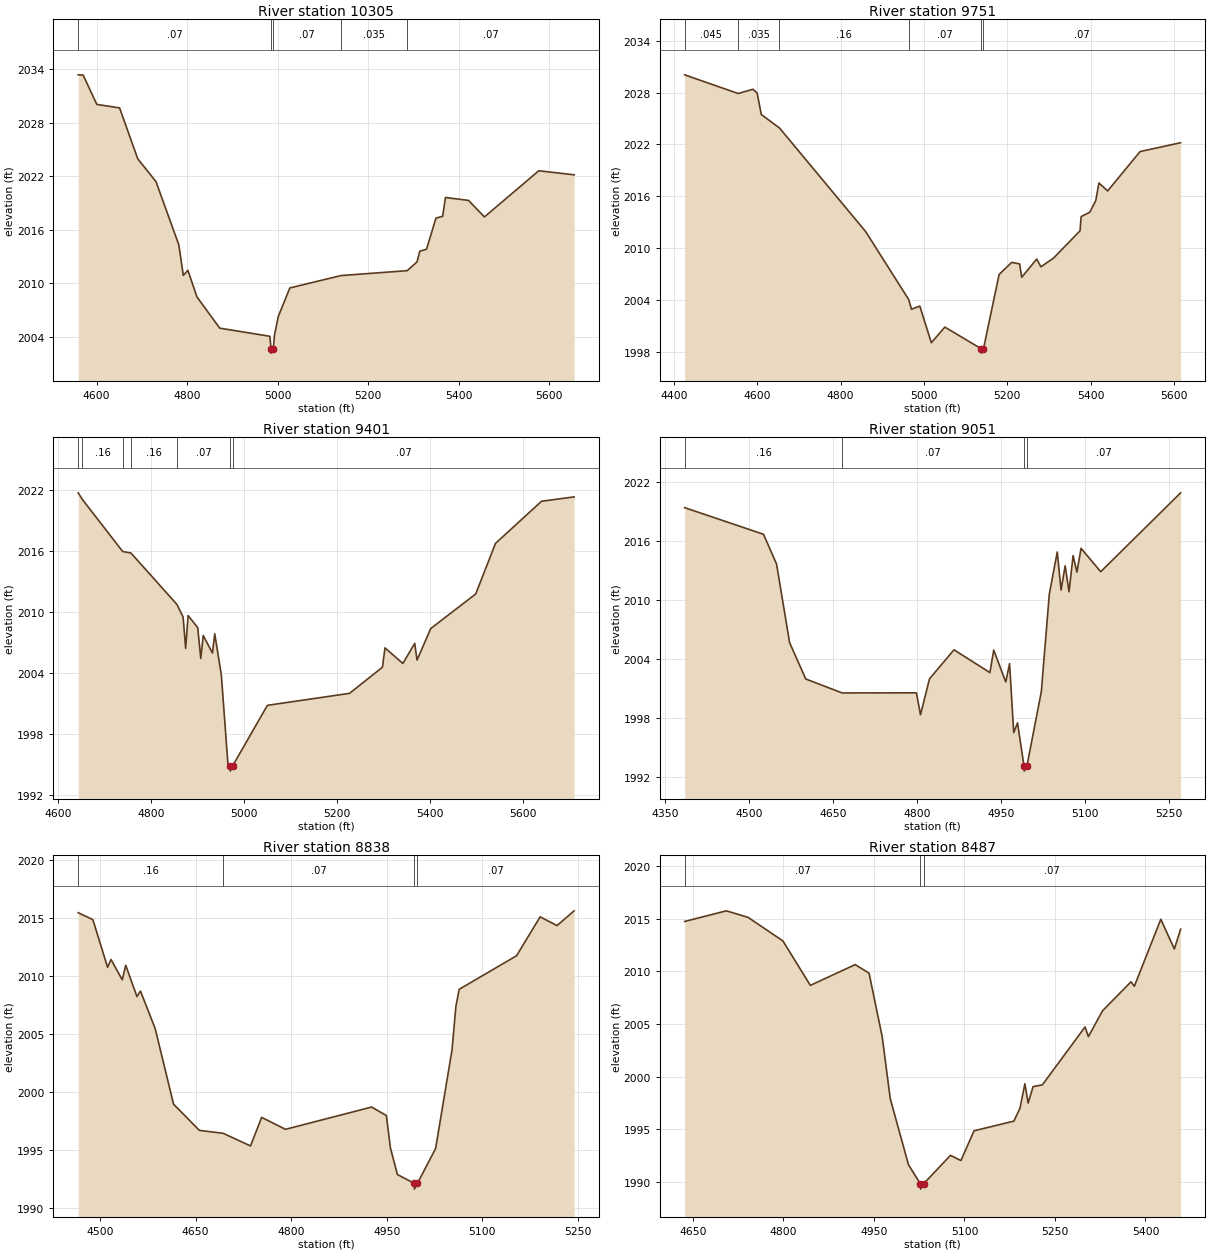
Type RM Length L Ch R = 1,10305,554,554,554
BEGIN DESCRIPTION:
Mapping XS ecf496fb
END DESCRIPTION:
XS GIS Cut Line= 4
      1496452.37      6814097.12      1496501.85      6814539.88
      1496731.02      6814865.40      1496915.95      6815037.31
#Sta/Elev= 30
  4559.2 2033.36  4570.1 2033.33  4600.3 2030.04  4650.6 2029.65  4690.9 2023.93
  4731.1 2021.38  4781.5 2014.30  4791.5 2010.86  4801.6 2011.43  4821.7 2008.44
  4872.0 2004.94  4982.7 2004.03  4985.4 2002.64  4985.7 2002.14  4990.4 2002.64
  4992.9 2004.14  5001.3 2006.24  5026.9 2009.45  5139.9 2010.84  5286.3 2011.39
  5308.1 2012.38  5314.2 2013.58  5329.0 2013.79  5349.9 2017.29  5364.7 2017.49
  5370.9 2019.60  5421.9 2019.27  5457.0 2017.42  5577.2 2022.60  5655.3 2022.14
#Mann=5,-1,0
  4559.2    0.07       0  4985.4    0.07       0  4990.4    0.07       0
  5139.9   0.035       0  5286.3    0.07       0
Bank Sta=4985.4,4990.4
Exp/Cntr=0.3,0.1

Type RM Length L Ch R = 1,9751,350,350,350
BEGIN DESCRIPTION:
Mapping XS 282c4ddf
END DESCRIPTION:
XS GIS Cut Line= 4
      1495731.23      6814848.25      1496288.53      6814861.27
      1496676.55      6814879.50      1496858.83      6815040.95
#Sta/Elev= 30
  4426.2 2030.05  4554.5 2027.89  4590.0 2028.38  4600.0 2027.95  4610.0 2025.46
  4653.5 2023.91  4860.1 2011.94  4963.4 2004.08  4970.1 2002.95  4990.1 2003.32
  5017.8 1999.08  5050.2 2000.89  5137.7 1998.38  5138.1 1997.88  5142.8 1998.38
  5180.3 2006.97  5210.4 2008.37  5229.5 2008.19  5234.5 2006.65  5270.4 2008.75
  5280.5 2007.86  5310.5 2008.85  5374.4 2012.02  5377.0 2013.66  5397.9 2014.17
  5412.2 2015.53  5419.7 2017.55  5440.6 2016.63  5518.4 2021.18  5615.6 2022.20
#Mann=6,-1,0
  4426.2   0.045       0  4554.5   0.035       0  4653.5    0.16       0
  4963.4    0.07       0  5137.7    0.07       0  5142.8    0.07       0
Bank Sta=5137.7,5142.8
Exp/Cntr=0.3,0.1

Type RM Length L Ch R = 1,9401,350,350,350
BEGIN DESCRIPTION:
Mapping XS c7678431
END DESCRIPTION:
XS GIS Cut Line= 5
      1495939.13      6815231.50      1496212.58      6815146.86
      1496488.18      6814890.79      1496672.64      6814897.30
      1496835.41      6815047.04
#Sta/Elev= 30
  4642.7 2021.74  4651.8 2021.08  4738.5 2015.96  4756.3 2015.81  4855.5 2010.74
  4868.7 2009.50  4874.1 2006.42  4879.4 2009.65  4900.1 2008.47  4906.7 2005.43
  4912.0 2007.69  4931.8 2005.96  4936.8 2007.85  4951.0 2003.80  4965.2 1995.02
  4970.0 1994.83  4970.4 1994.33  4975.1 1994.83  5050.2 2000.81  5227.1 2001.99
  5297.9 2004.56  5303.5 2006.47  5342.0 2004.93  5367.5 2006.92  5372.5 2005.27
  5402.0 2008.37  5498.9 2011.78  5541.5 2016.76  5640.7 2020.91  5710.9 2021.34
#Mann=7,-1,0
  4642.7   0.045       0  4651.8    0.16       0  4738.5    0.07       0
  4756.3    0.16       0  4855.5    0.07       0  4970.0    0.07       0
  4975.1    0.07       0
Bank Sta=4970,4975.1
Exp/Cntr=0.3,0.1

Type RM Length L Ch R = 1,9051,213,213,213
BEGIN DESCRIPTION:
Mapping XS f2c24a7d
END DESCRIPTION:
XS GIS Cut Line= 4
      1496049.82      6815379.06      1496468.65      6815194.61
      1496713.88      6814966.74      1496780.57      6815031.28
#Sta/Elev= 30
  4385.5 2019.41  4526.2 2016.70  4549.5 2013.67  4572.8 2005.67  4601.6 2001.97
  4666.5 2000.55  4799.2 2000.56  4806.4 1998.33  4822.5 2001.99  4866.2 2004.94
  4930.3 2002.62  4937.1 2004.91  4958.6 2001.67  4965.4 2003.53  4972.8 1996.51
  4979.6 1997.50  4991.2 1993.09  4991.6 1992.59  4996.3 1993.09  5022.1 2000.69
  5036.3 2010.59  5050.5 2014.90  5057.3 2011.03  5064.6 2013.49  5071.5 2010.85
  5078.8 2014.53  5085.6 2012.85  5093.0 2015.27  5128.1 2012.89  5270.7 2020.92
#Mann=4,-1,0
  4385.5    0.16       0  4666.5    0.07       0  4991.2    0.07       0
  4996.3    0.07       0
Bank Sta=4991.2,4996.3
Exp/Cntr=0.3,0.1

Type RM Length L Ch R = 1,8838,351,351,351
BEGIN DESCRIPTION:
Mapping XS 2d5aed17
END DESCRIPTION:
XS GIS Cut Line= 3
      1496168.76      6815492.34      1496657.02      6815271.00
      1496887.02      6815195.05
#Sta/Elev= 30
  4465.7 2015.47  4488.7 2014.87  4511.8 2010.77  4517.2 2011.44  4534.8 2009.69
  4540.3 2010.94  4557.9 2008.24  4563.4 2008.72  4586.5 2005.49  4615.3 1998.98
  4655.8 1996.72  4693.1 1996.47  4736.1 1995.38  4753.6 1997.84  4791.0 1996.81
  4926.2 1998.73  4949.3 1998.00  4955.6 1995.23  4966.6 1992.92  4993.0 1992.16
  4993.3 1991.66  4998.1 1992.16  5026.6 1995.16  5052.3 2003.64  5058.4 2007.39
  5063.6 2008.87  5153.6 2011.76  5190.6 2015.11  5217.1 2014.36  5244.0 2015.63
#Mann=4,-1,0
  4465.7    0.16       0  4693.1    0.07       0  4993.0    0.07       0
  4998.1    0.07       0
Bank Sta=4993,4998.1
Exp/Cntr=0.3,0.1

Type RM Length L Ch R = 1,8487,203,203,203
BEGIN DESCRIPTION:
Mapping XS b235d92c
END DESCRIPTION:
XS GIS Cut Line= 4
      1496413.93      6815839.59      1496639.66      6815709.36
      1496839.31      6815242.78      1496881.40      6815209.12
#Sta/Elev= 30
  4636.3 2014.72  4705.3 2015.73  4741.4 2015.11  4799.2 2012.87  4844.6 2008.66
  4918.9 2010.63  4941.9 2009.82  4963.6 2003.82  4977.0 1997.93  5007.2 1991.66
  5027.0 1989.84  5027.4 1989.34  5032.2 1989.84  5076.8 1992.54  5094.2 1992.05
  5115.9 1994.87  5182.0 1995.79  5192.1 1997.02  5200.2 1999.33  5205.6 1997.50
  5213.8 1999.06  5229.2 1999.23  5299.9 2004.72  5305.4 2003.80  5329.0 2006.26
  5376.1 2009.00  5381.6 2008.58  5425.5 2014.93  5447.9 2012.11  5458.3 2013.99
#Mann=3,-1,0
  4636.3    0.07       0  5027.0    0.07       0  5032.2    0.07       0
Bank Sta=5027,5032.2
Exp/Cntr=0.3,0.1

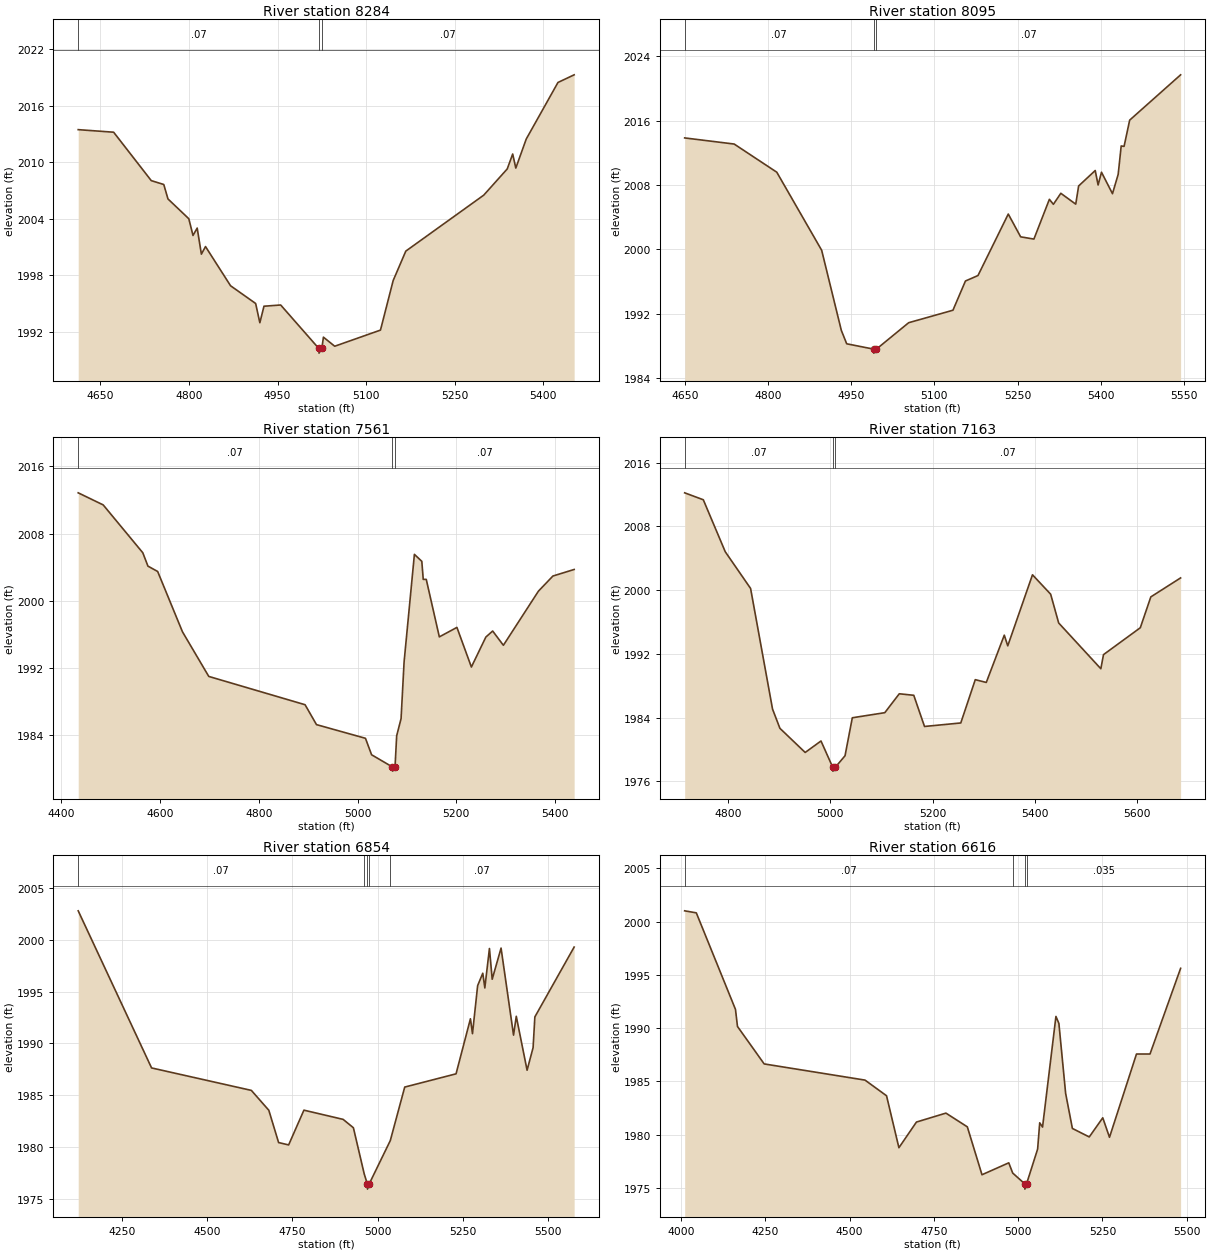
Type RM Length L Ch R = 1,8284,189,189,189
BEGIN DESCRIPTION:
Mapping XS 202471f9
END DESCRIPTION:
XS GIS Cut Line= 3
      1496602.77      6815930.72      1496865.35      6815670.30
      1497036.57      6815232.51
#Sta/Elev= 30
  4612.4 2013.45  4672.4 2013.18  4736.1 2008.05  4757.3 2007.64  4764.4 2006.11
  4799.7 2004.01  4806.8 2002.24  4813.9 2003.02  4821.0 2000.26  4828.0 2001.06
  4870.4 1996.91  4912.9 1995.03  4920.0 1992.99  4927.0 1994.74  4955.3 1994.87
  5019.8 1990.27  5020.2 1989.77  5025.0 1990.27  5027.7 1991.46  5046.8 1990.50
  5124.3 1992.21  5145.8 1997.46  5167.2 2000.58  5299.2 2006.51  5339.0 2009.29
  5348.2 2010.87  5353.5 2009.38  5371.2 2012.46  5424.9 2018.45  5452.3 2019.26
#Mann=3,-1,0
  4612.4    0.07       0  5019.8    0.07       0  5025.0    0.07       0
Bank Sta=5019.8,5025
Exp/Cntr=0.3,0.1

Type RM Length L Ch R = 1,8095,534,534,534
BEGIN DESCRIPTION:
Mapping XS 74a9b78a
END DESCRIPTION:
XS GIS Cut Line= 4
      1496605.81      6815961.10      1497124.47      6815692.00
      1497280.72      6815733.23      1497423.94      6815696.34
#Sta/Elev= 30
  4649.9 2013.85  4739.1 2013.09  4815.9 2009.59  4896.8 1999.89  4932.2 1989.94
  4941.9 1988.27  4990.3 1987.61  4990.7 1987.11  4995.5 1987.61  5053.6 1990.89
  5133.4 1992.44  5155.9 1996.07  5178.5 1996.75  5233.1 2004.39  5255.4 2001.56
  5279.3 2001.28  5307.2 2006.22  5314.4 2005.60  5327.8 2006.97  5354.7 2005.62
  5359.9 2007.88  5389.8 2009.80  5395.0 2008.00  5401.1 2009.59  5420.9 2006.92
  5431.2 2009.33  5436.6 2012.85  5441.8 2012.80  5451.9 2016.06  5543.7 2021.69
#Mann=3,-1,0
  4649.9    0.07       0  4990.3    0.07       0  4995.5    0.07       0
Bank Sta=4990.3,4995.5
Exp/Cntr=0.3,0.1

Type RM Length L Ch R = 1,7561,398,398,398
BEGIN DESCRIPTION:
Mapping XS d3391158
END DESCRIPTION:
XS GIS Cut Line= 5
      1496644.58      6816002.16      1496938.88      6816025.60
      1497050.86      6816176.64      1497173.25      6816356.33
      1497418.02      6816536.00
#Sta/Elev= 30
  4434.4 2012.85  4485.0 2011.41  4565.2 2005.71  4575.6 2004.12  4595.3 2003.48
  4645.5 1996.30  4698.8 1990.98  4893.8 1987.61  4916.9 1985.24  5016.1 1983.61
  5028.5 1981.65  5070.6 1980.20  5071.0 1979.70  5076.0 1980.20  5079.3 1983.91
  5088.2 1985.95  5094.3 1992.69  5115.2 2005.52  5130.2 2004.69  5133.1 2002.54
  5139.2 2002.54  5165.7 1995.69  5201.3 1996.82  5230.6 1992.10  5259.9 1995.67
  5273.7 1996.39  5295.4 1994.69  5366.4 2001.14  5395.7 2002.94  5438.7 2003.72
#Mann=3,-1,0
  4434.4    0.07       0  5070.6    0.07       0  5076.0    0.07       0
Bank Sta=5070.6,5076
Exp/Cntr=0.3,0.1

Type RM Length L Ch R = 1,7163,309,309,309
BEGIN DESCRIPTION:
Mapping XS f599a546
END DESCRIPTION:
XS GIS Cut Line= 4
      1496597.74      6816043.84      1496767.00      6816246.95
      1497071.69      6816530.80      1497351.46      6816600.75
#Sta/Elev= 30
  4715.6 2012.20  4752.0 2011.33  4794.9 2004.81  4844.4 2000.21  4887.3 1985.08
  4901.7 1982.67  4951.1 1979.64  4982.0 1981.08  5004.8 1977.80  5005.2 1977.30
  5010.2 1977.80  5029.0 1979.23  5043.2 1983.99  5106.7 1984.63  5135.0 1987.00
  5163.3 1986.81  5184.3 1982.90  5255.2 1983.34  5283.5 1988.77  5305.0 1988.42
  5340.2 1994.35  5347.0 1993.01  5395.3 2001.92  5430.8 1999.49  5446.5 1995.88
  5528.9 1990.14  5534.1 1991.91  5606.0 1995.28  5626.6 1999.15  5684.8 2001.53
#Mann=3,-1,0
  4715.6    0.07       0  5004.8    0.07       0  5010.2    0.07       0
Bank Sta=5004.8,5010.2
Exp/Cntr=0.3,0.1

Type RM Length L Ch R = 1,6854,238,238,238
BEGIN DESCRIPTION:
Mapping XS 686790f2
END DESCRIPTION:
XS GIS Cut Line= 5
      1495973.90      6816154.07      1496627.10      6816540.35
      1496998.19      6816509.97      1497061.13      6816551.20
      1497295.51      6816631.50
#Sta/Elev= 30
  4122.0 2002.81  4337.1 1987.63  4629.7 1985.46  4680.9 1983.54  4709.6 1980.42
  4739.0 1980.19  4783.8 1983.55  4898.8 1982.66  4928.9 1981.85  4960.8 1977.37
  4969.8 1976.42  4970.2 1975.92  4975.2 1976.42  5037.1 1980.61  5079.4 1985.78
  5229.9 1987.06  5272.1 1992.38  5278.1 1990.94  5293.2 1995.58  5308.3 1996.78
  5314.3 1995.36  5327.8 1999.17  5335.9 1996.20  5361.9 1999.21  5398.5 1990.80
  5406.5 1992.62  5438.2 1987.41  5455.8 1989.59  5461.0 1992.56  5576.2 1999.31
#Mann=5,-1,0
  4122.0    0.07       0  4960.8   0.035       0  4969.8   0.035       0
  4975.2   0.035       0  5037.1    0.07       0
Bank Sta=4969.8,4975.2
Exp/Cntr=0.3,0.1

Type RM Length L Ch R = 1,6616,680,680,680
BEGIN DESCRIPTION:
Mapping XS f1402d9a
END DESCRIPTION:
XS GIS Cut Line= 4
      1495945.68      6816181.42      1496609.74      6816591.57
      1496800.71      6816849.81      1496787.69      6817218.79
#Sta/Elev= 30
  4010.8 2001.02  4045.3 2000.83  4161.5 1991.76  4167.4 1990.16  4246.6 1986.64
  4545.7 1985.12  4609.5 1983.65  4646.2 1978.77  4698.2 1981.18  4785.6 1982.02
  4849.1 1980.73  4892.6 1976.23  4972.0 1977.35  4983.7 1976.39  5019.3 1975.38
  5019.8 1974.88  5024.8 1975.38  5057.6 1978.64  5063.8 1981.11  5072.2 1980.71
  5111.9 1991.10  5120.7 1990.44  5140.7 1983.87  5160.7 1980.58  5210.7 1979.78
  5250.8 1981.58  5270.8 1979.75  5350.8 1987.57  5390.9 1987.57  5481.7 1995.62
#Mann=4,-1,0
  4010.8    0.07       0  4983.7   0.035       0  5019.3   0.035       0
  5024.8   0.035       0
Bank Sta=5019.3,5024.8
Exp/Cntr=0.3,0.1