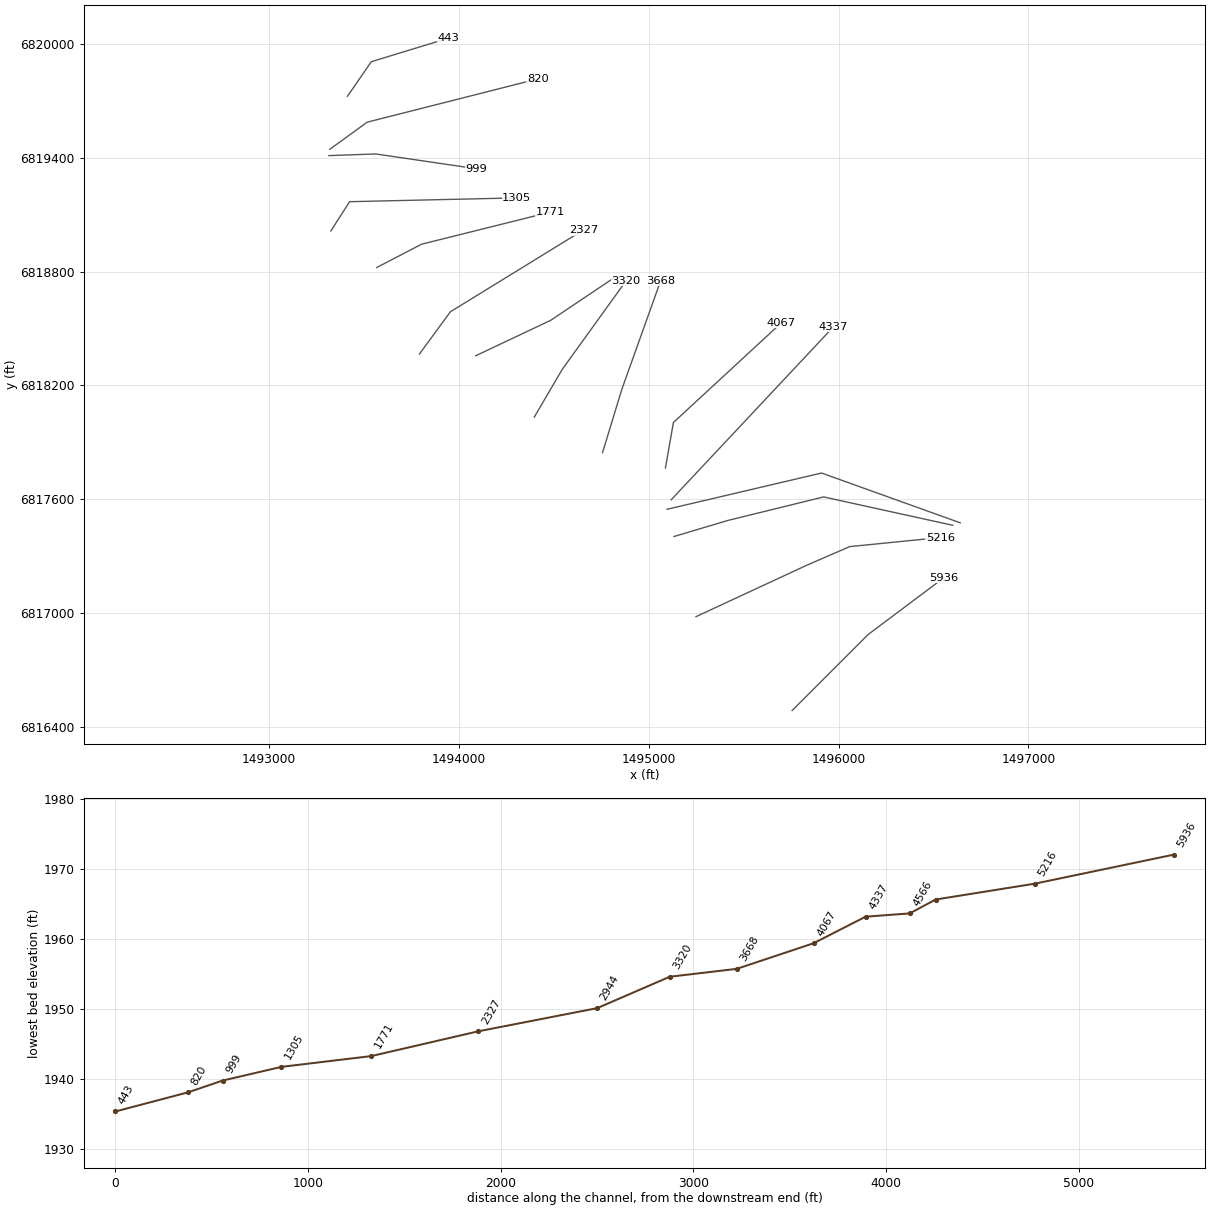
HEC-RAS study NUBIA CREEK TRIBUTARY 1_1.prj: NUBIA CREEK TRIBUTARY 1_1 Base Level Engineering

--- NUBIA CREEK TRIBUTARY 1_1.g01 (geometry) --- (continued)

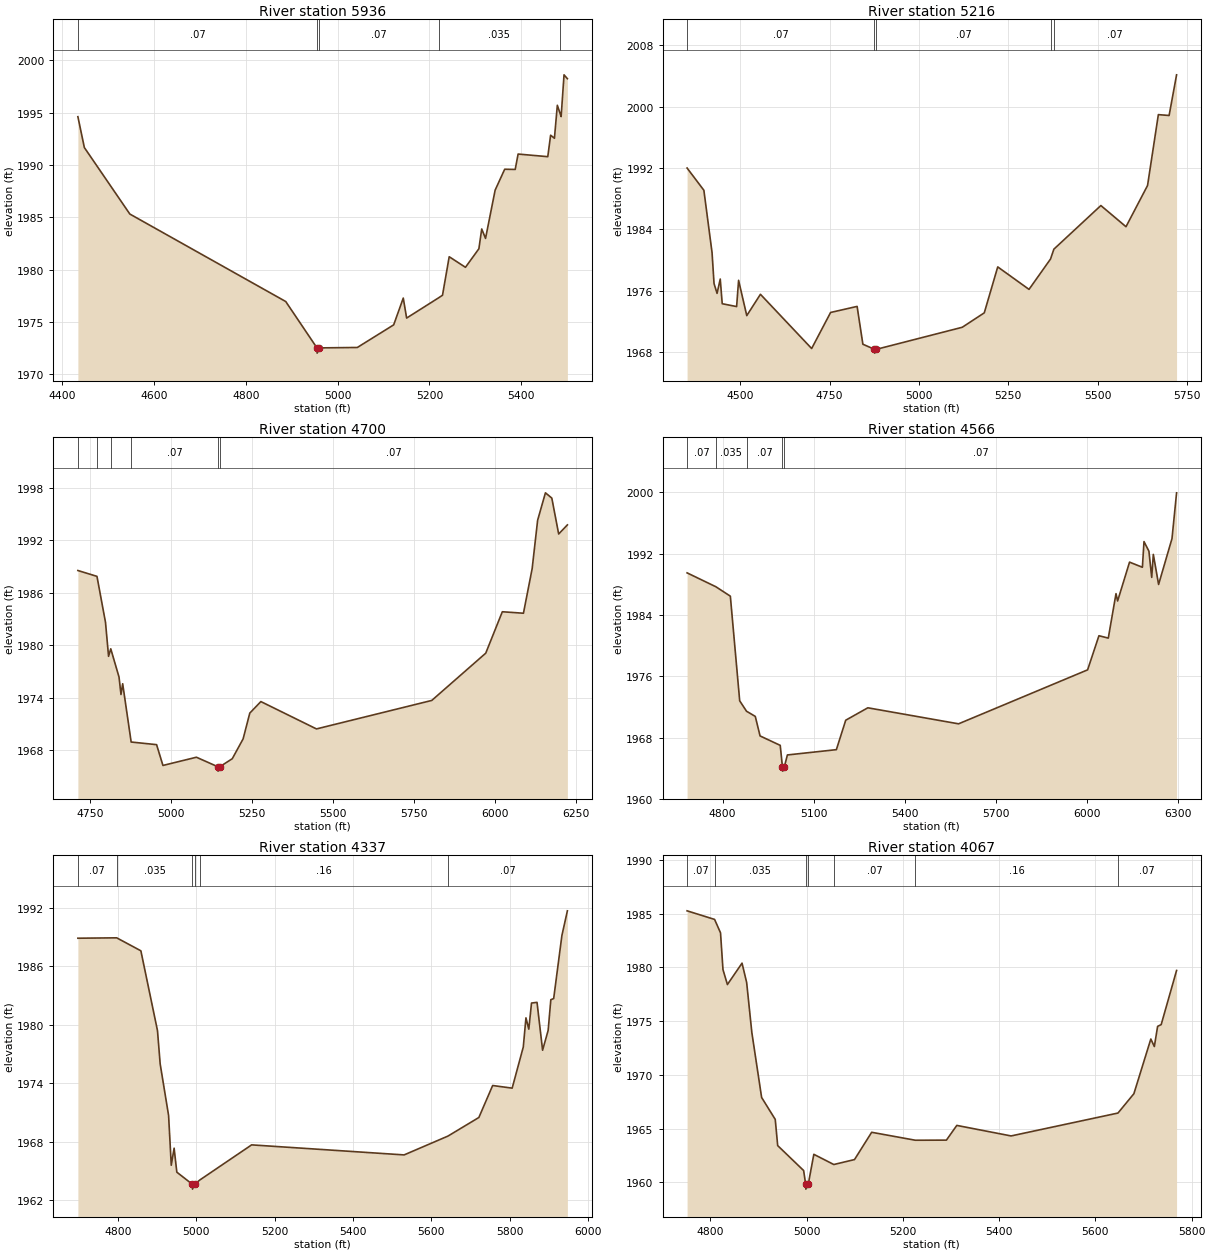
Type RM Length L Ch R = 1,5936,720,720,720
BEGIN DESCRIPTION:
NUBIA CREEK TRIBUTARY 1_1 12.0
END DESCRIPTION:
XS GIS Cut Line= 3
      1495755.01      6816488.01      1496155.00      6816888.00
      1496555.03      6817188.02
#Sta/Elev= 30
  4434.6 1994.60  4448.7 1991.65  4547.7 1985.30  4887.1 1976.94  4955.1 1972.51
  4955.5 1972.01  4960.6 1972.51  5043.0 1972.55  5122.1 1974.71  5143.0 1977.27
  5150.3 1975.36  5219.8 1977.29  5228.4 1977.54  5243.0 1981.22  5278.4 1980.21
  5307.6 1981.98  5313.8 1983.87  5322.1 1982.97  5343.0 1987.58  5363.8 1989.58
  5386.7 1989.56  5393.0 1991.03  5457.6 1990.78  5463.8 1992.83  5472.1 1992.54
  5478.4 1995.69  5484.5 1994.90  5486.7 1994.61  5493.0 1998.60  5500.3 1998.23
#Mann=5,-1,0
  4434.6    0.07       0  4955.1    0.07       0  4960.6    0.07       0
  5219.8   0.035       0  5484.5    0.07       0
Bank Sta=4955.1,4960.6
Exp/Cntr=0.3,0.1

Type RM Length L Ch R = 1,5216,516,516,516
BEGIN DESCRIPTION:
Mapping XS 98b9cfbc
END DESCRIPTION:
XS GIS Cut Line= 4
      1495248.92      6816982.47      1495828.32      6817251.55
      1496058.35      6817351.38      1496535.78      6817399.12
#Sta/Elev= 30
  4351.4 1992.00  4398.4 1989.10  4421.3 1980.96  4426.8 1976.94  4435.3 1975.66
  4444.2 1977.53  4449.7 1974.31  4490.0 1973.94  4495.5 1977.36  4518.4 1972.76
  4556.6 1975.54  4699.9 1968.47  4752.9 1973.17  4827.1 1973.96  4843.2 1969.03
  4875.6 1968.37  4876.0 1967.87  4881.2 1968.37  5121.2 1971.24  5182.8 1973.12
  5220.5 1979.11  5308.0 1976.18  5368.2 1980.14  5377.5 1981.42  5509.0 1987.11
  5579.3 1984.35  5639.6 1989.72  5669.8 1998.96  5699.9 1998.85  5720.8 2004.15
#Mann=5,-1,0
  4351.4    0.07       0  4875.6    0.07       0  4881.2    0.07       0
  5368.2   0.035       0  5377.5    0.07       0
Bank Sta=4875.6,4881.2
Exp/Cntr=0.3,0.1

Type RM Length L Ch R = 1,4700,134,134,134
BEGIN DESCRIPTION:
Mapping XS 7aea0bf4
END DESCRIPTION:
XS GIS Cut Line= 4
      1495133.29      6817404.77      1495417.54      6817489.40
      1495921.02      6817613.10      1496601.26      6817463.62
#Sta/Elev= 30
  4711.6 1988.56  4770.5 1987.89  4796.9 1982.62  4806.3 1978.74  4813.1 1979.60
  4838.6 1976.37  4844.7 1974.37  4849.9 1975.60  4876.1 1968.93  4954.6 1968.63
  4974.2 1966.25  5077.6 1967.19  5143.9 1966.10  5144.4 1965.60  5149.6 1966.10
  5188.3 1967.02  5221.8 1969.29  5242.4 1972.24  5276.6 1973.56  5448.3 1970.43
  5804.3 1973.69  5971.0 1979.10  6022.2 1983.84  6087.4 1983.67  6114.3 1988.77
  6131.2 1994.31  6155.3 1997.45  6175.0 1996.85  6196.2 1992.74  6223.1 1993.78
#Mann=6,-1,0
  4711.6   0.035       0  4770.5    0.07       0  4813.1   0.035       0
  4876.1    0.07       0  5143.9    0.07       0  5149.6    0.07       0
Bank Sta=5143.9,5149.6
Exp/Cntr=0.3,0.1

Type RM Length L Ch R = 1,4566,229,229,229
BEGIN DESCRIPTION:
Mapping XS c9c0d27f
END DESCRIPTION:
XS GIS Cut Line= 3
      1495096.32      6817547.98      1495910.17      6817738.96
      1496640.74      6817476.65
#Sta/Elev= 30
  4682.9 1989.48  4777.7 1987.67  4825.4 1986.44  4856.2 1972.79  4878.7 1971.43
  4907.5 1970.76  4923.3 1968.21  4989.7 1966.98  4997.1 1964.12  4997.6 1963.62
  5002.8 1964.12  5013.3 1965.73  5174.6 1966.42  5205.4 1970.26  5278.2 1971.88
  5577.1 1969.79  6002.1 1976.83  6039.4 1981.28  6070.2 1980.97  6095.6 1986.77
  6100.9 1985.81  6140.2 1990.88  6182.5 1990.21  6187.8 1993.56  6204.0 1992.31
  6213.2 1988.89  6218.5 1991.89  6235.9 1987.97  6280.0 1993.95  6295.1 1999.92
#Mann=5,-1,0
  4682.9    0.07       0  4777.7   0.035       0  4878.7    0.07       0
  4997.1    0.07       0  5002.8    0.07       0
Bank Sta=4997.1,5002.8
Exp/Cntr=0.3,0.1

Type RM Length L Ch R = 1,4337,270,270,270
BEGIN DESCRIPTION:
Mapping XS 2d7dc416
END DESCRIPTION:
XS GIS Cut Line= 2
      1495118.03      6817597.87      1495973.11      6818509.38
#Sta/Elev= 30
  4697.8 1988.89  4796.9 1988.93  4858.6 1987.60  4901.0 1979.42  4907.9 1975.99
  4929.4 1970.70  4936.2 1965.60  4943.5 1967.35  4950.4 1964.89  4990.0 1963.65
  4990.5 1963.15  4995.7 1963.65  5009.6 1964.10  5141.4 1967.69  5530.7 1966.66
  5642.6 1968.59  5721.6 1970.50  5756.8 1973.78  5806.6 1973.51  5835.0 1977.73
  5841.8 1980.72  5849.1 1979.56  5856.0 1982.24  5870.1 1982.31  5884.3 1977.40
  5898.5 1979.44  5905.3 1982.58  5912.6 1982.70  5933.6 1989.17  5947.6 1991.70
#Mann=6,-1,0
  4697.8    0.07       0  4796.9   0.035       0  4990.0   0.035       0
  4995.7   0.035       0  5009.6    0.16       0  5642.6    0.07       0
Bank Sta=4990,4995.7
Exp/Cntr=0.3,0.1

Type RM Length L Ch R = 1,4067,399,399,399
BEGIN DESCRIPTION:
NUBIA CREEK TRIBUTARY 1_1 8.0
END DESCRIPTION:
XS GIS Cut Line= 3
      1495087.82      6817765.47      1495129.85      6818005.03
      1495698.41      6818530.19
#Sta/Elev= 30
  4751.5 1985.26  4808.7 1984.46  4821.0 1983.21  4826.1 1979.79  4835.3 1978.40
  4865.7 1980.39  4875.3 1978.59  4886.1 1973.93  4906.4 1967.89  4934.7 1965.85
  4939.8 1963.41  4993.7 1961.09  4997.8 1959.86  4998.3 1959.36  5003.5 1959.86
  5014.9 1962.60  5056.4 1961.65  5099.4 1962.11  5135.1 1964.65  5225.8 1963.91
  5290.4 1963.92  5312.0 1965.29  5424.8 1964.31  5646.9 1966.44  5680.0 1968.24
  5715.2 1973.33  5722.5 1972.63  5729.3 1974.51  5736.7 1974.67  5768.7 1979.71
#Mann=7,-1,0
  4751.5    0.07       0  4808.7   0.035       0  4997.8   0.035       0
  5003.5   0.035       0  5056.4    0.07       0  5225.8    0.16       0
  5646.9    0.07       0
Bank Sta=4997.8,5003.5
Exp/Cntr=0.3,0.1

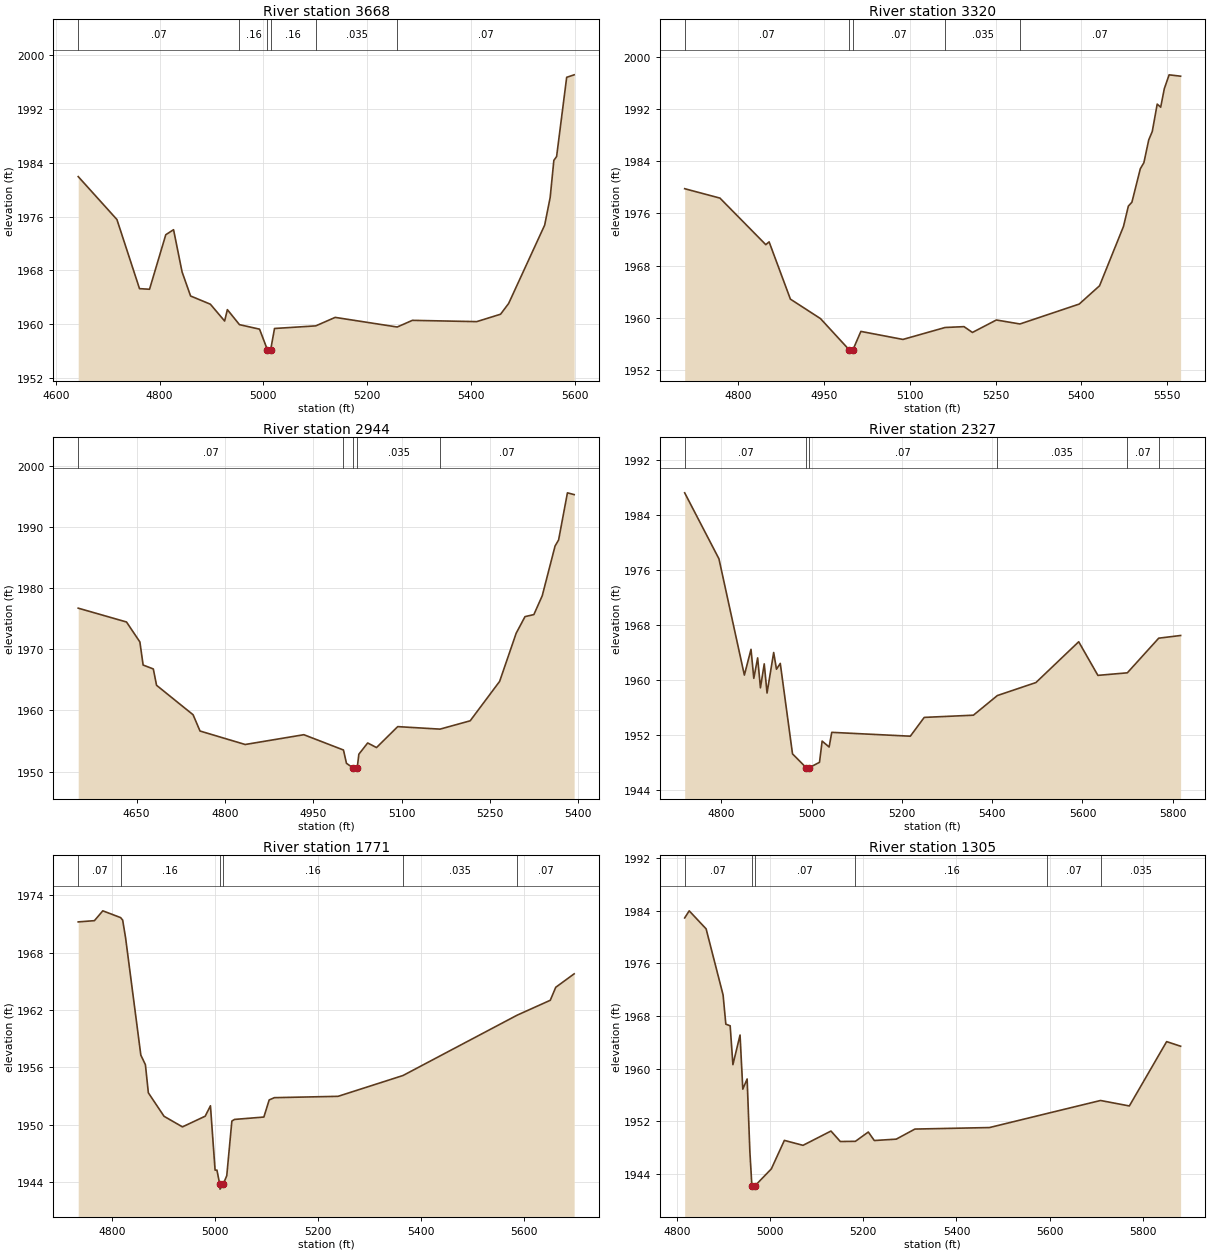
Type RM Length L Ch R = 1,3668,348,348,348
BEGIN DESCRIPTION:
Mapping XS 1385717e
END DESCRIPTION:
XS GIS Cut Line= 3
      1494756.58      6817846.60      1494858.58      6818180.81
      1495062.56      6818751.53
#Sta/Elev= 30
  4643.3 1981.93  4717.9 1975.55  4761.4 1965.28  4780.7 1965.19  4812.0 1973.29
  4827.0 1974.04  4843.4 1967.77  4859.8 1964.19  4897.9 1962.97  4925.4 1960.47
  4930.7 1962.16  4954.0 1959.93  4992.7 1959.26  5007.8 1956.20  5008.3 1955.70
  5014.1 1956.20  5021.5 1959.36  5101.0 1959.75  5138.4 1961.01  5257.9 1959.58
  5287.1 1960.57  5411.1 1960.38  5457.0 1961.48  5472.6 1963.08  5542.0 1974.72
  5552.6 1978.83  5559.7 1984.34  5565.0 1984.91  5584.4 1996.68  5598.8 1997.05
#Mann=6,-1,0
  4643.3    0.07       0  4954.0    0.16       0  5007.8    0.07       0
  5014.1    0.16       0  5101.0   0.035       0  5257.9    0.07       0
Bank Sta=5007.8,5014.1
Exp/Cntr=0.3,0.1

Type RM Length L Ch R = 1,3320,376,376,376
BEGIN DESCRIPTION:
Mapping XS 0fbe069b
END DESCRIPTION:
XS GIS Cut Line= 3
      1494396.83      6818033.27      1494544.43      6818285.04
      1494880.42      6818751.10
#Sta/Elev= 30
  4706.9 1979.78  4768.5 1978.34  4848.6 1971.20  4854.4 1971.63  4891.6 1962.85
  4944.2 1959.86  4994.4 1955.07  4994.9 1954.57  5000.8 1955.07  5014.7 1957.90
  5088.2 1956.67  5161.8 1958.50  5194.9 1958.63  5209.6 1957.74  5251.4 1959.65
  5292.6 1959.04  5396.1 1962.09  5431.7 1964.90  5473.5 1974.00  5482.0 1977.11
  5488.2 1977.71  5502.9 1982.84  5509.1 1983.76  5517.6 1987.26  5523.8 1988.56
  5532.4 1992.75  5538.5 1992.28  5544.8 1995.11  5553.2 1997.24  5573.3 1997.03
#Mann=5,-1,0
  4706.9    0.07       0  4994.4    0.07       0  5000.8    0.07       0
  5161.8   0.035       0  5292.6    0.07       0
Bank Sta=4994.4,5000.8
Exp/Cntr=0.3,0.1

Type RM Length L Ch R = 1,2944,617,617,617
BEGIN DESCRIPTION:
Mapping XS 3b28aa0d
END DESCRIPTION:
XS GIS Cut Line= 3
      1494088.71      6818356.66      1494483.66      6818543.29
      1494820.03      6818768.98
#Sta/Elev= 30
  4551.0 1976.71  4633.0 1974.45  4655.7 1971.19  4661.2 1967.42  4678.5 1966.78
  4684.0 1964.11  4746.0 1959.30  4757.8 1956.64  4834.5 1954.44  4934.0 1956.04
  5001.3 1953.54  5006.4 1951.36  5018.1 1950.59  5018.6 1950.09  5024.6 1950.59
  5027.4 1952.85  5042.4 1954.69  5057.4 1953.94  5093.4 1957.36  5165.2 1956.95
  5216.4 1958.31  5266.4 1964.75  5294.5 1972.62  5309.5 1975.33  5324.5 1975.66
  5338.7 1978.73  5360.5 1986.86  5366.5 1987.85  5381.5 1995.55  5392.9 1995.26
#Mann=5,-1,0
  4551.0    0.07       0  5001.3   0.035       0  5018.1    0.07       0
  5024.6   0.035       0  5165.2    0.07       0
Bank Sta=5018.1,5024.6
Exp/Cntr=0.3,0.1

Type RM Length L Ch R = 1,2327,556,556,556
BEGIN DESCRIPTION:
NUBIA CREEK TRIBUTARY 1_1 4.0
END DESCRIPTION:
XS GIS Cut Line= 3
      1493792.25      6818365.77      1493955.00      6818588.00
      1494655.96      6819018.98
#Sta/Elev= 30
  4719.1 1987.18  4795.0 1977.60  4851.3 1960.72  4866.0 1964.46  4872.2 1960.25
  4880.7 1963.22  4886.9 1958.87  4895.3 1962.35  4901.5 1958.12  4916.2 1964.00
  4922.4 1961.57  4930.8 1962.42  4957.9 1949.29  4988.2 1947.28  4988.7 1946.78
  4994.8 1947.28  5017.7 1948.06  5023.5 1951.14  5039.0 1950.28  5044.8 1952.41
  5218.8 1951.85  5249.6 1954.58  5358.5 1954.90  5411.5 1957.75  5497.0 1959.64
  5591.7 1965.56  5634.2 1960.68  5699.4 1961.05  5768.9 1966.08  5817.4 1966.47
#Mann=6,-1,0
  4719.1    0.07       0  4988.2    0.07       0  4994.8    0.07       0
  5411.5   0.035       0  5699.4    0.07       0  5768.9   0.035       0
Bank Sta=4988.2,4994.8
Exp/Cntr=0.3,0.1

Type RM Length L Ch R = 1,1771,466,466,466
BEGIN DESCRIPTION:
NUBIA CREEK TRIBUTARY 1_1 3.0
END DESCRIPTION:
XS GIS Cut Line= 3
      1493567.01      6818821.22      1493803.02      6818943.93
      1494480.06      6819112.85
#Sta/Elev= 30
  4734.0 1971.23  4765.5 1971.36  4781.8 1972.39  4816.4 1971.68  4820.4 1971.42
  4826.1 1969.55  4855.7 1957.28  4864.6 1956.27  4870.3 1953.33  4900.8 1950.87
  4936.6 1949.76  4980.8 1950.88  4991.0 1951.97  5000.0 1945.23  5003.6 1945.23
  5009.1 1943.74  5009.6 1943.24  5015.7 1943.74  5022.7 1944.65  5032.6 1950.37
  5037.8 1950.54  5094.8 1950.79  5105.1 1952.58  5115.2 1952.82  5239.0 1952.96
  5365.2 1955.14  5587.0 1961.46  5651.4 1963.02  5662.0 1964.38  5697.8 1965.79
#Mann=6,-1,0
  4734.0    0.07       0  4816.4    0.16       0  5009.1    0.07       0
  5015.7    0.16       0  5365.2   0.035       0  5587.0    0.07       0
Bank Sta=5009.1,5015.7
Exp/Cntr=0.3,0.1

Type RM Length L Ch R = 1,1305,306,306,306
BEGIN DESCRIPTION:
NUBIA CREEK TRIBUTARY 1_1 2.0
END DESCRIPTION:
XS GIS Cut Line= 3
      1493325.51      6819013.73      1493424.19      6819167.95
      1494304.96      6819188.00
#Sta/Elev= 30
  4816.9 1982.88  4826.6 1983.96  4862.9 1981.22  4899.3 1971.19  4905.2 1966.75
  4914.5 1966.50  4920.4 1960.60  4935.7 1965.10  4941.6 1956.88  4950.9 1958.43
  4956.8 1947.37  4961.1 1942.20  4961.6 1941.70  4967.7 1942.20  5002.9 1944.78
  5030.8 1949.10  5070.8 1948.35  5130.8 1950.52  5150.8 1948.93  5183.2 1948.96
  5210.9 1950.37  5223.8 1949.08  5270.9 1949.29  5310.9 1950.82  5470.9 1951.05
  5595.3 1953.20  5709.2 1955.16  5771.0 1954.33  5851.0 1964.10  5881.0 1963.40
#Mann=6,-1,0
  4816.9    0.07       0  4961.1    0.07       0  4967.7    0.07       0
  5183.2    0.16       0  5595.3    0.07       0  5709.2   0.035       0
Bank Sta=4961.1,4967.7
Exp/Cntr=0.3,0.1

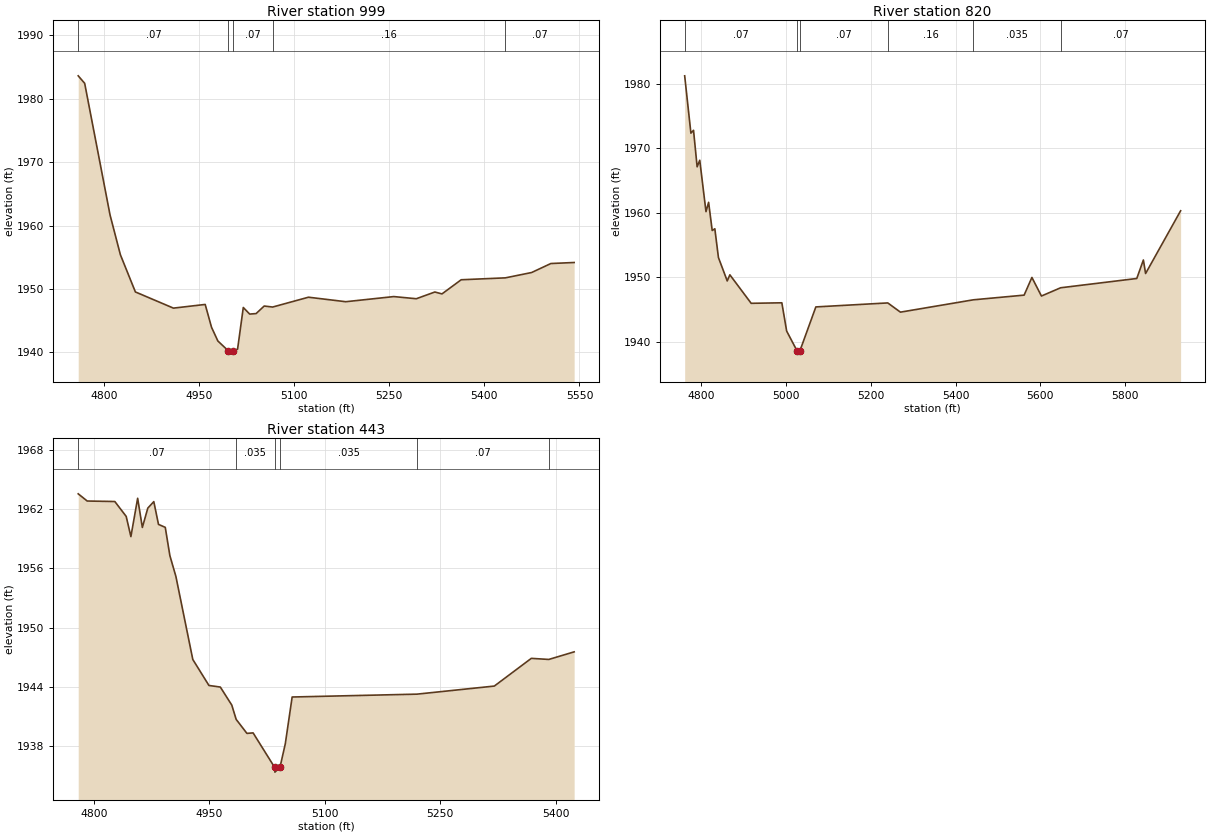
Type RM Length L Ch R = 1,999,179,179,179
BEGIN DESCRIPTION:
Mapping XS 3177ae68
END DESCRIPTION:
XS GIS Cut Line= 3
      1493314.86      6819410.62      1493562.22      6819419.30
      1494091.34      6819341.70
#Sta/Elev= 30
  4759.3 1983.60  4769.5 1982.42  4809.5 1961.68  4825.8 1955.41  4849.5 1949.54
  4909.5 1946.99  4959.6 1947.57  4969.6 1943.97  4979.6 1941.81  4996.3 1940.24
  4996.8 1939.74  5002.4 1939.74  5002.9 1940.24  5010.7 1940.53  5019.7 1947.09
  5029.8 1946.05  5039.9 1946.13  5052.7 1947.32  5066.0 1947.16  5122.5 1948.71
  5181.4 1948.00  5257.1 1948.81  5292.6 1948.47  5321.9 1949.53  5333.1 1949.23
  5363.4 1951.46  5433.1 1951.76  5474.5 1952.60  5504.9 1954.02  5541.6 1954.18
#Mann=5,-1,0
  4759.3    0.07       0  4996.3    0.07       0  5002.9    0.07       0
  5066.0    0.16       0  5433.1    0.07       0
Bank Sta=4996.3,5002.9
Exp/Cntr=0.3,0.1

Type RM Length L Ch R = 1,820,377,377,377
BEGIN DESCRIPTION:
Mapping XS 963e0eb2
END DESCRIPTION:
XS GIS Cut Line= 3
      1493319.30      6819443.48      1493516.80      6819586.71
      1494415.28      6819814.59
#Sta/Elev= 30
  4760.5 1981.22  4775.2 1972.33  4781.4 1972.77  4789.9 1967.11  4796.1 1968.13
  4810.8 1960.16  4817.0 1961.60  4825.5 1957.23  4831.7 1957.50  4840.2 1953.04
  4861.0 1949.41  4867.2 1950.36  4917.5 1945.94  4989.9 1946.02  5001.3 1941.63
  5025.9 1938.56  5026.4 1938.06  5032.5 1938.56  5070.2 1945.38  5240.0 1946.00
  5269.9 1944.57  5441.8 1946.48  5561.9 1947.21  5580.3 1949.95  5602.8 1947.07
  5648.1 1948.35  5827.9 1949.79  5843.5 1952.66  5848.7 1950.56  5931.4 1960.29
#Mann=6,-1,0
  4760.5    0.07       0  5025.9    0.07       0  5032.5    0.07       0
  5240.0    0.16       0  5441.8   0.035       0  5648.1    0.07       0
Bank Sta=5025.9,5032.5
Exp/Cntr=0.3,0.1

Type RM Length L Ch R = 1,443,0,0,0
BEGIN DESCRIPTION:
NUBIA CREEK TRIBUTARY 1_1 1.0
END DESCRIPTION:
XS GIS Cut Line= 3
      1493413.27      6819723.46      1493538.55      6819905.15
      1493944.27      6820028.98
#Sta/Elev= 30
  4779.3 1963.56  4791.0 1962.83  4826.9 1962.78  4841.7 1961.27  4847.8 1959.22
  4856.6 1963.11  4862.7 1960.15  4869.8 1962.11  4877.6 1962.77  4883.7 1960.46
  4892.5 1960.16  4898.5 1957.29  4906.3 1955.19  4928.3 1946.76  4949.3 1944.12
  4964.1 1943.96  4979.0 1942.13  4984.7 1940.68  4998.7 1939.26  5006.7 1939.31
  5034.6 1935.83  5035.1 1935.33  5041.7 1935.83  5048.6 1938.21  5057.5 1942.95
  5219.8 1943.24  5320.4 1944.06  5368.5 1946.87  5391.2 1946.76  5424.2 1947.53
#Mann=6,-1,0
  4779.3    0.07       0  4984.7   0.035       0  5034.6   0.035       0
  5041.7   0.035       0  5219.8    0.07       0  5391.2   0.035       0
Bank Sta=5034.6,5041.7
Exp/Cntr=0.3,0.1

Chan Stop Cuts=-1