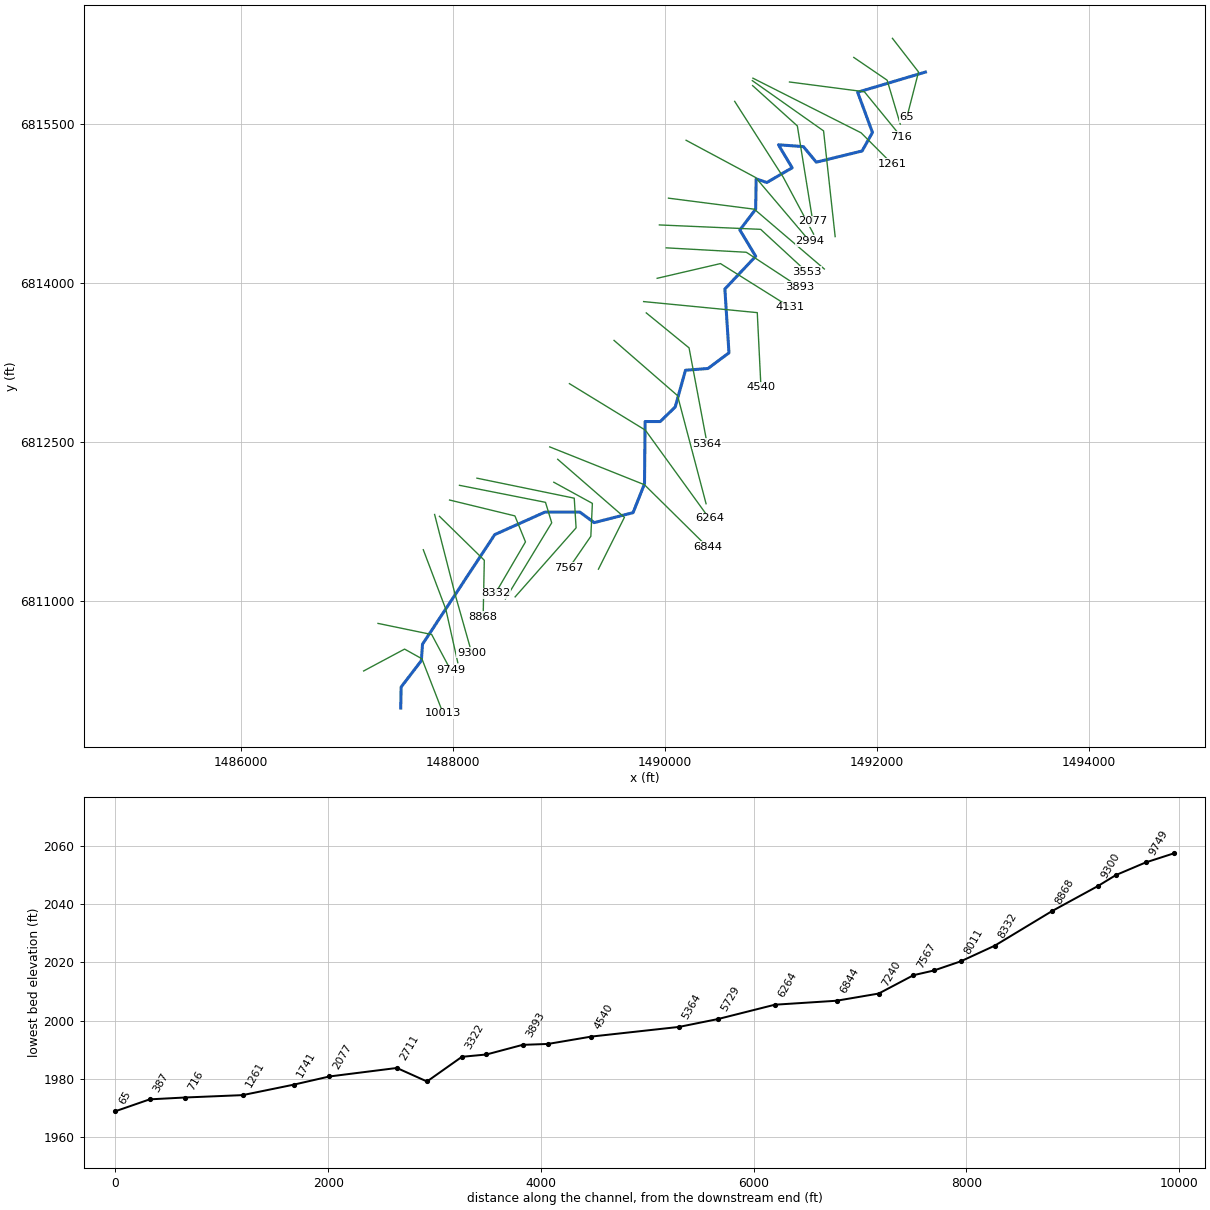
--- NUBIA CREEK TRIBUTARY 1_2.prj (project) ---

Proj Title=NUBIA CREEK TRIBUTARY 1_2 Base Level Engineering
Current Plan=p01
Default Exp/Contr=0.3,0.1
English Units
Geom File=g01
Flow File=f01
Plan File=p01
Y Axis Title=Elevation
X Axis Title(PF)=Main Channel Distance
X Axis Title(XS)=Station
BEGIN DESCRIPTION:
NUBIA CREEK TRIBUTARY 1_2
END DESCRIPTION:
DSS Export Rating Curves= 0
DSS Export Rating Curve Sorted= 0
DSS Export Volume Flow Curves= 0
DXF OffsetX= 0
DXF OffsetY= 0
DXF ScaleX= 1
DXF ScaleY= 10

--- NUBIA CREEK TRIBUTARY 1_2.p01 (plan) ---

Plan Title=Multiple Run
Short Identifier=Multiple
Geom File=g01
Flow File=f01
Subcritical Flow
K Sum by GR= 0
Std Step Tol= 0.01
Critical Tol= 0.01
Num of Std Step Trials= 20
Max Error Tol= 0.3
Flow Tol Ratio= 0.001
Split Flow NTrial= 30
Split Flow Tol= 0.02
Split Flow Ratio= 0.02
Log Output Level= 0
Friction Slope Method= 1
Unsteady Friction Slope Method= 2
Unsteady Bridges Friction Slope Method= 1
Parabolic Critical Depth
Global Vel Dist=  1 , 1 , 1
Global Log Level= 0
CheckData=True
Encroach Param= -1, 0, 0, 0
BEGIN DESCRIPTION:
Multiple Run
END DESCRIPTION:

--- NUBIA CREEK TRIBUTARY 1_2.f01 (steady flow) ---

Flow Title=Multiple
Program Version=4.10
Number of Profiles= 7
Profile Names=10-year,25-year,50-year,1pct_min,100-year,1pct_plu,500-year
River Rch & RM=NUBIA CREEK TRIB,Reach-1         ,10013
     236     326     399     244     487     971     731
River Rch & RM=NUBIA CREEK TRIB,Reach-1         ,4131
     293     409     505     311     620    1237     943
Boundary for River Rch & Prof#=NUBIA CREEK TRIB,Reach-1         , 1
Up Type= 0
Dn Type= 3
Dn Slope=0.00715
Boundary for River Rch & Prof#=NUBIA CREEK TRIB,Reach-1         , 2
Up Type= 0
Dn Type= 3
Dn Slope=0.00715
Boundary for River Rch & Prof#=NUBIA CREEK TRIB,Reach-1         , 3
Up Type= 0
Dn Type= 3
Dn Slope=0.00715
Boundary for River Rch & Prof#=NUBIA CREEK TRIB,Reach-1         , 4
Up Type= 0
Dn Type= 3
Dn Slope=0.00715
Boundary for River Rch & Prof#=NUBIA CREEK TRIB,Reach-1         , 5
Up Type= 0
Dn Type= 3
Dn Slope=0.00715
Boundary for River Rch & Prof#=NUBIA CREEK TRIB,Reach-1         , 6
Up Type= 0
Dn Type= 3
Dn Slope=0.00715
Boundary for River Rch & Prof#=NUBIA CREEK TRIB,Reach-1         , 7
Up Type= 0
Dn Type= 3
Dn Slope=0.00715
DSS Import GetInterval= 0
DSS Import GetPeak= 0
DSS Import FillOption= 0

--- NUBIA CREEK TRIBUTARY 1_2.g01 (geometry) ---

Geom Title=Existing Conditions

River Reach=NUBIA CREEK TRIB,Reach-1
Reach XY= 30
      1487505.00      6809988.00      1487508.62      6810186.50
      1487699.52      6810435.56      1487710.48      6810590.44
      1488391.76      6811624.39      1488865.50      6811836.78
      1489194.56      6811836.94      1489329.96      6811737.51
      1489697.00      6811831.61      1489804.61      6812103.28
      1489810.46      6812691.01      1489953.35      6812691.16
      1490094.24      6812828.32      1490191.26      6813174.80
      1490403.53      6813191.55      1490601.55      6813339.25
      1490562.82      6813941.41      1490853.86      6814250.04
      1490704.16      6814498.06      1490853.34      6814694.05
      1490858.08      6814980.43      1490958.27      6814946.11
      1491197.42      6815084.65      1491068.10      6815302.03
      1491303.75      6815284.54      1491424.95      6815137.74
      1491857.47      6815243.45      1491955.10      6815417.90
      1491815.19      6815797.73      1492455.00      6815988.00

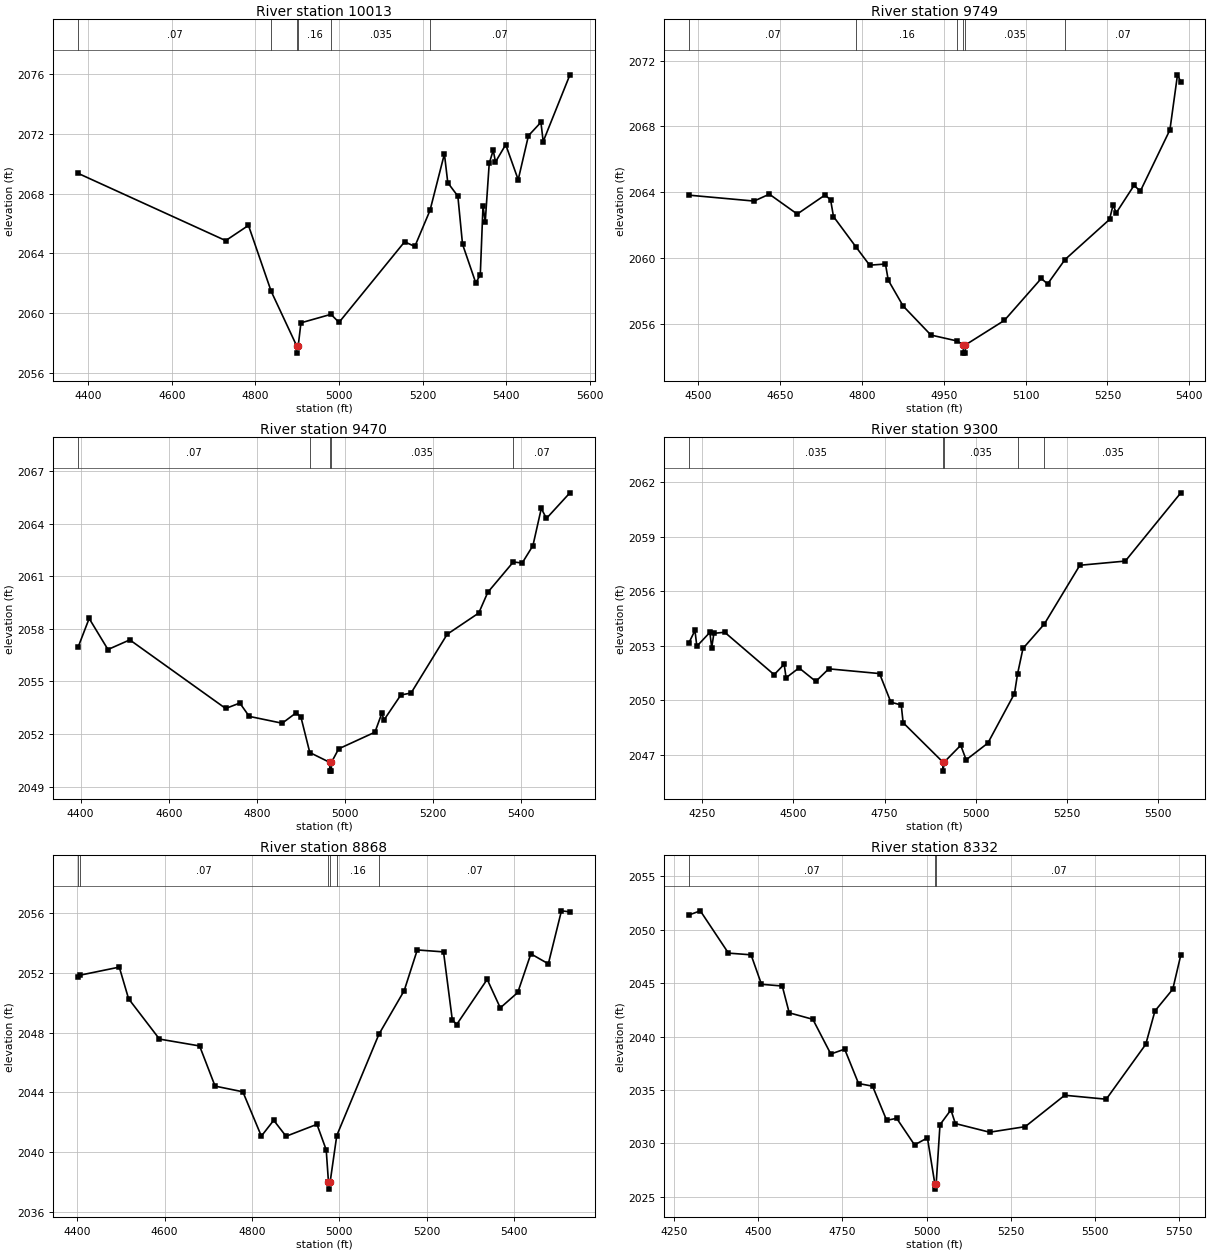
Type RM Length L Ch R = 1,10013,264,264,264
BEGIN DESCRIPTION:
NUBIA CREEK TRIBUTARY 1_2 17.0
END DESCRIPTION:
XS GIS Cut Line= 4
      1487155.04      6810338.02      1487541.29      6810544.31
      1487704.60      6810453.17      1487905.01      6809937.97
#Sta/Elev= 30
  4375.1 2069.36  4728.7 2064.85  4783.2 2065.87  4837.6 2061.45  4898.4 2057.81
  4898.7 2057.31  4902.4 2057.81  4908.8 2059.34  4980.7 2059.91  5000.0 2059.37
  5157.0 2064.77  5181.5 2064.46  5217.9 2066.88  5252.3 2070.66  5260.4 2068.73
  5284.5 2067.83  5295.7 2064.61  5327.4 2062.02  5338.2 2062.55  5344.7 2067.17
  5350.1 2066.12  5359.6 2070.02  5369.2 2070.91  5374.6 2070.12  5399.1 2071.28
  5429.0 2068.93  5453.5 2071.88  5483.4 2072.78  5488.8 2071.49  5552.8 2075.96
#Mann=6,-1,0
  4375.1    0.07       0  4837.6    0.16       0  4898.4   0.035       0
  4902.4    0.16       0  4980.7   0.035       0  5217.9    0.07       0
Bank Sta=4898.4,4902.4
Exp/Cntr=0.3,0.1

Type RM Length L Ch R = 1,9749,279,279,279
BEGIN DESCRIPTION:
NUBIA CREEK TRIBUTARY 1_2 16.0
END DESCRIPTION:
XS GIS Cut Line= 3
      1487290.67      6810786.71      1487796.84      6810681.95
      1487977.93      6810342.65
#Sta/Elev= 30
  4483.1 2063.81  4602.5 2063.45  4630.5 2063.87  4681.6 2062.66  4732.6 2063.82
  4742.8 2063.52  4748.0 2062.51  4789.0 2060.67  4814.3 2059.55  4843.3 2059.62
  4848.4 2058.64  4875.6 2057.07  4926.6 2055.30  4974.5 2054.94  4985.9 2054.70
  4986.2 2054.20  4989.7 2054.20  4989.9 2054.70  5061.2 2056.19  5128.8 2058.74
  5140.5 2058.41  5172.3 2059.89  5253.9 2062.33  5260.5 2063.21  5266.2 2062.73
  5298.8 2064.40  5310.5 2064.06  5364.6 2067.78  5378.5 2071.13  5384.6 2070.70
#Mann=6,-1,0
  4483.1    0.07       0  4789.0    0.16       0  4974.5   0.035       0
  4985.9   0.035       0  4989.9   0.035       0  5172.3    0.07       0
Bank Sta=4985.9,4989.9
Exp/Cntr=0.3,0.1

Type RM Length L Ch R = 1,9470,170,170,170
BEGIN DESCRIPTION:
Mapping XS 54149327
END DESCRIPTION:
XS GIS Cut Line= 3
      1487717.88      6811481.63      1487930.57      6810919.53
      1488043.42      6810416.01
#Sta/Elev= 30
  4394.0 2056.94  4419.3 2058.59  4462.0 2056.82  4511.6 2057.37  4729.3 2053.46
  4761.4 2053.77  4782.8 2053.01  4857.6 2052.62  4889.7 2053.22  4900.4 2052.95
  4920.3 2050.95  4965.5 2050.39  4965.8 2049.89  4969.3 2049.89  4969.5 2050.39
  4985.9 2051.16  5068.3 2052.11  5083.8 2053.18  5088.9 2052.81  5127.1 2054.23
  5150.3 2054.34  5232.3 2057.69  5304.0 2058.90  5324.5 2060.08  5382.5 2061.81
  5402.6 2061.75  5427.0 2062.74  5446.0 2064.86  5457.7 2064.29  5511.0 2065.75
#Mann=5,-1,0
  4394.0    0.07       0  4920.3   0.035       0  4965.5   0.035       0
  4969.5   0.035       0  5382.5    0.07       0
Bank Sta=4965.5,4969.5
Exp/Cntr=0.3,0.1

Type RM Length L Ch R = 1,9300,432,432,432
BEGIN DESCRIPTION:
Mapping XS c7f7253d
END DESCRIPTION:
XS GIS Cut Line= 3
      1487824.67      6811814.33      1488017.81      6811061.31
      1488173.64      6810511.56
#Sta/Elev= 30
  4213.5 2053.16  4230.1 2053.84  4235.2 2052.97  4270.9 2053.73  4276.0 2052.90
  4282.0 2053.68  4311.6 2053.74  4447.2 2051.41  4474.7 2051.98  4479.9 2051.24
  4515.5 2051.78  4561.4 2051.04  4597.0 2051.73  4736.2 2051.47  4767.2 2049.90
  4795.7 2049.74  4800.9 2048.77  4909.7 2046.61  4910.0 2046.11  4913.7 2046.61
  4958.8 2047.53  4973.7 2046.73  5033.2 2047.65  5106.2 2050.37  5114.6 2051.45
  5129.5 2052.85  5188.0 2054.19  5285.4 2057.42  5410.1 2057.65  5562.3 2061.40
#Mann=5,-1,0
  4213.5   0.035       0  4909.7   0.035       0  4913.7   0.035       0
  5114.6    0.16       0  5188.0   0.035       0
Bank Sta=4909.7,4913.7
Exp/Cntr=0.3,0.1

Type RM Length L Ch R = 1,8868,536,536,536
BEGIN DESCRIPTION:
Mapping XS 17e9a471
END DESCRIPTION:
XS GIS Cut Line= 3
      1487870.26      6811796.96      1488293.41      6811382.49
      1488282.56      6810848.62
#Sta/Elev= 30
  4401.9 2051.75  4406.5 2051.85  4496.4 2052.39  4517.7 2050.27  4588.4 2047.57
  4680.3 2047.11  4715.7 2044.42  4779.3 2044.04  4821.7 2041.07  4850.0 2042.13
  4878.3 2041.06  4949.0 2041.86  4970.2 2040.15  4975.3 2038.02  4975.6 2037.52
  4979.3 2038.02  4994.4 2041.11  5091.0 2047.90  5148.7 2050.81  5178.7 2053.54
  5238.8 2053.41  5258.8 2048.88  5268.8 2048.54  5338.8 2051.57  5368.8 2049.66
  5408.8 2050.69  5438.8 2053.28  5478.8 2052.61  5508.8 2056.16  5528.2 2056.09
#Mann=6,-1,0
  4401.9   0.035       0  4406.5    0.07       0  4975.3    0.07       0
  4979.3    0.07       0  4994.4    0.16       0  5091.0    0.07       0
Bank Sta=4975.3,4979.3
Exp/Cntr=0.3,0.1

Type RM Length L Ch R = 1,8332,321,321,321
BEGIN DESCRIPTION:
Mapping XS fe12a445
END DESCRIPTION:
XS GIS Cut Line= 4
      1487965.73      6811950.63      1488582.04      6811800.89
      1488681.87      6811555.67      1488398.56      6811071.24
#Sta/Elev= 30
  4294.2 2051.39  4328.0 2051.78  4411.5 2047.82  4478.7 2047.66  4509.6 2044.90
  4571.3 2044.74  4591.9 2042.23  4662.1 2041.62  4715.4 2038.37  4756.5 2038.83
  4797.7 2035.61  4839.4 2035.36  4881.2 2032.16  4910.9 2032.35  4964.0 2029.86
  5002.2 2030.52  5024.2 2026.22  5024.5 2025.72  5028.2 2026.22  5039.5 2031.75
  5071.9 2033.14  5085.1 2031.86  5186.8 2031.05  5292.5 2031.57  5409.8 2034.51
  5533.0 2034.14  5650.3 2039.28  5677.6 2042.40  5730.5 2044.44  5754.4 2047.65
#Mann=3,-1,0
  4294.2    0.07       0  5024.2    0.07       0  5028.2    0.07       0
Bank Sta=5024.2,5028.2
Exp/Cntr=0.3,0.1

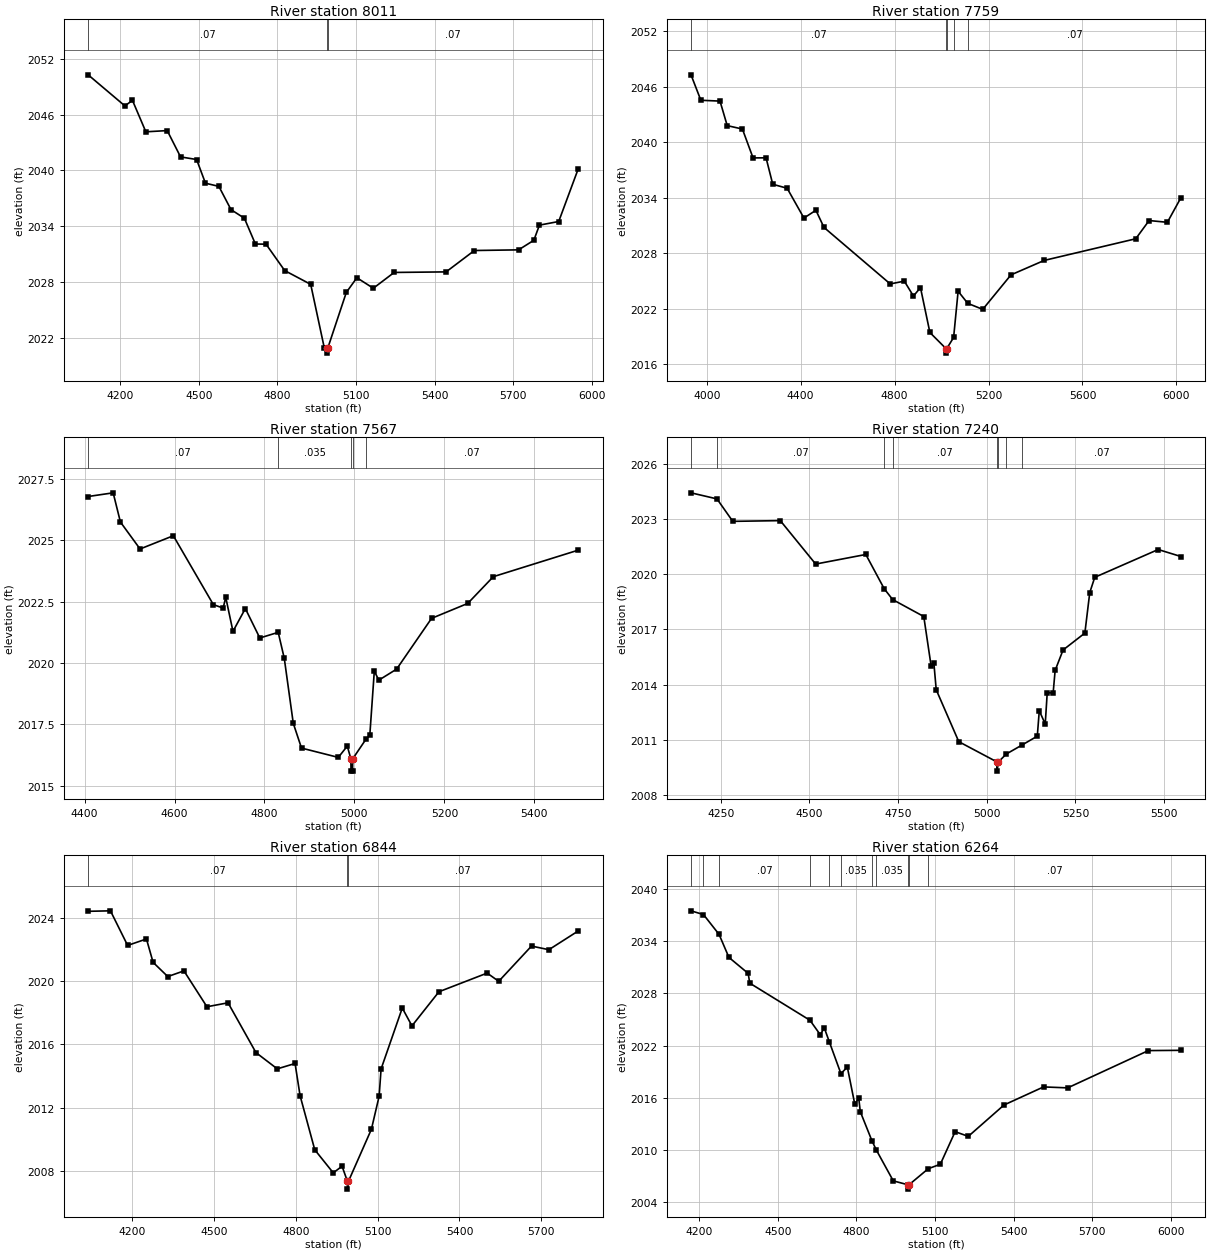
Type RM Length L Ch R = 1,8011,252,252,252
BEGIN DESCRIPTION:
Mapping XS 405ebde4
END DESCRIPTION:
XS GIS Cut Line= 4
      1488059.08      6812089.51      1488870.67      6811928.93
      1488929.26      6811735.79      1488493.09      6811017.51
#Sta/Elev= 30
  4078.1 2050.27  4218.2 2046.93  4247.2 2047.52  4298.2 2044.14  4379.8 2044.27
  4430.7 2041.44  4491.9 2041.16  4525.7 2038.61  4576.9 2038.27  4623.1 2035.77
  4674.3 2034.84  4716.2 2032.07  4756.9 2032.05  4828.1 2029.21  4927.3 2027.73
  4979.5 2020.85  4988.0 2020.83  4988.2 2020.33  4992.0 2020.83  5063.2 2026.86
  5103.5 2028.44  5166.3 2027.31  5245.8 2029.01  5444.0 2029.07  5552.0 2031.37
  5720.6 2031.44  5778.8 2032.47  5800.1 2034.10  5873.7 2034.49  5947.6 2040.11
#Mann=3,-1,0
  4078.1    0.07       0  4988.0    0.07       0  4992.0    0.07       0
Bank Sta=4988,4992
Exp/Cntr=0.3,0.1

Type RM Length L Ch R = 1,7759,192,192,192
BEGIN DESCRIPTION:
Mapping XS ec1579f7
END DESCRIPTION:
XS GIS Cut Line= 4
      1488223.99      6812156.79      1489141.94      6811967.99
      1489159.30      6811688.04      1488584.22      6811037.01
#Sta/Elev= 30
  3933.0 2047.28  3974.9 2044.53  4056.5 2044.44  4087.2 2041.79  4151.9 2041.42
  4197.2 2038.30  4252.6 2038.31  4281.1 2035.45  4342.4 2035.02  4413.9 2031.80
  4464.9 2032.64  4499.2 2030.79  4781.4 2024.68  4841.4 2024.98  4880.2 2023.37
  4910.2 2024.28  4950.3 2019.43  5018.4 2017.70  5018.7 2017.20  5022.4 2017.70
  5051.3 2018.89  5070.5 2023.89  5111.5 2022.58  5175.3 2021.93  5295.7 2025.66
  5437.1 2027.22  5826.9 2029.56  5883.8 2031.53  5961.6 2031.34  6019.3 2034.00
#Mann=5,-1,0
  3933.0    0.07       0  5018.4    0.07       0  5022.4    0.07       0
  5051.3   0.035       0  5111.5    0.07       0
Bank Sta=5018.4,5022.4
Exp/Cntr=0.3,0.1

Type RM Length L Ch R = 1,7567,327,327,327
BEGIN DESCRIPTION:
Mapping XS 1cd80b58
END DESCRIPTION:
XS GIS Cut Line= 4
      1488948.96      6812118.52      1489312.94      6811918.95
      1489298.34      6811608.54      1489092.19      6811309.09
#Sta/Elev= 30
  4407.9 2026.79  4463.5 2026.94  4479.6 2025.75  4523.3 2024.65  4597.3 2025.19
  4686.3 2022.38  4708.1 2022.24  4713.8 2022.68  4729.9 2021.29  4757.4 2022.22
  4789.6 2021.02  4830.5 2021.25  4844.0 2020.19  4864.0 2017.54  4882.3 2016.53
  4964.1 2016.15  4984.1 2016.61  4992.1 2016.09  4992.4 2015.59  4995.9 2015.59
  4996.1 2016.09  5025.2 2016.88  5034.2 2017.06  5044.2 2019.67  5054.2 2019.30
  5093.8 2019.75  5171.5 2021.82  5252.0 2022.43  5308.8 2023.52  5497.3 2024.60
#Mann=5,-1,0
  4407.9    0.07       0  4830.5   0.035       0  4992.1   0.035       0
  4996.1   0.035       0  5025.2    0.07       0
Bank Sta=4992.1,4996.1
Exp/Cntr=0.3,0.1

Type RM Length L Ch R = 1,7240,396,396,396
BEGIN DESCRIPTION:
Mapping XS 425242af
END DESCRIPTION:
XS GIS Cut Line= 3
      1488986.16      6812334.71      1489615.25      6811787.48
      1489369.96      6811298.23
#Sta/Elev= 30
  4166.2 2024.42  4239.4 2024.09  4284.0 2022.87  4417.9 2022.91  4517.6 2020.55
  4659.0 2021.07  4710.8 2019.21  4734.7 2018.62  4822.4 2017.70  4843.2 2015.00
  4850.9 2015.16  4857.5 2013.72  4921.1 2010.90  5028.7 2009.80  5029.0 2009.30
  5032.7 2009.80  5055.1 2010.23  5099.5 2010.72  5142.4 2011.20  5148.0 2012.58
  5164.8 2011.86  5170.4 2013.56  5187.1 2013.55  5192.7 2014.77  5215.0 2015.88
  5276.5 2016.80  5290.3 2019.00  5304.4 2019.83  5483.2 2021.34  5547.3 2020.96
#Mann=8,-1,0
  4166.2   0.035       0  4239.4    0.07       0  4710.8   0.035       0
  4734.7    0.07       0  5028.7    0.07       0  5032.7    0.07       0
  5055.1   0.035       0  5099.5    0.07       0
Bank Sta=5028.7,5032.7
Exp/Cntr=0.3,0.1

Type RM Length L Ch R = 1,6844,580,580,580
BEGIN DESCRIPTION:
Mapping XS 85b315ad
END DESCRIPTION:
XS GIS Cut Line= 3
      1488910.63      6812451.92      1489803.83      6812095.16
      1490397.58      6811509.22
#Sta/Elev= 30
  4038.9 2024.42  4120.6 2024.45  4183.6 2022.26  4252.6 2022.67  4276.9 2021.19
  4330.8 2020.29  4390.0 2020.65  4474.3 2018.38  4551.7 2018.63  4654.0 2015.48
  4732.2 2014.45  4797.4 2014.79  4815.7 2012.76  4869.6 2009.33  4937.4 2007.87
  4969.7 2008.29  4989.2 2007.34  4989.5 2006.84  4993.2 2007.34  5077.3 2010.63
  5105.6 2012.72  5112.7 2014.44  5190.4 2018.30  5225.9 2017.17  5324.9 2019.33
  5501.6 2020.51  5544.0 2019.99  5664.2 2022.22  5727.9 2021.99  5834.9 2023.17
#Mann=3,-1,0
  4038.9    0.07       0  4989.2    0.07       0  4993.2    0.07       0
Bank Sta=4989.2,4993.2
Exp/Cntr=0.3,0.1

Type RM Length L Ch R = 1,6264,535,535,535
BEGIN DESCRIPTION:
Mapping XS f4c479eb
END DESCRIPTION:
XS GIS Cut Line= 3
      1489096.48      6813048.39      1489812.62      6812610.03
      1490415.89      6811776.73
#Sta/Elev= 30
  4169.3 2037.50  4216.9 2037.07  4276.3 2034.79  4313.9 2032.14  4387.4 2030.30
  4393.3 2029.18  4622.9 2024.91  4662.2 2023.25  4677.6 2024.03  4696.9 2022.42
  4741.0 2018.77  4765.5 2019.52  4793.7 2015.28  4809.1 2015.91  4815.0 2014.39
  4859.1 2011.06  4876.4 2009.96  4940.7 2006.43  4996.7 2005.98  4997.0 2005.48
  5000.7 2005.98  5074.1 2007.83  5120.1 2008.34  5176.6 2012.09  5226.8 2011.55
  5363.0 2015.16  5513.8 2017.24  5605.8 2017.13  5913.6 2021.42  6037.7 2021.45
#Mann=11,-1,0
  4169.3    0.07       0  4216.9   0.035       0  4276.3    0.07       0
  4622.9   0.035       0  4696.9    0.07       0  4741.0   0.035       0
  4859.1    0.07       0  4876.4   0.035       0  4996.7   0.035       0
  5000.7   0.035       0  5074.1    0.07       0
Bank Sta=4996.7,5000.7
Exp/Cntr=0.3,0.1

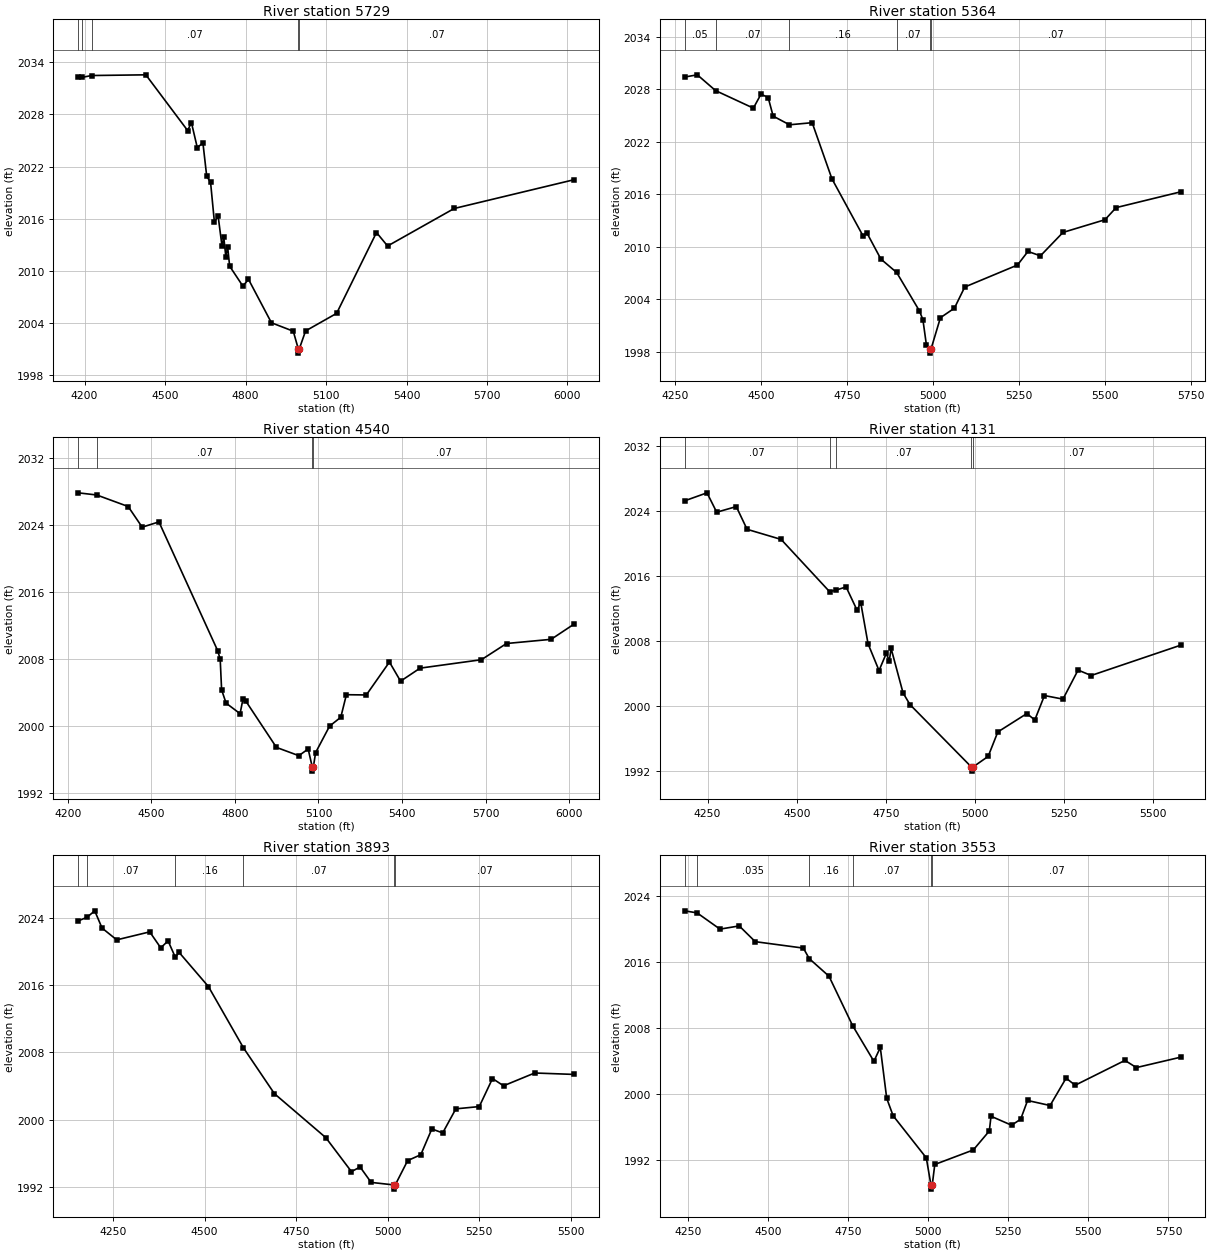
Type RM Length L Ch R = 1,5729,365,365,365
BEGIN DESCRIPTION:
Mapping XS 147d33eb
END DESCRIPTION:
XS GIS Cut Line= 3
      1489517.47      6813456.39      1490116.44      6812935.55
      1490385.53      6811915.60
#Sta/Elev= 30
  4176.3 2032.34  4189.5 2032.25  4226.1 2032.47  4428.4 2032.55  4584.1 2026.15
  4598.3 2027.06  4620.2 2024.18  4641.1 2024.74  4655.3 2020.89  4669.6 2020.21
  4683.8 2015.67  4698.0 2016.29  4712.3 2012.86  4718.9 2013.87  4726.5 2011.66
  4733.2 2012.79  4740.8 2010.56  4790.1 2008.27  4811.0 2009.05  4896.5 2004.06
  4977.9 2003.09  4996.5 2001.07  4996.8 2000.57  5000.5 2001.07  5023.8 2003.12
  5139.5 2005.14  5288.1 2014.43  5329.5 2012.88  5577.7 2017.19  6024.9 2020.50
#Mann=5,-1,0
  4176.3    0.07       0  4189.5    0.05       0  4226.1    0.07       0
  4996.5    0.07       0  5000.5    0.07       0
Bank Sta=4996.5,5000.5
Exp/Cntr=0.3,0.1

Type RM Length L Ch R = 1,5364,824,824,824
BEGIN DESCRIPTION:
Mapping XS 80740bbb
END DESCRIPTION:
XS GIS Cut Line= 3
      1489821.28      6813715.95      1490224.95      6813386.07
      1490395.36      6812482.01
#Sta/Elev= 30
  4277.5 2029.38  4314.2 2029.63  4367.3 2027.83  4477.1 2025.83  4499.4 2027.43
  4520.2 2027.03  4534.6 2024.92  4582.1 2023.93  4648.0 2024.17  4705.4 2017.77
  4795.6 2011.27  4807.0 2011.60  4847.7 2008.61  4893.6 2007.08  4959.7 2002.70
  4969.8 2001.70  4980.0 1998.82  4989.7 1998.38  4989.9 1997.88  4993.7 1998.38
  5020.7 2001.92  5061.4 2003.01  5091.4 2005.42  5244.6 2007.93  5275.1 2009.48
  5311.4 2008.98  5376.9 2011.65  5499.0 2013.10  5531.3 2014.48  5718.8 2016.28
#Mann=6,-1,0
  4277.5    0.05       0  4367.3    0.07       0  4582.1    0.16       0
  4893.6    0.07       0  4989.7    0.07       0  4993.7    0.07       0
Bank Sta=4989.7,4993.7
Exp/Cntr=0.3,0.1

Type RM Length L Ch R = 1,4540,409,409,409
BEGIN DESCRIPTION:
Mapping XS 99315d91
END DESCRIPTION:
XS GIS Cut Line= 3
      1489796.42      6813822.70      1490868.46      6813718.54
      1490903.19      6813015.39
#Sta/Elev= 30
  4237.1 2027.89  4303.8 2027.63  4416.5 2026.25  4466.8 2023.78  4527.0 2024.41
  4738.0 2008.99  4747.0 2007.98  4752.1 2004.30  4768.2 2002.71  4818.4 2001.45
  4828.5 2003.15  4838.5 2002.98  4949.0 1997.41  5029.4 1996.42  5062.9 1997.22
  5077.6 1995.07  5077.9 1994.57  5081.6 1995.07  5089.7 1996.79  5139.9 1999.96
  5180.1 2001.02  5200.2 2003.72  5271.8 2003.69  5354.8 2007.63  5394.8 2005.34
  5464.9 2006.90  5685.2 2007.91  5775.3 2009.85  5935.5 2010.35  6018.2 2012.18
#Mann=4,-1,0
  4237.1    0.05       0  4303.8    0.07       0  5077.6    0.07       0
  5081.6    0.07       0
Bank Sta=5077.6,5081.6
Exp/Cntr=0.3,0.1

Type RM Length L Ch R = 1,4131,238,238,238
BEGIN DESCRIPTION:
Mapping XS 58ba68ea
END DESCRIPTION:
XS GIS Cut Line= 3
      1489924.04      6814042.33      1490521.24      6814181.21
      1491180.48      6813768.32
#Sta/Elev= 30
  4185.8 2025.23  4248.4 2026.21  4275.6 2023.83  4330.5 2024.52  4360.8 2021.73
  4456.3 2020.49  4592.1 2014.08  4610.8 2014.27  4638.5 2014.66  4669.3 2011.80
  4679.6 2012.73  4700.1 2007.68  4730.9 2004.39  4751.5 2006.52  4759.6 2005.55
  4764.8 2007.10  4798.3 2001.64  4817.7 2000.21  4990.2 1992.54  4990.4 1992.04
  4994.2 1992.54  5037.0 1993.85  5064.1 1996.85  5145.6 1999.11  5167.8 1998.32
  5194.9 2001.32  5246.8 2000.88  5289.2 2004.45  5325.8 2003.78  5576.8 2007.50
#Mann=5,-1,0
  4185.8    0.07       0  4592.1    0.16       0  4610.8    0.07       0
  4990.2    0.07       0  4994.2    0.07       0
Bank Sta=4990.2,4994.2
Exp/Cntr=0.3,0.1

Type RM Length L Ch R = 1,3893,340,340,340
BEGIN DESCRIPTION:
Mapping XS 6cecb300
END DESCRIPTION:
XS GIS Cut Line= 3
      1490009.95      6814329.65      1490765.17      6814287.98
      1491265.16      6813959.86
#Sta/Elev= 30
  4154.7 2023.60  4179.0 2024.04  4199.8 2024.80  4219.8 2022.75  4259.9 2021.35
  4350.0 2022.30  4380.1 2020.40  4400.1 2021.23  4420.0 2019.27  4430.2 2019.86
  4510.3 2015.80  4605.8 2008.53  4690.6 2003.07  4830.8 1997.85  4900.9 1993.81
  4924.5 1994.36  4954.7 1992.53  5016.5 1992.23  5016.8 1991.73  5020.5 1992.23
  5054.4 1995.12  5090.3 1995.82  5120.4 1998.88  5150.1 1998.41  5186.0 2001.27
  5250.0 2001.54  5286.1 2004.87  5316.3 2004.01  5401.3 2005.53  5509.1 2005.36
#Mann=6,-1,0
  4154.7   0.035       0  4179.0    0.07       0  4420.0    0.16       0
  4605.8    0.07       0  5016.5    0.07       0  5020.5    0.07       0
Bank Sta=5016.5,5020.5
Exp/Cntr=0.3,0.1

Type RM Length L Ch R = 1,3553,231,231,231
BEGIN DESCRIPTION:
Mapping XS 9d04c92b
END DESCRIPTION:
XS GIS Cut Line= 3
      1489944.90      6814545.79      1490900.58      6814504.13
      1491335.50      6814103.06
#Sta/Elev= 30
  4239.7 2022.18  4278.5 2021.93  4349.9 2019.96  4410.0 2020.35  4460.0 2018.44
  4610.1 2017.66  4628.7 2016.38  4690.2 2014.25  4763.8 2008.27  4830.4 2003.93
  4850.4 2005.61  4870.4 1999.44  4890.4 1997.33  4994.0 1992.22  5008.5 1988.93
  5008.8 1988.43  5012.5 1988.93  5020.5 1991.42  5140.7 1993.18  5190.7 1995.48
  5196.0 1997.27  5260.2 1996.18  5288.6 1996.91  5310.1 1999.18  5380.4 1998.57
  5430.4 2001.89  5458.7 2001.03  5614.1 2004.04  5649.8 2003.17  5787.9 2004.43
#Mann=6,-1,0
  4239.7    0.07       0  4278.5   0.035       0  4628.7    0.16       0
  4763.8    0.07       0  5008.5    0.07       0  5012.5    0.07       0
Bank Sta=5008.5,5012.5
Exp/Cntr=0.3,0.1

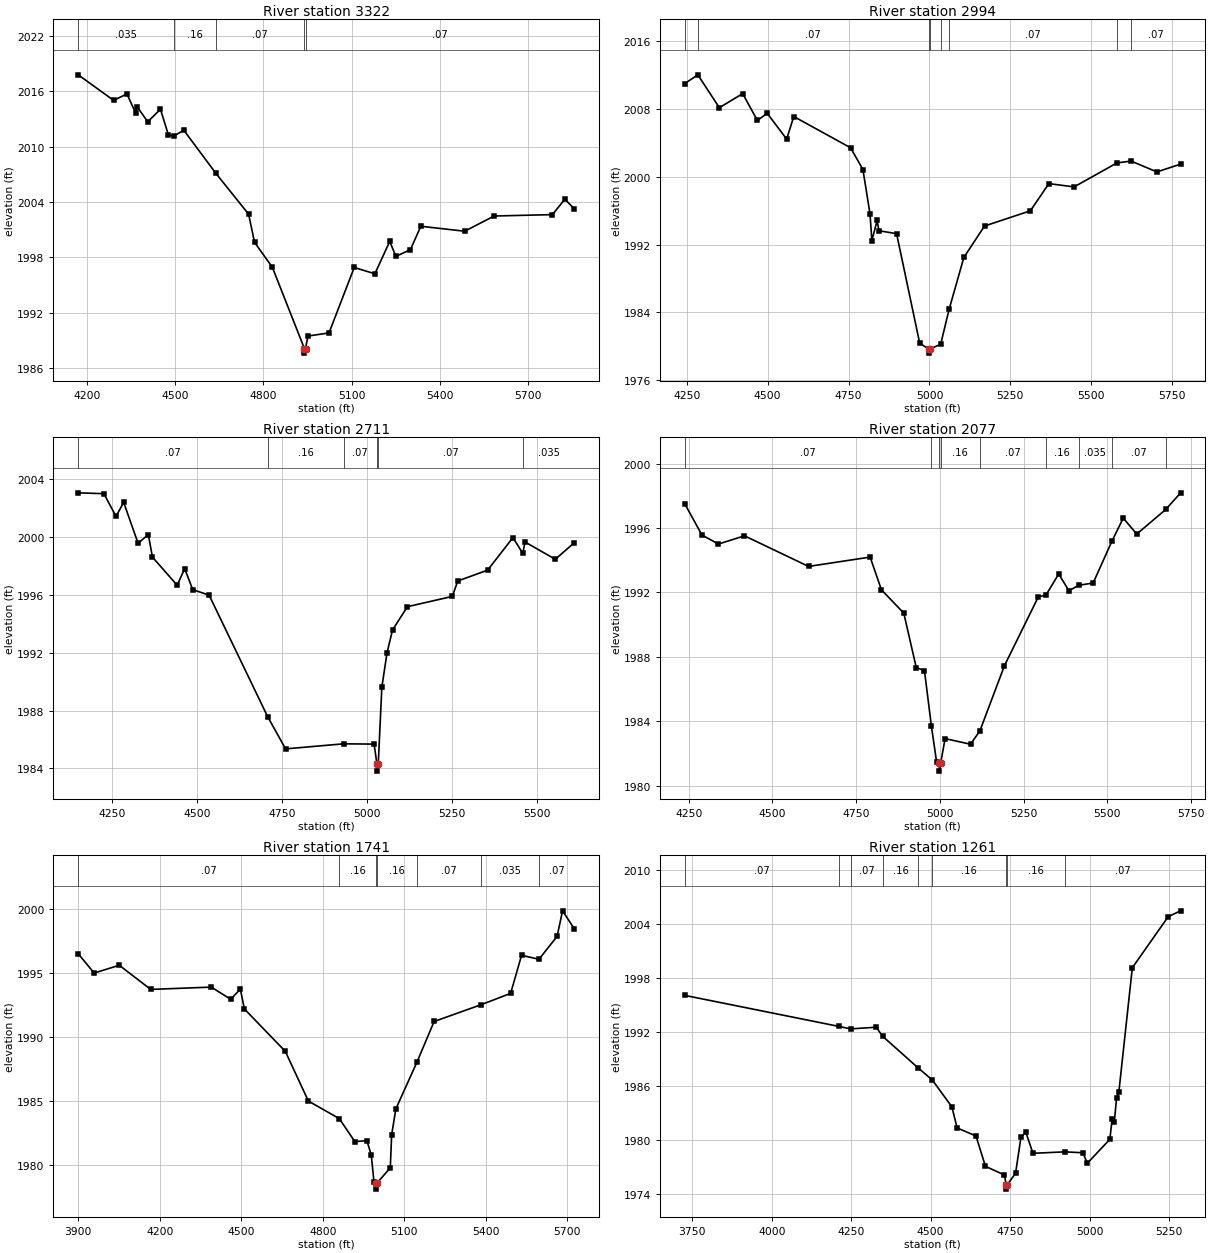
Type RM Length L Ch R = 1,3322,328,328,328
BEGIN DESCRIPTION:
Mapping XS db43ce92
END DESCRIPTION:
XS GIS Cut Line= 3
      1490030.76      6814798.40      1490840.69      6814694.23
      1491501.09      6814130.02
#Sta/Elev= 30
  4171.0 2017.79  4291.5 2015.02  4336.6 2015.72  4366.0 2013.66  4371.0 2014.34
  4407.2 2012.70  4450.5 2014.06  4477.7 2011.25  4496.1 2011.17  4530.0 2011.78
  4638.6 2007.12  4750.0 2002.69  4770.1 1999.64  4830.6 1996.94  4939.5 1988.13
  4939.8 1987.63  4943.5 1988.13  4951.6 1989.48  5023.2 1989.82  5108.9 1996.91
  5179.1 1996.23  5229.6 1999.74  5250.5 1998.11  5299.9 1998.85  5335.2 2001.38
  5484.3 2000.84  5584.2 2002.49  5782.4 2002.64  5824.6 2004.31  5856.2 2003.28
#Mann=5,-1,0
  4171.0   0.035       0  4496.1    0.16       0  4638.6    0.07       0
  4939.5    0.07       0  4943.5    0.07       0
Bank Sta=4939.5,4943.5
Exp/Cntr=0.3,0.1

Type RM Length L Ch R = 1,2994,283,283,283
BEGIN DESCRIPTION:
Mapping XS 5bc240cf
END DESCRIPTION:
XS GIS Cut Line= 3
      1490197.06      6815344.38      1490853.27      6814992.84
      1491362.94      6814392.17
#Sta/Elev= 30
  4243.8 2010.99  4284.5 2012.03  4350.9 2008.15  4423.0 2009.81  4468.4 2006.64
  4498.8 2007.49  4558.9 2004.44  4580.8 2007.11  4756.3 2003.42  4794.5 2000.85
  4816.4 1995.60  4822.1 1992.46  4838.4 1994.84  4844.0 1993.63  4898.5 1993.28
  4970.0 1980.33  4997.9 1979.68  4998.1 1979.18  5001.9 1979.68  5034.6 1980.22
  5060.7 1984.34  5106.4 1990.48  5170.1 1994.18  5311.8 1995.98  5369.0 1999.19
  5447.0 1998.80  5579.1 2001.63  5622.8 2001.85  5702.8 2000.57  5776.0 2001.49
#Mann=8,-1,0
  4243.8   0.035       0  4284.5    0.07       0  4997.9    0.07       0
  5001.9    0.07       0  5034.6    0.16       0  5060.7    0.07       0
  5579.1   0.035       0  5622.8    0.07       0
Bank Sta=4997.9,5001.9
Exp/Cntr=0.3,0.1

Type RM Length L Ch R = 1,2711,634,634,634
BEGIN DESCRIPTION:
Mapping XS 98a3943d
END DESCRIPTION:
XS GIS Cut Line= 3
      1490655.33      6815711.63      1491113.69      6814995.44
      1491400.08      6814459.12
#Sta/Elev= 30
  4151.5 2003.07  4227.0 2003.01  4262.7 2001.44  4285.2 2002.41  4327.5 1999.58
  4357.6 2000.18  4369.8 1998.62  4442.6 1996.67  4464.5 1997.83  4488.2 1996.37
  4536.4 1995.99  4708.7 1987.57  4761.3 1985.35  4932.1 1985.70  5021.6 1985.68
  5029.8 1984.31  5030.1 1983.81  5033.8 1984.31  5044.3 1989.61  5059.5 1991.99
  5075.7 1993.58  5119.6 1995.19  5251.4 1995.90  5267.6 1996.97  5355.4 1997.72
  5429.7 1999.97  5458.8 1998.88  5465.2 1999.67  5554.4 1998.47  5609.8 1999.61
#Mann=6,-1,0
  4151.5    0.07       0  4708.7    0.16       0  4932.1    0.07       0
  5029.8    0.07       0  5033.8    0.07       0  5458.8   0.035       0
Bank Sta=5029.8,5033.8
Exp/Cntr=0.3,0.1

Type RM Length L Ch R = 1,2077,336,336,336
BEGIN DESCRIPTION:
Mapping XS e770b370
END DESCRIPTION:
XS GIS Cut Line= 3
      1490824.60      6815860.05      1491246.50      6815479.82
      1491392.33      6814578.81
#Sta/Elev= 30
  4238.1 1997.51  4289.6 1995.56  4338.9 1995.00  4416.7 1995.51  4608.0 1993.61
  4791.8 1994.19  4825.5 1992.16  4892.3 1990.71  4929.5 1987.33  4954.0 1987.14
  4974.8 1983.68  4990.2 1981.48  4998.4 1981.40  4998.6 1980.90  5002.4 1981.40
  5015.6 1982.92  5091.5 1982.57  5119.3 1983.39  5192.9 1987.45  5294.2 1991.73
  5316.1 1991.81  5354.9 1993.14  5385.3 1992.10  5414.8 1992.44  5457.6 1992.58
  5513.6 1995.17  5547.4 1996.61  5587.9 1995.62  5674.5 1997.15  5718.8 1998.18
#Mann=9,-1,0
  4238.1    0.07       0  4974.8    0.16       0  4998.4    0.07       0
  5002.4    0.16       0  5119.3    0.07       0  5316.1    0.16       0
  5414.8   0.035       0  5513.6    0.07       0  5674.5   0.035       0
Bank Sta=4998.4,5002.4
Exp/Cntr=0.3,0.1

Type RM Length L Ch R = 1,1741,480,480,480
BEGIN DESCRIPTION:
Mapping XS d99f623c
END DESCRIPTION:
XS GIS Cut Line= 3
      1490822.01      6815906.91      1491493.90      6815432.94
      1491603.27      6814435.56
#Sta/Elev= 30
  3899.9 1996.51  3958.7 1995.00  4051.0 1995.61  4166.8 1993.72  4389.7 1993.90
  4461.1 1992.95  4496.8 1993.74  4511.6 1992.19  4662.3 1988.87  4747.2 1984.98
  4860.9 1983.61  4918.2 1981.81  4962.6 1981.88  4978.6 1980.77  4988.7 1978.65
  4996.7 1978.59  4997.0 1978.09  5000.8 1978.59  5048.7 1979.76  5053.7 1982.34
  5069.1 1984.36  5147.6 1988.07  5210.0 1991.21  5383.9 1992.53  5491.7 1993.41
  5531.9 1996.39  5596.0 1996.08  5662.7 1997.87  5682.8 1999.87  5725.5 1998.48
#Mann=7,-1,0
  3899.9    0.07       0  4860.9    0.16       0  4996.7    0.07       0
  5000.8    0.16       0  5147.6    0.07       0  5383.9   0.035       0
  5596.0    0.07       0
Bank Sta=4996.7,5000.8
Exp/Cntr=0.3,0.1

Type RM Length L Ch R = 1,1261,545,545,545
BEGIN DESCRIPTION:
Mapping XS c482380a
END DESCRIPTION:
XS GIS Cut Line= 3
      1490827.22      6815930.35      1491848.06      6815414.72
      1492142.31      6815120.48
#Sta/Elev= 30
  3726.3 1996.03  4211.7 1992.58  4248.3 1992.31  4328.8 1992.49  4348.5 1991.50
  4461.0 1987.96  4505.2 1986.63  4566.5 1983.66  4583.2 1981.31  4642.5 1980.41
  4672.3 1977.04  4732.1 1976.08  4737.2 1975.01  4737.4 1974.51  4741.3 1975.01
  4767.1 1976.29  4783.8 1980.26  4799.3 1980.83  4821.7 1978.49  4922.6 1978.65
  4978.6 1978.55  4992.8 1977.39  5063.5 1980.04  5070.6 1982.25  5077.6 1981.94
  5084.7 1984.66  5091.8 1985.28  5134.2 1999.10  5247.3 2004.78  5286.1 2005.42
#Mann=9,-1,0
  3726.3    0.07       0  4211.7    0.16       0  4248.3    0.07       0
  4348.5    0.16       0  4461.0    0.07       0  4505.2    0.16       0
  4737.2    0.07       0  4741.3    0.16       0  4922.6    0.07       0
Bank Sta=4737.2,4741.3
Exp/Cntr=0.3,0.1

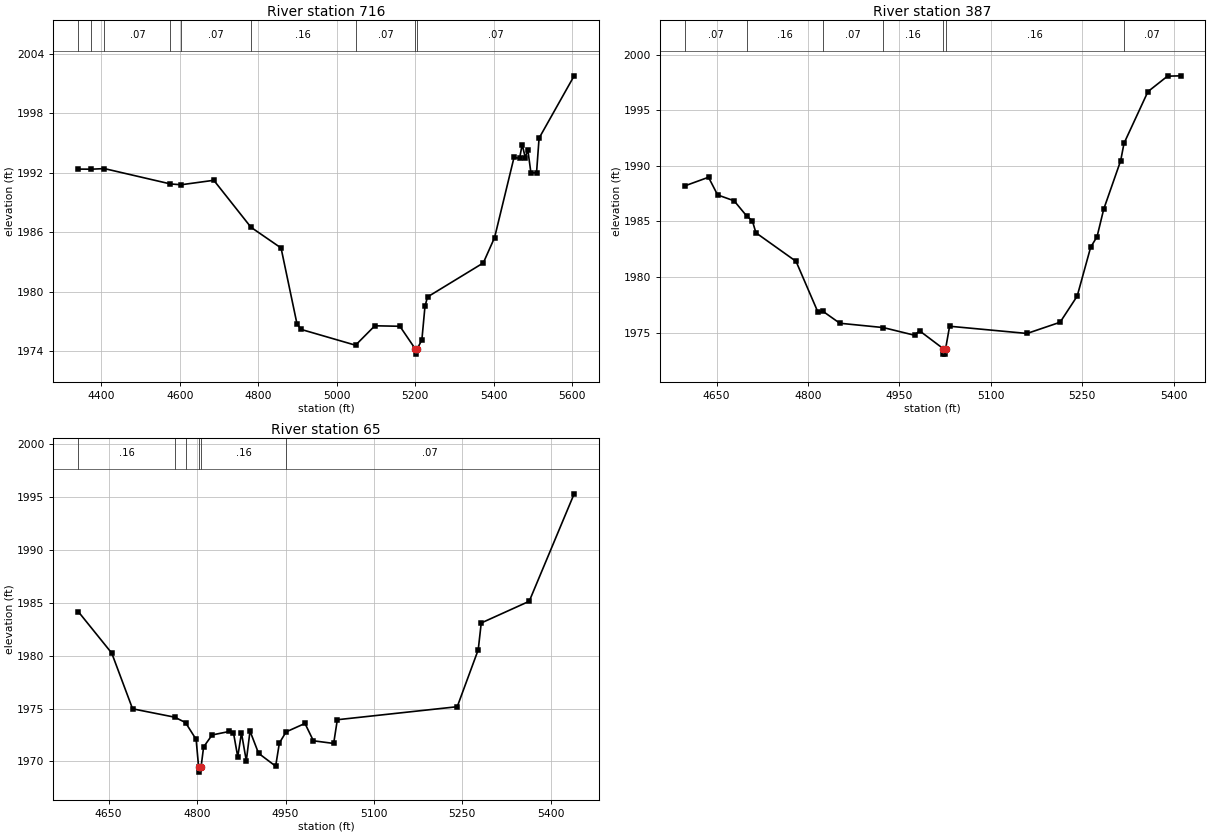
Type RM Length L Ch R = 1,716,329,329,329
BEGIN DESCRIPTION:
Mapping XS e8c4af62
END DESCRIPTION:
XS GIS Cut Line= 3
      1491172.29      6815894.28      1491878.85      6815802.27
      1492227.78      6815375.23
#Sta/Elev= 30
  4341.3 1992.36  4375.0 1992.35  4408.0 1992.41  4576.5 1990.86  4603.7 1990.78
  4686.9 1991.23  4781.6 1986.49  4858.3 1984.40  4898.7 1976.78  4908.8 1976.19
  5048.1 1974.59  5097.3 1976.55  5161.2 1976.50  5200.8 1974.19  5201.1 1973.69
  5204.9 1974.19  5217.2 1975.13  5225.1 1978.51  5231.6 1979.46  5373.7 1982.89
  5402.5 1985.45  5452.0 1993.53  5466.3 1993.45  5472.8 1994.84  5480.7 1993.52
  5487.2 1994.31  5495.1 1991.99  5509.4 1991.97  5515.9 1995.48  5605.3 2001.77
#Mann=9,-1,0
  4341.3    0.07       0  4375.0    0.16       0  4408.0    0.07       0
  4576.5    0.16       0  4603.7    0.07       0  4781.6    0.16       0
  5048.1    0.07       0  5200.8    0.07       0  5204.9    0.07       0
Bank Sta=5200.8,5204.9
Exp/Cntr=0.3,0.1

Type RM Length L Ch R = 1,387,322,322,322
BEGIN DESCRIPTION:
Mapping XS c7975021
END DESCRIPTION:
XS GIS Cut Line= 3
      1491779.05      6816125.96      1492093.72      6815911.11
      1492217.43      6815496.60
#Sta/Elev= 30
  4597.6 1988.20  4636.7 1988.98  4651.6 1987.39  4678.7 1986.86  4699.8 1985.46
  4708.5 1985.08  4714.5 1983.98  4780.3 1981.41  4816.2 1976.84  4824.8 1976.90
  4852.1 1975.84  4923.4 1975.45  4974.7 1974.76  4982.9 1975.16  5021.6 1973.56
  5021.8 1973.06  5025.4 1973.06  5025.7 1973.56  5032.2 1975.57  5159.3 1974.92
  5213.5 1975.93  5241.5 1978.28  5263.6 1982.68  5274.1 1983.63  5285.0 1986.10
  5312.9 1990.48  5318.3 1992.03  5357.6 1996.69  5389.7 1998.08  5411.2 1998.11
#Mann=7,-1,0
  4597.6    0.07       0  4699.8    0.16       0  4824.8    0.07       0
  4923.4    0.16       0  5021.6    0.07       0  5025.7    0.16       0
  5318.3    0.07       0
Bank Sta=5021.6,5025.7
Exp/Cntr=0.3,0.1

Type RM Length L Ch R = 1,65,0,0,0
BEGIN DESCRIPTION:
NUBIA CREEK TRIBUTARY 1_2 1.0
END DESCRIPTION:
XS GIS Cut Line= 3
      1492143.63      6816306.09      1492389.71      6815988.71
      1492280.00      6815563.02
#Sta/Elev= 30
  4598.4 1984.16  4655.3 1980.23  4690.6 1974.97  4762.1 1974.18  4780.4 1973.67
  4798.4 1972.08  4802.6 1969.49  4802.9 1968.99  4806.8 1969.49  4811.1 1971.37
  4825.5 1972.50  4854.5 1972.83  4861.7 1972.72  4869.0 1970.44  4875.3 1972.69
  4883.5 1970.06  4889.8 1972.87  4904.3 1970.77  4933.3 1969.55  4939.6 1971.74
  4951.0 1972.79  4983.0 1973.59  4997.3 1971.95  5031.7 1971.70  5037.9 1973.94
  5241.3 1975.17  5276.9 1980.55  5282.0 1983.08  5363.4 1985.13  5439.6 1995.28
#Mann=6,-1,0
  4598.4    0.16       0  4762.1    0.07       0  4780.4    0.16       0
  4802.6    0.07       0  4806.8    0.16       0  4951.0    0.07       0
Bank Sta=4802.6,4806.8
Exp/Cntr=0.3,0.1

Chan Stop Cuts=-1