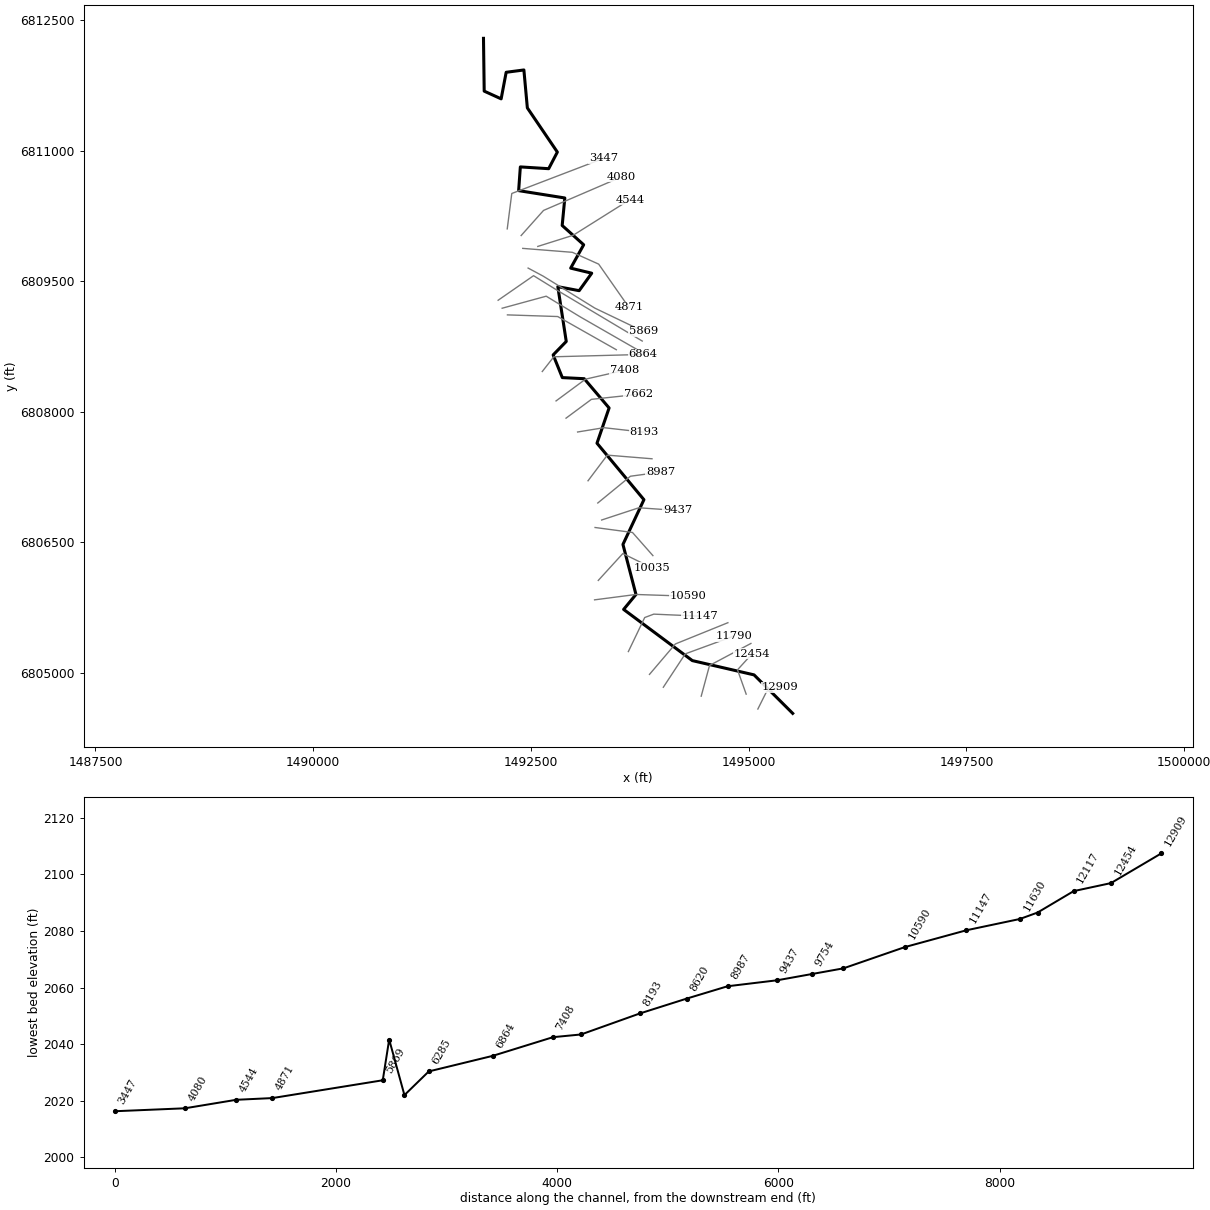
--- NUBIA CREEK TRIBUTARY 1_3.prj (project) ---

Proj Title=NUBIA CREEK TRIBUTARY 1_3 Base Level Engineering
Current Plan=p01
Default Exp/Contr=0.3,0.1
English Units
Geom File=g01
Flow File=f01
Plan File=p01
Y Axis Title=Elevation
X Axis Title(PF)=Main Channel Distance
X Axis Title(XS)=Station
BEGIN DESCRIPTION:
NUBIA CREEK TRIBUTARY 1_3
END DESCRIPTION:
DSS File=dss
DSS Export Rating Curves= 0
DSS Export Rating Curve Sorted= 0
DSS Export Volume Flow Curves= 0
DXF OffsetX= 0
DXF OffsetY= 0
DXF ScaleX= 1
DXF ScaleY= 10

--- NUBIA CREEK TRIBUTARY 1_3.p01 (plan) ---

Plan Title=Multiple Run
Program Version=4.10
Short Identifier=Multiple Run
Geom File=g01
Flow File=f01
Subcritical Flow
K Sum by GR= 0
Std Step Tol= 0.01
Critical Tol= 0.01
Num of Std Step Trials= 20
Max Error Tol= 0.3
Flow Tol Ratio= 0.001
Split Flow NTrial= 30
Split Flow Tol= 0.02
Split Flow Ratio= 0.02
Log Output Level= 0
Friction Slope Method= 1
Unsteady Friction Slope Method= 2
Unsteady Bridges Friction Slope Method= 1
Parabolic Critical Depth
Global Vel Dist= 1 , 1 , 1
Global Log Level= 0
CheckData=True
Encroach Param=-1 ,0,0, 0
BEGIN DESCRIPTION:
Multiple Run
END DESCRIPTION:
Computation Interval=1HOUR
Output Interval=1HOUR
Run HTab= 0
Run UNet= 0
Run PostProcess= 0
Run WQNet= 0
UNET Theta= 1
UNET Theta Warmup= 1
UNET ZTol= 0.02
UNET ZSATol= 0.05
UNET MxIter= 20
UNET MaxInSteps= 0
UNET DtIC= 0
UNET DtMin= 0
UNET MaxCRTS= 20
UNET WFStab= 2
UNET SFStab= 1
UNET WFX= 1
UNET SFX= 1
UNET DSS MLevel= 4
UNET DZMax Abort= 100
UNET Convert EG Bridges= 0
UNET Use Existing IB Tables=-1
UNET Froude Reduction=False
UNET Froude Limit= 1
UNET Froude Power= 10
UNET Time Slicing=0,0, 5
UNET Junction Losses=0
Instantaneous Interval=1HOUR
DSS File=dss
Write IC File= 0
Write IC File at Sim End=0
Echo Input=False
Echo Parameters=False
Echo Output=False
Write Detailed= 0
WQ AD Non Conservative
WQ ULTIMATE=-1
WQ Max Comp Step=1HOUR
WQ Output Interval=15MIN
WQ Output Selected Increments= 0
WQ Output face flow=0
WQ Output face velocity=0
WQ Output face area=0
WQ Output face dispersion=0
WQ Output cell volume=0
WQ Output cell surface area=0
WQ Output cell continuity=0
WQ Output cumulative cell continuity=0
WQ Output face conc=0
WQ Output face dconc_dx=0
WQ Output face courant=0
WQ Output face peclet=0
WQ Output face adv mass=0
WQ Output face disp mass=0
WQ Output cell mass=0
WQ Output cell source sink temp=0
WQ Output cell source sink nsm=0
WQ Output MaxMinRange=-1
WQ Daily Max Min Mean=-1
WQ Daily Range=0
WQ Daily Time=0
WQ Create Restart=0
WQ Fixed Restart=0
WQ System Summary=0
WQ Use Fixed Temperature=0
Sorting and Armoring Iterations= 10
XS Update Threshold= 0.02
Hydraulics Update Threshold= 0.02
Energy Slope Method= 1
Volume Change Method= 0
XS Weighting Method= 0
Number of US Weighted Cross Sections= 1
Number of DS Weighted Cross Sections= 1
Upstream XS Weight=0.25
Main XS Weight=0.5
Downstream XS Weight=0.25
Number of DS XS's Weighted with US Boundary= 1
Upstream Boundary Weight= 1
Weight of XSs Associated with US Boundary= 0
Number of US XS's Weighted with DS Boundary= 1
Downstream Boundary Weight= 0.5
Weight of XSs Associated with DS Boundary= 0.5
Sediment Output Level= 4
Mass or Volume Output= 0
Output Increment Type= 1
Profile and TS Output Increment= 10
XS Output Flag= 0
XS Output Increment= 10
Disregard all LS=0
Disregard all Conn=0
Disregard all Breaches=0
Disregard all Pumps=0

--- NUBIA CREEK TRIBUTARY 1_3.f01 (steady flow) ---

Flow Title=Multiple
Program Version=4.10
Number of Profiles= 7
Profile Names=10-year,25-year,50-year,1pct_min,100-year,1pct_plu,500-year
River Rch & RM=NUBIA CREEK TRIB,Reach-1         ,12909
     446     654     836     533    1064    2122    1740
River Rch & RM=NUBIA CREEK TRIB,Reach-1         ,9754
     500     736     944     603    1203    2400    1974
River Rch & RM=NUBIA CREEK TRIB,Reach-1         ,6285
     742    1116    1450     938    1871    3733    3149
River Rch & RM=NUBIA CREEK TRIB,Reach-1         ,4544
     955    1449    1894    1230    2455    4898    4173
Boundary for River Rch & Prof#=NUBIA CREEK TRIB,Reach-1         , 1
Up Type= 0
Dn Type= 3
Dn Slope=0.005
Boundary for River Rch & Prof#=NUBIA CREEK TRIB,Reach-1         , 2
Up Type= 0
Dn Type= 3
Dn Slope=0.005
Boundary for River Rch & Prof#=NUBIA CREEK TRIB,Reach-1         , 3
Up Type= 0
Dn Type= 3
Dn Slope=0.005
Boundary for River Rch & Prof#=NUBIA CREEK TRIB,Reach-1         , 4
Up Type= 0
Dn Type= 3
Dn Slope=0.005
Boundary for River Rch & Prof#=NUBIA CREEK TRIB,Reach-1         , 5
Up Type= 0
Dn Type= 3
Dn Slope=0.005
Boundary for River Rch & Prof#=NUBIA CREEK TRIB,Reach-1         , 6
Up Type= 0
Dn Type= 3
Dn Slope=0.005
Boundary for River Rch & Prof#=NUBIA CREEK TRIB,Reach-1         , 7
Up Type= 0
Dn Type= 3
Dn Slope=0.005
DSS Import GetInterval= 0
DSS Import GetPeak= 0
DSS Import FillOption= 0

--- NUBIA CREEK TRIBUTARY 1_3.g01 (geometry) ---

Geom Title=Existing Conditions
Program Version=4.10

River Reach=NUBIA CREEK TRIB,Reach-1
Reach XY= 30
        1495505.        6804538.      1495061.34      6804979.98
       1494352.7      6805143.83      1493563.88      6805731.49
      1493705.55      6805903.14      1493556.04      6806477.56
      1493796.92      6806991.31      1493258.09      6807639.67
      1493397.02      6808044.37      1493111.48      6808380.31
      1492860.01        6808393.      1492754.87      6808653.42
      1492905.11      6808807.89      1492808.45      6809436.81
      1493053.57      6809391.01      1493197.52      6809591.62
      1492955.98      6809649.69      1493105.23      6809917.92
      1492858.46       6810139.5      1492888.77      6810455.23
      1492358.61      6810539.48      1492378.05      6810811.86
      1492703.52      6810791.45      1492803.03       6810982.1
      1492458.54      6811489.46      1492418.74      6811924.81
      1492215.32      6811898.18      1492157.71      6811593.28
      1491963.13      6811681.92        1491955.        6812288.

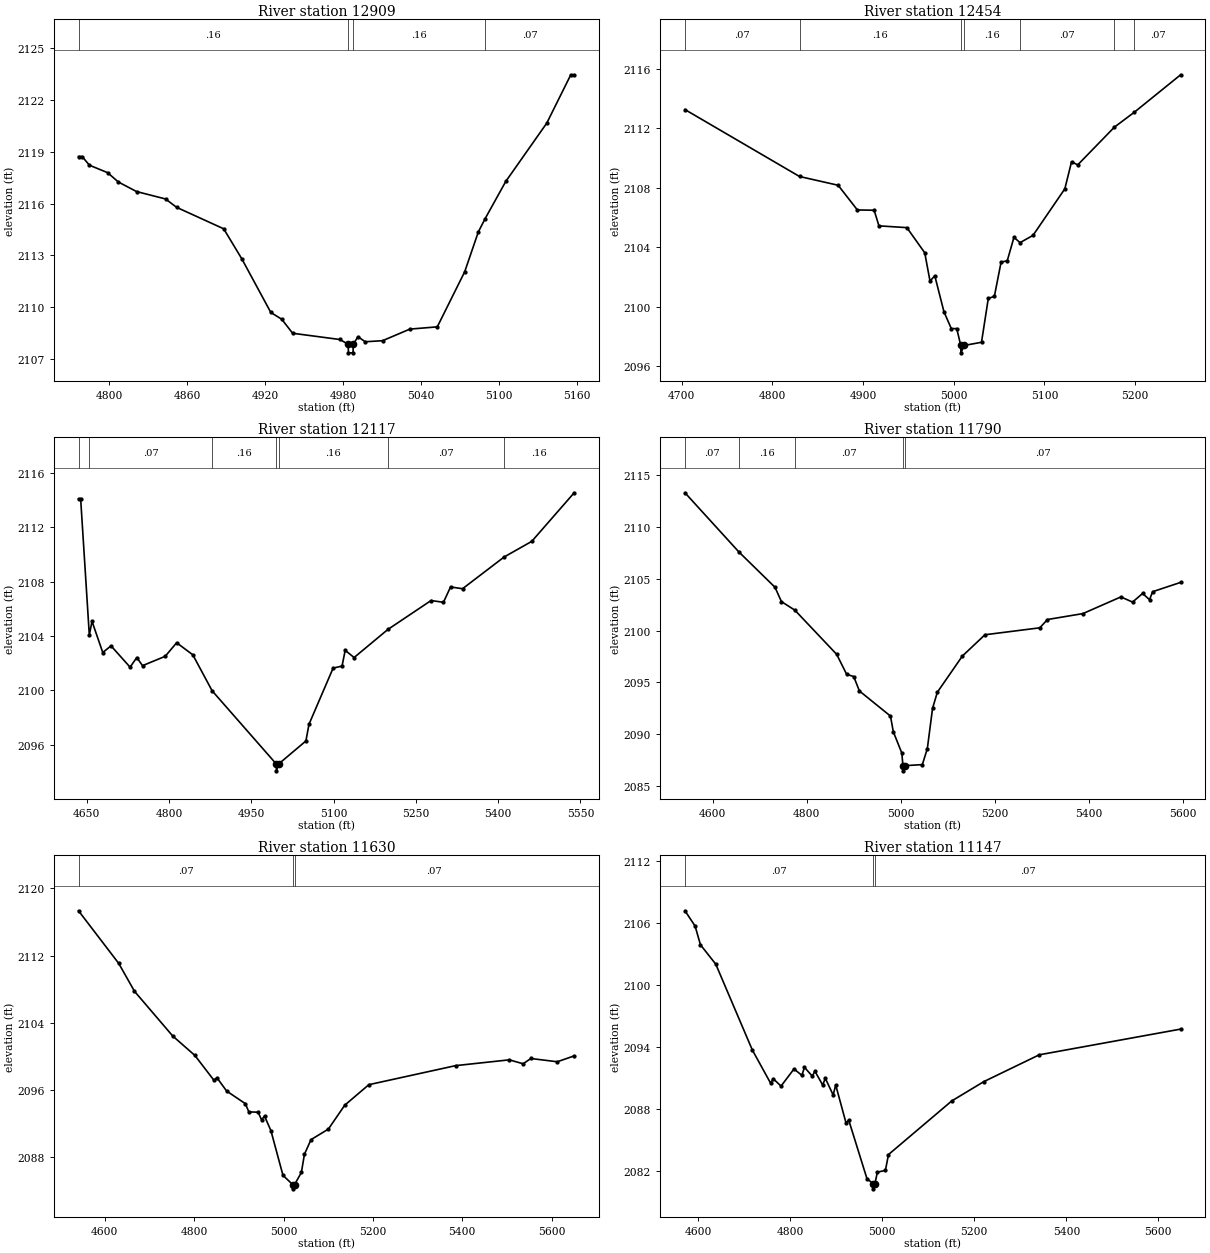
Type RM Length L Ch R = 1 ,12909   ,455,455,455
BEGIN DESCRIPTION:
NUBIA CREEK TRIBUTARY 1_3 17.0
END DESCRIPTION:
XS GIS Cut Line= 3
        1495105.        6804588.        1495205.        6804788.
      1495354.98      6804837.99
#Sta/Elev= 30
  4776.4 2118.71  4779.2 2118.71  4784.8 2118.21  4798.8 2117.78  4807.1 2117.24
  4821.1 2116.69  4843.5 2116.26  4851.9 2115.78  4888.2 2114.54  4902.2  2112.8
  4924.5 2109.71  4932.9 2109.32  4941.3 2108.51  4977.6 2108.15    4984 2107.88
  4984.3 2107.38  4987.8 2107.38    4988 2107.88  4991.6 2108.31  4997.2 2108.02
  5010.5 2108.08  5031.6 2108.75  5052.7 2108.88  5073.8 2112.06  5084.3 2114.36
  5089.5 2115.12  5105.4 2117.27    5137 2120.64  5155.5 2123.43  5158.1 2123.43
#Mann= 4 ,-1 , 0
  4776.4     .16       0    4984     .07       0    4988     .16       0
  5089.5     .07       0
Bank Sta=4984,4988
XS Rating Curve= 0 ,0
Exp/Cntr=0.3,0.1

Type RM Length L Ch R = 1 ,12454   ,337,337,337
BEGIN DESCRIPTION:
NUBIA CREEK TRIBUTARY 1_3 16.0
END DESCRIPTION:
XS GIS Cut Line= 3
       1494970.8       6804758.9      1494871.39      6805038.13
      1495039.97      6805223.01
#Sta/Elev= 30
  4703.6 2113.25  4829.9 2108.75  4872.5 2108.16  4893.7  2106.5  4912.2 2106.48
  4917.5 2105.43  4948.3 2105.31    4968 2103.62  4973.8 2101.72  4979.1 2102.07
  4989.2 2099.65  4997.3 2098.52  5003.3 2098.52  5007.7 2097.39  5007.9 2096.89
  5011.7 2097.39  5030.6  2097.6  5038.1 2100.55  5044.8 2100.69  5052.2 2102.99
    5059 2103.08  5066.4 2104.66  5073.1  2104.3  5087.4 2104.79  5122.5 2107.92
  5129.9 2109.74  5136.7 2109.53  5177.2 2112.07  5199.1 2113.07  5250.2 2115.59
#Mann= 7 ,-1 , 0
  4703.6     .07       0  4829.9     .16       0  5007.7     .07       0
  5011.7     .16       0  5073.1     .07       0  5177.2     .16       0
  5199.1     .07       0
Bank Sta=5007.7,5011.7
XS Rating Curve= 0 ,0
Exp/Cntr=0.3,0.1

Type RM Length L Ch R = 1 ,12117   ,327,327,327
BEGIN DESCRIPTION:
NUBIA CREEK TRIBUTARY 1_3 15.0
END DESCRIPTION:
XS GIS Cut Line= 3
      1494454.62      6804735.38      1494549.96      6805087.91
      1495025.37      6805340.84
#Sta/Elev= 30
  4634.8 2114.11  4638.7 2114.11  4654.5 2104.06  4659.4 2105.08    4679 2102.78
  4694.1 2103.27  4728.8  2101.7  4741.1 2102.41  4751.5 2101.81  4792.9  2102.5
  4813.7  2103.5  4843.2 2102.61  4878.4 2099.96  4995.5 2094.56  4995.7 2094.06
  4999.5 2094.56  5049.4 2096.26    5055 2097.49    5099 2101.63  5115.3 2101.78
    5121 2102.94  5137.3 2102.41  5198.9 2104.48  5277.6 2106.61  5300.2 2106.48
  5313.1 2107.61    5335 2107.48  5410.9 2109.82  5461.2 2110.97  5538.5 2114.55
#Mann= 7 ,-1 , 0
  4634.8     .16       0  4654.5     .07       0  4878.4     .16       0
  4995.5     .07       0  4999.5     .16       0  5198.9     .07       0
  5410.9     .16       0
Bank Sta=4995.5,4999.5
XS Rating Curve= 0 ,0
Exp/Cntr=0.3,0.1

Type RM Length L Ch R = 1 ,11790   ,160,160,160
BEGIN DESCRIPTION:
NUBIA CREEK TRIBUTARY 1_3 14.0
END DESCRIPTION:
XS GIS Cut Line= 3
      1494019.56      6804837.97      1494271.65       6805221.3
      1494831.04      6805426.12
#Sta/Elev= 30
  4541.2 2113.29  4655.8 2107.59  4732.7 2104.18  4746.4  2102.8    4775 2101.97
    4864 2097.71  4885.1 2095.79  4900.2 2095.57  4912.3 2094.18  4978.4 2091.76
  4984.4 2090.25  5002.5  2088.2  5004.9 2086.98  5005.2 2086.48  5008.9 2086.98
  5046.2 2087.08  5056.8 2088.62  5067.9  2092.5  5078.1 2094.06  5131.4 2097.55
  5179.4  2099.6  5296.1 2100.27  5312.4 2101.07  5387.7 2101.64  5468.6 2103.25
  5493.4 2102.75  5514.7 2103.58  5529.6 2102.98    5536 2103.75  5595.7 2104.65
#Mann= 5 ,-1 , 0
  4541.2     .07       0  4655.8     .16       0    4775     .07       0
  5004.9     .07       0  5008.9     .07       0
Bank Sta=5004.9,5008.9
XS Rating Curve= 0 ,0
Exp/Cntr=0.3,0.1

Type RM Length L Ch R = 1 ,11630   ,483,483,483
BEGIN DESCRIPTION:
NUBIA CREEK TRIBUTARY 1_3 13.0
END DESCRIPTION:
XS GIS Cut Line= 3
      1493860.71      6804985.54      1494158.04      6805334.95
      1494760.85      6805578.91
#Sta/Elev= 30
  4541.2 2117.34  4631.2 2111.07  4666.4 2107.75    4752 2102.42  4801.5 2100.11
  4844.3 2097.14  4850.9 2097.45  4872.7 2095.86  4914.5 2094.36  4922.3 2093.38
  4943.1 2093.34  4950.8 2092.44  4957.4 2092.88  4971.7 2091.15  4998.7 2085.82
  5020.6 2084.71  5020.8 2084.21  5024.6 2084.71  5039.9 2086.16  5046.7 2088.32
  5061.4 2090.07  5100.3 2091.33    5137 2094.18  5190.9 2096.62  5385.1 2098.89
  5505.2 2099.58  5536.1 2099.11  5553.4 2099.74  5612.5 2099.35  5650.3 2100.05
#Mann= 3 ,-1 , 0
  4541.2     .07       0  5020.6     .07       0  5024.6     .07       0
Bank Sta=5020.6,5024.6
XS Rating Curve= 0 ,0
Exp/Cntr=0.3,0.1

Type RM Length L Ch R = 1 ,11147   ,557,557,557
BEGIN DESCRIPTION:
Mapping XS e8dbd945
END DESCRIPTION:
XS GIS Cut Line= 4
       1493618.3      6805247.71      1493805.78      6805638.29
      1493909.95      6805677.35      1494441.94        6805654.
#Sta/Elev= 30
  4571.4 2107.16  4593.4 2105.68    4605 2103.87  4638.3 2101.99  4717.7 2093.68
  4757.5 2090.46    4763  2090.9  4780.1 2090.18  4808.3 2091.84  4825.4 2091.22
    4831    2092  4848.1 2091.14  4853.6 2091.63  4870.7 2090.28  4876.3 2090.94
  4893.4 2089.32  4898.9 2090.29  4921.5 2086.58  4927.1  2086.9  4966.8 2081.22
  4980.1 2080.73  4980.4 2080.23  4984.1 2080.73  4989.5 2081.85  5006.9 2082.01
  5013.6 2083.55    5151 2088.74    5221 2090.62  5341.2 2093.21  5648.4  2095.7
#Mann= 3 ,-1 , 0
  4571.4     .07       0  4980.1     .07       0  4984.1     .07       0
Bank Sta=4980.1,4984.1
XS Rating Curve= 0 ,0
Exp/Cntr=0.3,0.1

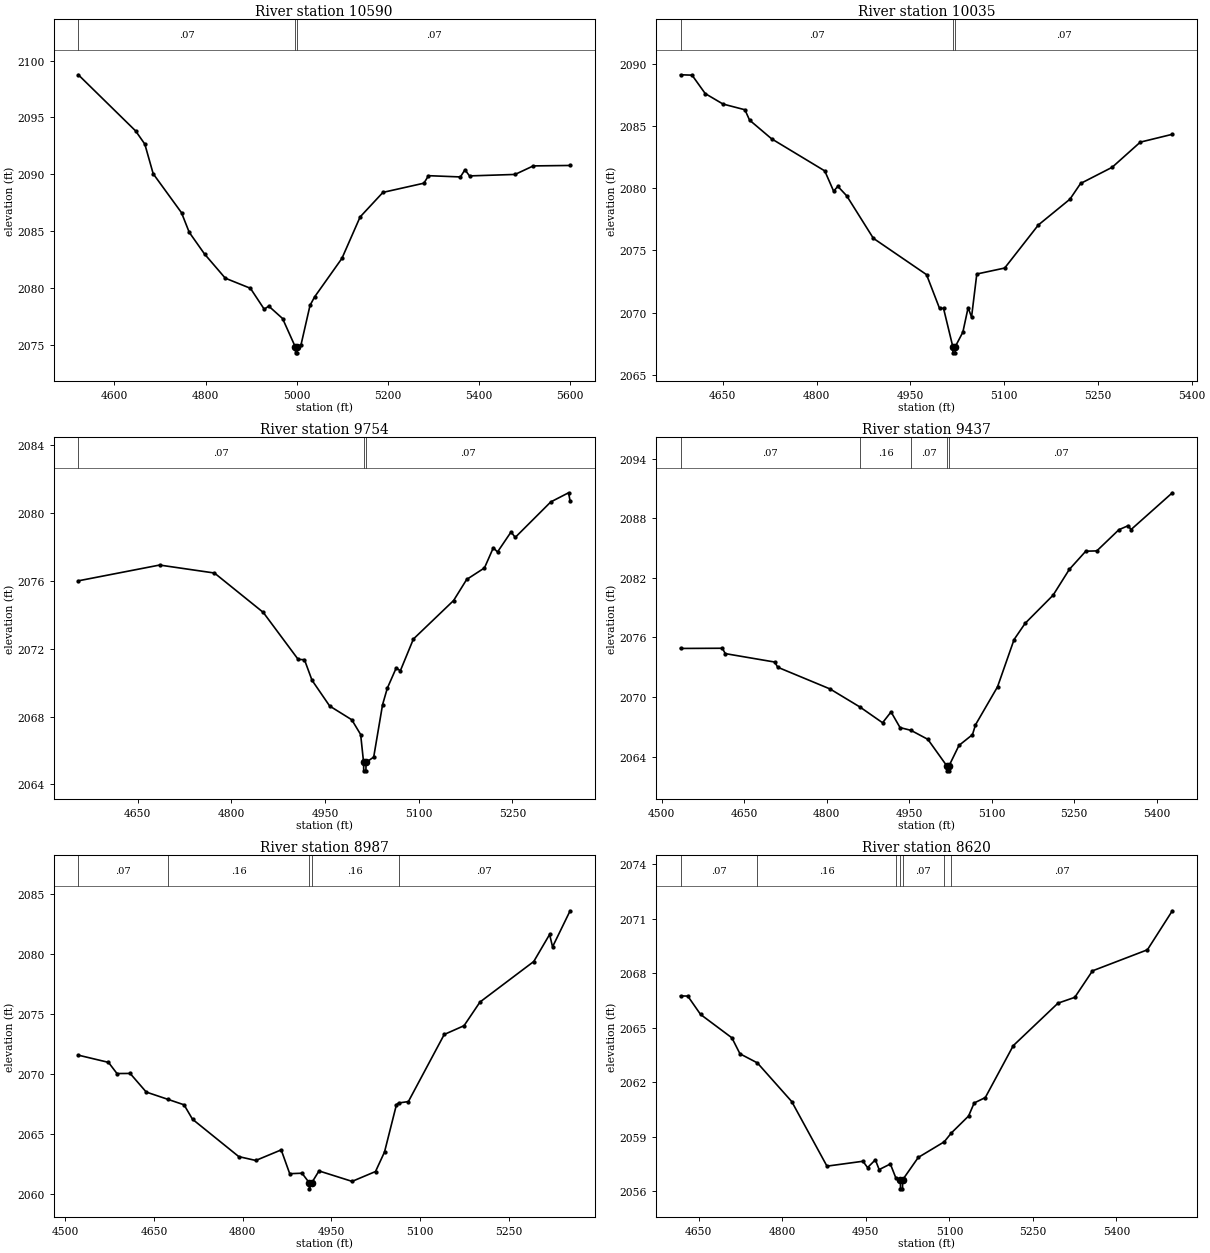
Type RM Length L Ch R = 1 ,10590   ,555,555,555
BEGIN DESCRIPTION:
NUBIA CREEK TRIBUTARY 1_3 12.0
END DESCRIPTION:
XS GIS Cut Line= 3
      1493230.24      6805841.41      1493705.55      6805903.14
      1494305.81      6805883.08
#Sta/Elev= 30
  4520.7 2098.75  4646.5 2093.81  4666.7 2092.65  4685.1 2090.04  4747.3 2086.61
  4764.2 2084.89  4797.8 2082.98  4843.4 2080.85  4898.6 2079.96  4928.9 2078.12
  4938.9 2078.39  4969.2  2077.3  4997.4 2074.78  4997.7 2074.28  5001.2 2074.28
  5001.4 2074.78  5009.5 2074.95  5029.5 2078.46  5039.5  2079.2  5099.5 2082.59
  5139.5 2086.24  5189.6  2088.4  5279.6 2089.21  5289.6 2089.87  5359.7 2089.76
  5369.7 2090.39  5379.7 2089.85  5479.7 2089.98  5519.7 2090.73  5600.6 2090.77
#Mann= 3 ,-1 , 0
  4520.7     .07       0  4997.4     .07       0  5001.4     .07       0
Bank Sta=4997.4,5001.4
XS Rating Curve= 0 ,0
Exp/Cntr=0.3,0.1

Type RM Length L Ch R = 1 ,10035   ,281,281,281
BEGIN DESCRIPTION:
Mapping XS 39cf071c
END DESCRIPTION:
XS GIS Cut Line= 3
      1493272.86       6806064.4      1493554.54      6806372.84
      1493885.78      6806210.24
#Sta/Elev= 30
  4582.3 2089.11  4600.7 2089.08  4621.8  2087.6  4650.2 2086.76  4685.3  2086.3
  4692.7 2085.47  4727.9 2083.97    4813 2081.39  4827.2 2079.76  4833.9 2080.15
  4848.1 2079.39  4890.7 2075.98  4975.8 2073.06  4996.6 2070.35    5003 2070.35
  5017.8 2067.28    5018 2066.78  5021.5 2066.78  5021.8 2067.28  5033.9 2068.44
  5042.3 2070.41  5047.8 2069.65  5056.2 2073.11  5100.8 2073.59  5154.7 2077.05
  5205.2 2079.12  5222.2 2080.38  5272.7 2081.68  5317.7  2083.7    5369 2084.33
#Mann= 3 ,-1 , 0
  4582.3     .07       0  5017.8     .07       0  5021.8     .07       0
Bank Sta=5017.8,5021.8
XS Rating Curve= 0 ,0
Exp/Cntr=0.3,0.1

Type RM Length L Ch R = 1 ,9754    ,317,317,317
BEGIN DESCRIPTION:
Mapping XS 41322388
END DESCRIPTION:
XS GIS Cut Line= 3
      1493235.95      6806672.08      1493665.69      6806614.78
      1493900.01      6806349.22
#Sta/Elev= 30
  4554.7    2076  4684.9 2076.93  4772.7 2076.46  4850.9 2074.14  4906.8 2071.37
  4916.9 2071.35    4929 2070.14  4957.3 2068.62  4992.7 2067.81  5006.9 2066.94
  5011.6  2065.3  5011.8  2064.8  5015.3  2064.8  5015.6  2065.3  5027.8 2065.61
    5042  2068.7  5049.6 2069.67  5063.8 2070.86  5070.5  2070.7  5091.4 2072.57
  5155.8 2074.84  5176.7 2076.08  5205.2 2076.76  5219.4 2077.95  5226.1  2077.7
  5247.8 2078.88  5254.5 2078.56  5311.4 2080.65  5339.9 2081.19  5342.4  2080.7
#Mann= 3 ,-1 , 0
  4554.7     .07       0  5011.6     .07       0  5015.6     .07       0
Bank Sta=5011.6,5015.6
XS Rating Curve= 0 ,0
Exp/Cntr=0.3,0.1

Type RM Length L Ch R = 1 ,9437    ,450,450,450
BEGIN DESCRIPTION:
Mapping XS b4a7383c
END DESCRIPTION:
XS GIS Cut Line= 3
      1493311.53      6806758.01       1493738.6      6806898.63
      1494181.98      6806867.52
#Sta/Elev= 30
  4534.3 2074.89  4610.3 2074.91  4615.6 2074.37  4705.6 2073.52  4710.9    2073
  4806.2 2070.81  4860.6 2068.99  4901.6 2067.41    4917  2068.5  4933.4 2066.92
  4953.1 2066.65  4983.9 2065.74  5018.4 2063.07  5018.7 2062.57  5022.2 2062.57
  5022.4 2063.07  5040.5 2065.13    5065 2066.21  5070.5  2067.2  5110.6 2071.03
  5140.7 2075.79  5160.8 2077.42  5211.6 2080.25    5241 2082.84    5271 2084.68
  5291.1 2084.71  5331.2 2086.84  5348.2 2087.25  5353.2 2086.85  5428.4 2090.56
#Mann= 5 ,-1 , 0
  4534.3     .07       0  4860.6     .16       0  4953.1     .07       0
  5018.4     .07       0  5022.4     .07       0
Bank Sta=5018.4,5022.4
XS Rating Curve= 0 ,0
Exp/Cntr=0.3,0.1

Type RM Length L Ch R = 1 ,8987    ,367,367,367
BEGIN DESCRIPTION:
Mapping XS d7c59b78
END DESCRIPTION:
XS GIS Cut Line= 3
      1493267.27      6806953.34      1493642.25      6807260.61
      1493985.97      6807307.48
#Sta/Elev= 30
  4522.1 2071.57  4573.1 2070.97  4587.5 2070.04  4609.7 2070.05    4637  2068.5
  4673.3  2067.9  4700.9 2067.44  4715.2 2066.24  4793.5 2063.13  4822.2 2062.81
  4865.2 2063.69  4879.6 2061.71  4900.4 2061.75  4912.7 2060.95    4913 2060.45
  4916.8 2060.95  4929.1 2061.94  4985.1 2061.07  5024.7 2061.89  5039.9 2063.51
  5060.1 2067.45  5063.7 2067.59  5080.3 2067.71  5140.9 2073.29  5174.4 2074.02
  5201.4 2075.99  5292.3 2079.36  5319.1 2081.61  5324.1 2080.58  5353.8 2083.58
#Mann= 5 ,-1 , 0
  4522.1     .07       0  4673.3     .16       0  4912.7     .07       0
  4916.8     .16       0  5063.7     .07       0
Bank Sta=4912.7,4916.8
XS Rating Curve= 0 ,0
Exp/Cntr=0.3,0.1

Type RM Length L Ch R = 1 ,8620    ,427,427,427
BEGIN DESCRIPTION:
Mapping XS 78c0ef6e
END DESCRIPTION:
XS GIS Cut Line= 3
      1493155.24      6807208.49      1493376.62       6807502.8
      1493889.66      6807461.13
#Sta/Elev= 30
  4617.3 2066.75  4630.3 2066.74  4653.2 2065.73  4709.5 2064.44    4724 2063.56
  4755.2 2063.06  4816.9 2060.93  4880.2 2057.37  4944.8 2057.64  4953.1 2057.29
  4967.1 2057.72  4973.9 2057.18    4994 2057.49    5004 2056.71    5012 2056.62
  5012.2 2056.12  5015.8 2056.12  5016.1 2056.62  5044.1 2057.85  5090.7 2058.71
  5103.6  2059.2  5134.4 2060.13  5144.5 2060.85  5164.5 2061.15  5214.7 2064.01
    5295 2066.35  5325.1 2066.67  5356.9 2068.13  5455.5 2069.29  5500.3 2071.44
#Mann= 7 ,-1 , 0
  4617.3     .07       0  4755.2     .16       0    5004     .07       0
    5012     .07       0  5016.1     .07       0  5090.7     .16       0
  5103.6     .07       0
Bank Sta=5012,5016.1
XS Rating Curve= 0 ,0
Exp/Cntr=0.3,0.1

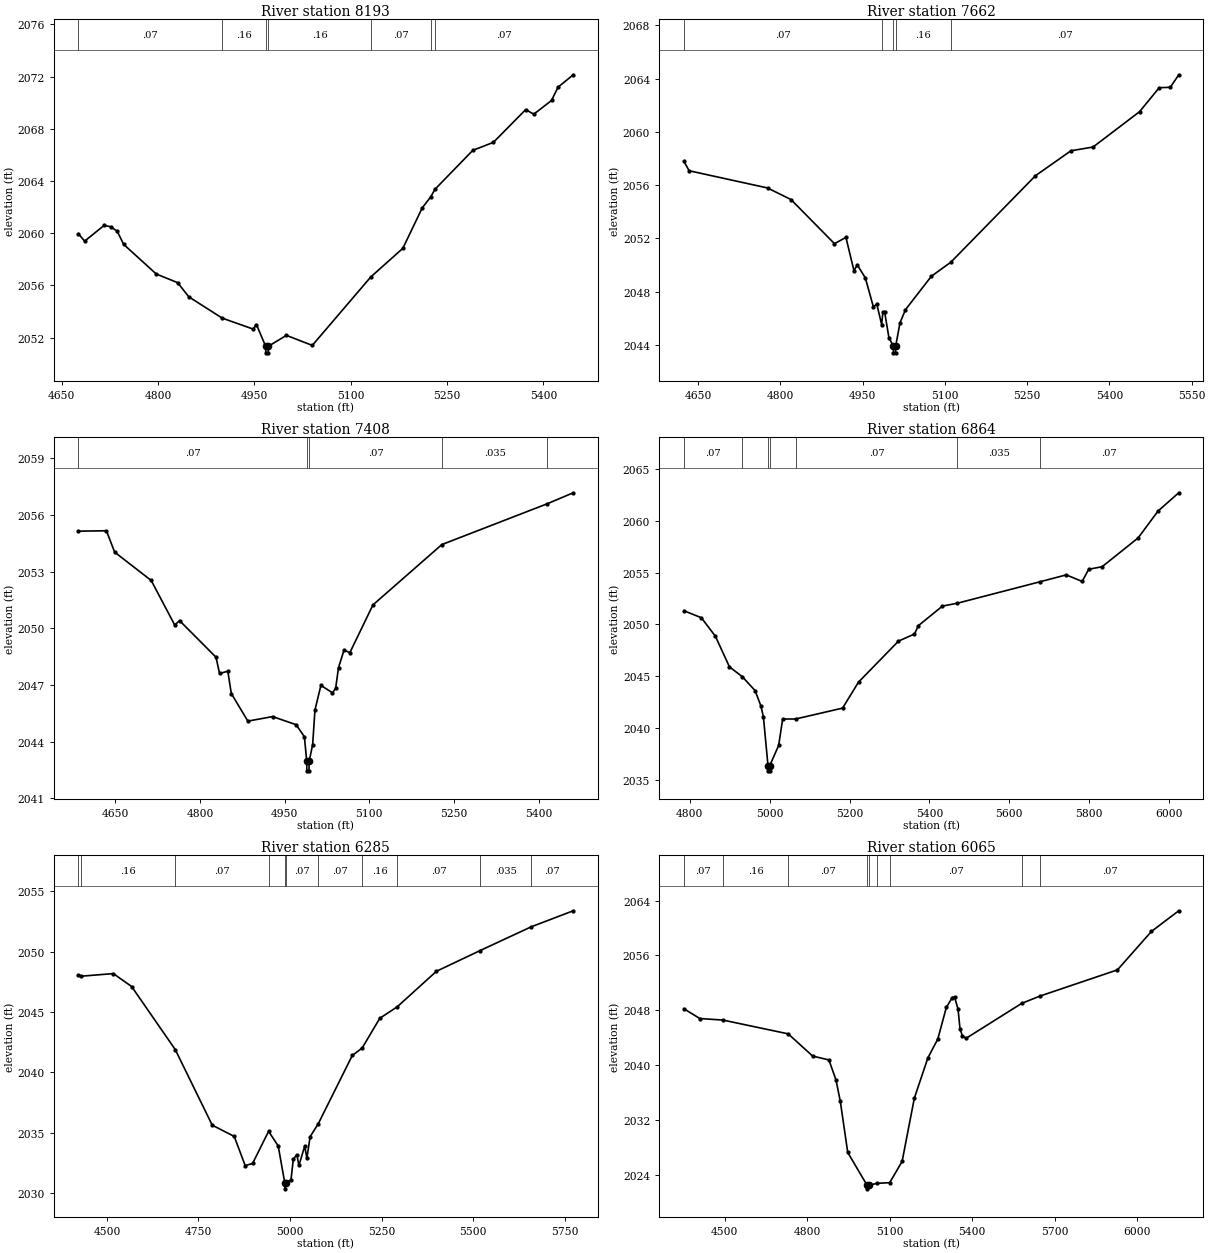
Type RM Length L Ch R = 1 ,8193    ,531,531,531
BEGIN DESCRIPTION:
Mapping XS e6cd5025
END DESCRIPTION:
XS GIS Cut Line= 3
       1493035.5      6807768.43      1493337.56       6807817.9
      1493798.54      6807765.82
#Sta/Elev= 30
  4676.4 2059.95    4686 2059.39  4716.4  2060.6  4726.6 2060.49  4736.7 2060.15
  4746.8 2059.14  4797.5 2056.87  4830.7 2056.21  4848.2 2055.12  4900.1 2053.49
  4948.3 2052.65  4953.4    2053  4967.7 2051.33  4967.9 2050.83  4971.6 2050.83
  4971.9 2051.33    5000 2052.17  5040.3  2051.4  5131.4 2056.65  5181.2 2058.84
  5211.4 2061.94  5224.4 2062.77  5231.3 2063.37  5290.1 2066.35  5322.1 2066.96
  5372.4 2069.47    5385 2069.12  5412.6 2070.17  5422.7 2071.19  5446.4 2072.14
#Mann= 7 ,-1 , 0
  4676.4     .07       0  4900.1     .16       0  4967.7     .07       0
  4971.9     .16       0  5131.4     .07       0  5224.4     .16       0
  5231.3     .07       0
Bank Sta=4967.7,4971.9
XS Rating Curve= 0 ,0
Exp/Cntr=0.3,0.1

Type RM Length L Ch R = 1 ,7662    ,254,254,254
BEGIN DESCRIPTION:
Mapping XS b5ed089a
END DESCRIPTION:
XS GIS Cut Line= 3
      1492902.67      6807927.28      1493194.33      6808143.43
      1493730.36      6808200.67
#Sta/Elev= 30
  4624.4 2057.78  4633.8 2057.08  4776.7 2055.79  4819.5 2054.92  4898.8 2051.61
  4919.7 2052.08  4934.3 2049.59  4940.5 2050.01  4955.1 2049.04  4969.7 2046.87
    4976 2047.08  4984.8 2045.54  4987.1 2046.48  4990.3 2046.48  4998.1 2044.55
  5006.1 2043.92  5006.4 2043.42  5010.1 2043.42  5010.4 2043.92  5018.3 2045.68
  5028.3 2046.66  5075.6 2049.17    5111 2050.22  5265.3 2056.71    5330 2058.58
  5370.3 2058.86    5455 2061.51  5490.9 2063.31  5511.1 2063.34  5526.5 2064.28
#Mann= 5 ,-1 , 0
  4624.4     .07       0  4984.8     .16       0  5006.1     .07       0
  5010.4     .16       0    5111     .07       0
Bank Sta=5006.1,5010.4
XS Rating Curve= 0 ,0
Exp/Cntr=0.3,0.1

Type RM Length L Ch R = 1 ,7408    ,544,544,544
BEGIN DESCRIPTION:
Mapping XS 13320ac3
END DESCRIPTION:
XS GIS Cut Line= 3
      1492788.04      6808125.17      1493126.62       6808375.2
      1493570.92      6808476.53
#Sta/Elev= 30
  4584.8 2055.14  4634.3 2055.16  4648.9 2054.03  4713.7 2052.53  4755.4 2050.17
  4763.8 2050.41  4828.5 2048.47  4834.8 2047.61  4849.4 2047.73  4855.6 2046.55
  4884.9 2045.09  4928.8 2045.33  4970.5  2044.9  4985.1 2044.26  4989.2 2042.96
  4989.4 2042.46  4993.2 2042.46  4993.5 2042.96  4999.7 2043.85  5003.8 2045.68
  5014.3 2046.98  5034.8 2046.59  5040.4 2046.82  5045.5 2047.92  5055.3 2048.85
  5065.6 2048.71  5106.6 2051.24  5228.6 2054.43  5415.4 2056.59  5461.4 2057.17
#Mann= 5 ,-1 , 0
  4584.8     .07       0  4989.2     .07       0  4993.5     .07       0
  5228.6    .035       0  5415.4     .07       0
Bank Sta=4989.2,4993.5
XS Rating Curve= 0 ,0
Exp/Cntr=0.3,0.1

Type RM Length L Ch R = 1 ,6864    ,579,579,579
BEGIN DESCRIPTION:
Mapping XS 43391a4e
END DESCRIPTION:
XS GIS Cut Line= 3
      1492630.01      6808463.01      1492762.47      6808631.98
      1493786.82      6808658.89
#Sta/Elev= 30
  4785.3 2051.31  4828.7 2050.64  4863.9 2048.86  4899.2  2045.9  4931.5 2044.95
  4963.4 2043.61  4977.8 2042.15  4984.2  2041.1  4995.8 2036.37  4996.1 2035.87
  4999.9 2035.87  5000.2 2036.37  5022.5 2038.32  5032.5 2040.87  5064.8 2040.87
  5182.6 2041.92  5222.6 2044.43  5322.6 2048.38  5362.7 2049.07  5372.7 2049.88
  5432.7 2051.76  5470.3 2052.04  5676.6  2054.1  5742.8 2054.77  5782.8 2054.14
  5799.1 2055.31  5832.8 2055.56  5922.8 2058.33  5972.9 2060.93  6024.7 2062.69
#Mann= 7 ,-1 , 0
  4785.3     .07       0  4931.5     .07       0  4995.8     .05       0
  5000.2     .07       0  5064.8     .07       0  5470.3    .035       0
  5676.6     .07       0
Bank Sta=4995.8,5000.2
XS Rating Curve= 0 ,0
Exp/Cntr=0.3,0.1

Type RM Length L Ch R = 1 ,6285    ,220,220,220
BEGIN DESCRIPTION:
Mapping XS 70186daf
END DESCRIPTION:
XS GIS Cut Line= 3
        1492230.        6809113.      1492807.29        6809094.
      1493479.99      6808713.01
#Sta/Elev= 30
  4422.4 2048.03  4428.4 2047.96  4517.5 2048.18  4567.5 2047.11  4686.6 2041.89
  4787.6 2035.63  4847.6  2034.7  4877.6 2032.28  4897.7 2032.46  4941.4 2035.12
  4967.7 2033.91  4985.5 2030.86  4985.8 2030.36  4989.9 2030.86  5002.6 2031.12
  5008.9 2032.81  5018.5 2033.19  5024.2  2032.3  5040.1  2033.9  5045.9 2032.89
  5054.8 2034.68  5076.4 2035.71  5169.9  2041.4  5196.9 2042.02    5245 2044.48
  5292.6 2045.43  5399.6 2048.37  5518.4 2050.08  5658.2 2052.05  5773.1 2053.38
#Mann= 11 ,-1 , 0
  4422.4     .07       0  4428.4     .16       0  4686.6     .07       0
  4941.4     .07       0  4985.5     .05       0  4989.9     .07       0
  5076.4     .07       0  5196.9     .16       0  5292.6     .07       0
  5518.4    .035       0  5658.2     .07       0
Bank Sta=4985.5,4989.9
XS Rating Curve= 0 ,0
Exp/Cntr=0.3,0.1

Type RM Length L Ch R = 1 ,6065    ,138,138,138
BEGIN DESCRIPTION:
Mapping XS 3c6f2f7b
END DESCRIPTION:
XS GIS Cut Line= 4
      1492169.38      6809189.43      1492675.04      6809327.62
      1493067.77      6809088.85       1493774.9      6808682.87
#Sta/Elev= 30
    4352 2048.23  4409.7 2046.81  4493.3 2046.59    4731 2044.58    4820 2041.34
  4879.1 2040.78  4904.9 2037.85  4920.4 2034.77  4947.5  2027.3  5018.1  2022.5
  5018.6    2022  5024.2  2022.5  5053.2  2022.8  5100.1  2022.9  5145.3    2026
  5189.7 2035.21    5239 2041.08    5275 2043.82    5306 2048.42  5327.3 2049.85
  5335.8 2049.98  5348.7 2048.16  5355.7 2045.34  5364.6 2044.25  5378.7 2043.95
  5580.5 2049.03  5647.8  2050.1  5928.2  2053.9  6051.9  2059.5  6151.2 2062.51
#Mann= 9 ,-1 , 0
    4352     .07       0  4493.3     .16       0    4731     .07       0
  5018.1     .05       0  5024.2     .07       0  5053.2     .16       0
  5100.1     .07       0  5580.5    .035       0  5647.8     .07       0
Bank Sta=5018.1,5024.2
XS Rating Curve= 0 ,0
Exp/Cntr=0.3,0.1

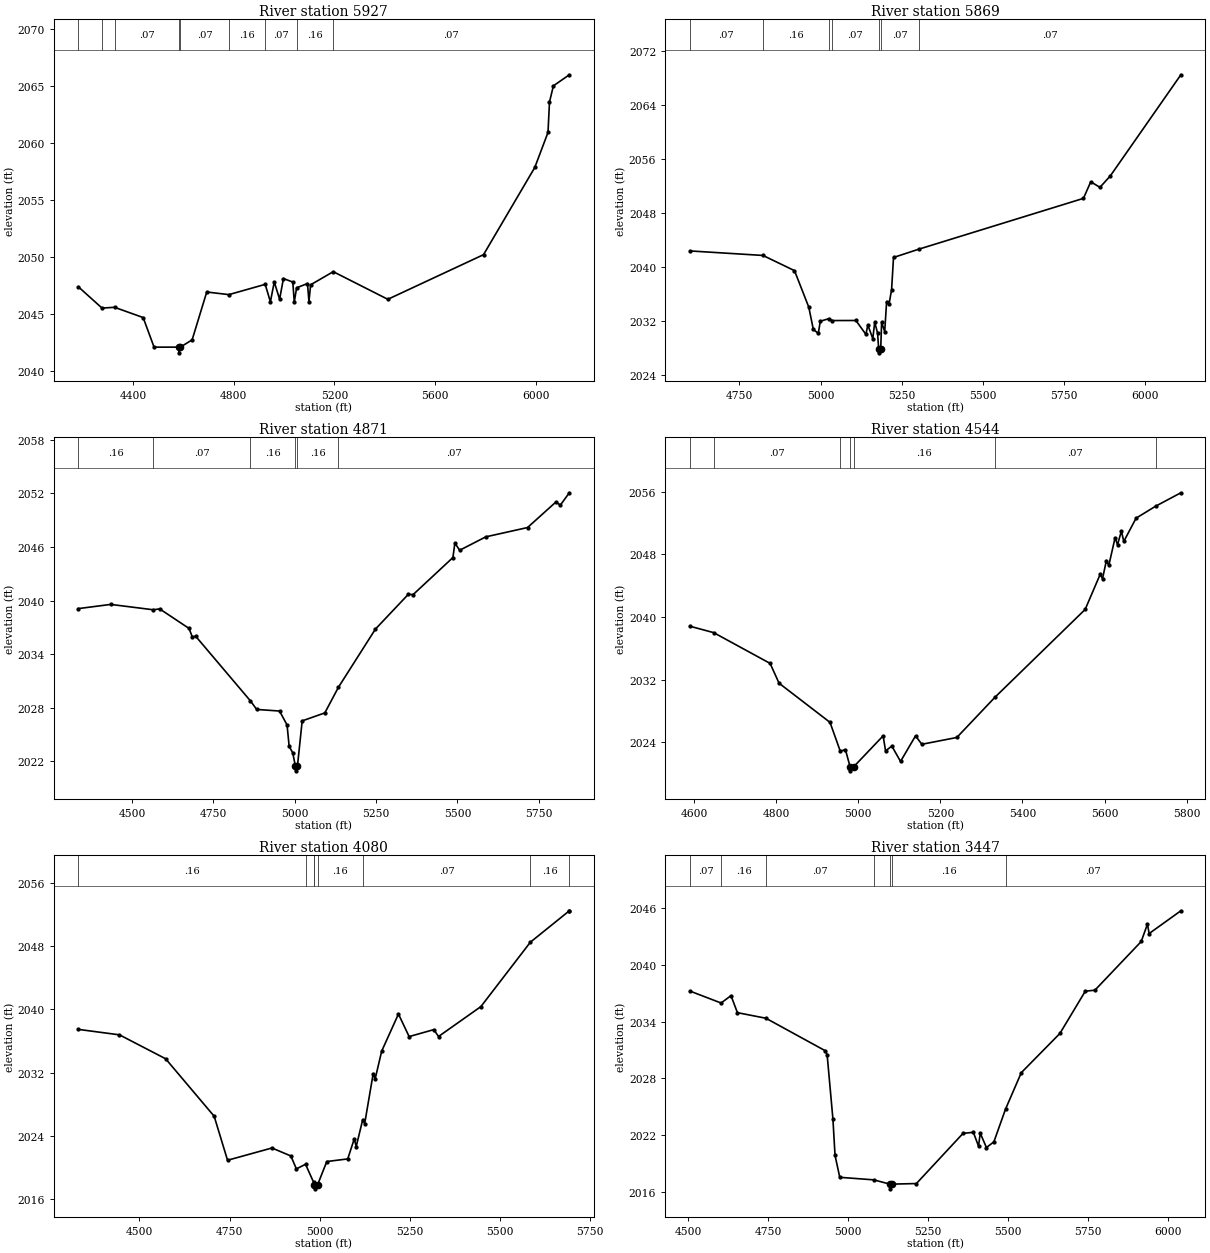
Type RM Length L Ch R = 1 ,5927    ,58,58,58
BEGIN DESCRIPTION:
NUBIA CREEK TRIBUTARY 1_3 5.0
END DESCRIPTION:
XS GIS Cut Line= 4
      1492123.11      6809281.14        1492530.        6809563.
      1492804.57      6809393.22      1493777.73      6808812.62
#Sta/Elev= 30
  4182.2 2047.42  4276.6 2045.55  4326.3 2045.62    4440 2044.72  4483.3 2042.13
  4581.6 2042.13  4582.1 2041.63  4587.7 2042.13  4634.6 2042.77  4692.6 2046.96
  4780.6 2046.73  4924.9 2047.63  4945.5  2046.1  4960.9 2047.84  4982.1 2046.33
  4997.3 2048.14  5034.5 2047.83  5040.4 2046.08  5049.7 2047.33  5092.9  2047.7
  5098.7 2046.11  5105.3 2047.59  5195.3 2048.74  5412.1 2046.32  5792.3 2050.23
    5996 2057.87  6048.5 2060.94  6054.4  2063.6  6069.9 2065.02  6133.2 2065.99
#Mann= 9 ,-1 , 0
  4182.2     .07       0  4276.6     .16       0  4326.3     .07       0
  4581.6     .05       0  4587.7     .07       0  4780.6     .16       0
  4924.9     .07       0  5049.7     .16       0  5195.3     .07       0
Bank Sta=4581.6,4587.7
XS Rating Curve= 0 ,0
Exp/Cntr=0.3,0.1

Type RM Length L Ch R = 1 ,5869    ,998,998,998
BEGIN DESCRIPTION:
Mapping XS 9001de6d
END DESCRIPTION:
XS GIS Cut Line= 4
      1492467.28      6809650.45      1492640.16      6809557.89
      1493232.61      6809191.14      1493790.84      6808923.39
#Sta/Elev= 30
  4597.1 2042.33  4822.3 2041.66  4919.4 2039.41  4963.5 2033.99  4977.3 2030.72
  4992.7 2030.11  4998.8 2031.92  5025.9 2032.31  5034.7 2032.02  5108.5 2032.03
  5139.3 2029.97  5145.2 2031.36  5160.5 2029.34  5166.4 2031.77  5175.2 2030.17
  5178.7 2027.74  5179.2 2027.24  5184.8 2027.74  5187.7 2031.76  5197.2 2030.38
  5203.1 2034.84  5210.5 2034.45  5218.4  2036.6  5224.3 2041.36  5302.3 2042.59
  5809.1 2050.11  5831.7 2052.57  5859.9 2051.74  5891.9 2053.44  6109.1 2068.41
#Mann= 7 ,-1 , 0
  4597.1     .07       0  4822.3     .16       0  5025.9     .07       0
  5034.7     .07       0  5178.7     .07       0  5184.8     .07       0
  5302.3     .07       0
Bank Sta=5178.7,5184.8
XS Rating Curve= 0 ,0
Exp/Cntr=0.3,0.1

Type RM Length L Ch R = 1 ,4871    ,327,327,327
BEGIN DESCRIPTION:
Mapping XS 2516ec3f
END DESCRIPTION:
XS GIS Cut Line= 4
      1492405.78      6809876.46      1492975.24      6809831.32
      1493277.32       6809695.9      1493624.56      6809199.36
#Sta/Elev= 30
  4335.3  2039.1  4434.8 2039.57  4565.7 2038.97  4585.3 2039.07  4675.6 2036.88
  4685.6 2035.92  4695.6 2036.02  4864.2 2028.77  4883.2 2027.82  4953.5 2027.64
  4976.6 2026.08    4983 2023.68    4994 2022.97  5002.2 2021.45  5002.7 2020.95
  5008.4 2021.45    5023 2026.54  5092.5 2027.43  5134.5 2030.31  5247.8  2036.8
    5349  2040.7  5363.8 2040.67  5485.9 2044.81    5492 2046.43  5506.8 2045.63
    5587 2047.13  5715.2 2048.17  5801.5    2051  5816.4  2050.7  5843.5 2052.06
#Mann= 6 ,-1 , 0
  4335.3     .16       0  4565.7     .07       0  4864.2     .16       0
  5002.2     .07       0  5008.4     .16       0  5134.5     .07       0
Bank Sta=5002.2,5008.4
XS Rating Curve= 0 ,0
Exp/Cntr=0.3,0.1

Type RM Length L Ch R = 1 ,4544    ,464,464,464
BEGIN DESCRIPTION:
NUBIA CREEK TRIBUTARY 1_3 2.0
END DESCRIPTION:
XS GIS Cut Line= 3
      1492578.36      6809899.02      1492984.14      6810026.79
      1493637.38      6810437.21
#Sta/Elev= 30
  4589.2 2038.81  4647.3 2037.99  4784.9 2034.06  4806.7 2031.53  4930.9 2026.53
  4955.9 2022.85  4968.5 2023.05  4979.9 2020.84  4980.4 2020.34  4988.3 2020.84
  5060.4 2024.81  5066.3 2022.89  5081.6  2023.5  5102.8 2021.54  5139.4 2024.81
  5154.7 2023.73    5240  2024.6  5333.4 2029.76  5552.8 2040.95  5589.3 2045.42
  5595.2 2044.89  5604.6  2047.2  5610.5 2046.58  5625.8 2050.12  5631.7 2049.21
  5641.1 2050.95    5647 2049.64    5677 2052.61  5724.4 2054.13  5786.1 2055.85
#Mann= 7 ,-1 , 0
  4589.2     .16       0  4647.3     .07       0  4955.9     .16       0
  4979.9     .07       0  4988.3     .16       0  5333.4     .07       0
  5724.4     .16       0
Bank Sta=4979.9,4988.3
XS Rating Curve= 0 ,0
Exp/Cntr=0.3,0.1

Type RM Length L Ch R = 1 ,4080    ,633,633,633
BEGIN DESCRIPTION:
Mapping XS cea23b8d
END DESCRIPTION:
XS GIS Cut Line= 3
      1492387.36      6810023.99      1492644.34      6810312.22
       1493540.1      6810697.61
#Sta/Elev= 30
  4330.6 2037.48  4444.8 2036.79  4572.7 2033.77  4707.3 2026.51  4744.4 2020.95
  4867.5  2022.5    4920 2021.49  4935.2 2019.86  4960.6 2020.44  4983.2 2018.15
  4985.4 2017.84  4985.9 2017.34  4993.9 2017.84  5019.6 2020.79  5077.6 2021.12
  5095.7 2023.65  5101.1 2022.68  5119.2 2026.09  5124.6 2025.58  5148.2  2031.9
  5153.6 2031.22  5171.7 2034.73  5218.2 2039.42  5247.8 2036.57  5316.2 2037.45
  5329.3 2036.58  5446.8 2040.36  5583.9 2048.49  5691.5 2052.44  5691.9 2052.46
#Mann= 8 ,-1 , 0
  4330.6     .16       0  4960.6     .07       0  4983.2     .16       0
  4985.4     .07       0  4993.9     .16       0  5119.2     .07       0
  5583.9     .16       0  5691.5     .07       0
Bank Sta=4985.4,4993.9
XS Rating Curve= 0 ,0
Exp/Cntr=0.3,0.1

Type RM Length L Ch R = 1 ,3447    ,867,867,867
BEGIN DESCRIPTION:
Mapping XS 35c07c29
END DESCRIPTION:
XS GIS Cut Line= 3
      1492227.67      6810100.38      1492279.75      6810506.66
      1493330.94       6810909.1
#Sta/Elev= 30
  4504.8 2037.23  4602.6 2035.96  4633.5 2036.74  4653.6 2034.94  4742.7 2034.35
  4928.8  2030.9  4934.1 2030.48  4952.2 2023.68  4958.8 2019.83  4973.6 2017.52
  5080.2 2017.25  5129.9  2016.8  5130.4  2016.3  5138.4  2016.8  5213.2 2016.86
    5359 2022.17  5391.2 2022.28  5407.4 2020.82  5412.8 2022.19  5432.1 2020.67
  5455.4 2021.27  5491.9 2024.74  5541.1 2028.59  5661.8 2032.74  5741.2 2037.21
  5771.3 2037.32  5916.1 2042.47  5935.5 2044.31  5940.8 2043.31    6040 2045.72
#Mann= 7 ,-1 , 0
  4504.8     .07       0  4602.6     .16       0  4742.7     .07       0
  5080.2     .16       0  5129.9     .07       0  5138.4     .16       0
  5491.9     .07       0
Bank Sta=5129.9,5138.4
XS Rating Curve= 0 ,0
Exp/Cntr=0.3,0.1