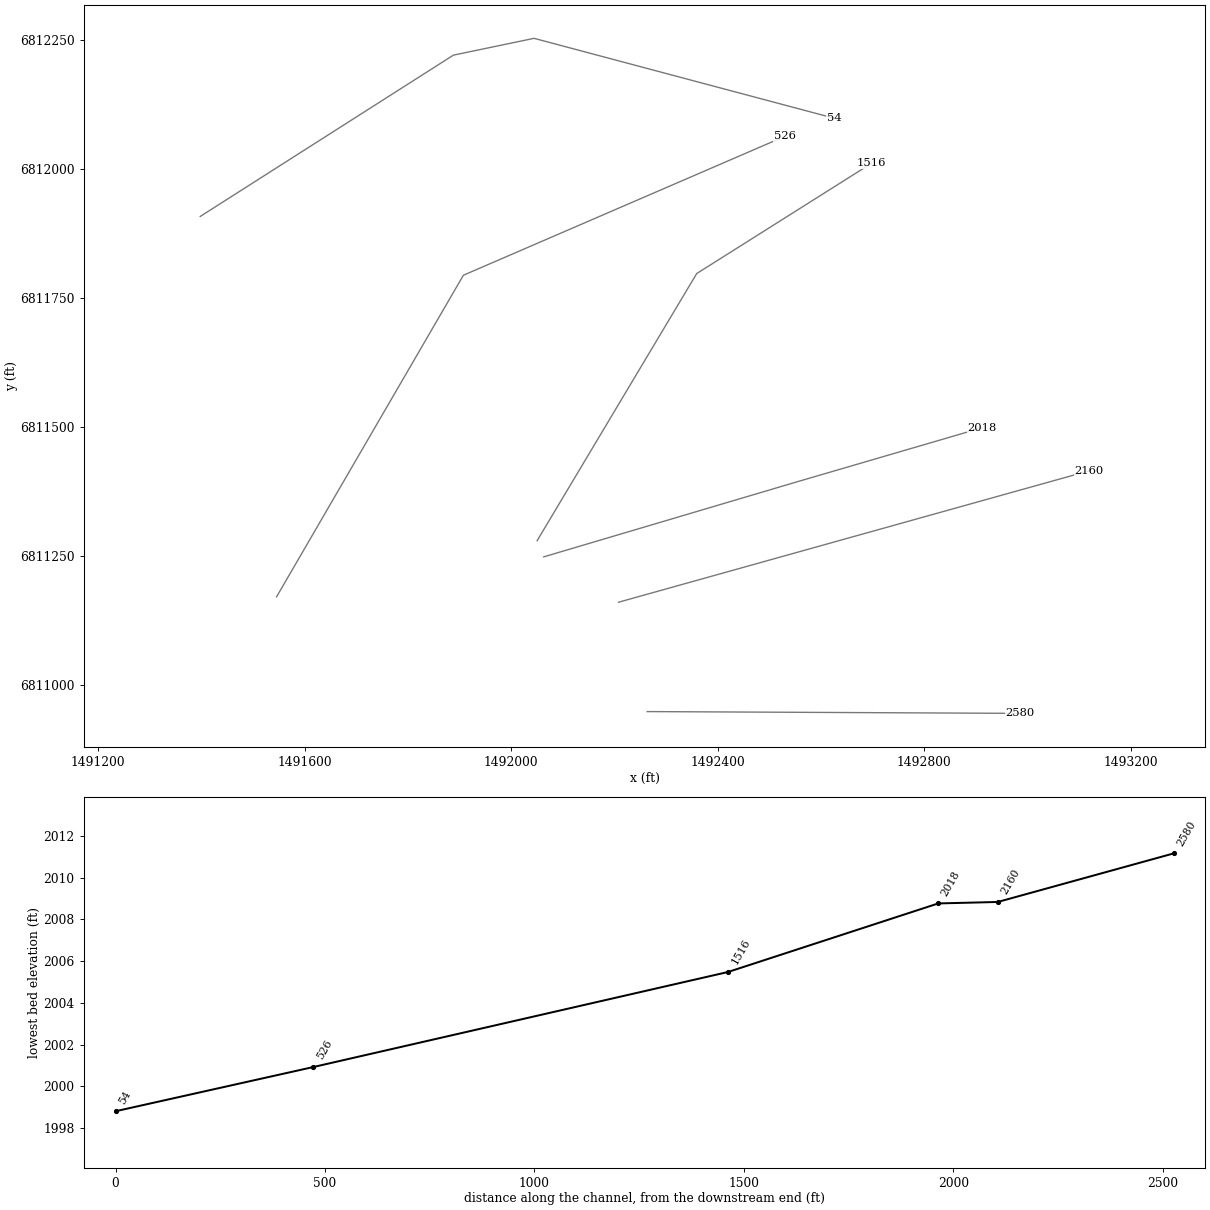
HEC-RAS study NUBIA CREEK TRIBUTARY 1_3.prj: NUBIA CREEK TRIBUTARY 1_3 Base Level Engineering

--- NUBIA CREEK TRIBUTARY 1_3.g01 (geometry) --- (continued)

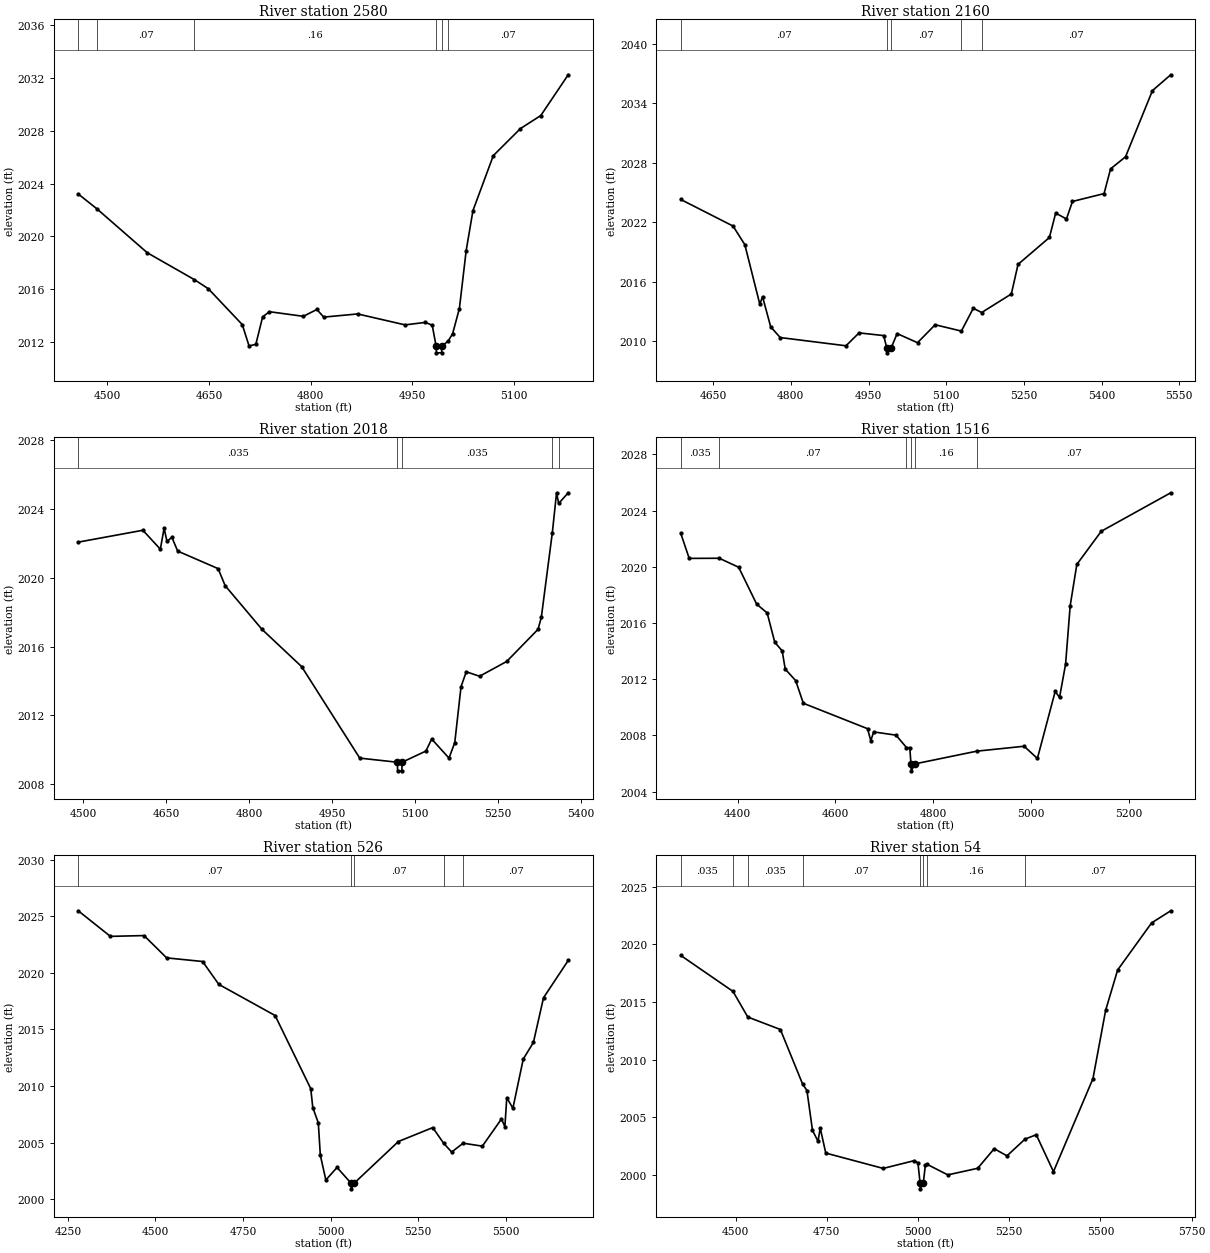
Type RM Length L Ch R = 1 ,2580    ,420,420,420
BEGIN DESCRIPTION:
Mapping XS 5de13b84
END DESCRIPTION:
XS GIS Cut Line= 2
      1492263.25      6810948.79      1492985.44      6810945.32
#Sta/Elev= 30
  4457.4 2023.22    4485 2022.09  4559.2 2018.76  4628.7 2016.72  4649.2 2016.03
  4699.2 2013.31  4709.2 2011.69  4719.2 2011.82  4729.2  2013.9  4739.2 2014.29
  4789.2 2013.94  4809.2 2014.46  4819.2 2013.88  4869.2 2014.12  4939.2 2013.29
  4969.2 2013.48  4979.2 2013.26  4984.9 2011.67  4985.4 2011.17  4992.9 2011.17
  4993.4 2011.67  5002.7 2012.07  5009.2 2012.62  5019.2 2014.53  5029.2 2018.93
  5039.2 2021.96  5069.2 2026.13  5109.2 2028.18  5139.2 2029.17  5179.6 2032.26
#Mann= 6 ,-1 , 0
  4457.4     .16       0    4485     .07       0  4628.7     .16       0
  4984.9     .07       0  4993.4     .16       0  5002.7     .07       0
Bank Sta=4984.9,4993.4
XS Rating Curve= 0 ,0
Exp/Cntr=0.3,0.1

Type RM Length L Ch R = 1 ,2160    ,142,142,142
BEGIN DESCRIPTION:
Mapping XS 0f6a4455
END DESCRIPTION:
XS GIS Cut Line= 2
      1492207.68      6811160.59      1493119.01      6811415.09
#Sta/Elev= 30
  4587.4 2024.29  4688.4 2021.61  4711.1 2019.74  4740.1 2013.73  4745.3  2014.5
  4761.1 2011.46  4779.5 2010.38  4906.5 2009.55  4931.7 2010.85  4979.2 2010.58
  4985.2 2009.34  4985.7 2008.84  4993.8 2009.34  5005.2 2010.78  5044.6 2009.86
  5078.7 2011.67  5129.3 2011.03  5152.3 2013.33  5168.5  2012.9  5225.8 2014.77
  5238.7 2017.75  5299.3 2020.46  5311.4 2022.92  5332.2 2022.32  5343.8 2024.09
  5404.8 2024.88  5417.4 2027.37  5446.3 2028.59  5498.3 2035.26  5533.6 2036.85
#Mann= 5 ,-1 , 0
  4587.4     .07       0  4985.2     .07       0  4993.8     .07       0
  5129.3     .16       0  5168.5     .07       0
Bank Sta=4985.2,4993.8
XS Rating Curve= 0 ,0
Exp/Cntr=0.3,0.1

Type RM Length L Ch R = 1 ,2018    ,502,502,502
BEGIN DESCRIPTION:
Mapping XS 56226cf2
END DESCRIPTION:
XS GIS Cut Line= 3
      1492062.84      6811248.46      1492551.45      6811393.24
      1492911.69      6811498.48
#Sta/Elev= 30
  4491.5 2022.07  4608.2 2022.76  4639.8 2021.66  4646.6 2022.88  4651.8 2022.11
  4660.6 2022.35  4671.1 2021.55  4744.1 2020.53  4756.8 2019.54  4823.3    2017
    4895 2014.83  4999.9 2009.51  5067.8 2009.27  5068.3 2008.77  5075.9 2008.77
  5076.4 2009.27  5119.4 2009.92  5129.8 2010.62  5161.1 2009.51  5171.5 2010.41
  5182.8 2013.66  5192.3 2014.53  5216.3 2014.27  5265.3 2015.13  5321.9    2017
  5327.8 2017.69  5347.7 2022.62  5355.3 2024.93  5359.2 2024.32  5376.4 2024.94
#Mann= 5 ,-1 , 0
  4491.5    .035       0  5067.8    .035       0  5076.4    .035       0
  5347.7     .07       0  5359.2    .035       0
Bank Sta=5067.8,5076.4
XS Rating Curve= 0 ,0
Exp/Cntr=0.3,0.1

Type RM Length L Ch R = 1 ,1516    ,990,990,990
BEGIN DESCRIPTION:
Mapping XS 47679db8
END DESCRIPTION:
XS GIS Cut Line= 3
      1492050.12      6811279.84      1492359.15       6811797.2
      1492697.54      6812010.63
#Sta/Elev= 30
  4283.5 2022.38  4300.8  2020.6  4362.3 2020.61    4402 2019.97  4438.9 2017.34
  4460.3 2016.72  4475.9 2014.63    4491 2014.02  4497.3 2012.72  4518.7  2011.9
  4534.3 2010.29  4665.7 2008.48  4672.4 2007.62  4678.2 2008.25    4724 2008.02
  4745.4 2007.14  4752.2 2007.12  4754.6 2005.98  4755.1 2005.48  4763.3 2005.98
  4889.2 2006.88  4986.2 2007.23  5013.3 2006.36  5049.8 2011.14  5058.6  2010.7
    5071 2013.07  5080.4 2017.23    5094 2020.17    5144 2022.53  5286.2 2025.27
#Mann= 6 ,-1 , 0
  4283.5    .035       0  4362.3     .07       0  4745.4     .16       0
  4754.6     .07       0  4763.3     .16       0  4889.2     .07       0
Bank Sta=4754.6,4763.3
XS Rating Curve= 0 ,0
Exp/Cntr=0.3,0.1

Type RM Length L Ch R = 1 ,526     ,472,472,472
BEGIN DESCRIPTION:
Mapping XS a1780e5a
END DESCRIPTION:
XS GIS Cut Line= 3
      1491545.37      6811171.01      1491907.24      6811793.93
      1492529.99        6812063.
#Sta/Elev= 30
  4279.6 2025.48  4371.4 2023.22  4467.5 2023.29    4532 2021.32  4634.6    2021
  4680.9 2018.98  4841.6 2016.23  4943.4 2009.77  4949.2  2008.1    4965 2006.74
  4970.7  2003.9  4986.5  2001.7  5018.4 2002.81  5058.5 2001.42    5059 2000.92
  5067.4 2001.42  5193.6  2005.1  5291.7 2006.33  5322.9 2004.94  5345.7 2004.17
  5378.4 2004.95  5433.3 2004.69  5487.8 2007.09  5497.6 2006.42    5503 2008.97
  5520.5 2008.04    5550 2012.38    5579 2013.85  5607.9  2017.8  5678.4 2021.09
#Mann= 5 ,-1 , 0
  4279.6     .07       0  5058.5     .07       0  5067.4     .07       0
  5322.9     .16       0  5378.4     .07       0
Bank Sta=5058.5,5067.4
XS Rating Curve= 0 ,0
Exp/Cntr=0.3,0.1

Type RM Length L Ch R = 1 ,54      ,0,0,0
BEGIN DESCRIPTION:
NUBIA CREEK TRIBUTARY 1_3 1.0
END DESCRIPTION:
XS GIS Cut Line= 4
      1491397.49      6811907.77      1491887.91      6812220.25
      1492044.16       6812252.8      1492625.59      6812098.01
#Sta/Elev= 30
  4349.9 2019.03  4493.1 2015.91  4533.6 2013.69  4622.9 2012.61  4683.6  2007.9
  4695.7 2007.32  4710.9 2003.87  4726.1 2002.92  4732.1 2004.07  4747.3  2001.9
  4904.7 2000.57  4989.3 2001.24  4999.9 2001.06  5005.7  1999.3  5006.2  1998.8
  5014.6  1999.3  5020.4  2000.9  5024.7 2000.93  5081.7 2000.01  5163.6 2000.58
  5208.9 2002.28  5243.8 2001.66  5293.4 2003.11  5324.1 2003.49  5371.3 2000.29
  5479.5 2008.35  5514.4 2014.29  5547.2 2017.77  5640.3 2021.85  5692.7  2022.9
#Mann= 8 ,-1 , 0
  4349.9    .035       0  4493.1     .07       0  4533.6    .035       0
  4683.6     .07       0  5005.7     .07       0  5014.6     .07       0
  5024.7     .16       0  5293.4     .07       0
Bank Sta=5005.7,5014.6
XS Rating Curve= 0 ,0
Exp/Cntr=0.3,0.1

Chan Stop Cuts=-1
Use User Specified Reach Order=0
Composite Channel Slope=5