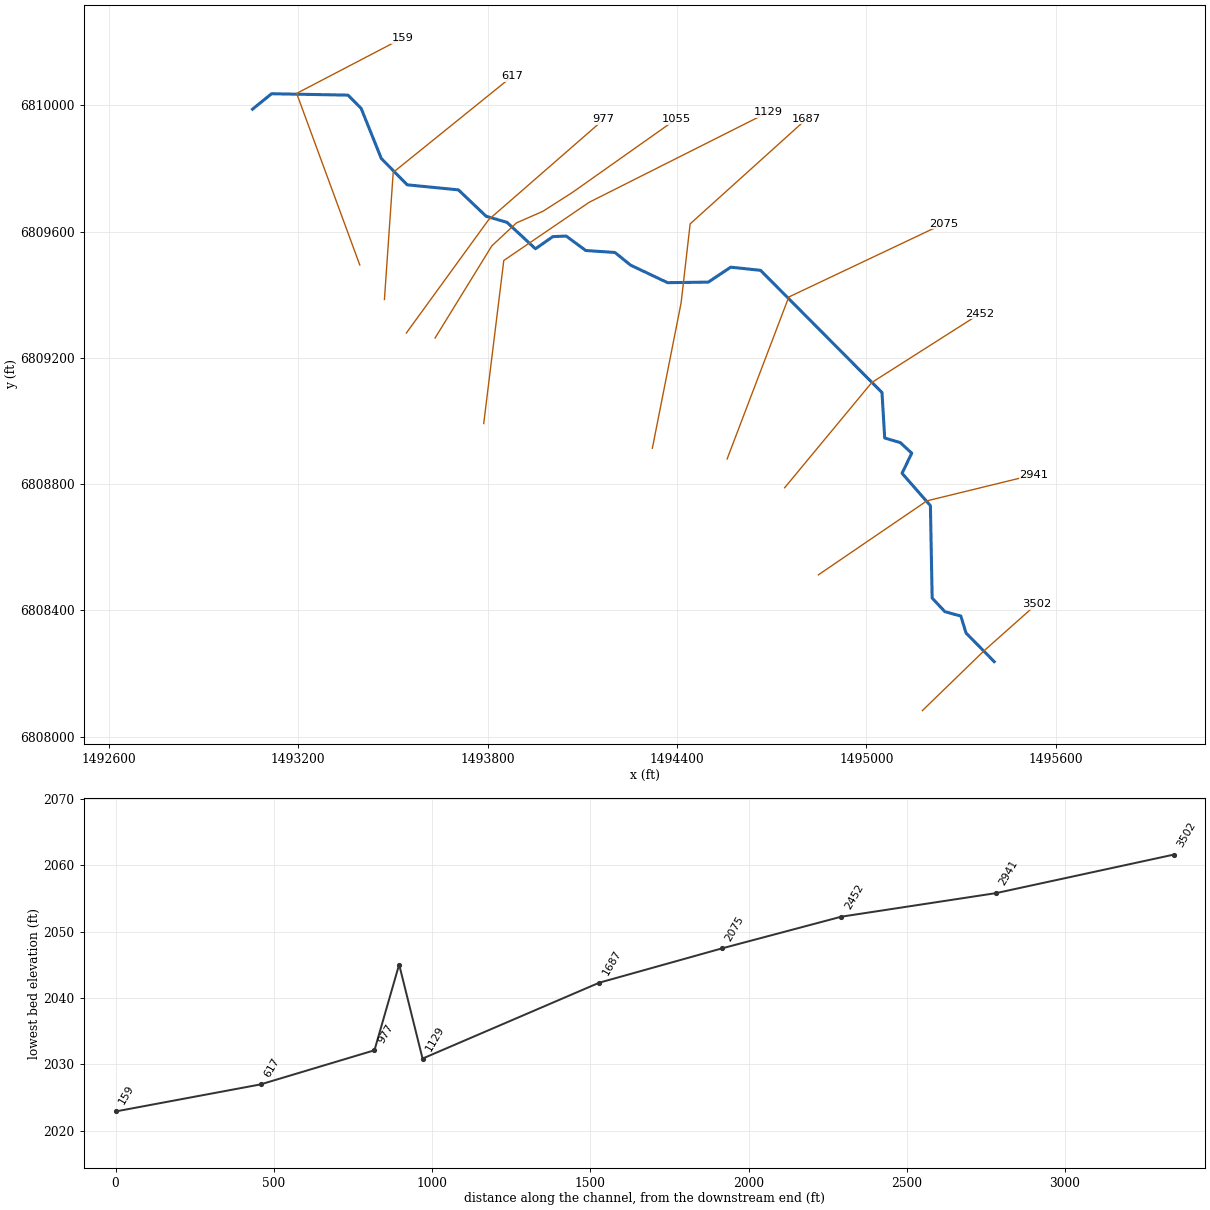
--- NUBIA CREEK TRIBUTARY 1_3_1.prj (project) ---

Proj Title=NUBIA CREEK TRIBUTARY 1_3_1 Base Level Engineering
Current Plan=p01
Default Exp/Contr=0.3,0.1
English Units
Geom File=g01
Flow File=f01
Plan File=p01
Y Axis Title=Elevation
X Axis Title(PF)=Main Channel Distance
X Axis Title(XS)=Station
BEGIN DESCRIPTION:
NUBIA CREEK TRIBUTARY 1_3_1
END DESCRIPTION:
DSS Export Rating Curves= 0
DSS Export Rating Curve Sorted= 0
DSS Export Volume Flow Curves= 0
DXF OffsetX= 0
DXF OffsetY= 0
DXF ScaleX= 1
DXF ScaleY= 10

--- NUBIA CREEK TRIBUTARY 1_3_1.p01 (plan) ---

Plan Title=Multiple Run
Short Identifier=Multiple
Geom File=g01
Flow File=f01
Subcritical Flow
K Sum by GR= 0
Std Step Tol= 0.01
Critical Tol= 0.01
Num of Std Step Trials= 20
Max Error Tol= 0.3
Flow Tol Ratio= 0.001
Split Flow NTrial= 30
Split Flow Tol= 0.02
Split Flow Ratio= 0.02
Log Output Level= 0
Friction Slope Method= 1
Unsteady Friction Slope Method= 2
Unsteady Bridges Friction Slope Method= 1
Parabolic Critical Depth
Global Vel Dist=  1 , 1 , 1
Global Log Level= 0
CheckData=True
Encroach Param= -1, 0, 0, 0
BEGIN DESCRIPTION:
Multiple Run
END DESCRIPTION:

--- NUBIA CREEK TRIBUTARY 1_3_1.f01 (steady flow) ---

Flow Title=Multiple
Program Version=4.10
Number of Profiles= 7
Profile Names=10-year,25-year,50-year,1pct_min,100-year,1pct_plu,500-year
River Rch & RM=NUBIA CREEK TRIB,Reach-1         ,3502
     395     572     726     459     917    1829    1476
Boundary for River Rch & Prof#=NUBIA CREEK TRIB,Reach-1         , 1
Up Type= 0
Dn Type= 3
Dn Slope=0.011
Boundary for River Rch & Prof#=NUBIA CREEK TRIB,Reach-1         , 2
Up Type= 0
Dn Type= 3
Dn Slope=0.011
Boundary for River Rch & Prof#=NUBIA CREEK TRIB,Reach-1         , 3
Up Type= 0
Dn Type= 3
Dn Slope=0.011
Boundary for River Rch & Prof#=NUBIA CREEK TRIB,Reach-1         , 4
Up Type= 0
Dn Type= 3
Dn Slope=0.011
Boundary for River Rch & Prof#=NUBIA CREEK TRIB,Reach-1         , 5
Up Type= 0
Dn Type= 3
Dn Slope=0.011
Boundary for River Rch & Prof#=NUBIA CREEK TRIB,Reach-1         , 6
Up Type= 0
Dn Type= 3
Dn Slope=0.011
Boundary for River Rch & Prof#=NUBIA CREEK TRIB,Reach-1         , 7
Up Type= 0
Dn Type= 3
Dn Slope=0.011
DSS Import GetInterval= 0
DSS Import GetPeak= 0
DSS Import FillOption= 0

--- NUBIA CREEK TRIBUTARY 1_3_1.g01 (geometry) ---

Geom Title=Existing Conditions

River Reach=NUBIA CREEK TRIB,Reach-1
Reach XY= 30
      1495405.00      6808238.00      1495315.83      6808328.58
      1495299.36      6808382.37      1495248.92      6808396.14
      1495208.48      6808439.26      1495202.93      6808732.15
      1495113.02      6808834.68      1495143.83      6808898.29
      1495107.44      6808931.98      1495058.13      6808946.31
      1495049.53      6809090.44      1494664.79      6809477.57
      1494570.28      6809487.62      1494499.06      6809440.25
      1494370.22      6809438.49      1494252.82      6809494.11
      1494203.42      6809534.17      1494110.97      6809540.38
      1494048.87      6809586.14      1494006.63      6809584.38
      1493951.60      6809545.83      1493861.05      6809629.80
      1493795.33      6809648.80      1493707.44      6809732.52
      1493545.18      6809748.47      1493463.13      6809831.93
      1493399.29      6809990.58      1493357.70      6810032.64
      1493115.40      6810037.04      1493055.00      6809988.00

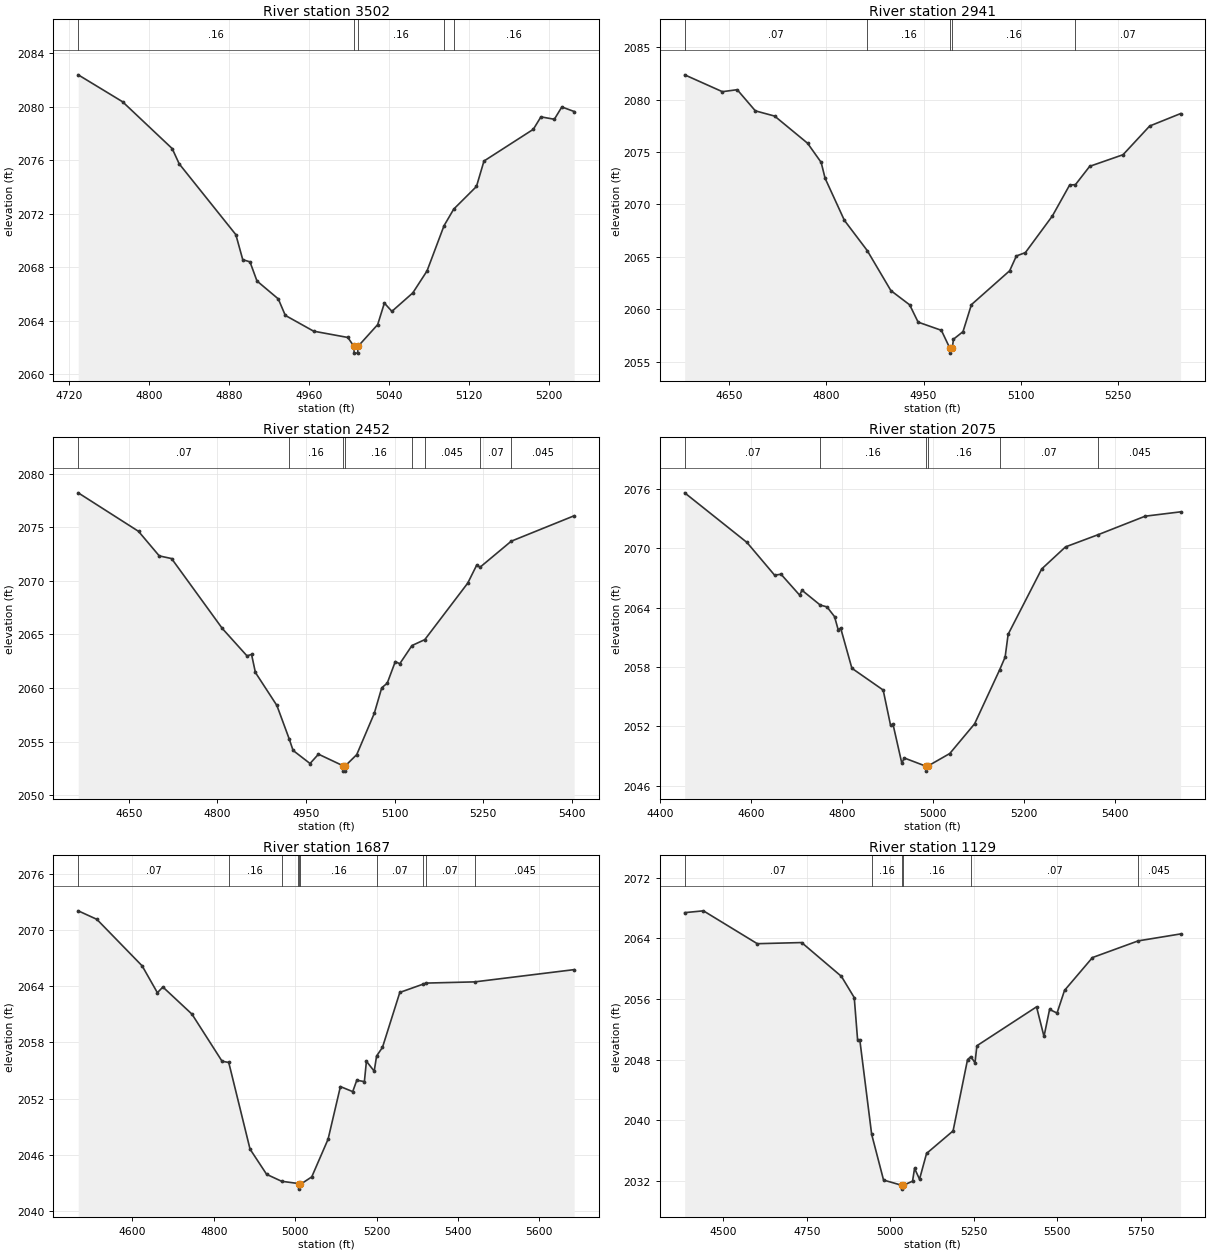
Type RM Length L Ch R = 1,3502,561,561,561
BEGIN DESCRIPTION:
NUBIA CREEK TRIBUTARY 1_3_1 6.0
END DESCRIPTION:
XS GIS Cut Line= 3
      1495177.49      6808082.84      1495371.65      6808271.18
      1495539.77      6808420.71
#Sta/Elev= 30
  4729.5 2082.38  4773.8 2080.37  4823.4 2076.87  4830.4 2075.73  4887.0 2070.44
  4893.9 2068.57  4901.1 2068.41  4908.1 2066.98  4929.4 2065.64  4936.4 2064.41
  4964.7 2063.23  4998.9 2062.76  5005.0 2062.09  5005.2 2061.59  5008.7 2061.59
  5009.0 2062.09  5028.7 2063.72  5035.4 2065.33  5042.9 2064.71  5063.8 2066.09
  5078.0 2067.73  5095.0 2071.11  5104.7 2072.35  5127.4 2074.04  5134.9 2075.94
  5184.2 2078.31  5191.8 2079.24  5205.2 2079.06  5212.7 2079.98  5225.0 2079.64
#Mann=5,-1,0
  4729.5    0.16       0  5005.0    0.07       0  5009.0    0.16       0
  5095.0    0.07       0  5104.7    0.16       0
Bank Sta=5005,5009
Exp/Cntr=0.3,0.1

Type RM Length L Ch R = 1,2941,489,489,489
BEGIN DESCRIPTION:
Mapping XS 8cc5a2c8
END DESCRIPTION:
XS GIS Cut Line= 3
      1494847.97      6808512.87      1495191.71      6808747.24
      1495531.39      6808830.22
#Sta/Elev= 30
  4581.2 2082.38  4639.4 2080.77  4662.3 2080.96  4690.3 2078.94  4720.1 2078.44
  4770.9 2075.85  4791.9 2074.02  4798.0 2072.50  4827.8 2068.48  4863.0 2065.60
  4899.6 2061.77  4928.6 2060.41  4941.6 2058.76  4977.5 2057.98  4990.4 2056.30
  4990.7 2055.80  4994.4 2056.30  4996.2 2057.13  5010.9 2057.85  5023.9 2060.43
  5083.0 2063.67  5093.3 2065.08  5107.2 2065.40  5148.9 2068.90  5175.6 2071.86
  5184.5 2071.89  5206.5 2073.64  5258.0 2074.75  5299.1 2077.49  5346.9 2078.68
#Mann=5,-1,0
  4581.2    0.07       0  4863.0    0.16       0  4990.4    0.07       0
  4994.4    0.16       0  5184.5    0.07       0
Bank Sta=4990.4,4994.4
Exp/Cntr=0.3,0.1

Type RM Length L Ch R = 1,2452,377,377,377
BEGIN DESCRIPTION:
Mapping XS e321390d
END DESCRIPTION:
XS GIS Cut Line= 3
      1494741.17      6808788.88      1495017.23      6809122.24
      1495360.49      6809340.68
#Sta/Elev= 30
  4564.2 2078.20  4666.3 2074.61  4701.4 2072.32  4722.3 2072.07  4808.2 2065.55
  4849.9 2063.00  4857.7 2063.13  4864.2 2061.45  4900.6 2058.37  4921.2 2055.29
  4928.0 2054.18  4956.7 2052.96  4971.0 2053.83  5012.6 2052.75  5012.9 2052.25
  5016.4 2052.25  5016.6 2052.75  5035.8 2053.79  5065.5 2057.64  5078.1 2060.02
  5087.4 2060.45  5101.1 2062.47  5108.6 2062.26  5129.3 2063.96  5151.0 2064.51
  5223.7 2069.78  5239.0 2071.47  5244.5 2071.26  5297.4 2073.69  5403.9 2076.06
#Mann=8,-1,0
  4564.2    0.07       0  4921.2    0.16       0  5012.6    0.07       0
  5016.6    0.16       0  5129.3    0.07       0  5151.0   0.045       0
  5244.5    0.07       0  5297.4   0.045       0
Bank Sta=5012.6,5016.6
Exp/Cntr=0.3,0.1

Type RM Length L Ch R = 1,2075,388,388,388
BEGIN DESCRIPTION:
Mapping XS 570498b5
END DESCRIPTION:
XS GIS Cut Line= 3
      1494558.89      6808880.03      1494754.21      6809393.08
      1495243.75      6809624.83
#Sta/Elev= 30
  4454.3 2075.59  4591.2 2070.58  4652.1 2067.27  4666.1 2067.37  4707.0 2065.26
  4712.3 2065.75  4752.5 2064.25  4767.2 2064.07  4783.8 2063.09  4791.9 2061.76
  4797.3 2061.93  4822.0 2057.87  4890.8 2055.67  4907.0 2052.12  4912.4 2052.22
  4931.8 2048.28  4937.1 2048.81  4984.6 2047.98  4984.9 2047.48  4988.6 2047.98
  5037.3 2049.26  5091.9 2052.26  5147.2 2057.74  5159.0 2059.00  5165.6 2061.30
  5239.4 2067.90  5291.8 2070.13  5364.0 2071.37  5466.9 2073.23  5544.9 2073.67
#Mann=6,-1,0
  4454.3    0.07       0  4752.5    0.16       0  4984.6    0.07       0
  4988.6    0.16       0  5147.2    0.07       0  5364.0   0.045       0
Bank Sta=4984.6,4988.6
Exp/Cntr=0.3,0.1

Type RM Length L Ch R = 1,1687,558,558,558
BEGIN DESCRIPTION:
Mapping XS 6e151fc4
END DESCRIPTION:
XS GIS Cut Line= 4
      1494321.92      6808913.91      1494413.07      6809374.85
      1494441.71      6809624.85      1494810.73      6809957.48
#Sta/Elev= 30
  4467.0 2072.08  4512.8 2071.17  4624.1 2066.19  4661.5 2063.32  4675.0 2063.93
  4746.4 2061.03  4820.4 2055.99  4836.8 2055.86  4889.1 2046.59  4929.9 2043.89
  4966.7 2043.15  5006.1 2042.92  5008.5 2042.81  5008.7 2042.31  5012.5 2042.81
  5040.7 2043.62  5080.8 2047.65  5111.1 2053.28  5141.3 2052.74  5151.4 2053.96
  5170.0 2053.81  5175.0 2055.99  5194.1 2054.93  5200.0 2056.55  5214.4 2057.47
  5257.0 2063.35  5315.1 2064.25  5320.7 2064.35  5441.2 2064.48  5685.3 2065.79
#Mann=10,-1,0
  4467.0    0.07       0  4836.8    0.16       0  4966.7    0.07       0
  5006.1    0.16       0  5008.5    0.07       0  5012.5    0.16       0
  5200.0    0.07       0  5315.1    0.16       0  5320.7    0.07       0
  5441.2   0.045       0
Bank Sta=5008.5,5012.5
Exp/Cntr=0.3,0.1

Type RM Length L Ch R = 1,1129,74,74,74
BEGIN DESCRIPTION:
Mapping XS 5fed3e61
END DESCRIPTION:
XS GIS Cut Line= 4
      1493787.64      6808992.29      1493851.21      6809508.75
      1494121.84      6809693.21      1494690.38      6809979.22
#Sta/Elev= 30
  4384.5 2067.40  4440.6 2067.64  4601.8 2063.30  4734.6 2063.45  4853.7 2058.98
  4892.0 2056.18  4902.0 2050.61  4908.6 2050.61  4944.1 2038.13  4979.7 2032.09
  5034.6 2031.39  5034.9 2030.89  5038.6 2031.39  5066.5 2031.94  5072.5 2033.63
  5087.4 2032.20  5108.4 2035.60  5187.8 2038.58  5231.1 2048.00  5241.1 2048.39
  5253.4 2047.56  5259.0 2049.82  5437.6 2054.96  5459.9 2051.05  5476.6 2054.62
  5499.0 2054.14  5521.3 2057.13  5605.0 2061.47  5741.7 2063.67  5868.8 2064.59
#Mann=6,-1,0
  4384.5    0.07       0  4944.1    0.16       0  5034.6    0.07       0
  5038.6    0.16       0  5241.1    0.07       0  5741.7   0.045       0
Bank Sta=5034.6,5038.6
Exp/Cntr=0.3,0.1

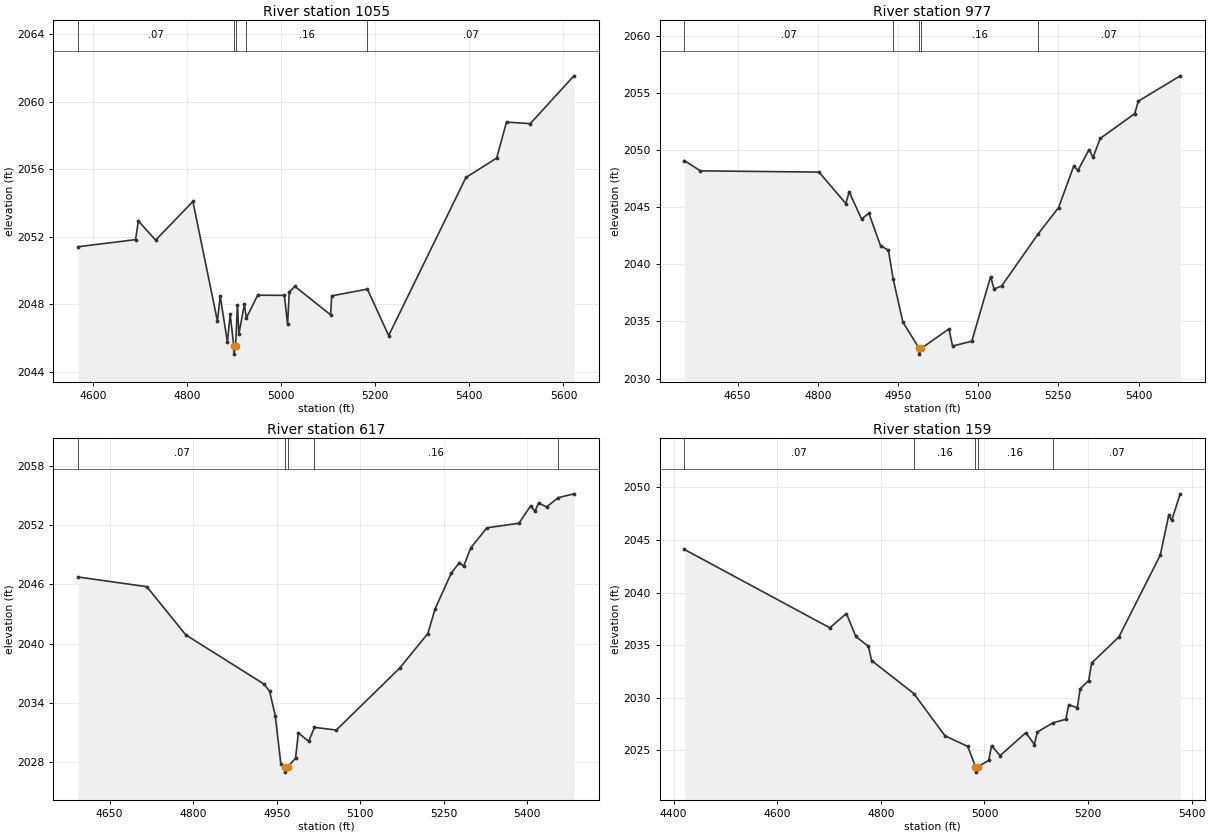
Type RM Length L Ch R = 1,1055,78,78,78
BEGIN DESCRIPTION:
Mapping XS 46bd56c2
END DESCRIPTION:
XS GIS Cut Line= 6
      1493633.55      6809263.29      1493813.24      6809554.97
      1493891.37      6809627.88      1493974.70      6809664.34
      1494068.45      6809724.24      1494396.58      6809956.02
#Sta/Elev= 30
  4568.9 2051.41  4690.8 2051.83  4696.7 2052.94  4733.4 2051.80  4812.6 2054.09
  4864.7 2047.01  4870.6 2048.48  4886.0 2045.77  4891.8 2047.43  4899.4 2045.55
  4899.6 2045.05  4903.4 2045.55  4907.2 2047.98  4910.3 2046.24  4922.0 2048.00
  4926.2 2047.19  4950.3 2048.54  5007.0 2048.53  5013.8 2046.81  5017.4 2048.73
  5029.4 2049.06  5105.1 2047.38  5107.6 2048.50  5183.4 2048.90  5228.6 2046.15
  5392.8 2055.51  5458.1 2056.66  5479.0 2058.79  5529.5 2058.70  5622.3 2061.53
#Mann=5,-1,0
  4568.9    0.07       0  4899.4    0.07       0  4903.4    0.07       0
  4926.2    0.16       0  5183.4    0.07       0
Bank Sta=4899.4,4903.4
Exp/Cntr=0.3,0.1

Type RM Length L Ch R = 1,977,360,360,360
BEGIN DESCRIPTION:
Mapping XS 68cb4c39
END DESCRIPTION:
XS GIS Cut Line= 3
      1493542.39      6809278.91      1493803.24      6809637.94
      1494167.84      6809955.66
#Sta/Elev= 30
  4550.5 2049.06  4580.4 2048.17  4802.2 2048.06  4852.4 2045.31  4858.6 2046.34
  4881.8 2043.96  4895.5 2044.46  4917.4 2041.62  4932.1 2041.23  4940.9 2038.73
  4959.1 2034.95  4989.5 2032.64  4989.8 2032.14  4993.5 2032.64  5045.3 2034.35
  5052.0 2032.85  5088.1 2033.27  5123.2 2038.91  5129.8 2037.83  5144.1 2038.11
  5212.4 2042.67  5250.4 2044.96  5278.9 2048.60  5286.5 2048.20  5307.4 2050.03
  5315.0 2049.36  5328.2 2051.00  5392.8 2053.17  5399.5 2054.26  5477.9 2056.48
#Mann=5,-1,0
  4550.5    0.07       0  4940.9    0.16       0  4989.5    0.07       0
  4993.5    0.16       0  5212.4    0.07       0
Bank Sta=4989.5,4993.5
Exp/Cntr=0.3,0.1

Type RM Length L Ch R = 1,617,458,458,458
BEGIN DESCRIPTION:
Mapping XS a633adbd
END DESCRIPTION:
XS GIS Cut Line= 3
      1493473.07      6809385.18      1493500.85      6809787.91
      1493879.00      6810093.21
#Sta/Elev= 30
  4593.8 2046.75  4716.9 2045.77  4787.1 2040.88  4927.4 2035.91  4937.4 2035.17
  4947.5 2032.70  4957.5 2027.82  4965.5 2027.50  4965.8 2027.00  4969.5 2027.50
  4983.9 2028.41  4988.9 2030.97  5007.4 2030.12  5017.8 2031.53  5057.0 2031.26
  5170.6 2037.52  5221.3 2041.03  5234.5 2043.55  5263.3 2047.14  5277.7 2048.20
  5285.6 2047.86  5298.5 2049.71  5327.3 2051.73  5384.8 2052.19  5405.6 2053.94
  5413.6 2053.41  5420.0 2054.25  5434.4 2053.84  5455.2 2054.78  5483.5 2055.17
#Mann=5,-1,0
  4593.8    0.07       0  4965.5    0.07       0  4969.5    0.07       0
  5017.8    0.16       0  5455.2    0.07       0
Bank Sta=4965.5,4969.5
Exp/Cntr=0.3,0.1

Type RM Length L Ch R = 1,159,0,0,0
BEGIN DESCRIPTION:
NUBIA CREEK TRIBUTARY 1_3_1 1.0
END DESCRIPTION:
XS GIS Cut Line= 3
      1493394.94      6809494.52      1493194.96      6810038.11
      1493529.96      6810212.98
#Sta/Elev= 30
  4420.8 2044.10  4701.5 2036.65  4733.5 2038.01  4751.6 2035.83  4776.1 2034.88
  4782.1 2033.54  4863.7 2030.40  4923.7 2026.39  4967.9 2025.37  4982.7 2023.43
  4982.9 2022.93  4986.7 2023.43  5008.1 2024.04  5013.8 2025.44  5030.2 2024.50
  5080.0 2026.68  5096.5 2025.55  5102.1 2026.75  5132.7 2027.63  5157.1 2027.95
  5162.7 2029.34  5179.2 2029.05  5184.8 2030.85  5201.3 2031.64  5206.9 2033.30
  5259.5 2035.78  5339.4 2043.56  5355.9 2047.37  5361.5 2046.86  5377.9 2049.39
#Mann=5,-1,0
  4420.8    0.07       0  4863.7    0.16       0  4982.7    0.07       0
  4986.7    0.16       0  5132.7    0.07       0
Bank Sta=4982.7,4986.7
Exp/Cntr=0.3,0.1

Chan Stop Cuts=-1