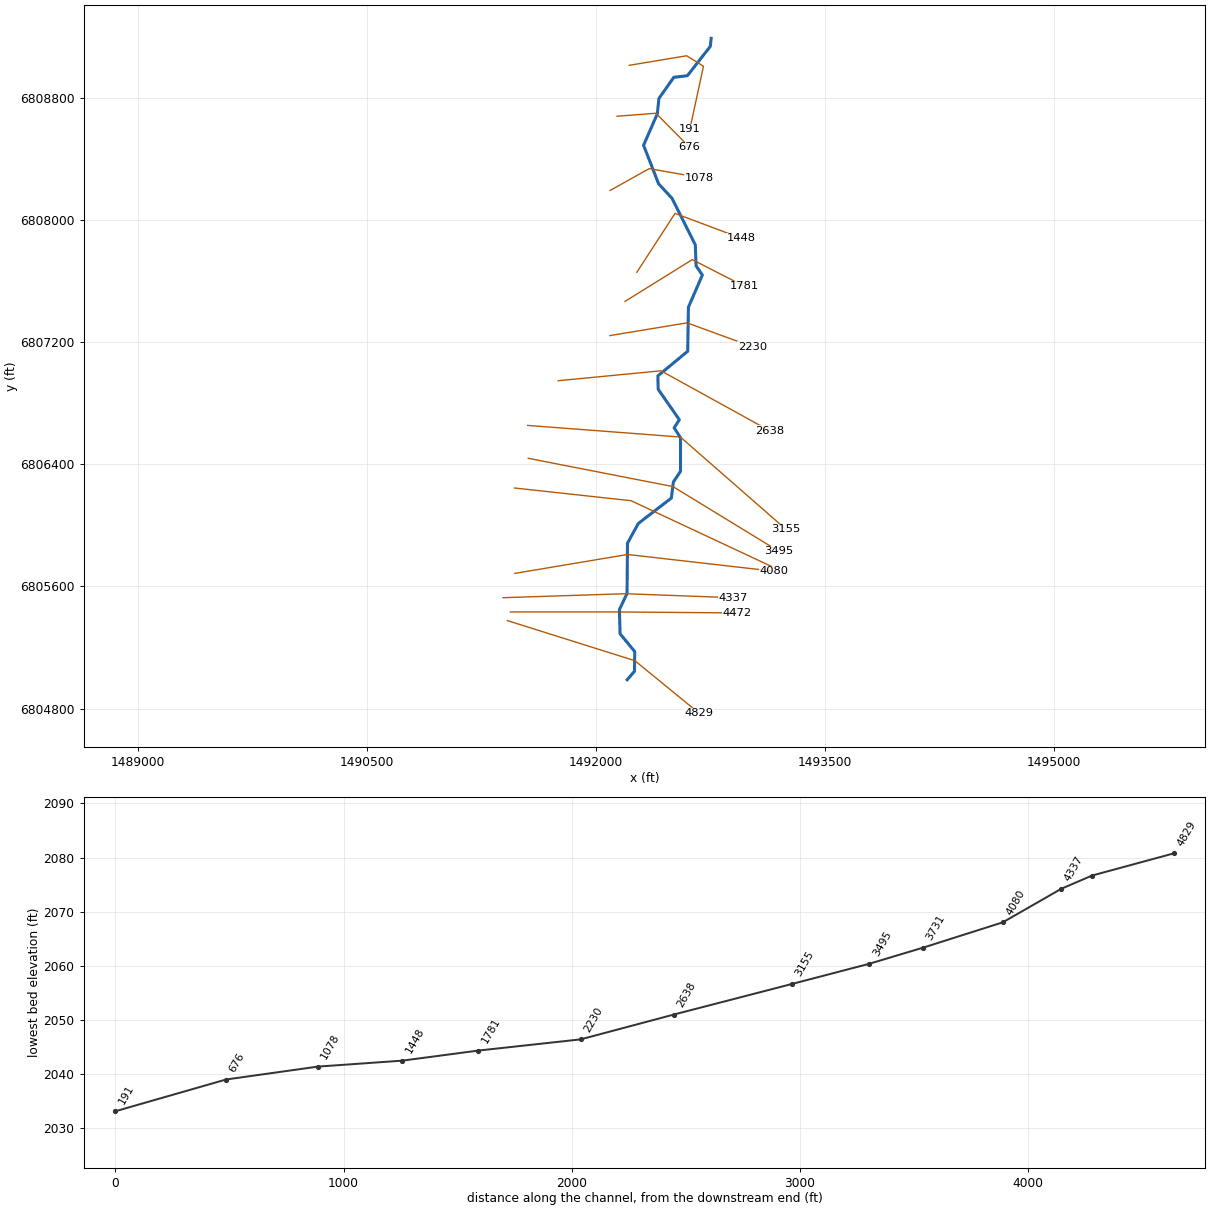
--- NUBIA CREEK TRIBUTARY 1_3_2.prj (project) ---

Proj Title=NUBIA CREEK TRIBUTARY 1_3_2 Base Level Engineering
Current Plan=p01
Default Exp/Contr=0.3,0.1
English Units
Geom File=g01
Flow File=f01
Plan File=p01
Y Axis Title=Elevation
X Axis Title(PF)=Main Channel Distance
X Axis Title(XS)=Station
BEGIN DESCRIPTION:
NUBIA CREEK TRIBUTARY 1_3_2
END DESCRIPTION:
DSS Export Rating Curves= 0
DSS Export Rating Curve Sorted= 0
DSS Export Volume Flow Curves= 0
DXF OffsetX= 0
DXF OffsetY= 0
DXF ScaleX= 1
DXF ScaleY= 10

--- NUBIA CREEK TRIBUTARY 1_3_2.p01 (plan) ---

Plan Title=Multiple Run
Short Identifier=Multiple
Geom File=g01
Flow File=f01
Subcritical Flow
K Sum by GR= 0
Std Step Tol= 0.01
Critical Tol= 0.01
Num of Std Step Trials= 20
Max Error Tol= 0.3
Flow Tol Ratio= 0.001
Split Flow NTrial= 30
Split Flow Tol= 0.02
Split Flow Ratio= 0.02
Log Output Level= 0
Friction Slope Method= 1
Unsteady Friction Slope Method= 2
Unsteady Bridges Friction Slope Method= 1
Parabolic Critical Depth
Global Vel Dist=  1 , 1 , 1
Global Log Level= 0
CheckData=True
Encroach Param= -1, 0, 0, 0
BEGIN DESCRIPTION:
Multiple Run
END DESCRIPTION:

--- NUBIA CREEK TRIBUTARY 1_3_2.f01 (steady flow) ---

Flow Title=Multiple
Program Version=4.10
Number of Profiles= 7
Profile Names=10-year,25-year,50-year,1pct_min,100-year,1pct_plu,500-year
River Rch & RM=NUBIA CREEK TRIB,Reach-1         ,4829
     395     575     731     464     926    1847    1498
Boundary for River Rch & Prof#=NUBIA CREEK TRIB,Reach-1         , 1
Up Type= 0
Dn Type= 3
Dn Slope=0.012
Boundary for River Rch & Prof#=NUBIA CREEK TRIB,Reach-1         , 2
Up Type= 0
Dn Type= 3
Dn Slope=0.012
Boundary for River Rch & Prof#=NUBIA CREEK TRIB,Reach-1         , 3
Up Type= 0
Dn Type= 3
Dn Slope=0.012
Boundary for River Rch & Prof#=NUBIA CREEK TRIB,Reach-1         , 4
Up Type= 0
Dn Type= 3
Dn Slope=0.012
Boundary for River Rch & Prof#=NUBIA CREEK TRIB,Reach-1         , 5
Up Type= 0
Dn Type= 3
Dn Slope=0.012
Boundary for River Rch & Prof#=NUBIA CREEK TRIB,Reach-1         , 6
Up Type= 0
Dn Type= 3
Dn Slope=0.012
Boundary for River Rch & Prof#=NUBIA CREEK TRIB,Reach-1         , 7
Up Type= 0
Dn Type= 3
Dn Slope=0.012
DSS Import GetInterval= 0
DSS Import GetPeak= 0
DSS Import FillOption= 0

--- NUBIA CREEK TRIBUTARY 1_3_2.g01 (geometry) ---

Geom Title=Existing Conditions

River Reach=NUBIA CREEK TRIB,Reach-1
Reach XY= 30
      1492205.00      6804988.00      1492253.12      6805043.79
      1492254.63      6805172.84      1492158.55      6805289.47
      1492154.54      6805448.18      1492204.48      6805553.22
      1492207.24      6805882.07      1492278.01      6806011.47
      1492494.61      6806177.90      1492507.36      6806282.02
      1492554.48      6806353.22      1492554.35      6806572.84
      1492512.80      6806638.10      1492546.76      6806691.23
      1492408.47      6806889.50      1492405.93      6806977.52
      1492601.55      6807139.25      1492606.22      6807427.50
      1492697.44      6807638.00      1492656.40      6807698.44
      1492651.24      6807836.44      1492499.15      6808140.29
      1492410.84      6808235.71      1492312.56      6808488.00
      1492402.64      6808693.98      1492412.88      6808794.17
      1492510.54      6808932.71      1492599.46      6808943.29
      1492749.69      6809135.48      1492755.00      6809188.00

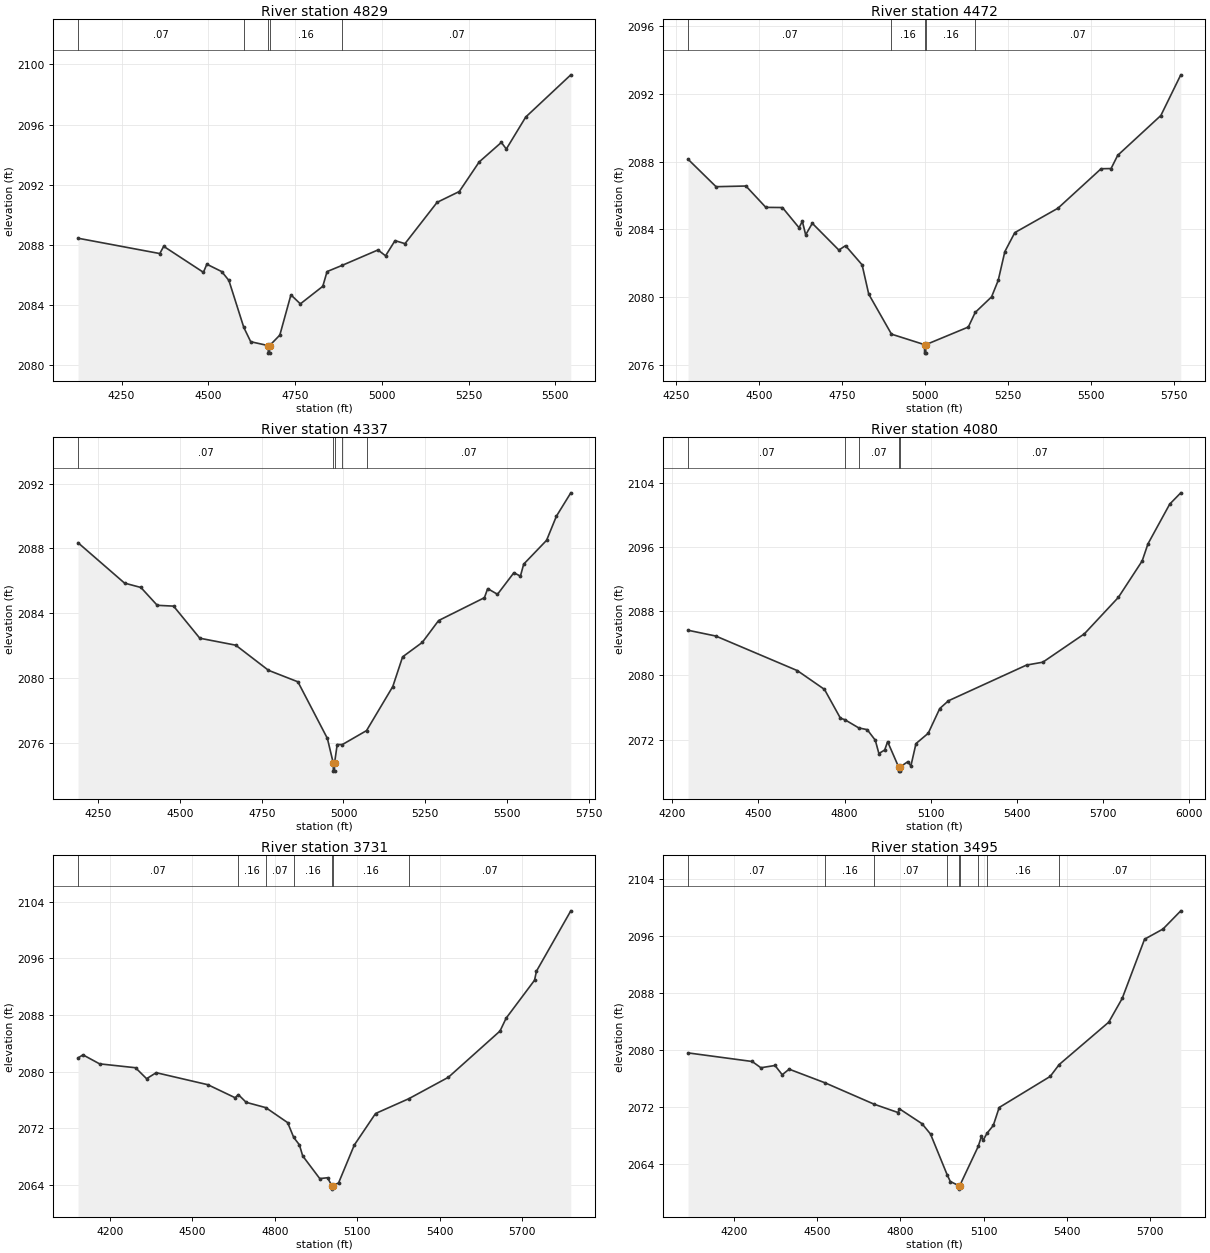
Type RM Length L Ch R = 1,4829,357,357,357
BEGIN DESCRIPTION:
NUBIA CREEK TRIBUTARY 1_3_2 4.0
END DESCRIPTION:
XS GIS Cut Line= 3
      1491420.25      6805375.75      1492255.40      6805113.02
      1492677.23      6804768.10
#Sta/Elev= 30
  4124.5 2088.43  4360.1 2087.41  4371.4 2087.89  4485.9 2086.16  4495.7 2086.70
  4538.6 2086.21  4559.3 2085.62  4602.3 2082.49  4622.2 2081.54  4672.6 2081.28
  4672.9 2080.78  4676.4 2080.78  4676.6 2081.28  4706.1 2081.98  4738.1 2084.66
  4765.3 2084.06  4830.0 2085.23  4842.3 2086.21  4885.4 2086.62  4989.1 2087.65
  5010.9 2087.26  5038.2 2088.27  5066.9 2088.07  5159.5 2090.82  5223.4 2091.54
  5280.8 2093.51  5344.7 2094.81  5359.0 2094.37  5415.0 2096.50  5544.9 2099.31
#Mann=5,-1,0
  4124.5    0.07       0  4602.3    0.16       0  4672.6    0.07       0
  4676.6    0.16       0  4885.4    0.07       0
Bank Sta=4672.6,4676.6
Exp/Cntr=0.3,0.1

Type RM Length L Ch R = 1,4472,135,135,135
BEGIN DESCRIPTION:
Mapping XS e617d495
END DESCRIPTION:
XS GIS Cut Line= 3
      1491440.65      6805432.20      1492148.12      6805432.20
      1492925.02      6805425.69
#Sta/Elev= 30
  4286.0 2088.14  4370.4 2086.52  4460.4 2086.56  4520.4 2085.30  4570.4 2085.29
  4620.4 2084.10  4630.4 2084.48  4640.4 2083.68  4660.4 2084.36  4740.4 2082.78
  4760.4 2083.04  4810.4 2081.91  4830.4 2080.18  4898.9 2077.82  4998.4 2077.20
  4998.6 2076.70  5002.1 2076.70  5002.4 2077.20  5130.4 2078.24  5151.1 2079.10
  5200.4 2080.02  5220.4 2080.99  5240.4 2082.69  5270.4 2083.81  5400.4 2085.25
  5530.4 2087.58  5560.4 2087.59  5580.4 2088.37  5710.4 2090.72  5770.4 2093.12
#Mann=5,-1,0
  4286.0    0.07       0  4898.9    0.16       0  4998.4    0.07       0
  5002.4    0.16       0  5151.1    0.07       0
Bank Sta=4998.4,5002.4
Exp/Cntr=0.3,0.1

Type RM Length L Ch R = 1,4337,257,257,257
BEGIN DESCRIPTION:
Mapping XS adf8e858
END DESCRIPTION:
XS GIS Cut Line= 3
      1491392.91      6805525.52      1492193.69      6805551.56
      1492899.00      6805525.51
#Sta/Elev= 30
  4188.3 2088.35  4330.5 2085.86  4380.5 2085.59  4430.5 2084.49  4480.5 2084.44
  4560.6 2082.46  4670.6 2082.03  4770.7 2080.48  4860.7 2079.77  4950.8 2076.28
  4968.8 2074.76  4969.1 2074.26  4972.6 2074.26  4972.8 2074.76  4980.8 2075.90
  4996.7 2075.90  5070.6 2076.76  5150.9 2079.48  5180.9 2081.31  5241.0 2082.20
  5291.0 2083.55  5431.1 2084.96  5441.1 2085.52  5471.1 2085.17  5521.2 2086.50
  5541.2 2086.29  5551.2 2087.03  5621.2 2088.50  5651.3 2089.99  5695.3 2091.43
#Mann=5,-1,0
  4188.3    0.07       0  4968.8    0.07       0  4972.8    0.07       0
  4996.7    0.16       0  5070.6    0.07       0
Bank Sta=4968.8,4972.8
Exp/Cntr=0.3,0.1

Type RM Length L Ch R = 1,4080,349,349,349
BEGIN DESCRIPTION:
Mapping XS ba290555
END DESCRIPTION:
XS GIS Cut Line= 3
      1491469.79      6805684.77      1492207.61      6805808.46
      1493168.54      6805698.66
#Sta/Elev= 30
  4254.7 2085.65  4351.2 2084.93  4635.1 2080.61  4729.7 2078.26  4785.2 2074.66
  4800.4 2074.48  4849.0 2073.45  4878.5 2073.23  4906.6 2071.91  4919.1 2070.25
  4939.3 2070.69  4949.5 2071.73  4988.0 2068.55  4988.3 2068.05  4991.8 2068.05
  4992.0 2068.55  5020.3 2069.24  5030.4 2068.68  5048.2 2071.49  5090.8 2072.78
  5131.0 2075.87  5161.2 2076.84  5433.0 2081.30  5489.8 2081.66  5634.3 2085.20
  5752.8 2089.76  5835.6 2094.31  5855.7 2096.44  5931.5 2101.41  5970.0 2102.82
#Mann=5,-1,0
  4254.7    0.07       0  4800.4    0.16       0  4849.0    0.07       0
  4988.0    0.07       0  4992.0    0.07       0
Bank Sta=4988,4992
Exp/Cntr=0.3,0.1

Type RM Length L Ch R = 1,3731,236,236,236
BEGIN DESCRIPTION:
Mapping XS d25bae76
END DESCRIPTION:
XS GIS Cut Line= 3
      1491467.19      6806243.79      1492231.05      6806160.46
      1493158.09      6805726.45
#Sta/Elev= 30
  4084.2 2081.93  4102.1 2082.36  4162.5 2081.09  4293.2 2080.54  4333.5 2078.99
  4368.4 2079.84  4556.2 2078.14  4655.4 2076.30  4667.1 2076.74  4695.6 2075.65
  4767.0 2074.90  4846.5 2072.78  4868.5 2070.69  4889.2 2069.64  4901.1 2068.08
  4963.2 2064.87  4991.5 2064.99  5006.9 2063.88  5007.1 2063.38  5010.9 2063.88
  5031.7 2064.26  5088.8 2069.61  5166.1 2074.07  5287.0 2076.16  5430.9 2079.19
  5618.8 2085.73  5640.9 2087.54  5744.3 2092.91  5751.3 2094.19  5876.2 2102.72
#Mann=7,-1,0
  4084.2    0.07       0  4667.1    0.16       0  4767.0    0.07       0
  4868.5    0.16       0  5006.9    0.07       0  5010.9    0.16       0
  5287.0    0.07       0
Bank Sta=5006.9,5010.9
Exp/Cntr=0.3,0.1

Type RM Length L Ch R = 1,3495,340,340,340
BEGIN DESCRIPTION:
NUBIA CREEK TRIBUTARY 1_3_2 3.0
END DESCRIPTION:
XS GIS Cut Line= 3
      1491557.40      6806438.25      1492504.87      6806253.04
      1493196.34      6805830.59
#Sta/Elev= 30
  4034.6 2079.56  4265.9 2078.35  4297.1 2077.47  4348.0 2077.79  4374.1 2076.49
  4399.0 2077.27  4528.4 2075.35  4705.5 2072.34  4791.5 2071.17  4796.6 2071.69
  4877.9 2069.60  4908.4 2068.15  4968.3 2062.43  4979.8 2061.47  5009.9 2060.90
  5010.1 2060.40  5013.9 2060.90  5080.4 2066.41  5092.0 2067.83  5097.9 2067.26
  5112.2 2068.27  5134.6 2069.35  5155.9 2071.88  5339.7 2076.25  5372.1 2077.92
  5550.7 2083.88  5599.2 2087.22  5679.8 2095.55  5746.2 2096.98  5810.3 2099.54
#Mann=9,-1,0
  4034.6    0.07       0  4528.4    0.16       0  4705.5    0.07       0
  4968.3    0.16       0  5009.9    0.07       0  5013.9    0.16       0
  5080.4    0.07       0  5112.2    0.16       0  5372.1    0.07       0
Bank Sta=5009.9,5013.9
Exp/Cntr=0.3,0.1

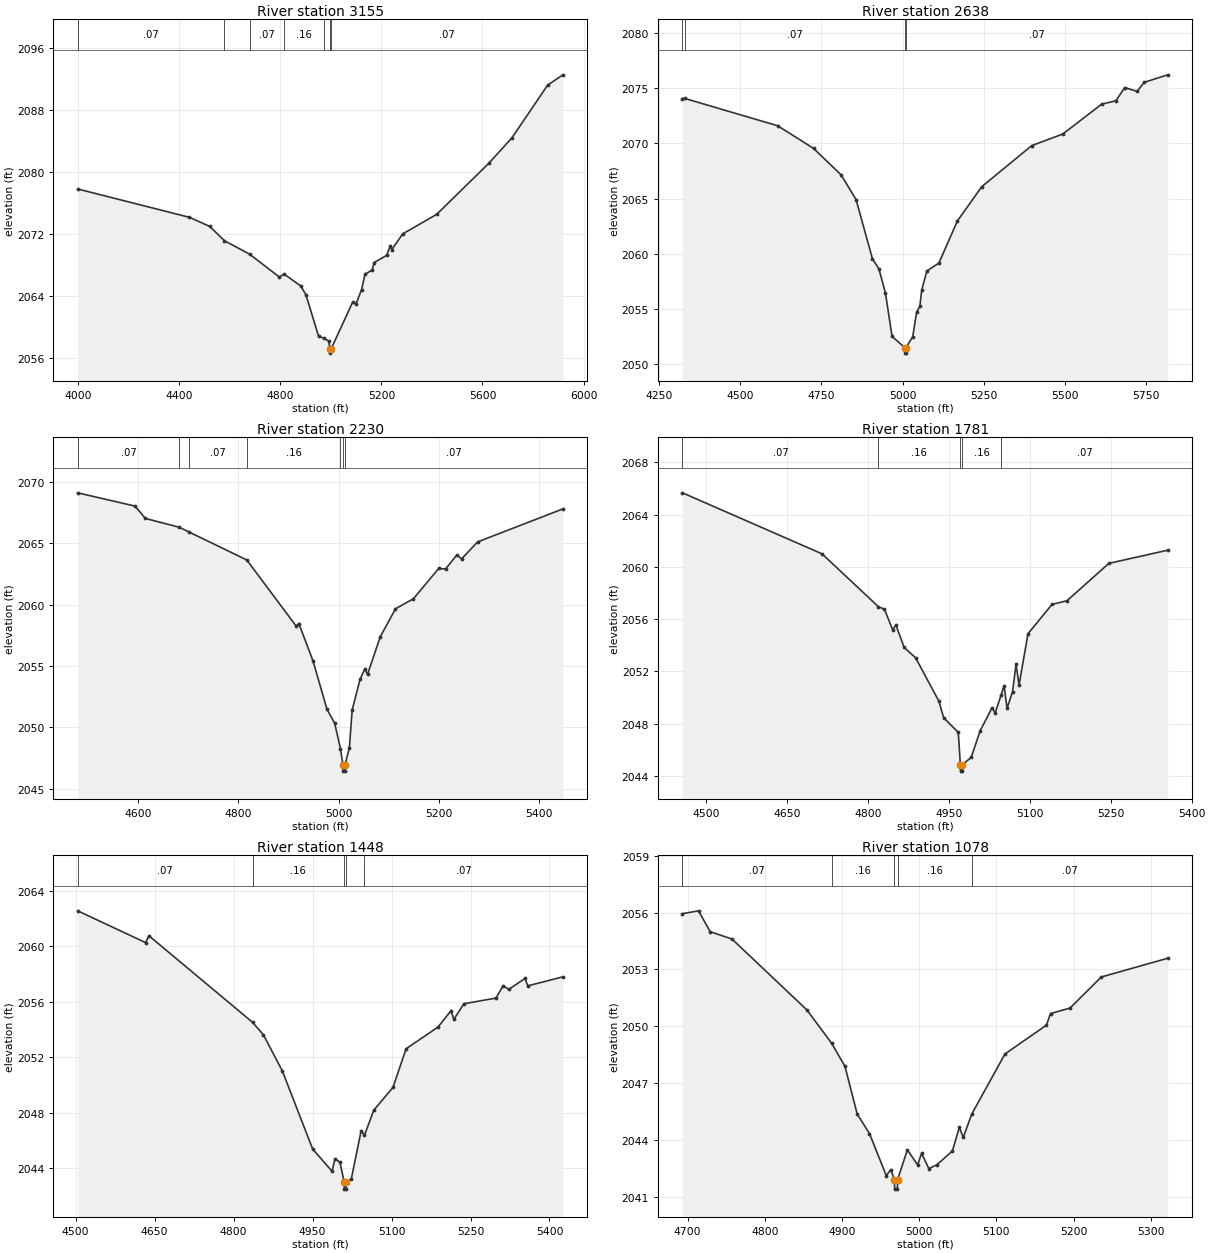
Type RM Length L Ch R = 1,3155,517,517,517
BEGIN DESCRIPTION:
NUBIA CREEK TRIBUTARY 1_3_2 2.0
END DESCRIPTION:
XS GIS Cut Line= 3
      1491554.01      6806653.51      1492553.62      6806577.57
      1493244.94      6805972.96
#Sta/Elev= 30
  3997.5 2077.81  4439.8 2074.16  4520.0 2072.99  4578.7 2071.14  4678.2 2069.41
  4796.0 2066.46  4814.4 2066.85  4881.0 2065.30  4901.1 2064.17  4951.2 2058.83
  4971.7 2058.59  4991.4 2058.20  4996.2 2057.16  4996.4 2056.66  5000.2 2057.16
  5085.5 2063.19  5099.8 2063.03  5121.4 2064.85  5134.9 2066.83  5163.4 2067.36
  5171.0 2068.33  5220.3 2069.25  5234.5 2070.44  5241.2 2070.01  5283.9 2072.02
  5418.7 2074.54  5624.7 2081.11  5716.7 2084.41  5858.1 2091.20  5918.4 2092.52
#Mann=7,-1,0
  3997.5    0.07       0  4578.7    0.16       0  4678.2    0.07       0
  4814.4    0.16       0  4971.7    0.07       0  4996.2    0.07       0
  5000.2    0.07       0
Bank Sta=4996.2,5000.2
Exp/Cntr=0.3,0.1

Type RM Length L Ch R = 1,2638,408,408,408
BEGIN DESCRIPTION:
Mapping XS fbde17e7
END DESCRIPTION:
XS GIS Cut Line= 3
      1491753.63      6806946.09      1492426.33      6807011.19
      1493141.27      6806616.89
#Sta/Elev= 30
  4323.3 2074.06  4330.7 2074.07  4616.0 2071.60  4726.5 2069.55  4811.1 2067.16
  4857.2 2064.91  4907.4 2059.57  4927.5 2058.64  4947.6 2056.45  4967.7 2052.54
  5007.0 2051.52  5007.3 2051.02  5010.8 2051.02  5011.0 2051.52  5031.5 2052.51
  5043.3 2054.72  5053.3 2055.26  5059.0 2056.73  5075.0 2058.46  5111.8 2059.17
  5168.9 2062.99  5243.5 2066.08  5397.3 2069.80  5493.4 2070.86  5612.6 2073.56
  5656.1 2073.86  5683.6 2075.06  5721.5 2074.71  5743.2 2075.53  5815.6 2076.21
#Mann=4,-1,0
  4323.3    0.16       0  4330.7    0.07       0  5007.0    0.07       0
  5011.0    0.07       0
Bank Sta=5007,5011
Exp/Cntr=0.3,0.1

Type RM Length L Ch R = 1,2230,449,449,449
BEGIN DESCRIPTION:
Mapping XS 199893ca
END DESCRIPTION:
XS GIS Cut Line= 3
      1492092.35      6807241.77      1492597.57      6807325.11
      1493024.63      6807168.86
#Sta/Elev= 30
  4480.1 2069.12  4594.3 2068.04  4615.1 2067.03  4682.2 2066.32  4701.2 2065.94
  4817.0 2063.65  4915.6 2058.25  4920.7 2058.47  4949.0 2055.42  4976.8 2051.48
  4992.1 2050.35  5003.6 2048.28  5008.7 2046.94  5009.0 2046.44  5012.5 2046.44
  5012.7 2046.94  5021.4 2048.34  5027.0 2051.42  5042.7 2053.92  5052.2 2054.77
  5057.6 2054.32  5082.8 2057.37  5113.3 2059.67  5149.1 2060.49  5199.5 2062.96
  5213.0 2062.91  5235.4 2064.05  5245.0 2063.74  5276.9 2065.12  5446.9 2067.81
#Mann=7,-1,0
  4480.1    0.07       0  4682.2    0.16       0  4701.2    0.07       0
  4817.0    0.16       0  5003.6    0.07       0  5008.7    0.07       0
  5012.7    0.07       0
Bank Sta=5008.7,5012.7
Exp/Cntr=0.3,0.1

Type RM Length L Ch R = 1,1781,333,333,333
BEGIN DESCRIPTION:
Mapping XS 97122f72
END DESCRIPTION:
XS GIS Cut Line= 3
      1492191.28      6807465.71      1492631.42      6807739.17
      1492971.27      6807565.35
#Sta/Elev= 30
  4455.7 2065.67  4714.5 2061.00  4818.9 2056.96  4830.2 2056.76  4845.6 2055.18
  4851.5 2055.55  4866.8 2053.84  4888.1 2053.04  4931.0 2049.74  4940.1 2048.46
  4967.2 2047.33  4971.0 2044.87  4971.3 2044.37  4974.8 2044.37  4975.0 2044.87
  4991.1 2045.42  5007.7 2047.45  5029.9 2049.23  5035.5 2048.81  5046.8 2050.22
  5052.1 2050.91  5057.7 2049.18  5067.8 2050.45  5074.3 2052.54  5079.9 2050.97
  5096.5 2054.89  5141.0 2057.13  5168.8 2057.41  5246.4 2060.27  5355.6 2061.28
#Mann=5,-1,0
  4455.7    0.07       0  4818.9    0.16       0  4971.0    0.07       0
  4975.0    0.16       0  5046.8    0.07       0
Bank Sta=4971,4975
Exp/Cntr=0.3,0.1

Type RM Length L Ch R = 1,1448,370,370,370
BEGIN DESCRIPTION:
Mapping XS aba8a1c1
END DESCRIPTION:
XS GIS Cut Line= 3
      1492268.58      6807656.31      1492518.60      6808041.76
      1492951.28      6807879.08
#Sta/Elev= 30
  4503.8 2062.54  4633.0 2060.25  4639.0 2060.75  4835.9 2054.52  4856.5 2053.62
  4892.3 2051.04  4950.1 2045.40  4987.1 2043.79  4992.5 2044.71  5002.1 2044.43
  5010.0 2043.01  5010.3 2042.51  5013.8 2042.51  5014.0 2043.01  5023.5 2043.23
  5042.2 2046.71  5048.6 2046.39  5066.2 2048.19  5102.7 2049.83  5127.6 2052.61
  5188.1 2054.17  5213.0 2055.35  5218.3 2054.72  5237.2 2055.85  5298.3 2056.26
  5312.0 2057.15  5322.6 2056.89  5353.4 2057.67  5358.8 2057.14  5425.5 2057.79
#Mann=5,-1,0
  4503.8    0.07       0  4835.9    0.16       0  5010.0    0.07       0
  5014.0    0.16       0  5048.6    0.07       0
Bank Sta=5010,5014
Exp/Cntr=0.3,0.1

Type RM Length L Ch R = 1,1078,402,402,402
BEGIN DESCRIPTION:
Mapping XS df1beb51
END DESCRIPTION:
XS GIS Cut Line= 3
      1492093.63      6808191.85      1492349.74      6808335.09
      1492679.63      6808276.49
#Sta/Elev= 30
  4693.5 2055.94  4714.3 2056.09  4729.4 2054.99  4757.7 2054.60  4854.7 2050.86
  4886.6 2049.11  4903.9 2047.89  4919.8 2045.37  4935.7 2044.34  4957.5 2042.12
  4963.2 2042.44  4968.1 2041.91  4968.3 2041.41  4971.8 2041.41  4972.1 2041.91
  4984.8 2043.48  4998.1 2042.69  5003.2 2043.30  5012.6 2042.49  5022.8 2042.69
  5043.1 2043.42  5052.1 2044.67  5057.2 2044.14  5068.2 2045.37  5111.2 2048.54
  5164.9 2050.06  5170.2 2050.67  5195.4 2050.96  5236.0 2052.60  5322.0 2053.59
#Mann=5,-1,0
  4693.5    0.07       0  4886.6    0.16       0  4968.1    0.07       0
  4972.1    0.16       0  5068.2    0.07       0
Bank Sta=4968.1,4972.1
Exp/Cntr=0.3,0.1

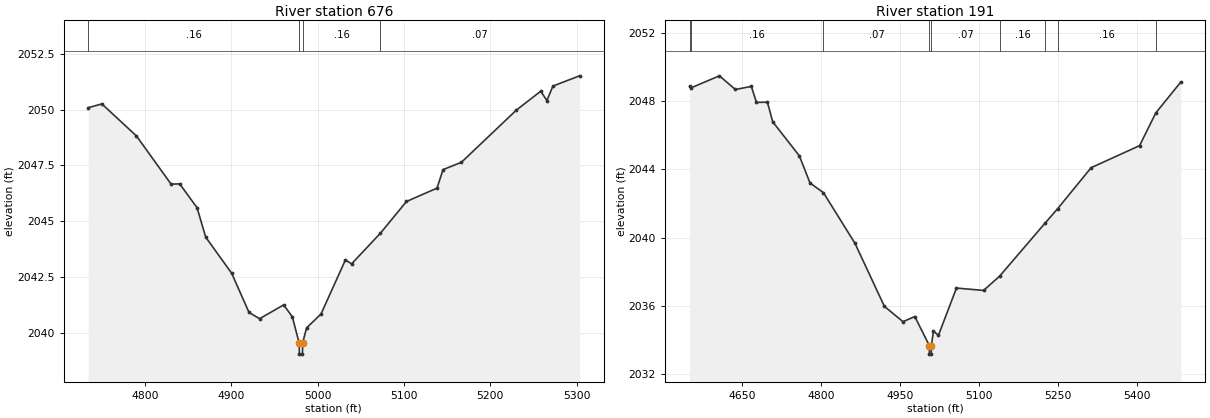
Type RM Length L Ch R = 1,676,485,485,485
BEGIN DESCRIPTION:
Mapping XS b5b07275
END DESCRIPTION:
XS GIS Cut Line= 3
      1492139.28      6808677.98      1492393.14      6808697.51
      1492614.50      6808473.97
#Sta/Elev= 30
  4734.1 2050.09  4749.9 2050.26  4790.0 2048.82  4830.1 2046.66  4840.1 2046.67
  4860.2 2045.60  4870.2 2044.28  4900.3 2042.66  4920.4 2040.90  4932.7 2040.62
  4960.5 2041.24  4970.5 2040.71  4978.5 2039.53  4978.8 2039.03  4982.3 2039.03
  4982.5 2039.53  4987.1 2040.21  5003.8 2040.83  5032.1 2043.26  5039.2 2043.08
  5072.7 2044.46  5102.8 2045.88  5138.2 2046.48  5145.2 2047.31  5166.5 2047.64
  5230.1 2049.98  5258.4 2050.83  5265.5 2050.41  5272.5 2051.06  5303.3 2051.52
#Mann=4,-1,0
  4734.1    0.16       0  4978.5    0.07       0  4982.5    0.16       0
  5072.7    0.07       0
Bank Sta=4978.5,4982.5
Exp/Cntr=0.3,0.1

Type RM Length L Ch R = 1,191,0,0,0
BEGIN DESCRIPTION:
NUBIA CREEK TRIBUTARY 1_3_2 1.0
END DESCRIPTION:
XS GIS Cut Line= 4
      1492219.06      6809011.32      1492594.11      6809073.89
      1492704.82      6809005.53      1492615.29      6808591.24
#Sta/Elev= 30
  4549.6 2048.85  4552.0 2048.76  4606.3 2049.47  4636.7 2048.67  4667.1 2048.85
  4676.8 2047.91  4697.6 2047.93  4707.7 2046.78  4758.4 2044.78  4778.7 2043.19
  4804.1 2042.63  4864.3 2039.65  4920.0 2035.97  4955.4 2035.07  4977.9 2035.37
  5005.5 2033.67  5005.7 2033.17  5009.2 2033.17  5009.5 2033.67  5013.3 2034.51
  5022.9 2034.28  5057.1 2037.04  5108.6 2036.90  5139.0 2037.73  5226.1 2040.86
  5249.3 2041.68  5313.2 2044.09  5405.3 2045.38  5436.2 2047.30  5483.8 2049.11
#Mann=9,-1,0
  4549.6    0.07       0  4552.0    0.16       0  4804.1    0.07       0
  5005.5    0.07       0  5009.5    0.07       0  5139.0    0.16       0
  5226.1    0.07       0  5249.3    0.16       0  5436.2    0.07       0
Bank Sta=5005.5,5009.5
Exp/Cntr=0.3,0.1

Chan Stop Cuts=-1