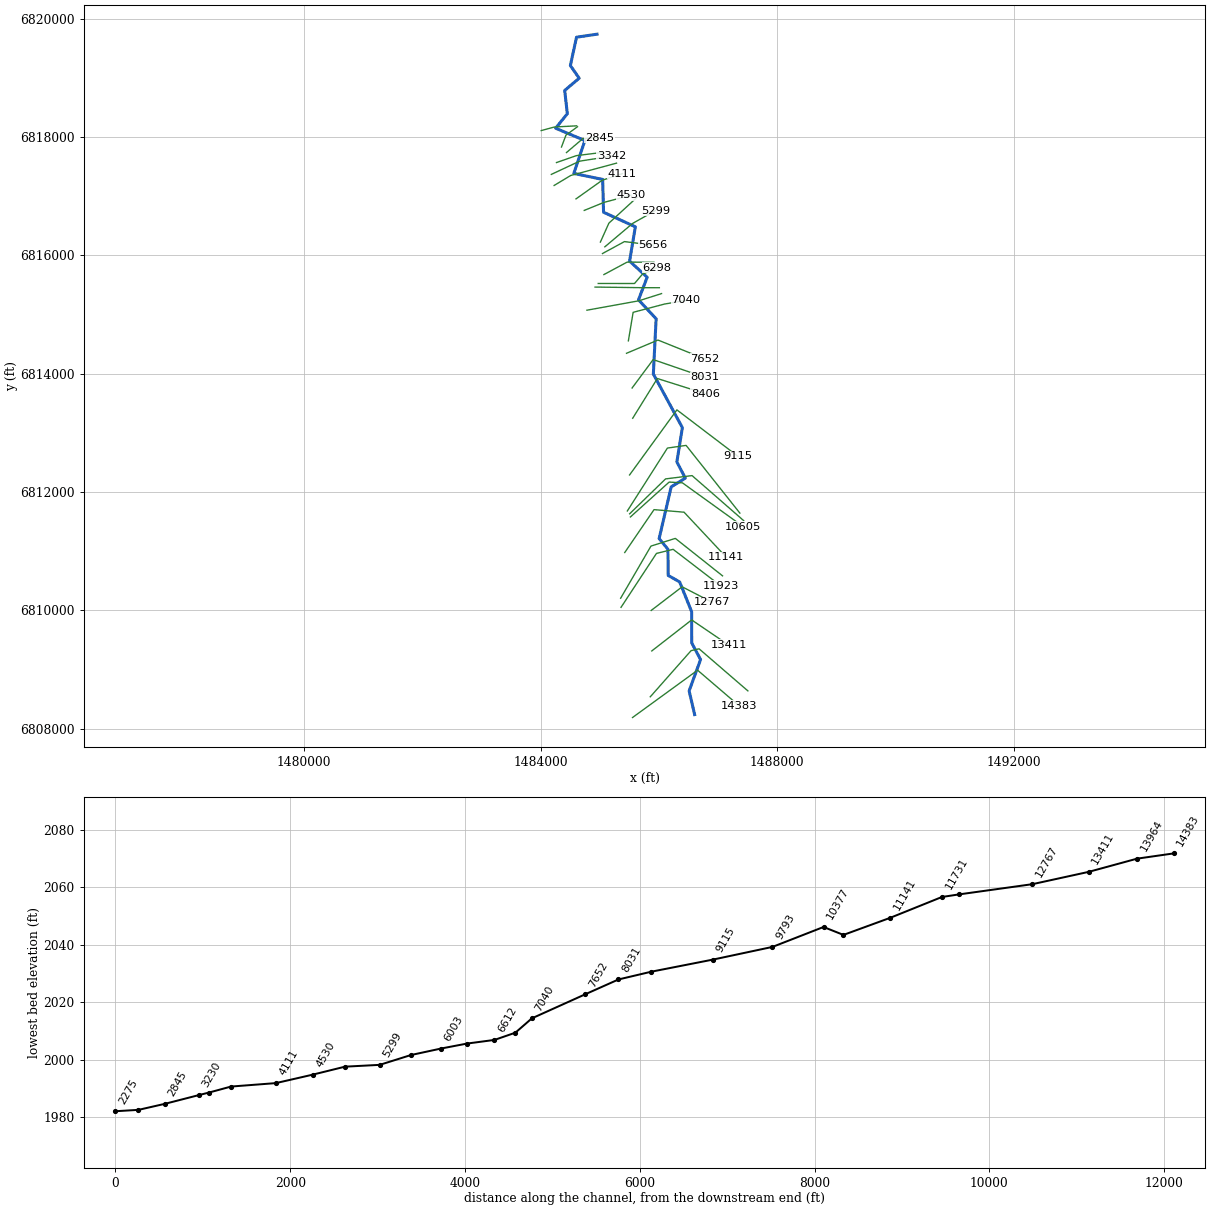
--- NUBIA CREEK TRIBUTARY 2.prj (project) ---

Proj Title=NUBIA CREEK TRIBUTARY 2 Base Level Engineering
Current Plan=p01
Default Exp/Contr=0.3,0.1
English Units
Geom File=g01
Flow File=f01
Plan File=p01
Y Axis Title=Elevation
X Axis Title(PF)=Main Channel Distance
X Axis Title(XS)=Station
BEGIN DESCRIPTION:
NUBIA CREEK TRIBUTARY 2
END DESCRIPTION:
DSS Export Rating Curves= 0
DSS Export Rating Curve Sorted= 0
DSS Export Volume Flow Curves= 0
DXF OffsetX= 0
DXF OffsetY= 0
DXF ScaleX= 1
DXF ScaleY= 10

--- NUBIA CREEK TRIBUTARY 2.p01 (plan) ---

Plan Title=Multiple Run
Short Identifier=Multiple
Geom File=g01
Flow File=f01
Subcritical Flow
K Sum by GR= 0
Std Step Tol= 0.01
Critical Tol= 0.01
Num of Std Step Trials= 20
Max Error Tol= 0.3
Flow Tol Ratio= 0.001
Split Flow NTrial= 30
Split Flow Tol= 0.02
Split Flow Ratio= 0.02
Log Output Level= 0
Friction Slope Method= 1
Unsteady Friction Slope Method= 2
Unsteady Bridges Friction Slope Method= 1
Parabolic Critical Depth
Global Vel Dist=  1 , 1 , 1
Global Log Level= 0
CheckData=True
Encroach Param= -1, 0, 0, 0
BEGIN DESCRIPTION:
Multiple Run
END DESCRIPTION:

--- NUBIA CREEK TRIBUTARY 2.f01 (steady flow) ---

Flow Title=Multiple
Program Version=4.10
Number of Profiles= 7
Profile Names=10-year,25-year,50-year,1pct_min,100-year,1pct_plu,500-year
River Rch & RM=NUBIA CREEK TRIB,Reach-1         ,14383
     443     646     822     520    1038    2071    1677
River Rch & RM=NUBIA CREEK TRIB,Reach-1         ,6851
     711    1062    1373     881    1759    3509    2923
Boundary for River Rch & Prof#=NUBIA CREEK TRIB,Reach-1         , 1
Up Type= 0
Dn Type= 3
Dn Slope=0.005
Boundary for River Rch & Prof#=NUBIA CREEK TRIB,Reach-1         , 2
Up Type= 0
Dn Type= 3
Dn Slope=0.005
Boundary for River Rch & Prof#=NUBIA CREEK TRIB,Reach-1         , 3
Up Type= 0
Dn Type= 3
Dn Slope=0.005
Boundary for River Rch & Prof#=NUBIA CREEK TRIB,Reach-1         , 4
Up Type= 0
Dn Type= 3
Dn Slope=0.005
Boundary for River Rch & Prof#=NUBIA CREEK TRIB,Reach-1         , 5
Up Type= 0
Dn Type= 3
Dn Slope=0.005
Boundary for River Rch & Prof#=NUBIA CREEK TRIB,Reach-1         , 6
Up Type= 0
Dn Type= 3
Dn Slope=0.005
Boundary for River Rch & Prof#=NUBIA CREEK TRIB,Reach-1         , 7
Up Type= 0
Dn Type= 3
Dn Slope=0.005
DSS Import GetInterval= 0
DSS Import GetPeak= 0
DSS Import FillOption= 0

--- NUBIA CREEK TRIBUTARY 2.g01 (geometry) ---

Geom Title=Existing Conditions
Program Version=4.10

River Reach=NUBIA CREEK TRIB,Reach-1
Reach XY= 30
        1486605.        6808238.      1486512.03      6808637.79
      1486705.22       6809167.8      1486555.75      6809448.68
      1486553.94      6809977.57      1486351.62      6810479.85
      1486158.15      6810589.63       1486153.4      6811032.12
      1486004.78       6811212.9      1486208.54      6812086.54
      1486447.33       6812234.3      1486304.61      6812508.13
      1486397.47      6813087.99      1485906.97      6813993.89
      1485953.95      6814927.57      1485656.04      6815248.44
      1485802.41       6815629.5      1485505.36      6815903.15
      1485603.04      6816482.12      1485065.47      6816728.18
      1485050.41      6817282.83      1484562.65       6817384.3
      1484749.95      6817940.28       1484255.5       6818148.5
      1484453.04      6818393.89      1484408.74      6818786.48
      1484653.39      6818994.03      1484504.57      6819208.03
      1484608.53      6819687.01        1484955.        6819738.

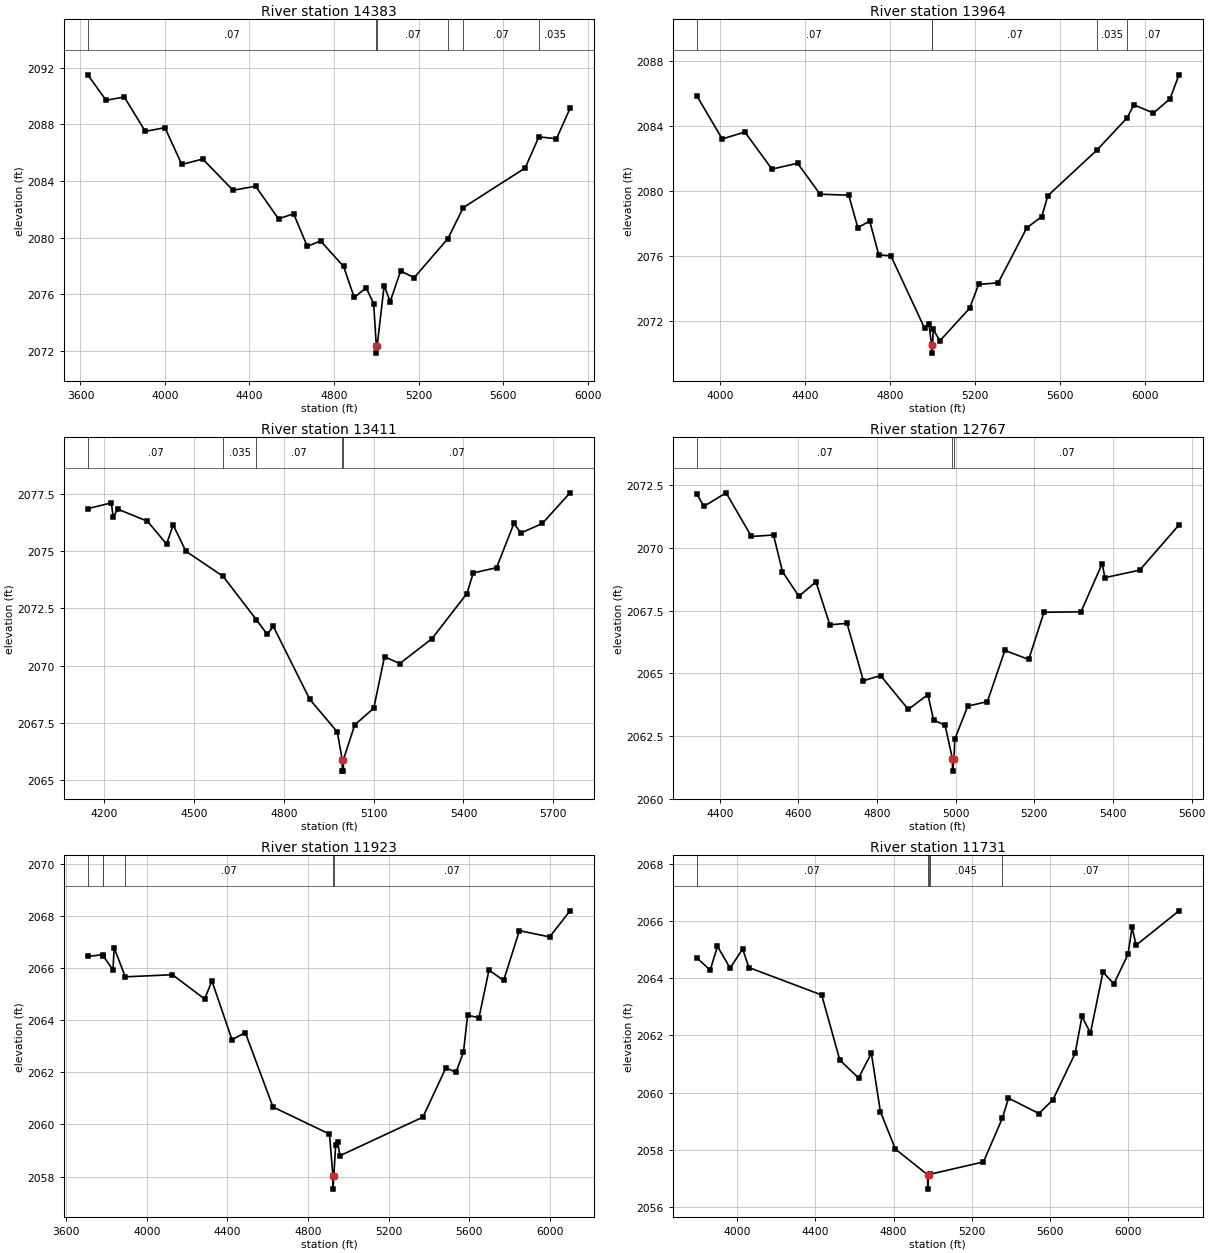
Type RM Length L Ch R = 1 ,14383   ,419,419,419
BEGIN DESCRIPTION:
NUBIA CREEK TRIBUTARY 2 24.0
END DESCRIPTION:
XS GIS Cut Line= 3
        1485555.        6808188.        1486655.        6808988.
        1487355.        6808388.
#Sta/Elev= 30
  3634.8 2091.51  3721.4 2089.71  3807.5 2089.94  3906.8 2087.51    4000 2087.77
  4079.6 2085.17  4178.9 2085.55  4322.2 2083.34  4428.9 2083.63  4537.4 2081.32
  4608.9 2081.68  4673.5 2079.37  4736.4 2079.76  4845.4 2077.95  4895.6 2075.76
  4952.1 2076.44  4987.6 2075.32  5000.1 2072.32  5000.3 2071.82  5004.1 2072.32
  5037.2  2076.6  5065.7 2075.46  5115.1 2077.63  5179.3 2077.16  5339.3 2079.93
  5411.2 2082.11  5704.5 2084.92  5769.3 2087.12  5852.7 2086.99  5916.9 2089.14
#Mann= 6 ,-1 , 0
  3634.8     .07       0  5000.1     .07       0  5004.1     .07       0
  5339.3    .035       0  5411.2     .07       0  5769.3    .035       0
Bank Sta=5000.1,5004.1
XS Rating Curve= 0 ,0
Exp/Cntr=0.3,0.1

Type RM Length L Ch R = 1 ,13964   ,553,553,553
BEGIN DESCRIPTION:
NUBIA CREEK TRIBUTARY 2 23.0
END DESCRIPTION:
XS GIS Cut Line= 4
      1485855.01      6808538.01       1486544.9      6809318.29
      1486680.32      6809349.54      1487504.99      6808638.01
#Sta/Elev= 30
  3889.3 2085.89  4009.4 2083.21  4116.2 2083.64  4243.5 2081.35    4364 2081.71
  4470.2  2079.8  4604.9 2079.74  4647.6 2077.74  4703.6 2078.14  4746.2 2076.05
  4803.1    2076  4961.7 2071.53  4982.2 2071.81  4994.9 2070.49  4995.1 2069.99
    4999 2070.49  5002.8 2071.45  5033.6 2070.75  5173.3 2072.75  5216.1 2074.23
  5308.3 2074.33  5443.2 2077.73  5513.4 2078.42    5542 2079.71  5774.1 2082.54
  5915.3 2084.52  5946.7 2085.32  6038.9 2084.81  6116.8 2085.69    6159 2087.17
#Mann= 5 ,-1 , 0
  3889.3     .07       0  4994.9     .07       0    4999     .07       0
  5774.1    .035       0  5915.3     .07       0
Bank Sta=4994.9,4999
XS Rating Curve= 0 ,0
Exp/Cntr=0.3,0.1

Type RM Length L Ch R = 1 ,13411   ,644,644,644
BEGIN DESCRIPTION:
NUBIA CREEK TRIBUTARY 2 22.0
END DESCRIPTION:
XS GIS Cut Line= 3
      1485880.01      6809313.01       1486554.6      6809837.83
      1487179.96      6809413.03
#Sta/Elev= 30
  4145.3 2076.86    4224 2077.11  4230.3 2076.48  4244.8 2076.84  4344.4 2076.31
  4408.6 2075.31  4430.4 2076.15  4472.8    2075  4597.3  2073.9  4708.2 2072.01
  4744.3 2071.37  4765.1 2071.71  4886.5 2068.53  4978.7  2067.1    4995 2065.89
  4995.3 2065.39  4998.9 2065.39  4999.1 2065.89  5036.8 2067.41  5100.4 2068.14
  5136.3 2070.39  5187.2 2070.09    5295 2071.18  5411.5 2073.15  5432.7 2074.05
  5510.6 2074.28  5568.7 2076.22  5591.3 2075.79  5663.2 2076.21    5756 2077.55
#Mann= 5 ,-1 , 0
  4145.3     .07       0  4597.3    .035       0  4708.2     .07       0
    4995     .07       0  4999.1     .07       0
Bank Sta=4995,4999.1
XS Rating Curve= 0 ,0
Exp/Cntr=0.3,0.1

Type RM Length L Ch R = 1 ,12767   ,844,844,844
BEGIN DESCRIPTION:
NUBIA CREEK TRIBUTARY 2 21.0
END DESCRIPTION:
XS GIS Cut Line= 3
      1485870.42      6809997.68      1486393.94      6810397.61
      1486898.55       6810137.3
#Sta/Elev= 30
  4341.2 2072.15  4359.5 2071.65    4416 2072.19  4480.4 2070.45  4536.6 2070.51
  4559.4 2069.05    4601 2068.07  4644.6 2068.64  4679.9 2066.93  4723.5 2066.99
  4765.2  2064.7  4808.7 2064.91  4879.4 2063.56  4929.3 2064.15  4943.8 2063.13
  4972.9 2062.93  4991.6  2061.6  4991.9  2061.1  4995.8  2061.6  4997.5 2062.37
  5030.6 2063.69  5080.5 2063.87    5125 2065.91  5185.7 2065.55  5224.4 2067.43
  5318.7 2067.45  5372.5 2069.37  5379.5 2068.81  5468.1 2069.11  5567.8 2070.91
#Mann= 3 ,-1 , 0
  4341.2     .07       0  4991.6     .07       0  4995.8     .07       0
Bank Sta=4991.6,4995.8
XS Rating Curve= 0 ,0
Exp/Cntr=0.3,0.1

Type RM Length L Ch R = 1 ,11923   ,192,192,192
BEGIN DESCRIPTION:
Mapping XS a145a45c
END DESCRIPTION:
XS GIS Cut Line= 4
      1485360.45      6810049.95       1485959.4      6810961.39
      1486241.51      6811030.84      1487044.48      6810414.51
#Sta/Elev= 30
  3707.6 2066.44    3783 2066.51    3785 2066.45  3832.6 2065.93  3838.6 2066.77
  3893.7 2065.66  4127.8 2065.74  4287.5 2064.81  4323.7  2065.5  4423.2 2063.25
  4489.4 2063.52  4626.6 2060.67    4907 2059.63  4924.3 2058.02  4924.6 2057.52
  4928.6 2058.02  4937.9 2059.23  4948.2 2059.31  4958.5  2058.8  5370.6 2060.28
  5484.8 2062.17  5534.7    2062  5571.9 2062.77  5592.7 2064.19  5648.9 2064.09
  5698.7 2065.92  5771.3 2065.52  5849.5 2067.43  5999.7 2067.19    6101 2068.19
#Mann= 6 ,-1 , 0
  3707.6     .16       0    3783     .07       0    3785     .16       0
  3893.7     .07       0  4924.3     .07       0  4928.6     .07       0
Bank Sta=4924.3,4928.6
XS Rating Curve= 0 ,0
Exp/Cntr=0.3,0.1

Type RM Length L Ch R = 1 ,11731   ,590,590,590
BEGIN DESCRIPTION:
Mapping XS 535e1fb5
END DESCRIPTION:
XS GIS Cut Line= 4
      1485354.38      6810204.49      1485866.51      6811085.52
      1486278.84      6811215.73      1487076.87      6810582.51
#Sta/Elev= 30
  3791.6 2064.71  3860.9 2064.28  3898.1 2065.11  3962.7 2064.35  4027.2 2065.02
  4058.7 2064.37  4431.8 2063.41  4524.6 2061.14  4620.7 2060.51  4686.3 2061.38
  4732.4 2059.34  4809.2 2058.03  4974.7 2057.13    4975 2056.63    4979 2057.13
  4986.8 2057.15  5260.4 2057.58  5357.4 2059.11  5388.6 2059.81  5544.5 2059.27
  5616.1 2059.75  5729.9 2061.37  5765.1 2062.66  5808.4 2062.08  5872.5 2064.21
  5928.5  2063.8  6000.7 2064.83  6021.5 2065.77  6042.4 2065.15  6261.8 2066.35
#Mann= 5 ,-1 , 0
  3791.6     .07       0  4974.7    .045       0    4979     .07       0
  4986.8    .045       0  5357.4     .07       0
Bank Sta=4974.7,4979
XS Rating Curve= 0 ,0
Exp/Cntr=0.3,0.1

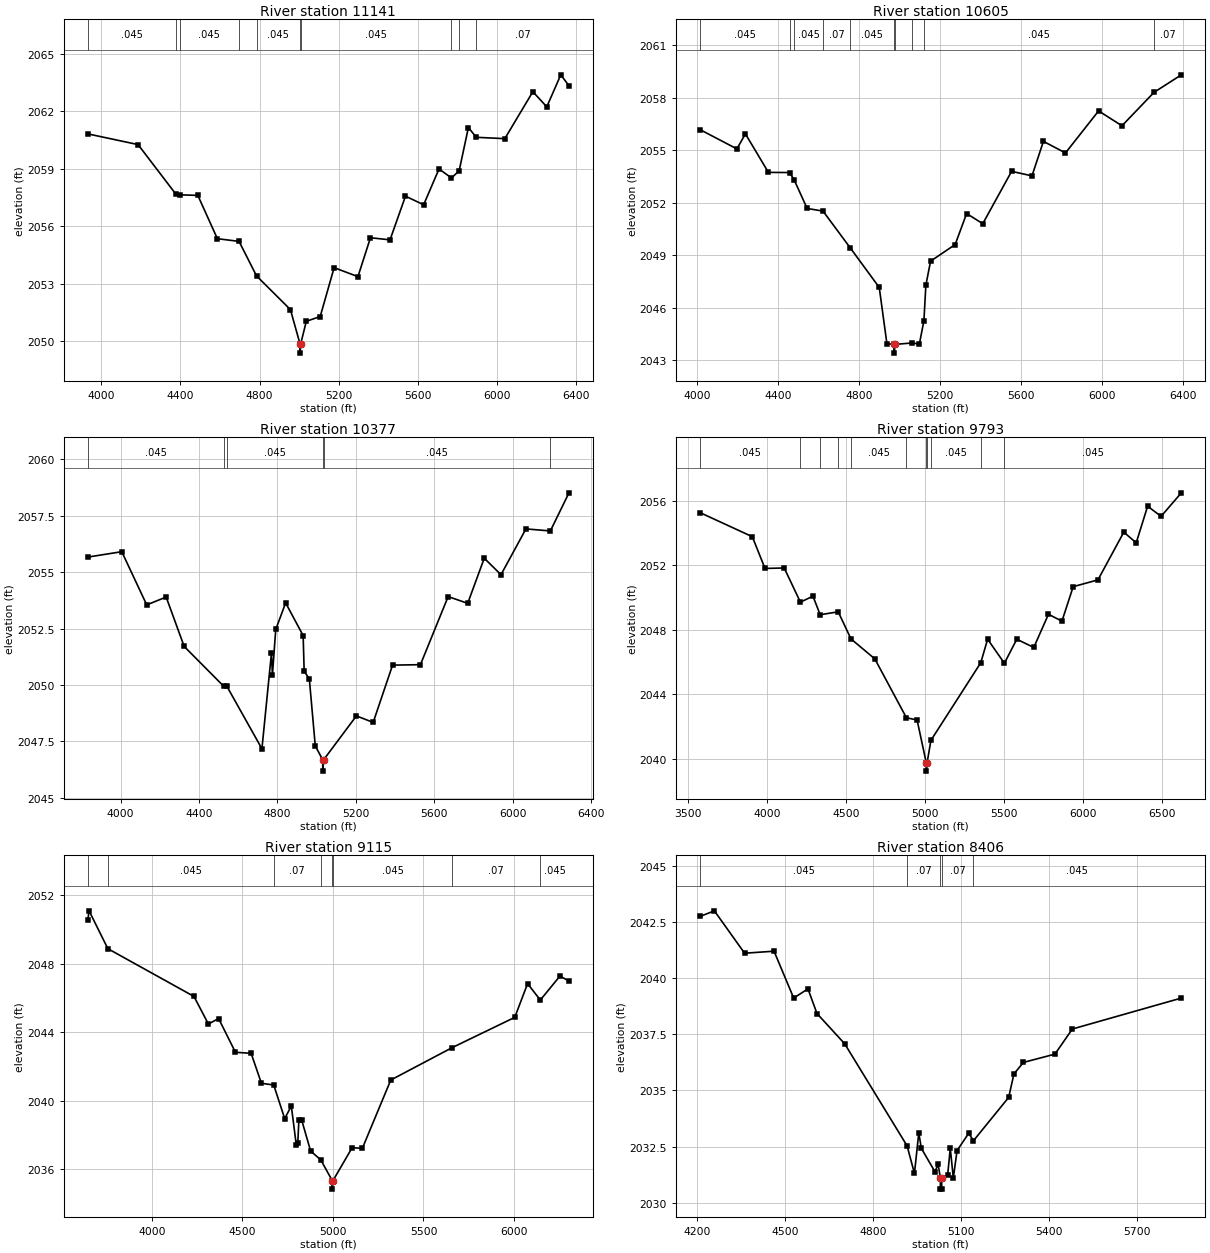
Type RM Length L Ch R = 1 ,11141   ,536,536,536
BEGIN DESCRIPTION:
Mapping XS f7ae3897
END DESCRIPTION:
XS GIS Cut Line= 4
       1485423.8        6810977.       1485918.6      6811701.84
      1486426.41      6811658.44      1487141.28      6810895.92
#Sta/Elev= 30
  3931.7 2060.83  4186.1 2060.27  4376.1  2057.7  4396.1 2057.65  4488.2 2057.62
    4587 2055.36  4696.6 2055.22  4784.9 2053.42  4956.3 2051.66  5004.2 2049.89
  5004.5 2049.39  5008.6 2049.89  5036.5 2051.05  5106.8  2051.3  5177.1 2053.85
  5297.5 2053.38  5360.7 2055.41  5459.7  2055.3  5537.8 2057.58  5629.6 2057.13
  5707.3    2059  5770.1 2058.53    5809  2058.9  5855.8 2061.16  5895.5 2060.65
  6039.9 2060.58  6181.6 2063.03    6252 2062.24  6322.8 2063.91  6364.2 2063.34
#Mann= 10 ,-1 , 0
  3931.7    .045       0  4376.1     .07       0  4396.1    .045       0
  4696.6     .07       0  4784.9    .045       0  5004.2    .045       0
  5008.6    .045       0  5770.1     .07       0    5809    .045       0
  5895.5     .07       0
Bank Sta=5004.2,5008.6
XS Rating Curve= 0 ,0
Exp/Cntr=0.3,0.1

Type RM Length L Ch R = 1 ,10605   ,228,228,228
BEGIN DESCRIPTION:
NUBIA CREEK TRIBUTARY 2 19.0
END DESCRIPTION:
XS GIS Cut Line= 4
      1485519.04      6811577.61       1486174.5      6812167.71
      1486398.46      6812154.69       1487429.4      6811412.52
#Sta/Elev= 30
  4014.4 2056.18  4196.2 2055.08  4238.1 2055.94  4351.7 2053.74  4456.4 2053.73
    4479 2053.31    4543 2051.68  4621.3 2051.53  4754.6 2049.45  4899.1 2047.17
  4936.9 2043.96  4972.6 2043.92  4972.9 2043.42    4977 2043.92  5061.7    2044
  5097.2 2043.94  5119.7 2045.27  5129.3  2047.3  5152.5 2048.67    5274 2049.62
  5330.5 2051.39  5410.3 2050.81  5552.7  2053.8  5653.3 2053.54  5709.8 2055.51
  5818.8 2054.85  5982.3 2057.25  6097.6  2056.4  6256.1 2058.31    6391 2059.31
#Mann= 10 ,-1 , 0
  4014.4    .045       0  4456.4     .07       0    4479    .045       0
  4621.3     .07       0  4754.6    .045       0  4972.6    .045       0
    4977    .045       0  5061.7     .07       0  5119.7    .045       0
  6256.1     .07       0
Bank Sta=4972.6,4977
XS Rating Curve= 0 ,0
Exp/Cntr=0.3,0.1

Type RM Length L Ch R = 1 ,10377   ,584,584,584
BEGIN DESCRIPTION:
Mapping XS e67b543e
END DESCRIPTION:
XS GIS Cut Line= 4
      1485506.11      6811631.26      1486113.74      6812221.53
      1486561.66      6812277.09      1487433.18      6811516.67
#Sta/Elev= 30
    3832 2055.67  4005.7 2055.91    4133 2053.55  4232.1  2053.9  4323.9 2051.71
  4526.1 2049.94  4541.3 2049.95  4720.7 2047.17  4769.2 2051.41  4774.2 2050.45
  4791.2 2052.46  4841.6 2053.64    4931 2052.19  4936.1 2050.61  4962.5 2050.27
  4992.8  2047.3  5030.9 2046.68  5031.2 2046.18  5035.3 2046.68  5202.7 2048.63
  5288.2 2048.34  5387.1 2050.88  5529.3  2050.9  5670.7 2053.92  5770.4 2053.62
  5854.9 2055.62  5940.3 2054.89  6067.5 2056.92  6192.2 2056.83  6287.1 2058.52
#Mann= 6 ,-1 , 0
    3832    .045       0  4526.1     .07       0  4541.3    .045       0
  5030.9    .045       0  5035.3    .045       0  6192.2     .07       0
Bank Sta=5030.9,5035.3
XS Rating Curve= 0 ,0
Exp/Cntr=0.3,0.1

Type RM Length L Ch R = 1 ,9793    ,678,678,678
BEGIN DESCRIPTION:
Mapping XS 60a30140
END DESCRIPTION:
XS GIS Cut Line= 4
      1485467.92      6811679.89      1486144.99      6812742.36
      1486460.96       6812787.5      1487369.81      6811642.77
#Sta/Elev= 30
  3578.7 2055.27  3908.5 2053.78  3988.7 2051.81  4110.1 2051.84  4212.4 2049.72
  4291.8 2050.09  4337.2 2048.94  4451.4 2049.12    4532 2047.44  4682.8  2046.2
  4882.3 2042.55  4949.7 2042.41  5008.1 2039.74  5008.4 2039.24  5012.6 2039.74
  5037.1 2041.15  5351.9 2045.96  5395.4 2047.42  5501.2 2045.93  5579.6 2047.42
    5687 2046.91  5779.9 2048.97  5864.8 2048.54    5936 2050.68  6092.3  2051.1
  6255.7 2054.06  6334.2  2053.4  6406.3 2055.67  6491.2 2055.04  6619.4  2056.5
#Mann= 11 ,-1 , 0
  3578.7    .045       0  4212.4     .07       0  4337.2    .045       0
  4451.4     .07       0    4532    .045       0  4882.3     .07       0
  5008.1     .07       0  5012.6     .07       0  5037.1    .045       0
  5351.9     .07       0  5501.2    .045       0
Bank Sta=5008.1,5012.6
XS Rating Curve= 0 ,0
Exp/Cntr=0.3,0.1

Type RM Length L Ch R = 1 ,9115    ,709,709,709
BEGIN DESCRIPTION:
NUBIA CREEK TRIBUTARY 2 18.0
END DESCRIPTION:
XS GIS Cut Line= 3
      1485504.99      6812287.99        1486305.        6813388.
       1487338.6      6812601.94
#Sta/Elev= 30
  3645.1 2050.53  3652.5 2051.09  3756.3 2048.88  4232.1 2046.09  4311.7 2044.48
  4368.1  2044.8  4461.2 2042.83  4547.8 2042.77  4604.6 2041.02  4672.7 2040.92
  4733.2 2038.96  4769.9 2039.69    4797 2037.44  4805.5 2037.54  4811.7 2038.86
  4826.4  2038.9  4876.6 2037.06  4932.6 2036.55  4995.7 2035.34    4996 2034.84
  5000.2 2035.34  5105.8 2037.26  5162.2 2037.22  5319.3 2041.21    5658  2043.1
  6004.4 2044.87  6075.1 2046.84  6145.4 2045.88  6253.9 2047.28  6303.8 2046.99
#Mann= 8 ,-1 , 0
  3645.1     .07       0  3756.3    .045       0  4672.7     .07       0
  4932.6    .045       0  4995.7    .045       0  5000.2    .045       0
    5658     .07       0  6145.4    .045       0
Bank Sta=4995.7,5000.2
XS Rating Curve= 0 ,0
Exp/Cntr=0.3,0.1

Type RM Length L Ch R = 1 ,8406    ,375,375,375
BEGIN DESCRIPTION:
NUBIA CREEK TRIBUTARY 2 17.0
END DESCRIPTION:
XS GIS Cut Line= 3
      1485558.33      6813246.71      1485974.78      6813918.15
      1486786.62      6813661.64
#Sta/Elev= 30
  4209.9 2042.76  4258.5 2043.01  4361.7 2041.12  4462.1 2041.21  4529.1 2039.12
  4577.8 2039.53  4608.6 2038.43  4703.1 2037.08  4915.9 2032.53    4941  2031.3
  4955.8 2033.11  4964.5 2032.42  5010.7 2031.38  5021.8  2031.7  5029.4  2031.1
  5029.7  2030.6  5033.7  2030.6    5034  2031.1  5054.1 2031.21  5063.2 2032.42
  5073.6  2031.1  5086.4 2032.32  5126.1 2033.09  5142.4 2032.76  5262.4 2034.69
  5280.4 2035.74  5312.7 2036.25  5420.2 2036.62  5479.6 2037.74  5851.4 2039.12
#Mann= 5 ,-1 , 0
  4209.9    .045       0  4915.9     .07       0  5029.4     .07       0
    5034     .07       0  5142.4    .045       0
Bank Sta=5029.4,5034
XS Rating Curve= 0 ,0
Exp/Cntr=0.3,0.1

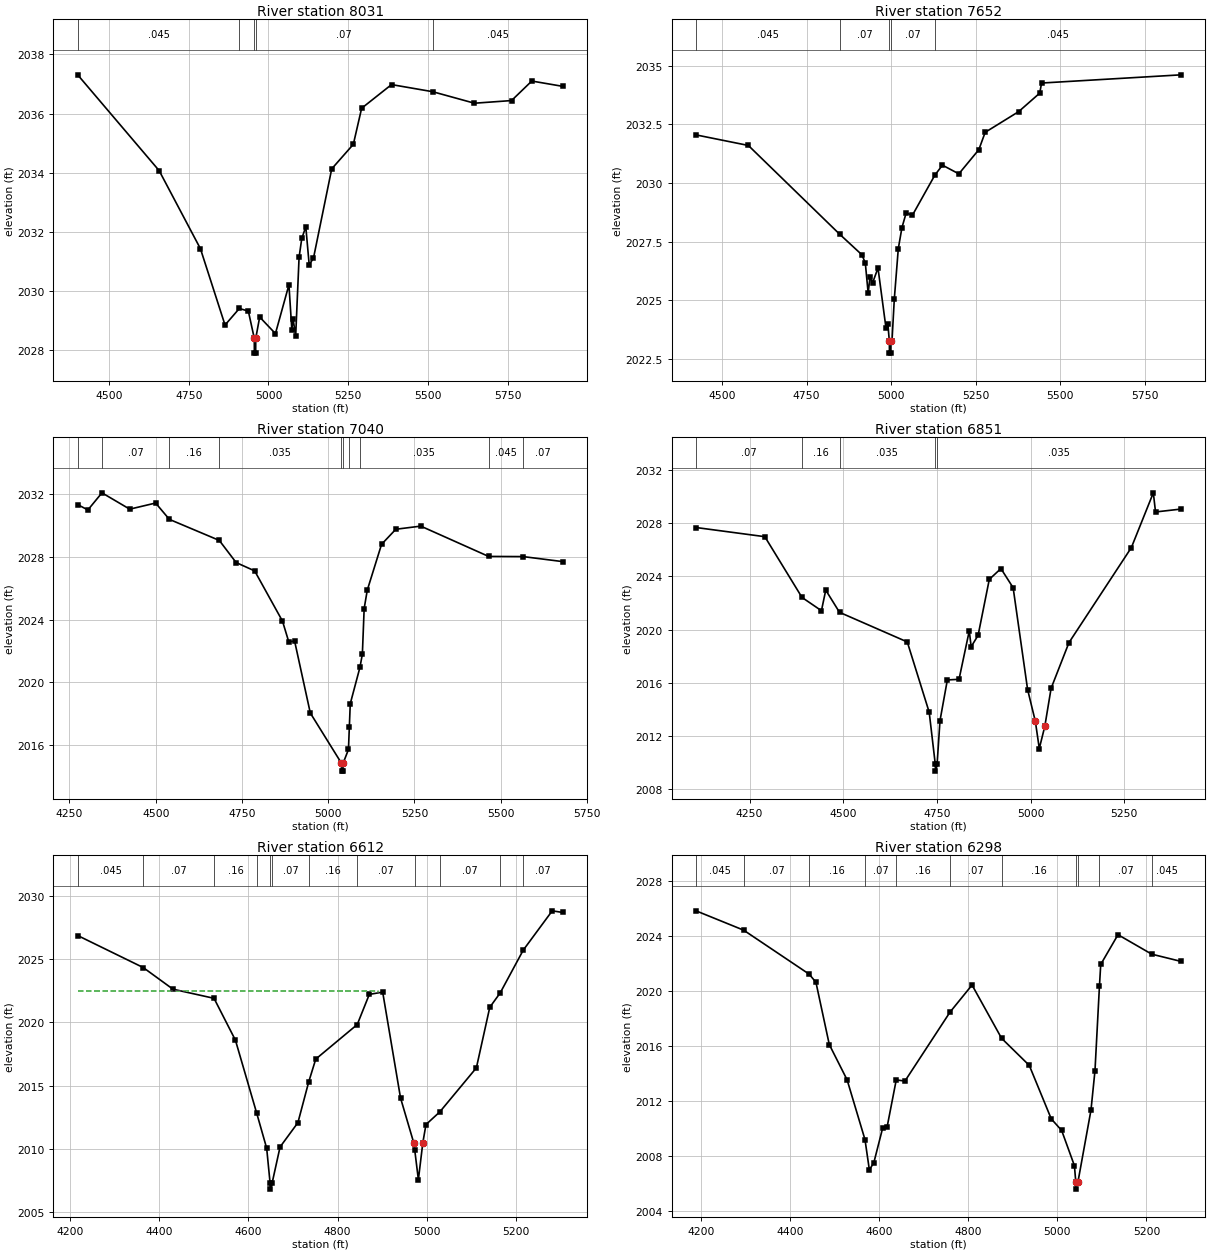
Type RM Length L Ch R = 1 ,8031    ,379,379,379
BEGIN DESCRIPTION:
NUBIA CREEK TRIBUTARY 2 16.0
END DESCRIPTION:
XS GIS Cut Line= 3
      1485547.83      6813757.82      1485904.24        6814238.
      1486776.94      6813938.39
#Sta/Elev= 30
    4402 2037.31  4657.4 2034.07  4786.8 2031.43  4863.9 2028.85  4908.8 2029.41
    4937 2029.32  4955.6  2028.4  4955.9  2027.9  4959.9  2027.9  4960.2  2028.4
  4972.5 2029.12  5021.9 2028.56  5064.2 2030.21  5073.3 2028.69    5077 2029.06
  5085.4 2028.49    5096 2031.14  5104.5 2031.78  5117.1 2032.17  5127.7 2030.89
  5141.1 2031.11  5198.3 2034.13  5266.1 2034.96  5292.1 2036.18  5385.8 2036.98
  5514.5 2036.74  5645.7 2036.35    5762 2036.44  5825.5  2037.1  5922.7 2036.92
#Mann= 5 ,-1 , 0
    4402    .045       0  4908.8     .07       0  4955.6     .07       0
  4960.2     .07       0  5514.5    .045       0
Bank Sta=4955.6,4960.2
XS Rating Curve= 0 ,0
Exp/Cntr=0.3,0.1

Type RM Length L Ch R = 1 ,7652    ,612,612,612
BEGIN DESCRIPTION:
NUBIA CREEK TRIBUTARY 2 15.0
END DESCRIPTION:
XS GIS Cut Line= 3
      1485453.62      6814344.61      1485985.23      6814568.17
       1486780.9      6814248.18
#Sta/Elev= 30
  4423.3 2032.05    4578  2031.6  4847.8 2027.82  4913.8 2026.94  4923.8 2026.59
  4932.2 2025.31  4937.6 2025.98  4945.5 2025.75  4961.3 2026.38  4985.1  2023.8
  4990.5 2023.99  4994.9 2023.25  4995.2 2022.75  4999.2 2022.75  4999.5 2023.25
  5002.6 2023.25  5009.5 2025.05  5021.3  2027.2  5032.1  2028.1  5044.5 2028.72
  5063.2 2028.63  5129.6 2030.34  5151.9 2030.76  5200.3 2030.39  5259.4 2031.42
  5278.2 2032.16    5377 2033.04  5439.5 2033.83  5444.9 2034.26  5857.6 2034.61
#Mann= 5 ,-1 , 0
  4423.3    .045       0  4847.8     .07       0  4994.9     .07       0
  4999.5     .07       0  5129.6    .045       0
Bank Sta=4994.9,4999.5
XS Rating Curve= 0 ,0
Exp/Cntr=0.3,0.1

Type RM Length L Ch R = 1 ,7040    ,189,189,189
BEGIN DESCRIPTION:
Mapping XS a333a435
END DESCRIPTION:
XS GIS Cut Line= 4
       1485484.9      6814555.16      1485565.62      6815036.89
      1486099.47      6815177.52      1486460.26      6815237.16
#Sta/Elev= 30
  4273.8 2031.32  4303.4 2030.98  4344.2 2032.07  4424.7 2031.03  4499.7 2031.42
  4539.6 2030.38  4684.3 2029.04  4733.1 2027.63  4786.8  2027.1  4867.5  2023.9
  4885.7 2022.58  4902.6 2022.63  4948.1 2018.05  5038.5 2014.85  5038.8 2014.35
  5042.8 2014.35  5043.2 2014.85  5058.7 2015.73  5061.2 2017.13  5063.9 2018.64
    5092 2020.96    5099  2021.8  5104.2  2024.7  5113.2 2025.87  5154.6 2028.79
  5195.9 2029.75  5268.3 2029.95    5465 2028.02  5564.8 2028.01    5680 2027.69
#Mann= 10 ,-1 , 0
  4273.8    .045       0  4344.2     .07       0  4539.6     .16       0
  4684.3    .035       0  5038.5    .035       0  5043.2    .035       0
  5061.2     .07       0    5092    .035       0    5465    .045       0
  5564.8     .07       0
Bank Sta=5038.5,5043.2
XS Rating Curve= 0 ,0
Exp/Cntr=0.3,0.1

Type RM Length L Ch R = 1 ,6851    ,239,239,239
BEGIN DESCRIPTION:
Mapping XS 07acf4d9
END DESCRIPTION:
XS GIS Cut Line= 3
       1484784.3       6815072.7      1485662.81      6815231.81
      1486045.84      6815353.49
#Sta/Elev= 30
  4107.2 2027.68  4290.8 2026.99    4390 2022.42  4441.9 2021.42  4453.4 2022.97
  4490.1  2021.3    4671 2019.07  4729.5 2013.78  4745.8 2009.85  4746.2 2009.35
  4750.5 2009.85  4758.3 2013.15  4777.9 2016.21  4809.1 2016.26  4836.4  2019.9
  4841.5 2018.71    4860 2019.57  4889.9 2023.78  4920.9 2024.59  4953.5 2023.15
  4992.1 2015.49  5012.8 2013.09  5023.3 2011.05    5038 2012.72  5054.8 2015.58
  5102.5 2019.02    5269 2026.17  5327.6 2030.29  5333.5 2028.85  5401.9 2029.07
#Mann= 5 ,-1 , 0
  4107.2     .07       0    4390     .16       0  4490.1    .035       0
  4745.8    .035       0  4750.5    .035       0
#XS Ineff= 2 , 0
       0  4920.9 2024.59               0
Permanent Ineff=
       F       F
Bank Sta=5012.8,5038
XS Rating Curve= 0 ,0
Exp/Cntr=0.3,0.1

Type RM Length L Ch R = 1 ,6612    ,314,314,314
BEGIN DESCRIPTION:
NUBIA CREEK TRIBUTARY 2 14.0
END DESCRIPTION:
XS GIS Cut Line= 3
      1484921.46      6815463.62      1485703.99      6815453.42
      1486008.69      6815452.77
#Sta/Elev= 30
  4217.4 2026.86  4364.3 2024.33    4431 2022.62    4523  2021.9    4571 2018.59
  4618.8 2012.81    4641 2010.06  4648.6 2007.33    4649 2006.83  4653.3 2007.33
    4671 2010.16    4711 2012.08  4735.3 2015.31    4751  2017.1    4844 2019.83
    4871 2022.21    4901 2022.39    4941 2014.03    4971 2010.44  4972.9  2009.9
    4981 2007.58    4991  2010.5    4998 2011.93    5029 2012.93    5111 2016.41
    5141 2021.19  5164.4 2022.33  5216.1 2025.71    5281 2028.81  5304.7 2028.68
#Mann= 12 ,-1 , 0
  4217.4    .045       0  4364.3     .07       0    4523     .16       0
  4618.8     .07       0  4648.6     .07       0  4653.3     .07       0
  4735.3     .16       0    4844     .07       0  4972.9     .16       0
    5029     .07       0  5164.4     .16       0  5216.1     .07       0
#XS Ineff= 2 , 0
       0    4891 2022.46               0
Permanent Ineff=
       F       F
Bank Sta=4971,4991
XS Rating Curve= 0 ,0
Exp/Cntr=0.3,0.1

Type RM Length L Ch R = 1 ,6298    ,295,295,295
BEGIN DESCRIPTION:
Mapping XS 7df94aa6
END DESCRIPTION:
XS GIS Cut Line= 4
      1484975.65      6815524.38      1485588.98      6815523.92
      1485720.05      6815678.46      1485969.65      6815791.32
#Sta/Elev= 30
  4188.2 2025.85  4295.2 2024.44  4442.5 2021.23  4457.6 2020.64  4487.6  2016.1
  4527.6 2013.53  4567.8 2009.17  4577.6 2006.97  4587.6 2007.48  4607.6 2010.03
  4617.6 2010.11    4638 2013.52  4657.6 2013.44  4758.7 2018.46  4808.3 2020.44
  4874.6 2016.56  4936.9 2014.58  4986.3 2010.68  5009.6 2009.84  5038.3 2007.27
  5041.4 2006.06  5041.7 2005.56  5046.1 2006.06  5075.5 2011.32  5084.5  2014.2
  5094.5 2020.34  5097.4 2021.94  5136.2 2024.11    5212 2022.69  5278.1 2022.16
#Mann= 11 ,-1 , 0
  4188.2    .045       0  4295.2     .07       0  4442.5     .16       0
  4567.8     .07       0    4638     .16       0  4758.7     .07       0
  4874.6     .16       0  5041.4     .07       0  5046.1     .16       0
  5094.5     .07       0    5212    .045       0
#XS Ineff= 2 , 0
       0  4808.3 2020.44               0
Permanent Ineff=
       F       F
Bank Sta=5041.4,5046.1
XS Rating Curve= 0 ,0
Exp/Cntr=0.3,0.1

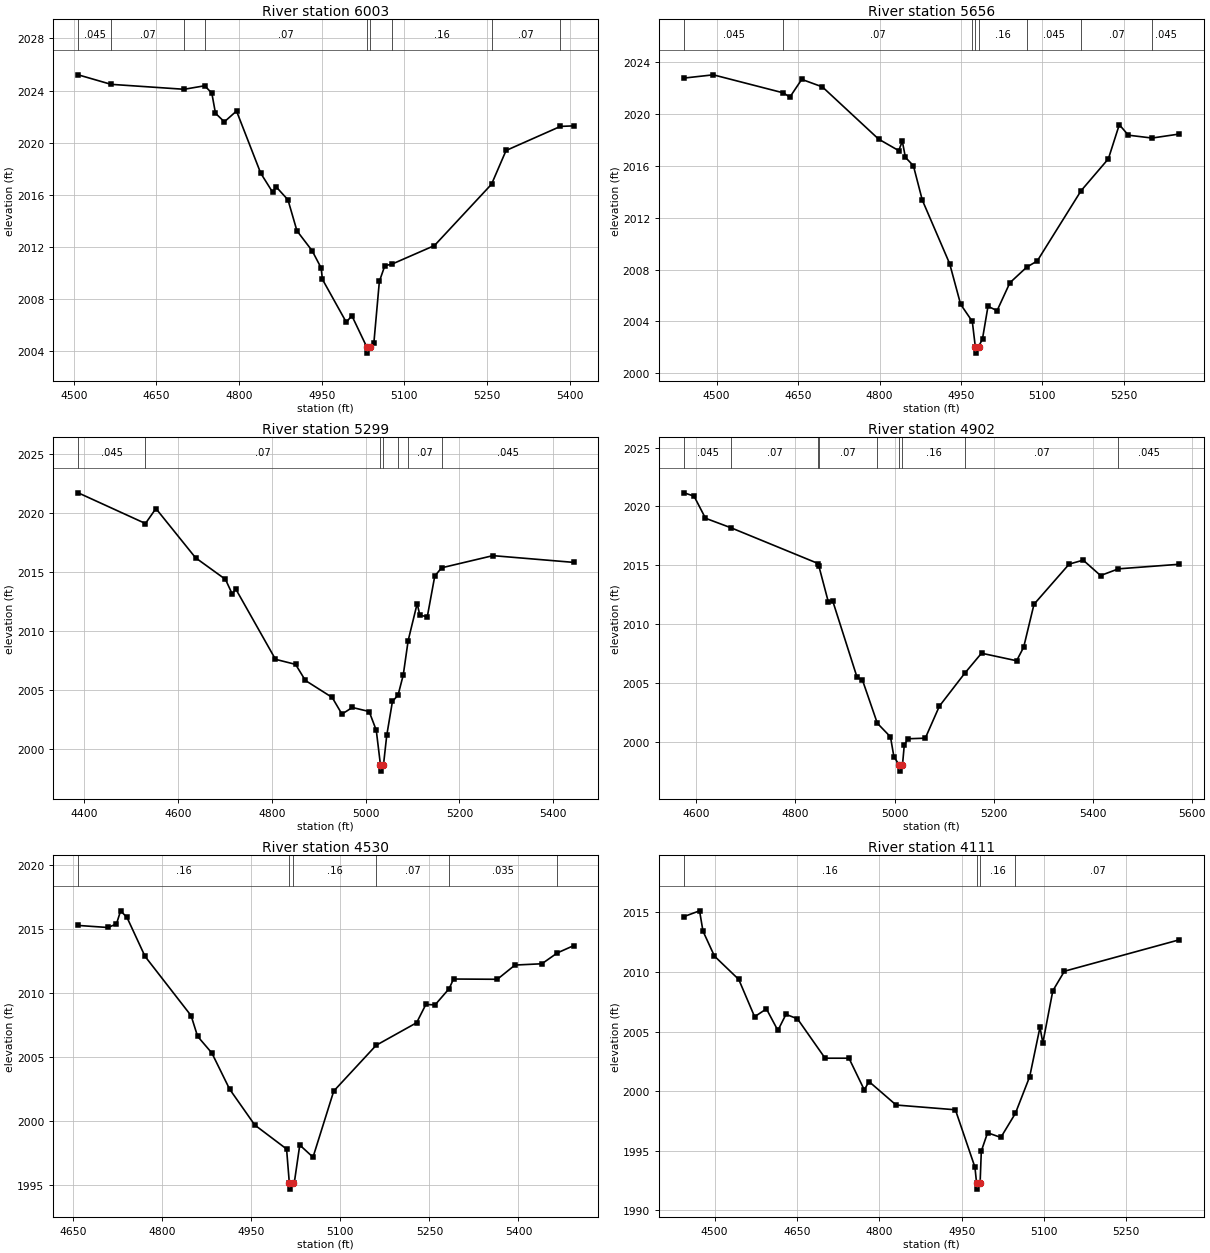
Type RM Length L Ch R = 1 ,6003    ,347,347,347
BEGIN DESCRIPTION:
Mapping XS 97ca5f61
END DESCRIPTION:
XS GIS Cut Line= 3
      1485071.17      6815674.84      1485463.97      6815885.35
      1485917.51      6815883.18
#Sta/Elev= 30
    4508 2025.21  4567.6 2024.48  4700.3  2024.1  4737.7 2024.37  4750.6  2023.8
  4757.2 2022.26  4773.3  2021.6  4795.4 2022.43  4839.3 2017.66  4861.2 2016.18
  4866.9 2016.63  4888.8 2015.61  4905.1 2013.23  4932.7  2011.7  4948.9 2010.39
  4951.4  2009.5  4994.7 2006.21  5004.7 2006.72  5031.5 2004.34    5032 2003.84
  5037.8 2004.34  5044.7 2004.61  5054.7 2009.35  5064.7 2010.56  5076.8 2010.66
  5154.7  2012.1  5258.3 2016.81  5284.7  2019.4  5383.4 2021.25  5407.2 2021.29
#Mann= 9 ,-1 , 0
    4508    .045       0  4567.6     .07       0  4700.3     .16       0
  4737.7     .07       0  5031.5     .07       0  5037.8     .07       0
  5076.8     .16       0  5258.3     .07       0  5383.4    .045       0
Bank Sta=5031.5,5037.8
XS Rating Curve= 0 ,0
Exp/Cntr=0.3,0.1

Type RM Length L Ch R = 1 ,5656    ,357,357,357
BEGIN DESCRIPTION:
Mapping XS a71bcf09
END DESCRIPTION:
XS GIS Cut Line= 3
      1485047.64      6816030.49      1485418.72      6816232.31
      1485904.83      6816171.54
#Sta/Elev= 30
    4440 2022.75  4493.9    2023  4622.9 2021.61  4634.9 2021.28  4656.8 2022.65
  4694.8 2022.07  4798.3 2018.05  4835.4 2017.16    4842 2017.89  4847.7 2016.64
  4862.4    2016  4878.8 2013.35  4929.2 2008.45  4949.4 2005.32  4970.9    2004
  4976.4 2002.06  4976.9 2001.56  4982.7 2002.06  4989.7 2002.67  4999.8 2005.17
  5016.5 2004.83  5040.1 2006.98    5071 2008.18  5090.5 2008.66  5171.2 2014.07
  5221.5 2016.53  5241.6 2019.16  5258.3 2018.35  5301.9 2018.13  5352.3 2018.44
#Mann= 8 ,-1 , 0
    4440    .045       0  4622.9     .07       0  4970.9     .16       0
  4976.4     .07       0  4982.7     .16       0    5071    .045       0
  5171.2     .07       0  5301.9    .045       0
Bank Sta=4976.4,4982.7
XS Rating Curve= 0 ,0
Exp/Cntr=0.3,0.1

Type RM Length L Ch R = 1 ,5299    ,397,397,397
BEGIN DESCRIPTION:
NUBIA CREEK TRIBUTARY 2 11.0
END DESCRIPTION:
XS GIS Cut Line= 3
      1485086.72      6816143.36      1485555.34      6816538.38
      1485940.86        6816757.
#Sta/Elev= 30
  4387.1 2021.71  4530.5 2019.11  4552.8 2020.38  4637.3 2016.21  4701.1 2014.38
  4715.4 2013.15  4723.1 2013.56  4807.7 2007.61  4850.6 2007.18  4871.4 2005.82
  4928.6 2004.38  4949.4 2002.97  4971.5 2003.53  5007.4 2003.19  5022.6  2001.6
  5031.6 1998.64  5032.1 1998.14  5037.9 1998.64  5044.9 2001.16  5057.1 2004.05
    5069 2004.57  5080.1 2006.28  5090.6  2009.2  5109.8 2012.33  5115.5 2011.34
  5131.4 2011.22  5147.3 2014.66  5161.9 2015.36  5271.3 2016.39  5443.2 2015.82
#Mann= 7 ,-1 , 0
  4387.1    .045       0  4530.5     .07       0  5031.6     .07       0
  5037.9     .07       0    5069    .045       0  5090.6     .07       0
  5161.9    .045       0
Bank Sta=5031.6,5037.9
XS Rating Curve= 0 ,0
Exp/Cntr=0.3,0.1

Type RM Length L Ch R = 1 ,4902    ,372,372,372
BEGIN DESCRIPTION:
Mapping XS 6eeca902
END DESCRIPTION:
XS GIS Cut Line= 3
       1485011.9      6816224.23      1485155.12      6816543.22
      1485634.28      6816983.36
#Sta/Elev= 30
    4575 2021.16  4595.2 2020.88  4618.3    2019  4670.4 2018.18  4845.9 2015.15
    4847 2014.98  4866.5 2011.87  4875.1 2011.99  4924.5 2005.47  4935.2 2005.26
  4965.3 2001.58  4991.9 2000.42  4998.7 1998.75  5009.7 1998.01  5010.2 1997.51
  5016.1 1998.01  5019.7 1999.71  5027.1 2000.26  5062.2 2000.31  5090.6 2003.03
  5141.9 2005.83  5175.7 2007.53  5246.6 2006.89  5260.8 2008.04  5281.7 2011.69
  5352.6  2015.1    5381 2015.44  5416.1 2014.13  5452.2  2014.7  5575.3 2015.09
#Mann= 9 ,-1 , 0
    4575    .045       0  4670.4     .07       0  4845.9     .16       0
    4847     .07       0  4965.3     .16       0  5009.7     .07       0
  5016.1     .16       0  5141.9     .07       0  5452.2    .045       0
Bank Sta=5009.7,5016.1
XS Rating Curve= 0 ,0
Exp/Cntr=0.3,0.1

Type RM Length L Ch R = 1 ,4530    ,419,419,419
BEGIN DESCRIPTION:
Mapping XS a85a0d3e
END DESCRIPTION:
XS GIS Cut Line= 3
      1484738.88      6816759.36      1485072.22      6816894.78
      1485530.27       6817017.1
#Sta/Elev= 30
  4658.8 2015.28  4708.6 2015.12  4723.2 2015.39  4730.2 2016.42    4741  2015.9
  4771.3 2012.87  4848.9 2008.24  4859.8 2006.63  4883.8 2005.33  4913.7 2002.51
  4956.1 1999.71  5009.6 1997.84  5014.2 1995.21  5014.7 1994.71  5020.6 1995.21
  5022.6 1995.21  5031.8 1998.15  5054.1  1997.2    5089 2002.36  5160.4 2005.93
  5228.5 2007.69  5244.1 2009.12  5259.5 2009.08  5283.3 2010.35  5290.6  2011.1
  5364.4 2011.08  5394.1 2012.19  5439.4 2012.29  5465.5 2013.14  5492.7  2013.7
#Mann= 6 ,-1 , 0
  4658.8     .16       0  5014.2     .07       0  5020.6     .16       0
  5160.4     .07       0  5283.3    .035       0  5465.5     .07       0
Bank Sta=5014.2,5020.6
XS Rating Curve= 0 ,0
Exp/Cntr=0.3,0.1

Type RM Length L Ch R = 1 ,4111    ,513,513,513
BEGIN DESCRIPTION:
Mapping XS 827bb6e2
END DESCRIPTION:
XS GIS Cut Line= 3
      1484600.19      6816954.23      1485042.92      6817269.35
      1485384.09      6817381.33
#Sta/Elev= 30
  4444.2 2014.66  4472.5 2015.14  4478.7 2013.44  4499.6 2011.34  4543.9 2009.38
  4572.8 2006.25  4594.3 2006.91  4615.2  2005.1  4629.9 2006.45  4650.8 2006.08
  4701.2 2002.77  4744.7 2002.77  4772.6 2000.11  4781.2 2000.81  4830.6 1998.84
  4938.6 1998.44  4974.2 1993.62  4977.2 1992.28  4977.7 1991.78  4983.6 1992.28
  4985.8 1994.97  4997.2 1996.51  5021.4 1996.12  5047.9 1998.14    5074 2001.23
  5092.7 2005.37  5097.9 2004.05  5116.1 2008.43  5137.2 2010.07  5346.7 2012.71
#Mann= 4 ,-1 , 0
  4444.2     .16       0  4977.2     .07       0  4983.6     .16       0
  5047.9     .07       0
Bank Sta=4977.2,4983.6
XS Rating Curve= 0 ,0
Exp/Cntr=0.3,0.1

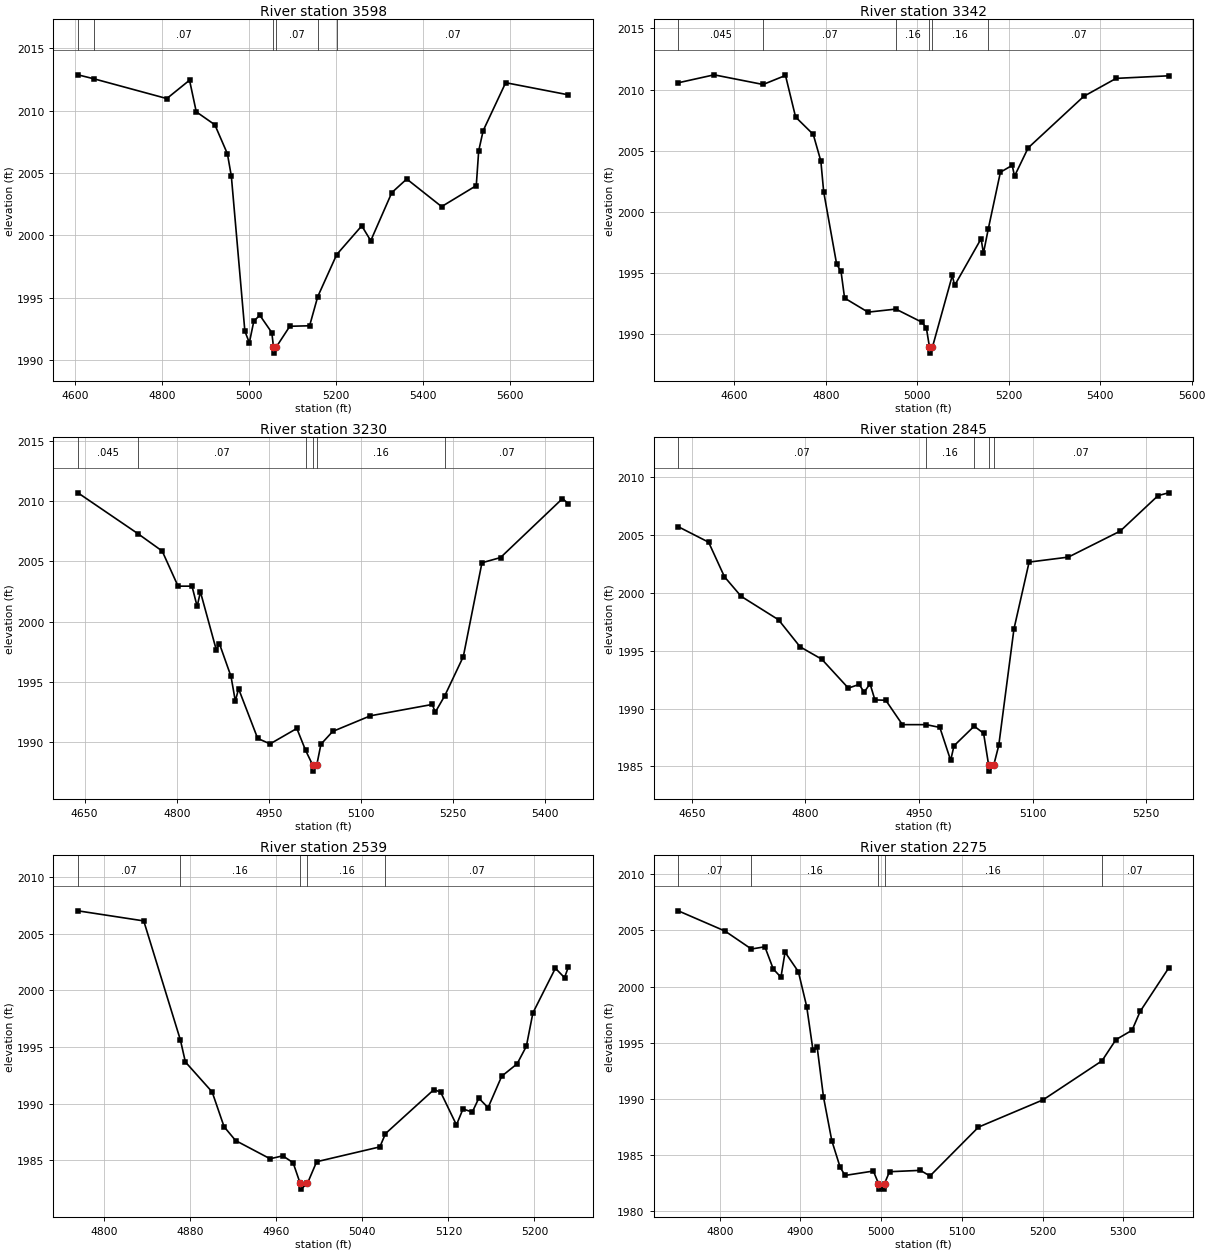
Type RM Length L Ch R = 1 ,3598    ,256,256,256
BEGIN DESCRIPTION:
Mapping XS 72678924
END DESCRIPTION:
XS GIS Cut Line= 3
      1484229.58      6817180.62       1484510.8      6817349.87
      1485284.21       6817558.2
#Sta/Elev= 30
  4605.8 2012.86  4643.9 2012.53  4810.5 2010.96  4862.8 2012.43  4878.3  2009.9
  4921.1 2008.86    4950 2006.54  4959.1 2004.74  4990.2 1992.34  5000.5 1991.41
  5010.9 1993.15  5024.7 1993.61  5052.3 1992.22  5056.1 1991.08  5056.6 1990.58
  5062.7 1991.08  5093.7 1992.73  5139.3 1992.77    5158  1995.1  5201.7 1998.47
  5259.4 2000.77  5280.1 1999.58  5328.6 2003.43    5363 2004.52  5443.3 2002.31
  5523.1 2003.99  5528.7 2006.78    5539 2008.39  5590.8 2012.23    5735 2011.26
#Mann= 6 ,-1 , 0
  4605.8    .045       0  4643.9     .07       0  5056.1     .07       0
  5062.7     .07       0    5158     .16       0  5201.7     .07       0
Bank Sta=5056.1,5062.7
XS Rating Curve= 0 ,0
Exp/Cntr=0.3,0.1

Type RM Length L Ch R = 1 ,3342    ,112,112,112
BEGIN DESCRIPTION:
Mapping XS be9b6af8
END DESCRIPTION:
XS GIS Cut Line= 3
      1484182.64      6817368.08      1484661.84      6817592.06
      1485198.35       6817675.4
#Sta/Elev= 30
  4477.7 2010.56  4556.1 2011.21  4663.2 2010.42  4712.1 2011.16  4734.2 2007.76
  4772.8 2006.34  4789.4 2004.16  4795.6 2001.65    4824 1995.72  4833.5 1995.14
  4841.3 1992.96  4892.5 1991.81  4953.4 1992.06  5009.7    1991    5020 1990.54
  5026.8 1988.96  5027.3 1988.46  5033.4 1988.96  5076.8 1994.81  5081.8 1993.99
  5139.7 1997.81  5144.8 1996.63  5155.4 1998.61  5181.9 2003.25  5207.7 2003.81
  5212.8 2002.93  5242.6 2005.24  5364.1 2009.45  5434.9 2010.92  5549.6 2011.13
#Mann= 6 ,-1 , 0
  4477.7    .045       0  4663.2     .07       0  4953.4     .16       0
  5026.8     .07       0  5033.4     .16       0  5155.4     .07       0
Bank Sta=5026.8,5033.4
XS Rating Curve= 0 ,0
Exp/Cntr=0.3,0.1

Type RM Length L Ch R = 1 ,3230    ,385,385,385
BEGIN DESCRIPTION:
Mapping XS 094d6634
END DESCRIPTION:
XS GIS Cut Line= 3
      1484269.74      6817568.17      1484606.08      6817685.35
      1485044.47       6817739.6
#Sta/Elev= 30
  4639.3 2010.69  4736.7 2007.31  4776.4 2005.86  4802.2 2002.95  4824.9 2002.95
  4833.3 2001.27  4838.6 2002.48  4864.4 1997.67  4869.6 1998.17  4888.4 1995.46
  4895.4 1993.42  4900.7 1994.44  4931.8 1990.32    4952 1989.87  4995.5 1991.15
  5009.6 1989.35  5021.3 1988.11  5021.8 1987.61  5027.9 1988.11  5034.7 1989.84
  5053.8  1990.9  5115.3  1992.2  5215.8 1993.14  5220.8  1992.5  5236.2 1993.86
  5266.4 1997.11  5296.7 2004.89  5326.9 2005.32  5427.7 2010.21  5437.2  2009.8
#Mann= 6 ,-1 , 0
  4639.3    .045       0  4736.7     .07       0  5009.6     .16       0
  5021.3     .07       0  5027.9     .16       0  5236.2     .07       0
Bank Sta=5021.3,5027.9
XS Rating Curve= 0 ,0
Exp/Cntr=0.3,0.1

Type RM Length L Ch R = 1 ,2845    ,306,306,306
BEGIN DESCRIPTION:
Mapping XS bbca9420
END DESCRIPTION:
XS GIS Cut Line= 3
      1484438.94       6817737.4      1484716.76      6817973.98
      1484998.83      6817991.34
#Sta/Elev= 30
  4632.2 2005.73  4672.3 2004.39  4693.2  2001.4  4715.2 1999.71  4764.6 1997.68
  4793.1 1995.34  4821.7 1994.27  4856.8 1991.77  4871.1 1992.09  4877.7 1991.41
  4885.4 1992.15  4891.9 1990.75  4906.2 1990.72  4928.2 1988.61  4959.6 1988.61
  4977.6 1988.37  4991.9 1985.52  4996.3 1986.78    5023 1988.48  5035.4 1987.86
  5042.1 1985.09  5042.6 1984.59  5048.7 1985.09  5055.4 1986.81  5075.5 1996.89
  5095.5 2002.67  5147.3  2003.1  5215.8 2005.35  5265.8 2008.42  5279.7 2008.66
#Mann= 5 ,-1 , 0
  4632.2     .07       0  4959.6     .16       0    5023     .07       0
  5042.1     .07       0  5048.7     .07       0
Bank Sta=5042.1,5048.7
XS Rating Curve= 0 ,0
Exp/Cntr=0.3,0.1

Type RM Length L Ch R = 1 ,2539    ,264,264,264
BEGIN DESCRIPTION:
Mapping XS 88994dfd
END DESCRIPTION:
XS GIS Cut Line= 3
      1484354.35      6817830.77       1484430.3      6818032.57
      1484625.17      6818173.31
#Sta/Elev= 30
  4775.5 2007.03  4836.7 2006.14  4870.8 1995.62  4875.4 1993.69  4900.3 1991.04
  4911.4 1987.97  4922.1 1986.75  4954.2 1985.14    4966  1985.4  4975.6 1984.79
  4982.2 1982.96  4982.7 1982.46  4988.9 1982.96  4997.5 1984.88  5056.3 1986.19
  5061.5 1987.36  5106.6 1991.25  5112.8 1991.02  5127.5 1988.13  5133.6 1989.54
  5142.2 1989.26  5148.3 1990.49  5156.9 1989.65  5169.6 1992.43  5183.9 1993.52
  5192.5 1995.07  5198.6 1998.02  5219.5 2001.96    5228 2001.13  5231.5 2002.05
#Mann= 5 ,-1 , 0
  4775.5     .07       0  4870.8     .16       0  4982.2     .07       0
  4988.9     .16       0  5061.5     .07       0
Bank Sta=4982.2,4988.9
XS Rating Curve= 0 ,0
Exp/Cntr=0.3,0.1

Type RM Length L Ch R = 1 ,2275    ,326,326,326
BEGIN DESCRIPTION:
Mapping XS 6c8965e8
END DESCRIPTION:
XS GIS Cut Line= 3
      1484011.44      6818108.52      1484234.98      6818169.29
      1484610.22      6818188.81
#Sta/Elev= 30
  4748.6 2006.75  4806.5 2004.95  4839.2 2003.35  4855.9 2003.55  4866.3 2001.57
  4875.8 2000.84  4880.9 2003.07  4897.4 2001.33  4907.7 1998.23  4915.5 1994.34
  4920.7  1994.6  4928.5 1990.18  4938.8 1986.29  4949.2 1983.91  4955.3  1983.2
  4990.3 1983.59  4996.6 1982.48  4997.1 1981.98  5003.6 1981.98  5004.1 1982.48
  5010.3 1983.53  5048.5 1983.65  5060.4 1983.15  5120.5  1987.5  5200.6 1989.93
  5273.5  1993.4  5290.7 1995.28  5310.7 1996.12  5320.7 1997.79    5356 2001.65
#Mann= 5 ,-1 , 0
  4748.6     .07       0  4839.2     .16       0  4996.6     .07       0
  5004.1     .16       0  5273.5     .07       0
Bank Sta=4996.6,5004.1
XS Rating Curve= 0 ,0
Exp/Cntr=0.3,0.1