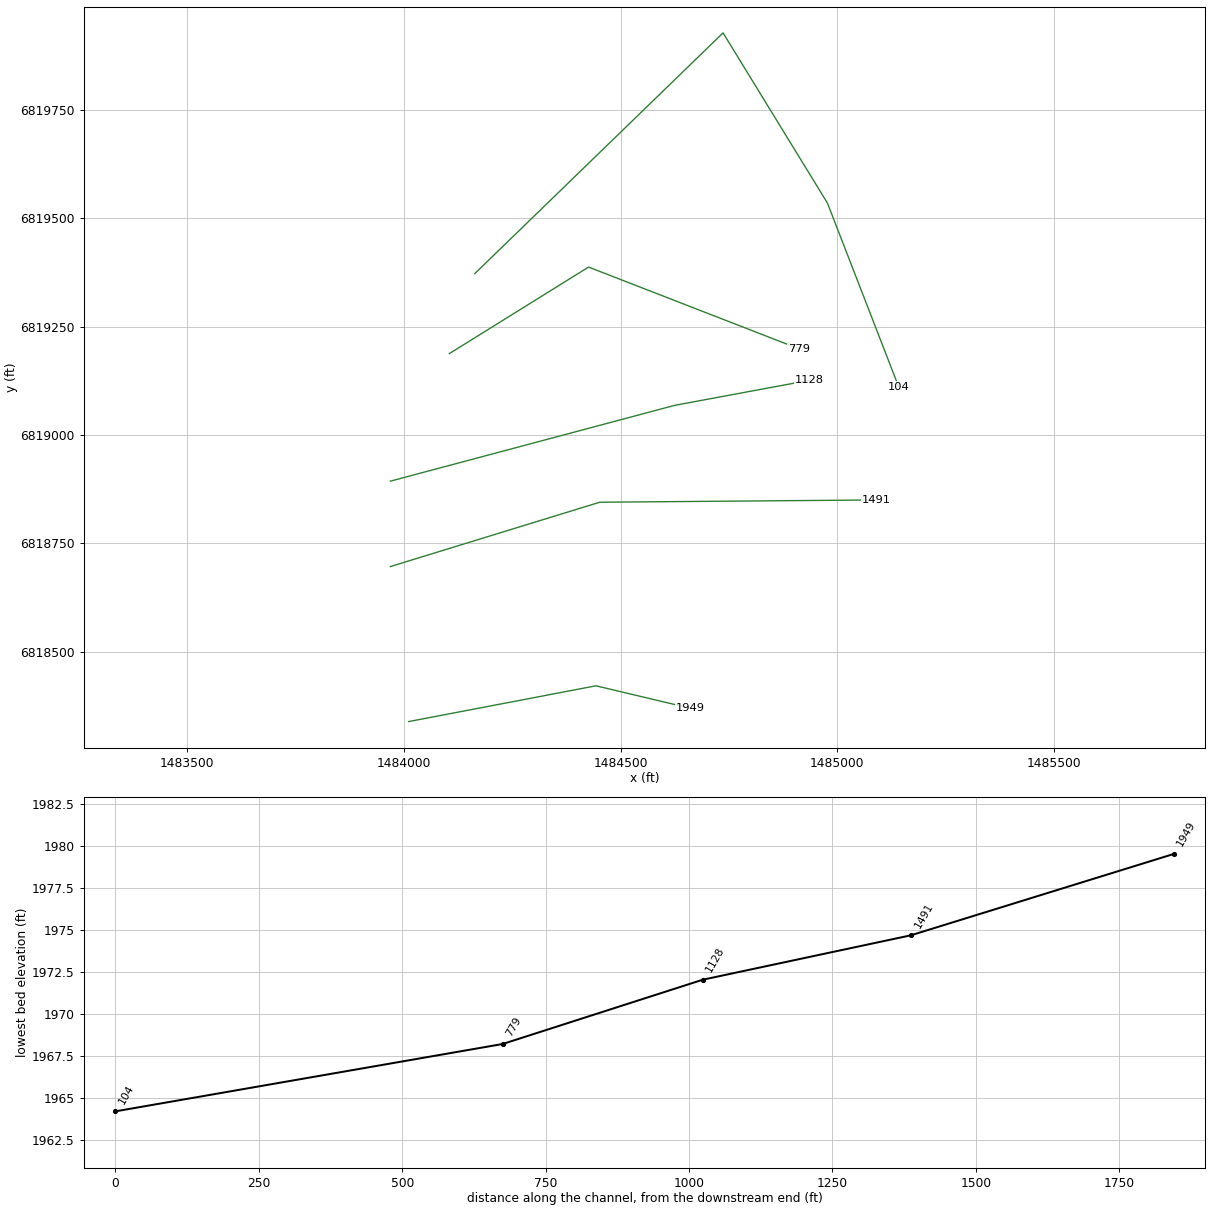
HEC-RAS study NUBIA CREEK TRIBUTARY 2.prj: NUBIA CREEK TRIBUTARY 2 Base Level Engineering

--- NUBIA CREEK TRIBUTARY 2.g01 (geometry) --- (continued)

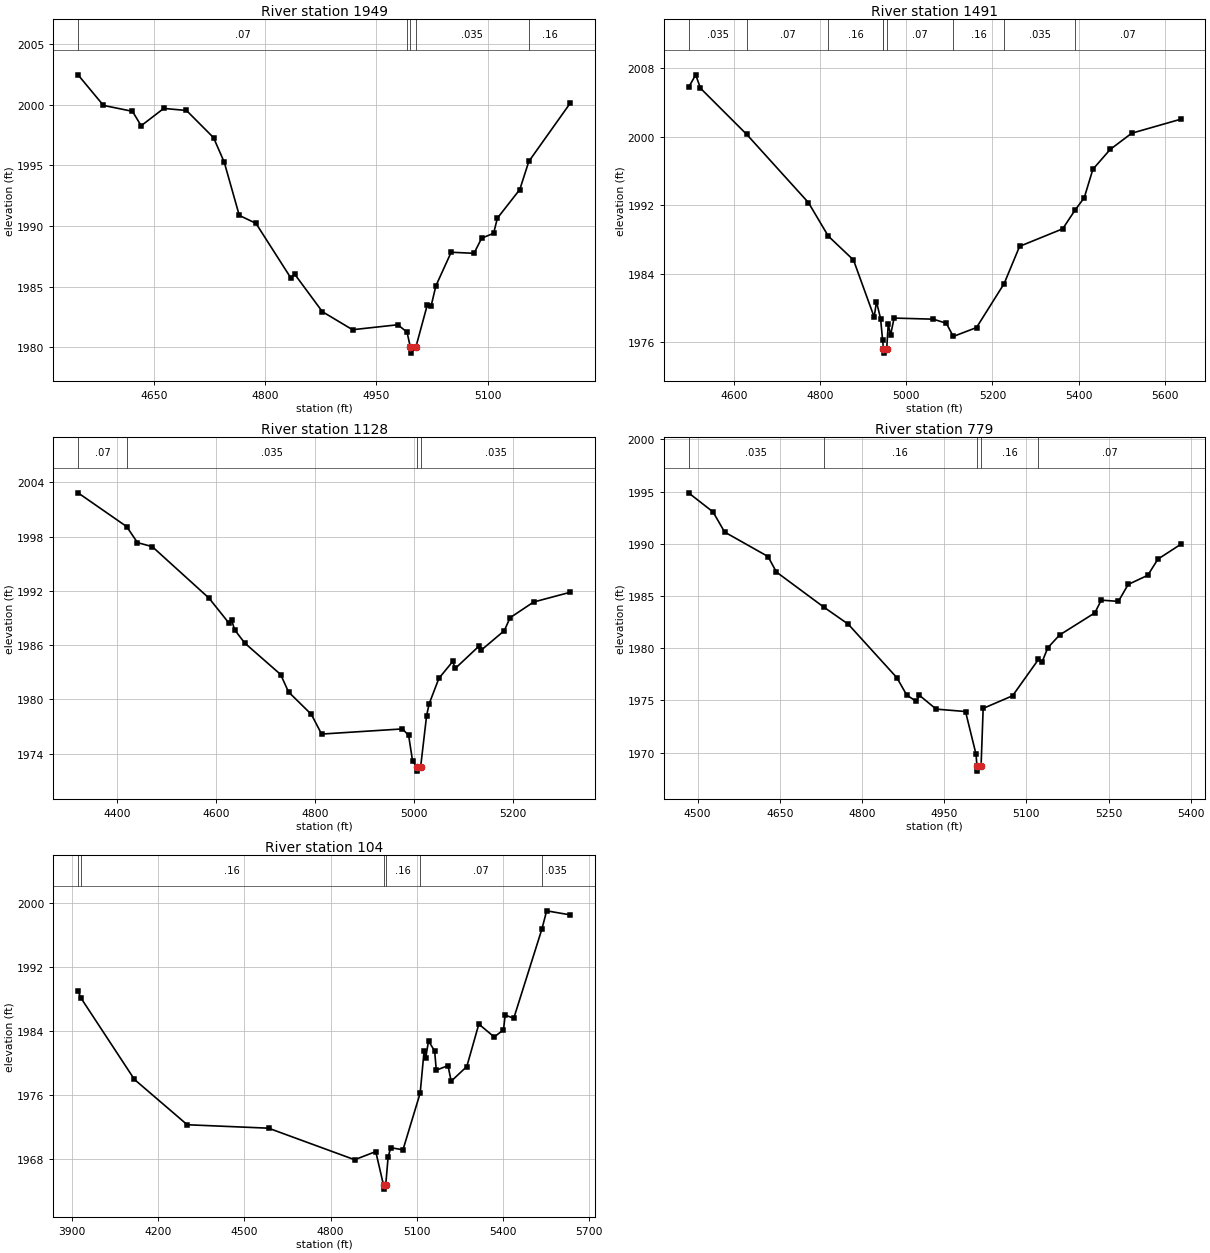
Type RM Length L Ch R = 1 ,1949    ,458,458,458
BEGIN DESCRIPTION:
Mapping XS 9f54c9cd
END DESCRIPTION:
XS GIS Cut Line= 3
      1484011.42      6818338.55      1484443.32      6818421.03
      1484661.25      6818369.24
#Sta/Elev= 30
  4547.6 2002.47  4581.8 1999.95    4621 1999.46  4632.7 1998.27  4663.2  1999.7
  4693.8 1999.53  4730.3 1997.29  4744.7 1995.27    4765 1990.88  4787.5 1990.22
  4834.5 1985.72  4839.6 1986.04    4877 1982.94  4917.7 1981.45  4978.8 1981.86
  4991.2 1981.25  4995.6 1980.02  4996.1 1979.52  5003.1 1980.02  5018.4 1983.47
  5023.5 1983.37  5030.1 1985.07  5050.7 1987.84  5081.5 1987.75  5091.8    1989
  5107.9  1989.4    5113 1990.65  5143.2 1993.01  5155.4 1995.33  5211.3 2000.14
#Mann= 5 ,-1 , 0
  4547.6     .07       0  4991.2    .035       0  4995.6    .035       0
  5003.1    .035       0  5155.4     .16       0
Bank Sta=4995.6,5003.1
XS Rating Curve= 0 ,0
Exp/Cntr=0.3,0.1

Type RM Length L Ch R = 1 ,1491    ,363,363,363
BEGIN DESCRIPTION:
NUBIA CREEK TRIBUTARY 2 3.0
END DESCRIPTION:
XS GIS Cut Line= 3
      1483969.15      6818696.23      1484452.07       6818844.6
      1485088.94      6818849.87
#Sta/Elev= 30
  4494.8 2005.76  4511.4 2007.24  4522.5 2005.67  4629.8 2000.27  4772.9  1992.3
    4819 1988.38  4877.5 1985.58  4925.5  1978.9  4930.8 1980.71  4940.3 1978.73
  4945.1 1976.19    4947 1975.19  4947.5 1974.69  4954.5 1975.19  4958.2  1978.1
  4963.5  1976.8  4971.7 1978.79  5062.9 1978.66  5092.9 1978.18    5109 1976.64
  5162.9 1977.68    5227 1982.82  5262.9 1987.18  5362.9 1989.23  5391.3  1991.4
  5412.9 1992.87  5432.9 1996.19    5473 1998.51    5523 2000.41  5636.9 2002.05
#Mann= 9 ,-1 , 0
  4494.8    .035       0  4629.8     .07       0    4819     .16       0
  4945.1     .07       0    4947     .07       0  4954.5     .07       0
    5109     .16       0    5227    .035       0  5391.3     .07       0
Bank Sta=4947,4954.5
XS Rating Curve= 0 ,0
Exp/Cntr=0.3,0.1

Type RM Length L Ch R = 1 ,1128    ,349,349,349
BEGIN DESCRIPTION:
NUBIA CREEK TRIBUTARY 2 2.0
END DESCRIPTION:
XS GIS Cut Line= 3
      1483969.18      6818893.29      1484625.46      6819068.24
      1484936.15      6819125.91
#Sta/Elev= 30
  4320.8 2002.84    4419 1999.11    4441 1997.33  4470.8 1996.89  4585.6 1991.19
    4626 1988.42  4631.2  1988.8  4637.3 1987.69    4658 1986.21  4730.4 1982.74
  4746.4 1980.81  4792.5 1978.33  4813.2 1976.15  4976.7 1976.72  4989.2    1976
  4997.2 1973.14  5005.9 1972.55  5006.4 1972.05  5013.5 1972.55  5025.5 1978.18
  5030.6 1979.49  5050.4 1982.32  5078.3 1984.18  5083.4 1983.41  5131.2 1985.87
  5136.3 1985.45  5182.6 1987.59  5194.2 1989.02  5241.9 1990.76    5316 1991.84
#Mann= 4 ,-1 , 0
  4320.8     .07       0    4419    .035       0  5005.9    .035       0
  5013.5    .035       0
Bank Sta=5005.9,5013.5
XS Rating Curve= 0 ,0
Exp/Cntr=0.3,0.1

Type RM Length L Ch R = 1 ,779     ,675,675,675
BEGIN DESCRIPTION:
Mapping XS faa2d77d
END DESCRIPTION:
XS GIS Cut Line= 3
       1484105.1      6819187.54      1484426.25      6819387.17
      1484911.22      6819198.81
#Sta/Elev= 30
  4483.4 1994.89  4528.1 1993.06  4549.3 1991.13  4628.4 1988.79  4643.8  1987.3
  4729.8 1983.96  4774.8 1982.31  4863.6 1977.18  4881.7 1975.51  4899.2 1974.91
  4904.6  1975.5  4935.3 1974.17  4988.9 1973.94  5008.1 1969.84  5009.7 1968.73
  5010.2 1968.23  5017.3 1968.73  5021.1 1974.24  5074.8 1975.45    5122 1978.93
  5128.4 1978.66  5139.1 1980.05  5160.6 1981.27  5224.9 1983.39  5236.6 1984.61
  5267.9 1984.49  5285.7 1986.11  5321.5 1986.99  5340.1 1988.54  5381.8 1989.96
#Mann= 5 ,-1 , 0
  4483.4    .035       0  4729.8     .16       0  5009.7     .07       0
  5017.3     .16       0    5122     .07       0
Bank Sta=5009.7,5017.3
XS Rating Curve= 0 ,0
Exp/Cntr=0.3,0.1

Type RM Length L Ch R = 1 ,104     ,0,0,0
BEGIN DESCRIPTION:
NUBIA CREEK TRIBUTARY 2 1.0
END DESCRIPTION:
XS GIS Cut Line= 4
      1484163.65      6819371.97      1484736.58      6819927.53
      1484977.47      6819534.74       1485141.7       6819111.2
#Sta/Elev= 30
    3921 1989.03  3930.9 1988.17  4117.3 1977.96    4301 1972.29  4583.9 1971.86
  4883.6 1967.91  4957.1 1968.93  4984.1 1964.73  4984.6 1964.23  4991.8 1964.73
  5000.1 1968.24  5009.2 1969.42  5051.8 1969.15  5111.7 1976.26  5125.3 1981.53
  5131.1  1980.7  5140.7 1982.77    5162 1981.53  5167.8 1979.12  5208.5 1979.69
  5219.6 1977.74    5274 1979.58  5315.8 1984.89  5369.4 1983.28  5401.6 1984.17
  5407.5 1986.02  5437.4 1985.62  5535.5 1996.81  5551.8 1999.07  5634.1 1998.56
#Mann= 6 ,-1 , 0
    3921    .035       0  3930.9     .16       0  4984.1     .07       0
  4991.8     .16       0  5111.7     .07       0  5535.5    .035       0
Bank Sta=4984.1,4991.8
XS Rating Curve= 0 ,0
Exp/Cntr=0.3,0.1

Chan Stop Cuts=-1
Use User Specified Reach Order=0
Composite Channel Slope=5