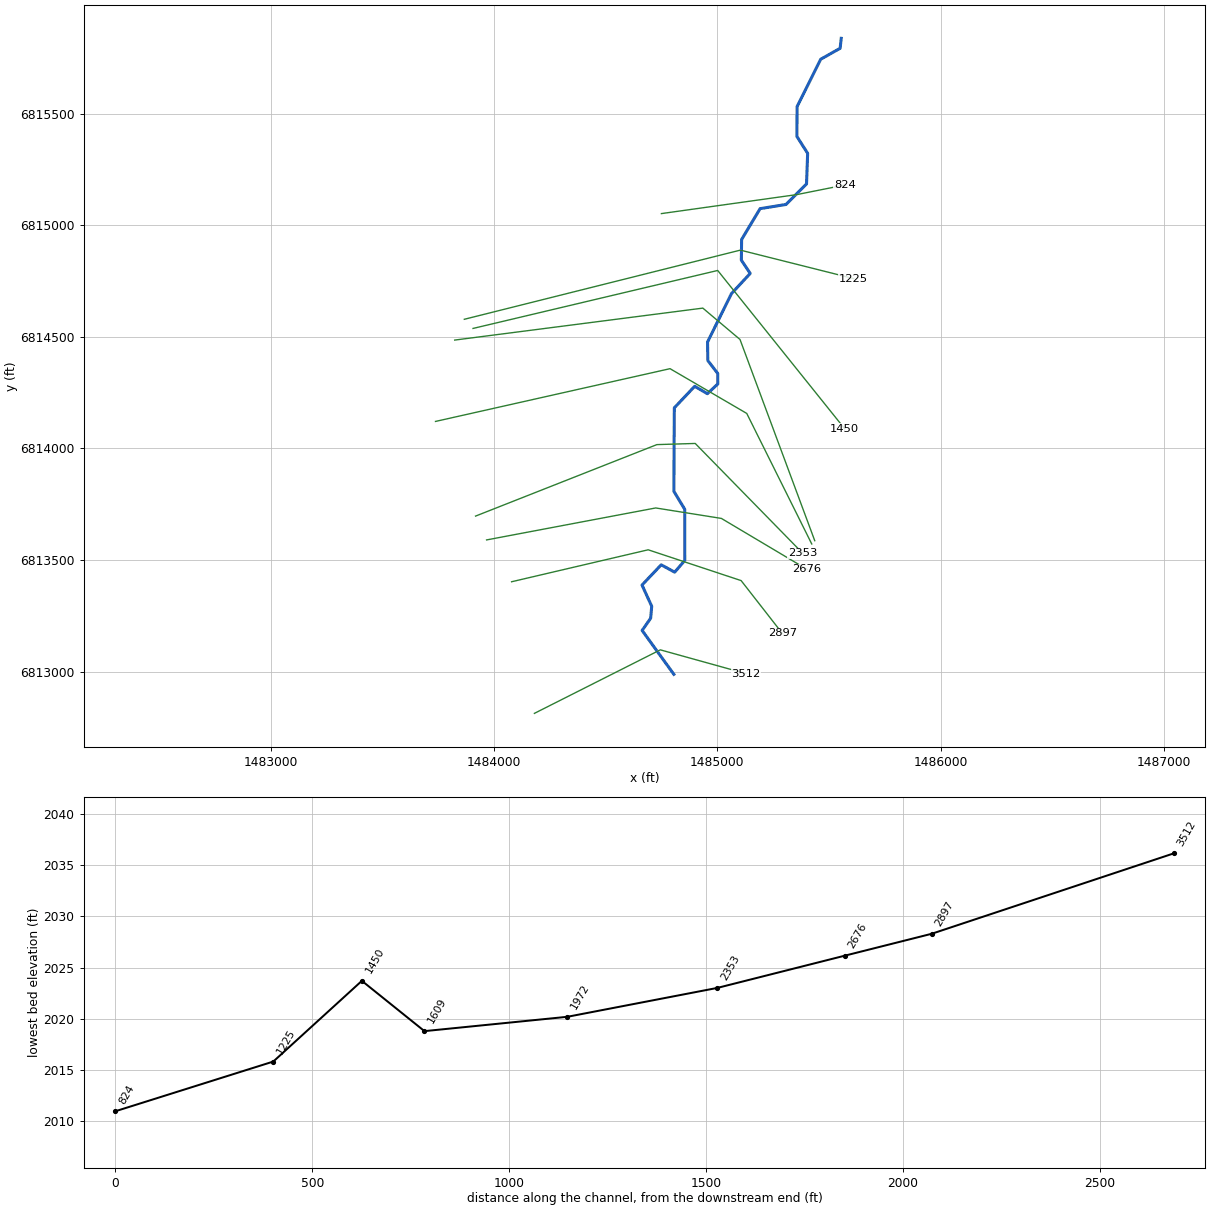
--- NUBIA CREEK TRIBUTARY 2_1.prj (project) ---

Proj Title=NUBIA CREEK TRIBUTARY 2_1 Base Level Engineering
Current Plan=p01
Default Exp/Contr=0.3,0.1
English Units
Geom File=g01
Flow File=f01
Plan File=p01
Y Axis Title=Elevation
X Axis Title(PF)=Main Channel Distance
X Axis Title(XS)=Station
BEGIN DESCRIPTION:
NUBIA CREEK TRIBUTARY 2_1
END DESCRIPTION:
DSS Export Rating Curves= 0
DSS Export Rating Curve Sorted= 0
DSS Export Volume Flow Curves= 0
DXF OffsetX= 0
DXF OffsetY= 0
DXF ScaleX= 1
DXF ScaleY= 10

--- NUBIA CREEK TRIBUTARY 2_1.p01 (plan) ---

Plan Title=Multiple Run
Short Identifier=Multiple
Geom File=g01
Flow File=f01
Subcritical Flow
K Sum by GR= 0
Std Step Tol= 0.01
Critical Tol= 0.01
Num of Std Step Trials= 20
Max Error Tol= 0.3
Flow Tol Ratio= 0.001
Split Flow NTrial= 30
Split Flow Tol= 0.02
Split Flow Ratio= 0.02
Log Output Level= 0
Friction Slope Method= 1
Unsteady Friction Slope Method= 2
Unsteady Bridges Friction Slope Method= 1
Parabolic Critical Depth
Global Vel Dist=  1 , 1 , 1
Global Log Level= 0
CheckData=True
Encroach Param= -1, 0, 0, 0
BEGIN DESCRIPTION:
Multiple Run
END DESCRIPTION:

--- NUBIA CREEK TRIBUTARY 2_1.f01 (steady flow) ---

Flow Title=Multiple
Number of Profiles=7
Profile Names=10-year,25-year,50-year,1pct_min,100-year,1pct_plu,500-year
River Rch & RM= NUBIA CREEK TRIB,Reach-1,3512
     304     435     547     343     684    1364    1080
Boundary for River Rch & Prof#=NUBIA CREEK TRIB,Reach-1,1
Up Type=0
Dn Type=3
Dn Slope=0.005
Boundary for River Rch & Prof#=NUBIA CREEK TRIB,Reach-1,2
Up Type=0
Dn Type=3
Dn Slope=0.005
Boundary for River Rch & Prof#=NUBIA CREEK TRIB,Reach-1,3
Up Type=0
Dn Type=3
Dn Slope=0.005
Boundary for River Rch & Prof#=NUBIA CREEK TRIB,Reach-1,4
Up Type=0
Dn Type=3
Dn Slope=0.005
Boundary for River Rch & Prof#=NUBIA CREEK TRIB,Reach-1,5
Up Type=0
Dn Type=3
Dn Slope=0.005
Boundary for River Rch & Prof#=NUBIA CREEK TRIB,Reach-1,6
Up Type=0
Dn Type=3
Dn Slope=0.005
Boundary for River Rch & Prof#=NUBIA CREEK TRIB,Reach-1,7
Up Type=0
Dn Type=3
Dn Slope=0.005

--- NUBIA CREEK TRIBUTARY 2_1.g01 (geometry) ---

Geom Title=Existing Conditions
Program Version=4.10

River Reach=NUBIA CREEK TRIB,Reach-1
Reach XY= 30
        1484805.        6812988.      1484662.81      6813184.59
      1484701.05       6813239.5      1484705.74      6813293.04
      1484662.32      6813388.12       1484748.3      6813478.69
      1484808.62      6813445.88      1484853.95      6813498.11
      1484853.78       6813727.5      1484805.07      6813808.03
      1484807.06      6814182.17      1484898.32       6814278.7
      1484955.28      6814245.47      1485001.87      6814289.17
      1485001.66      6814336.19      1484957.19      6814393.96
      1484956.09      6814477.46      1485063.18      6814694.06
      1485147.19      6814784.59      1485107.37      6814843.89
      1485108.68      6814936.42      1485191.34      6815074.74
      1485307.44      6815093.52      1485399.55      6815185.54
      1485404.49      6815322.78      1485356.21      6815398.51
      1485357.23      6815532.07      1485463.04      6815744.33
      1485550.04      6815793.34        1485555.        6815838.

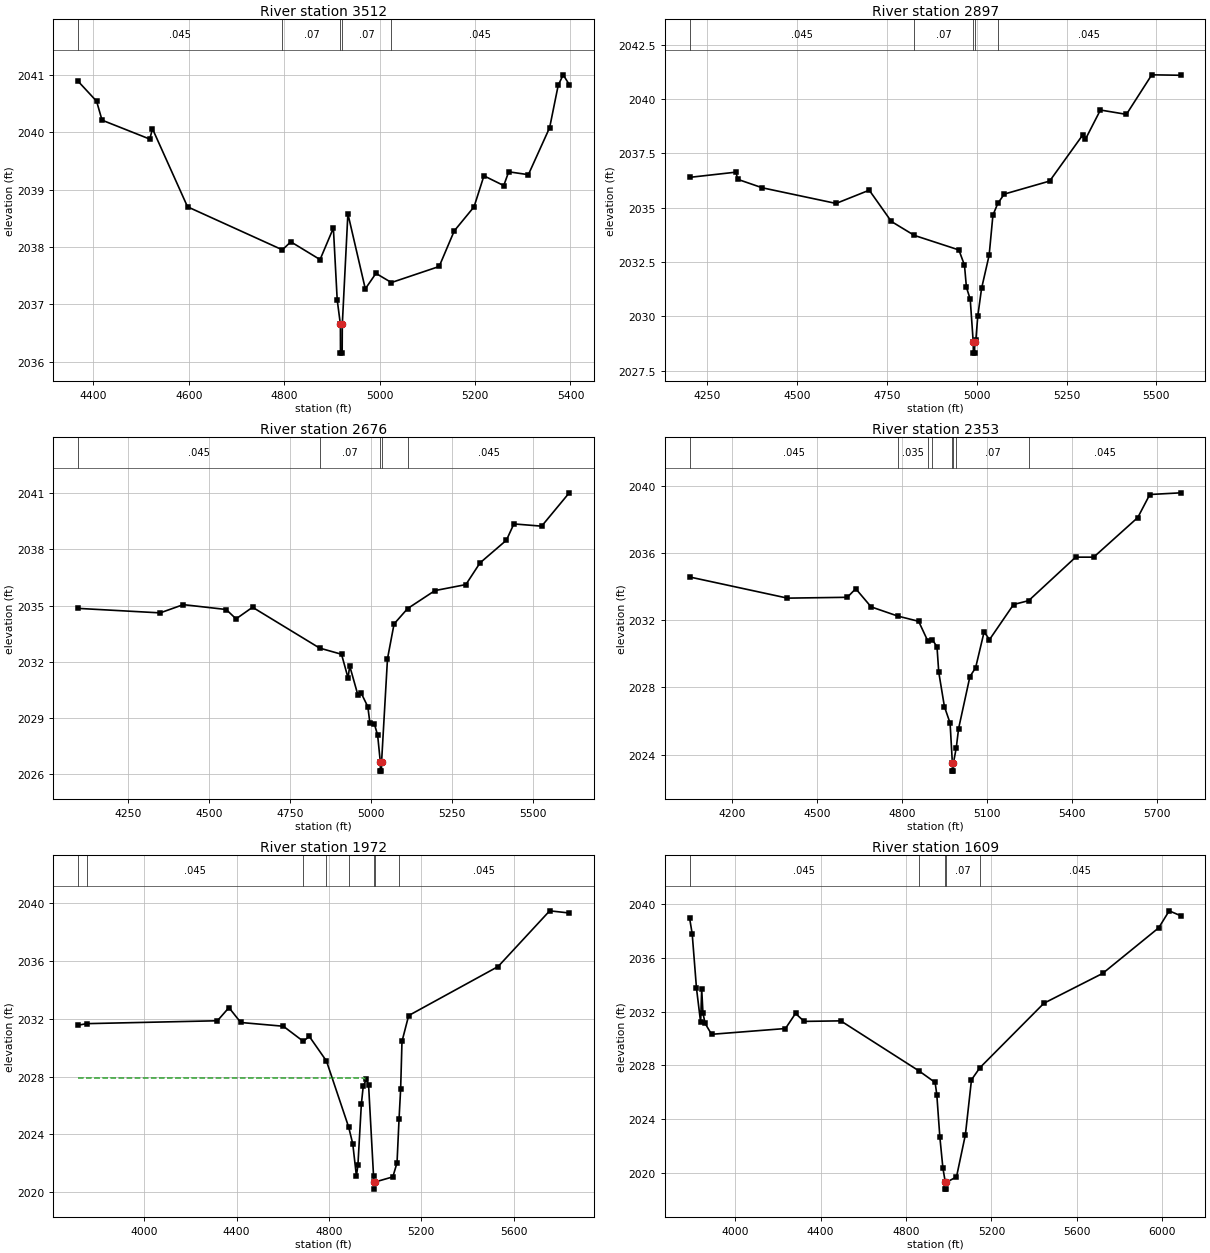
Type RM Length L Ch R = 1 ,3512    ,615,615,615
BEGIN DESCRIPTION:
NUBIA CREEK TRIBUTARY 2_1 3.0
END DESCRIPTION:
XS GIS Cut Line= 3
      1484180.01      6812813.01      1484744.25      6813097.71
      1485127.26      6812991.36
#Sta/Elev= 30
    4368 2040.89    4407 2040.54  4418.4 2040.21  4518.5 2039.88  4524.1 2040.06
  4597.6  2038.7  4796.3 2037.95    4814 2038.09  4875.3 2037.78  4903.2 2038.33
  4911.2 2037.08  4917.9 2036.65  4918.1 2036.15  4921.6 2036.15  4921.9 2036.65
  4933.6 2038.58  4970.1 2037.27  4992.4 2037.54  5024.8 2037.38  5124.9 2037.66
  5156.5 2038.28    5198  2038.7  5218.7 2039.24  5260.2 2039.07  5270.6 2039.31
  5311.8 2039.26  5356.4 2040.08  5374.4 2040.82  5384.8    2041  5397.5 2040.83
#Mann= 5 ,-1 , 0
    4368    .045       0  4796.3     .07       0  4917.9     .07       0
  4921.9     .07       0  5024.8    .045       0
Bank Sta=4917.9,4921.9
XS Rating Curve= 0 ,0
Exp/Cntr=0.3,0.1

Type RM Length L Ch R = 1 ,2897    ,221,221,221
BEGIN DESCRIPTION:
Mapping XS 57691d24
END DESCRIPTION:
XS GIS Cut Line= 4
      1484077.84      6813402.81       1484689.8      6813546.03
      1485106.47      6813408.01      1485291.36      6813171.04
#Sta/Elev= 30
  4200.1 2036.39  4329.1 2036.63  4334.2  2036.3  4402.6 2035.91    4608 2035.19
  4700.4  2035.8    4762 2034.36  4825.8 2033.72    4950 2033.05  4965.6 2032.35
    4971 2031.33  4981.6 2030.78    4990  2028.8  4990.3  2028.3  4993.8  2028.3
    4994  2028.8  4997.3 2028.91  5002.6    2030  5013.2 2031.28  5034.3 2032.81
  5044.8 2034.65  5058.3 2035.19  5076.4 2035.62  5202.8 2036.22  5294.4 2038.33
  5302.5 2038.15  5344.1 2039.49  5416.5 2039.29  5487.1 2041.11  5568.1 2041.09
#Mann= 5 ,-1 , 0
  4200.1    .045       0  4825.8     .07       0    4990     .07       0
    4994     .07       0  5058.3    .045       0
Bank Sta=4990,4994
XS Rating Curve= 0 ,0
Exp/Cntr=0.3,0.1

Type RM Length L Ch R = 1 ,2676    ,323,323,323
BEGIN DESCRIPTION:
Mapping XS cec8d719
END DESCRIPTION:
XS GIS Cut Line= 4
      1483965.79      6813590.29      1484723.65      6813733.53
      1485017.92      6813686.66      1485401.66      6813458.49
#Sta/Elev= 30
  4095.5 2034.85  4349.1 2034.61  4420.4 2035.05  4552.7 2034.79  4583.2 2034.29
  4634.1 2034.91    4841 2032.73  4908.6  2032.4  4928.8 2031.13  4933.8 2031.78
  4959.3 2030.21  4969.4 2030.32  4989.7  2029.6    4996 2028.75  5009.9 2028.68
    5020 2028.08  5028.2 2026.66  5028.4 2026.16  5031.9 2026.16  5032.2 2026.66
  5050.4 2032.16  5070.7 2034.02  5112.5 2034.84  5196.8  2035.8  5292.2 2036.12
  5335.9 2037.28  5417.3 2038.49  5440.3 2039.36    5526 2039.24  5611.2 2041.02
#Mann= 5 ,-1 , 0
  4095.5    .045       0    4841     .07       0  5028.2     .07       0
  5032.2     .07       0  5112.5    .045       0
Bank Sta=5028.2,5032.2
XS Rating Curve= 0 ,0
Exp/Cntr=0.3,0.1

Type RM Length L Ch R = 1 ,2353    ,381,381,381
BEGIN DESCRIPTION:
Mapping XS ac269901
END DESCRIPTION:
XS GIS Cut Line= 4
      1483916.38      6813697.08      1484728.86      6814017.39
      1484900.74      6814022.59      1485382.49      6813530.42
#Sta/Elev= 30
  4050.5 2034.58  4396.1 2033.32  4607.3 2033.37    4637 2033.88  4691.2  2032.8
  4785.8 2032.25    4859 2031.94    4891 2030.78  4907.8 2030.84  4923.8 2030.42
    4930 2028.91    4950 2026.86    4970 2025.88    4978 2023.52  4978.2 2023.02
  4981.7 2023.02    4982 2023.52  4991.9 2024.42    5000 2025.55    5040 2028.65
    5060 2029.17  5090.1 2031.31  5109.1 2030.85    5194 2032.94  5247.3 2033.17
  5413.2 2035.76  5476.9 2035.76  5632.5 2038.12  5674.9 2039.49  5784.5 2039.59
#Mann= 8 ,-1 , 0
  4050.5    .045       0  4785.8    .035       0    4891     .07       0
  4907.8    .035       0    4978     .07       0    4982    .035       0
  4991.9     .07       0  5247.3    .045       0
Bank Sta=4978,4982
XS Rating Curve= 0 ,0
Exp/Cntr=0.3,0.1

Type RM Length L Ch R = 1 ,1972    ,363,363,363
BEGIN DESCRIPTION:
Mapping XS 55bf83ae
END DESCRIPTION:
XS GIS Cut Line= 4
      1483736.83      6814121.25      1484787.89      6814357.66
      1485131.64      6814157.14      1485422.86       6813572.1
#Sta/Elev= 30
  3712.7 2031.56  3750.5 2031.67  4316.9 2031.87  4366.8 2032.78  4418.1 2031.75
  4602.6 2031.49  4688.6 2030.45  4715.3 2030.78  4789.4 2029.08  4885.4 2024.51
  4903.4 2023.34  4919.1 2021.12  4925.6 2021.84  4940.6 2026.09  4948.8 2027.34
  4962.1  2027.8  4971.9 2027.43  4993.5 2021.08  4997.3  2020.7  4997.5  2020.2
  5001.3  2020.7  5077.1 2021.05  5095.2 2022.03    5104 2025.08  5110.8 2027.12
  5116.7 2030.44  5145.6 2032.23  5533.3 2035.63  5756.7 2039.49  5841.5 2039.34
#Mann= 8 ,-1 , 0
  3712.7     .07       0  3750.5    .045       0  4688.6     .07       0
  4789.4    .035       0  4885.4     .07       0  4997.3     .07       0
  5001.3     .07       0    5104    .045       0
#XS Ineff= 2 , 0
       0  4956.3 2027.89               0
Permanent Ineff=
       F       F
Bank Sta=4997.3,5001.3
XS Rating Curve= 0 ,0
Exp/Cntr=0.3,0.1

Type RM Length L Ch R = 1 ,1609    ,159,159,159
BEGIN DESCRIPTION:
Mapping XS ce0af579
END DESCRIPTION:
XS GIS Cut Line= 4
      1483822.84      6814485.85      1484934.79      6814629.08
      1485101.46      6814488.45      1485436.32      6813586.84
#Sta/Elev= 30
  3786.2 2038.96  3798.5 2037.78  3818.6 2033.73    3838  2031.2    3843 2033.67
  3848.9 2031.89    3859 2031.12  3889.2 2030.31  4235.3 2030.74  4282.4 2031.86
  4322.8 2031.27  4494.2 2031.31  4860.6 2027.59  4936.3 2026.73  4944.1 2025.83
  4958.3  2022.7  4972.6 2020.38  4984.1  2019.3  4984.4  2018.8  4987.9  2018.8
  4988.1  2019.3  5036.4 2019.71    5078 2022.84  5106.6 2026.93  5146.2 2027.83
  5445.9 2032.62  5721.2 2034.84  5983.7 2038.23  6032.6 2039.49  6087.2 2039.12
#Mann= 5 ,-1 , 0
  3786.2    .045       0  4860.6     .07       0  4984.1     .07       0
  4988.1     .07       0  5146.2    .045       0
Bank Sta=4984.1,4988.1
XS Rating Curve= 0 ,0
Exp/Cntr=0.3,0.1

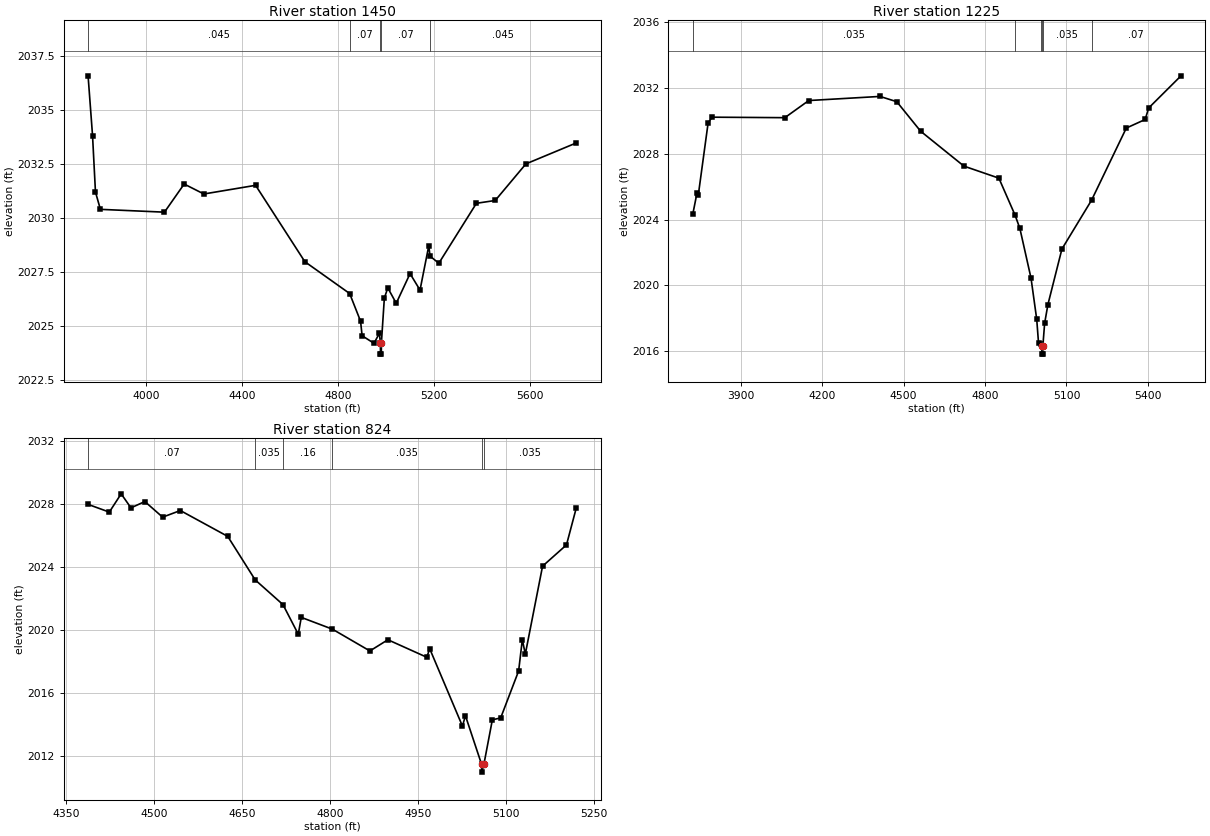
Type RM Length L Ch R = 1 ,1450    ,225,225,225
BEGIN DESCRIPTION:
NUBIA CREEK TRIBUTARY 2_1 2.0
END DESCRIPTION:
XS GIS Cut Line= 3
        1483905.        6814538.      1485001.43      6814797.77
      1485570.86      6814087.93
#Sta/Elev= 30
  3757.1 2036.57  3775.7 2033.81  3787.9  2031.2  3808.5  2030.4  4075.7 2030.27
  4157.9 2031.57  4240.1 2031.11  4455.9 2031.51  4661.5 2027.98  4848.3 2026.51
  4893.8 2025.23  4900.2 2024.56  4949.8 2024.21  4972.2 2024.67  4976.6 2024.21
  4976.9 2023.71  4980.4 2023.71  4980.6 2024.21    4993  2026.3  5007.4 2026.77
  5042.6 2026.06  5100.2 2027.43  5141.8 2026.67  5178.4 2028.72  5183.4 2028.24
  5220.3 2027.91  5377.1 2030.68  5455.5 2030.81  5583.5  2032.5  5793.9 2033.47
#Mann= 5 ,-1 , 0
  3757.1    .045       0  4848.3     .07       0  4976.6     .07       0
  4980.6     .07       0  5183.4    .045       0
Bank Sta=4976.6,4980.6
XS Rating Curve= 0 ,0
Exp/Cntr=0.3,0.1

Type RM Length L Ch R = 1 ,1225    ,401,401,401
BEGIN DESCRIPTION:
Mapping XS bf9882bb
END DESCRIPTION:
XS GIS Cut Line= 3
        1483866.      6814579.01      1485102.99      6814888.91
       1485610.4      6814761.41
#Sta/Elev= 30
  3723.5 2024.31  3738.9 2025.59  3744.1  2025.5  3780.1 2029.86  3794.6 2030.21
  4062.7 2030.18  4150.8 2031.22  4413.2 2031.47    4475 2031.15  4562.8 2029.36
  4722.4 2027.24  4851.1 2026.51  4910.3 2024.28  4928.4 2023.46  4969.5 2020.44
  4990.5 2017.94  4997.2 2016.49  5005.1 2016.42  5009.1 2016.33  5009.4 2015.83
  5012.9 2015.83  5013.1 2016.33  5019.6  2017.7  5031.7 2018.84  5083.3 2022.21
  5192.4 2025.17  5320.4 2029.55  5389.9 2030.07  5402.9 2030.77  5521.9 2032.72
#Mann= 6 ,-1 , 0
  3723.5    .035       0  4910.3     .07       0  5005.1    .035       0
  5009.1     .07       0  5013.1    .035       0  5192.4     .07       0
Bank Sta=5009.1,5013.1
XS Rating Curve= 0 ,0
Exp/Cntr=0.3,0.1

Type RM Length L Ch R = 1 ,824     ,0,0,0
BEGIN DESCRIPTION:
NUBIA CREEK TRIBUTARY 2_1 1.0
END DESCRIPTION:
XS GIS Cut Line= 3
      1484749.18      6815052.63      1485355.35      6815137.66
      1485571.48      6815180.81
#Sta/Elev= 30
  4387.9 2027.97  4424.1 2027.48  4444.3 2028.64    4461 2027.75  4484.7 2028.15
    4515 2027.16  4545.2 2027.58    4626 2025.94  4672.8 2023.18  4720.2 2021.61
  4746.3 2019.73  4751.4  2020.8  4804.6 2020.05  4868.4 2018.67  4899.1 2019.38
  4965.4 2018.27  4970.4 2018.81  5026.2  2013.9  5031.3 2014.56  5058.8 2011.48
  5059.1 2010.98  5062.8 2011.48  5077.2  2014.3  5091.4 2014.42    5122  2017.4
  5128.3 2019.38  5133.4 2018.47  5162.8 2024.05  5203.6  2025.4  5220.4 2027.76
#Mann= 6 ,-1 , 0
  4387.9     .07       0  4672.8    .035       0  4720.2     .16       0
  4804.6    .035       0  5058.8    .035       0  5062.8    .035       0
Bank Sta=5058.8,5062.8
XS Rating Curve= 0 ,0
Exp/Cntr=0.3,0.1

Chan Stop Cuts=-1
Use User Specified Reach Order=0
Composite Channel Slope=5