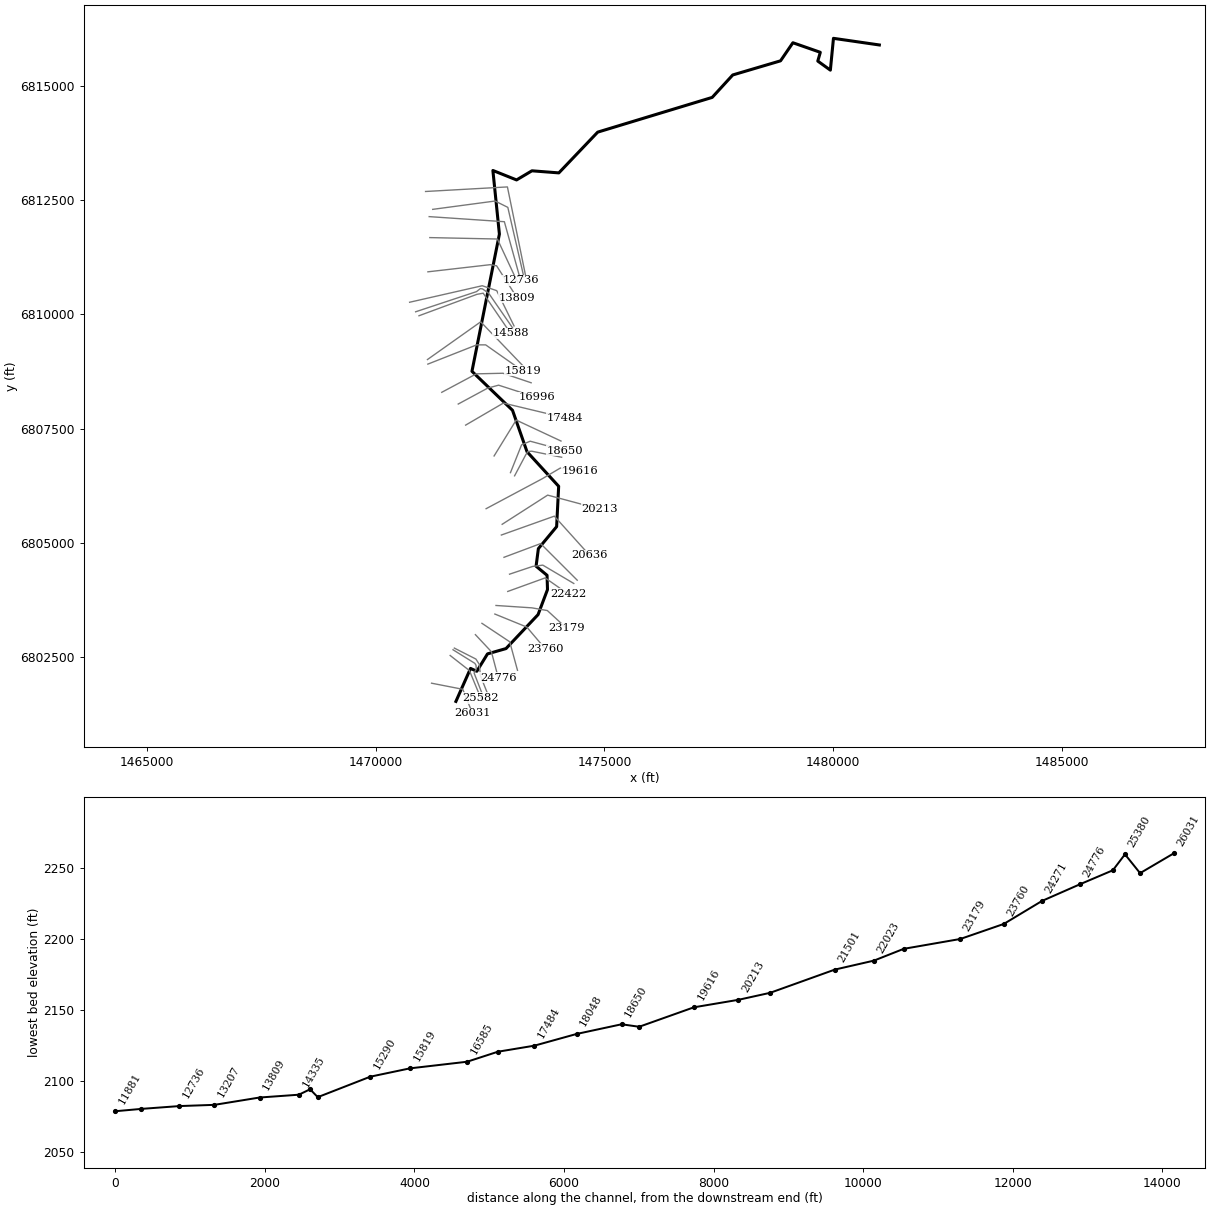
--- NUBIA CREEK TRIBUTARY 3.prj (project) ---

Proj Title=NUBIA CREEK TRIBUTARY 3 Base Level Engineering
Current Plan=p01
Default Exp/Contr=0.3,0.1
English Units
Geom File=g01
Flow File=f01
Plan File=p01
BEGIN DESCRIPTION:
NUBIA CREEK TRIBUTARY 3
END DESCRIPTION:

--- NUBIA CREEK TRIBUTARY 3.p01 (plan) ---

Plan Title=Multiple Run
Short Identifier=Multiple
Geom File=g01
Flow File=f01
Subcritical Flow
K Sum by GR= 0
Std Step Tol= 0.01
Critical Tol= 0.01
Num of Std Step Trials= 20
Max Error Tol= 0.3
Flow Tol Ratio= 0.001
Split Flow NTrial= 30
Split Flow Tol= 0.02
Split Flow Ratio= 0.02
Log Output Level= 0
Friction Slope Method= 1
Unsteady Friction Slope Method= 2
Unsteady Bridges Friction Slope Method= 1
Parabolic Critical Depth
Global Vel Dist=  1 , 1 , 1
Global Log Level= 0
CheckData=True
Encroach Param= -1, 0, 0, 0
BEGIN DESCRIPTION:
Multiple Run
END DESCRIPTION:

--- NUBIA CREEK TRIBUTARY 3.f01 (steady flow) ---

Flow Title=Multiple
Number of Profiles=7
Profile Names=10-year,25-year,50-year,1pct_min,100-year,1pct_plu,500-year
River Rch & RM= NUBIA CREEK TRIB,Reach-1,26031
     419     615     786     501    1000    1995    1635
River Rch & RM= NUBIA CREEK TRIB,Reach-1,22422
     661     990    1284     828    1651    3295    2766
River Rch & RM= NUBIA CREEK TRIB,Reach-1,15819
     764    1147    1489     960    1915    3821    3210
River Rch & RM= NUBIA CREEK TRIB,Reach-1,7065
     888    1342    1750    1133    2260    4510    3820
River Rch & RM= NUBIA CREEK TRIB,Reach-1,5017
    1009    1534    2007    1303    2600    5188    4420
River Rch & RM= NUBIA CREEK TRIB,Reach-1,3146
    1078    1641    2149    1396    2785    5556    4739
Boundary for River Rch & Prof#=NUBIA CREEK TRIB,Reach-1,1
Up Type=0
Dn Type=3
Dn Slope=0.005
Boundary for River Rch & Prof#=NUBIA CREEK TRIB,Reach-1,2
Up Type=0
Dn Type=3
Dn Slope=0.005
Boundary for River Rch & Prof#=NUBIA CREEK TRIB,Reach-1,3
Up Type=0
Dn Type=3
Dn Slope=0.005
Boundary for River Rch & Prof#=NUBIA CREEK TRIB,Reach-1,4
Up Type=0
Dn Type=3
Dn Slope=0.005
Boundary for River Rch & Prof#=NUBIA CREEK TRIB,Reach-1,5
Up Type=0
Dn Type=3
Dn Slope=0.005
Boundary for River Rch & Prof#=NUBIA CREEK TRIB,Reach-1,6
Up Type=0
Dn Type=3
Dn Slope=0.005
Boundary for River Rch & Prof#=NUBIA CREEK TRIB,Reach-1,7
Up Type=0
Dn Type=3
Dn Slope=0.005

--- NUBIA CREEK TRIBUTARY 3.g01 (geometry) ---

Geom Title=Existing Conditions

River Reach=NUBIA CREEK TRIB,Reach-1
Reach XY= 30
      1471755.00      6801538.00      1472074.78      6802259.07
      1472211.95      6802196.85      1472445.32      6802577.22
      1472849.56      6802693.18      1473549.53      6803435.01
      1473755.81      6803982.97      1473745.87      6804294.74
      1473506.54      6804493.85      1473556.22      6804877.50
      1473955.11      6805358.08      1473999.55      6806240.45
      1473308.34      6806996.17      1472991.60      6807901.72
      1472105.64      6808753.84      1472704.97      6811753.42
      1472562.74      6813144.55      1473079.96      6812937.49
      1473415.48      6813137.06      1474003.50      6813091.61
      1474852.55      6813982.54      1477353.50      6814741.61
      1477802.45      6815232.27      1478846.65      6815541.19
      1479116.49      6815936.52      1479715.44      6815727.24
      1479660.06      6815535.70      1479934.94      6815337.31
      1480002.67      6816032.91      1481005.00      6815888.00

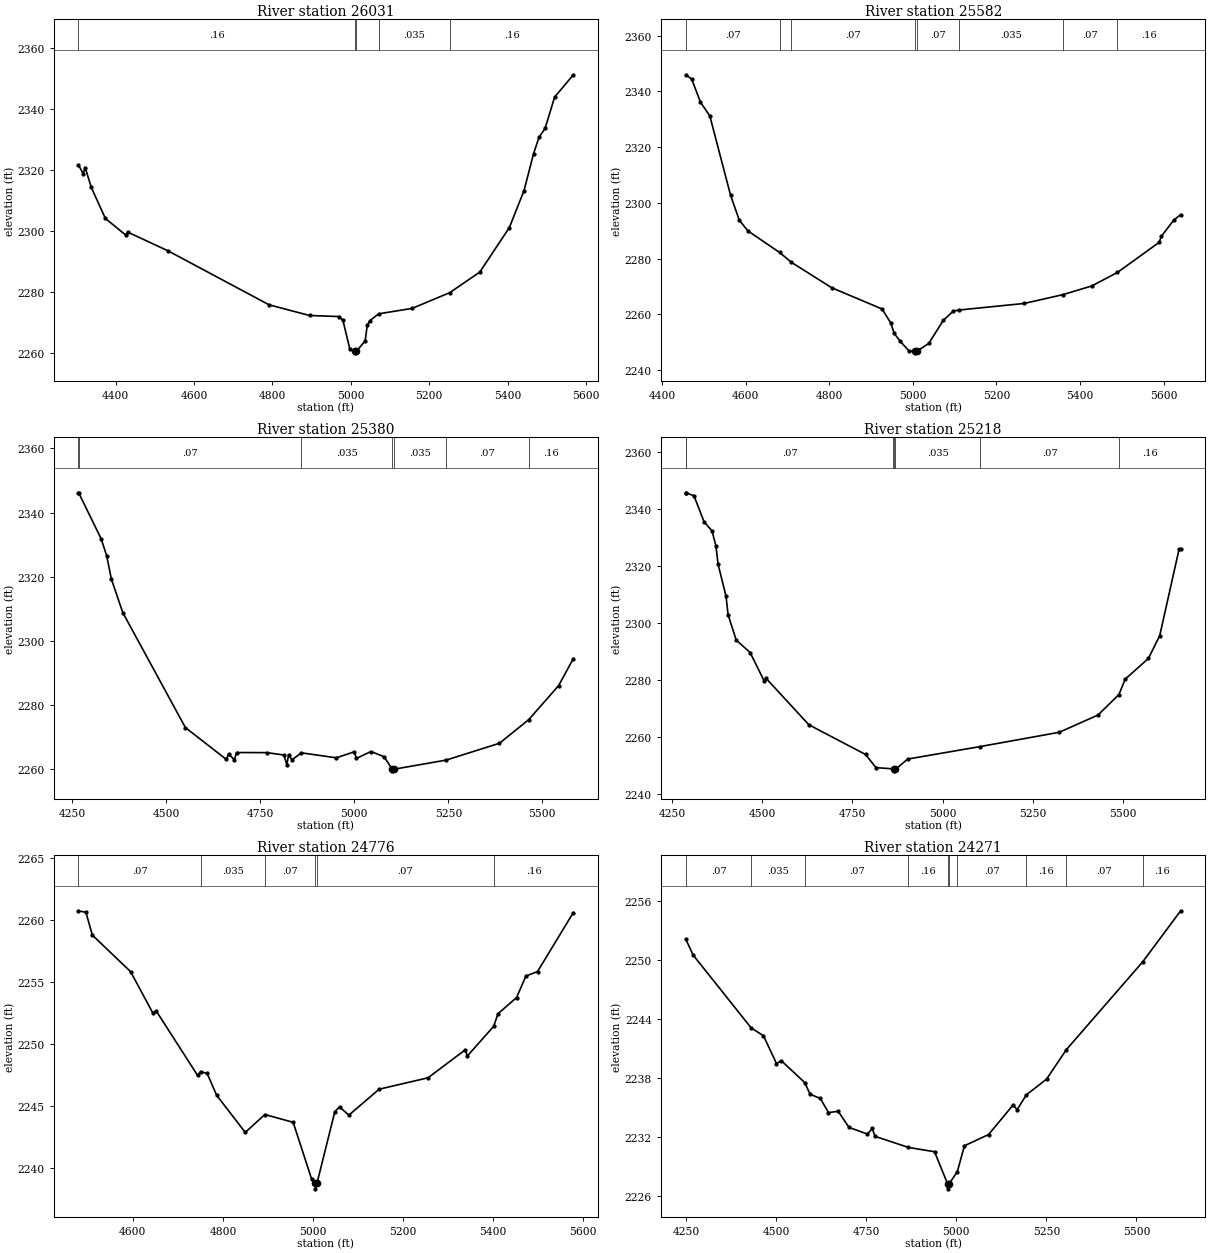
Type RM Length L Ch R = 1,26031,449,449,449
BEGIN DESCRIPTION:
NUBIA CREEK TRIBUTARY 3 46.0
END DESCRIPTION:
XS GIS Cut Line= 3
      1471222.94      6801936.26      1471904.85      6801803.06
      1472117.08      6801276.52
#Sta/Elev= 30
  4305.2 2321.72  4317.3 2318.90  4322.4 2320.90  4337.9 2314.39  4373.9 2304.19
  4425.5 2298.78  4430.6 2299.73  4533.7 2293.57  4791.5 2275.85  4894.6 2272.35
  4969.6 2272.00  4979.8 2270.80  4997.5 2261.29  5010.3 2260.59  5010.6 2260.09
  5014.3 2260.59  5036.5 2264.02  5041.9 2269.10  5048.6 2270.66  5071.1 2272.90
  5156.4 2274.68  5252.4 2279.85  5328.9 2286.58  5404.4 2301.20  5441.9 2313.37
  5466.1 2325.42  5479.9 2330.79  5495.6 2333.75  5519.8 2344.02  5567.7 2351.36
#Mann=5,-1,0
  4305.2    0.16       0  5010.3    0.07       0  5014.3    0.16       0
  5071.1   0.035       0  5252.4    0.16       0
Bank Sta=5010.3,5014.3
Exp/Cntr=0.3,0.1

Type RM Length L Ch R = 1,25582,202,202,202
BEGIN DESCRIPTION:
Mapping XS 4c15a031
END DESCRIPTION:
XS GIS Cut Line= 3
      1471629.26      6802542.13      1472051.10      6802211.42
      1472297.86      6801611.41
#Sta/Elev= 30
  4456.2 2345.95  4470.4 2344.39  4491.2 2336.16  4513.8 2331.16  4563.5 2302.70
  4584.3 2293.80  4605.1 2289.94  4680.9 2282.21  4708.8 2278.71  4805.8 2269.55
  4926.1 2261.95  4946.9 2256.95  4955.0 2253.25  4969.4 2250.40  4990.2 2246.95
  5004.7 2246.72  5005.0 2246.22  5008.7 2246.72  5037.8 2249.58  5072.6 2257.84
  5096.6 2261.18  5111.2 2261.59  5266.2 2263.93  5358.6 2267.07  5428.4 2270.22
  5489.7 2275.06  5589.6 2285.86  5595.0 2288.06  5624.4 2293.81  5641.0 2295.80
#Mann=8,-1,0
  4456.2    0.07       0  4680.9    0.16       0  4708.8    0.07       0
  5004.7    0.07       0  5008.7    0.07       0  5111.2   0.035       0
  5358.6    0.07       0  5489.7    0.16       0
Bank Sta=5004.7,5008.7
Exp/Cntr=0.3,0.1

Type RM Length L Ch R = 1,25380,162,162,162
BEGIN DESCRIPTION:
Mapping XS b676912f
END DESCRIPTION:
XS GIS Cut Line= 6
      1471691.71      6802667.17      1472168.29      6802370.28
      1472194.33      6802328.61      1472199.54      6802247.88
      1472152.66      6802156.74      1472342.12      6801671.41
#Sta/Elev= 30
  4266.5 2346.16  4267.0 2346.16  4326.8 2331.82  4341.7 2326.45  4353.9 2319.28
  4384.3 2308.80  4550.8 2272.95  4659.9 2262.99  4665.8 2264.73  4681.0 2262.89
  4686.9 2265.16  4767.3 2265.13  4813.0 2264.38  4820.6 2261.36  4825.4 2264.49
  4834.1 2262.87  4859.3 2265.06  4952.3 2263.51  5000.0 2265.40  5005.6 2263.32
  5044.3 2265.48  5079.0 2263.86  5101.1 2259.95  5101.3 2259.45  5105.1 2259.95
  5244.1 2262.80  5385.9 2268.05  5463.5 2275.38  5543.2 2286.00  5582.5 2294.47
#Mann=7,-1,0
  4266.5    0.16       0  4267.0    0.07       0  4859.3   0.035       0
  5101.1   0.035       0  5105.1   0.035       0  5244.1    0.07       0
  5463.5    0.16       0
Bank Sta=5101.1,5105.1
Exp/Cntr=0.3,0.1

Type RM Length L Ch R = 1,25218,442,442,442
BEGIN DESCRIPTION:
Mapping XS 023a44c8
END DESCRIPTION:
XS GIS Cut Line= 6
      1471720.39      6802703.61      1472191.73      6802464.03
      1472264.64      6802349.45      1472277.66      6802229.65
      1472288.08      6802104.65      1472459.97      6801674.94
#Sta/Elev= 30
  4287.6 2345.75  4287.7 2345.75  4310.3 2344.71  4338.2 2335.61  4360.4 2332.38
  4371.3 2327.09  4377.1 2320.77  4399.3 2309.41  4405.0 2302.97  4427.4 2294.14
  4466.1 2289.72  4505.0 2279.80  4510.6 2280.64  4629.3 2264.38  4786.4 2253.98
  4815.4 2249.37  4863.1 2248.93  4865.0 2248.74  4865.2 2248.24  4869.0 2248.74
  4903.4 2252.37  5104.0 2256.74  5323.7 2261.75  5431.4 2267.80  5489.6 2275.00
  5506.8 2280.38  5571.4 2287.65  5602.7 2295.63  5656.5 2325.98  5660.9 2325.98
#Mann=7,-1,0
  4287.6    0.16       0  4287.7    0.07       0  4863.1   0.035       0
  4865.0   0.035       0  4869.0   0.035       0  5104.0    0.07       0
  5489.6    0.16       0
Bank Sta=4865,4869
Exp/Cntr=0.3,0.1

Type RM Length L Ch R = 1,24776,505,505,505
BEGIN DESCRIPTION:
Mapping XS e41f5c7e
END DESCRIPTION:
XS GIS Cut Line= 3
      1472180.77      6802997.39      1472529.75      6802624.97
      1472680.39      6802056.15
#Sta/Elev= 30
  4479.3 2260.77  4495.9 2260.64  4510.1 2258.81  4595.1 2255.86  4644.4 2252.53
  4651.7 2252.71  4743.6 2247.51  4750.3 2247.81  4765.0 2247.66  4786.1 2245.90
  4849.6 2242.91  4893.2 2244.35  4956.0 2243.72  4996.9 2239.15  5005.2 2238.86
  5005.5 2238.36  5009.2 2238.86  5048.6 2244.59  5059.0 2244.96  5079.6 2244.30
  5146.9 2246.39  5255.5 2247.31  5337.6 2249.55  5342.8 2249.07  5401.2 2251.46
  5410.7 2252.47  5452.1 2253.78  5472.7 2255.51  5498.5 2255.87  5578.1 2260.63
#Mann=6,-1,0
  4479.3    0.07       0  4750.3   0.035       0  4893.2    0.07       0
  5005.2    0.07       0  5009.2    0.07       0  5401.2    0.16       0
Bank Sta=5005.2,5009.2
Exp/Cntr=0.3,0.1

Type RM Length L Ch R = 1,24271,511,511,511
BEGIN DESCRIPTION:
Mapping XS a21e6104
END DESCRIPTION:
XS GIS Cut Line= 3
      1472324.00      6803244.77      1472930.79      6802841.11
      1473100.04      6802218.81
#Sta/Elev= 30
  4249.0 2252.14  4269.2 2250.53  4430.6 2243.09  4464.6 2242.30  4500.7 2239.47
  4514.4 2239.75  4579.4 2237.52  4593.9 2236.34  4622.5 2235.91  4645.0 2234.47
  4672.0 2234.60  4702.1 2232.96  4753.2 2232.28  4766.7 2232.85  4774.2 2232.05
  4866.9 2230.92  4939.5 2230.48  4975.8 2227.20  4976.0 2226.70  4979.8 2227.20
  5002.7 2228.45  5022.5 2231.09  5089.5 2232.23  5157.2 2235.23  5169.0 2234.78
  5194.2 2236.27  5250.5 2237.88  5304.9 2240.86  5517.1 2249.82  5622.7 2255.03
#Mann=10,-1,0
  4249.0    0.07       0  4430.6   0.035       0  4579.4    0.07       0
  4866.9    0.16       0  4975.8    0.07       0  4979.8    0.16       0
  5002.7    0.07       0  5194.2    0.16       0  5304.9    0.07       0
  5517.1    0.16       0
Bank Sta=4975.8,4979.8
Exp/Cntr=0.3,0.1

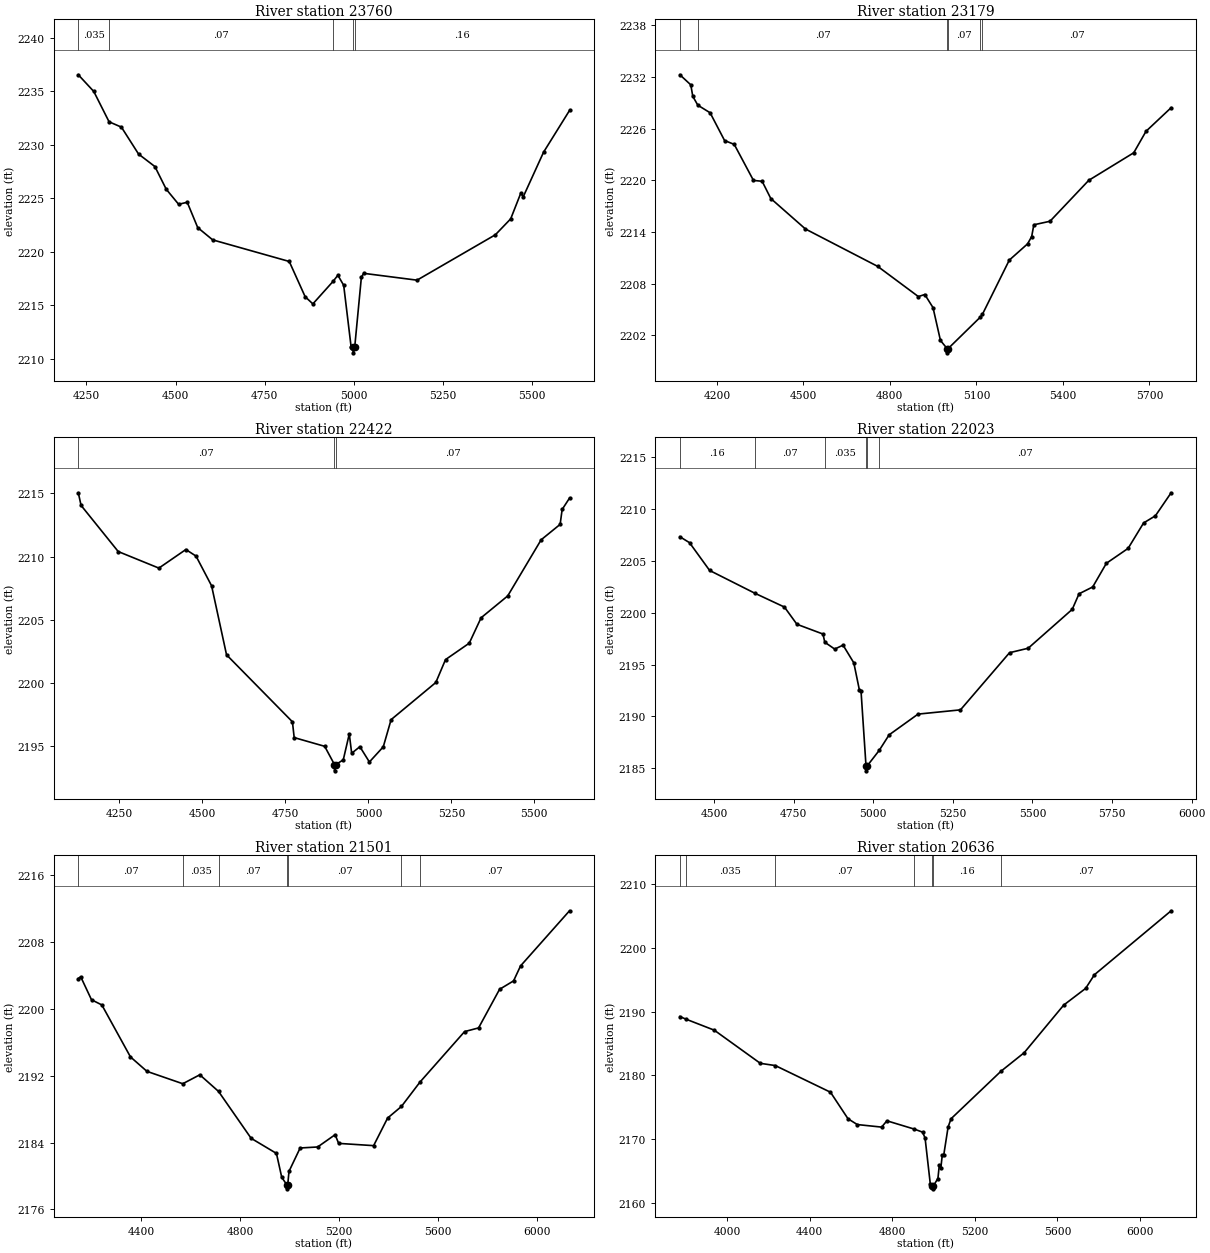
Type RM Length L Ch R = 1,23760,581,581,581
BEGIN DESCRIPTION:
Mapping XS c3685c34
END DESCRIPTION:
XS GIS Cut Line= 3
      1472606.14      6803447.88      1473304.05      6803163.16
      1473706.85      6802687.44
#Sta/Elev= 30
  4227.4 2236.56  4270.8 2235.00  4313.7 2232.16  4348.3 2231.66  4396.4 2229.14
  4442.2 2227.97  4473.9 2225.85  4508.7 2224.44  4532.8 2224.63  4562.2 2222.26
  4604.2 2221.11  4818.8 2219.09  4863.4 2215.79  4885.0 2215.12  4941.7 2217.23
  4955.1 2217.80  4971.4 2216.86  4992.4 2211.05  4998.2 2211.04  4998.4 2210.54
  5002.2 2211.04  5021.0 2217.62  5027.5 2217.98  5177.0 2217.34  5396.7 2221.59
  5439.6 2223.08  5468.1 2225.50  5474.7 2225.14  5531.8 2229.32  5604.5 2233.22
#Mann=5,-1,0
  4227.4   0.035       0  4313.7    0.07       0  4941.7    0.16       0
  4998.2    0.07       0  5002.2    0.16       0
Bank Sta=4998.2,5002.2
Exp/Cntr=0.3,0.1

Type RM Length L Ch R = 1,23179,757,757,757
BEGIN DESCRIPTION:
Mapping XS 7dc517e2
END DESCRIPTION:
XS GIS Cut Line= 4
      1472630.44      6803635.38      1473415.16      6803583.30
      1473751.97      6803524.27      1474175.56      6803135.41
#Sta/Elev= 30
  4071.9 2232.25  4109.7 2231.08  4116.6 2229.75  4134.1 2228.72  4176.7 2227.84
  4226.8 2224.62  4260.4 2224.17  4327.0 2219.99  4357.1 2219.89  4387.1 2217.89
  4507.4 2214.35  4758.0 2210.01  4898.8 2206.51  4921.1 2206.75  4949.6 2205.23
  4975.4 2201.42  4998.3 2200.48  4998.6 2199.98  5002.3 2200.48  5113.2 2204.11
  5120.8 2204.44  5214.1 2210.74  5277.6 2212.63  5291.8 2213.48  5299.2 2214.84
  5355.3 2215.25  5489.7 2220.00  5645.7 2223.20  5688.2 2225.69  5775.3 2228.43
#Mann=6,-1,0
  4071.9   0.035       0  4134.1    0.07       0  4998.3    0.07       0
  5002.3    0.07       0  5113.2    0.16       0  5120.8    0.07       0
Bank Sta=4998.3,5002.3
Exp/Cntr=0.3,0.1

Type RM Length L Ch R = 1,22422,399,399,399
BEGIN DESCRIPTION:
NUBIA CREEK TRIBUTARY 3 38.0
END DESCRIPTION:
XS GIS Cut Line= 3
      1472887.43      6803941.82      1473705.00      6804238.00
      1474205.01      6803887.99
#Sta/Elev= 30
  4126.0 2215.05  4134.4 2214.05  4246.3 2210.40  4368.8 2209.09  4450.1 2210.56
  4480.7 2210.04  4527.6 2207.69  4572.6 2202.23  4771.1 2196.93  4776.4 2195.68
  4868.3 2194.99  4897.7 2193.55  4898.0 2193.05  4901.9 2193.55  4924.3 2193.92
  4942.4 2195.97  4949.6 2194.44  4974.3 2194.96  5003.0 2193.75  5044.8 2194.95
  5068.4 2197.10  5203.1 2200.04  5232.3 2201.85  5303.8 2203.15  5339.5 2205.16
  5419.7 2206.89  5520.4 2211.33  5577.6 2212.55  5583.7 2213.73  5605.9 2214.63
#Mann=3,-1,0
  4126.0    0.07       0  4897.7    0.07       0  4901.9    0.07       0
Bank Sta=4897.7,4901.9
Exp/Cntr=0.3,0.1

Type RM Length L Ch R = 1,22023,522,522,522
BEGIN DESCRIPTION:
Mapping XS 2fb6fe06
END DESCRIPTION:
XS GIS Cut Line= 4
      1472926.40      6804319.40      1473431.66      6804488.68
      1473653.01      6804517.33      1474330.01      6804116.34
#Sta/Elev= 30
  4392.6 2207.33  4422.8 2206.76  4486.0 2204.08  4627.7 2201.89  4721.0 2200.55
  4760.2 2198.89  4842.0 2197.95  4847.7 2197.16  4878.8 2196.50  4905.1 2196.88
  4938.9 2195.17  4956.6 2192.52  4961.6 2192.42  4977.1 2185.26  4977.4 2184.76
  4981.4 2185.26  5018.6 2186.73  5049.8 2188.23  5140.6 2190.23  5273.9 2190.64
  5428.0 2196.15  5486.5 2196.58  5624.9 2200.33  5646.3 2201.83  5689.2 2202.49
  5732.1 2204.77  5800.4 2206.21  5849.0 2208.66  5886.1 2209.35  5935.5 2211.57
#Mann=6,-1,0
  4392.6    0.16       0  4627.7    0.07       0  4847.7   0.035       0
  4977.1   0.035       0  4981.4   0.035       0  5018.6    0.07       0
Bank Sta=4977.1,4981.4
Exp/Cntr=0.3,0.1

Type RM Length L Ch R = 1,21501,865,865,865
BEGIN DESCRIPTION:
NUBIA CREEK TRIBUTARY 3 36.0
END DESCRIPTION:
XS GIS Cut Line= 3
      1472805.04      6804688.01      1473605.00      6804988.00
      1474404.98      6804188.02
#Sta/Elev= 30
  4145.2 2203.64  4155.0 2203.85  4198.6 2201.10  4240.4 2200.48  4356.1 2194.26
  4422.8 2192.53  4567.5 2191.05  4636.4 2192.12  4712.1 2190.13  4843.8 2184.52
  4946.2 2182.71  4967.5 2179.86  4987.6 2178.97  4987.9 2178.47  4991.9 2178.97
  4996.9 2180.56  5042.0 2183.36  5112.7 2183.48  5183.4 2184.95  5197.6 2183.91
  5339.0 2183.64  5395.5 2186.94  5451.4 2188.33  5526.5 2191.25  5706.7 2197.29
  5763.2 2197.73  5848.1 2202.35  5904.7 2203.36  5932.9 2205.15  6130.9 2211.75
#Mann=7,-1,0
  4145.2    0.07       0  4567.5   0.035       0  4712.1    0.07       0
  4987.6    0.07       0  4991.9    0.07       0  5451.4    0.16       0
  5526.5    0.07       0
Bank Sta=4987.6,4991.9
Exp/Cntr=0.3,0.1

Type RM Length L Ch R = 1,20636,423,423,423
BEGIN DESCRIPTION:
NUBIA CREEK TRIBUTARY 3 35.0
END DESCRIPTION:
XS GIS Cut Line= 3
      1472748.10      6805175.33      1473905.00      6805588.00
      1474674.94      6804732.84
#Sta/Elev= 30
  3771.8 2189.22  3799.0 2188.84  3938.3 2187.08  4161.3 2181.87  4233.8 2181.52
  4501.1 2177.33  4586.0 2173.16  4630.9 2172.25  4748.8 2171.85  4774.3 2172.84
  4905.5 2171.55  4947.0 2171.06  4959.2 2170.14  4984.7 2162.85  4995.1 2162.65
  4995.5 2162.15  4999.7 2162.65  5021.4 2163.77  5028.1 2165.87  5035.6 2165.47
  5042.3 2167.39  5049.8 2167.50  5070.7 2171.86  5084.9 2173.16  5326.5 2180.62
  5439.2 2183.54  5630.5 2191.02  5736.7 2193.64  5779.3 2195.79  6150.8 2205.84
#Mann=7,-1,0
  3771.8    0.16       0  3799.0   0.035       0  4233.8    0.07       0
  4905.5    0.16       0  4995.1    0.07       0  4999.7    0.16       0
  5326.5    0.07       0
Bank Sta=4995.1,4999.7
Exp/Cntr=0.3,0.1

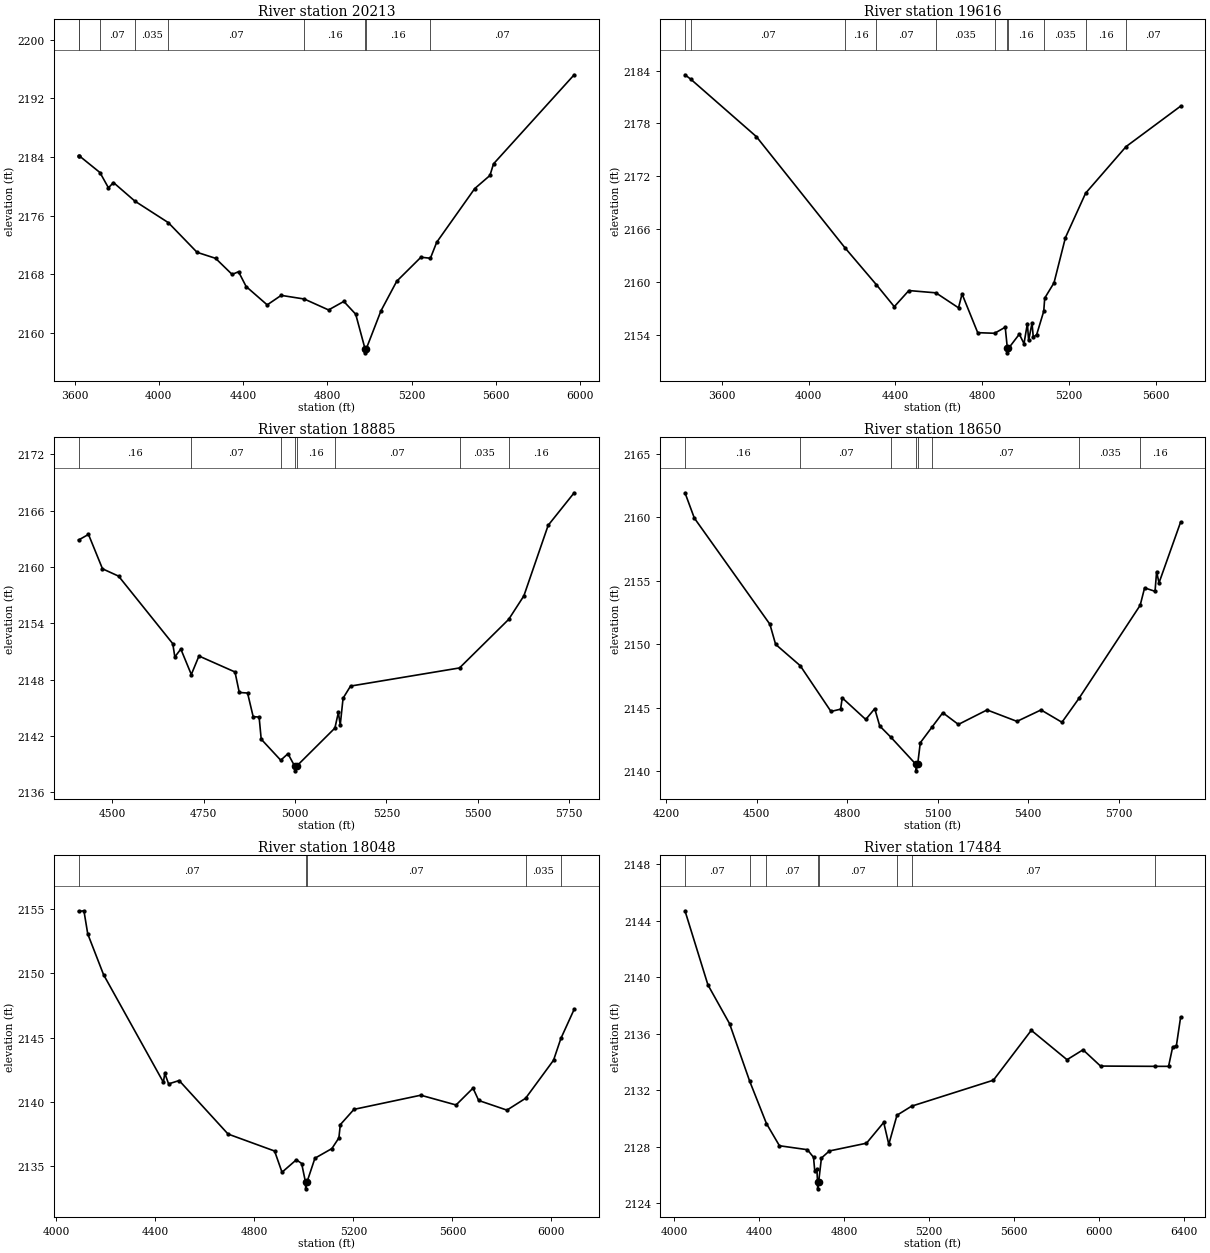
Type RM Length L Ch R = 1,20213,597,597,597
BEGIN DESCRIPTION:
Mapping XS 07dbef2e
END DESCRIPTION:
XS GIS Cut Line= 3
      1472765.39      6805409.67      1473759.35      6806047.71
      1474891.13      6805744.17
#Sta/Elev= 30
  3618.7 2184.19  3620.9 2184.19  3720.4 2181.88  3760.8 2179.79  3784.6 2180.51
  3886.5 2177.97  4045.2 2175.03  4181.5 2170.98  4269.3 2170.16  4347.9 2167.96
  4378.3 2168.33  4414.4 2166.31  4514.4 2163.80  4580.8 2165.10  4690.5 2164.60
  4805.7 2163.11  4878.1 2164.27  4934.5 2162.53  4979.3 2157.75  4979.6 2157.25
  4984.0 2157.75  5054.5 2162.99  5129.3 2167.03  5244.2 2170.31  5289.2 2170.17
  5319.0 2172.35  5499.4 2179.68  5571.8 2181.48  5588.7 2183.06  5971.6 2195.23
#Mann=9,-1,0
  3618.7    0.16       0  3620.9   0.035       0  3720.4    0.07       0
  3886.5   0.035       0  4045.2    0.07       0  4690.5    0.16       0
  4979.3    0.07       0  4984.0    0.16       0  5289.2    0.07       0
Bank Sta=4979.3,4984
Exp/Cntr=0.3,0.1

Type RM Length L Ch R = 1,19616,731,731,731
BEGIN DESCRIPTION:
Mapping XS 92a665fe
END DESCRIPTION:
XS GIS Cut Line= 4
      1472414.70      6805750.82      1473643.90      6806407.08
      1474036.26      6806639.72      1474466.78      6806577.23
#Sta/Elev= 30
  3429.8 2183.52  3457.8 2182.99  3758.9 2176.50  4167.3 2163.88  4312.5 2159.68
  4394.6 2157.20  4461.7 2159.03  4586.4 2158.77  4690.6 2157.07  4706.9 2158.64
  4779.1 2154.25  4857.0 2154.18  4905.9 2154.87  4915.8 2152.46  4916.2 2151.96
  4920.7 2152.46  4970.9 2154.08  4992.4 2153.00  5008.0 2155.29  5013.8 2153.37
  5029.4 2155.34  5035.2 2153.74  5050.9 2154.03  5083.5 2156.69  5087.9 2158.17
  5130.8 2159.91  5183.4 2165.04  5276.4 2170.08  5462.9 2175.37  5714.4 2179.96
#Mann=11,-1,0
  3429.8    0.16       0  3457.8    0.07       0  4167.3    0.16       0
  4312.5    0.07       0  4586.4   0.035       0  4857.0    0.16       0
  4915.8    0.07       0  4920.7    0.16       0  5083.5   0.035       0
  5276.4    0.16       0  5462.9    0.07       0
Bank Sta=4915.8,4920.7
Exp/Cntr=0.3,0.1

Type RM Length L Ch R = 1,18885,235,235,235
BEGIN DESCRIPTION:
Mapping XS 9fabf6de
END DESCRIPTION:
XS GIS Cut Line= 5
      1473036.93      6806469.43      1473279.98      6806927.76
      1473328.59      6807000.68      1473411.92      6807007.62
      1474064.68      6806875.68
#Sta/Elev= 30
  4407.8 2162.86  4435.1 2163.46  4473.4 2159.80  4517.4 2159.02  4665.7 2151.83
  4671.3 2150.42  4687.7 2151.26  4716.4 2148.55  4737.3 2150.52  4835.9 2148.82
  4847.6 2146.64  4870.3 2146.58  4885.6 2144.07  4901.9 2144.02  4907.6 2141.67
  4961.0 2139.43  4980.8 2140.12  4999.2 2138.80  4999.6 2138.30  5004.5 2138.80
  5109.2 2142.85  5118.7 2144.51  5123.8 2143.18  5131.6 2146.03  5152.0 2147.32
  5450.1 2149.25  5584.7 2154.42  5626.2 2156.92  5692.7 2164.43  5763.8 2167.89
#Mann=8,-1,0
  4407.8    0.16       0  4716.4    0.07       0  4961.0    0.16       0
  4999.2    0.07       0  5004.5    0.16       0  5109.2    0.07       0
  5450.1   0.035       0  5584.7    0.16       0
Bank Sta=4999.2,5004.5
Exp/Cntr=0.3,0.1

Type RM Length L Ch R = 1,18650,602,602,602
BEGIN DESCRIPTION:
Mapping XS 3ec3edf6
END DESCRIPTION:
XS GIS Cut Line= 4
      1472946.64      6806538.85      1473189.70      6807146.51
      1473377.20      6807226.37      1474134.19      6807021.50
#Sta/Elev= 30
  4262.9 2161.92  4293.9 2159.93  4544.3 2151.58  4563.2 2150.00  4644.8 2148.32
  4746.7 2144.72  4778.6 2144.90  4784.0 2145.79  4862.0 2144.09  4891.7 2144.94
  4908.2 2143.58  4945.8 2142.68  5028.6 2140.55  5029.0 2140.05  5033.9 2140.55
  5042.7 2142.26  5080.8 2143.47  5117.3 2144.62  5168.9 2143.70  5263.9 2144.84
  5363.1 2143.94  5442.8 2144.84  5512.1 2143.87  5569.4 2145.78  5771.3 2153.07
  5786.0 2154.44  5820.6 2154.17  5825.8 2155.72  5833.7 2154.83  5905.4 2159.62
#Mann=8,-1,0
  4262.9    0.16       0  4644.8    0.07       0  4945.8    0.16       0
  5028.6    0.07       0  5033.9    0.16       0  5080.8    0.07       0
  5569.4   0.035       0  5771.3    0.16       0
Bank Sta=5028.6,5033.9
Exp/Cntr=0.3,0.1

Type RM Length L Ch R = 1,18048,564,564,564
BEGIN DESCRIPTION:
Mapping XS 428d537a
END DESCRIPTION:
XS GIS Cut Line= 3
      1472589.03      6806903.49      1473071.65      6807688.18
      1474050.40      6807230.04
#Sta/Elev= 30
  4089.8 2154.81  4111.7 2154.86  4127.1 2153.06  4191.0 2149.89  4432.5 2141.53
  4438.3 2142.22  4453.7 2141.40  4496.3 2141.66  4693.8 2137.50  4881.7 2136.18
  4911.7 2134.53  4969.7 2135.50  4991.0 2135.21  5006.8 2133.74  5007.2 2133.24
  5012.1 2133.74  5044.6 2135.62  5113.1 2136.37  5141.4 2137.20  5147.2 2138.23
  5202.4 2139.42  5472.2 2140.52  5614.7 2139.76  5683.2 2141.07  5706.1 2140.11
  5820.2 2139.36  5895.5 2140.28  6008.4 2143.24  6038.0 2144.93  6091.7 2147.20
#Mann=5,-1,0
  4089.8    0.07       0  5006.8    0.07       0  5012.1    0.07       0
  5895.5   0.035       0  6038.0    0.07       0
Bank Sta=5006.8,5012.1
Exp/Cntr=0.3,0.1

Type RM Length L Ch R = 1,17484,488,488,488
BEGIN DESCRIPTION:
Mapping XS 200b7eaa
END DESCRIPTION:
XS GIS Cut Line= 3
      1471967.52      6807577.96      1472792.13      6808059.71
      1474131.64      6807738.92
#Sta/Elev= 30
  4051.8 2144.70  4159.9 2139.45  4261.6 2136.71  4356.5 2132.63  4435.2 2129.64
  4496.3 2128.07  4628.0 2127.79  4656.7 2127.25  4662.7 2126.25  4672.4 2126.42
  4675.6 2125.52  4676.0 2125.02  4680.9 2125.52  4693.9 2127.20  4731.1 2127.70
  4905.9 2128.25  4987.0 2129.72  5010.9 2128.17  5049.4 2130.23  5118.1 2130.87
  5503.1 2132.71  5681.5 2136.24  5849.6 2134.16  5924.9 2134.86  6007.2 2133.71
  6261.6 2133.69  6327.4 2133.69  6346.5 2135.04  6364.3 2135.16  6384.2 2137.18
#Mann=8,-1,0
  4051.8    0.07       0  4356.5    0.16       0  4435.2    0.07       0
  4675.6    0.07       0  4680.9    0.07       0  5049.4    0.16       0
  5118.1    0.07       0  6261.6   0.035       0
Bank Sta=4675.6,4680.9
Exp/Cntr=0.3,0.1

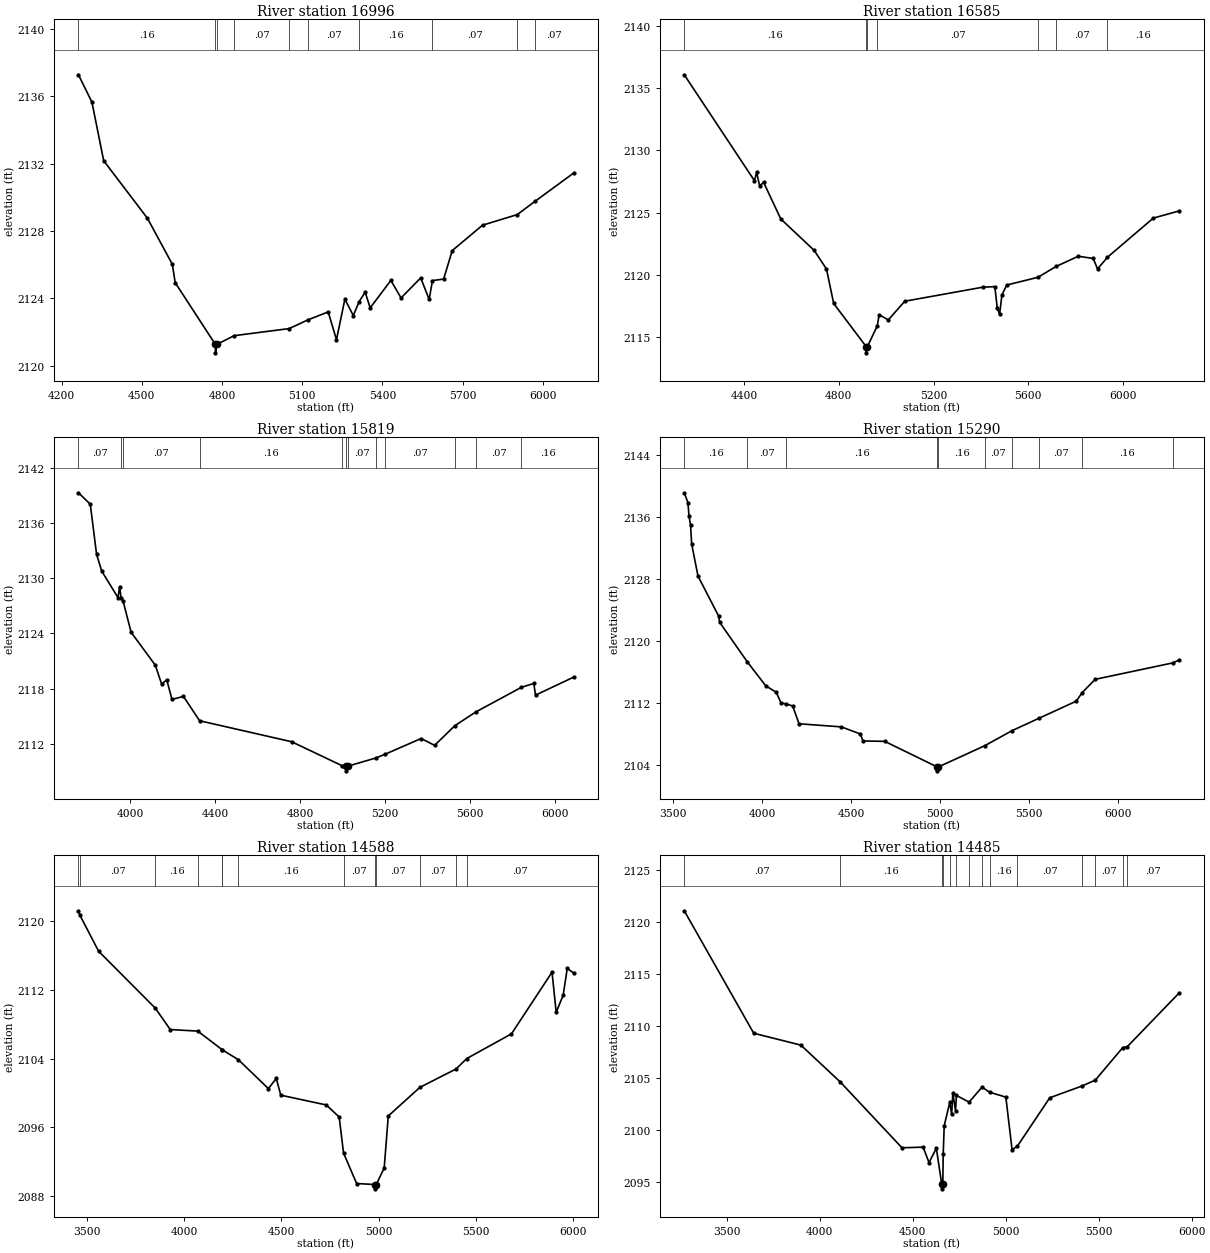
Type RM Length L Ch R = 1,16996,411,411,411
BEGIN DESCRIPTION:
Mapping XS 21672c41
END DESCRIPTION:
XS GIS Cut Line= 4
      1471806.00      6808038.86      1472448.38      6808386.10
      1472687.10      6808451.20      1473518.85      6808182.61
#Sta/Elev= 30
  4263.1 2137.28  4313.5 2135.65  4357.3 2132.18  4521.0 2128.76  4614.4 2126.02
  4624.7 2124.94  4775.2 2121.27  4775.6 2120.77  4780.5 2121.27  4845.4 2121.79
  5051.3 2122.21  5121.7 2122.73  5197.1 2123.20  5228.2 2121.55  5259.6 2123.96
  5291.1 2122.98  5312.5 2123.80  5335.5 2124.37  5354.2 2123.44  5431.6 2125.07
  5469.7 2124.03  5543.3 2125.22  5574.8 2123.94  5587.2 2125.06  5629.0 2125.15
  5661.1 2126.84  5774.5 2128.35  5904.6 2128.98  5971.2 2129.77  6114.8 2131.44
#Mann=10,-1,0
  4263.1    0.16       0  4775.2    0.07       0  4780.5    0.16       0
  4845.4    0.07       0  5051.3    0.16       0  5121.7    0.07       0
  5312.5    0.16       0  5587.2    0.07       0  5904.6    0.16       0
  5971.2    0.07       0
Bank Sta=4775.2,4780.5
Exp/Cntr=0.3,0.1

Type RM Length L Ch R = 1,16585,766,766,766
BEGIN DESCRIPTION:
Mapping XS 1a315d19
END DESCRIPTION:
XS GIS Cut Line= 4
      1471445.78      6808294.95      1472200.99      6808698.60
      1472782.58      6808711.62      1473398.87      6808503.29
#Sta/Elev= 30
  4148.3 2136.05  4444.5 2127.55  4453.6 2128.21  4466.5 2127.12  4482.8 2127.43
  4555.6 2124.48  4696.5 2121.96  4748.4 2120.46  4778.7 2117.70  4915.8 2114.24
  4916.2 2113.74  4921.1 2114.24  4962.7 2115.91  4970.5 2116.80  5009.1 2116.38
  5078.6 2117.88  5408.7 2119.01  5458.7 2119.05  5468.7 2117.36  5478.7 2116.84
  5488.7 2118.39  5508.8 2119.18  5640.4 2119.80  5717.0 2120.67  5810.6 2121.49
  5873.9 2121.31  5892.0 2120.47  5933.9 2121.41  6127.3 2124.55  6236.9 2125.13
#Mann=7,-1,0
  4148.3    0.16       0  4915.8    0.07       0  4921.1    0.16       0
  4962.7    0.07       0  5640.4    0.16       0  5717.0    0.07       0
  5933.9    0.16       0
Bank Sta=4915.8,4921.1
Exp/Cntr=0.3,0.1

Type RM Length L Ch R = 1,15819,529,529,529
BEGIN DESCRIPTION:
Mapping XS 446978b2
END DESCRIPTION:
XS GIS Cut Line= 4
      1471141.95      6808911.27      1472209.67      6809332.28
      1472404.98      6809332.28      1473211.16      6808764.48
#Sta/Elev= 30
  3757.0 2139.27  3812.5 2138.03  3842.2 2132.58  3866.6 2130.75  3943.0 2127.88
  3950.5 2129.06  3957.8 2127.80  3966.3 2127.56  4004.6 2124.12  4118.3 2120.55
  4148.0 2118.51  4172.4 2118.95  4196.8 2116.83  4250.9 2117.15  4326.9 2114.51
  4760.0 2112.23  4997.8 2109.62  5017.1 2109.57  5017.6 2109.07  5023.1 2109.57
  5156.7 2110.47  5197.3 2110.85  5369.1 2112.58  5432.6 2111.84  5527.6 2113.97
  5626.7 2115.47  5840.9 2118.14  5899.4 2118.56  5907.3 2117.29  6086.1 2119.24
#Mann=12,-1,0
  3757.0    0.07       0  3957.8    0.16       0  3966.3    0.07       0
  4326.9    0.16       0  4997.8    0.07       0  5017.1    0.07       0
  5023.1    0.07       0  5156.7    0.16       0  5197.3    0.07       0
  5527.6    0.16       0  5626.7    0.07       0  5840.9    0.16       0
Bank Sta=5017.1,5023.1
Exp/Cntr=0.3,0.1

Type RM Length L Ch R = 1,15290,702,702,702
BEGIN DESCRIPTION:
Mapping XS 5731c7f8
END DESCRIPTION:
XS GIS Cut Line= 3
      1471133.28      6809011.10      1472296.47      6809835.75
      1473233.98      6808859.18
#Sta/Elev= 30
  3563.9 2139.15  3584.4 2137.88  3590.6 2136.14  3599.2 2134.97  3605.3 2132.56
  3641.0 2128.39  3756.7 2123.23  3762.8 2122.41  3917.8 2117.31  4021.2 2114.22
  4080.3 2113.38  4107.3 2112.00  4136.6 2111.87  4172.6 2111.61  4208.3 2109.31
  4445.7 2108.91  4552.8 2107.99  4567.5 2107.09  4689.4 2107.04  4984.4 2103.73
  4984.9 2103.23  4990.4 2103.73  5250.7 2106.47  5405.3 2108.43  5557.5 2110.04
  5765.0 2112.23  5798.0 2113.33  5871.3 2115.05  6306.0 2117.17  6343.5 2117.56
#Mann=10,-1,0
  3563.9    0.16       0  3917.8    0.07       0  4136.6    0.16       0
  4984.4    0.07       0  4990.4    0.16       0  5250.7    0.07       0
  5405.3    0.16       0  5557.5    0.07       0  5798.0    0.16       0
  6306.0    0.07       0
Bank Sta=4984.4,4990.4
Exp/Cntr=0.3,0.1

Type RM Length L Ch R = 1,14588,103,103,103
BEGIN DESCRIPTION:
Mapping XS 938c1fc9
END DESCRIPTION:
XS GIS Cut Line= 4
      1470948.38      6809968.56      1472215.74      6810437.31
      1472351.16      6810461.62      1472948.36      6809586.65
#Sta/Elev= 30
  3455.4 2121.18  3462.6 2120.67  3559.2 2116.47  3851.1 2109.85  3927.8 2107.37
  4069.5 2107.19  4193.7 2105.05  4194.3 2105.03  4278.2 2103.87  4432.7 2100.51
  4473.6 2101.68  4496.7 2099.74  4731.2 2098.60  4797.4 2097.20  4819.7 2093.02
  4887.2 2089.47  4981.9 2089.35  4982.4 2088.85  4988.1 2089.35  5029.1 2091.27
  5050.1 2097.32  5212.9 2100.65  5398.6 2102.78  5454.1 2104.00  5684.2 2106.87
  5893.0 2114.04  5914.5 2109.38  5950.4 2111.36  5971.4 2114.48  6003.6 2113.95
#Mann=13,-1,0
  3455.4    0.16       0  3462.6    0.07       0  3851.1    0.16       0
  4069.5    0.07       0  4193.7    0.16       0  4194.3    0.07       0
  4278.2    0.16       0  4819.7    0.07       0  4981.9    0.07       0
  4988.1    0.07       0  5212.9    0.07       0  5398.6    0.16       0
  5454.1    0.07       0
Bank Sta=4981.9,4988.1
Exp/Cntr=0.3,0.1

Type RM Length L Ch R = 1,14485,150,150,150
BEGIN DESCRIPTION:
Mapping XS 8719c105
END DESCRIPTION:
XS GIS Cut Line= 6
      1470875.45      6810055.36      1472205.33      6810496.34
      1472288.66      6810562.31      1472337.27      6810555.37
      1472472.69      6810458.14      1473003.93      6809687.33
#Sta/Elev= 30
  3270.8 2121.06  3644.4 2109.31  3898.0 2108.17  4109.7 2104.64  4441.9 2098.32
  4555.6 2098.38  4587.3 2096.90  4626.8 2098.27  4655.4 2094.88  4655.9 2094.38
  4661.6 2094.88  4663.8 2097.76  4669.1 2100.43  4698.9 2102.67  4709.1 2101.53
  4715.5 2103.58  4729.9 2101.88  4735.0 2103.34  4802.9 2102.70  4872.6 2104.14
  4913.3 2103.65  5000.6 2103.18  5034.1 2098.14  5062.6 2098.47  5236.9 2103.12
  5409.4 2104.24  5481.7 2104.81  5629.5 2107.93  5654.4 2108.03  5933.6 2113.19
#Mann=14,-1,0
  3270.8    0.07       0  4109.7    0.16       0  4655.4    0.07       0
  4661.6    0.16       0  4698.9    0.07       0  4735.0    0.16       0
  4802.9   0.035       0  4872.6    0.07       0  4913.3    0.16       0
  5062.6    0.07       0  5409.4    0.16       0  5481.7    0.07       0
  5629.5    0.16       0  5654.4    0.07       0
Bank Sta=4655.4,4661.6
Exp/Cntr=0.3,0.1

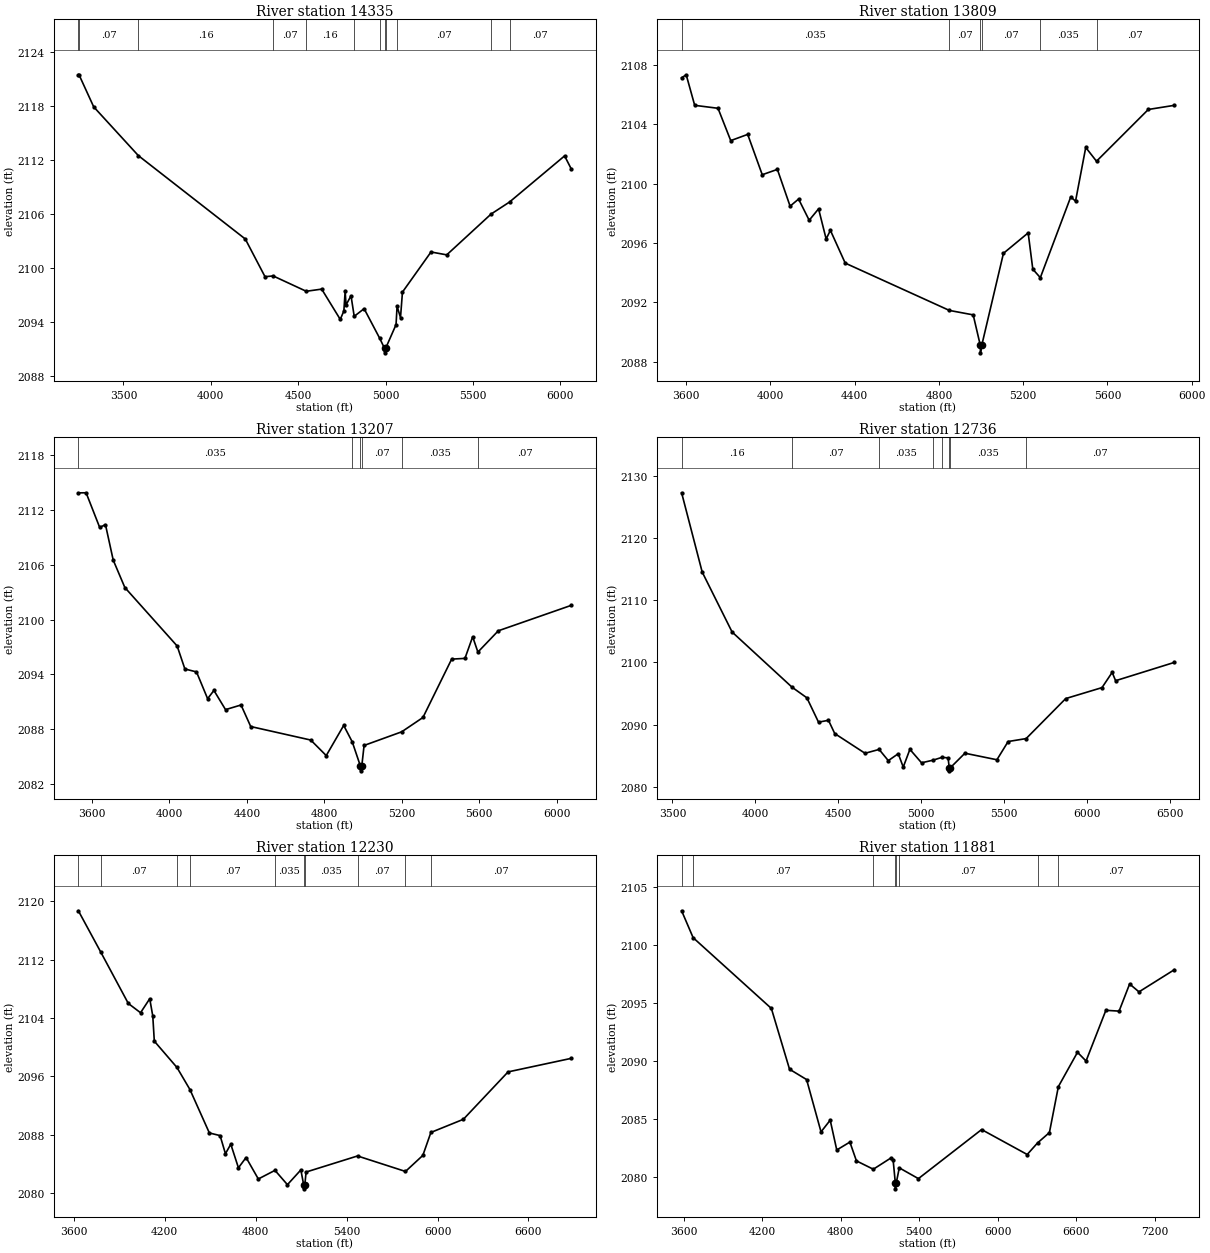
Type RM Length L Ch R = 1,14335,526,526,526
BEGIN DESCRIPTION:
Mapping XS e12bc69a
END DESCRIPTION:
XS GIS Cut Line= 4
      1470743.52      6810263.70      1472330.33      6810624.81
      1472646.30      6810517.17      1473024.77      6809746.35
#Sta/Elev= 30
  3241.7 2121.42  3247.1 2121.35  3329.5 2117.86  3585.1 2112.45  4197.0 2103.20
  4309.8 2099.02  4356.6 2099.10  4545.9 2097.40  4634.2 2097.64  4740.5 2094.28
  4761.1 2095.21  4768.5 2097.38  4773.6 2095.89  4802.1 2096.90  4820.4 2094.62
  4877.0 2095.47  4966.1 2092.19  4994.0 2091.07  4994.5 2090.57  5000.2 2091.07
  5059.8 2093.70  5065.7 2095.74  5085.3 2094.48  5096.5 2097.31  5259.9 2101.76
  5349.9 2101.44  5603.9 2105.97  5709.1 2107.30  6024.4 2112.42  6061.6 2111.01
#Mann=12,-1,0
  3241.7    0.16       0  3247.1    0.07       0  3585.1    0.16       0
  4356.6    0.07       0  4545.9    0.16       0  4820.4   0.035       0
  4966.1    0.16       0  4994.0    0.07       0  5000.2    0.16       0
  5065.7    0.07       0  5603.9    0.16       0  5709.1    0.07       0
Bank Sta=4994,5000.2
Exp/Cntr=0.3,0.1

Type RM Length L Ch R = 1,13809,602,602,602
BEGIN DESCRIPTION:
Mapping XS 2188338a
END DESCRIPTION:
XS GIS Cut Line= 4
      1471143.34      6810928.92      1472504.46      6811085.17
      1472643.35      6811060.86      1473090.59      6810363.99
#Sta/Elev= 30
  3578.7 2107.14  3600.5 2107.34  3640.8 2105.28  3751.5 2105.08  3811.9 2102.90
  3892.4 2103.32  3961.5 2100.60  4033.3 2100.96  4093.7 2098.48  4134.0 2098.96
  4184.3 2097.53  4228.9 2098.30  4264.8 2096.27  4285.0 2096.85  4355.4 2094.64
  4849.8 2091.45  4962.9 2091.15  4996.8 2089.09  4997.3 2088.59  5003.4 2089.09
  5106.5 2095.30  5223.9 2096.68  5245.9 2094.23  5281.6 2093.66  5425.9 2099.10
  5448.8 2098.82  5497.2 2102.44  5548.3 2101.51  5794.2 2105.00  5917.8 2105.28
#Mann=6,-1,0
  3578.7   0.035       0  4849.8    0.07       0  4996.8    0.07       0
  5003.4    0.07       0  5281.6   0.035       0  5548.3    0.07       0
Bank Sta=4996.8,5003.4
Exp/Cntr=0.3,0.1

Type RM Length L Ch R = 1,13207,471,471,471
BEGIN DESCRIPTION:
Mapping XS 7553a6a2
END DESCRIPTION:
XS GIS Cut Line= 3
      1471185.05      6811677.18      1472660.71      6811645.93
      1473112.08      6810677.22
#Sta/Elev= 30
  3529.8 2113.88  3569.8 2113.89  3639.8 2110.10  3669.8 2110.40  3709.8 2106.52
  3769.8 2103.52  4039.9 2097.12  4079.9 2094.60  4139.9 2094.28  4197.3 2091.35
  4229.9 2092.25  4289.9 2090.15  4369.9 2090.66  4419.9 2088.30  4730.0 2086.82
  4810.0 2085.12  4900.1 2088.42  4944.3 2086.62  4986.8 2083.95  4987.3 2083.45
  4993.4 2083.95  5005.4 2086.23  5199.5 2087.72  5309.4 2089.29  5457.7 2095.68
  5526.3 2095.76  5566.2 2098.13  5593.2 2096.45  5698.5 2098.78  6074.5 2101.56
#Mann=6,-1,0
  3529.8   0.035       0  4944.3    0.07       0  4986.8    0.07       0
  4993.4    0.07       0  5199.5   0.035       0  5593.2    0.07       0
Bank Sta=4986.8,4993.4
Exp/Cntr=0.3,0.1

Type RM Length L Ch R = 1,12736,506,506,506
BEGIN DESCRIPTION:
Mapping XS 480afaf8
END DESCRIPTION:
XS GIS Cut Line= 3
      1471171.13      6812135.52      1472813.49      6812024.41
      1473167.66      6810746.59
#Sta/Elev= 30
  3555.0 2127.25  3679.2 2114.51  3859.6 2104.88  4220.9 2096.02  4310.6 2094.31
  4380.8 2090.40  4440.9 2090.70  4478.6 2088.57  4661.4 2085.40  4746.3 2086.02
  4801.7 2084.22  4861.8 2085.33  4891.9 2083.18  4932.0 2086.03  5002.2 2083.87
  5071.1 2084.29  5125.7 2084.75  5162.5 2084.66  5169.1 2083.08  5169.6 2082.58
  5176.0 2083.08  5263.9 2085.41  5456.8 2084.36  5524.6 2087.29  5633.1 2087.76
  5871.9 2094.19  6090.8 2095.95  6152.1 2098.40  6172.8 2097.06  6527.1 2100.00
#Mann=8,-1,0
  3555.0    0.16       0  4220.9    0.07       0  4746.3   0.035       0
  5071.1    0.07       0  5125.7   0.035       0  5169.1   0.035       0
  5176.0   0.035       0  5633.1    0.07       0
Bank Sta=5169.1,5176
Exp/Cntr=0.3,0.1

Type RM Length L Ch R = 1,12230,349,349,349
BEGIN DESCRIPTION:
Mapping XS 79665597
END DESCRIPTION:
XS GIS Cut Line= 4
      1471248.40      6812294.37      1472611.23      6812476.66
      1472889.01      6812337.77      1473239.93      6810812.76
#Sta/Elev= 30
  3630.6 2118.68  3777.4 2113.06  3960.1 2105.99  4040.8 2104.72  4101.4 2106.64
  4121.5 2104.27  4131.6 2100.83  4280.9 2097.23  4366.7 2094.20  4494.8 2088.26
  4565.5 2087.90  4600.8 2085.42  4636.1 2086.72  4686.5 2083.49  4737.0 2084.90
  4817.7 2081.96  4927.6 2083.14  5009.7 2081.18  5098.4 2083.20  5117.3 2081.11
  5117.8 2080.61  5124.3 2081.11  5132.8 2082.91  5472.1 2085.11  5788.5 2082.99
  5903.1 2085.19  5956.1 2088.33  6170.3 2090.13  6465.2 2096.62  6881.0 2098.47
#Mann=10,-1,0
  3630.6    0.16       0  3777.4    0.07       0  4280.9    0.16       0
  4366.7    0.07       0  4927.6   0.035       0  5117.3   0.035       0
  5124.3   0.035       0  5472.1    0.07       0  5788.5   0.035       0
  5956.1    0.07       0
Bank Sta=5117.3,5124.3
Exp/Cntr=0.3,0.1

Type RM Length L Ch R = 1,11881,1107,1107,1107
BEGIN DESCRIPTION:
Mapping XS 025a1c7f
END DESCRIPTION:
XS GIS Cut Line= 3
      1471092.16      6812685.00      1472880.33      6812784.82
      1473275.28      6810853.45
#Sta/Elev= 30
  3585.3 2102.93  3673.3 2100.61  4270.7 2094.51  4409.4 2089.27  4539.6 2088.38
  4649.8 2083.87  4719.9 2084.88  4770.0 2082.31  4870.1 2082.99  4920.2 2081.37
  5049.1 2080.65  5180.6 2081.60  5200.7 2081.41  5217.2 2079.46  5217.7 2078.96
  5224.2 2079.46  5247.3 2080.77  5393.4 2079.84  5876.0 2084.07  6224.2 2081.92
  6303.3 2082.92  6393.7 2083.81  6462.0 2087.77  6608.1 2090.73  6673.4 2089.98
  6824.8 2094.35  6925.7 2094.28  7006.1 2096.62  7077.6 2095.94  7347.6 2097.85
#Mann=8,-1,0
  3585.3   0.035       0  3673.3    0.07       0  5049.1   0.035       0
  5217.2    0.07       0  5224.2   0.035       0  5247.3    0.07       0
  6303.3   0.035       0  6462.0    0.07       0
Bank Sta=5217.2,5224.2
Exp/Cntr=0.3,0.1