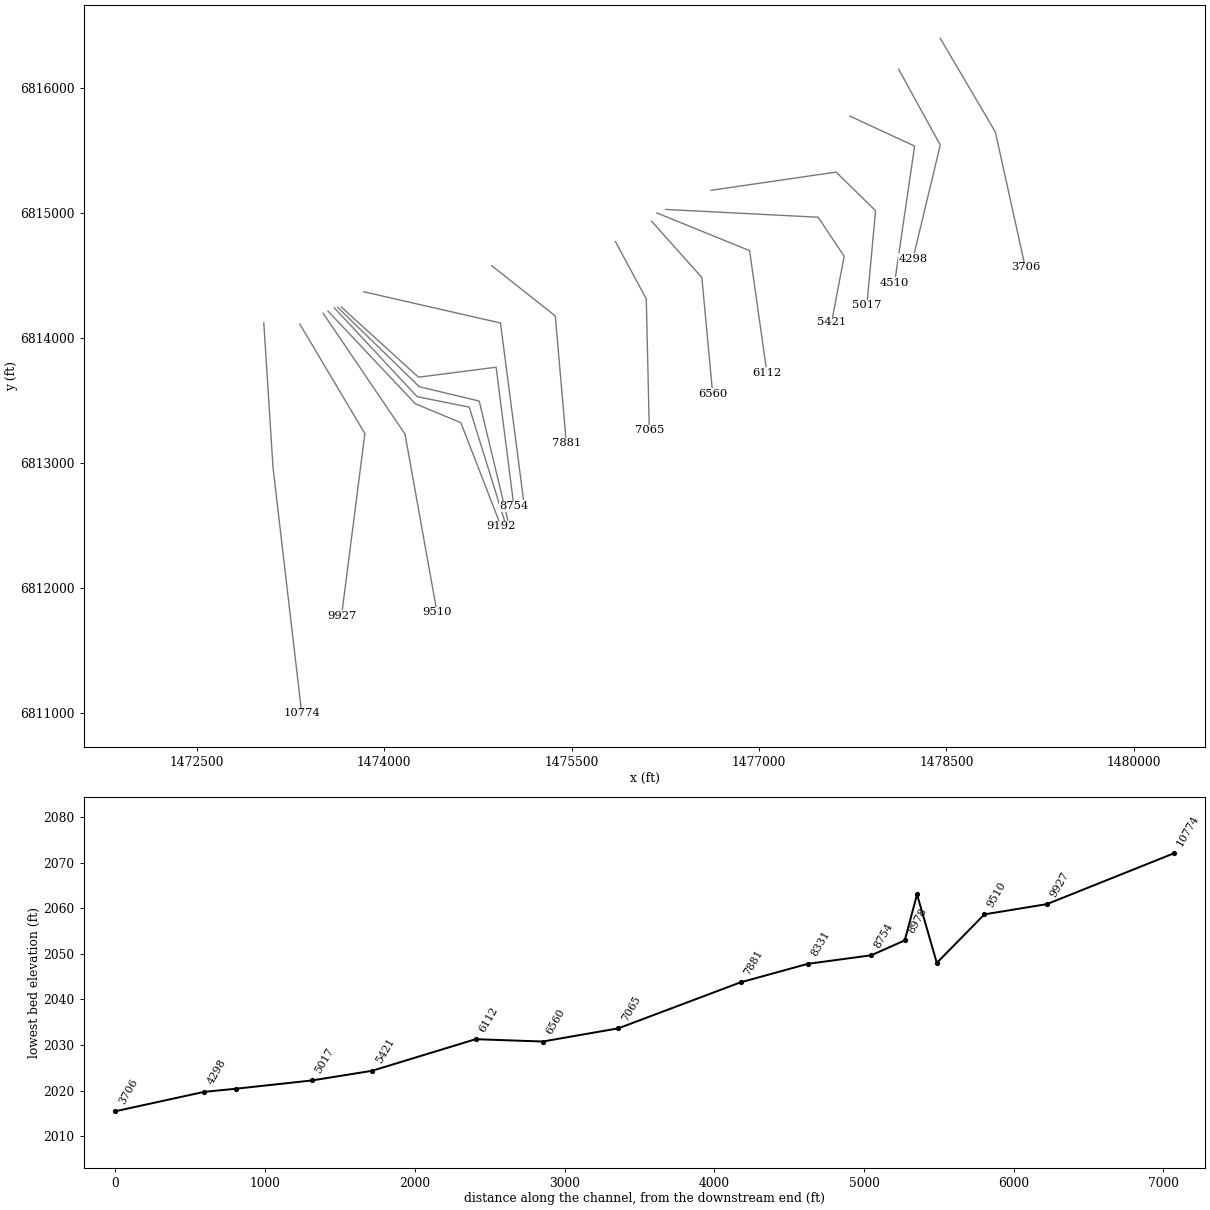
HEC-RAS study NUBIA CREEK TRIBUTARY 3.prj: NUBIA CREEK TRIBUTARY 3 Base Level Engineering

--- NUBIA CREEK TRIBUTARY 3.g01 (geometry) --- (continued)

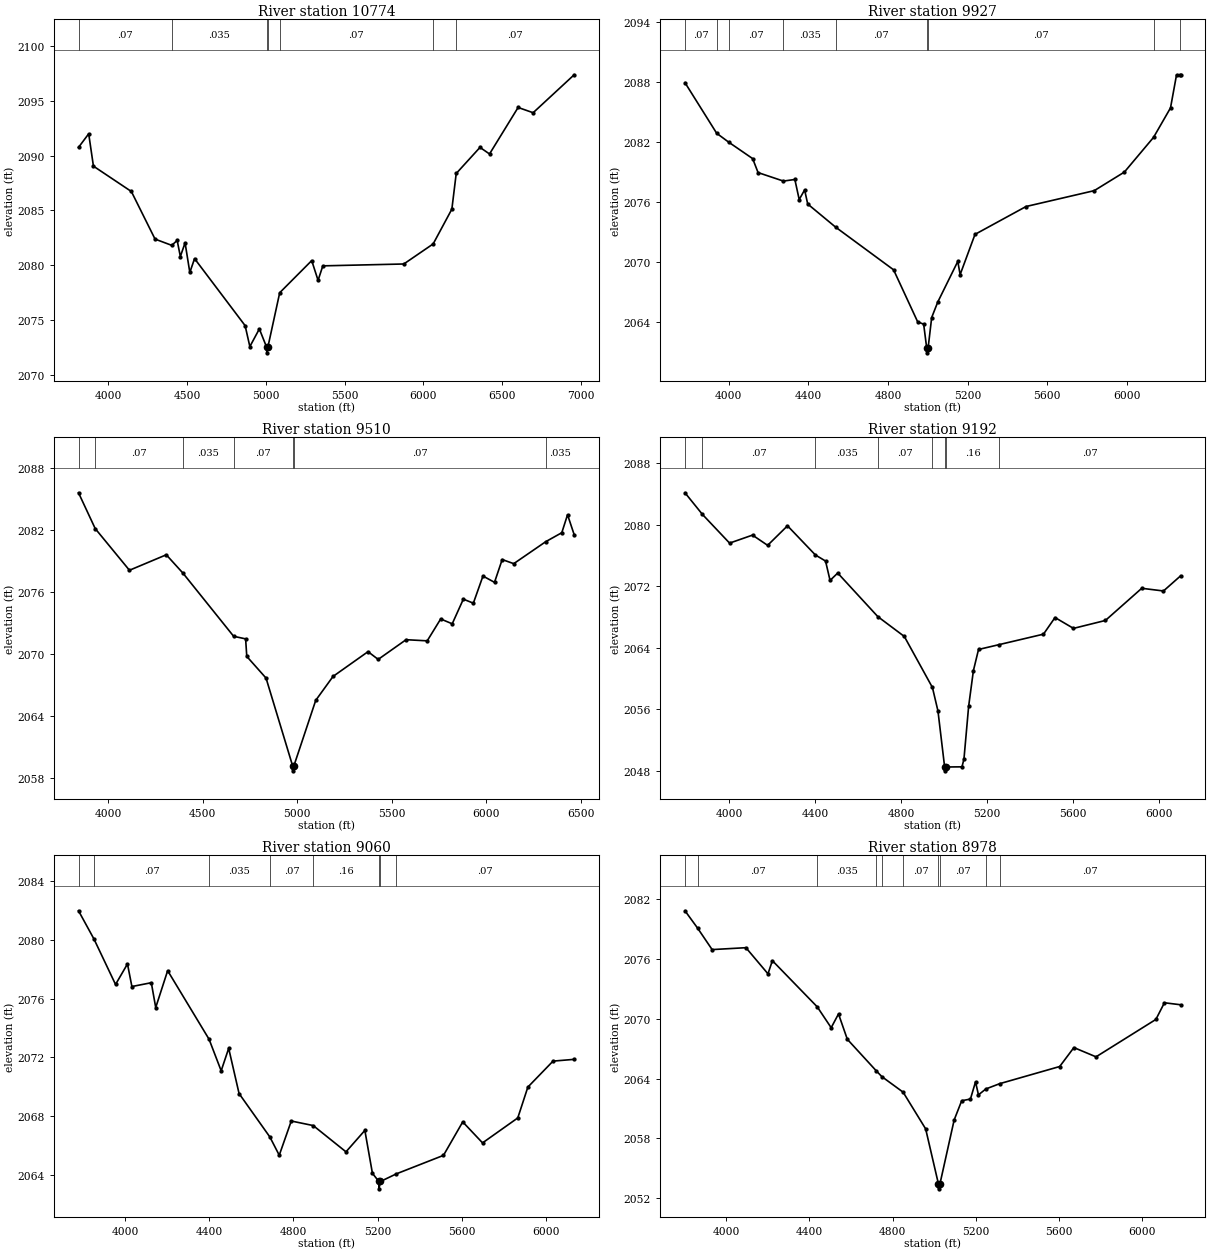
Type RM Length L Ch R = 1,10774,847,847,847
BEGIN DESCRIPTION:
Mapping XS 017e6fc3
END DESCRIPTION:
XS GIS Cut Line= 3
      1473036.58      6814122.45      1473110.36      6812963.64
      1473340.20      6810994.86
#Sta/Elev= 30
  3812.2 2090.75  3876.8 2091.99  3906.8 2089.04  4147.3 2086.73  4297.6 2082.39
  4403.4 2081.82  4437.9 2082.27  4458.0 2080.80  4488.0 2082.05  4518.1 2079.35
  4548.1 2080.61  4868.8 2074.50  4898.8 2072.59  4959.0 2074.20  5005.6 2072.52
  5006.1 2072.02  5012.8 2072.52  5088.1 2077.50  5291.1 2080.43  5331.4 2078.63
  5361.6 2079.95  5875.1 2080.12  6061.3 2081.95  6179.9 2085.12  6207.5 2088.37
  6358.3 2090.75  6418.7 2090.15  6600.0 2094.39  6695.3 2093.91  6955.5 2097.37
#Mann=7,-1,0
  3812.2    0.07       0  4403.4   0.035       0  5005.6   0.035       0
  5012.8   0.035       0  5088.1    0.07       0  6061.3   0.035       0
  6207.5    0.07       0
Bank Sta=5005.6,5012.8
Exp/Cntr=0.3,0.1

Type RM Length L Ch R = 1,9927,417,417,417
BEGIN DESCRIPTION:
Mapping XS db804ba5
END DESCRIPTION:
XS GIS Cut Line= 3
      1473324.76      6814112.62      1473845.60      6813235.86
      1473658.98      6811777.55
#Sta/Elev= 30
  3780.7 2087.97  3939.9 2082.90  4000.9 2082.00  4120.7 2080.36  4147.9 2078.96
  4275.1 2078.11  4332.7 2078.27  4354.5 2076.26  4381.7 2077.22  4397.3 2075.81
  4537.7 2073.49  4828.6 2069.22  4949.6 2064.01  4979.8 2063.77  4994.9 2061.40
  4995.4 2060.90  5002.2 2061.40  5020.1 2064.44  5050.4 2065.98  5151.2 2070.06
  5163.0 2068.74  5237.7 2072.77  5494.0 2075.56  5836.7 2077.15  5988.0 2079.01
  6134.7 2082.49  6219.8 2085.44  6250.1 2088.75  6266.9 2088.76  6270.7 2088.70
#Mann=9,-1,0
  3780.7    0.07       0  3939.9    0.16       0  4000.9    0.07       0
  4275.1   0.035       0  4537.7    0.07       0  4994.9    0.07       0
  5002.2    0.07       0  6134.7   0.035       0  6266.9    0.07       0
Bank Sta=4994.9,5002.2
Exp/Cntr=0.3,0.1

Type RM Length L Ch R = 1,9510,318,318,318
BEGIN DESCRIPTION:
Mapping XS f2a453b9
END DESCRIPTION:
XS GIS Cut Line= 3
      1473511.41      6814199.39      1474166.79      6813231.52
      1474422.86      6811803.58
#Sta/Elev= 30
  3844.3 2085.61  3932.5 2082.14  4113.5 2078.10  4308.2 2079.60  4395.9 2077.83
  4664.2 2071.70  4727.5 2071.45  4733.6 2069.75  4835.4 2067.65  4975.6 2059.16
  4976.1 2058.66  4982.9 2059.16  5098.0 2065.49  5189.5 2067.81  5374.4 2070.21
  5428.1 2069.46  5575.5 2071.37  5687.3 2071.26  5758.4 2073.38  5819.4 2072.91
  5878.2 2075.30  5931.1 2074.91  5981.9 2077.54  6042.9 2076.93  6083.5 2079.14
  6144.5 2078.74  6313.6 2080.87  6398.5 2081.74  6428.9 2083.48  6463.9 2081.55
#Mann=7,-1,0
  3844.3    0.16       0  3932.5    0.07       0  4395.9   0.035       0
  4664.2    0.07       0  4975.6    0.07       0  4982.9    0.07       0
  6313.6   0.035       0
Bank Sta=4975.6,4982.9
Exp/Cntr=0.3,0.1

Type RM Length L Ch R = 1,9192,132,132,132
BEGIN DESCRIPTION:
Mapping XS 7720e00d
END DESCRIPTION:
XS GIS Cut Line= 4
      1473550.49      6814216.74      1474249.25      6813474.58
      1474613.83      6813322.67      1474935.00      6812493.72
#Sta/Elev= 30
  3795.8 2084.15  3876.9 2081.34  4003.1 2077.61  4109.6 2078.65  4179.9 2077.32
  4272.2 2079.86  4401.8 2076.07  4449.0 2075.28  4470.0 2072.76  4505.6 2073.72
  4691.9 2068.06  4815.1 2065.48  4945.7 2058.85  4971.4 2055.80  5002.4 2048.52
  5002.9 2048.02  5009.8 2048.52  5083.0 2048.54  5092.2 2049.55  5113.9 2056.39
  5136.1 2061.04  5159.9 2063.79  5254.2 2064.41  5461.8 2065.78  5515.4 2067.94
  5601.2 2066.53  5749.5 2067.56  5918.4 2071.74  6019.4 2071.39  6099.1 2073.36
#Mann=8,-1,0
  3795.8    0.16       0  3876.9    0.07       0  4401.8   0.035       0
  4691.9    0.07       0  4945.7    0.16       0  5002.4    0.07       0
  5009.8    0.16       0  5254.2    0.07       0
Bank Sta=5002.4,5009.8
Exp/Cntr=0.3,0.1

Type RM Length L Ch R = 1,9060,82,82,82
BEGIN DESCRIPTION:
Mapping XS b93525ca
END DESCRIPTION:
XS GIS Cut Line= 4
      1473600.83      6814242.79      1474264.01      6813531.00
      1474680.67      6813447.67      1474965.09      6812532.00
#Sta/Elev= 30
  3778.4 2081.98  3852.1 2080.05  3954.5 2076.96  4011.2 2078.36  4032.2 2076.82
  4124.5 2077.08  4145.5 2075.39  4202.2 2077.90  4399.1 2073.23  4456.7 2071.08
  4492.4 2072.61  4541.8 2069.53  4688.3 2066.57  4732.8 2065.33  4790.0 2067.66
  4894.3 2067.35  5050.1 2065.56  5139.8 2067.02  5175.8 2064.10  5206.4 2063.54
  5206.9 2063.04  5213.8 2063.54  5289.5 2064.06  5513.6 2065.32  5605.2 2067.60
  5699.4 2066.17  5866.9 2067.87  5914.8 2069.97  6034.5 2071.74  6135.0 2071.86
#Mann=8,-1,0
  3778.4    0.16       0  3852.1    0.07       0  4399.1   0.035       0
  4688.3    0.07       0  4894.3    0.16       0  5206.4    0.07       0
  5213.8    0.16       0  5289.5    0.07       0
Bank Sta=5206.4,5213.8
Exp/Cntr=0.3,0.1

Type RM Length L Ch R = 1,8978,224,224,224
BEGIN DESCRIPTION:
Mapping XS 93e96c02
END DESCRIPTION:
XS GIS Cut Line= 4
      1473628.62      6814246.25      1474281.37      6813610.86
      1474760.54      6813496.28      1474989.52      6812542.18
#Sta/Elev= 30
  3801.4 2080.82  3862.5 2079.07  3932.0 2076.93  4094.6 2077.12  4200.8 2074.50
  4221.9 2075.82  4437.8 2071.19  4504.8 2069.10  4540.1 2070.48  4582.5 2067.94
  4721.2 2064.79  4748.4 2064.20  4850.9 2062.64  4959.4 2058.96  5020.8 2053.45
  5021.3 2052.95  5028.2 2053.45  5096.5 2059.85  5132.8 2061.78  5174.9 2061.95
  5199.3 2063.67  5213.5 2062.37  5248.9 2062.96  5315.6 2063.49  5604.3 2065.21
  5672.6 2067.11  5779.1 2066.18  6067.1 2069.93  6108.2 2071.60  6186.2 2071.40
#Mann=10,-1,0
  3801.4    0.16       0  3862.5    0.07       0  4437.8   0.035       0
  4721.2    0.07       0  4748.4    0.16       0  4850.9    0.07       0
  5020.8    0.07       0  5028.2    0.07       0  5248.9    0.16       0
  5315.6    0.07       0
Bank Sta=5020.8,5028.2
Exp/Cntr=0.3,0.1

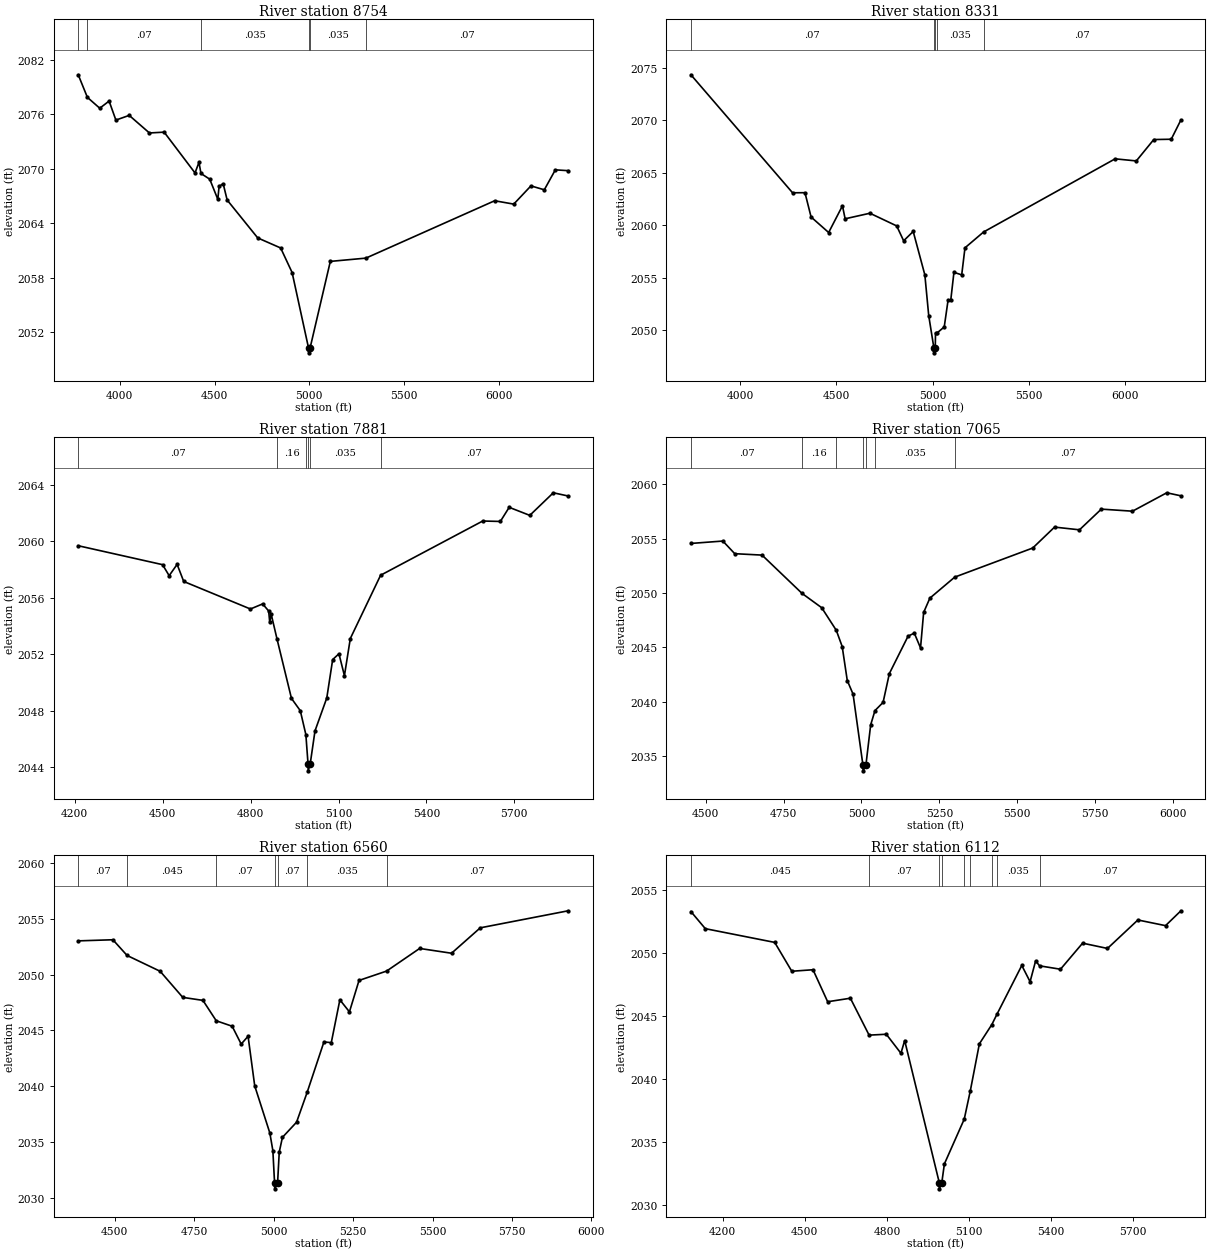
Type RM Length L Ch R = 1,8754,423,423,423
BEGIN DESCRIPTION:
Mapping XS 7694e9f8
END DESCRIPTION:
XS GIS Cut Line= 4
      1473656.35      6814249.77      1474274.42      6813687.25
      1474895.95      6813767.11      1475038.29      6812652.73
#Sta/Elev= 30
  3780.6 2080.37  3828.9 2077.88  3894.2 2076.68  3943.5 2077.47  3979.3 2075.37
  4049.6 2075.89  4156.3 2073.95  4234.0 2074.04  4396.9 2069.54  4417.8 2070.71
  4428.3 2069.48  4474.6 2068.85  4517.2 2066.63  4523.9 2068.06  4545.5 2068.35
  4566.5 2066.55  4727.8 2062.37  4848.8 2061.26  4909.3 2058.55  4996.3 2050.19
  4996.8 2049.69  5003.7 2050.19  5110.9 2059.78  5298.5 2060.14  5978.0 2066.47
  6078.8 2066.10  6169.5 2068.11  6240.1 2067.68  6298.3 2069.88  6366.4 2069.79
#Mann=6,-1,0
  3780.6    0.16       0  3828.9    0.07       0  4428.3   0.035       0
  4996.3   0.035       0  5003.7   0.035       0  5298.5    0.07       0
Bank Sta=4996.3,5003.7
Exp/Cntr=0.3,0.1

Type RM Length L Ch R = 1,8331,450,450,450
BEGIN DESCRIPTION:
Mapping XS 6f37010a
END DESCRIPTION:
XS GIS Cut Line= 3
      1473836.97      6814371.27      1474930.67      6814121.28
      1475114.70      6812708.12
#Sta/Elev= 30
  3743.8 2074.35  4272.3 2063.09  4336.7 2063.10  4368.5 2060.78  4459.8 2059.30
  4531.6 2061.85  4545.4 2060.61  4674.3 2061.14  4813.4 2059.93  4849.6 2058.51
  4899.3 2059.40  4959.8 2055.26  4979.9 2051.38  5006.5 2048.32  5007.0 2047.82
  5014.0 2048.32  5015.3 2049.72  5022.2 2049.70  5060.6 2050.29  5080.8 2052.88
  5094.4 2052.83  5111.0 2055.50  5151.4 2055.26  5168.4 2057.84  5265.1 2059.35
  5948.9 2066.33  6059.0 2066.13  6149.7 2068.17  6240.5 2068.20  6290.8 2070.04
#Mann=5,-1,0
  3743.8    0.07       0  5006.5    0.07       0  5014.0    0.07       0
  5022.2   0.035       0  5265.1    0.07       0
Bank Sta=5006.5,5014
Exp/Cntr=0.3,0.1

Type RM Length L Ch R = 1,7881,816,816,816
BEGIN DESCRIPTION:
Mapping XS 16d7f41d
END DESCRIPTION:
XS GIS Cut Line= 3
      1474861.54      6814579.19      1475369.37      6814178.14
      1475457.91      6813157.27
#Sta/Elev= 30
  4212.0 2059.70  4499.7 2058.36  4522.2 2057.58  4549.4 2058.38  4571.9 2057.17
  4799.5 2055.22  4841.1 2055.58  4861.7 2055.08  4865.3 2054.29  4870.4 2054.85
  4890.5 2053.07  4939.5 2048.89  4969.6 2048.02  4988.6 2046.33  4996.0 2044.26
  4996.5 2043.76  5003.5 2044.26  5019.8 2046.59  5060.0 2048.92  5080.1 2051.64
  5101.5 2052.05  5120.2 2050.50  5140.3 2053.13  5243.6 2057.61  5592.0 2061.45
  5652.2 2061.42  5682.3 2062.42  5752.6 2061.85  5832.9 2063.45  5883.8 2063.22
#Mann=6,-1,0
  4212.0    0.07       0  4890.5    0.16       0  4988.6   0.035       0
  4996.0   0.035       0  5003.5   0.035       0  5243.6    0.07       0
Bank Sta=4996,5003.5
Exp/Cntr=0.3,0.1

Type RM Length L Ch R = 1,7065,505,505,505
BEGIN DESCRIPTION:
Mapping XS 24cf1c37
END DESCRIPTION:
XS GIS Cut Line= 3
      1475851.14      6814772.75      1476097.67      6814314.42
      1476121.97      6813262.62
#Sta/Elev= 30
  4452.8 2054.55  4555.3 2054.77  4593.5 2053.61  4681.1 2053.48  4809.7 2049.96
  4872.6 2048.65  4919.3 2046.58  4938.3 2045.09  4954.6 2041.97  4973.2 2040.72
  5005.0 2034.18  5005.5 2033.68  5014.3 2034.18  5029.7 2037.90  5043.5 2039.21
  5069.5 2039.96  5089.7 2042.61  5149.7 2046.04  5169.7 2046.32  5189.7 2044.96
  5199.7 2048.22  5219.7 2049.53  5299.5 2051.46  5549.8 2054.13  5619.8 2056.05
  5699.8 2055.80  5769.9 2057.70  5869.9 2057.51  5979.9 2059.20  6025.3 2058.92
#Mann=7,-1,0
  4452.8    0.07       0  4809.7    0.16       0  4919.3    0.07       0
  5005.0    0.07       0  5014.3    0.07       0  5043.5   0.035       0
  5299.5    0.07       0
Bank Sta=5005,5014.3
Exp/Cntr=0.3,0.1

Type RM Length L Ch R = 1,6560,448,448,448
BEGIN DESCRIPTION:
Mapping XS a5cce845
END DESCRIPTION:
XS GIS Cut Line= 3
      1476139.67      6814937.00      1476542.46      6814485.60
      1476629.20      6813552.30
#Sta/Elev= 30
  4384.8 2053.04  4493.9 2053.14  4538.6 2051.73  4642.7 2050.31  4713.8 2047.97
  4777.3 2047.70  4819.2 2045.87  4869.3 2045.38  4897.7 2043.78  4919.4 2044.48
  4940.3 2040.03  4987.9 2035.80  4997.4 2034.22  5002.8 2031.29  5003.3 2030.79
  5012.2 2031.29  5017.5 2034.09  5027.5 2035.41  5072.0 2036.77  5105.2 2039.44
  5158.1 2043.97  5181.3 2043.91  5208.3 2047.75  5238.4 2046.67  5268.6 2049.49
  5355.4 2050.33  5459.4 2052.36  5559.8 2051.93  5650.2 2054.21  5927.1 2055.74
#Mann=7,-1,0
  4384.8    0.07       0  4538.6   0.045       0  4819.2    0.07       0
  5002.8    0.07       0  5012.2    0.07       0  5105.2   0.035       0
  5355.4    0.07       0
Bank Sta=5002.8,5012.2
Exp/Cntr=0.3,0.1

Type RM Length L Ch R = 1,6112,691,691,691
BEGIN DESCRIPTION:
Mapping XS 00fd4b22
END DESCRIPTION:
XS GIS Cut Line= 3
      1476181.38      6815002.95      1476924.40      6814700.88
      1477063.20      6813722.36
#Sta/Elev= 30
  4083.6 2053.31  4136.3 2051.95  4389.8 2050.86  4452.2 2048.57  4529.8 2048.69
  4583.3 2046.15  4666.3 2046.43  4734.7 2043.50  4797.5 2043.57  4851.0 2042.06
  4864.7 2043.07  4991.0 2031.80  4991.5 2031.30  5000.4 2031.80  5009.8 2033.28
  5082.3 2036.83  5104.6 2039.09  5137.6 2042.81  5183.2 2044.34  5203.1 2045.21
  5292.6 2049.03  5322.9 2047.74  5343.1 2049.39  5357.6 2049.00  5434.0 2048.73
  5514.8 2050.80  5605.7 2050.38  5716.8 2052.64  5817.8 2052.19  5874.0 2053.37
#Mann=9,-1,0
  4083.6   0.045       0  4734.7    0.07       0  4991.0    0.07       0
  5000.4    0.07       0  5082.3    0.16       0  5104.6    0.07       0
  5183.2    0.16       0  5203.1   0.035       0  5357.6    0.07       0
Bank Sta=4991,5000.4
Exp/Cntr=0.3,0.1

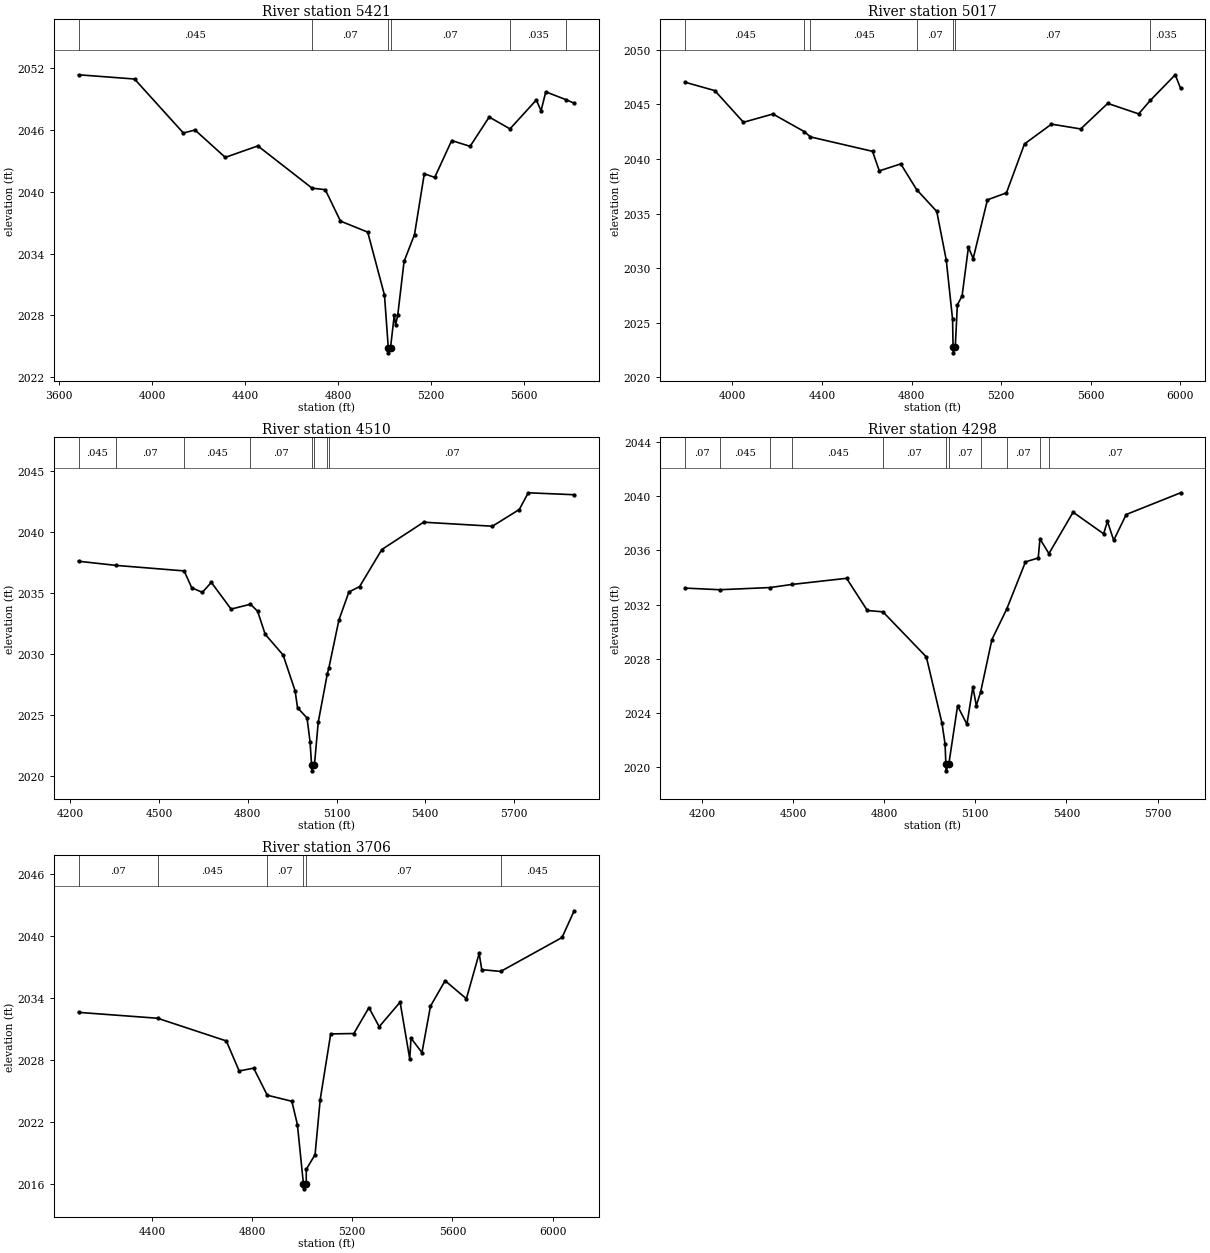
Type RM Length L Ch R = 1,5421,404,404,404
BEGIN DESCRIPTION:
Mapping XS 72867f47
END DESCRIPTION:
XS GIS Cut Line= 4
      1476254.26      6815030.74      1477473.01      6814968.24
      1477681.35      6814655.74      1477580.66      6814128.00
#Sta/Elev= 30
  3682.8 2051.31  3923.9 2050.90  4134.1 2045.67  4184.2 2045.96  4314.4 2043.31
  4454.6 2044.42  4688.0 2040.33  4744.9 2040.18  4810.1 2037.14  4927.5 2036.07
  4999.6 2029.97  5016.0 2024.88  5016.5 2024.38  5025.6 2024.88  5041.8 2028.03
  5047.8 2027.11  5056.8 2028.05  5083.9 2033.23  5128.9 2035.84  5171.0 2041.72
  5215.9 2041.37  5288.8 2044.94  5368.1 2044.38  5450.3 2047.22  5539.8 2046.07
  5653.1 2048.87  5673.5 2047.82  5693.8 2049.66  5779.3 2048.91  5816.0 2048.56
#Mann=6,-1,0
  3682.8   0.045       0  4688.0    0.07       0  5016.0    0.07       0
  5025.6    0.07       0  5539.8   0.035       0  5779.3    0.07       0
Bank Sta=5016,5025.6
Exp/Cntr=0.3,0.1

Type RM Length L Ch R = 1,5017,507,507,507
BEGIN DESCRIPTION:
Mapping XS 157d5166
END DESCRIPTION:
XS GIS Cut Line= 4
      1476616.57      6815184.04      1477616.59      6815329.87
      1477932.56      6815020.85      1477863.12      6814263.89
#Sta/Elev= 30
  3788.5 2047.03  3921.6 2046.26  4049.7 2043.36  4181.0 2044.12  4320.8 2042.51
  4348.7 2042.02  4625.7 2040.70  4656.0 2038.91  4751.7 2039.55  4822.5 2037.20
  4912.4 2035.20  4954.8 2030.76  4983.1 2025.33  4985.4 2022.75  4985.9 2022.25
  4995.1 2022.75  5004.4 2026.63  5025.6 2027.47  5053.9 2031.92  5075.1 2030.88
  5138.7 2036.26  5223.6 2036.90  5304.2 2041.38  5424.7 2043.19  5555.2 2042.75
  5675.7 2045.09  5813.8 2044.13  5866.2 2045.37  5977.0 2047.71  6001.2 2046.46
#Mann=7,-1,0
  3788.5   0.045       0  4320.8    0.07       0  4348.7   0.045       0
  4822.5    0.07       0  4985.4    0.07       0  4995.1    0.07       0
  5866.2   0.035       0
Bank Sta=4985.4,4995.1
Exp/Cntr=0.3,0.1

Type RM Length L Ch R = 1,4510,212,212,212
BEGIN DESCRIPTION:
Mapping XS 027b0875
END DESCRIPTION:
XS GIS Cut Line= 3
      1477727.68      6815777.80      1478245.06      6815538.21
      1478085.34      6814444.47
#Sta/Elev= 30
  4227.7 2037.61  4354.9 2037.27  4584.7 2036.82  4610.5 2035.44  4646.3 2035.06
  4676.6 2035.88  4743.5 2033.69  4809.0 2034.09  4833.2 2033.51  4858.7 2031.63
  4919.3 2029.93  4959.8 2027.00  4968.1 2025.61  5000.2 2024.77  5010.3 2022.84
  5015.6 2020.94  5016.1 2020.44  5025.3 2020.94  5038.0 2024.42  5068.8 2028.39
  5073.7 2028.84  5108.0 2032.80  5141.7 2035.09  5178.0 2035.54  5253.0 2038.57
  5394.3 2040.81  5626.8 2040.48  5717.7 2041.85  5748.0 2043.22  5903.2 2043.06
#Mann=8,-1,0
  4227.7   0.045       0  4354.9    0.07       0  4584.7   0.045       0
  4809.0    0.07       0  5015.6    0.07       0  5025.3    0.07       0
  5068.8    0.16       0  5073.7    0.07       0
Bank Sta=5015.6,5025.3
Exp/Cntr=0.3,0.1

Type RM Length L Ch R = 1,4298,592,592,592
BEGIN DESCRIPTION:
Mapping XS bab0e59f
END DESCRIPTION:
XS GIS Cut Line= 3
      1478116.98      6816154.53      1478450.33      6815546.86
      1478231.58      6814633.69
#Sta/Elev= 30
  4143.9 2033.21  4258.1 2033.09  4423.9 2033.25  4496.6 2033.48  4676.0 2033.93
  4744.4 2031.56  4795.7 2031.46  4938.7 2028.14  4990.1 2023.27  5000.3 2021.73
  5003.0 2020.25  5003.5 2019.75  5012.7 2020.25  5041.5 2024.53  5072.3 2023.18
  5091.9 2025.92  5103.2 2024.56  5117.2 2025.53  5154.6 2029.42  5203.2 2031.66
  5265.1 2035.14  5307.1 2035.43  5312.8 2036.83  5342.3 2035.75  5421.9 2038.80
  5522.4 2037.21  5535.1 2038.12  5555.6 2036.73  5596.8 2038.63  5776.0 2040.23
#Mann=11,-1,0
  4143.9    0.07       0  4258.1   0.045       0  4423.9    0.07       0
  4496.6   0.045       0  4795.7    0.07       0  5003.0    0.07       0
  5012.7    0.07       0  5117.2    0.16       0  5203.2    0.07       0
  5312.8    0.16       0  5342.3    0.07       0
Bank Sta=5003,5012.7
Exp/Cntr=0.3,0.1

Type RM Length L Ch R = 1,3706,560,560,560
BEGIN DESCRIPTION:
Mapping XS f68bb1a8
END DESCRIPTION:
XS GIS Cut Line= 3
      1478450.32      6816401.05      1478891.30      6815651.03
      1479130.89      6814567.66
#Sta/Elev= 30
  4106.6 2032.62  4422.4 2032.05  4696.9 2029.85  4748.2 2026.94  4806.2 2027.21
  4860.4 2024.59  4958.6 2024.00  4980.8 2021.74  5004.8 2016.01  5005.3 2015.51
  5016.1 2016.01  5016.3 2017.40  5051.4 2018.83  5071.9 2024.17  5113.8 2030.53
  5206.2 2030.57  5266.5 2033.08  5307.5 2031.23  5391.0 2033.61  5429.5 2028.11
  5434.6 2030.12  5478.3 2028.72  5512.3 2033.22  5570.7 2035.69  5655.7 2033.94
  5706.7 2038.33  5717.2 2036.76  5792.8 2036.59  6037.8 2039.88  6086.2 2042.47
#Mann=6,-1,0
  4106.6    0.07       0  4422.4   0.045       0  4860.4    0.07       0
  5004.8    0.07       0  5016.1    0.07       0  5792.8   0.045       0
Bank Sta=5004.8,5016.1
Exp/Cntr=0.3,0.1