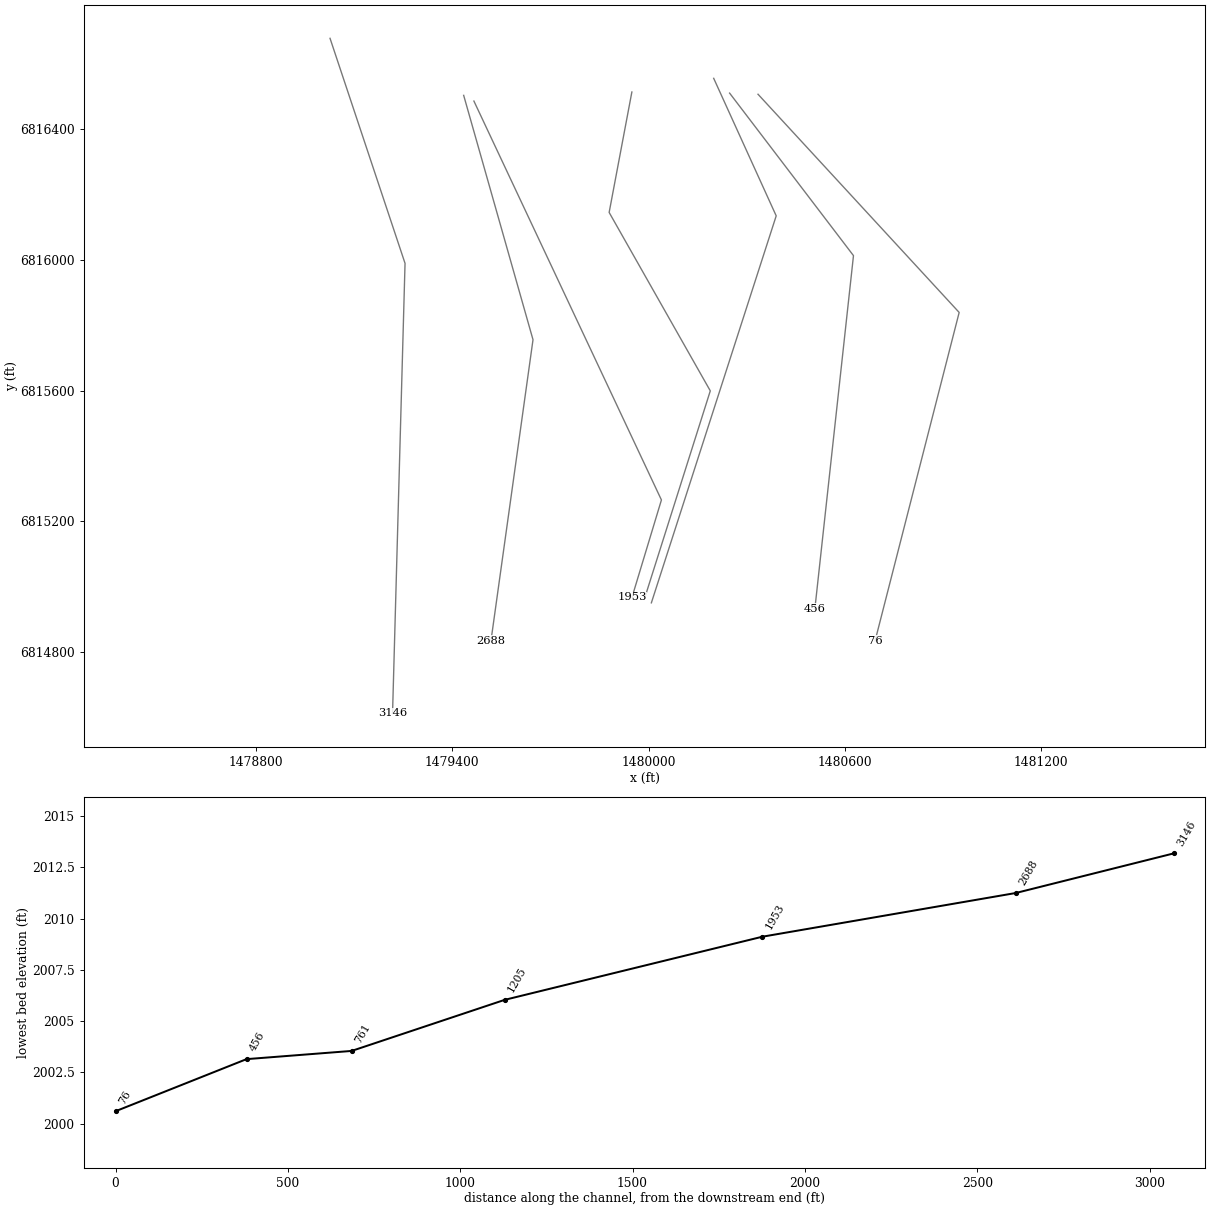
HEC-RAS study NUBIA CREEK TRIBUTARY 3.prj: NUBIA CREEK TRIBUTARY 3 Base Level Engineering

--- NUBIA CREEK TRIBUTARY 3.g01 (geometry) --- (continued)

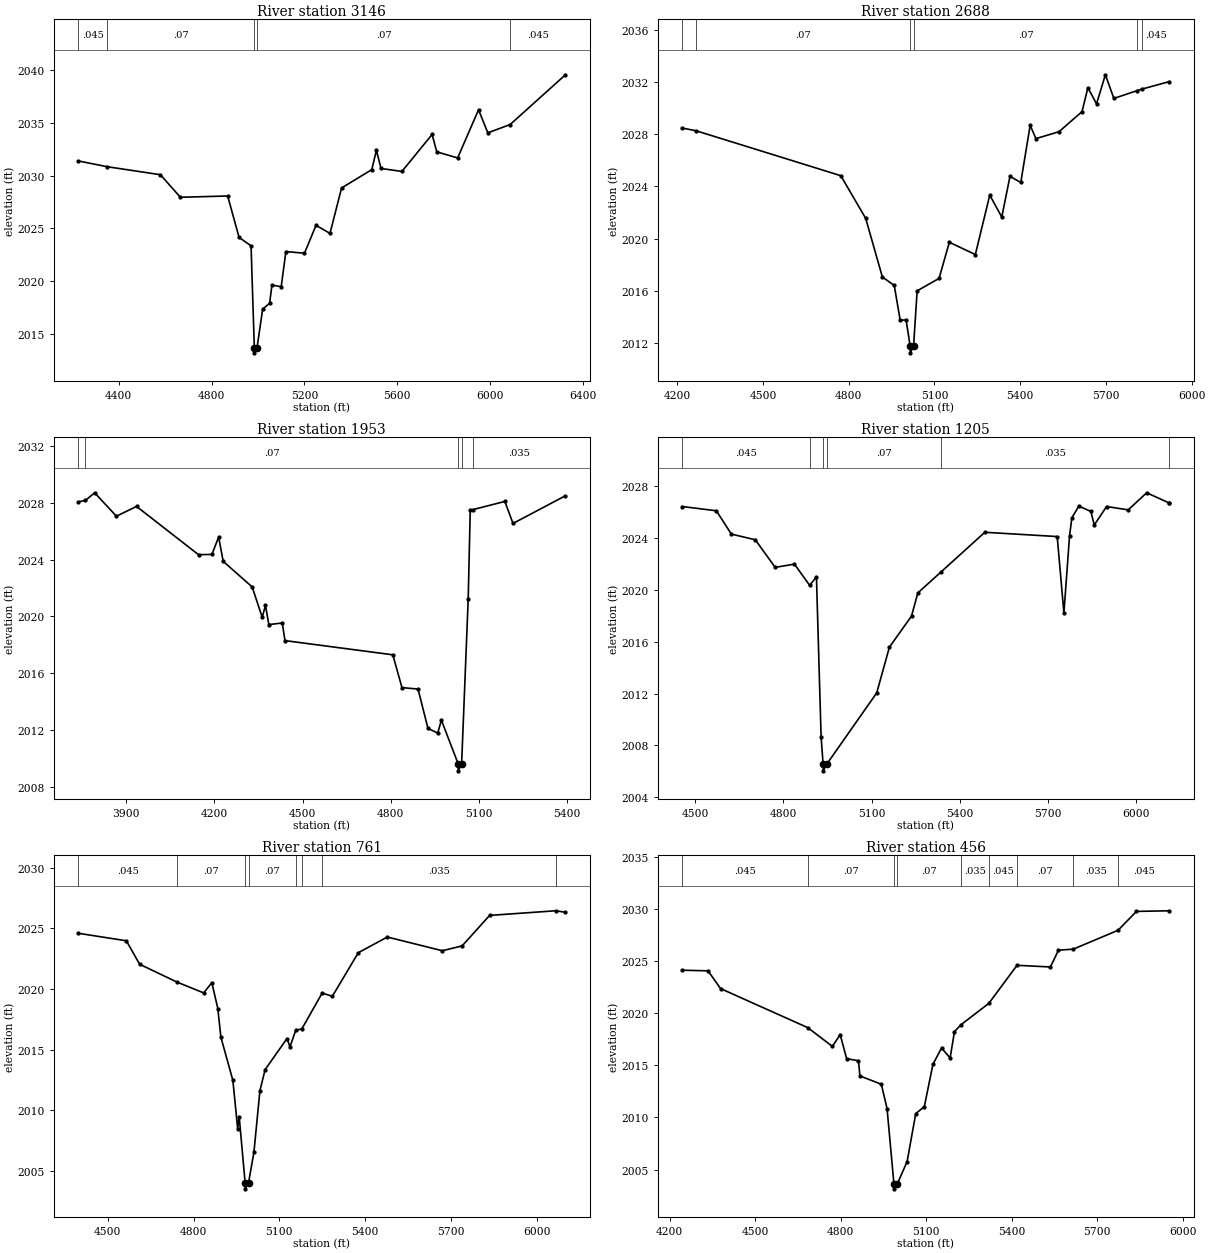
Type RM Length L Ch R = 1,3146,458,458,458
BEGIN DESCRIPTION:
Mapping XS 6a7ca7e9
END DESCRIPTION:
XS GIS Cut Line= 3
      1479026.72      6816676.20      1479255.88      6815988.70
      1479217.69      6814613.72
#Sta/Elev= 30
  4224.7 2031.39  4349.5 2030.84  4579.4 2030.08  4665.5 2027.94  4869.3 2028.06
  4918.5 2024.13  4970.1 2023.33  4984.2 2013.68  4984.7 2013.18  4996.0 2013.68
  5020.1 2017.33  5050.1 2017.88  5060.1 2019.60  5100.1 2019.46  5120.2 2022.79
  5200.2 2022.63  5250.2 2025.28  5310.2 2024.51  5360.2 2028.82  5490.3 2030.56
  5510.3 2032.39  5530.3 2030.67  5620.3 2030.39  5750.4 2033.90  5770.4 2032.25
  5860.4 2031.67  5950.5 2036.24  5990.5 2034.05  6086.8 2034.84  6324.9 2039.56
#Mann=5,-1,0
  4224.7   0.045       0  4349.5    0.07       0  4984.2    0.07       0
  4996.0    0.07       0  6086.8   0.045       0
Bank Sta=4984.2,4996
Exp/Cntr=0.3,0.1

Type RM Length L Ch R = 1,2688,735,735,735
BEGIN DESCRIPTION:
Mapping XS 23e8d483
END DESCRIPTION:
XS GIS Cut Line= 3
      1479435.04      6816501.94      1479646.86      6815755.37
      1479518.38      6814835.23
#Sta/Elev= 30
  4217.3 2028.47  4266.2 2028.26  4772.3 2024.82  4859.5 2021.55  4917.8 2017.06
  4959.4 2016.41  4980.2 2013.74  5000.8 2013.78  5015.1 2011.75  5015.6 2011.25
  5026.9 2011.75  5039.5 2016.00  5116.1 2016.95  5152.2 2019.72  5243.1 2018.78
  5293.6 2023.33  5335.6 2021.65  5364.3 2024.77  5402.1 2024.30  5434.9 2028.68
  5455.1 2027.66  5535.9 2028.19  5616.5 2029.73  5636.9 2031.56  5667.2 2030.32
  5698.1 2032.55  5727.8 2030.74  5809.9 2031.34  5827.0 2031.46  5922.4 2032.03
#Mann=6,-1,0
  4217.3   0.045       0  4266.2    0.07       0  5015.1    0.07       0
  5026.9    0.07       0  5809.9   0.035       0  5827.0   0.045       0
Bank Sta=5015.1,5026.9
Exp/Cntr=0.3,0.1

Type RM Length L Ch R = 1,1953,748,748,748
BEGIN DESCRIPTION:
Mapping XS 39c5c536
END DESCRIPTION:
XS GIS Cut Line= 3
      1479466.30      6816484.53      1480039.22      6815265.78
      1479949.47      6814968.94
#Sta/Elev= 30
  3736.8 2028.06  3761.6 2028.16  3793.1 2028.70  3867.1 2027.05  3935.5 2027.74
  4146.2 2024.34  4191.8 2024.36  4214.6 2025.58  4230.2 2023.87  4328.6 2022.07
  4362.8 2019.93  4373.9 2020.77  4385.3 2019.42  4430.9 2019.53  4440.1 2018.29
  4806.8 2017.29  4837.9 2014.98  4892.5 2014.88  4926.3 2012.11  4959.5 2011.78
  4971.9 2012.69  5028.9 2009.62  5029.4 2009.12  5040.7 2009.62  5063.1 2021.23
  5070.0 2027.50  5078.2 2027.51  5187.7 2028.09  5215.4 2026.54  5393.6 2028.49
#Mann=5,-1,0
  3736.8   0.045       0  3761.6    0.07       0  5028.9    0.07       0
  5040.7    0.07       0  5078.2   0.035       0
Bank Sta=5028.9,5040.7
Exp/Cntr=0.3,0.1

Type RM Length L Ch R = 1,1205,444,444,444
BEGIN DESCRIPTION:
Mapping XS 53e33f54
END DESCRIPTION:
XS GIS Cut Line= 4
      1479948.93      6816512.27      1479879.50      6816144.26
      1480188.52      6815599.12      1479990.62      6814974.14
#Sta/Elev= 30
  4456.1 2026.45  4572.4 2026.12  4623.3 2024.32  4704.7 2023.88  4772.4 2021.75
  4837.8 2022.00  4889.6 2020.36  4912.6 2021.02  4928.5 2008.65  4935.3 2006.54
  4935.8 2006.04  4947.2 2006.54  5117.5 2012.06  5160.7 2015.59  5235.8 2017.99
  5257.4 2019.78  5335.8 2021.39  5485.1 2024.46  5731.1 2024.13  5753.9 2018.23
  5773.1 2024.19  5781.0 2025.58  5804.6 2026.48  5845.6 2026.07  5857.0 2025.02
  5899.0 2026.45  5972.4 2026.19  6035.3 2027.51  6110.1 2026.74  6112.8 2026.74
#Mann=6,-1,0
  4456.1   0.045       0  4889.6    0.07       0  4935.3    0.07       0
  4947.2    0.07       0  5335.8   0.035       0  6110.1    0.07       0
Bank Sta=4935.3,4947.2
Exp/Cntr=0.3,0.1

Type RM Length L Ch R = 1,761,305,305,305
BEGIN DESCRIPTION:
Mapping XS 7cb53cc8
END DESCRIPTION:
XS GIS Cut Line= 3
      1480198.92      6816554.02      1480389.91      6816133.84
      1480008.48      6814951.39
#Sta/Elev= 30
  4396.3 2024.59  4565.1 2023.97  4611.3 2022.04  4742.2 2020.57  4835.3 2019.68
  4864.0 2020.52  4884.9 2018.39  4895.5 2016.04  4937.5 2012.48  4954.3 2008.50
  4959.5 2009.50  4980.4 2004.05  4980.9 2003.55  4992.3 2004.05  5011.1 2006.57
  5032.1 2011.64  5050.4 2013.37  5126.7 2015.92  5137.2 2015.24  5157.1 2016.59
  5179.0 2016.73  5249.8 2019.67  5285.3 2019.40  5376.2 2022.99  5477.6 2024.28
  5669.8 2023.15  5739.2 2023.55  5835.3 2026.06  6065.8 2026.44  6100.3 2026.32
#Mann=8,-1,0
  4396.3   0.045       0  4742.2    0.07       0  4980.4    0.07       0
  4992.3    0.07       0  5157.1   0.035       0  5179.0    0.07       0
  5249.8   0.035       0  6065.8    0.07       0
Bank Sta=4980.4,4992.3
Exp/Cntr=0.3,0.1

Type RM Length L Ch R = 1,456,380,380,380
BEGIN DESCRIPTION:
Mapping XS 1d29b82b
END DESCRIPTION:
XS GIS Cut Line= 3
      1480247.54      6816508.86      1480626.02      6816012.31
      1480507.99      6814932.69
#Sta/Elev= 30
  4243.7 2024.12  4334.7 2024.06  4378.3 2022.36  4684.6 2018.61  4771.1 2016.81
  4798.2 2017.95  4821.0 2015.64  4862.6 2015.43  4867.6 2013.98  4942.8 2013.18
  4962.9 2010.84  4986.9 2003.65  4987.4 2003.15  4999.2 2003.65  5033.3 2005.77
  5063.5 2010.36  5093.7 2011.04  5123.9 2015.10  5154.1 2016.66  5184.2 2015.70
  5199.4 2018.23  5222.3 2018.89  5320.1 2020.94  5419.0 2024.59  5536.3 2024.43
  5564.5 2026.04  5616.6 2026.14  5773.6 2027.95  5838.1 2029.76  5954.1 2029.82
#Mann=9,-1,0
  4243.7   0.045       0  4684.6    0.07       0  4986.9    0.07       0
  4999.2    0.07       0  5222.3   0.035       0  5320.1   0.045       0
  5419.0    0.07       0  5616.6   0.035       0  5773.6   0.045       0
Bank Sta=4986.9,4999.2
Exp/Cntr=0.3,0.1

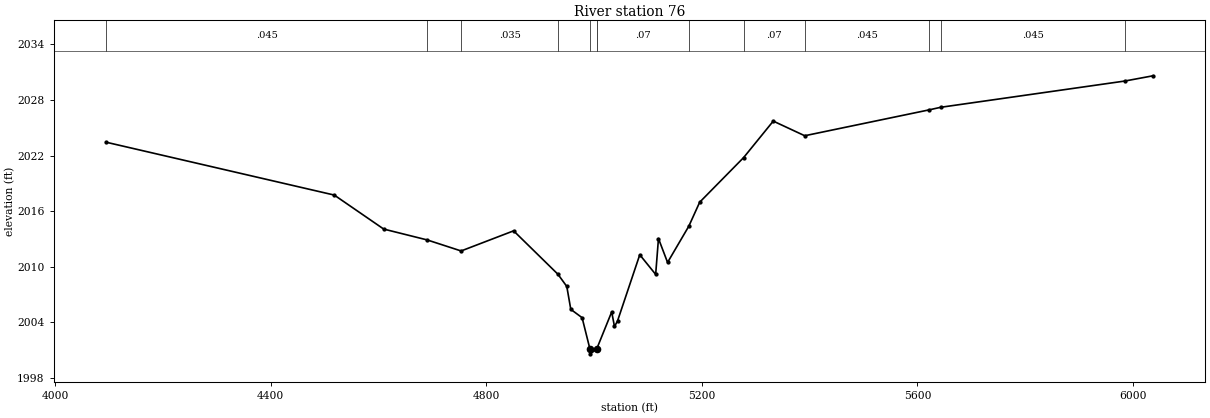
Type RM Length L Ch R = 1,76,0,0,0
BEGIN DESCRIPTION:
NUBIA CREEK TRIBUTARY 3 1.0
END DESCRIPTION:
XS GIS Cut Line= 3
      1480334.34      6816505.39      1480948.94      6815838.70
      1480692.00      6814835.23
#Sta/Elev= 30
  4094.7 2023.44  4517.9 2017.74  4609.7 2014.07  4690.3 2012.90  4753.3 2011.71
  4850.7 2013.88  4932.9 2009.20  4949.4 2007.88  4956.8 2005.41  4977.8 2004.51
  4992.4 2001.11  4992.9 2000.61  5004.7 2001.11  5005.0 2001.15  5032.7 2005.13
  5037.9 2003.56  5043.5 2004.15  5084.8 2011.30  5114.3 2009.18  5119.5 2013.05
  5136.4 2010.47  5175.8 2014.38  5196.0 2016.97  5277.6 2021.79  5332.5 2025.72
  5390.9 2024.14  5622.4 2026.94  5643.2 2027.21  5984.6 2030.04  6037.3 2030.61
#Mann=13,-1,0
  4094.7   0.045       0  4690.3    0.07       0  4753.3   0.035       0
  4932.9    0.16       0  4992.4    0.07       0  5004.7    0.16       0
  5005.0    0.07       0  5175.8    0.16       0  5277.6    0.07       0
  5390.9   0.045       0  5622.4   0.035       0  5643.2   0.045       0
  5984.6   0.035       0
Bank Sta=4992.4,5004.7
Exp/Cntr=0.3,0.1

Chan Stop Cuts=-1