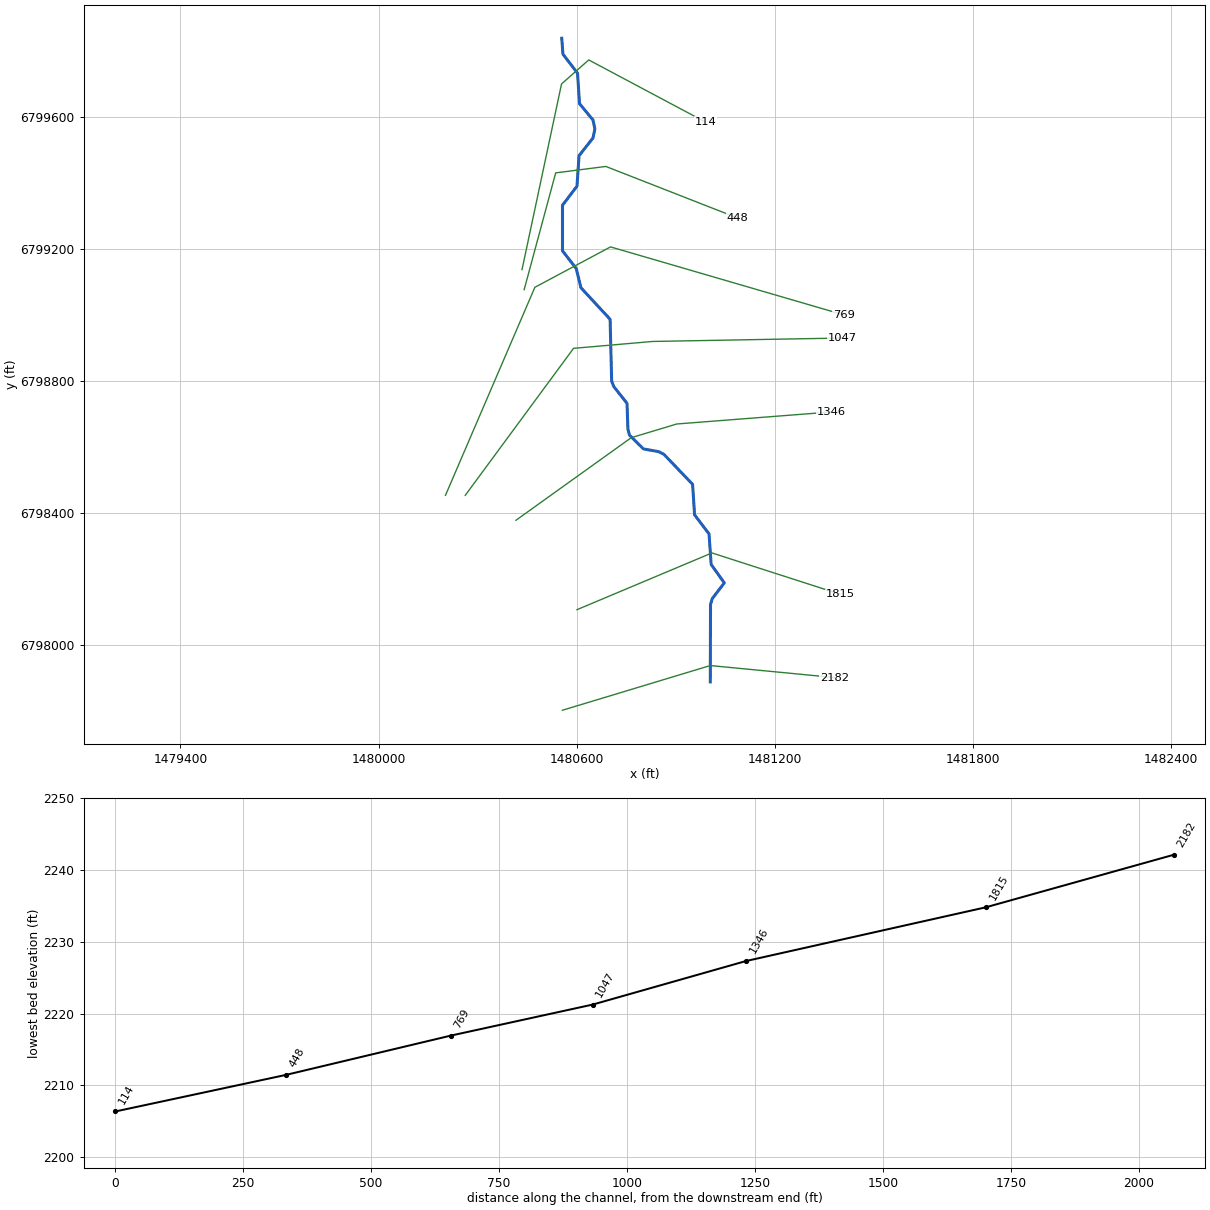
--- NUBIA CREEK TRIBUTARY 4.prj (project) ---

Proj Title=NUBIA CREEK TRIBUTARY 4 Base Level Engineering
Current Plan=p01
Default Exp/Contr=0.3,0.1
English Units
Geom File=g01
Flow File=f01
Plan File=p01
Y Axis Title=Elevation
X Axis Title(PF)=Main Channel Distance
X Axis Title(XS)=Station
BEGIN DESCRIPTION:
NUBIA CREEK TRIBUTARY 4
END DESCRIPTION:
DSS Export Rating Curves= 0
DSS Export Rating Curve Sorted= 0
DSS Export Volume Flow Curves= 0
DXF OffsetX= 0
DXF OffsetY= 0
DXF ScaleX= 1
DXF ScaleY= 10

--- NUBIA CREEK TRIBUTARY 4.p01 (plan) ---

Plan Title=Multiple Run
Short Identifier=Multiple
Geom File=g01
Flow File=f01
Subcritical Flow
K Sum by GR= 0
Std Step Tol= 0.01
Critical Tol= 0.01
Num of Std Step Trials= 20
Max Error Tol= 0.3
Flow Tol Ratio= 0.001
Split Flow NTrial= 30
Split Flow Tol= 0.02
Split Flow Ratio= 0.02
Log Output Level= 0
Friction Slope Method= 1
Unsteady Friction Slope Method= 2
Unsteady Bridges Friction Slope Method= 1
Parabolic Critical Depth
Global Vel Dist=  1 , 1 , 1
Global Log Level= 0
CheckData=True
Encroach Param= -1, 0, 0, 0
BEGIN DESCRIPTION:
Multiple Run
END DESCRIPTION:

--- NUBIA CREEK TRIBUTARY 4.f01 (steady flow) ---

Flow Title=Multiple
Program Version=4.10
Number of Profiles= 7
Profile Names=10-year,25-year,50-year,1pct_min,100-year,1pct_plu,500-year
River Rch & RM=NUBIA CREEK TRIB,Reach-1         ,2182
     274     390     488     305     609    1216     958
Boundary for River Rch & Prof#=NUBIA CREEK TRIB,Reach-1         , 1
Up Type= 0
Dn Type= 3
Dn Slope=0.017
Boundary for River Rch & Prof#=NUBIA CREEK TRIB,Reach-1         , 2
Up Type= 0
Dn Type= 3
Dn Slope=0.017
Boundary for River Rch & Prof#=NUBIA CREEK TRIB,Reach-1         , 3
Up Type= 0
Dn Type= 3
Dn Slope=0.017
Boundary for River Rch & Prof#=NUBIA CREEK TRIB,Reach-1         , 4
Up Type= 0
Dn Type= 3
Dn Slope=0.017
Boundary for River Rch & Prof#=NUBIA CREEK TRIB,Reach-1         , 5
Up Type= 0
Dn Type= 3
Dn Slope=0.017
Boundary for River Rch & Prof#=NUBIA CREEK TRIB,Reach-1         , 6
Up Type= 0
Dn Type= 3
Dn Slope=0.017
Boundary for River Rch & Prof#=NUBIA CREEK TRIB,Reach-1         , 7
Up Type= 0
Dn Type= 3
Dn Slope=0.017
DSS Import GetInterval= 0
DSS Import GetPeak= 0
DSS Import FillOption= 0

--- NUBIA CREEK TRIBUTARY 4.g01 (geometry) ---

Geom Title=Existing Conditions
Program Version=4.10

River Reach=NUBIA CREEK TRIB,Reach-1
Reach XY= 30
        1481005.        6797888.      1481005.66      6798122.84
      1481011.02      6798140.45      1481047.44        6798188.
      1481007.55      6798243.89      1481001.15       6798336.4
      1480957.36      6798393.98      1480951.39      6798486.52
      1480864.68      6798577.22      1480848.92      6798585.45
      1480802.43      6798593.74      1480760.42      6798635.33
      1480755.47      6798653.09      1480752.64      6798732.02
      1480713.14      6798781.94      1480706.22       6798798.5
      1480701.45      6798986.53      1480613.16      6799081.95
      1480598.86      6799140.17      1480557.23      6799193.93
      1480557.25      6799332.06      1480601.14       6799389.6
      1480607.38      6799482.03      1480649.63      6799535.82
       1480655.4        6799563.      1480649.63      6799590.18
      1480608.88      6799639.58      1480602.78      6799732.08
      1480558.64      6799789.51        1480555.        6799838.

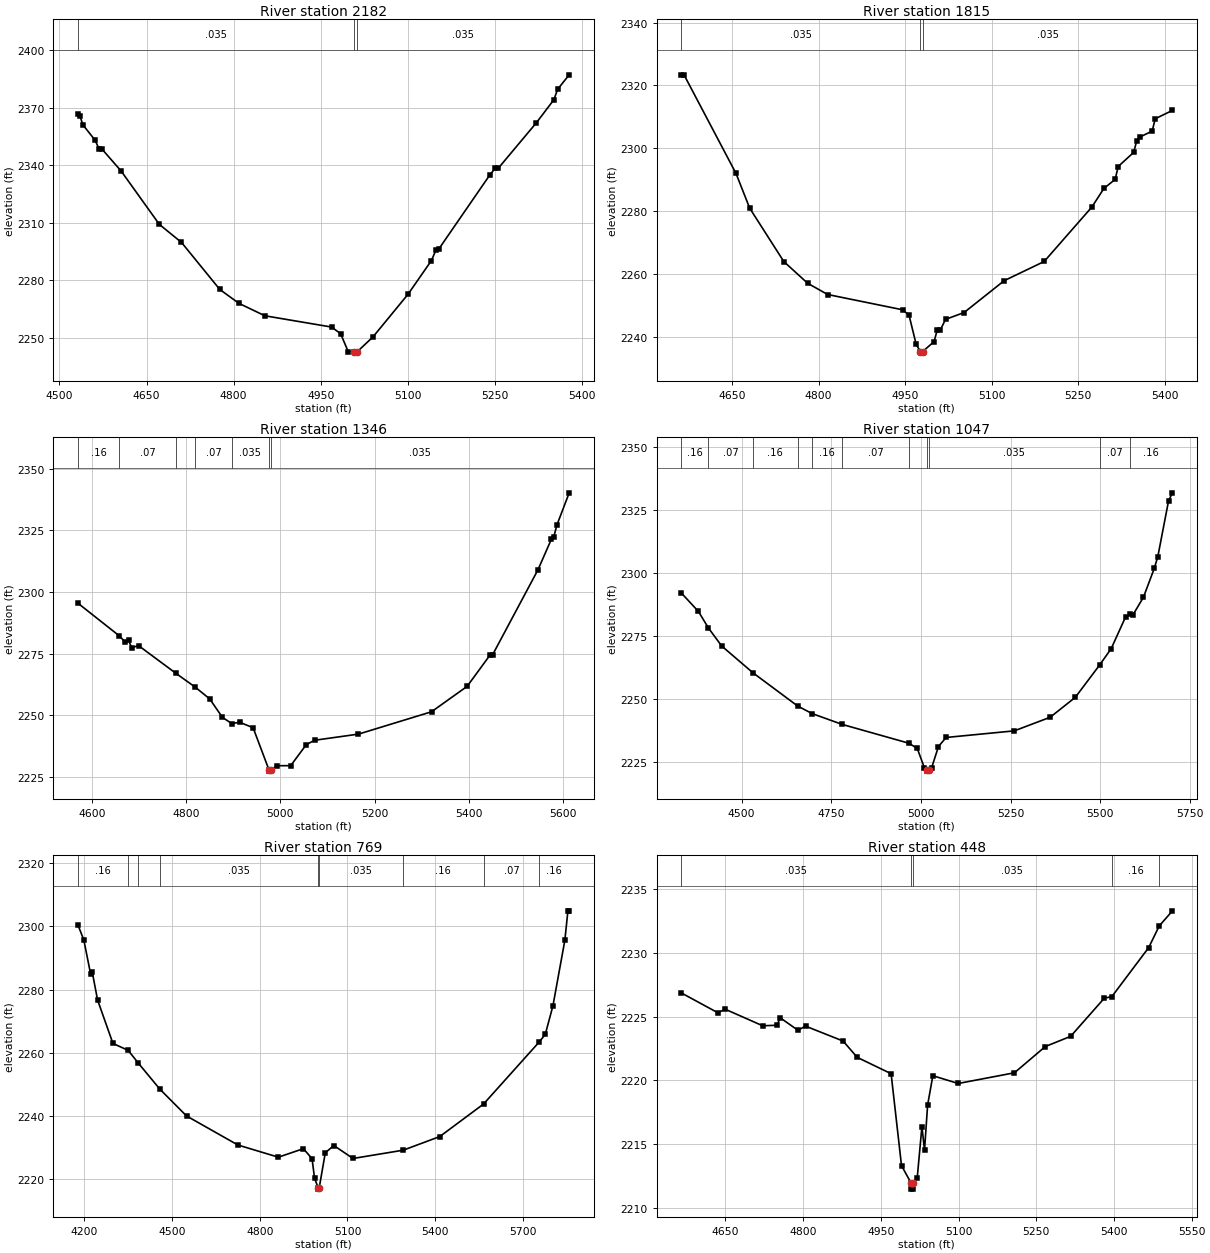
Type RM Length L Ch R = 1 ,2182    ,367,367,367
BEGIN DESCRIPTION:
NUBIA CREEK TRIBUTARY 4 3.0
END DESCRIPTION:
XS GIS Cut Line= 3
       1480556.9      6797802.12      1481004.98      6797937.54
      1481381.23       6797901.2
#Sta/Elev= 30
  4531.9 2366.69    4535  2365.9  4540.4 2361.06  4561.3  2353.1    4568 2348.71
  4573.2 2348.45  4606.2 2337.03  4672.1 2309.19  4710.2 2299.82  4776.2  2275.3
  4809.1 2268.08  4853.8  2261.6  4968.7 2255.72  4984.3 2252.27  4997.4 2242.87
  5008.1 2242.64  5008.3 2242.14  5012.1 2242.64  5040.2 2250.65  5100.5 2272.86
  5140.7 2290.37  5148.5 2295.85  5153.5 2296.42  5241.1 2334.89  5250.7 2338.49
  5255.7  2338.4  5321.5 2362.17  5351.6 2374.16    5358 2379.59    5378 2387.13
#Mann= 3 ,-1 , 0
  4531.9    .035       0  5008.1    .035       0  5012.1    .035       0
Bank Sta=5008.1,5012.1
XS Rating Curve= 0 ,0
Exp/Cntr=0.3,0.1

Type RM Length L Ch R = 1 ,1815    ,469,469,469
BEGIN DESCRIPTION:
Mapping XS e2b2b372
END DESCRIPTION:
XS GIS Cut Line= 3
      1480601.17      6798106.81      1481010.03      6798278.69
      1481398.07      6798153.68
#Sta/Elev= 30
    4562 2323.37  4566.8 2323.37  4656.9 2291.98  4680.6 2280.94  4739.7 2263.96
    4781 2257.05  4815.7 2253.47  4945.8  2248.6  4956.7 2246.89    4969 2237.65
  4976.4 2235.32  4976.6 2234.82  4980.4 2235.32  5000.1  2238.5  5005.5 2242.15
  5010.8 2242.15    5020 2245.56  5052.1 2247.74  5121.5 2257.86  5190.9 2263.98
  5273.4 2281.28  5294.4 2287.23  5313.9 2290.11  5319.1  2294.2  5345.9 2298.68
  5351.2 2302.32  5357.4 2303.65    5378 2305.46  5383.3 2309.39  5413.2 2312.06
#Mann= 3 ,-1 , 0
    4562    .035       0  4976.4    .035       0  4980.4    .035       0
Bank Sta=4976.4,4980.4
XS Rating Curve= 0 ,0
Exp/Cntr=0.3,0.1

Type RM Length L Ch R = 1 ,1346    ,299,299,299
BEGIN DESCRIPTION:
Mapping XS dd29e2a9
END DESCRIPTION:
XS GIS Cut Line= 4
      1480416.25      6798377.62      1480765.23      6798627.64
      1480903.26      6798669.31      1481370.97      6798705.69
#Sta/Elev= 30
  4570.4 2295.42  4658.4 2282.14  4669.5 2279.89    4678 2280.37  4684.2 2277.35
  4698.9 2278.24  4777.7 2267.07  4819.6 2261.33    4850 2256.61    4877 2249.12
    4897  2246.6  4913.3 2247.16  4942.1 2244.92  4975.8 2227.82    4976 2227.32
  4979.8 2227.82  4992.5 2229.51  5021.9 2229.54  5054.9 2238.05  5072.6 2239.84
  5165.7 2242.33  5320.8  2251.4  5396.4 2261.71  5445.4 2274.51  5450.5 2274.54
  5546.8 2309.02  5575.1 2321.36  5580.1 2322.25    5587 2327.19    5613  2340.2
#Mann= 7 ,-1 , 0
  4570.4     .16       0  4658.4     .07       0  4777.7     .16       0
  4819.6     .07       0    4897    .035       0  4975.8    .035       0
  4979.8    .035       0
Bank Sta=4975.8,4979.8
XS Rating Curve= 0 ,0
Exp/Cntr=0.3,0.1

Type RM Length L Ch R = 1 ,1047    ,278,278,278
BEGIN DESCRIPTION:
Mapping XS f40a0412
END DESCRIPTION:
XS GIS Cut Line= 4
      1480262.63      6798453.17      1480590.76      6798898.48
      1480830.34      6798919.31      1481405.82      6798929.73
#Sta/Elev= 30
    4332 2292.02  4379.8 2284.67  4407.8 2278.08  4444.6 2270.95    4532 2260.29
  4656.1 2247.14  4696.3 2244.13  4780.3 2239.82  4966.9 2232.32  4989.8 2230.26
  5009.9 2222.52  5017.9 2221.76  5018.1 2221.26  5021.9 2221.76  5029.9 2222.59
  5048.9 2231.03  5070.1 2234.62  5260.3 2237.25  5360.3 2242.65  5430.3 2250.55
  5497.8 2263.33  5530.4  2269.9  5570.4 2282.47  5582.2 2283.52  5590.4 2283.15
  5620.4 2290.34  5650.4 2301.75  5660.4 2306.47  5690.4 2328.69  5701.2 2331.76
#Mann= 11 ,-1 , 0
    4332     .16       0  4407.8     .07       0    4532     .16       0
  4656.1     .07       0  4696.3     .16       0  4780.3     .07       0
  4966.9    .035       0  5017.9    .035       0  5021.9    .035       0
  5497.8     .07       0  5582.2     .16       0
Bank Sta=5017.9,5021.9
XS Rating Curve= 0 ,0
Exp/Cntr=0.3,0.1

Type RM Length L Ch R = 1 ,769     ,321,321,321
BEGIN DESCRIPTION:
Mapping XS 4308a211
END DESCRIPTION:
XS GIS Cut Line= 4
      1480202.75       6798453.2      1480473.57      6799083.37
      1480702.73      6799205.77      1481408.45      6799000.04
#Sta/Elev= 30
  4177.8 2300.44  4197.8 2295.73  4221.3 2284.83  4226.7 2285.54  4244.9 2276.73
  4297.4 2263.01  4349.7  2260.8    4383 2256.92  4457.6 2248.58  4549.2 2240.07
  4724.9 2230.88  4863.5 2227.02  4949.1 2229.72  4978.7 2226.55  4987.3 2220.36
  4999.4 2217.42  4999.6 2216.92  5003.4 2217.42    5024 2228.42  5053.2 2230.71
    5119 2226.62  5290.4 2229.23  5415.8 2233.55  5565.7 2243.85  5756.1 2263.48
  5776.7 2265.88  5802.9 2274.88  5843.7 2295.62  5854.2 2304.95  5858.6 2304.95
#Mann= 9 ,-1 , 0
  4177.8     .16       0  4349.7     .07       0    4383     .16       0
  4457.6    .035       0  4999.4    .035       0  5003.4    .035       0
  5290.4     .16       0  5565.7     .07       0  5756.1     .16       0
Bank Sta=4999.4,5003.4
XS Rating Curve= 0 ,0
Exp/Cntr=0.3,0.1

Type RM Length L Ch R = 1 ,448     ,334,334,334
BEGIN DESCRIPTION:
Mapping XS 0b744e5b
END DESCRIPTION:
XS GIS Cut Line= 4
      1480441.14      6799076.26      1480536.62      6799429.96
      1480688.53      6799449.49      1481087.83      6799293.24
#Sta/Elev= 30
  4564.7 2226.86  4635.4  2225.3  4649.4 2225.58  4721.9 2224.28    4750 2224.32
  4755.2 2224.92  4789.9 2223.93  4804.7 2224.25  4877.2 2223.08  4904.4  2221.8
  4969.8 2220.52  4989.9  2213.3  5008.1 2211.96  5008.3 2211.46  5011.8 2211.46
  5012.1 2211.96  5020.2 2212.33  5029.3 2216.37  5034.3 2214.51  5040.3 2218.06
  5050.4 2220.36  5099.3 2219.75  5207.9 2220.59  5267.5 2222.65  5316.4 2223.45
  5381.5 2226.45  5395.8 2226.56    5467 2230.41  5487.5 2232.12    5513  2233.3
#Mann= 5 ,-1 , 0
  4564.7    .035       0  5008.1    .035       0  5012.1    .035       0
  5395.8     .16       0  5487.5     .07       0
Bank Sta=5008.1,5012.1
XS Rating Curve= 0 ,0
Exp/Cntr=0.3,0.1

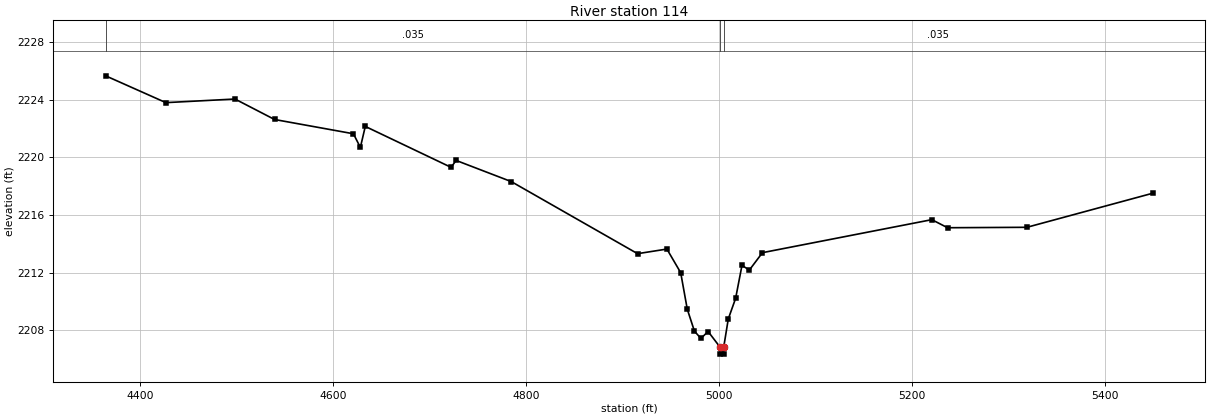
Type RM Length L Ch R = 1 ,114     ,0,0,0
BEGIN DESCRIPTION:
Mapping XS 3f7a1f3f
END DESCRIPTION:
XS GIS Cut Line= 4
      1480434.62      6799136.96      1480554.34      6799699.42
      1480636.81      6799772.11      1480990.09      6799584.08
#Sta/Elev= 30
  4364.3 2225.66  4426.7  2223.8  4498.3 2224.05  4539.3 2222.63    4621 2221.64
  4628.2 2220.69  4633.3 2222.15  4722.2 2219.31  4727.4 2219.79  4784.6 2218.32
  4915.4 2213.32  4945.8 2213.64  4960.1    2212  4966.9 2209.47  4974.3 2207.95
    4981 2207.44  4988.5 2207.92  5000.7 2206.85    5001 2206.35  5004.5 2206.35
  5004.7 2206.85  5009.4 2208.79    5017 2210.22  5023.6 2212.51  5031.2 2212.18
  5044.8 2213.39  5220.3 2215.68  5236.6 2215.12  5318.8 2215.15  5449.5 2217.52
#Mann= 3 ,-1 , 0
  4364.3    .035       0  5000.7    .035       0  5004.7    .035       0
Bank Sta=5000.7,5004.7
XS Rating Curve= 0 ,0
Exp/Cntr=0.3,0.1

Chan Stop Cuts=-1
Use User Specified Reach Order=0
Composite Channel Slope=5