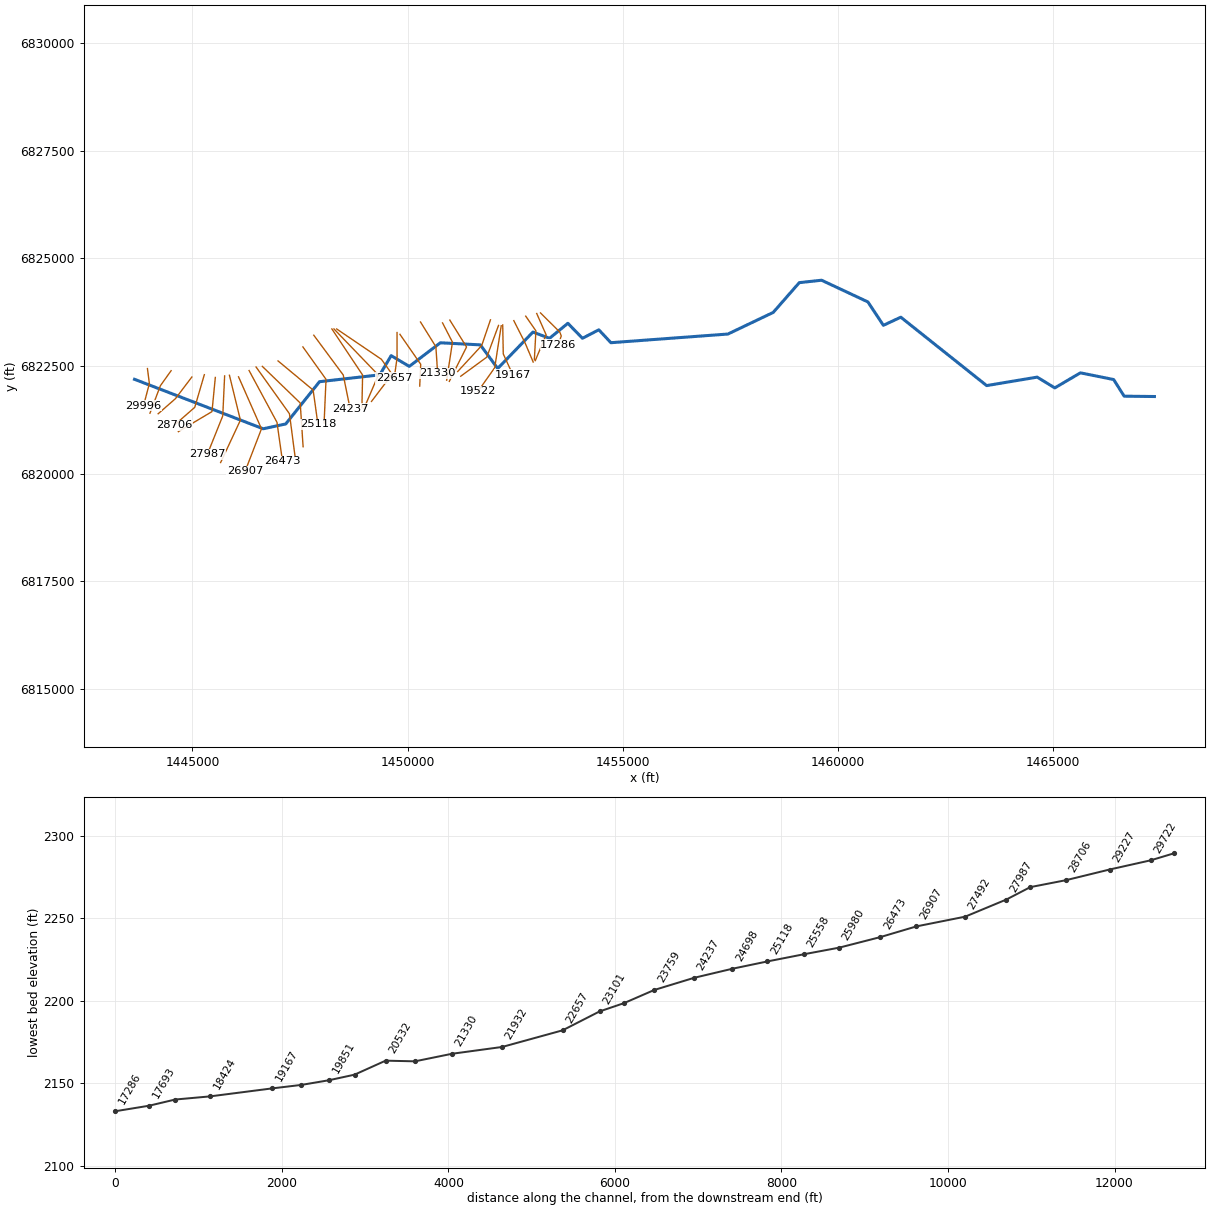
--- WEAVER SPRINGS CREEK.prj (project) ---

Proj Title=WEAVER SPRINGS CREEK Base Level Engineering
Current Plan=p01
Default Exp/Contr=0.3,0.1
English Units
Geom File=g01
Flow File=f01
Plan File=p01
Y Axis Title=Elevation
X Axis Title(PF)=Main Channel Distance
X Axis Title(XS)=Station
BEGIN DESCRIPTION:
WEAVER SPRINGS CREEK
END DESCRIPTION:
DSS Export Rating Curves= 0
DSS Export Rating Curve Sorted= 0
DSS Export Volume Flow Curves= 0
DXF OffsetX= 0
DXF OffsetY= 0
DXF ScaleX= 1
DXF ScaleY= 10

--- WEAVER SPRINGS CREEK.p01 (plan) ---

Plan Title=Multiple Run
Short Identifier=Multiple
Geom File=g01
Flow File=f01
Subcritical Flow
K Sum by GR= 0
Std Step Tol= 0.01
Critical Tol= 0.01
Num of Std Step Trials= 20
Max Error Tol= 0.3
Flow Tol Ratio= 0.001
Split Flow NTrial= 30
Split Flow Tol= 0.02
Split Flow Ratio= 0.02
Log Output Level= 0
Friction Slope Method= 1
Unsteady Friction Slope Method= 2
Unsteady Bridges Friction Slope Method= 1
Parabolic Critical Depth
Global Vel Dist=  1 , 1 , 1
Global Log Level= 0
CheckData=True
Encroach Param= -1, 0, 0, 0
BEGIN DESCRIPTION:
Multiple Run
END DESCRIPTION:

--- WEAVER SPRINGS CREEK.f01 (steady flow) ---

Flow Title=Multiple
Program Version=4.10
Number of Profiles= 7
Profile Names=10-year,25-year,50-year,1pct_min,100-year,1pct_plu,500-year
River Rch & RM=WEAVER SPRINGS C,Reach-1         ,29996
     520     766     983     627    1251    2495    2051
River Rch & RM=WEAVER SPRINGS C,Reach-1         ,26473
     574     849    1092     698    1394    2781    2297
River Rch & RM=WEAVER SPRINGS C,Reach-1         ,22657
     963    1460    1906    1235    2465    4918    4174
River Rch & RM=WEAVER SPRINGS C,Reach-1         ,15513
    1652    2546    3361    2198    4386    8752    7567
River Rch & RM=WEAVER SPRINGS C,Reach-1         ,13447
    1712    2642    3491    2284    4557    9093    7871
River Rch & RM=WEAVER SPRINGS C,Reach-1         ,11578
    2643    4133    5512    3636    7255   14477   12732
River Rch & RM=WEAVER SPRINGS C,Reach-1         ,2381
    2698    4218    5625    3710    7403   14770   12985
Boundary for River Rch & Prof#=WEAVER SPRINGS C,Reach-1         , 1
Up Type= 0
Dn Type= 3
Dn Slope=0.00479
Boundary for River Rch & Prof#=WEAVER SPRINGS C,Reach-1         , 2
Up Type= 0
Dn Type= 3
Dn Slope=0.00479
Boundary for River Rch & Prof#=WEAVER SPRINGS C,Reach-1         , 3
Up Type= 0
Dn Type= 3
Dn Slope=0.00479
Boundary for River Rch & Prof#=WEAVER SPRINGS C,Reach-1         , 4
Up Type= 0
Dn Type= 3
Dn Slope=0.00479
Boundary for River Rch & Prof#=WEAVER SPRINGS C,Reach-1         , 5
Up Type= 0
Dn Type= 3
Dn Slope=0.00479
Boundary for River Rch & Prof#=WEAVER SPRINGS C,Reach-1         , 6
Up Type= 0
Dn Type= 3
Dn Slope=0.00479
Boundary for River Rch & Prof#=WEAVER SPRINGS C,Reach-1         , 7
Up Type= 0
Dn Type= 3
Dn Slope=0.00479
DSS Import GetInterval= 0
DSS Import GetPeak= 0
DSS Import FillOption= 0

--- WEAVER SPRINGS CREEK.g01 (geometry) ---

Geom Title=Existing Conditions
Program Version=4.10

River Reach=WEAVER SPRINGS C,Reach-1
Reach XY= 30
        1443655.        6822188.      1446644.71      6821039.01
      1447168.73      6821151.16      1447952.69      6822132.18
      1449353.54      6822291.54      1449617.93      6822736.96
      1450039.78      6822488.24      1450760.87      6823035.96
      1451689.98      6822987.68      1452094.51      6822438.93
        1452913.      6823285.02      1453299.14      6823140.06
      1453725.06      6823488.52      1454063.51      6823140.57
      1454443.96      6823337.32      1454724.87      6823037.91
       1457444.5       6823239.2       1458496.7      6823741.07
      1459102.42      6824432.29      1459620.26      6824488.52
      1460696.69      6823984.91      1461056.56      6823441.42
      1461461.34      6823629.98      1463456.55      6822041.75
      1464630.12       6822238.3       1465039.8      6821988.48
      1465634.97      6822337.93      1466407.47      6822182.55
      1466651.57      6821795.79        1467355.        6821788.

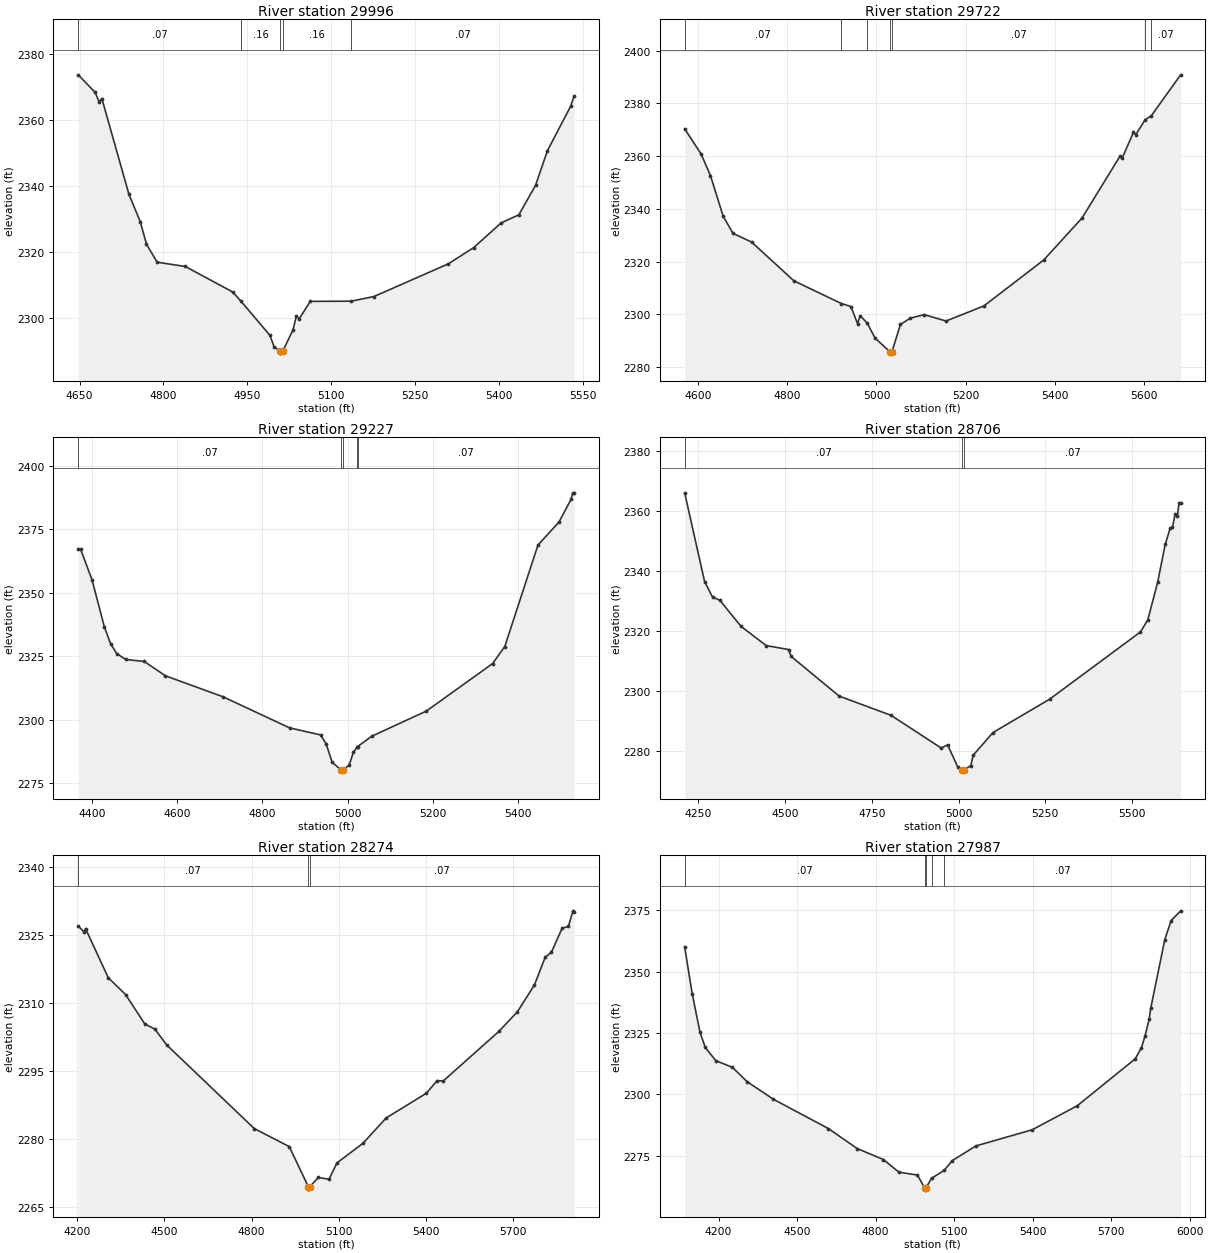
Type RM Length L Ch R = 1 ,29996   ,274,274,274
BEGIN DESCRIPTION:
WEAVER SPRINGS CREEK 57.0
END DESCRIPTION:
XS GIS Cut Line= 3
        1443955.      6822437.97      1443999.82      6822088.44
      1443863.48      6821571.93
#Sta/Elev= 30
  4647.6 2373.59  4677.8 2368.29  4684.9 2365.43  4689.9 2366.41  4738.3 2337.46
  4758.5 2329.21  4769.6 2322.41  4788.7 2316.95  4839.1 2315.66  4923.8 2307.94
  4938.9 2305.11  4990.4 2294.83  4997.7  2291.4  5008.7 2289.97  5008.9 2289.47
  5012.9 2289.97  5031.5 2296.44  5037.6 2300.63  5042.7 2299.85  5062.5 2305.11
  5135.7 2305.17  5176.3 2306.58  5309.2 2316.45  5354.6 2321.37  5403.8 2328.85
  5435.2 2331.26  5465.1 2340.14  5486.5  2350.7  5527.9 2364.06  5534.2  2367.2
#Mann= 5 ,-1 , 0
  4647.6     .07       0  4938.9     .16       0  5008.7     .07       0
  5012.9     .16       0  5135.7     .07       0
Bank Sta=5008.7,5012.9
XS Rating Curve= 0 ,0
Exp/Cntr=0.3,0.1

Type RM Length L Ch R = 1 ,29722   ,495,495,495
BEGIN DESCRIPTION:
WEAVER SPRINGS CREEK 56.0
END DESCRIPTION:
XS GIS Cut Line= 3
      1444505.02      6822388.03      1444255.32      6822038.33
      1444013.62      6821401.24
#Sta/Elev= 30
  4570.3  2370.3  4607.2 2360.75  4628.1 2352.57  4656.4 2337.25  4678.5 2330.69
  4720.3  2327.4  4814.9 2312.71  4921.4  2304.1  4942.7 2302.96  4957.5 2296.52
  4963.6 2299.47  4979.1 2296.71  4997.1 2290.95  5030.3  2285.8  5030.6  2285.3
  5034.6  2285.8  5053.8 2296.19    5076 2298.56  5107.3 2299.89  5155.7 2297.47
  5240.8 2303.19  5374.7  2320.6  5460.3 2336.46  5545.6 2359.95  5550.9 2359.41
  5575.7 2368.95  5581.1 2368.15  5602.1 2373.82  5615.5 2375.21  5681.4 2390.79
#Mann= 7 ,-1 , 0
  4570.3     .07       0  4921.4     .16       0  4979.1     .07       0
  5030.3     .07       0  5034.6     .07       0  5602.1     .16       0
  5615.5     .07       0
Bank Sta=5030.3,5034.6
XS Rating Curve= 0 ,0
Exp/Cntr=0.3,0.1

Type RM Length L Ch R = 1 ,29227   ,521,521,521
BEGIN DESCRIPTION:
WEAVER SPRINGS CREEK 55.0
END DESCRIPTION:
XS GIS Cut Line= 3
      1444987.37      6822241.52        1444605.        6821738.
      1444204.97      6821387.97
#Sta/Elev= 30
    4368 2367.22  4373.4 2367.22  4400.3 2355.18  4429.4 2336.52  4443.9 2329.97
  4458.4 2326.04  4479.3 2323.72  4522.9 2322.91  4572.8 2317.26    4708 2308.99
  4864.1 2296.75  4936.8 2293.97    4950 2290.37  4963.9 2283.22  4984.5  2280.2
  4984.8  2279.7  4988.8  2280.2  5003.6 2281.99    5014 2287.21  5022.9 2289.18
  5023.8 2289.39  5056.7 2293.45  5184.9 2303.36  5340.5  2322.1    5369 2328.82
  5446.8 2368.77  5496.2 2377.87  5524.6 2386.85  5528.4 2389.39  5531.8 2389.39
#Mann= 5 ,-1 , 0
    4368     .07       0  4984.5     .07       0  4988.8     .07       0
  5022.9     .16       0  5023.8     .07       0
Bank Sta=4984.5,4988.8
XS Rating Curve= 0 ,0
Exp/Cntr=0.3,0.1

Type RM Length L Ch R = 1 ,28706   ,432,432,432
BEGIN DESCRIPTION:
WEAVER SPRINGS CREEK 54.0
END DESCRIPTION:
XS GIS Cut Line= 3
        1445277.      6822295.06      1445054.86      6821537.67
      1444573.08      6821116.84
#Sta/Elev= 30
  4210.7 2365.96    4268 2336.41    4291 2331.21  4311.9 2330.19  4373.4 2321.45
  4445.4 2315.09  4509.9 2313.76  4517.4 2311.48  4655.8 2298.25  4805.5 2291.84
  4949.5 2280.98  4968.4 2281.97  4997.2 2274.76  5011.2 2273.76  5011.5 2273.26
  5015.6 2273.76  5035.3 2275.08  5041.9 2278.54  5098.9  2286.1  5262.1 2297.21
  5524.1 2319.63    5545 2323.59  5573.5 2336.15  5595.3 2348.75  5609.5 2354.16
  5616.2 2354.47  5623.8  2358.8  5630.4 2358.27  5635.1 2362.66  5639.7 2362.66
#Mann= 3 ,-1 , 0
  4210.7     .07       0  5011.2     .07       0  5015.6     .07       0
Bank Sta=5011.2,5015.6
XS Rating Curve= 0 ,0
Exp/Cntr=0.3,0.1

Type RM Length L Ch R = 1 ,28274   ,287,287,287
BEGIN DESCRIPTION:
WEAVER SPRINGS CREEK 53.0
END DESCRIPTION:
XS GIS Cut Line= 3
       1445532.2       6822230.8        1445455.        6821438.
      1444673.57      6820972.56
#Sta/Elev= 30
  4203.5 2326.98  4223.8 2325.63  4228.8  2326.4  4306.8 2315.59  4367.1 2311.83
  4432.5  2305.4  4467.5 2304.25  4507.7 2300.79  4809.2 2282.35  4929.7 2278.37
  4995.3 2269.51  4995.6 2269.01  4999.7 2269.51  5029.3 2271.58  5066.3 2271.18
  5093.5 2274.77  5183.1 2279.11  5262.9 2284.69  5401.1 2290.13  5438.1  2292.9
  5459.5 2292.85  5650.4 2303.74  5714.6  2308.1    5773    2314    5810 2320.09
  5831.4  2321.2  5868.4 2326.51  5889.8 2326.87  5905.4 2330.32  5909.6 2330.04
#Mann= 3 ,-1 , 0
  4203.5     .07       0  4995.3     .07       0  4999.7     .07       0
Bank Sta=4995.3,4999.7
XS Rating Curve= 0 ,0
Exp/Cntr=0.3,0.1

Type RM Length L Ch R = 1 ,27987   ,495,495,495
BEGIN DESCRIPTION:
WEAVER SPRINGS CREEK 52.0
END DESCRIPTION:
XS GIS Cut Line= 3
      1445748.49      6822266.53        1445705.      6821337.85
      1445345.24      6820441.99
#Sta/Elev= 30
  4070.3 2360.03  4098.9 2341.08  4128.9 2325.29  4148.9 2319.15    4189 2313.79
  4252.9 2311.03  4309.1  2305.2  4409.2 2298.07  4619.4 2286.14  4729.6    2278
  4829.7 2273.54  4888.9 2268.38  4959.8 2267.21  4987.3 2261.99  4987.7 2261.49
  4992.3 2261.99  5013.6  2265.9  5061.4 2269.07  5092.7 2273.09    5183 2279.06
  5398.6 2285.65    5571 2295.45  5791.8  2314.5  5815.9 2319.07  5829.6  2323.9
  5845.5 2330.78  5851.2 2335.12    5905 2363.01  5928.9 2370.72  5965.4 2374.73
#Mann= 5 ,-1 , 0
  4070.3     .07       0  4987.3     .07       0  4992.3     .07       0
  5013.6     .16       0  5061.4     .07       0
Bank Sta=4987.3,4992.3
XS Rating Curve= 0 ,0
Exp/Cntr=0.3,0.1

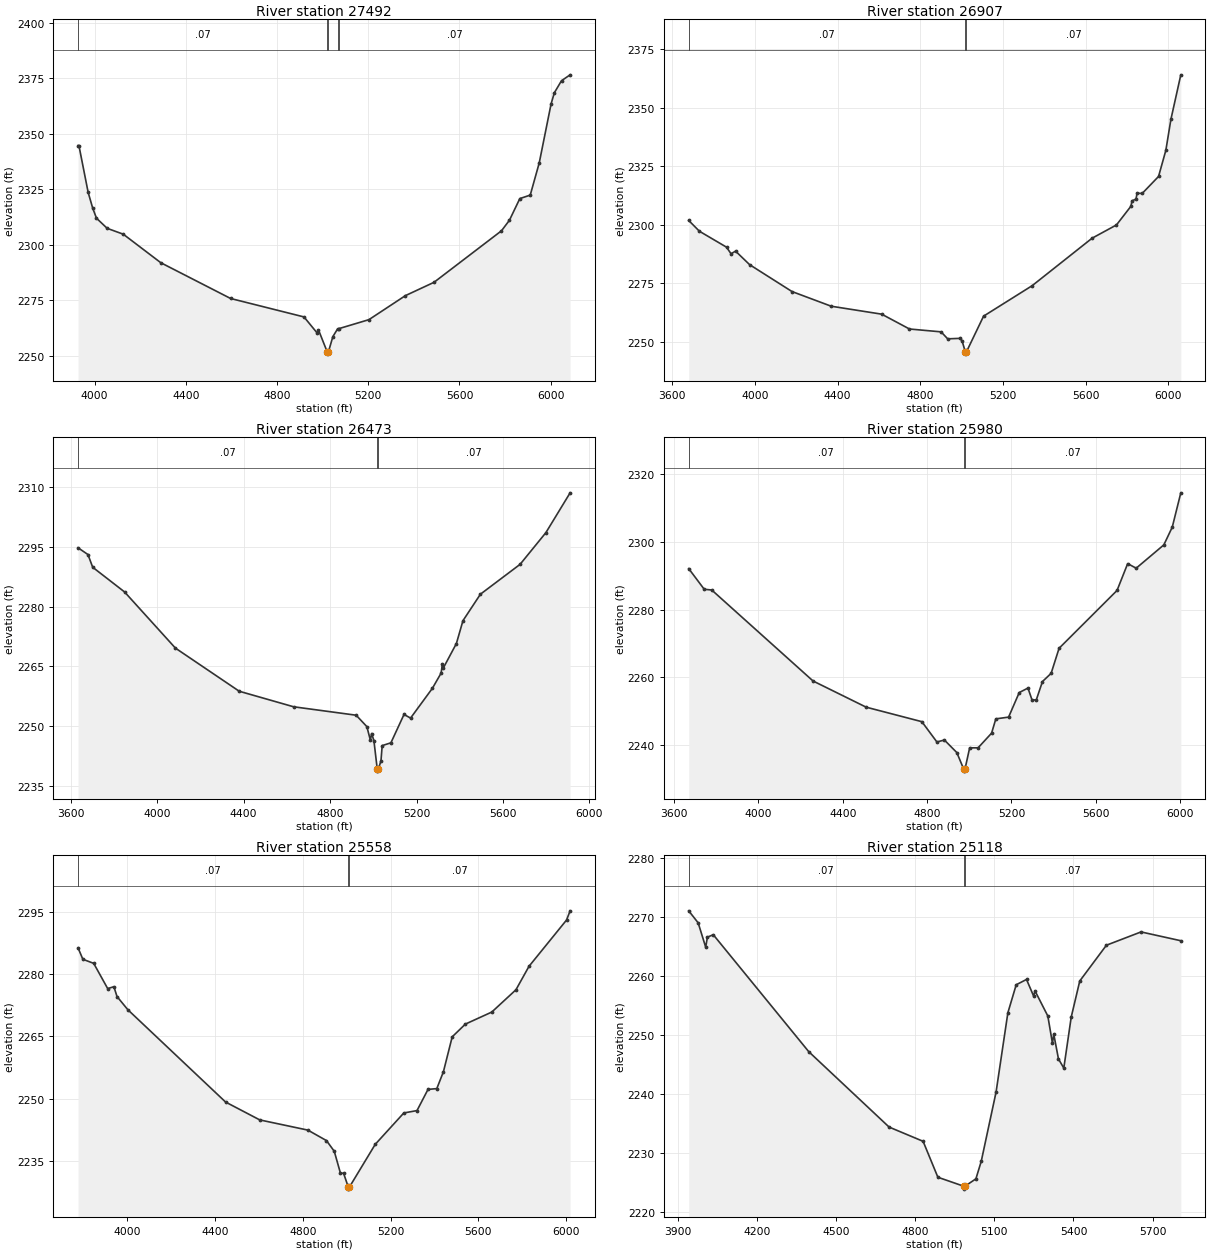
Type RM Length L Ch R = 1 ,27492   ,585,585,585
BEGIN DESCRIPTION:
WEAVER SPRINGS CREEK 51.0
END DESCRIPTION:
XS GIS Cut Line= 3
      1445860.55       6822280.8      1446115.23      6821238.46
      1445655.63      6820255.28
#Sta/Elev= 30
    3927  2344.6    3931  2344.6  3971.5  2323.5  3991.6 2316.36    4008 2311.89
  4054.8 2307.33  4125.5 2304.68  4290.2 2291.82  4596.3 2275.71  4918.1  2267.4
  4976.4 2260.09  4981.5  2261.6  5020.1 2251.59  5020.5 2251.09  5025.1 2251.59
  5044.7 2258.54  5065.6 2262.02    5070 2262.09    5203 2266.18  5362.9    2277
  5488.2 2282.99  5784.3 2306.22  5819.1 2310.96  5864.7 2320.73  5910.4  2322.3
  5949.8 2336.79  6001.8 2363.38  6016.1 2368.42  6047.5 2373.84  6085.3  2376.5
#Mann= 5 ,-1 , 0
    3927     .07       0  5020.1     .07       0  5025.1     .07       0
  5065.6     .16       0    5070     .07       0
Bank Sta=5020.1,5025.1
XS Rating Curve= 0 ,0
Exp/Cntr=0.3,0.1

Type RM Length L Ch R = 1 ,26907   ,434,434,434
BEGIN DESCRIPTION:
WEAVER SPRINGS CREEK 50.0
END DESCRIPTION:
XS GIS Cut Line= 3
      1446072.16      6822245.37        1446605.        6821038.
      1446223.18      6820047.46
#Sta/Elev= 30
  3679.8 2301.88  3731.6 2297.27  3862.7 2290.47  3884.6 2287.65  3906.5 2288.77
  3974.6 2282.99  4179.7  2271.5  4369.5 2265.23  4613.6 2261.84  4748.1  2255.5
  4901.1 2254.28    4933  2251.3  4990.6 2251.49  5002.2 2250.56  5018.4 2245.69
  5018.8 2245.19  5023.5 2245.69  5106.7 2260.99  5342.1 2274.03  5631.8  2294.3
  5749.7 2299.96  5819.6 2307.94  5824.9 2310.24  5844.2 2311.03  5849.5 2313.53
  5874.2 2313.42  5953.4 2320.68  5988.7 2331.86  6013.3 2345.14  6061.1 2364.11
#Mann= 3 ,-1 , 0
  3679.8     .07       0  5018.4     .07       0  5023.5     .07       0
Bank Sta=5018.4,5023.5
XS Rating Curve= 0 ,0
Exp/Cntr=0.3,0.1

Type RM Length L Ch R = 1 ,26473   ,493,493,493
BEGIN DESCRIPTION:
WEAVER SPRINGS CREEK 49.0
END DESCRIPTION:
XS GIS Cut Line= 3
      1446316.94      6822391.23      1446965.05      6821188.77
      1447092.97       6820287.1
#Sta/Elev= 30
    3634 2294.78    3680 2293.08  3701.9 2289.89  3849.5 2283.68  4084.7 2269.58
  4379.9 2258.75  4631.4 2254.85  4920.9 2252.73  4970.4 2249.86  4986.6 2246.45
  4992.3 2248.13  5002.9 2246.37  5018.4 2239.19  5018.8 2238.69  5023.6 2239.19
  5035.7 2241.31  5041.2  2245.1  5081.6  2245.8  5142.2 2252.92  5172.5 2252.01
  5273.5 2259.49  5313.9 2263.31  5319.5 2265.54  5324.5 2264.63  5384.6 2270.74
  5414.9 2276.47  5495.7 2283.12  5679.2 2290.62  5798.7 2298.59  5910.7 2308.58
#Mann= 3 ,-1 , 0
    3634     .07       0  5018.4     .07       0  5023.6     .07       0
Bank Sta=5018.4,5023.6
XS Rating Curve= 0 ,0
Exp/Cntr=0.3,0.1

Type RM Length L Ch R = 1 ,25980   ,422,422,422
BEGIN DESCRIPTION:
WEAVER SPRINGS CREEK 48.0
END DESCRIPTION:
XS GIS Cut Line= 3
      1446478.42      6822474.52        1447255.        6821388.
      1447384.65      6820398.17
#Sta/Elev= 30
  3669.6 2292.14  3743.2 2286.03  3778.8 2285.82  4259.3 2258.93  4511.1  2251.2
  4775.3 2246.91  4846.6 2240.92  4882.2 2241.49  4941.2 2237.78  4974.3  2232.8
  4974.7  2232.3  4979.5  2232.8    5002 2239.18    5042 2239.19    5106 2243.52
  5126.1 2247.74  5186.7 2248.26  5237.1 2255.52  5278.5 2256.84  5297.6 2253.37
  5317.8 2253.31  5347.3 2258.77  5388.4  2261.2  5426.1  2268.6    5701 2285.69
  5751.4 2293.61  5791.8 2292.26  5922.9 2299.15  5962.9  2304.4  6003.4 2314.53
#Mann= 3 ,-1 , 0
  3669.6     .07       0  4974.3     .07       0  4979.5     .07       0
Bank Sta=4974.3,4979.5
XS Rating Curve= 0 ,0
Exp/Cntr=0.3,0.1

Type RM Length L Ch R = 1 ,25558   ,440,440,440
BEGIN DESCRIPTION:
WEAVER SPRINGS CREEK 47.0
END DESCRIPTION:
XS GIS Cut Line= 3
      1446624.24      6822488.43        1447505.        6821638.
      1447572.06      6820621.73
#Sta/Elev= 30
  3775.6 2286.29  3797.7 2283.53  3847.1 2282.55  3910.8 2276.49  3939.1 2276.94
  3953.3 2274.58  4002.7 2271.41  4448.2 2249.23  4603.9 2244.94  4823.1 2242.49
    4908 2239.97  4943.5  2237.4  4971.7 2232.13  4985.9 2232.13  5007.3 2228.81
  5007.7 2228.31  5012.6 2228.81  5130.2 2239.07  5260.5 2246.61  5320.6 2247.18
  5370.7 2252.27  5410.8 2252.46  5440.9  2256.5    5481  2264.9  5541.1 2267.96
  5661.4 2270.85  5771.6 2276.21    5831 2281.84  6002.1 2292.96  6018.4 2295.17
#Mann= 3 ,-1 , 0
  3775.6     .07       0  5007.3     .07       0  5012.6     .07       0
Bank Sta=5007.3,5012.6
XS Rating Curve= 0 ,0
Exp/Cntr=0.3,0.1

Type RM Length L Ch R = 1 ,25118   ,420,420,420
BEGIN DESCRIPTION:
WEAVER SPRINGS CREEK 46.0
END DESCRIPTION:
XS GIS Cut Line= 3
      1446990.58      6822614.29        1447805.        6821938.
       1447917.5      6821138.69
#Sta/Elev= 30
  3941.1 2271.03  3976.9    2269  4005.5 2264.88    4012 2266.57  4034.2 2266.99
  4396.2  2247.2  4700.9 2234.44  4829.8 2232.03  4885.8 2225.95  4983.4 2224.44
  4983.8 2223.94  4988.7 2224.44    5030 2225.68  5050.2 2228.64  5106.5 2240.37
  5151.2 2253.78  5182.8 2258.52  5221.9 2259.42    5249 2256.59    5254 2257.49
  5302.7 2253.23  5320.2 2248.62  5325.2 2250.15  5343.1 2245.96  5363.3 2244.42
  5391.4 2253.05  5423.8 2259.16  5524.8 2265.21  5656.1 2267.46  5806.9 2265.97
#Mann= 3 ,-1 , 0
  3941.1     .07       0  4983.4     .07       0  4988.7     .07       0
Bank Sta=4983.4,4988.7
XS Rating Curve= 0 ,0
Exp/Cntr=0.3,0.1

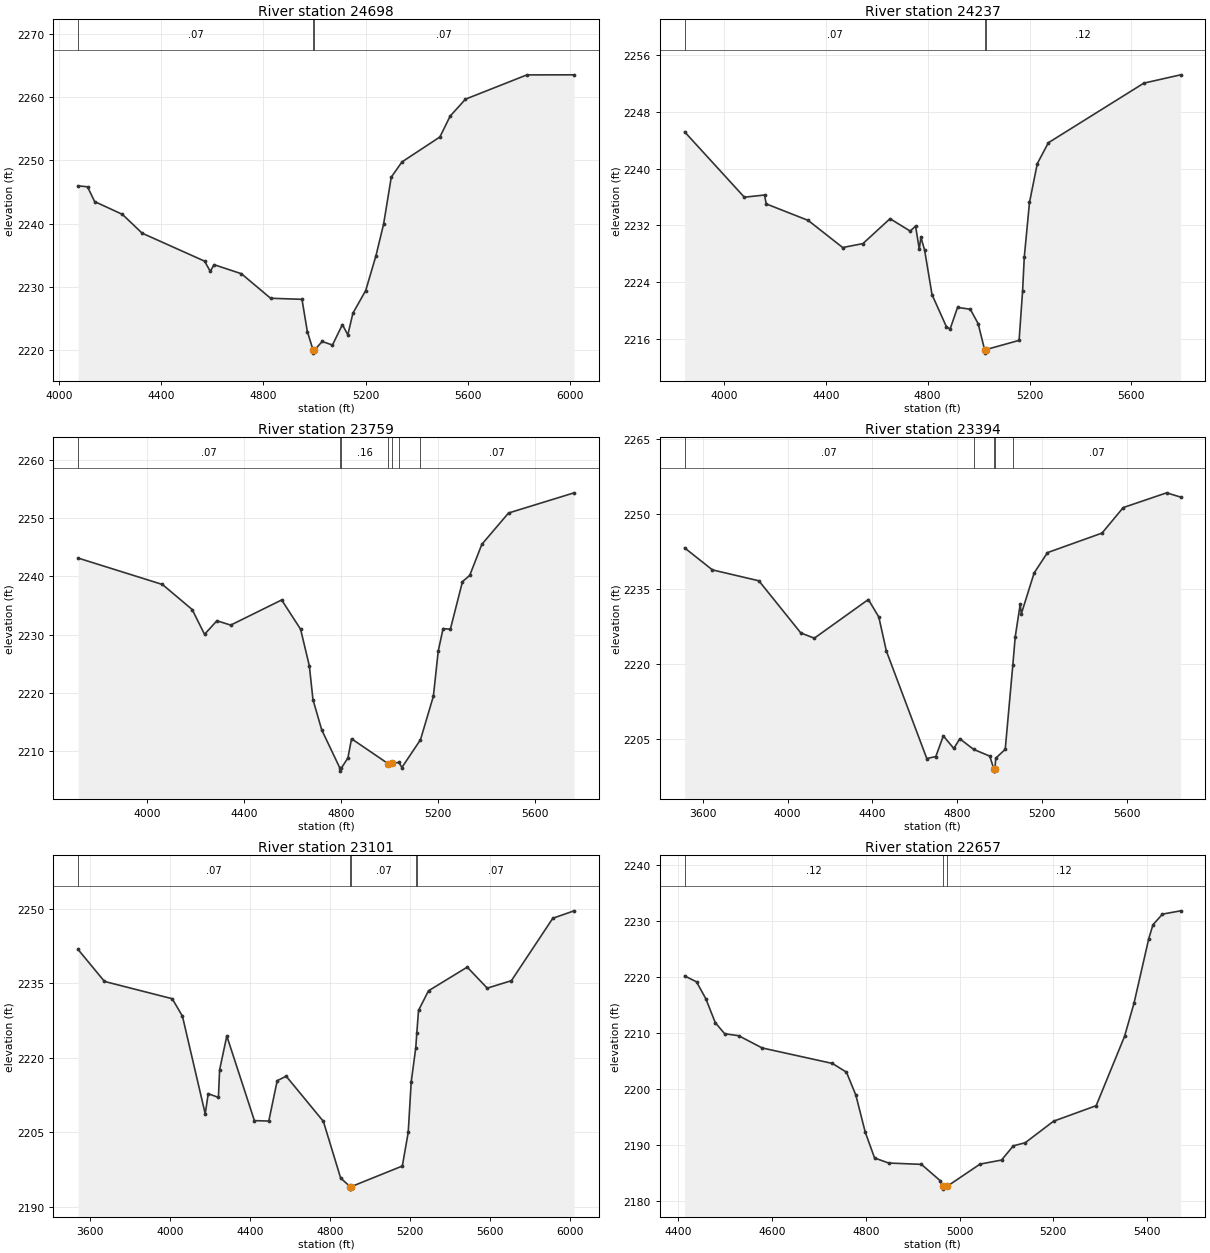
Type RM Length L Ch R = 1 ,24698   ,461,461,461
BEGIN DESCRIPTION:
WEAVER SPRINGS CREEK 45.0
END DESCRIPTION:
XS GIS Cut Line= 3
      1447566.93      6822940.71        1448105.        6822188.
        1448060.      6821173.45
#Sta/Elev= 30
  4074.8 2245.97  4111.7 2245.82  4139.6 2243.48  4248.1 2241.46  4325.5 2238.48
  4569.8 2234.06  4592.1 2232.44  4606.7  2233.5  4713.8 2232.07    4828 2228.19
  4950.9 2228.02  4971.8 2222.93  4994.2 2220.01  4994.7 2219.51  4999.7 2220.01
  5030.1 2221.35  5070.1 2220.79    5109 2224.02  5130.2  2222.4  5150.2 2225.83
  5200.2 2229.41  5240.3 2234.91  5270.3 2239.93  5300.3 2247.35    5342 2249.75
  5490.5  2253.7  5530.6    2257  5590.6 2259.68  5830.9 2263.52  6015.6 2263.53
#Mann= 3 ,-1 , 0
  4074.8     .07       0  4994.2     .07       0  4999.7     .07       0
Bank Sta=4994.2,4999.7
XS Rating Curve= 0 ,0
Exp/Cntr=0.3,0.1

Type RM Length L Ch R = 1 ,24237   ,478,478,478
BEGIN DESCRIPTION:
WEAVER SPRINGS CREEK 44.0
END DESCRIPTION:
XS GIS Cut Line= 3
      1447820.43      6823211.51        1448505.        6822288.
      1448664.15      6821506.72
#Sta/Elev= 30
  3846.2  2245.2  4080.7 2235.98    4160 2236.29  4166.3 2235.04  4331.1 2232.71
  4466.8 2228.88  4546.1 2229.44  4652.5 2232.95  4731.8  2231.2  4752.7 2231.91
  4767.3 2228.65  4773.5 2230.34  4788.1 2228.55  4817.4 2222.23  4873.7 2217.72
  4888.3 2217.39  4917.5 2220.44  4967.6 2220.18  4998.3 2218.15  5023.6 2214.49
  5024.1 2213.99  5029.1 2214.49  5159.1 2215.79  5172.7 2222.69  5179.5 2227.55
  5199.9 2235.24  5230.5 2240.71  5273.9 2243.66  5648.9 2252.07  5793.1 2253.24
#Mann= 3 ,-1 , 0
  3846.2     .07       0  5023.6     .07       0  5029.1     .12       0
#XS Ineff= 2 , 0
       0  4917.5 2220.44               0
Permanent Ineff=
       F       F
Bank Sta=5023.6,5029.1
XS Rating Curve= 0 ,0
Exp/Cntr=0.3,0.1

Type RM Length L Ch R = 1 ,23759   ,365,365,365
BEGIN DESCRIPTION:
WEAVER SPRINGS CREEK 43.0
END DESCRIPTION:
XS GIS Cut Line= 3
      1448240.53       6823357.4        1448955.        6822288.
      1448938.46       6821527.5
#Sta/Elev= 30
  3713.8 2243.14  4061.9 2238.61  4184.5 2234.32  4235.6 2230.07  4286.6 2232.39
  4343.7 2231.65  4553.9 2235.96    4632 2230.94    4668 2224.68  4683.1 2218.87
  4719.1  2213.7  4794.4 2207.12  4794.9 2206.62  4799.9 2207.12  4827.2 2208.88
  4842.2 2212.17  4992.4 2207.92  5009.9 2207.94  5037.6 2208.12  5049.9 2207.24
  5126.7    2212    5180 2219.47    5200  2227.2    5220 2231.05    5250 2230.94
    5300  2239.1    5330 2240.17    5380  2245.5    5490 2250.86  5760.6 2254.32
#Mann= 7 ,-1 , 0
  3713.8     .07       0  4794.4     .07       0  4799.9     .16       0
  4992.4     .07       0  5009.9     .07       0  5037.6     .16       0
  5126.7     .07       0
#XS Ineff= 2 , 0
       0  4842.2 2212.17               0
Permanent Ineff=
       F       F
Bank Sta=4992.4,5009.9
XS Rating Curve= 0 ,0
Exp/Cntr=0.3,0.1

Type RM Length L Ch R = 1 ,23394   ,293,293,293
BEGIN DESCRIPTION:
WEAVER SPRINGS CREEK 42.0
END DESCRIPTION:
XS GIS Cut Line= 3
      1448289.17      6823357.36       1449320.2      6822287.51
       1448983.6      6821503.19
#Sta/Elev= 30
  3514.2 2243.23  3645.2 2238.83  3864.4 2236.65  4062.4 2226.22    4126 2225.18
  4380.7 2232.91  4430.1 2229.41  4465.6 2222.63  4656.5 2201.12  4698.9 2201.53
  4734.4 2205.65  4783.8 2203.14  4812.1 2205.08  4877.1 2202.96  4953.6 2201.61
  4971.9 2199.11  4972.4 2198.61  4977.4 2199.11  4981.9 2201.21  5026.3 2202.97
  5062.3 2219.89  5073.4 2225.43    5097 2231.97  5102.4 2230.07  5162.7 2238.22
  5225.6 2242.28    5483 2246.19  5582.7 2251.28  5787.5 2254.23  5853.5 2253.38
#Mann= 5 ,-1 , 0
  3514.2     .07       0  4877.1     .12       0  4971.9     .07       0
  4977.4     .12       0  5062.3     .07       0
#XS Ineff= 2 , 0
       0  4812.1 2205.08               0
Permanent Ineff=
       F       F
Bank Sta=4971.9,4977.4
XS Rating Curve= 0 ,0
Exp/Cntr=0.3,0.1

Type RM Length L Ch R = 1 ,23101   ,444,444,444
BEGIN DESCRIPTION:
WEAVER SPRINGS CREEK 41.0
END DESCRIPTION:
XS GIS Cut Line= 4
      1448351.66      6823357.37      1449392.02       6822652.6
      1449640.72      6822304.94      1449160.67      6821673.33
#Sta/Elev= 30
  3540.7  2241.8  3672.4 2235.37  4010.9 2231.89  4061.8 2228.39  4175.7 2208.72
  4190.7 2212.78  4241.6 2212.03  4247.6 2217.58  4283.5 2224.39  4421.3 2207.36
  4493.2 2207.27  4535.2 2215.39    4580  2216.3  4765.8 2207.21  4852.1  2195.8
  4899.5 2194.07  4899.9 2193.57    4905 2194.07  5160.2 2198.22  5189.7 2205.01
  5204.4 2215.07  5227.3 2222.03  5232.4  2224.9  5241.1 2229.54    5291 2233.49
  5484.4 2238.25  5584.2 2234.02  5704.9 2235.52  5911.7 2248.08  6018.1 2249.58
#Mann= 5 ,-1 , 0
  3540.7     .07       0  4899.5     .07       0    4905     .07       0
  5227.3     .16       0  5232.4     .07       0
Bank Sta=4899.5,4905
XS Rating Curve= 0 ,0
Exp/Cntr=0.3,0.1

Type RM Length L Ch R = 1 ,22657   ,725,725,725
BEGIN DESCRIPTION:
WEAVER SPRINGS CREEK 40.0
END DESCRIPTION:
XS GIS Cut Line= 3
      1449754.87      6823273.43      1449756.11      6822686.73
      1449689.88       6822219.6
#Sta/Elev= 30
  4413.3 2220.19  4438.7 2219.13  4458.7 2216.09  4478.7 2211.85  4498.7 2209.87
  4528.7 2209.51  4578.7 2207.33  4728.7 2204.56  4758.7    2203  4778.7 2198.91
  4798.7 2192.31  4818.7 2187.68  4848.7 2186.78  4918.7 2186.54  4958.7 2183.63
  4963.9 2182.62  4964.4 2182.12  4973.5 2182.62  5043.8 2186.59  5089.6 2187.31
  5114.8 2189.85  5140.1  2190.4  5200.7 2194.25  5291.6 2197.02  5352.2 2209.41
  5372.4 2215.34  5403.7  2226.8  5412.8 2229.32    5433 2231.22  5471.8 2231.81
#Mann= 3 ,-1 , 0
  4413.3     .12       0  4963.9     .07       0  4973.5     .12       0
Bank Sta=4963.9,4973.5
XS Rating Curve= 0 ,0
Exp/Cntr=0.3,0.1

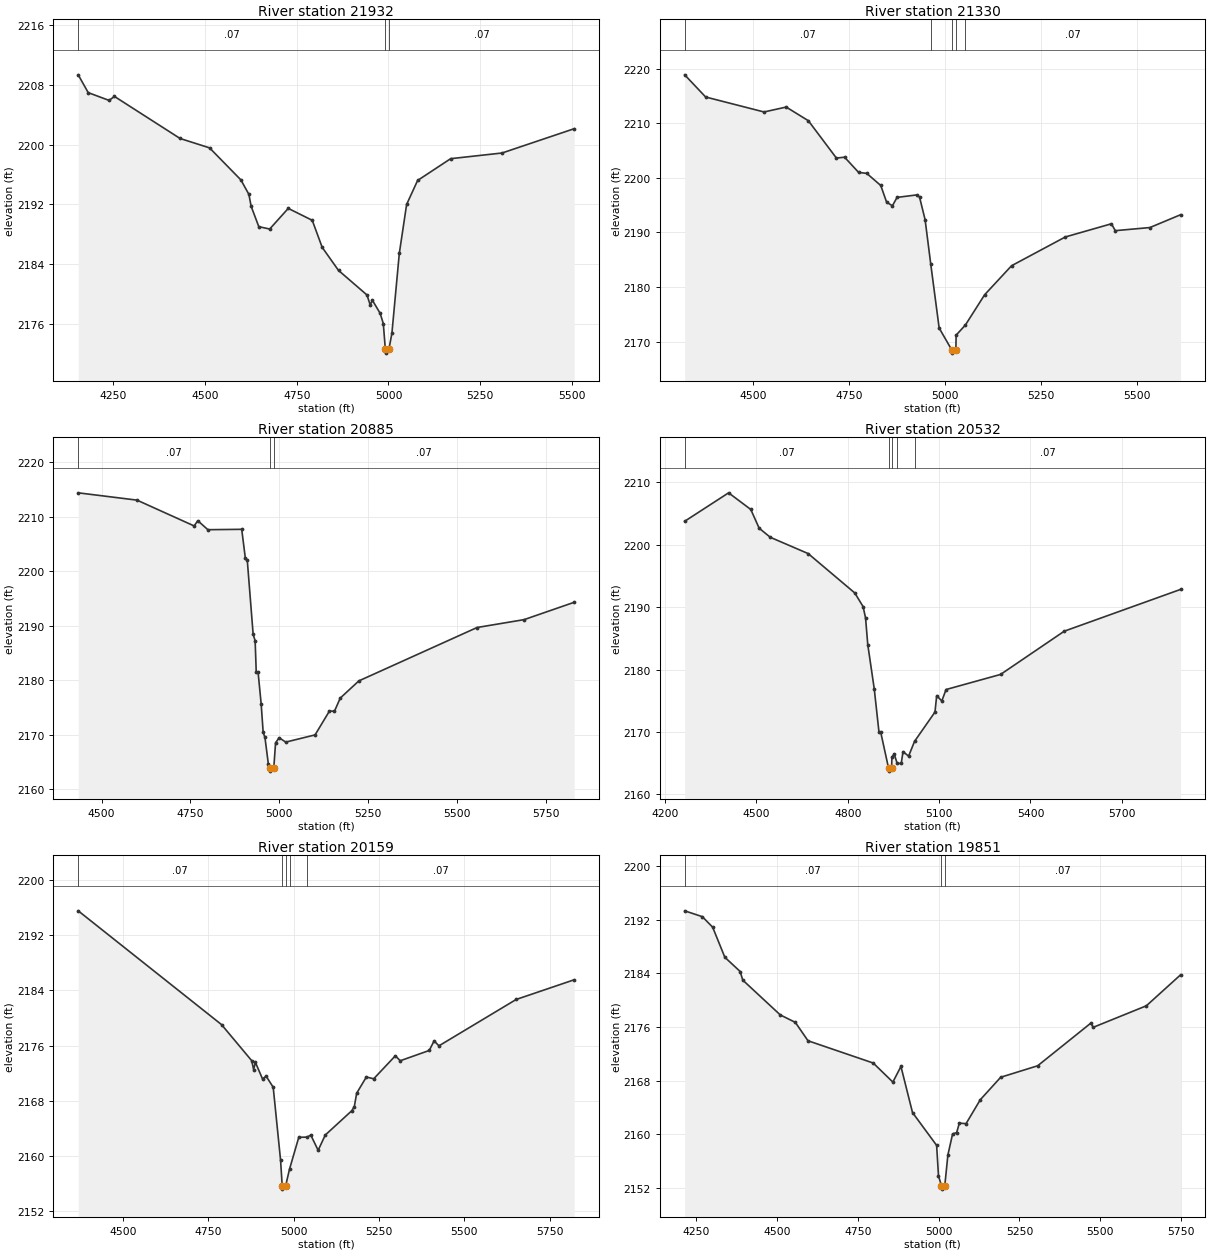
Type RM Length L Ch R = 1 ,21932   ,602,602,602
BEGIN DESCRIPTION:
WEAVER SPRINGS CREEK 39.0
END DESCRIPTION:
XS GIS Cut Line= 3
      1449822.16      6823232.22        1450305.        6822538.
      1450282.28      6822031.54
#Sta/Elev= 30
  4153.9 2209.38  4181.2 2206.99    4238 2205.95  4252.8 2206.48  4431.7 2200.84
  4512.1 2199.58  4597.6 2195.28  4619.4 2193.34  4625.5 2191.75  4646.4 2189.01
  4676.1 2188.69  4726.8 2191.46  4792.2 2189.86  4819.3 2186.23  4863.8 2183.14
  4941.5 2179.84  4950.2 2178.51  4956.3 2179.13  4977.3 2177.39    4986 2176.01
  4991.6 2172.54  4992.1 2172.04  5001.3 2172.54  5009.5 2174.73  5029.6 2185.41
  5049.6 2191.99  5079.6 2195.21  5169.7 2198.13  5309.8 2198.89  5506.5 2202.15
#Mann= 3 ,-1 , 0
  4153.9     .07       0  4991.6     .07       0  5001.3     .07       0
Bank Sta=4991.6,5001.3
XS Rating Curve= 0 ,0
Exp/Cntr=0.3,0.1

Type RM Length L Ch R = 1 ,21330   ,445,445,445
BEGIN DESCRIPTION:
WEAVER SPRINGS CREEK 38.0
END DESCRIPTION:
XS GIS Cut Line= 3
       1450300.3      6823518.12      1450657.91      6822943.37
      1450698.35      6822327.92
#Sta/Elev= 30
  4320.6 2218.86  4375.3  2214.8  4527.6 2212.06  4585.4 2212.96  4643.2 2210.46
  4716.4 2203.62  4737.7 2203.78  4774.3    2201  4795.5 2200.82  4832.1  2198.6
  4847.4 2195.54  4862.5 2194.89  4874.6 2196.42  4926.5 2196.88  4933.2 2196.49
  4947.8 2192.33  4962.6 2184.15  4984.4 2172.51    5018 2168.41  5018.5 2167.91
    5028 2168.41  5028.7  2171.2  5052.9 2173.06  5103.1  2178.6  5173.3 2183.91
  5313.6 2189.18  5433.8 2191.59  5443.9 2190.33  5534.1  2190.9  5614.3 2193.25
#Mann= 5 ,-1 , 0
  4320.6     .07       0  4962.6     .16       0    5018     .07       0
    5028     .16       0  5052.9     .07       0
Bank Sta=5018,5028
XS Rating Curve= 0 ,0
Exp/Cntr=0.3,0.1

Type RM Length L Ch R = 1 ,20885   ,353,353,353
BEGIN DESCRIPTION:
WEAVER SPRINGS CREEK 37.0
END DESCRIPTION:
XS GIS Cut Line= 3
      1450812.75      6823497.27      1451042.78      6823050.24
      1450908.22      6822166.97
#Sta/Elev= 30
  4434.3 2214.34  4599.8    2213  4760.7 2208.27  4770.9 2209.23  4799.4 2207.58
  4894.6 2207.65  4904.7 2202.43  4910.3 2201.97  4926.8 2188.38  4932.4 2187.23
  4935.5 2181.45  4940.7 2181.45  4949.4 2175.61    4955 2170.42    4960  2169.5
  4969.6 2164.62  4974.8 2163.82  4975.3 2163.32  4984.8 2163.82  4989.9 2168.51
    5000 2169.44  5018.5 2168.64  5101.1 2169.96  5141.6 2174.34  5155.7  2174.3
    5172 2176.71  5224.3 2179.86  5557.2 2189.65  5689.4 2191.09  5830.5 2194.27
#Mann= 3 ,-1 , 0
  4434.3     .07       0  4974.8     .07       0  4984.8     .07       0
Bank Sta=4974.8,4984.8
XS Rating Curve= 0 ,0
Exp/Cntr=0.3,0.1

Type RM Length L Ch R = 1 ,20532   ,373,373,373
BEGIN DESCRIPTION:
WEAVER SPRINGS CREEK 36.0
END DESCRIPTION:
XS GIS Cut Line= 3
        1450982.      6823562.42      1451370.06      6822937.86
      1450969.48      6822139.74
#Sta/Elev= 30
  4264.7 2203.77  4408.9 2208.33  4481.8 2205.66  4509.2 2202.66  4545.9  2201.2
  4670.2 2198.59  4823.2 2192.28  4850.5 2190.09  4858.6 2188.26  4865.8 2184.01
  4887.1 2176.92  4902.5 2170.04  4908.3 2169.97    4934 2164.22  4934.5 2163.72
  4944.1 2164.22    4945 2165.95  4952.7 2166.47  4962.4 2164.95  4975.7 2164.96
  4981.6 2166.85  4999.9 2166.12  5019.4 2168.49  5086.5 2173.19  5092.1 2175.82
  5108.9 2174.96  5122.9  2176.8  5301.9 2179.22  5510.9 2186.15    5893 2192.85
#Mann= 5 ,-1 , 0
  4264.7     .07       0    4934     .07       0  4944.1     .07       0
  4962.4     .16       0  5019.4     .07       0
Bank Sta=4934,4944.1
XS Rating Curve= 0 ,0
Exp/Cntr=0.3,0.1

Type RM Length L Ch R = 1 ,20159   ,308,308,308
BEGIN DESCRIPTION:
WEAVER SPRINGS CREEK 35.0
END DESCRIPTION:
XS GIS Cut Line= 3
      1451926.03      6823568.94      1451722.22      6822971.76
      1451164.28      6822368.79
#Sta/Elev= 30
    4369  2195.5  4788.8 2179.03  4877.2 2173.81  4882.7 2172.53    4888 2173.56
  4908.8 2171.17  4919.4 2171.57  4940.1 2169.96  4961.7 2159.39  4966.4 2155.72
  4966.9 2155.22  4976.6 2155.72  4987.9 2158.12    5015 2162.72  5039.7 2162.75
  5050.1 2163.05  5071.7 2160.84  5092.6 2163.05  5170.3 2166.57  5177.7 2167.17
  5184.5  2169.1  5212.9 2171.45  5234.4 2171.19  5297.9 2174.52  5312.1  2173.8
  5397.1 2175.29  5411.3 2176.68  5425.5 2175.96  5651.7 2182.67  5821.5 2185.52
#Mann= 5 ,-1 , 0
    4369     .07       0  4966.4     .07       0  4976.6     .07       0
  4987.9     .16       0  5039.7     .07       0
Bank Sta=4966.4,4976.6
XS Rating Curve= 0 ,0
Exp/Cntr=0.3,0.1

Type RM Length L Ch R = 1 ,19851   ,329,329,329
BEGIN DESCRIPTION:
Mapping XS c11bf6f2
END DESCRIPTION:
XS GIS Cut Line= 3
      1452113.39      6823439.16      1451839.94      6822702.15
      1451235.78      6822259.44
#Sta/Elev= 30
    4214 2193.31  4268.6 2192.44  4300.6 2190.87  4338.3 2186.39  4385.9 2184.26
  4393.7 2182.99  4509.9  2177.8  4556.5 2176.69  4595.7 2173.95  4797.6 2170.63
  4858.4 2167.79  4883.4 2170.12  4919.2 2163.25  4993.9 2158.36  4999.6 2153.83
  5008.9 2152.34  5009.4 2151.84  5019.1 2152.34  5028.7 2156.92  5043.3 2160.07
  5055.8 2160.26  5064.2 2161.67    5085  2161.6    5129 2165.16  5192.2 2168.51
  5306.6 2170.22  5471.8  2176.6    5478 2175.94  5643.1 2179.16  5749.1 2183.78
#Mann= 3 ,-1 , 0
    4214     .07       0  5008.9     .07       0  5019.1     .07       0
Bank Sta=5008.9,5019.1
XS Rating Curve= 0 ,0
Exp/Cntr=0.3,0.1

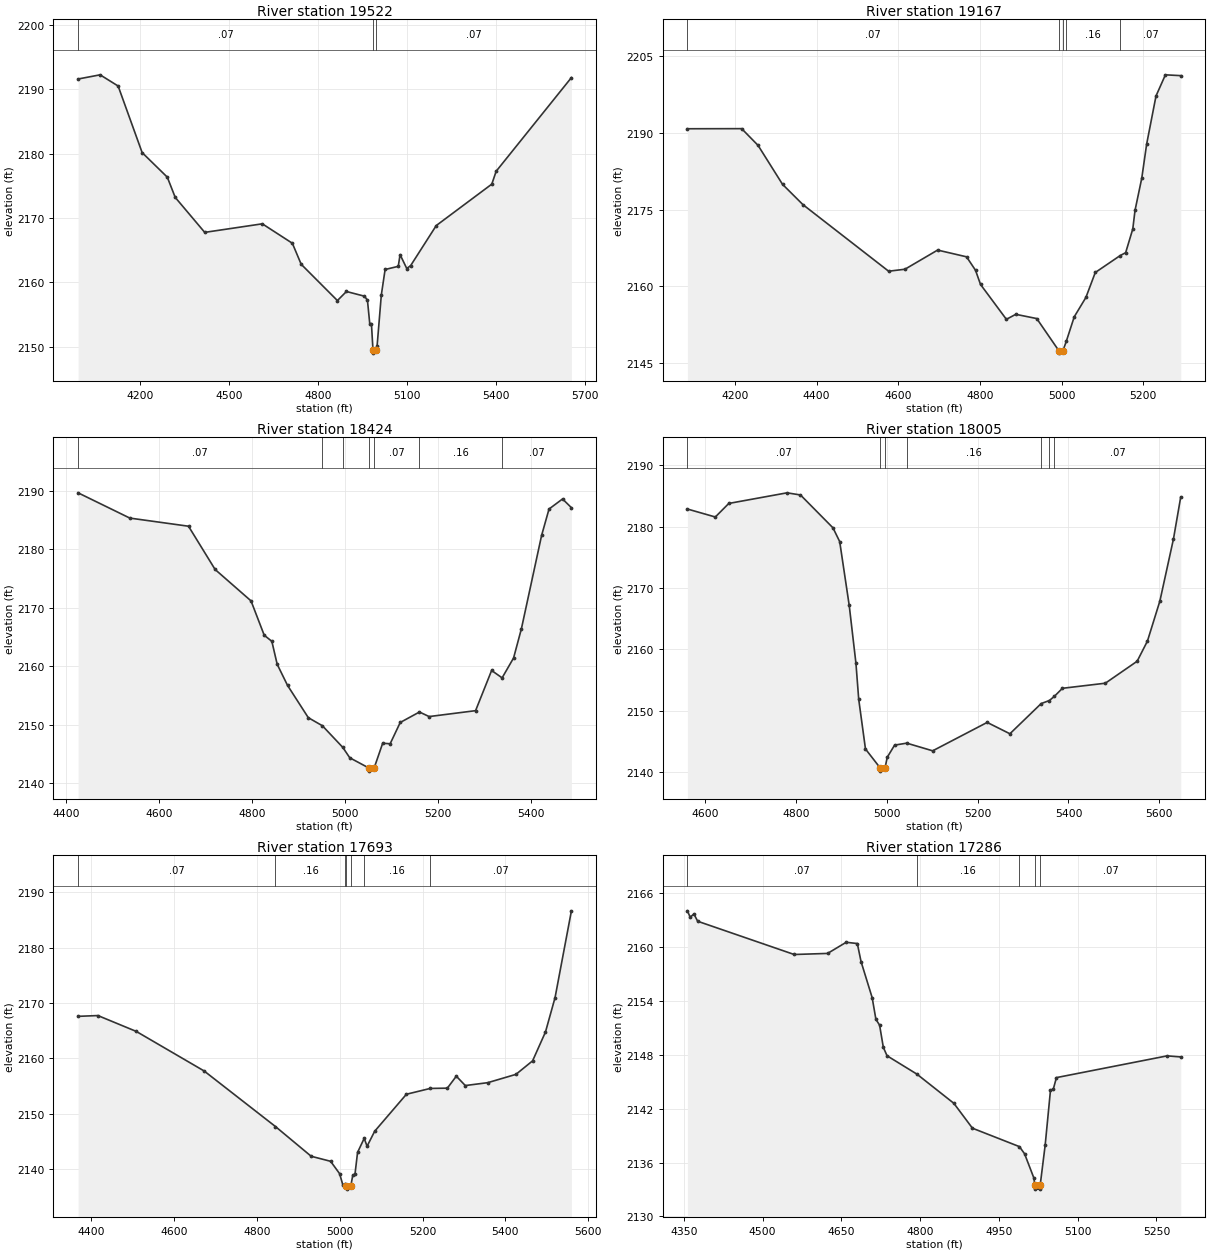
Type RM Length L Ch R = 1 ,19522   ,355,355,355
BEGIN DESCRIPTION:
Mapping XS 032627f3
END DESCRIPTION:
XS GIS Cut Line= 3
      1452175.88       6823431.3      1452024.84      6822457.36
       1451634.2      6821905.26
#Sta/Elev= 30
  3992.6 2191.63  4066.8 2192.28  4127.5 2190.54  4208.4 2180.19  4293.2 2176.37
  4319.8 2173.23  4419.2 2167.79  4613.2 2169.12  4714.4  2166.1  4744.2 2162.83
  4866.2 2157.19  4896.6  2158.6  4957.3 2157.87  4967.4 2157.25  4975.3 2153.53
  4980.9 2153.53    4986 2149.52  4986.5 2149.02  4996.3 2149.52  4999.8 2150.06
  5014.1 2158.05  5026.9 2162.02  5071.2 2162.51  5077.3 2164.33  5099.9 2162.17
    5113 2162.63  5199.2 2168.85  5386.3 2175.29    5401 2177.29  5654.5 2191.85
#Mann= 3 ,-1 , 0
  3992.6     .07       0    4986     .07       0  4996.3     .07       0
Bank Sta=4986,4996.3
XS Rating Curve= 0 ,0
Exp/Cntr=0.3,0.1

Type RM Length L Ch R = 1 ,19167   ,743,743,743
BEGIN DESCRIPTION:
Mapping XS 9ab5472e
END DESCRIPTION:
XS GIS Cut Line= 3
       1452210.6      6823450.92      1452223.62      6822776.45
      1452446.78       6822291.2
#Sta/Elev= 30
  4083.4 2190.82  4216.3 2190.84  4256.4 2187.57  4316.4 2179.94  4366.4 2175.96
  4576.4 2162.92  4616.4 2163.31  4696.4 2167.06  4767.3 2165.74  4789.3  2163.1
  4801.5 2160.33  4864.9  2153.5  4887.9 2154.48  4939.3 2153.65  4993.2 2147.38
  4993.7 2146.88  5003.6 2147.38  5011.6 2149.17  5031.2    2154  5059.7 2157.78
  5082.7 2162.67  5143.6 2165.98  5157.1 2166.55  5174.6  2171.2  5180.1 2174.85
  5196.6 2181.14  5208.6 2187.83  5231.5 2197.24  5254.5 2201.38  5292.1 2201.22
#Mann= 5 ,-1 , 0
  4083.4     .07       0  4993.2     .07       0  5003.6     .07       0
  5011.6     .16       0  5143.6     .07       0
Bank Sta=4993.2,5003.6
XS Rating Curve= 0 ,0
Exp/Cntr=0.3,0.1

Type RM Length L Ch R = 1 ,18424   ,419,419,419
BEGIN DESCRIPTION:
Mapping XS f2f3d708
END DESCRIPTION:
XS GIS Cut Line= 3
      1452468.39      6823549.93      1452726.23      6823042.08
      1452918.95      6822588.91
#Sta/Elev= 30
  4425.6 2189.64    4537 2185.32  4663.3 2183.93  4720.6 2176.53  4797.9 2171.16
  4826.3 2165.29  4842.7 2164.25  4854.2 2160.32  4876.5 2156.71  4921.2 2151.19
  4951.5 2149.81  4995.3 2146.12  5010.5 2144.33  5052.4 2142.55  5052.9 2142.05
  5062.8 2142.55  5081.3 2146.82  5097.4 2146.73  5119.1 2150.37  5160.5 2152.16
  5181.3 2151.38  5281.3 2152.39  5315.8 2159.26  5338.4    2158  5363.1  2161.4
  5379.9 2166.38  5423.4 2182.35  5439.4 2186.87  5468.5 2188.59  5487.6  2187.1
#Mann= 7 ,-1 , 0
  4425.6     .07       0  4951.5     .16       0  4995.3     .07       0
  5052.4     .07       0  5062.8     .07       0  5160.5     .16       0
  5338.4     .07       0
Bank Sta=5052.4,5062.8
XS Rating Curve= 0 ,0
Exp/Cntr=0.3,0.1

Type RM Length L Ch R = 1 ,18005   ,312,312,312
BEGIN DESCRIPTION:
Mapping XS e975f7a9
END DESCRIPTION:
XS GIS Cut Line= 3
      1452745.33      6823654.05       1452982.3      6823312.91
       1452945.9      6822642.06
#Sta/Elev= 30
  4560.2 2182.86  4621.7 2181.56  4651.4 2183.77  4779.7  2185.5  4809.4 2185.15
    4881 2179.79  4895.8 2177.55  4916.8 2167.14  4931.6 2157.71  4937.7 2151.85
  4952.6 2143.75  4985.2 2140.64  4985.7 2140.14  4995.7 2140.64  5000.5 2142.39
  5016.8 2144.38  5043.6  2144.7  5100.7 2143.45  5220.8 2148.08  5270.9 2146.23
  5339.8 2151.15  5357.9 2151.65  5368.9 2152.33  5386.6 2153.64  5481.2 2154.47
  5551.3 2158.05    5574 2161.34  5601.4 2167.86  5631.4    2178  5647.4 2184.84
#Mann= 7 ,-1 , 0
  4560.2     .07       0  4985.2     .07       0  4995.7     .07       0
  5043.6     .16       0  5339.8     .07       0  5357.9     .16       0
  5368.9     .07       0
Bank Sta=4985.2,4995.7
XS Rating Curve= 0 ,0
Exp/Cntr=0.3,0.1

Type RM Length L Ch R = 1 ,17693   ,407,407,407
BEGIN DESCRIPTION:
Mapping XS 07f9e981
END DESCRIPTION:
XS GIS Cut Line= 3
      1453000.52      6823716.59      1453219.28      6823221.77
      1452967.24      6822621.56
#Sta/Elev= 30
  4367.8 2167.58  4415.7 2167.72  4508.4 2164.86  4672.4 2157.72  4844.6  2147.7
    4931 2142.33    4978 2141.42  4999.7 2139.19  5007.7 2137.11  5013.8  2137.4
  5016.1  2136.9  5016.6  2136.4  5026.6  2136.9  5031.4 2138.86  5036.9 2139.13
  5043.1 2143.03  5059.1 2145.56  5066.1 2144.14  5084.4 2146.84  5161.1 2153.52
  5218.6 2154.57    5260 2154.62  5281.7 2156.78  5303.4 2155.09  5357.6 2155.61
  5425.8 2157.11    5466 2159.55  5497.1 2164.75  5520.3 2170.97  5559.8 2186.62
#Mann= 7 ,-1 , 0
  4367.8     .07       0  4844.6     .16       0  5013.8     .07       0
  5016.1     .07       0  5026.6     .07       0  5059.1     .16       0
  5218.6     .07       0
Bank Sta=5016.1,5026.6
XS Rating Curve= 0 ,0
Exp/Cntr=0.3,0.1

Type RM Length L Ch R = 1 ,17286   ,491,491,491
BEGIN DESCRIPTION:
Mapping XS 755f121c
END DESCRIPTION:
XS GIS Cut Line= 4
      1453089.08      6823729.58      1453536.99      6823284.27
      1453570.84      6823195.73      1453504.63      6822993.38
#Sta/Elev= 30
  4356.9 2164.01  4362.2  2163.3  4369.3 2163.66  4376.4 2162.85  4560.2 2159.15
  4623.8 2159.27  4659.2 2160.51  4680.4 2160.37  4687.5 2158.36  4708.7 2154.34
  4715.8 2151.93  4722.8 2151.29  4729.9 2148.82    4737 2147.88  4793.8 2145.84
  4864.2 2142.59  4899.6 2139.82    4989 2137.77  4998.8 2136.98  5016.6 2134.27
  5018.2 2133.54  5018.7 2133.04  5028.2 2133.04  5028.7 2133.54    5038  2137.9
  5048.2 2144.06  5053.5 2144.16  5059.5 2145.45  5270.3 2147.87  5296.2 2147.75
#Mann= 5 ,-1 , 0
  4356.9     .07       0  4793.8     .16       0    4989     .07       0
  5018.2     .07       0  5028.7     .07       0
Bank Sta=5018.2,5028.7
XS Rating Curve= 0 ,0
Exp/Cntr=0.3,0.1