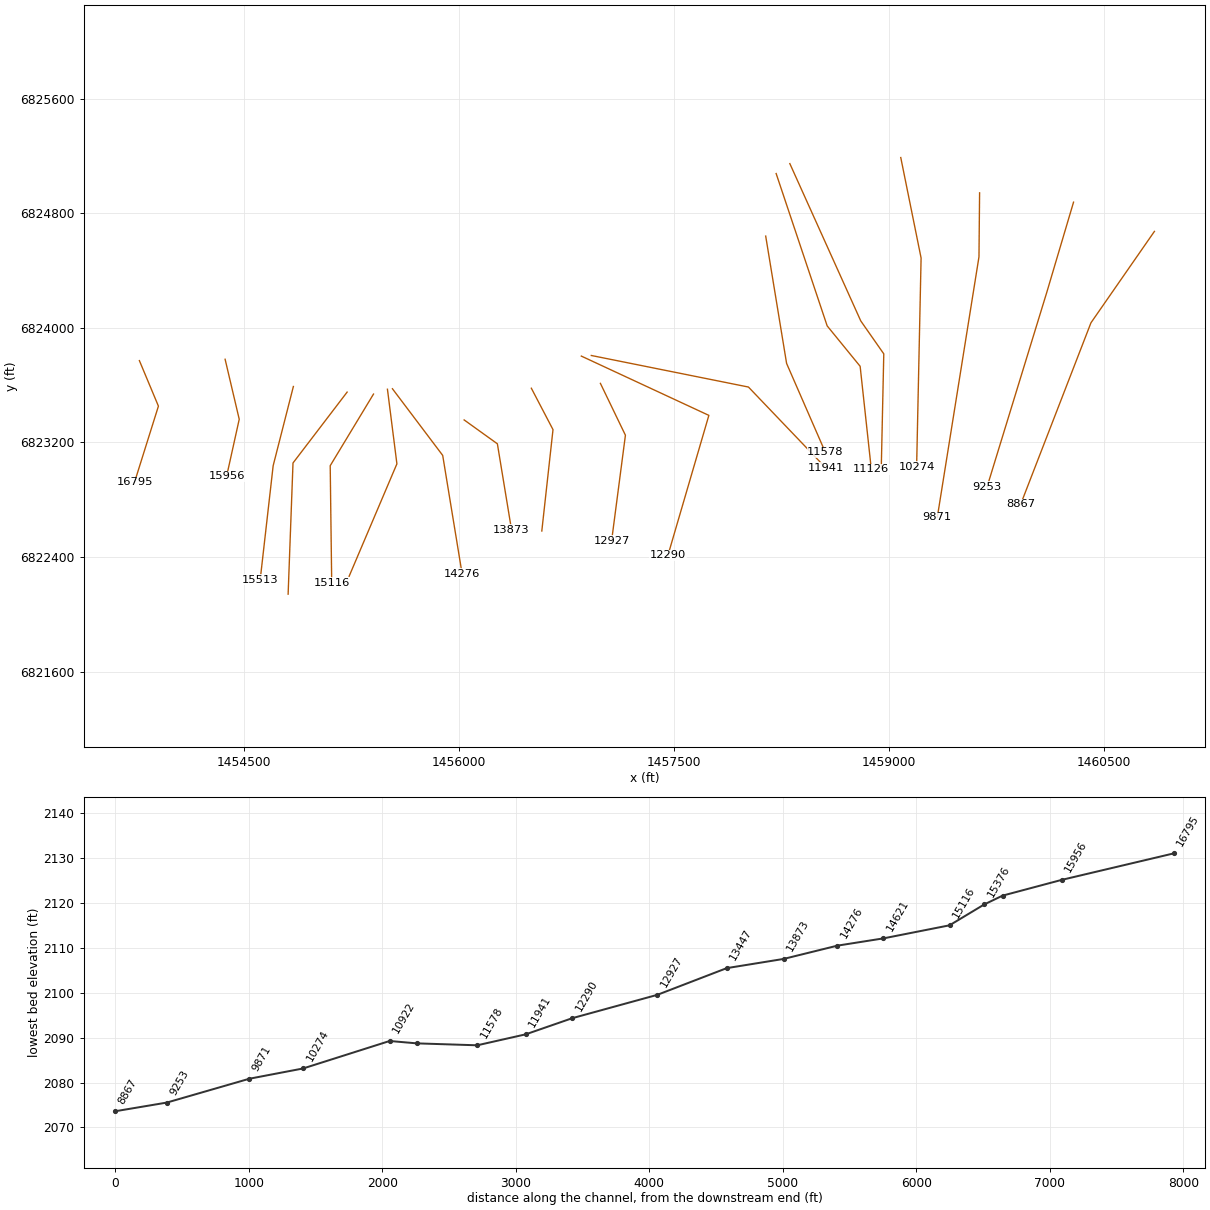
HEC-RAS study WEAVER SPRINGS CREEK.prj: WEAVER SPRINGS CREEK Base Level Engineering

--- WEAVER SPRINGS CREEK.g01 (geometry) --- (continued)

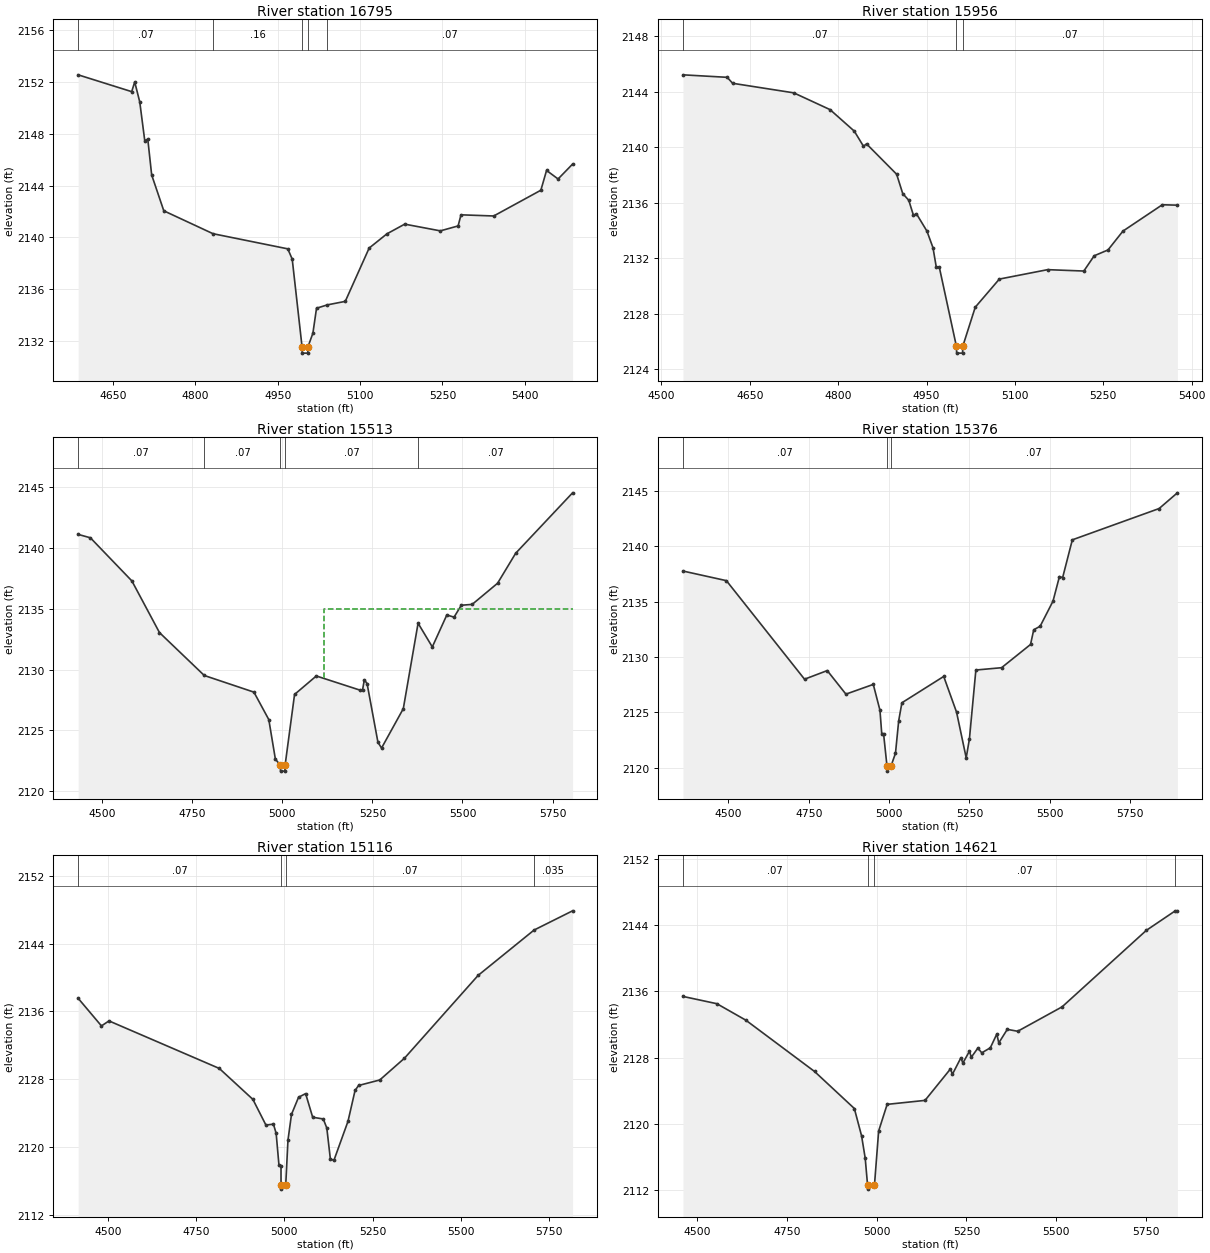
Type RM Length L Ch R = 1 ,16795   ,839,839,839
BEGIN DESCRIPTION:
Mapping XS f8c9c7f1
END DESCRIPTION:
XS GIS Cut Line= 3
      1453771.73      6823771.64      1453904.55      6823453.91
      1453737.93       6822922.8
#Sta/Elev= 30
  4586.2 2152.56  4683.8 2151.26  4689.3 2152.01  4698.5 2150.46  4707.6 2147.47
  4713.1 2147.59  4720.2 2144.82  4742.3 2142.05    4832 2140.28  4968.2 2139.11
  4976.3 2138.32  4994.2 2131.55  4994.7 2131.05  5004.6 2131.05  5005.1 2131.55
    5014 2132.59  5020.6 2134.52  5040.4 2134.78    5073 2135.05  5116.5 2139.17
  5148.9 2140.27  5181.3 2141.02  5246.2  2140.5  5278.6 2140.88  5283.9 2141.74
  5343.5 2141.65  5429.4 2143.64  5439.8 2145.17  5460.8 2144.51  5487.2 2145.66
#Mann= 5 ,-1 , 0
  4586.2     .07       0    4832     .16       0  4994.2     .07       0
  5005.1     .16       0  5040.4     .07       0
Bank Sta=4994.2,5005.1
XS Rating Curve= 0 ,0
Exp/Cntr=0.3,0.1

Type RM Length L Ch R = 1 ,15956   ,443,443,443
BEGIN DESCRIPTION:
Mapping XS 81583b21
END DESCRIPTION:
XS GIS Cut Line= 3
      1454369.75      6823781.08       1454468.3      6823362.28
      1454379.99      6822962.97
#Sta/Elev= 30
  4536.6 2145.22  4611.7 2145.04  4620.9 2144.61  4724.7 2143.92  4786.3 2142.71
  4827.4 2141.16    4843 2140.07  4848.2 2140.24  4899.3 2138.05  4909.6 2136.66
  4919.9 2136.17  4927.8 2135.09  4932.9  2135.2  4950.7 2133.95    4961 2132.75
  4966.5 2131.37  4971.6 2131.37  5000.7 2125.65  5001.2 2125.15  5011.1 2125.15
  5011.6 2125.65  5032.7 2128.46  5073.6 2130.49  5155.6 2131.17    5217 2131.07
  5234.6 2132.17    5258 2132.59  5283.4 2133.95  5350.2 2135.85  5375.8 2135.82
#Mann= 3 ,-1 , 0
  4536.6     .07       0  5000.7     .07       0  5011.6     .07       0
Bank Sta=5000.7,5011.6
XS Rating Curve= 0 ,0
Exp/Cntr=0.3,0.1

Type RM Length L Ch R = 1 ,15513   ,137,137,137
BEGIN DESCRIPTION:
WEAVER SPRINGS CREEK 26.0
END DESCRIPTION:
XS GIS Cut Line= 3
      1454846.01       6823590.9        1454705.        6823038.
      1454614.45      6822241.12
#Sta/Elev= 30
  4433.1 2141.12  4467.1 2140.84  4582.3 2137.29  4658.9 2133.04  4783.3 2129.51
  4921.1 2128.14  4962.4 2125.88  4980.7 2122.62  4994.5 2122.14    4995 2121.64
  5007.2 2121.64  5007.7 2122.14  5033.9 2127.95  5094.3 2129.47    5215 2128.31
  5222.6 2128.31  5227.6 2129.15  5235.2 2128.85  5265.4 2124.01  5275.4 2123.54
  5335.8 2126.78  5376.8 2133.81  5416.3 2131.86  5456.6 2134.49  5476.7 2134.31
  5496.8 2135.29    5527 2135.36  5597.5  2137.1  5647.8 2139.57  5805.7 2144.54
#Mann= 5 ,-1 , 0
  4433.1     .07       0  4783.3     .07       0  4994.5     .07       0
  5007.7     .07       0  5376.8     .07       0
#XS Ineff= 2 , 0
       0                  5114.4       0    2135
Permanent Ineff=
       F       F
Bank Sta=4994.5,5007.7
XS Rating Curve= 0 ,0
Exp/Cntr=0.3,0.1

Type RM Length L Ch R = 1 ,15376   ,260,260,260
BEGIN DESCRIPTION:
Mapping XS fb0f4c9b
END DESCRIPTION:
XS GIS Cut Line= 3
      1455221.01      6823551.84      1454843.41      6823057.05
      1454809.35      6822141.19
#Sta/Elev= 30
  4358.5 2137.77  4493.7  2136.9  4736.9 2127.99  4807.6 2128.77  4865.7 2126.64
  4950.9 2127.52  4971.7 2125.18  4977.2 2123.07  4982.9 2123.07  4993.4 2120.18
  4993.9 2119.68  5006.6 2120.18    5020  2121.3    5030 2124.24    5040 2125.86
  5170.1 2128.24  5210.1 2125.01  5240.1 2120.88  5250.1 2122.59  5270.2 2128.82
  5350.2 2129.03  5440.3 2131.13  5450.3 2132.46  5470.3 2132.78  5510.3 2135.05
  5530.3 2137.27  5540.3 2137.18  5570.4 2140.59  5840.6 2143.42  5897.4 2144.84
#Mann= 3 ,-1 , 0
  4358.5     .07       0  4993.4     .07       0  5006.6     .07       0
Bank Sta=4993.4,5006.6
XS Rating Curve= 0 ,0
Exp/Cntr=0.3,0.1

Type RM Length L Ch R = 1 ,15116   ,495,495,495
BEGIN DESCRIPTION:
WEAVER SPRINGS CREEK 25.0
END DESCRIPTION:
XS GIS Cut Line= 3
      1455405.02      6823538.04      1455102.96      6823037.99
      1455113.37      6822222.06
#Sta/Elev= 30
  4415.8 2137.55  4481.8 2134.29  4503.2 2134.88  4815.6 2129.27  4910.7 2125.62
  4947.6 2122.59  4968.9  2122.7  4976.6  2121.6  4984.4 2117.91  4990.3 2117.79
  4990.4 2115.53  4990.9 2115.03  5003.7 2115.53    5010  2120.8    5020 2123.85
    5040 2125.87    5060  2126.3    5080 2123.51    5110 2123.31    5120 2122.24
    5130 2118.62    5140 2118.41    5180 2123.03    5200 2126.67    5210 2127.26
    5270 2127.91    5340 2130.48  5548.5 2140.25  5706.9  2145.6    5816 2147.87
#Mann= 4 ,-1 , 0
  4415.8     .07       0  4990.4     .07       0  5003.7     .07       0
  5706.9    .035       0
Bank Sta=4990.4,5003.7
XS Rating Curve= 0 ,0
Exp/Cntr=0.3,0.1

Type RM Length L Ch R = 1 ,14621   ,345,345,345
BEGIN DESCRIPTION:
Mapping XS b36edf62
END DESCRIPTION:
XS GIS Cut Line= 3
      1455502.27      6823571.76      1455568.24      6823050.98
      1455234.92      6822266.28
#Sta/Elev= 30
  4460.1  2135.4  4554.6 2134.52  4635.3 2132.53  4826.8 2126.33  4937.6 2121.86
  4957.8 2118.55  4967.9 2115.85  4974.4 2112.62  4974.9 2112.12  4993.7 2112.62
  5005.3 2119.14    5029 2122.36  5134.5 2122.84  5205.4 2126.64  5210.9    2126
  5234.5 2127.99    5240 2127.35  5258.2 2128.77  5263.6 2128.06  5281.6 2129.15
  5292.7 2128.59  5316.4 2129.19  5334.6 2130.86    5340 2129.78  5363.7 2131.42
  5392.7 2131.19  5516.4 2134.14  5751.1 2143.38  5830.7 2145.71  5837.6 2145.74
#Mann= 4 ,-1 , 0
  4460.1     .07       0  4974.4     .07       0  4993.7     .07       0
  5830.7    .035       0
Bank Sta=4974.4,4993.7
XS Rating Curve= 0 ,0
Exp/Cntr=0.3,0.1

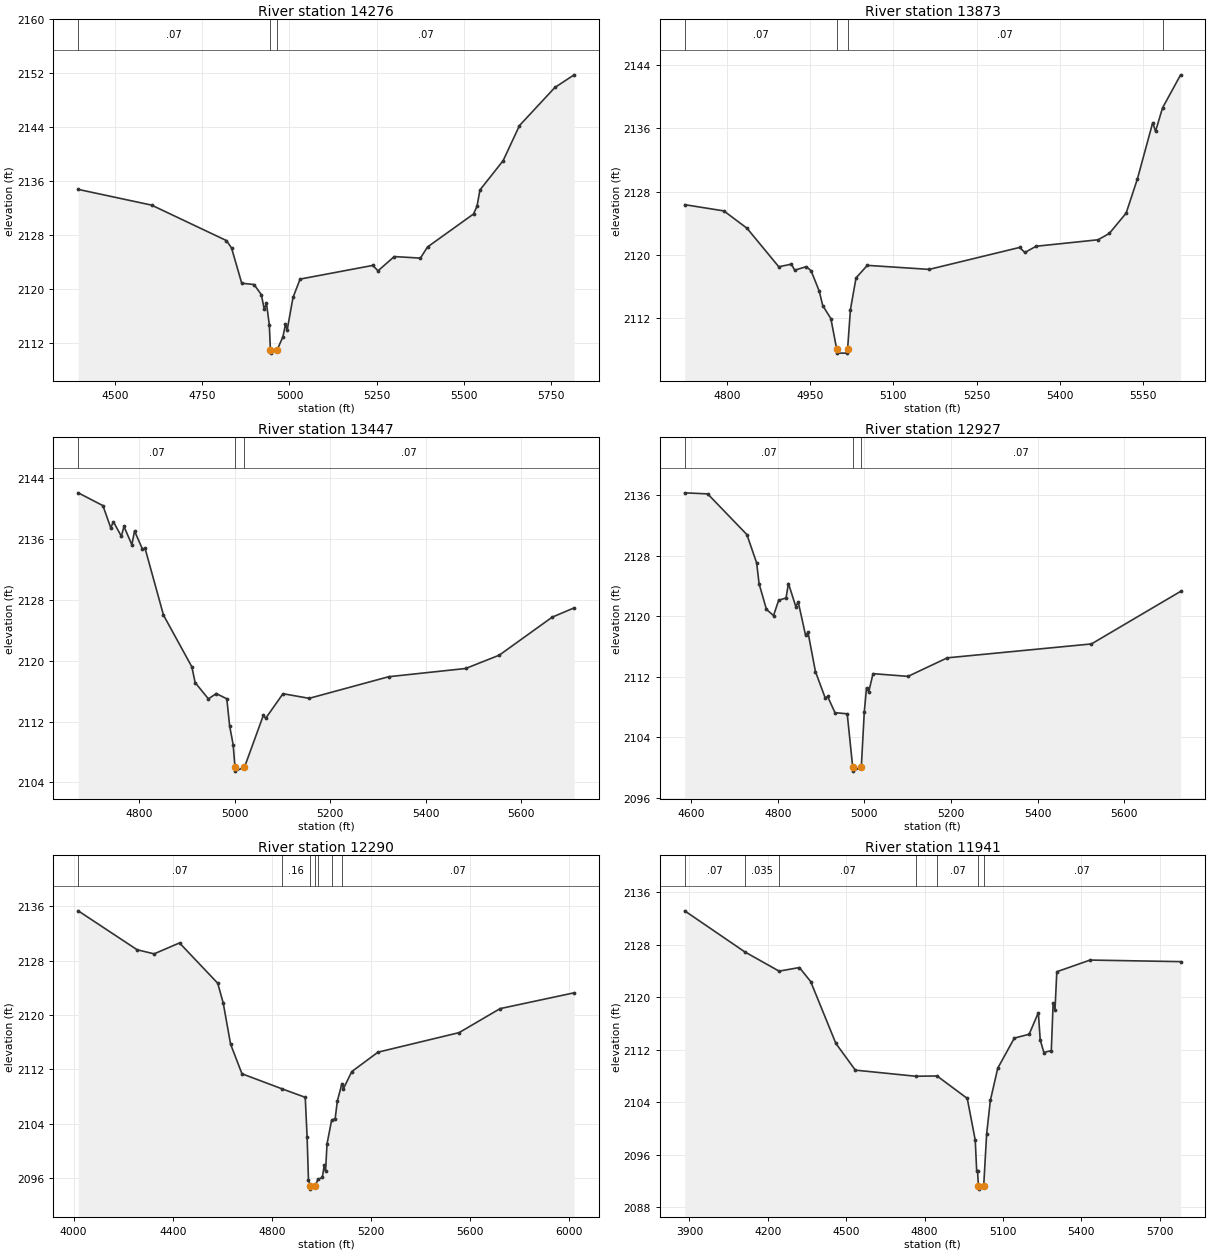
Type RM Length L Ch R = 1 ,14276   ,403,403,403
BEGIN DESCRIPTION:
Mapping XS 455f0b1f
END DESCRIPTION:
XS GIS Cut Line= 3
      1455536.98      6823575.29      1455887.68      6823110.01
      1456023.11      6822283.58
#Sta/Elev= 30
    4395 2134.78  4605.1 2132.45  4819.5 2127.19  4834.1 2126.09  4863.2 2120.87
  4898.6 2120.67  4919.4 2119.17  4927.7 2116.99    4934 2117.92  4942.3 2114.64
  4945.3    2111  4945.8  2110.5  4964.9    2111  4981.2 2112.94  4988.4 2114.75
  4993.4 2113.94  5010.1 2118.76  5030.4 2121.48  5238.7 2123.51  5253.3  2122.7
    5300 2124.82  5374.9 2124.59  5395.2 2126.24  5526.9 2131.13    5537 2132.29
  5545.3 2134.69  5611.7 2139.04  5658.6 2144.25    5760  2149.9  5815.1 2151.77
#Mann= 3 ,-1 , 0
    4395     .07       0  4945.3     .07       0  4964.9     .07       0
Bank Sta=4945.3,4964.9
XS Rating Curve= 0 ,0
Exp/Cntr=0.3,0.1

Type RM Length L Ch R = 1 ,13873   ,426,426,426
BEGIN DESCRIPTION:
Mapping XS cb456c56
END DESCRIPTION:
XS GIS Cut Line= 3
      1456037.39      6823357.53      1456269.14      6823190.89
      1456367.79      6822591.19
#Sta/Elev= 30
  4724.1 2126.35  4794.6 2125.56  4836.4 2123.36  4893.6 2118.48  4916.2 2118.81
  4922.3 2118.05  4943.2  2118.5  4951.8 2117.97  4966.5 2115.39  4972.7 2113.57
  4987.4 2111.92  4997.9 2108.04  4998.4 2107.54    5017 2107.54  5017.5 2108.04
  5022.6 2113.04  5032.7 2117.07    5053 2118.66  5164.5 2118.15  5327.3 2120.93
  5336.8 2120.29    5357 2121.08  5468.5  2121.9  5488.8  2122.7  5519.2 2125.28
  5539.5 2129.62  5567.1 2136.75  5572.1 2135.64  5584.7 2138.61  5617.3  2142.8
#Mann= 4 ,-1 , 0
  4724.1     .07       0  4997.9     .07       0  5017.5     .07       0
  5584.7     .16       0
Bank Sta=4997.9,5017.5
XS Rating Curve= 0 ,0
Exp/Cntr=0.3,0.1

Type RM Length L Ch R = 1 ,13447   ,520,520,520
BEGIN DESCRIPTION:
Mapping XS 27c8e5d6
END DESCRIPTION:
XS GIS Cut Line= 3
      1456506.12      6823578.89      1456657.16      6823289.84
      1456579.11      6822582.26
#Sta/Elev= 30
  4672.4 2142.04  4724.1 2140.36  4740.5 2137.45  4746.1 2138.24  4762.6 2136.34
  4768.2 2137.62  4784.7 2135.22  4790.3 2137.03  4806.7 2134.67  4812.4 2134.73
  4850.9 2125.98  4910.3 2119.18  4917.1 2117.12  4944.9 2114.98  4961.3 2115.68
  4983.4 2114.99  4989.3 2111.44  4996.7 2108.97  5000.5 2105.99    5001 2105.49
  5020.3 2105.99  5059.8  2112.8  5064.8 2112.43    5101 2115.66  5155.7 2115.05
  5322.3 2117.89  5483.3 2118.97  5553.7 2120.72  5664.4 2125.71  5710.4 2126.93
#Mann= 3 ,-1 , 0
  4672.4     .07       0  5000.5     .07       0  5020.3     .07       0
Bank Sta=5000.5,5020.3
XS Rating Curve= 0 ,0
Exp/Cntr=0.3,0.1

Type RM Length L Ch R = 1 ,12927   ,637,637,637
BEGIN DESCRIPTION:
Mapping XS faba7a44
END DESCRIPTION:
XS GIS Cut Line= 3
      1456987.89      6823612.76      1457162.37      6823250.78
      1457066.01      6822513.79
#Sta/Elev= 30
  4585.2 2136.34  4638.3  2136.2  4728.8 2130.82  4751.4 2127.07    4757 2124.32
    4774 2120.93  4790.3 2120.11  4802.2 2122.13  4819.2 2122.44  4824.8 2124.35
  4841.8  2121.3  4847.4 2121.91  4864.4 2117.48    4870 2117.88  4887.1 2112.71
  4909.7 2109.21  4915.2 2109.41  4932.3 2107.27  4960.5 2107.12  4973.2 2100.04
  4973.7 2099.54    4993 2100.04  4999.9 2107.37  5005.1 2110.56  5010.2 2110.03
  5020.1 2112.43  5100.8 2112.07  5191.5 2114.52  5524.4 2116.36  5730.3 2123.31
#Mann= 3 ,-1 , 0
  4585.2     .07       0  4973.2     .07       0    4993     .07       0
Bank Sta=4973.2,4993
XS Rating Curve= 0 ,0
Exp/Cntr=0.3,0.1

Type RM Length L Ch R = 1 ,12290   ,349,349,349
BEGIN DESCRIPTION:
Mapping XS dae04495
END DESCRIPTION:
XS GIS Cut Line= 3
       1456854.9      6823803.13      1457744.45      6823389.32
      1457458.68      6822411.42
#Sta/Elev= 30
  4018.9 2135.35  4256.2 2129.62  4324.9 2129.01  4427.4 2130.62  4581.5 2124.68
  4603.6 2121.77  4633.4  2115.7  4679.2 2111.34  4839.9 2109.13  4934.4 2107.87
  4941.9 2102.04  4947.4 2095.73  4954.8 2094.84  4955.3 2094.34  4974.7 2094.84
  4985.4 2095.76  5003.3 2096.06  5011.2 2097.91  5016.4 2097.04  5022.2 2100.99
  5040.8  2104.5  5055.1 2104.73  5063.9 2107.33  5082.4 2109.89  5088.6 2109.15
    5122 2111.66  5227.6 2114.52  5554.7  2117.4  5720.2 2120.94  6018.8 2123.27
#Mann= 7 ,-1 , 0
  4018.9     .07       0  4839.9     .16       0  4954.8     .07       0
  4974.7     .16       0  4985.4     .07       0  5040.8     .16       0
  5082.4     .07       0
Bank Sta=4954.8,4974.7
XS Rating Curve= 0 ,0
Exp/Cntr=0.3,0.1

Type RM Length L Ch R = 1 ,11941   ,363,363,363
BEGIN DESCRIPTION:
WEAVER SPRINGS CREEK 22.0
END DESCRIPTION:
XS GIS Cut Line= 3
      1456924.37      6823807.46      1458020.65      6823587.13
       1458559.8      6823022.77
#Sta/Elev= 30
  3881.8 2133.19  4111.9 2126.93  4243.3 2123.99    4321 2124.54  4364.1 2122.41
  4460.7 2112.96  4535.2 2108.89  4766.3 2107.96    4848    2108  4963.6 2104.58
  4994.2 2098.23  4999.7 2093.56  5002.9 2093.56  5006.4 2091.24  5006.9 2090.74
  5026.6 2091.24  5037.9 2099.18  5052.1 2104.27  5080.4 2109.19  5143.9 2113.78
  5200.5 2114.36  5235.8 2117.65    5243 2113.49  5257.1 2111.58  5285.4 2111.86
  5292.4  2119.1  5299.6 2118.13  5306.5  2123.9  5433.9 2125.68  5780.5 2125.44
#Mann= 7 ,-1 , 0
  3881.8     .07       0  4111.9    .035       0  4243.3     .07       0
  4766.3     .16       0    4848     .07       0  5006.4     .07       0
  5026.6     .07       0
Bank Sta=5006.4,5026.6
XS Rating Curve= 0 ,0
Exp/Cntr=0.3,0.1

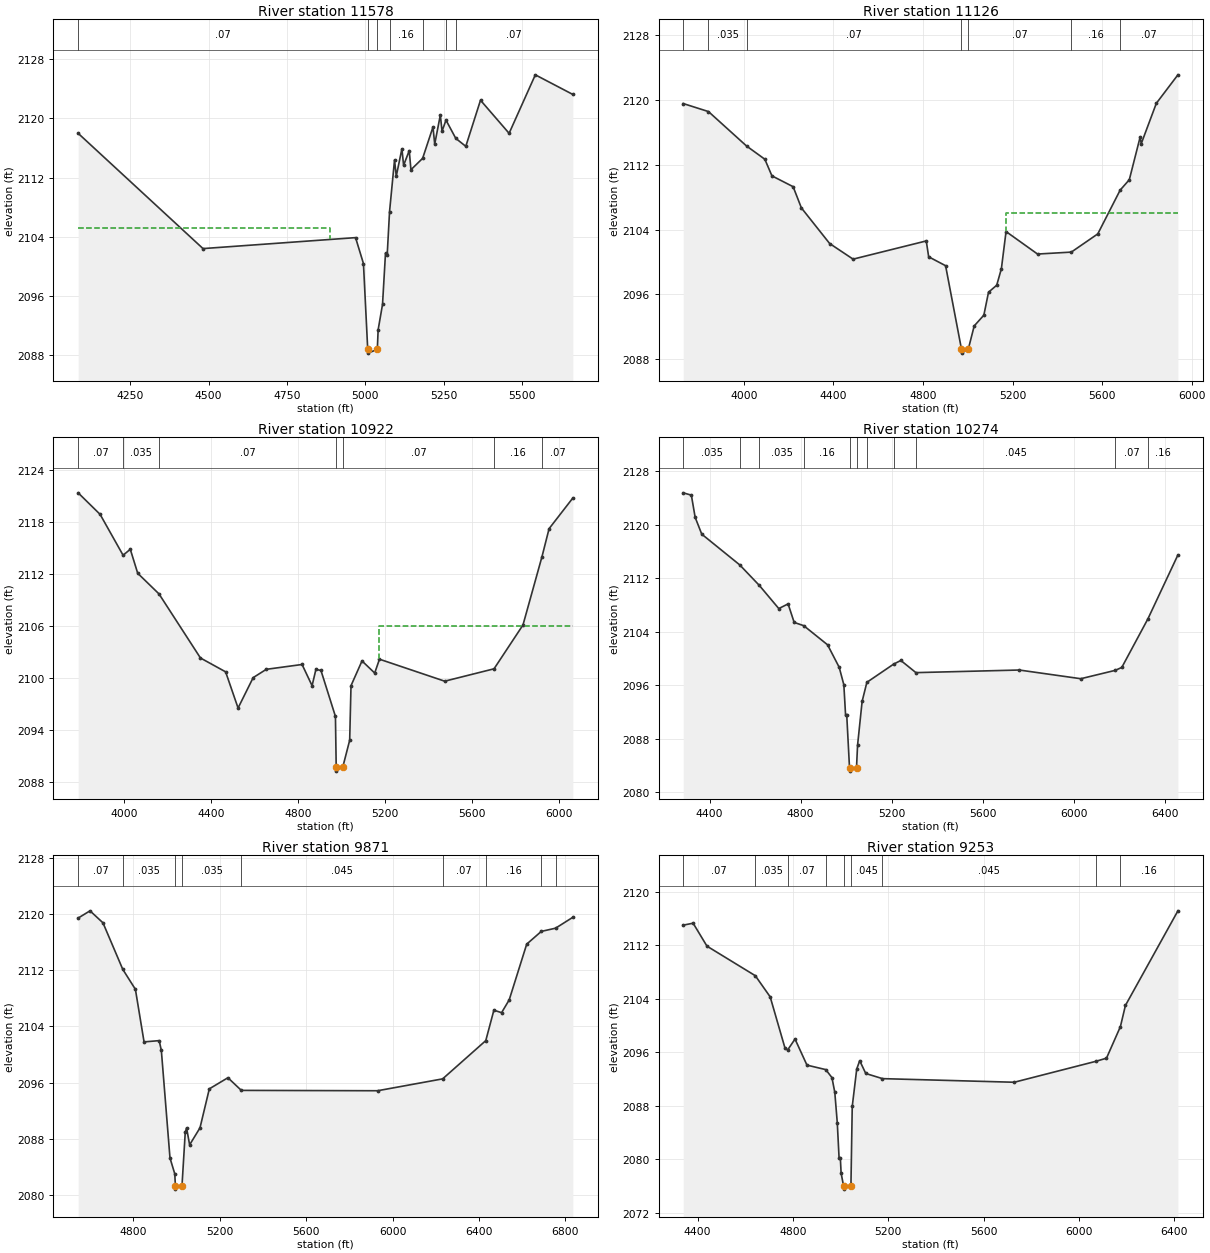
Type RM Length L Ch R = 1 ,11578   ,452,452,452
BEGIN DESCRIPTION:
Mapping XS e67e0e38
END DESCRIPTION:
XS GIS Cut Line= 3
      1458140.95      6824640.82      1458286.79       6823751.9
      1458557.03      6823131.73
#Sta/Elev= 30
    4084 2117.99  4482.1 2102.42  4968.5  2103.9  4993.7  2100.4  5007.3  2088.8
  5007.8  2088.3  5037.9  2088.8  5040.5 2091.44  5054.5 2094.88    5064 2101.81
  5069.4 2101.56  5076.9 2107.41  5092.8 2114.39  5098.3  2112.2  5116.3  2115.9
  5121.7 2113.67  5139.7 2115.65  5145.1 2113.07  5182.4 2114.61  5215.4 2118.84
  5220.9 2116.53  5238.8 2120.45  5244.3 2118.28  5256.9 2119.77    5288 2117.31
    5320 2116.23  5366.9 2122.46  5458.1 2117.99  5541.7 2125.89  5661.3 2123.24
#Mann= 7 ,-1 , 0
    4084     .07       0  5007.3     .07       0  5037.9     .07       0
  5076.9     .16       0  5182.4     .07       0  5256.9     .16       0
    5288     .07       0
#XS Ineff= 2 , 0
       0  4887.4 2105.21               0
Permanent Ineff=
       F       F
Bank Sta=5007.3,5037.9
XS Rating Curve= 0 ,0
Exp/Cntr=0.3,0.1

Type RM Length L Ch R = 1 ,11126   ,204,204,204
BEGIN DESCRIPTION:
Mapping XS 49362dca
END DESCRIPTION:
XS GIS Cut Line= 4
      1458213.88      6825077.41      1458569.77      6824014.06
      1458799.81      6823731.94      1458877.85       6823012.2
#Sta/Elev= 30
  3729.4 2119.56  3842.1 2118.57    4012 2114.32  4093.9 2112.68  4125.5 2110.63
  4220.2 2109.29  4257.1 2106.67  4383.3 2102.27    4488 2100.34  4814.8 2102.59
  4825.5 2100.63  4901.1 2099.53    4972 2089.23  4972.5 2088.73  5002.6 2089.23
  5028.9 2092.09    5072 2093.42  5092.8 2096.25  5129.5 2097.12  5150.3 2099.16
  5171.1 2103.75  5311.8 2100.97  5462.7 2101.21  5580.8 2103.46  5680.8 2108.87
  5721.6 2110.15    5770 2115.42    5775 2114.61  5842.3 2119.59  5938.7 2123.11
#Mann= 7 ,-1 , 0
  3729.4     .07       0  3842.1    .035       0    4012     .07       0
    4972     .07       0  5002.6     .07       0  5462.7     .16       0
  5680.8     .07       0
#XS Ineff= 2 , 0
       0                  5171.1       0    2106
Permanent Ineff=
       F       F
Bank Sta=4972,5002.6
XS Rating Curve= 0 ,0
Exp/Cntr=0.3,0.1

Type RM Length L Ch R = 1 ,10922   ,648,648,648
BEGIN DESCRIPTION:
Mapping XS dcd74cf1
END DESCRIPTION:
XS GIS Cut Line= 4
      1458309.35      6825146.88      1458804.15      6824048.78
      1458964.74      6823818.74      1458947.38       6823028.8
#Sta/Elev= 30
  3787.2 2121.41  3888.2 2118.92  3993.9  2114.2    4027 2114.89  4061.1 2112.12
  4159.1 2109.73  4349.7 2102.33  4465.4 2100.73  4522.7 2096.55  4592.1 2100.06
  4652.5 2101.02    4817 2101.58  4863.1 2099.13  4880.7 2101.01  4903.9 2100.89
  4970.5 2095.58    4974 2089.76  4974.5 2089.26  5004.6 2089.76    5036 2092.83
  5042.1 2099.13  5092.7 2101.99  5151.1 2100.59    5173 2102.19    5473 2099.65
  5699.9 2101.08    5833 2106.14  5920.6 2114.05  5953.1 2117.27  6062.3 2120.81
#Mann= 7 ,-1 , 0
  3787.2     .07       0  3993.9    .035       0  4159.1     .07       0
    4974     .07       0  5004.6     .07       0  5699.9     .16       0
  5920.6     .07       0
#XS Ineff= 2 , 0
       0                    5173       0    2106
Permanent Ineff=
       F       F
Bank Sta=4974,5004.6
XS Rating Curve= 0 ,0
Exp/Cntr=0.3,0.1

Type RM Length L Ch R = 1 ,10274   ,403,403,403
BEGIN DESCRIPTION:
Mapping XS 2bf84921
END DESCRIPTION:
XS GIS Cut Line= 3
      1459083.17      6825189.24      1459225.02      6824487.94
      1459193.83      6823031.67
#Sta/Elev= 30
  4284.5 2124.76  4320.2 2124.41  4336.8  2121.1  4365.8 2118.58  4532.6 2113.98
  4618.7 2110.91  4704.1 2107.45  4744.9 2108.15  4771.6 2105.38  4813.7 2104.89
  4918.3 2102.03  4969.3 2098.67  4989.7 2096.06  4997.4 2091.48  5002.5 2091.48
  5014.6 2083.64  5015.1 2083.14  5045.3 2083.64    5050 2087.02    5070 2093.57
  5090.8 2096.42  5208.2 2099.14    5240 2099.69  5306.2 2097.87  5760.1 2098.26
  6030.2 2096.96  6181.3 2098.21  6210.2 2098.65  6324.8 2105.91  6456.6 2115.47
#Mann= 11 ,-1 , 0
  4284.5    .035       0  4532.6     .07       0  4618.7    .035       0
  4813.7     .16       0  5014.6     .07       0  5045.3     .16       0
  5090.8    .045       0  5208.2    .035       0  5306.2    .045       0
  6181.3     .07       0  6324.8     .16       0
Bank Sta=5014.6,5045.3
XS Rating Curve= 0 ,0
Exp/Cntr=0.3,0.1

Type RM Length L Ch R = 1 ,9871    ,618,618,618
BEGIN DESCRIPTION:
Mapping XS 3656645f
END DESCRIPTION:
XS GIS Cut Line= 3
      1459633.14      6824942.87       1459628.8      6824495.83
      1459338.01      6822677.29
#Sta/Elev= 30
  4545.4 2119.42  4600.3 2120.45  4660.3 2118.74  4751.9 2112.12  4810.3 2109.28
  4850.3  2101.8  4920.3 2101.98  4930.3 2100.59  4970.3 2085.28  4992.5 2083.02
  4995.2 2081.35  4995.7 2080.85  5025.9 2081.35  5040.9 2088.93  5047.1 2089.56
  5061.1 2087.15  5109.1 2089.57  5152.3 2095.12  5238.3  2096.7  5300.4  2094.9
  5930.9 2094.85  6231.8 2096.54  6431.3 2101.98  6468.8 2106.31  6504.5 2105.96
  6539.7 2107.78  6620.7 2115.71  6688.1 2117.52  6754.3 2117.98  6834.1 2119.53
#Mann= 9 ,-1 , 0
  4545.4     .07       0  4751.9    .035       0  4995.2    .035       0
  5025.9    .035       0  5300.4    .045       0  6231.8     .07       0
  6431.3     .16       0  6688.1     .07       0  6754.3    .035       0
Bank Sta=4995.2,5025.9
XS Rating Curve= 0 ,0
Exp/Cntr=0.3,0.1

Type RM Length L Ch R = 1 ,9253    ,386,386,386
BEGIN DESCRIPTION:
Mapping XS 96c9c65c
END DESCRIPTION:
XS GIS Cut Line= 3
      1460288.52      6824877.75      1460101.89      6824248.43
      1459685.69      6822891.43
#Sta/Elev= 30
    4340 2115.01  4381.5  2115.3  4439.6 2111.87  4642.4 2107.45  4704.8 2104.29
  4767.4 2096.58  4778.2 2096.35  4809.1 2097.98  4859.2 2094.08    4938 2093.41
  4964.1 2092.21    4976 2090.01  4986.4 2085.47    4994 2080.16  4999.3 2080.16
  5002.5 2077.93  5012.7 2076.04  5013.2 2075.54  5043.7 2076.04  5049.2  2087.9
    5068 2093.49  5080.5 2094.75  5105.9 2092.83  5176.1 2092.06    5729 2091.52
  6072.8 2094.66  6116.1 2095.12  6174.5 2099.84  6195.5    2103  6415.8 2117.15
#Mann= 9 ,-1 , 0
    4340     .07       0  4642.4    .035       0  4778.2     .07       0
    4938    .045       0  5012.7    .045       0  5043.7    .045       0
  5176.1    .045       0  6072.8     .07       0  6174.5     .16       0
#XS Ineff= 2 , 0
       0                  5080.5       0 2094.75
Permanent Ineff=
       F       F
Bank Sta=5012.7,5043.7
XS Rating Curve= 0 ,0
Exp/Cntr=0.3,0.1

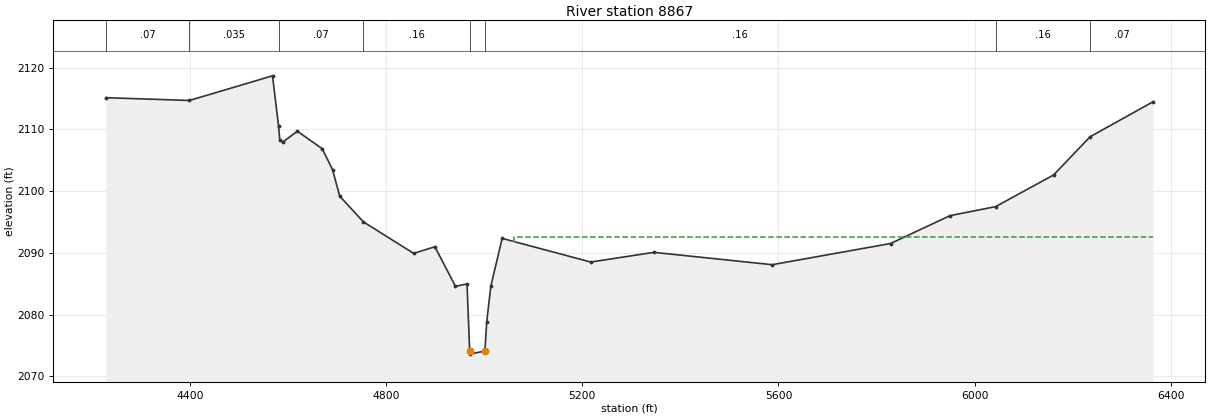
Type RM Length L Ch R = 1 ,8867    ,506,506,506
BEGIN DESCRIPTION:
Mapping XS 290a00f6
END DESCRIPTION:
XS GIS Cut Line= 3
      1460852.74      6824673.75      1460410.05      6824035.76
      1459919.81      6822768.94
#Sta/Elev= 30
  4228.7 2115.13  4399.1 2114.68  4568.6 2118.67    4581 2110.48  4583.5 2108.21
  4589.5 2107.95  4619.3  2109.7  4669.9 2106.87  4690.9 2103.49  4705.7 2099.17
    4754 2095.02  4856.4 2089.92  4899.6    2091  4941.6 2084.58  4965.1 2084.98
  4970.5 2074.11    4971 2073.61  5001.6 2074.11  5005.2 2078.81  5013.6  2084.6
  5036.7 2092.35  5217.3 2088.52    5346 2090.09  5587.2 2088.09  5828.5 2091.52
  5949.6 2096.03  6042.6 2097.49  6160.9 2102.62  6235.2  2108.8  6363.6 2114.47
#Mann= 8 ,-1 , 0
  4228.7     .07       0  4399.1    .035       0    4581     .07       0
    4754     .16       0  4970.5     .07       0  5001.6     .16       0
  6042.6     .16       0  6235.2     .07       0
#XS Ineff= 2 , 0
       0                  5061.3       0 2092.55
Permanent Ineff=
       F       F
Bank Sta=4970.5,5001.6
XS Rating Curve= 0 ,0
Exp/Cntr=0.3,0.1