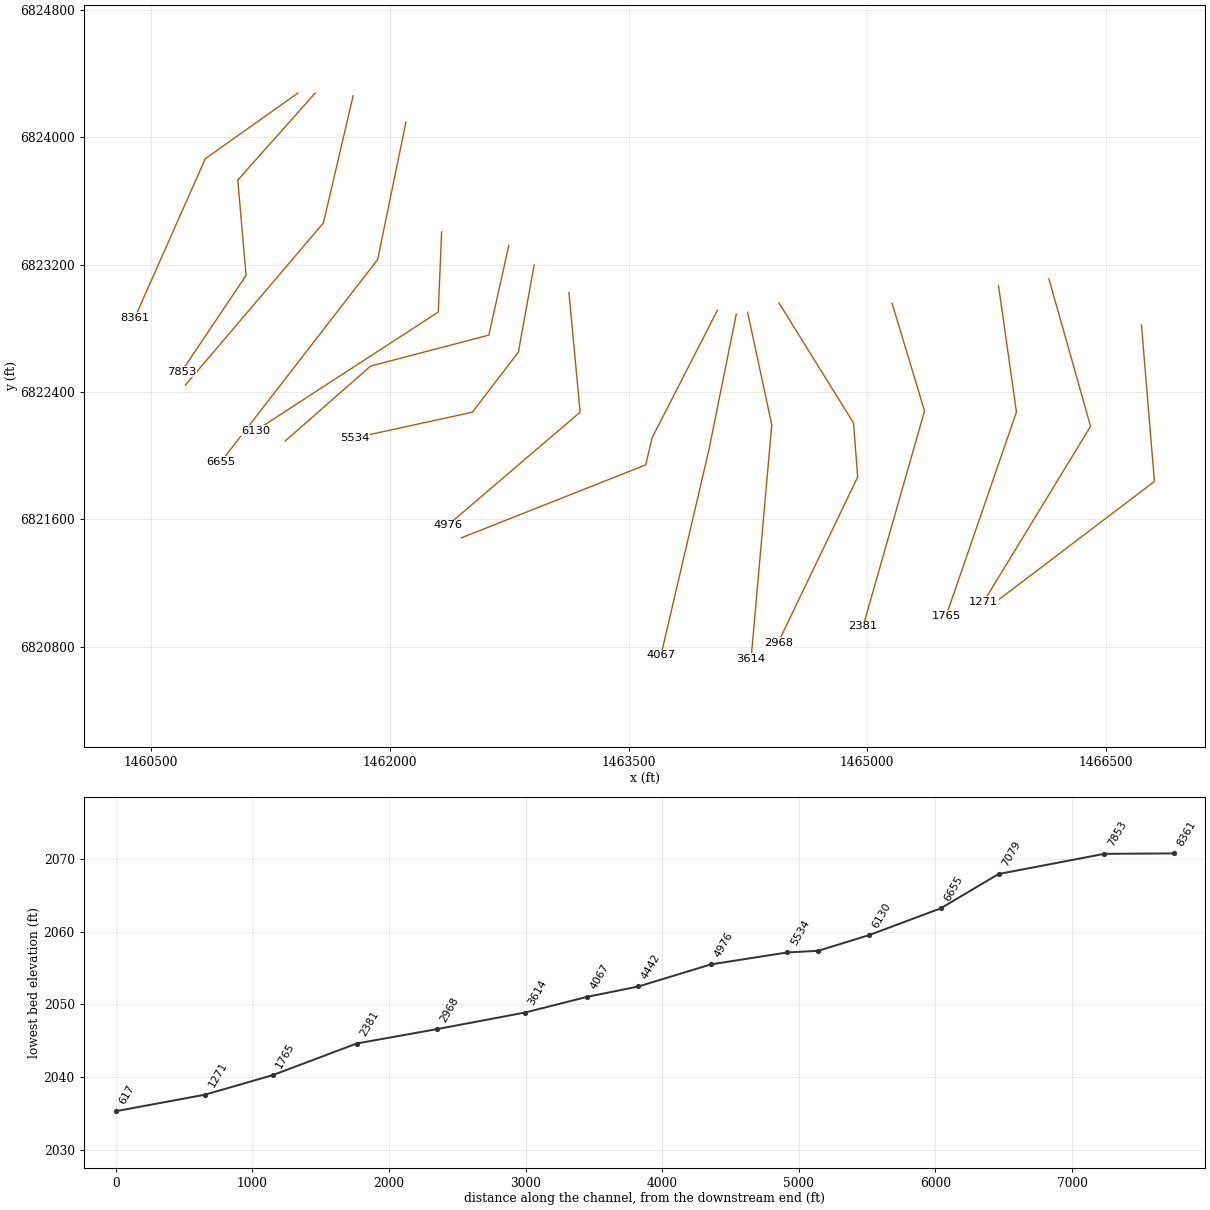
HEC-RAS study WEAVER SPRINGS CREEK.prj: WEAVER SPRINGS CREEK Base Level Engineering

--- WEAVER SPRINGS CREEK.g01 (geometry) --- (continued)

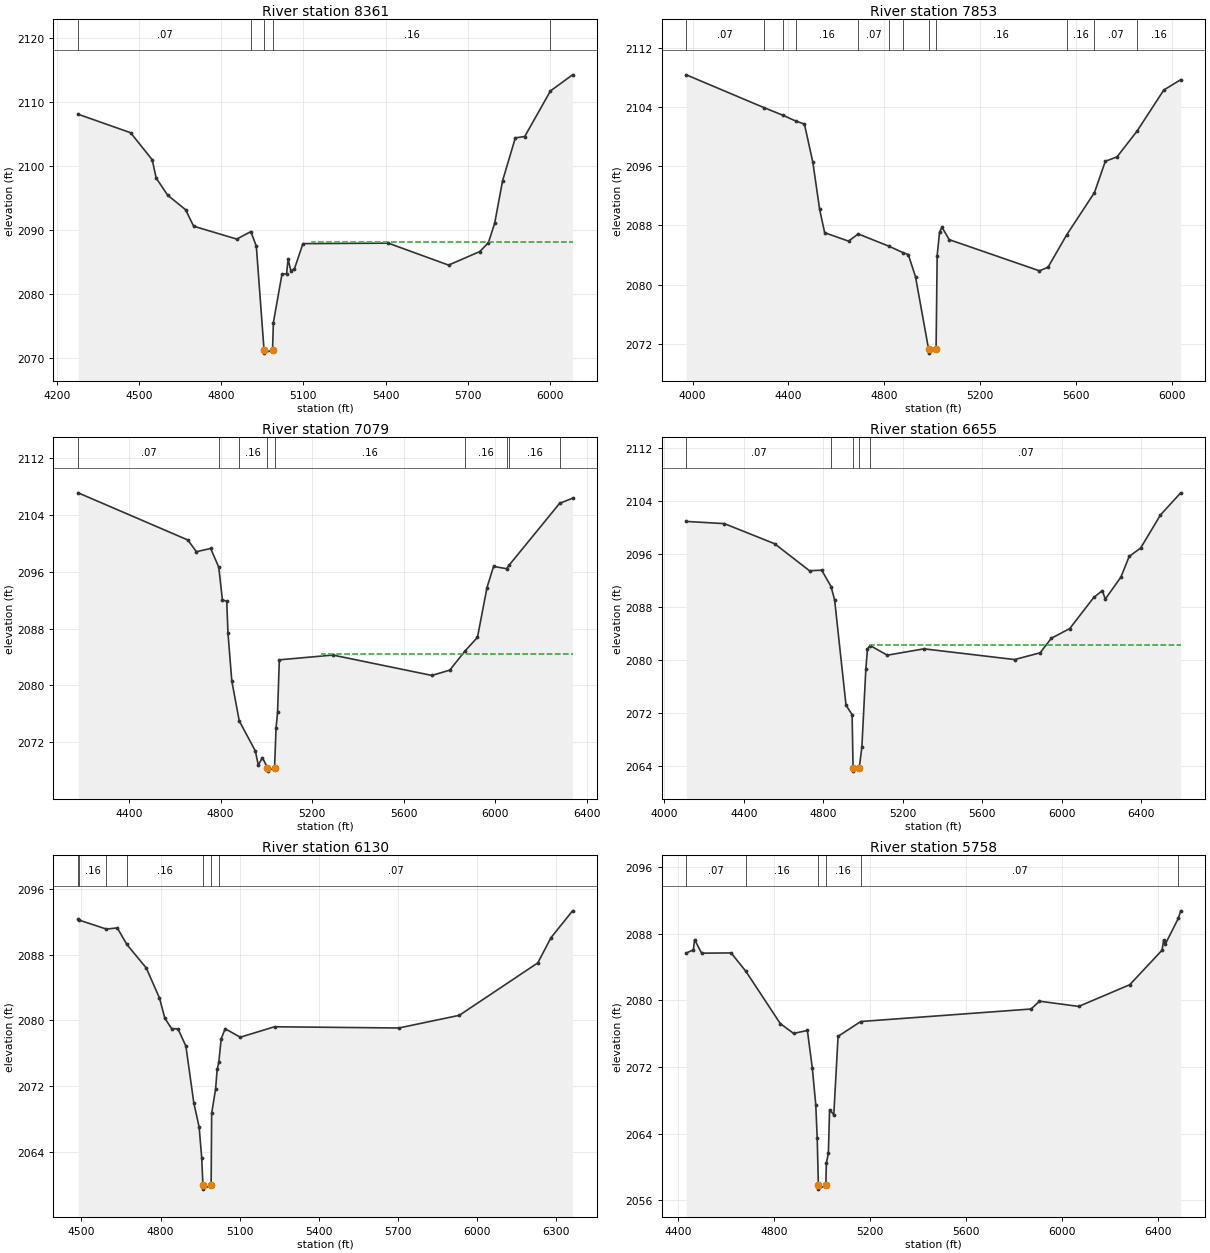
Type RM Length L Ch R = 1 ,8361    ,508,508,508
BEGIN DESCRIPTION:
Mapping XS 04d334c3
END DESCRIPTION:
XS GIS Cut Line= 3
       1461421.3      6824278.78      1460839.74      6823866.49
      1460397.03      6822868.23
#Sta/Elev= 30
  4277.7 2108.06  4469.3 2105.17    4548 2100.96  4562.8 2098.08  4604.6 2095.42
  4669.8 2093.16  4699.4 2090.58  4856.9 2088.57  4908.1 2089.74  4928.2 2087.46
  4956.3 2071.27  4956.8 2070.77  4987.4 2071.27  4990.4 2075.53  5021.7 2083.06
  5038.7 2083.19  5044.2  2085.4  5054.6 2083.57  5067.5 2083.95  5098.3 2087.86
  5409.7 2087.94  5630.1 2084.51  5743.7 2086.62  5775.2 2087.99  5798.4 2091.06
  5827.2 2097.69  5873.7 2104.37    5908 2104.58  6001.9  2111.7  6082.6 2114.21
#Mann= 5 ,-1 , 0
  4277.7     .07       0  4908.1     .16       0  4956.3     .07       0
  4987.4     .16       0  6001.9     .16       0
#XS Ineff= 2 , 0
       0                  5131.1       0 2088.05
Permanent Ineff=
       F       F
Bank Sta=4956.3,4987.4
XS Rating Curve= 0 ,0
Exp/Cntr=0.3,0.1

Type RM Length L Ch R = 1 ,7853    ,774,774,774
BEGIN DESCRIPTION:
Mapping XS 9fe179a6
END DESCRIPTION:
XS GIS Cut Line= 4
      1461529.84      6824278.81      1461043.73      6823731.94
      1461095.81      6823132.98      1460688.89      6822526.92
#Sta/Elev= 30
  3973.6  2108.4  4298.4 2103.95  4376.6 2102.93  4431.9 2102.12  4466.6 2101.73
  4501.7 2096.56  4530.1 2090.17    4551 2087.02  4650.5 2085.88  4691.1 2086.85
  4819.9 2085.18  4877.2 2084.33    4900 2084.05  4930.1 2081.05  4984.8 2071.21
  4985.3 2070.71  5015.9 2071.21  5020.4 2083.93  5030.4  2087.1  5040.5 2087.77
  5070.6 2086.08  5446.8 2081.86  5482.8 2082.33  5560.1 2086.69  5676.8 2092.46
    5722 2096.69  5770.8 2097.29  5854.2 2100.77  5965.9 2106.34  6036.5 2107.74
#Mann= 12 ,-1 , 0
  3973.6     .07       0  4298.4     .16       0  4376.6     .07       0
  4431.9     .16       0  4691.1     .07       0  4819.9     .16       0
  4877.2     .16       0  4984.8     .07       0  5015.9     .16       0
  5560.1     .16       0  5676.8     .07       0  5854.2     .16       0
#XS Ineff= 2 , 0
       0                  5040.5       0 2087.77
Permanent Ineff=
       F       F
Bank Sta=4984.8,5015.9
XS Rating Curve= 0 ,0
Exp/Cntr=0.3,0.1

Type RM Length L Ch R = 1 ,7079    ,424,424,424
BEGIN DESCRIPTION:
Mapping XS 212fc6cc
END DESCRIPTION:
XS GIS Cut Line= 3
      1461768.57      6824261.49      1461581.93      6823462.84
      1460713.94      6822442.96
#Sta/Elev= 30
  4178.2 2107.11  4657.3 2100.47  4694.7 2098.82  4756.9 2099.28  4792.3 2096.65
  4808.2 2092.07  4827.3 2091.82  4832.5 2087.41  4849.3 2080.63  4881.9    2075
    4952 2070.78  4965.1 2068.78  4982.8 2069.82    5005 2068.43  5005.5 2067.93
  5036.1 2068.43  5042.6 2073.99  5049.2 2076.19  5056.9  2083.6  5290.8 2084.27
  5723.4  2081.4  5801.4 2082.15  5866.7  2084.8  5922.2 2086.76  5963.9 2093.77
  5992.5 2096.75  6049.3 2096.43  6061.9 2096.98  6281.1 2105.63  6337.6 2106.35
#Mann= 9 ,-1 , 0
  4178.2     .07       0  4792.3     .16       0  4881.9     .16       0
    5005     .07       0  5036.1     .16       0  5866.7     .16       0
  6049.3     .07       0  6061.9     .16       0  6281.1     .07       0
#XS Ineff= 2 , 0
       0                  5241.1       0 2084.42
Permanent Ineff=
       F       F
Bank Sta=5005,5036.1
XS Rating Curve= 0 ,0
Exp/Cntr=0.3,0.1

Type RM Length L Ch R = 1 ,6655    ,525,525,525
BEGIN DESCRIPTION:
Mapping XS a2edf2da
END DESCRIPTION:
XS GIS Cut Line= 3
      1462100.44      6824095.62      1461922.49      6823231.94
      1460938.31       6821961.6
#Sta/Elev= 30
  4109.7 2100.91  4301.3 2100.58  4554.6 2097.54  4730.1 2093.46  4791.3 2093.55
  4838.5 2091.08  4856.5 2089.03  4913.9 2073.14  4944.5 2071.73  4949.3  2063.7
  4949.8  2063.2  4980.5  2063.7  4993.6 2066.82  5013.7 2078.68  5021.8 2081.64
  5035.6 2082.16  5121.5 2080.71  5306.1 2081.67  5762.4 2080.05    5891 2081.07
  5947.1 2083.26  6040.4 2084.74  6160.8 2089.43  6204.2 2090.46  6218.7 2089.18
  6297.5  2092.5  6339.1 2095.62  6397.1  2096.9  6496.7 2101.89  6598.5 2105.23
#Mann= 5 ,-1 , 0
  4109.7     .07       0  4838.5     .16       0  4949.3     .07       0
  4980.5     .16       0  5035.6     .07       0
#XS Ineff= 2 , 0
       0                  5034.5       0 2082.22
Permanent Ineff=
       F       F
Bank Sta=4949.3,4980.5
XS Rating Curve= 0 ,0
Exp/Cntr=0.3,0.1

Type RM Length L Ch R = 1 ,6130    ,372,372,372
BEGIN DESCRIPTION:
Mapping XS a4f38de0
END DESCRIPTION:
XS GIS Cut Line= 3
      1462324.69      6823406.18      1462303.86      6822902.69
      1461154.55      6822156.16
#Sta/Elev= 30
  4487.3  2092.3  4488.9 2092.21  4594.6 2091.09  4635.6 2091.24  4671.7 2089.24
  4745.7 2086.36  4795.7 2082.72  4815.8 2080.28  4841.7    2079  4865.8 2078.98
  4895.8 2076.88  4925.9 2069.97  4945.9 2067.08  4955.9 2063.27  4960.3 2060.01
  4960.8 2059.51  4991.5 2060.01  4993.5 2068.71  5008.4 2071.66  5014.3 2074.04
  5020.6 2074.93  5029.5 2077.75  5044.6 2078.99    5102 2077.96  5231.8 2079.23
    5703 2079.08  5932.4 2080.62    6230 2086.99  6279.7 2090.04  6361.7 2093.31
#Mann= 7 ,-1 , 0
  4487.3     .07       0  4488.9     .16       0  4594.6     .07       0
  4671.7     .16       0  4960.3     .07       0  4991.5     .16       0
  5020.6     .07       0
Bank Sta=4960.3,4991.5
XS Rating Curve= 0 ,0
Exp/Cntr=0.3,0.1

Type RM Length L Ch R = 1 ,5758    ,224,224,224
BEGIN DESCRIPTION:
Mapping XS bf1c489a
END DESCRIPTION:
XS GIS Cut Line= 4
      1462746.79      6823320.26      1462621.78      6822757.73
      1461878.73      6822563.28      1461341.61        6822092.
#Sta/Elev= 30
  4435.1 2085.68  4464.7 2086.07  4469.8  2087.3  4498.9 2085.67  4621.8  2085.7
  4683.1  2083.5  4826.7 2077.22  4882.2 2076.04  4939.4  2076.4  4959.9 2071.91
  4974.4 2067.47  4980.3 2063.53  4985.2 2057.86  4985.7 2057.36  5016.4 2057.86
  5018.4 2060.48  5026.8 2061.64  5031.9 2066.89  5049.4 2066.28  5067.2 2075.69
  5161.8 2077.47  5870.8 2078.97    5906 2079.91  6069.2 2079.28  6281.7 2081.88
  6416.5 2086.03  6423.1 2087.28  6430.7  2086.8  6484.3 2089.86    6494 2090.75
#Mann= 6 ,-1 , 0
  4435.1     .07       0  4683.1     .16       0  4985.2     .07       0
  5016.4     .16       0  5161.8     .07       0  6484.3    .035       0
Bank Sta=4985.2,5016.4
XS Rating Curve= 0 ,0
Exp/Cntr=0.3,0.1

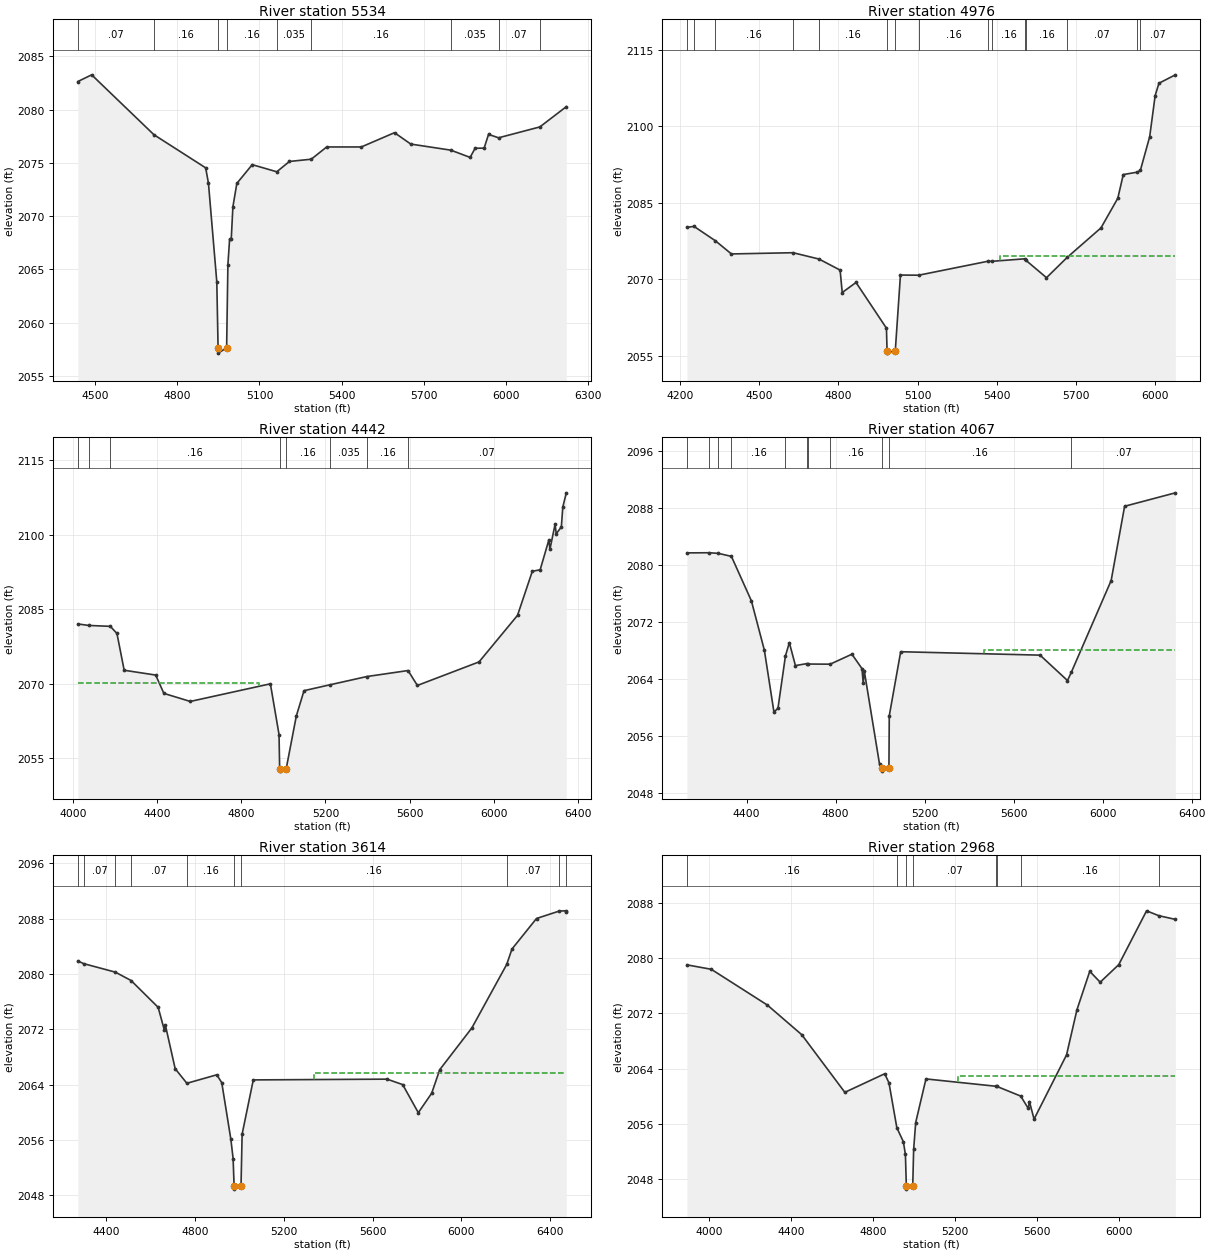
Type RM Length L Ch R = 1 ,5534    ,558,558,558
BEGIN DESCRIPTION:
Mapping XS a8c720be
END DESCRIPTION:
XS GIS Cut Line= 4
      1462906.24      6823197.74      1462807.28      6822650.83
      1462518.22      6822273.23      1461781.55      6822112.65
#Sta/Elev= 30
  4436.1 2082.63  4486.6 2083.26  4714.2 2077.64  4903.3 2074.53  4913.5 2073.09
    4944 2063.83  4948.7 2057.64  4949.2 2057.14  4979.9 2057.64  4984.6 2065.45
  4990.8 2067.83  4996.8 2067.83  5002.8 2070.87  5017.3 2073.07  5073.5 2074.83
  5163.2 2074.16  5209.6 2075.13  5289.2 2075.34  5345.6 2076.49  5472.2 2076.49
  5593.5 2077.83  5653.1 2076.76  5799.3 2076.19  5869.9 2075.51  5888.2 2076.37
  5921.1 2076.38  5937.2 2077.67  5973.9 2077.35  6124.7 2078.37  6221.4 2080.27
#Mann= 9 ,-1 , 0
  4436.1     .07       0  4714.2     .16       0  4948.7     .07       0
  4979.9     .16       0  5163.2    .035       0  5289.2     .16       0
  5799.3    .035       0  5973.9     .07       0  6124.7     .16       0
#XS Ineff= 2 , 0
       0                  5593.5       0 2077.83
Permanent Ineff=
       F       F
Bank Sta=4948.7,4979.9
XS Rating Curve= 0 ,0
Exp/Cntr=0.3,0.1

Type RM Length L Ch R = 1 ,4976    ,534,534,534
BEGIN DESCRIPTION:
Mapping XS 408d6438
END DESCRIPTION:
XS GIS Cut Line= 3
      1463124.98      6823025.88       1463195.3      6822273.23
        1462363.      6821562.33
#Sta/Elev= 30
  4225.9 2080.17  4252.7 2080.37  4333.8 2077.54  4394.5 2074.96  4628.1  2075.2
  4726.2 2073.96  4806.3 2071.79  4814.3 2067.39  4866.6 2069.36  4981.8  2060.4
  4984.2    2056  4984.7  2055.5  5015.4    2056  5034.9 2070.82  5104.3 2070.79
  5367.8 2073.54  5380.4 2073.51  5507.5 2074.01  5510.7 2073.69  5588.2  2070.3
  5666.5 2074.28  5794.6 2080.07  5858.3 2085.88  5879.1 2090.53  5932.6 2091.01
  5943.8 2091.35  5979.1 2097.95  5999.9 2106.03  6014.2 2108.45  6076.4  2110.1
#Mann= 15 ,-1 , 0
  4225.9     .16       0  4252.7     .07       0  4333.8     .16       0
  4628.1     .07       0  4726.2     .16       0  4984.2     .07       0
  5015.4     .16       0  5104.3     .16       0  5367.8     .07       0
  5380.4     .16       0  5507.5     .07       0  5510.7     .16       0
  5666.5     .07       0  5932.6     .16       0  5943.8     .07       0
#XS Ineff= 2 , 0
       0                  5411.5       0  2074.6
Permanent Ineff=
       F       F
Bank Sta=4984.2,5015.4
XS Rating Curve= 0 ,0
Exp/Cntr=0.3,0.1

Type RM Length L Ch R = 1 ,4442    ,375,375,375
BEGIN DESCRIPTION:
Mapping XS 3ee6c0db
END DESCRIPTION:
XS GIS Cut Line= 4
       1464058.1      6822913.34      1463647.94      6822112.99
      1463607.58      6821941.98      1462449.57      6821483.77
#Sta/Elev= 30
  4023.6 2082.08  4075.5 2081.78    4178  2081.6  4209.4 2080.16  4243.7 2072.76
  4393.5 2071.79  4432.3  2068.1  4557.7 2066.48  4938.3 2070.03  4979.4 2059.81
  4982.3 2052.95  4982.8 2052.45  5013.5 2052.95  5061.6 2063.57  5098.1 2068.65
  5223.3 2069.85  5396.3 2071.49  5592.2  2072.7  5636.6  2069.7  5929.5 2074.44
  6112.3 2083.81  6182.6 2092.68  6219.9 2092.99    6261 2098.97  6266.4 2097.13
  6290.8 2102.16  6296.1 2100.23  6320.5 2101.61  6327.4 2105.61    6344 2108.48
#Mann= 8 ,-1 , 0
  4023.6     .16       0  4075.5    .045       0    4178     .16       0
  4982.3     .07       0  5013.5     .16       0  5223.3    .035       0
  5396.3     .16       0  5592.2     .07       0
#XS Ineff= 2 , 0
       0  4883.6 2070.23               0
Permanent Ineff=
       F       F
Bank Sta=4982.3,5013.5
XS Rating Curve= 0 ,0
Exp/Cntr=0.3,0.1

Type RM Length L Ch R = 1 ,4067    ,453,453,453
BEGIN DESCRIPTION:
Mapping XS 20b710f1
END DESCRIPTION:
XS GIS Cut Line= 3
      1464176.84      6822889.26      1464005.03      6822037.92
       1463703.5      6820745.84
#Sta/Elev= 30
  4131.5 2081.69    4232 2081.71  4273.1 2081.62  4331.5  2081.2  4421.2 2074.96
  4479.6 2068.02  4522.7 2059.32  4540.8 2059.86  4574.5 2067.23  4591.9 2069.07
  4619.2 2065.85  4670.6 2066.13    4675 2066.07  4775.4 2066.05  4873.1 2067.45
  4918.3 2065.43  4923.9  2063.4    4929 2065.04  4997.4 2051.97  5008.3 2051.52
  5008.8 2051.02  5039.5 2051.52    5041  2058.8  5092.3  2067.8  5718.7 2067.32
    5842 2063.75  5859.3 2064.92  6038.2  2077.8  6098.7 2088.24  6326.8 2090.13
#Mann= 11 ,-1 , 0
  4131.5    .045       0    4232     .16       0  4273.1    .045       0
  4331.5     .16       0  4574.5     .07       0  4670.6     .16       0
    4675     .07       0  4775.4     .16       0  5008.3     .07       0
  5039.5     .16       0  5859.3     .07       0
#XS Ineff= 2 , 0
       0  4591.9 2069.07  5464.7       0 2067.99
Permanent Ineff=
       F       F
Bank Sta=5008.3,5039.5
XS Rating Curve= 0 ,0
Exp/Cntr=0.3,0.1

Type RM Length L Ch R = 1 ,3614    ,646,646,646
BEGIN DESCRIPTION:
Mapping XS c84360c0
END DESCRIPTION:
XS GIS Cut Line= 3
        1464248.      6822901.43      1464399.92      6822193.92
      1464269.88       6820724.4
#Sta/Elev= 30
  4272.9 2081.88  4299.2 2081.49  4441.7 2080.26  4512.5 2079.05  4634.4 2075.17
  4661.7 2071.96  4666.8 2072.62  4711.1 2066.29  4763.8 2064.18  4898.4 2065.41
  4920.8 2064.27  4961.7 2056.09  4971.9  2053.3  4976.3 2049.37  4976.8 2048.87
  5007.5 2049.37  5012.5 2056.83  5062.7 2064.67  5665.1 2064.78  5735.3 2063.99
  5805.6 2059.93  5865.8 2062.74  5902.1 2066.15  6046.5 2072.18  6203.5 2081.37
  6227.2  2083.6  6337.7 2088.02  6440.4  2089.1    6470 2089.13  6471.8 2089.02
#Mann= 10 ,-1 , 0
  4272.9    .045       0  4299.2     .07       0  4441.7     .16       0
  4512.5     .07       0  4763.8     .16       0  4976.3     .07       0
  5007.5     .16       0  6203.5     .07       0  6440.4     .16       0
    6470     .07       0
#XS Ineff= 2 , 0
       0  4898.4 2065.41  5337.4       0 2065.62
Permanent Ineff=
       F       F
Bank Sta=4976.3,5007.5
XS Rating Curve= 0 ,0
Exp/Cntr=0.3,0.1

Type RM Length L Ch R = 1 ,2968    ,587,587,587
BEGIN DESCRIPTION:
Mapping XS dd923ce8
END DESCRIPTION:
XS GIS Cut Line= 4
      1464445.04      6822960.16      1464913.81      6822204.91
      1464939.85      6821866.37      1464439.94      6820824.88
#Sta/Elev= 30
  3893.2 2079.04    4012  2078.4  4285.9 2073.22  4453.7 2068.93  4663.9 2060.59
  4858.5 2063.28  4879.3 2061.96  4917.7 2055.47  4949.5 2053.44  4959.5 2051.61
    4964 2047.08  4964.5 2046.58  4995.3 2047.08  4999.7 2052.33  5009.7 2056.22
  5059.8 2062.53  5401.1 2061.47  5405.6 2061.45  5521.9 2060.05  5559.2 2058.26
  5564.7 2059.26  5587.4 2056.71  5745.9 2066.01  5796.7 2072.55  5859.1  2078.1
    5910 2076.53  6000.6 2079.07  6136.4 2086.86  6195.7 2086.16  6276.9 2085.62
#Mann= 8 ,-1 , 0
  3893.2     .16       0  4917.7     .07       0    4964     .07       0
  4995.3     .07       0  5401.1     .16       0  5405.6     .07       0
  5521.9     .16       0  6195.7     .07       0
#XS Ineff= 2 , 0
       0  4858.5 2063.28  5213.9       0 2062.99
Permanent Ineff=
       F       F
Bank Sta=4964,4995.3
XS Rating Curve= 0 ,0
Exp/Cntr=0.3,0.1

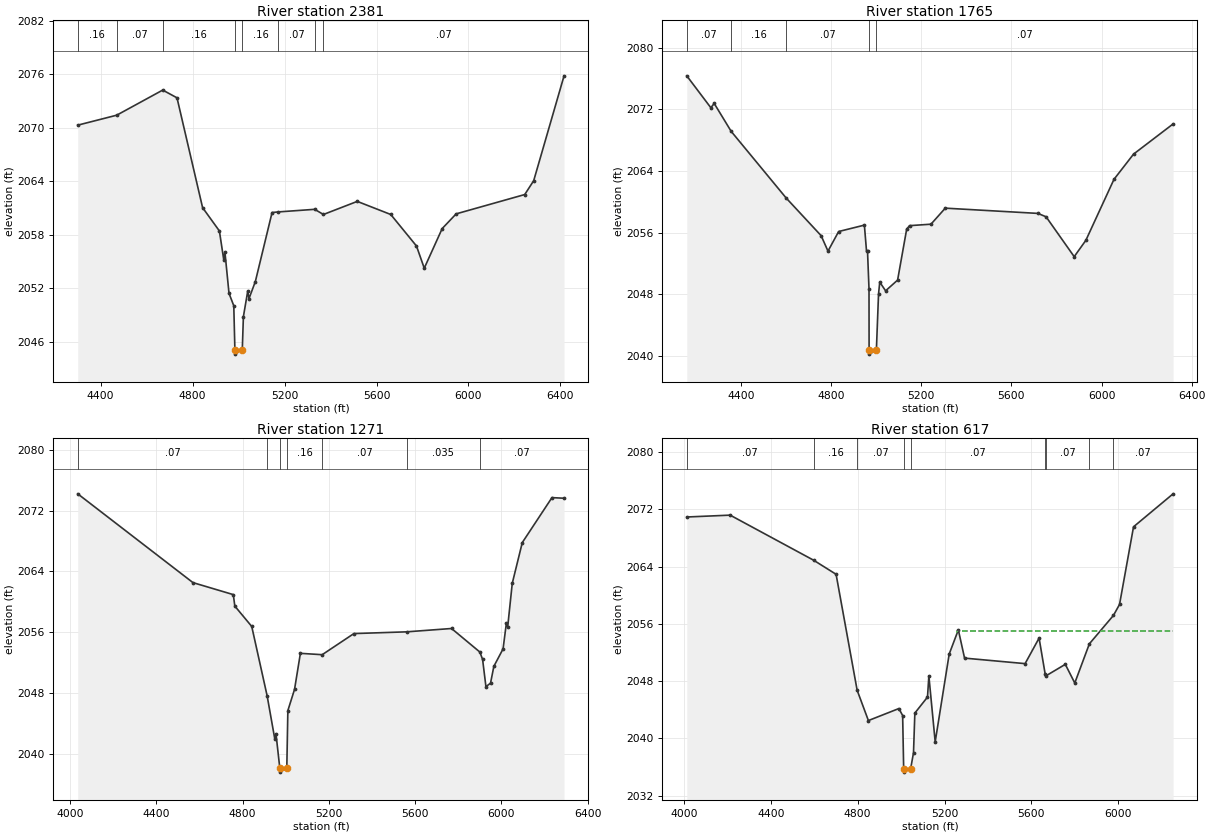
Type RM Length L Ch R = 1 ,2381    ,616,616,616
BEGIN DESCRIPTION:
Mapping XS a1b4468c
END DESCRIPTION:
XS GIS Cut Line= 3
      1465155.92      6822957.98      1465359.92      6822280.87
      1464973.62      6820926.67
#Sta/Elev= 30
  4300.3 2070.31  4469.9 2071.43    4670 2074.25  4732.1 2073.38  4843.4 2061.05
  4916.5 2058.43  4935.3 2055.22  4940.5 2056.07  4958.3 2051.43  4979.1 2050.03
  4983.9  2045.1  4984.4  2044.6  5016.1  2045.1  5020.9 2048.81    5040 2051.71
  5045.2 2050.83  5072.9 2052.75  5145.6  2060.5  5173.5 2060.57    5331 2060.86
    5369 2060.28  5516.2 2061.75  5661.9 2060.28  5773.8 2056.74  5807.6 2054.25
  5885.6  2058.7  5946.4 2060.35  6244.7 2062.52  6283.7 2064.08  6415.7 2075.85
#Mann= 8 ,-1 , 0
  4300.3     .16       0  4469.9     .07       0    4670     .16       0
  4983.9     .07       0  5016.1     .16       0  5173.5     .07       0
    5331     .16       0    5369     .07       0
#XS Ineff= 2 , 0
       0                  5516.2       0 2061.75
Permanent Ineff=
       F       F
Bank Sta=4983.9,5016.1
XS Rating Curve= 0 ,0
Exp/Cntr=0.3,0.1

Type RM Length L Ch R = 1 ,1765    ,494,494,494
BEGIN DESCRIPTION:
Mapping XS b76b7246
END DESCRIPTION:
XS GIS Cut Line= 3
      1465824.91      6823068.45      1465937.76      6822274.22
      1465495.42      6820992.19
#Sta/Elev= 30
  4159.2 2076.33  4266.1 2072.19  4280.9 2072.75  4356.5 2069.12  4600.5 2060.48
  4755.6  2055.6  4785.9  2053.6  4833.3 2056.14  4947.5 2056.97    4957 2053.59
  4961.4 2053.59    4968 2048.69  4968.4 2040.74  4968.9 2040.24  5000.7 2040.74
  5010.3 2048.03  5015.7 2049.58  5041.6 2048.45  5094.9 2049.84  5135.2 2056.45
  5147.8  2056.9    5243 2057.09  5306.5 2059.17  5717.4 2058.49  5753.9 2058.05
  5878.7 2052.88  5930.5    2055  6055.3 2062.91  6142.2 2066.18  6317.6 2070.09
#Mann= 5 ,-1 , 0
  4159.2     .07       0  4356.5     .16       0  4600.5     .07       0
  4968.4     .07       0  5000.7     .07       0
#XS Ineff= 2 , 0
       0                  5306.5       0 2059.17
Permanent Ineff=
       F       F
Bank Sta=4968.4,5000.7
XS Rating Curve= 0 ,0
Exp/Cntr=0.3,0.1

Type RM Length L Ch R = 1 ,1271    ,654,654,654
BEGIN DESCRIPTION:
Mapping XS 0ec8925f
END DESCRIPTION:
XS GIS Cut Line= 3
      1466141.74      6823111.93      1466403.55      6822184.47
      1465732.26      6821082.78
#Sta/Elev= 30
  4036.3  2074.2  4570.3 2062.51  4757.3 2060.93  4764.3 2059.42  4842.7 2056.74
  4914.1  2047.6  4949.9 2041.87    4955 2042.62  4972.9 2038.06  4973.4 2037.56
  5005.2 2038.06  5010.1 2045.66  5041.1 2048.46  5068.2  2053.2  5169.2 2053.02
  5316.1  2055.8  5560.8 2056.03  5768.7 2056.47  5899.9 2053.37  5912.6  2052.4
  5928.1 2048.81  5949.4 2049.28  5964.8 2051.49  6007.5 2053.79  6022.9 2057.19
  6028.8 2056.66  6050.1 2062.42  6096.5 2067.78    6234  2073.7  6290.1 2073.62
#Mann= 7 ,-1 , 0
  4036.3     .07       0  4914.1     .16       0  4972.9     .07       0
  5005.2     .16       0  5169.2     .07       0  5560.8    .035       0
  5899.9     .07       0
#XS Ineff= 2 , 0
       0                  5768.7       0 2056.47
Permanent Ineff=
       F       F
Bank Sta=4972.9,5005.2
XS Rating Curve= 0 ,0
Exp/Cntr=0.3,0.1

Type RM Length L Ch R = 1 ,617     ,0,0,0
BEGIN DESCRIPTION:
WEAVER SPRINGS CREEK 1.0
END DESCRIPTION:
XS GIS Cut Line= 3
      1466723.42      6822821.19        1466805.        6821838.
      1465807.64       6821080.8
#Sta/Elev= 30
  4013.5 2070.95  4213.2 2071.21  4597.9  2064.9  4700.9 2062.94  4797.9 2046.72
  4849.6 2042.49    4990 2044.17  5007.3 2043.19    5012 2035.78  5012.5 2035.28
  5044.3 2035.78  5057.3    2038  5063.5 2043.54  5121.7 2045.77    5128 2048.73
  5157.1 2039.51  5221.6 2051.79  5263.7 2055.17  5292.3 2051.22    5571 2050.45
  5635.4 2054.02  5663.1 2049.05  5665.7 2048.72  5756.1 2050.35  5799.7 2047.74
  5866.9 2053.22  5977.7 2057.19  6005.7 2058.72  6070.2 2069.58  6252.3 2074.19
#Mann= 9 ,-1 , 0
  4013.5     .07       0  4597.9     .16       0  4797.9     .07       0
    5012     .07       0  5044.3     .07       0  5663.1    .035       0
  5665.7     .07       0  5866.9     .16       0  5977.7     .07       0
#XS Ineff= 2 , 0
       0                  5256.9       0 2055.02
Permanent Ineff=
       F       F
Bank Sta=5012,5044.3
XS Rating Curve= 0 ,0
Exp/Cntr=0.3,0.1

Chan Stop Cuts=-1
Use User Specified Reach Order=0
Composite Channel Slope=5