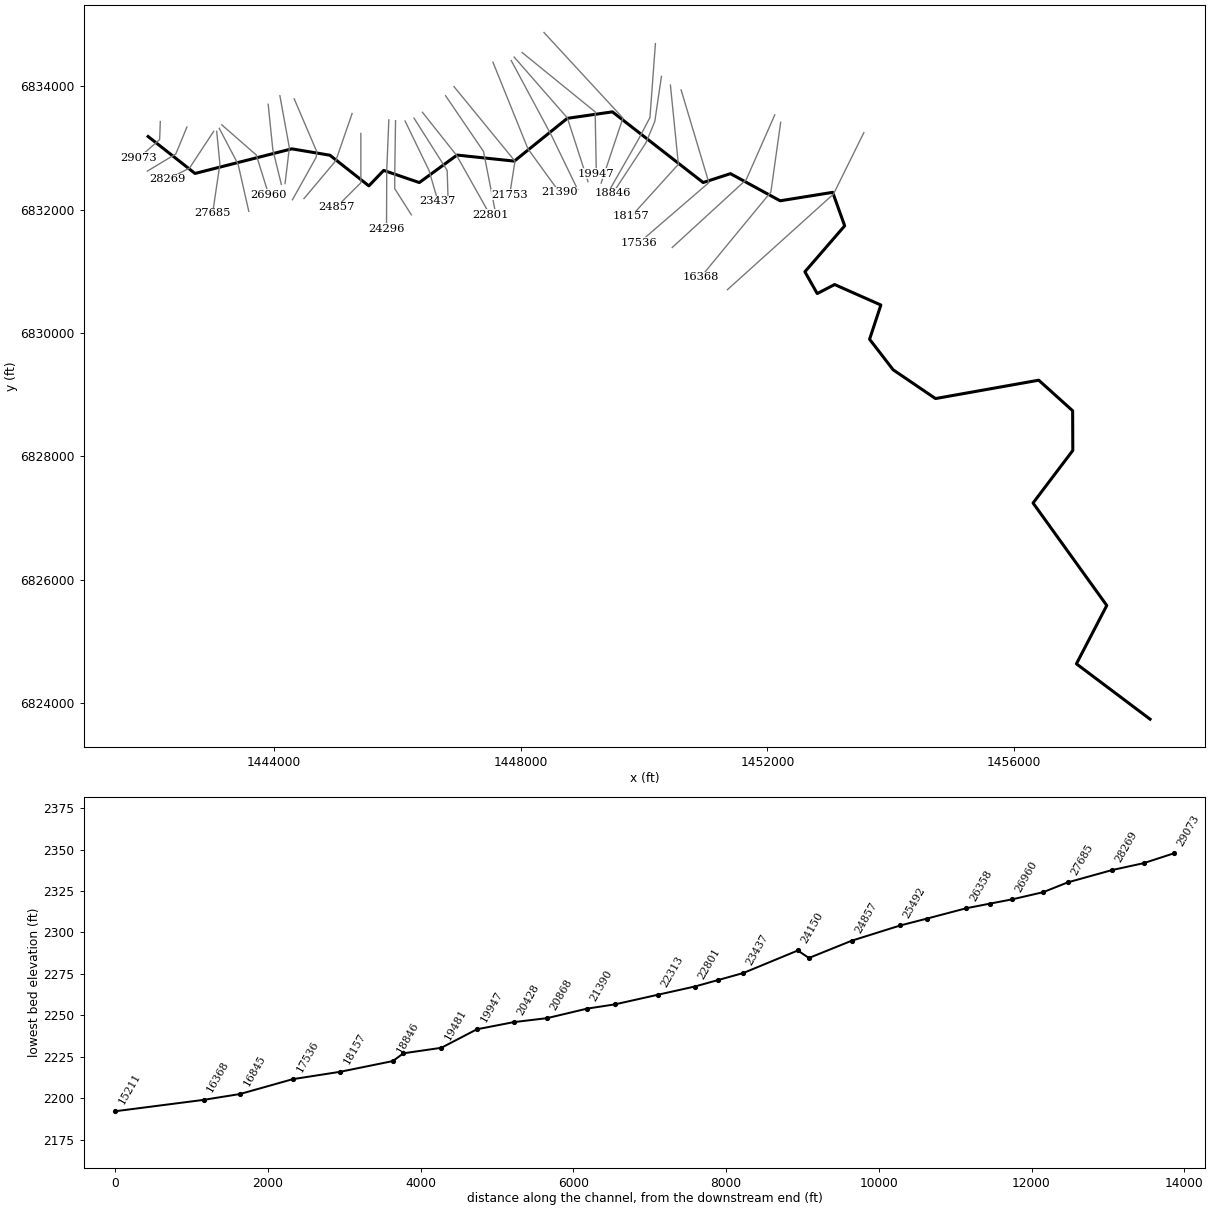
--- WEAVER SPRINGS CREEK TRIB 1.prj (project) ---

Proj Title=WEAVER SPRINGS CREEK TRIB 1 Base Level Engineering
Current Plan=p01
Default Exp/Contr=0.3,0.1
English Units
Geom File=g01
Flow File=f01
Plan File=p01
Y Axis Title=Elevation
X Axis Title(PF)=Main Channel Distance
X Axis Title(XS)=Station
BEGIN DESCRIPTION:
WEAVER SPRINGS CREEK TRIB 1
END DESCRIPTION:
DSS Export Rating Curves= 0
DSS Export Rating Curve Sorted= 0
DSS Export Volume Flow Curves= 0
DXF OffsetX= 0
DXF OffsetY= 0
DXF ScaleX= 1
DXF ScaleY= 10

--- WEAVER SPRINGS CREEK TRIB 1.p01 (plan) ---

Plan Title=Multiple Run
Short Identifier=Multiple
Geom File=g01
Flow File=f01
Subcritical Flow
K Sum by GR= 0
Std Step Tol= 0.01
Critical Tol= 0.01
Num of Std Step Trials= 20
Max Error Tol= 0.3
Flow Tol Ratio= 0.001
Split Flow NTrial= 30
Split Flow Tol= 0.02
Split Flow Ratio= 0.02
Log Output Level= 0
Friction Slope Method= 1
Unsteady Friction Slope Method= 2
Unsteady Bridges Friction Slope Method= 1
Parabolic Critical Depth
Global Vel Dist=  1 , 1 , 1
Global Log Level= 0
CheckData=True
Encroach Param= -1, 0, 0, 0
BEGIN DESCRIPTION:
Multiple Run
END DESCRIPTION:

--- WEAVER SPRINGS CREEK TRIB 1.f01 (steady flow) ---

Flow Title=Multiple
Program Version=4.10
Number of Profiles= 7
Profile Names=10-year,25-year,50-year,1pct_min,100-year,1pct_plu,500-year
River Rch & RM=WEAVER SPRINGS C,Reach-1         ,29073
     523     770     986     628    1254    2502    2051
River Rch & RM=WEAVER SPRINGS C,Reach-1         ,24296
     647     961    1239     794    1584    3160    2619
River Rch & RM=WEAVER SPRINGS C,Reach-1         ,18985
    1096    1671    2191    1425    2843    5673    4852
River Rch & RM=WEAVER SPRINGS C,Reach-1         ,16845
    1299    1994    2627    1716    3424    6831    5892
River Rch & RM=WEAVER SPRINGS C,Reach-1         ,15211
    1323    2029    2670    1742    3475    6934    5965
River Rch & RM=WEAVER SPRINGS C,Reach-1         ,10805
    1424    2188    2882    1882    3755    7491    6455
River Rch & RM=WEAVER SPRINGS C,Reach-1         ,8032
    1455    2230    2935    1913    3817    7616    6542
River Rch & RM=WEAVER SPRINGS C,Reach-1         ,1775
    1534    2356    3104    2026    4042    8065    6944
Boundary for River Rch & Prof#=WEAVER SPRINGS C,Reach-1         , 1
Up Type= 0
Dn Type= 3
Dn Slope=0.00796
Boundary for River Rch & Prof#=WEAVER SPRINGS C,Reach-1         , 2
Up Type= 0
Dn Type= 3
Dn Slope=0.00796
Boundary for River Rch & Prof#=WEAVER SPRINGS C,Reach-1         , 3
Up Type= 0
Dn Type= 3
Dn Slope=0.00796
Boundary for River Rch & Prof#=WEAVER SPRINGS C,Reach-1         , 4
Up Type= 0
Dn Type= 3
Dn Slope=0.00796
Boundary for River Rch & Prof#=WEAVER SPRINGS C,Reach-1         , 5
Up Type= 0
Dn Type= 3
Dn Slope=0.00796
Boundary for River Rch & Prof#=WEAVER SPRINGS C,Reach-1         , 6
Up Type= 0
Dn Type= 3
Dn Slope=0.00796
Boundary for River Rch & Prof#=WEAVER SPRINGS C,Reach-1         , 7
Up Type= 0
Dn Type= 3
Dn Slope=0.00796
DSS Import GetInterval= 0
DSS Import GetPeak= 0
DSS Import FillOption= 0

--- WEAVER SPRINGS CREEK TRIB 1.g01 (geometry) ---

Geom Title=Existing Conditions
Program Version=4.10

River Reach=WEAVER SPRINGS C,Reach-1
Reach XY= 30
        1441955.        6833188.      1442715.48      6832588.93
      1444285.01      6832988.06      1444903.54      6832884.46
      1445534.97      6832387.55      1445775.05      6832638.21
      1446353.38      6832441.12      1446965.27      6832887.03
       1447893.3      6832788.99      1448752.32      6833482.58
      1449484.97      6833587.94      1450956.58      6832441.67
      1451399.07      6832585.77      1452204.96      6832145.52
      1453057.45      6832282.54      1453251.96      6831739.42
      1452606.74      6830994.16      1452806.64      6830641.09
      1453089.04      6830787.11      1453838.95      6830455.05
      1453655.81      6829899.94      1454038.24      6829404.43
      1454724.88      6828937.93      1456399.07      6829235.76
      1456949.18      6828740.28      1456951.84      6828096.34
      1456307.14      6827243.97      1457502.77       6825582.1
      1457010.54      6824635.63        1458205.        6823738.

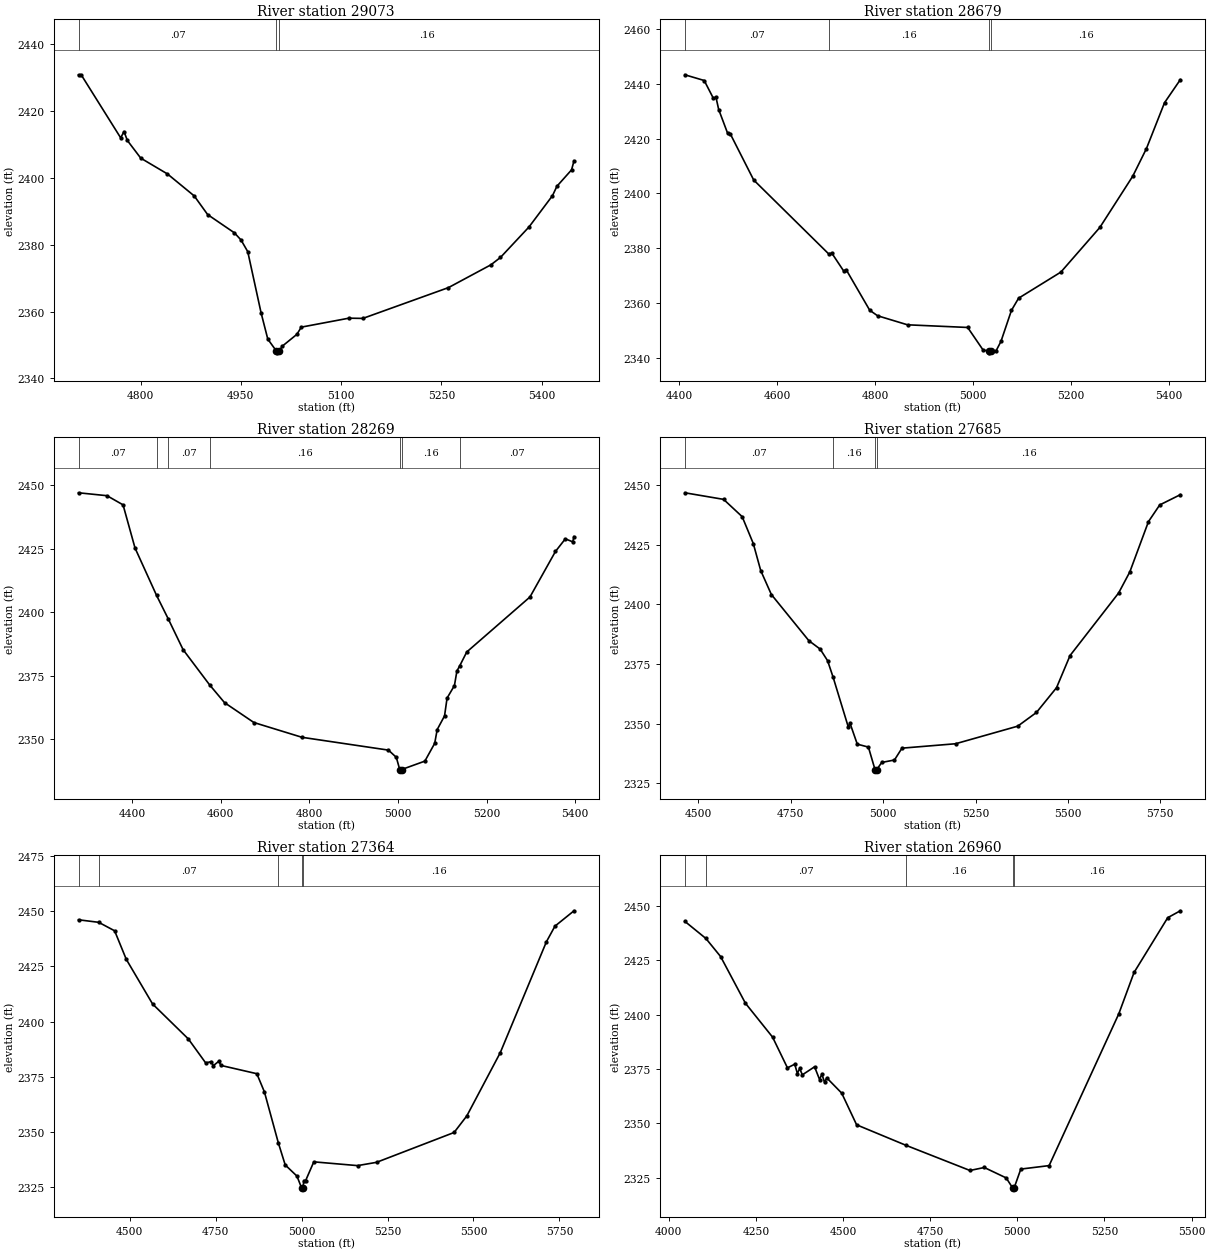
Type RM Length L Ch R = 1 ,29073   ,394,394,394
BEGIN DESCRIPTION:
WEAVER SPRINGS CREEK TRIB 1 50.0
END DESCRIPTION:
XS GIS Cut Line= 3
      1442152.44      6833431.03      1442141.94      6833138.32
        1441805.      6832842.45
#Sta/Elev= 30
  4707.1 2430.76  4711.1 2430.76  4770.2 2411.91  4775.2  2413.8  4780.2 2411.12
  4800.2 2405.85  4840.2 2401.12  4880.2 2394.56  4900.3 2388.98  4940.3 2383.53
  4950.3 2381.37  4960.3  2377.9  4980.3 2359.57  4990.3 2351.75  5003.3 2348.16
  5003.6 2347.66  5007.3 2348.16    5012 2349.66  5033.8 2353.19  5040.4 2355.34
  5111.6 2358.02  5132.5 2357.95  5260.6 2367.16  5324.1 2373.97  5338.4 2376.18
  5381.1 2385.29  5416.2 2394.64  5422.8 2397.44  5444.7 2402.34  5448.4 2405.05
#Mann= 3 ,-1 , 0
  4707.1     .07       0  5003.3     .07       0  5007.3     .16       0
Bank Sta=5003.3,5007.3
XS Rating Curve= 0 ,0
Exp/Cntr=0.3,0.1

Type RM Length L Ch R = 1 ,28679   ,410,410,410
BEGIN DESCRIPTION:
Mapping XS 37b88874
END DESCRIPTION:
XS GIS Cut Line= 3
      1442584.17      6833341.95       1442403.6      6832904.41
      1441941.83      6832626.66
#Sta/Elev= 30
    4411 2443.34  4450.6 2441.25  4469.2 2434.78  4474.6 2435.15  4480.2 2430.64
  4498.5 2421.94  4503.9 2421.75  4551.7  2404.9  4704.5 2377.97  4711.5 2378.12
  4735.4 2371.68  4740.9 2372.05  4788.7 2357.32  4804.7 2355.31  4865.9    2352
  4988.8 2351.03  5019.9 2342.89  5032.4 2342.26  5032.7 2341.76  5036.4 2342.26
  5047.1  2342.6  5056.8 2345.93  5078.2 2357.27  5092.8 2361.72  5179.2 2371.26
  5258.8 2387.57  5326.1 2406.32    5354  2416.4  5390.9 2433.13  5423.2 2441.56
#Mann= 4 ,-1 , 0
    4411     .07       0  4704.5     .16       0  5032.4     .07       0
  5036.4     .16       0
Bank Sta=5032.4,5036.4
XS Rating Curve= 0 ,0
Exp/Cntr=0.3,0.1

Type RM Length L Ch R = 1 ,28269   ,584,584,584
BEGIN DESCRIPTION:
Mapping XS b6f909a2
END DESCRIPTION:
XS GIS Cut Line= 3
      1443018.16      6833272.44      1442625.82      6832675.25
      1442266.44       6832492.1
#Sta/Elev= 30
  4279.4 2447.01  4343.7 2445.86  4379.9 2442.26  4406.9 2425.29  4455.6 2406.61
    4482 2397.36  4515.4 2385.29  4575.1 2371.47  4608.8 2364.47  4675.1 2356.64
  4783.6 2350.83  4978.7 2345.79  4996.4 2342.94  5004.1 2338.14  5004.3 2337.64
  5008.1 2338.14  5060.8 2341.46    5083 2348.46  5088.6 2353.87  5105.2 2359.25
  5110.9 2366.26  5127.5 2371.18  5133.1  2376.9  5139.7 2379.03  5155.3 2384.39
  5297.9 2406.02  5355.5 2423.95  5377.7 2428.89  5394.3 2427.72  5397.3 2429.76
#Mann= 7 ,-1 , 0
  4279.4     .07       0  4455.6     .16       0    4482     .07       0
  4575.1     .16       0  5004.1     .07       0  5008.1     .16       0
  5139.7     .07       0
Bank Sta=5004.1,5008.1
XS Rating Curve= 0 ,0
Exp/Cntr=0.3,0.1

Type RM Length L Ch R = 1 ,27685   ,321,321,321
BEGIN DESCRIPTION:
Mapping XS 967a19d7
END DESCRIPTION:
XS GIS Cut Line= 3
      1443066.79      6833272.44      1443118.88      6832741.22
      1443000.84      6831942.76
#Sta/Elev= 30
  4463.3 2446.68  4568.2 2443.92  4618.5 2436.67  4648.6  2425.4  4668.7 2414.09
  4697.5 2404.05    4799  2384.7  4829.5 2381.19  4849.6 2376.34  4864.8  2369.3
  4905.5 2348.63  4910.5 2350.03    4930 2341.35  4960.1 2340.12    4978 2330.67
  4978.3 2330.17  4982.5 2330.67  4996.2 2333.69  5030.6 2334.71  5050.9 2339.67
    5196 2341.52  5364.2 2348.89  5414.8 2354.62  5469.2 2365.01  5505.8 2378.49
  5637.2 2404.69  5667.5 2413.52    5718 2434.61  5748.4 2441.58  5804.2 2445.88
#Mann= 4 ,-1 , 0
  4463.3     .07       0  4864.8     .16       0    4978     .07       0
  4982.5     .16       0
Bank Sta=4978,4982.5
XS Rating Curve= 0 ,0
Exp/Cntr=0.3,0.1

Type RM Length L Ch R = 1 ,27364   ,404,404,404
BEGIN DESCRIPTION:
Mapping XS 11519a1f
END DESCRIPTION:
XS GIS Cut Line= 3
      1443108.45       6833321.1      1443414.01      6832737.75
      1443587.62      6831973.86
#Sta/Elev= 30
  4350.7 2446.15  4409.5    2445  4455.8 2441.16  4489.7 2428.24  4566.3    2408
  4670.3 2392.17  4720.7 2381.32  4737.2  2381.9  4742.8 2380.03  4759.2 2382.08
  4764.9 2380.18  4869.6 2376.42  4891.6  2368.2  4932.2 2345.08  4952.2 2335.09
  4986.4 2330.02  4999.6 2324.76    5000 2324.26  5004.2 2324.76  5006.3 2328.02
  5011.7 2328.02  5035.4 2336.49  5162.8 2334.78    5218 2336.27  5443.6 2349.79
  5480.7 2357.31  5577.9 2385.92  5712.3  2436.2  5737.1 2443.26  5792.6 2450.23
#Mann= 5 ,-1 , 0
  4350.7     .16       0  4409.5     .07       0  4932.2     .16       0
  4999.6     .07       0  5004.2     .16       0
Bank Sta=4999.6,5004.2
XS Rating Curve= 0 ,0
Exp/Cntr=0.3,0.1

Type RM Length L Ch R = 1 ,26960   ,296,296,296
BEGIN DESCRIPTION:
Mapping XS 1bc3d40a
END DESCRIPTION:
XS GIS Cut Line= 3
      1443149.24      6833377.52      1443709.15      6832887.92
      1443911.71      6832241.29
#Sta/Elev= 30
  4046.2 2442.79  4106.6 2434.93  4148.9 2426.61    4220  2405.2  4297.9 2389.63
  4340.6 2375.52  4361.5 2377.19  4369.1 2372.92  4375.7 2375.26  4383.3  2372.3
  4418.4    2376  4432.7 2370.16  4439.3 2372.63  4446.9 2368.97  4453.5  2370.9
  4496.2 2363.91    4539 2349.36  4679.8    2340  4864.1 2328.39  4905.2 2329.76
    4968 2324.98  4986.3 2320.46  4986.6 2319.96    4991 2320.46    5010 2329.03
  5091.2 2330.63  5291.1 2400.33  5334.8  2419.3  5431.4 2444.46  5467.6 2447.64
#Mann= 5 ,-1 , 0
  4046.2     .16       0  4106.6     .07       0  4679.8     .16       0
  4986.3     .07       0    4991     .16       0
Bank Sta=4986.3,4991
XS Rating Curve= 0 ,0
Exp/Cntr=0.3,0.1

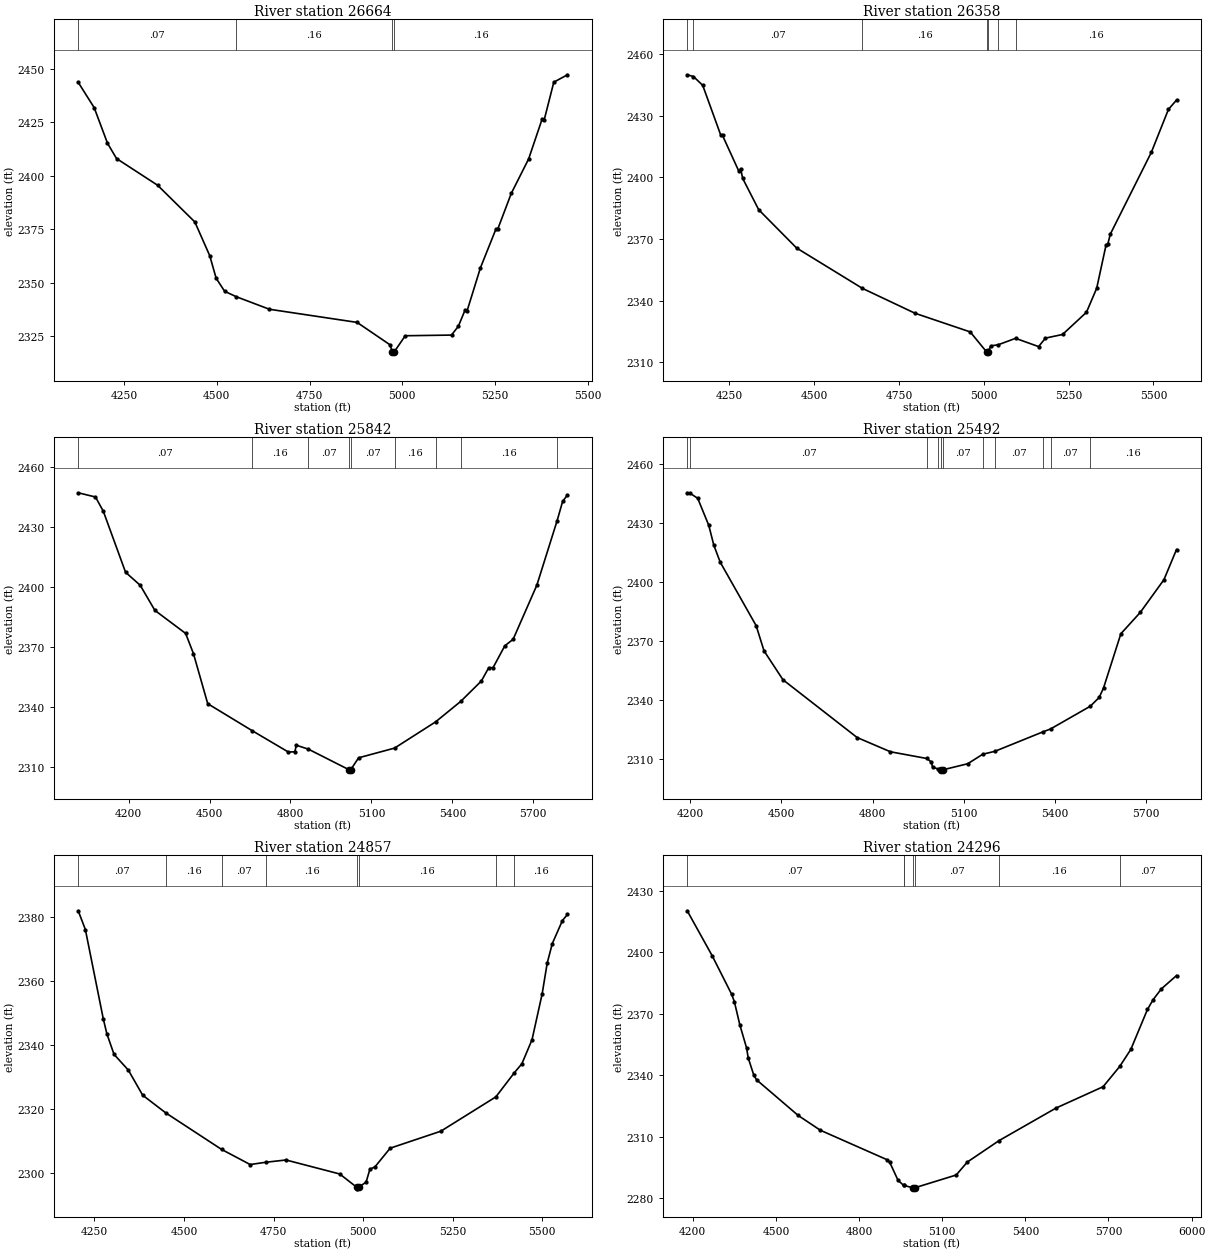
Type RM Length L Ch R = 1 ,26664   ,306,306,306
BEGIN DESCRIPTION:
Mapping XS e53a533c
END DESCRIPTION:
XS GIS Cut Line= 3
      1443901.86      6833710.84      1443977.38      6832973.86
      1444115.21      6832412.16
#Sta/Elev= 30
  4126.2 2443.61  4169.3 2431.78  4205.2 2415.16  4229.6 2408.02  4340.2 2395.57
  4440.7 2378.42  4480.9 2362.66  4498.1 2352.16  4521.1 2346.04  4552.3 2343.54
  4641.7 2337.67  4878.1 2331.54  4966.4 2321.14  4973.5 2317.83  4973.9 2317.33
  4978.5 2317.83    5008 2325.31  5132.7 2325.62  5151.1 2329.72  5169.1 2337.24
  5174.3  2336.7  5210.7 2357.01  5252.3 2375.03  5257.4  2375.1  5293.9 2391.78
  5340.6 2407.82    5377 2426.44  5382.2 2425.79  5408.5 2443.67  5445.4 2447.12
#Mann= 4 ,-1 , 0
  4126.2     .07       0  4552.3     .16       0  4973.5     .07       0
  4978.5     .16       0
Bank Sta=4973.5,4978.5
XS Rating Curve= 0 ,0
Exp/Cntr=0.3,0.1

Type RM Length L Ch R = 1 ,26358   ,516,516,516
BEGIN DESCRIPTION:
Mapping XS ba920654
END DESCRIPTION:
XS GIS Cut Line= 3
      1444091.96      6833848.87      1444245.61      6833005.11
       1444175.3      6832424.39
#Sta/Elev= 30
  4125.6 2449.96    4144 2449.11  4171.3 2444.82  4224.7 2420.48  4229.7 2420.41
    4278 2402.95  4283.1 2404.27  4289.1 2399.53  4336.4 2384.26  4448.1 2365.63
  4642.2 2345.97  4797.3 2333.86    4960 2324.77    5008 2315.09  5008.4 2314.59
    5013 2315.09  5020.6 2317.98  5042.1  2318.5  5093.7 2321.65  5161.6 2317.63
  5181.8 2321.76  5232.1 2323.52  5302.7 2334.34  5332.9 2346.04  5360.4 2367.03
  5365.4 2367.43  5373.2 2372.43    5494 2412.21  5544.4 2433.11  5568.2 2437.64
#Mann= 7 ,-1 , 0
  4125.6     .16       0    4144     .07       0  4642.2     .16       0
    5008     .07       0    5013     .16       0  5042.1     .07       0
  5093.7     .16       0
Bank Sta=5008,5013
XS Rating Curve= 0 ,0
Exp/Cntr=0.3,0.1

Type RM Length L Ch R = 1 ,25842   ,350,350,350
BEGIN DESCRIPTION:
Mapping XS 28e9befa
END DESCRIPTION:
XS GIS Cut Line= 4
      1444323.74      6833799.38      1444690.92        6832940.
      1444680.51      6832851.46      1444295.54      6832162.16
#Sta/Elev= 30
  4013.3 2447.12  4077.4 2445.01  4106.4 2437.89  4188.8 2407.45  4243.2 2400.93
  4297.5 2388.41  4411.4 2376.92  4440.4 2366.84  4493.3 2341.84  4657.9 2328.37
  4792.6 2317.67  4816.2 2317.86  4821.6 2321.11  4866.7 2319.12  5017.7 2308.82
  5018.1 2308.32  5022.9 2308.82  5052.4 2314.83  5185.7 2319.67  5337.6 2332.75
  5430.8 2342.98  5507.3 2353.15  5534.7 2359.79  5550.7 2359.82  5594.1 2370.71
  5625.1 2373.99  5712.9 2400.98  5788.1 2433.19  5808.4 2442.78  5826.5 2446.06
#Mann= 9 ,-1 , 0
  4013.3     .07       0  4657.9     .16       0  4866.7     .07       0
  5017.7     .07       0  5022.9     .07       0  5185.7     .16       0
  5337.6     .07       0  5430.8     .16       0  5788.1     .07       0
Bank Sta=5017.7,5022.9
XS Rating Curve= 0 ,0
Exp/Cntr=0.3,0.1

Type RM Length L Ch R = 1 ,25492   ,635,635,635
BEGIN DESCRIPTION:
WEAVER SPRINGS CREEK TRIB 1 42.0
END DESCRIPTION:
XS GIS Cut Line= 3
      1445263.08      6833560.65      1444998.51      6832794.76
      1444482.93      6832181.76
#Sta/Elev= 30
  4189.7 2445.42  4199.8 2445.08  4224.2 2442.63  4260.8 2428.84  4277.1  2418.9
  4298.3 2410.19  4416.7 2377.92  4442.6 2365.13    4505 2350.44  4749.2  2321.1
    4859 2313.85  4978.7 2310.44  4993.4 2308.68  4997.7 2306.09  5014.9 2305.15
  5025.9 2304.67  5026.3 2304.17  5031.2 2304.67  5113.4 2307.77  5163.1 2312.62
  5202.6 2314.07  5361.4 2323.99  5386.1 2325.43  5517.1 2336.99  5546.3 2341.44
  5560.6 2346.23  5617.8 2373.82  5681.5 2384.61  5759.6 2401.27    5801 2416.59
#Mann= 11 ,-1 , 0
  4189.7     .16       0  4199.8     .07       0  4978.7     .16       0
  5014.9     .07       0  5025.9     .07       0  5031.2     .07       0
  5163.1     .16       0  5202.6     .07       0  5361.4     .16       0
  5386.1     .07       0  5517.1     .16       0
Bank Sta=5025.9,5031.2
XS Rating Curve= 0 ,0
Exp/Cntr=0.3,0.1

Type RM Length L Ch R = 1 ,24857   ,561,561,561
BEGIN DESCRIPTION:
WEAVER SPRINGS CREEK TRIB 1 41.0
END DESCRIPTION:
XS GIS Cut Line= 3
        1445405.      6833238.03        1445405.        6832438.
      1445005.01      6832038.01
#Sta/Elev= 30
  4204.7 2381.82  4224.7 2375.97  4274.7 2348.09  4284.7 2343.42  4304.7 2336.99
  4344.7 2332.06  4384.7 2324.23  4449.3 2318.69  4604.8 2307.31  4684.7 2302.58
  4729.6 2303.31  4784.7    2304  4934.7 2299.63  4982.1 2295.49  4982.5 2294.99
  4987.4 2295.49  5008.3 2297.08  5018.9 2301.12    5033 2301.85  5075.4 2307.68
  5216.9 2312.99  5370.5 2323.71  5422.2 2331.27  5443.1 2334.05  5471.4 2341.55
  5499.7 2355.88  5513.8  2365.5    5528 2371.58  5556.3 2378.78  5570.4 2380.67
#Mann= 8 ,-1 , 0
  4204.7     .07       0  4449.3     .16       0  4604.8     .07       0
  4729.6     .16       0  4982.1     .07       0  4987.4     .16       0
  5370.5     .07       0  5422.2     .16       0
Bank Sta=4982.1,4987.4
XS Rating Curve= 0 ,0
Exp/Cntr=0.3,0.1

Type RM Length L Ch R = 1 ,24296   ,146,146,146
BEGIN DESCRIPTION:
WEAVER SPRINGS CREEK TRIB 1 40.0
END DESCRIPTION:
XS GIS Cut Line= 3
      1445858.78      6833457.81      1445825.04      6832638.61
      1445821.15      6831693.22
#Sta/Elev= 30
  4180.1 2420.19    4270  2398.3    4340 2379.56  4350.1 2375.92  4370.1 2364.46
  4394.3 2353.27  4400.1 2348.45  4420.1 2340.11  4430.1 2337.75  4580.3 2320.36
  4660.3 2313.14  4900.5 2298.79  4910.5 2297.56  4940.6 2288.75  4960.5 2286.27
  4961.4 2286.23  4994.9 2285.05  4995.4 2284.55  5000.7 2285.05  5150.6  2291.3
  5190.6 2297.61  5305.6 2308.11  5510.6 2323.95  5680.6 2334.37  5740.4 2344.23
  5780.6 2352.57  5840.6 2372.06  5860.6 2376.75  5890.6 2382.08  5945.4 2388.58
#Mann= 7 ,-1 , 0
  4180.1     .07       0  4960.5     .16       0  4961.4     .07       0
  4994.9     .07       0  5000.7     .07       0  5305.6     .16       0
  5740.4     .07       0
Bank Sta=4994.9,5000.7
XS Rating Curve= 0 ,0
Exp/Cntr=0.3,0.1

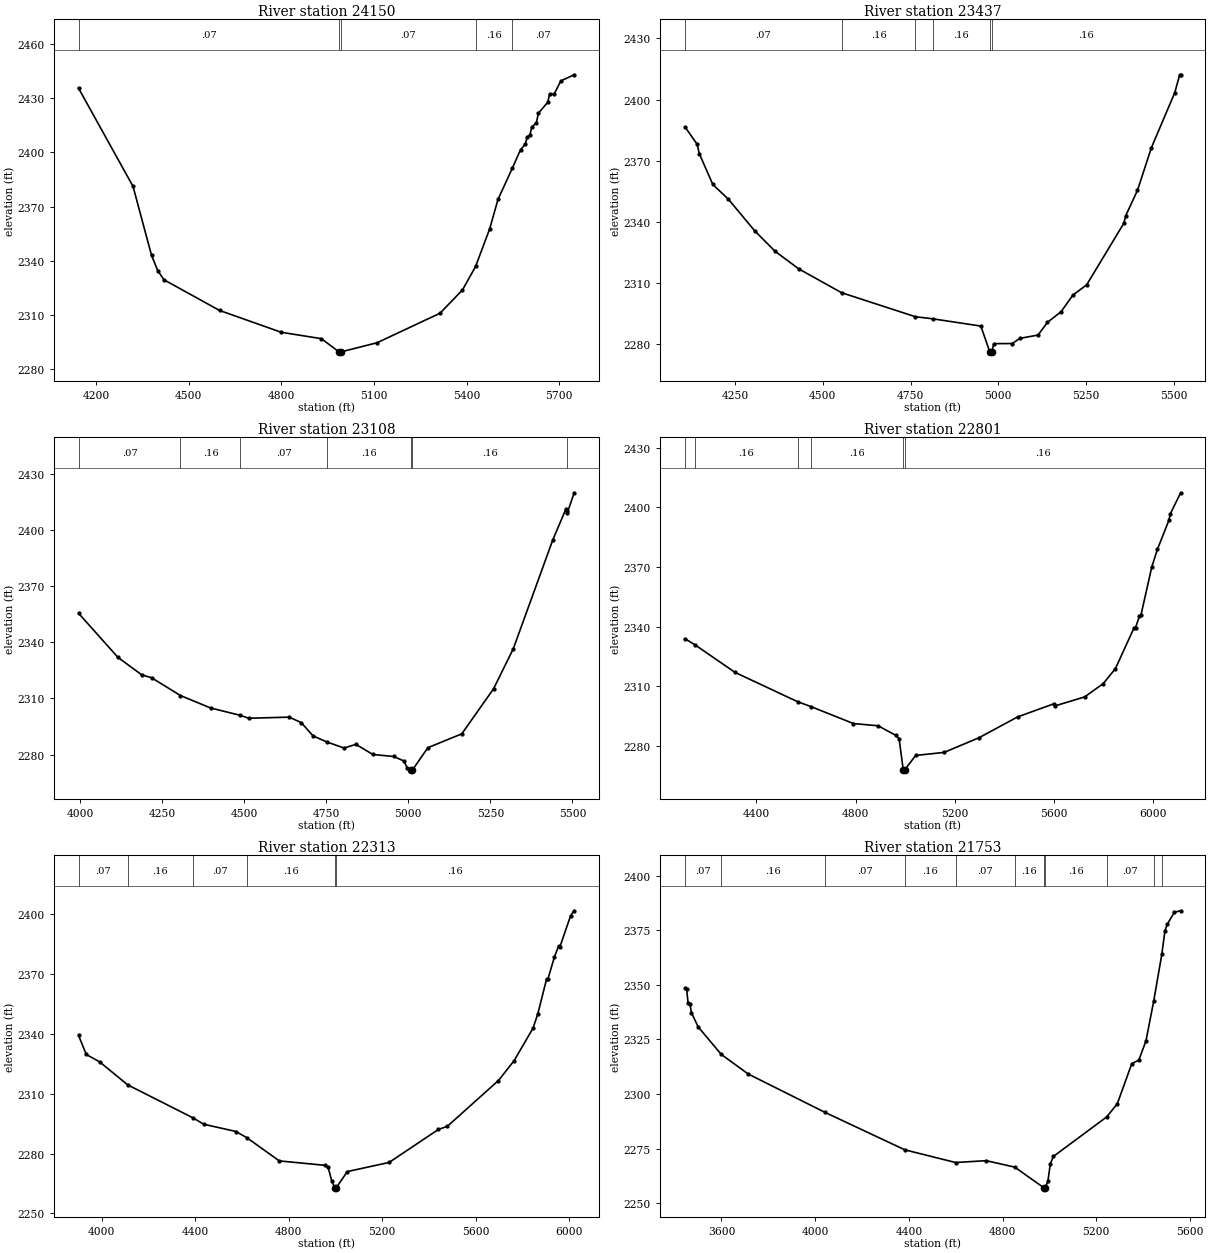
Type RM Length L Ch R = 1 ,24150   ,713,713,713
BEGIN DESCRIPTION:
WEAVER SPRINGS CREEK TRIB 1 39.0
END DESCRIPTION:
XS GIS Cut Line= 4
      1445967.44      6833444.51      1445954.83       6832587.6
      1445954.56      6832341.89      1446224.25      6831918.02
#Sta/Elev= 30
    4143 2435.49  4319.5 2381.16  4379.5 2342.99  4399.5 2334.57  4419.5 2329.51
  4599.6 2312.53  4799.6 2300.44  4929.6  2296.9  4986.7 2289.57  4987.2 2289.07
  4992.5 2289.57  5109.6 2294.64  5313.6 2310.97  5386.4 2323.85  5429.1 2336.93
  5474.5 2357.67  5501.6 2374.02  5548.1 2391.32  5574.4 2401.43  5589.6 2404.45
  5595.6 2408.33  5604.9 2409.65  5610.8 2413.95    5626 2416.42    5632 2421.56
  5662.5 2427.68  5668.4 2432.04  5683.6  2432.3  5704.8 2439.51  5748.1 2442.89
#Mann= 5 ,-1 , 0
    4143     .07       0  4986.7     .07       0  4992.5     .07       0
  5429.1     .16       0  5548.1     .07       0
Bank Sta=4986.7,4992.5
XS Rating Curve= 0 ,0
Exp/Cntr=0.3,0.1

Type RM Length L Ch R = 1 ,23437   ,329,329,329
BEGIN DESCRIPTION:
WEAVER SPRINGS CREEK TRIB 1 38.0
END DESCRIPTION:
XS GIS Cut Line= 3
      1446122.16      6833439.32      1446510.85      6832636.46
      1446655.01      6832137.98
#Sta/Elev= 30
    4108 2386.53  4142.8 2377.97  4148.6 2373.44  4187.2 2358.25  4231.7 2350.96
  4306.7 2335.42    4365 2325.33  4431.7 2316.78  4553.9 2305.03  4763.8 2293.25
  4813.8  2292.2  4950.2 2288.65  4975.5 2275.99  4975.9 2275.49  4981.3 2275.99
  4987.2 2280.01    5040 2280.06  5060.9 2282.59  5112.9 2284.22  5139.9 2290.49
  5178.7 2295.72  5212.4 2303.92  5251.2 2308.86  5357.2 2339.15  5362.7 2342.95
    5396 2355.33  5435.6 2376.26  5502.1 2403.31  5516.3 2412.15  5518.9 2412.15
#Mann= 6 ,-1 , 0
    4108     .07       0  4553.9     .16       0  4763.8     .07       0
  4813.8     .16       0  4975.5     .07       0  4981.3     .16       0
Bank Sta=4975.5,4981.3
XS Rating Curve= 0 ,0
Exp/Cntr=0.3,0.1

Type RM Length L Ch R = 1 ,23108   ,307,307,307
BEGIN DESCRIPTION:
WEAVER SPRINGS CREEK TRIB 1 37.0
END DESCRIPTION:
XS GIS Cut Line= 3
      1446266.82      6833486.07        1446805.        6832638.
      1446820.65      6832132.66
#Sta/Elev= 30
  3995.2 2355.61  4115.2    2332    4188 2322.59  4217.9 2321.08  4305.7 2311.56
  4397.3 2304.92  4488.6 2300.93    4514 2299.41    4637    2300  4673.5  2297.1
  4709.9 2289.93  4753.3 2286.62  4803.9 2283.47  4840.4 2285.41    4892 2280.01
  4955.6 2278.94  4986.1 2276.56  4996.7 2272.81  5006.7 2271.76  5007.2 2271.26
  5012.6 2271.76  5059.6 2283.66  5162.9 2291.06  5259.7  2315.2  5319.8 2336.62
  5439.8 2394.72  5479.5 2411.17  5482.5 2410.09  5484.5 2409.37  5505.2 2420.06
#Mann= 7 ,-1 , 0
  3995.2     .07       0  4305.7     .16       0  4488.6     .07       0
  4753.3     .16       0  5006.7     .07       0  5012.6     .16       0
  5482.5     .07       0
Bank Sta=5006.7,5012.6
XS Rating Curve= 0 ,0
Exp/Cntr=0.3,0.1

Type RM Length L Ch R = 1 ,22801   ,488,488,488
BEGIN DESCRIPTION:
WEAVER SPRINGS CREEK TRIB 1 36.0
END DESCRIPTION:
XS GIS Cut Line= 3
      1446403.99      6833580.23      1446956.23      6832884.57
       1447500.2      6831916.43
#Sta/Elev= 30
  4111.8 2333.87  4151.7 2330.86  4313.5 2316.93  4565.9 2302.16  4620.2 2299.67
    4791 2291.16  4890.3 2290.03  4960.8  2285.3  4975.2 2283.52    4992 2267.83
  4992.5 2267.33  4997.9 2267.83    5042 2275.08  5156.7 2276.62  5296.8 2283.97
    5453 2294.49    5599 2301.09  5604.7 2300.08  5723.3 2304.56  5798.6  2311.3
  5847.7 2318.87  5922.9 2339.45  5928.6 2339.46  5944.6 2345.23  5950.3 2345.66
    5994 2369.98  6016.9  2378.9  6062.8 2393.44  6068.9 2396.79  6110.5  2407.4
#Mann= 6 ,-1 , 0
  4111.8     .07       0  4151.7     .16       0  4565.9     .07       0
  4620.2     .16       0    4992     .07       0  4997.9     .16       0
Bank Sta=4992,4997.9
XS Rating Curve= 0 ,0
Exp/Cntr=0.3,0.1

Type RM Length L Ch R = 1 ,22313   ,560,560,560
BEGIN DESCRIPTION:
WEAVER SPRINGS CREEK TRIB 1 35.0
END DESCRIPTION:
XS GIS Cut Line= 3
      1446779.85      6833848.47      1447394.45      6832945.68
      1447592.35      6831935.31
#Sta/Elev= 30
  3900.5 2339.18  3933.8  2329.6  3990.7 2325.91  4111.2 2314.37  4389.7 2297.92
  4436.6 2294.67  4574.2 2291.03  4622.3 2287.83    4760 2276.31  4954.4 2274.11
  4969.3 2273.01  4984.3 2266.32  4997.5 2262.82    4998 2262.32  5003.4 2262.82
  5051.4 2270.98  5229.7 2275.52  5440.7 2292.04  5479.4 2293.63  5698.1 2316.56
  5764.7 2326.42  5846.2 2342.79  5866.6 2349.95  5904.1 2367.33  5909.2 2367.15
  5937.9 2378.48  5955.6 2383.93  5960.7 2383.31  6007.1  2399.1  6022.2 2401.55
#Mann= 6 ,-1 , 0
  3900.5     .07       0  4111.2     .16       0  4389.7     .07       0
  4622.3     .16       0  4997.5     .07       0  5003.4     .16       0
Bank Sta=4997.5,5003.4
XS Rating Curve= 0 ,0
Exp/Cntr=0.3,0.1

Type RM Length L Ch R = 1 ,21753   ,363,363,363
BEGIN DESCRIPTION:
WEAVER SPRINGS CREEK TRIB 1 34.0
END DESCRIPTION:
XS GIS Cut Line= 3
      1446915.28      6833997.76        1447905.        6832788.
      1447818.23      6832241.88
#Sta/Elev= 30
  3444.1 2348.63  3450.9 2348.21  3457.4 2341.82  3465.3 2341.32  3471.7 2337.28
  3500.4 2330.76    3599 2318.15  3714.3 2309.15  4041.6  2291.6  4382.8 2274.41
  4599.6  2268.6  4730.1 2269.45  4851.8 2266.49  4976.1 2257.04  4976.6 2256.54
  4982.2 2257.04  4993.5 2260.04  5003.9 2268.07  5017.3 2271.42  5244.4  2289.5
  5289.7 2295.53  5351.4 2313.86  5381.8 2315.58  5412.2 2324.39  5445.6 2342.84
  5479.7 2364.02  5493.2 2374.87  5503.3 2377.85  5533.7 2383.31  5560.1 2383.97
#Mann= 11 ,-1 , 0
  3444.1     .07       0    3599     .16       0  4041.6     .07       0
  4382.8     .16       0  4599.6     .07       0  4851.8     .16       0
  4976.1     .07       0  4982.2     .16       0  5244.4     .07       0
  5445.6     .16       0  5479.7     .07       0
Bank Sta=4976.1,4982.2
XS Rating Curve= 0 ,0
Exp/Cntr=0.3,0.1

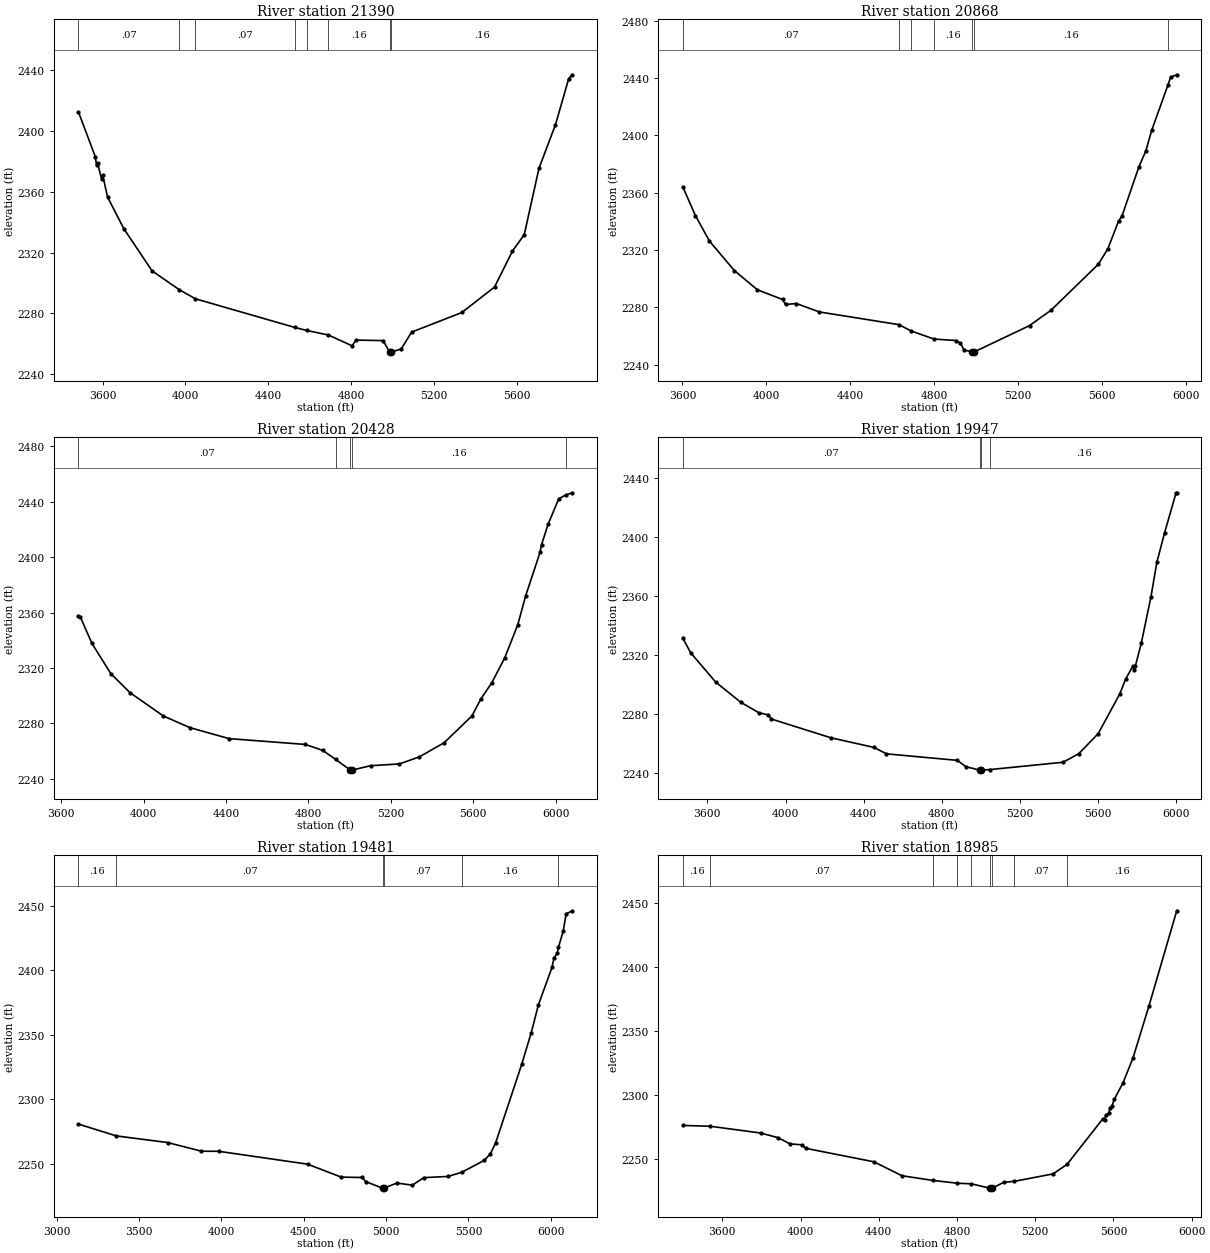
Type RM Length L Ch R = 1 ,21390   ,522,522,522
BEGIN DESCRIPTION:
WEAVER SPRINGS CREEK TRIB 1 33.0
END DESCRIPTION:
XS GIS Cut Line= 3
      1447547.12      6834393.63      1448115.19      6832987.55
      1448625.25      6832284.23
#Sta/Elev= 30
  3483.5 2412.67  3565.1 2383.16  3570.9 2377.55  3576.3 2378.89    3595 2368.58
  3600.4 2371.09  3624.5 2356.54  3702.3 2335.86  3839.2 2307.98  3970.2 2295.61
  4048.6 2289.58  4528.5 2270.72  4586.4 2268.71  4690.8 2265.75  4805.4 2258.61
  4823.8 2262.39  4955.2 2262.06    4987 2254.49  4987.5 2253.99  4993.2 2254.49
  5042.5  2256.5  5092.7 2267.63  5335.5 2280.56  5493.6 2297.36    5580 2321.04
    5637 2331.85  5708.1 2375.56  5787.8 2404.26  5851.8 2434.65  5868.8 2437.12
#Mann= 8 ,-1 , 0
  3483.5     .07       0  3970.2     .16       0  4048.6     .07       0
  4528.5     .16       0  4586.4     .07       0  4690.8     .16       0
    4987     .07       0  4993.2     .16       0
Bank Sta=4987,4993.2
XS Rating Curve= 0 ,0
Exp/Cntr=0.3,0.1

Type RM Length L Ch R = 1 ,20868   ,440,440,440
BEGIN DESCRIPTION:
WEAVER SPRINGS CREEK TRIB 1 32.0
END DESCRIPTION:
XS GIS Cut Line= 3
      1447844.03       6834419.6        1448505.        6833188.
      1448922.14      6832325.87
#Sta/Elev= 30
  3602.2 2363.94  3661.8  2344.1  3728.9 2326.26  3847.7 2305.68  3957.3 2292.29
  4077.5 2285.49    4092    2282  4143.3 2282.69  4252.9  2276.8    4633 2267.93
  4691.1 2263.51  4799.8 2257.89  4904.1 2256.85  4926.1 2255.02  4942.3 2250.39
  4982.9 2248.76  4983.4 2248.26  4989.5 2248.76  5255.5 2267.26  5358.4 2278.03
  5584.3 2310.17  5629.5 2320.97  5680.2 2340.23  5697.2 2343.98  5777.6 2378.23
  5810.2 2389.04  5838.3 2403.51  5915.1 2434.88  5928.7 2440.58  5957.7 2442.31
#Mann= 7 ,-1 , 0
  3602.2     .07       0    4633     .16       0  4691.1     .07       0
  4799.8     .16       0  4982.9     .07       0  4989.5     .16       0
  5915.1     .07       0
Bank Sta=4982.9,4989.5
XS Rating Curve= 0 ,0
Exp/Cntr=0.3,0.1

Type RM Length L Ch R = 1 ,20428   ,481,481,481
BEGIN DESCRIPTION:
WEAVER SPRINGS CREEK TRIB 1 31.0
END DESCRIPTION:
XS GIS Cut Line= 3
      1447890.91       6834476.9        1448755.        6833488.
      1449088.81      6832456.08
#Sta/Elev= 30
    3683 2357.83  3692.5 2356.79  3748.5 2337.79  3840.9 2315.86  3933.6  2302.2
  4095.9 2285.37  4224.1 2277.01  4414.8 2269.07  4783.8 2264.89  4868.6 2260.64
  4931.3 2254.13  5003.4 2246.33  5003.9 2245.83  5010.1 2246.33  5101.3 2249.53
  5241.6 2250.82  5337.6 2255.86  5458.7  2266.1  5593.7 2285.45  5637.4 2297.78
  5689.7 2309.26    5753 2327.41    5816 2351.11    5855 2372.29  5924.3 2403.45
  5931.6 2408.96  5963.2 2423.58  6015.1 2442.12  6049.3 2444.89  6080.8 2446.44
#Mann= 5 ,-1 , 0
    3683     .07       0  4931.3     .16       0  5003.4     .07       0
  5010.1     .16       0  6049.3     .07       0
Bank Sta=5003.4,5010.1
XS Rating Curve= 0 ,0
Exp/Cntr=0.3,0.1

Type RM Length L Ch R = 1 ,19947   ,466,466,466
BEGIN DESCRIPTION:
WEAVER SPRINGS CREEK TRIB 1 30.0
END DESCRIPTION:
XS GIS Cut Line= 3
      1448021.13      6834549.81        1449205.        6833588.
      1449224.22      6832586.31
#Sta/Elev= 30
  3474.7 2331.45  3514.6  2321.6  3642.4 2301.74  3770.3 2288.09  3862.9 2280.97
  3912.5 2279.45  3926.9 2276.69  4232.1 2263.95  4452.7 2257.41  4516.6 2253.05
  4879.4 2248.63  4922.5 2244.33  4993.4 2242.02  4993.9 2241.52  5000.2 2242.02
  5047.2 2242.39  5420.1 2247.34  5500.1  2253.1  5600.1 2266.75  5710.2 2293.64
  5740.2  2303.7  5778.5  2312.8  5783.5 2309.86  5790.2 2312.57  5820.2 2327.94
  5870.2  2359.7  5900.2    2383  5940.2 2403.21  5998.6 2430.16  6001.9 2430.16
#Mann= 4 ,-1 , 0
  3474.7     .07       0  4993.4     .07       0  5000.2     .07       0
  5047.2     .16       0
Bank Sta=4993.4,5000.2
XS Rating Curve= 0 ,0
Exp/Cntr=0.3,0.1

Type RM Length L Ch R = 1 ,19481   ,496,496,496
BEGIN DESCRIPTION:
WEAVER SPRINGS CREEK TRIB 1 29.0
END DESCRIPTION:
XS GIS Cut Line= 3
      1448375.28      6834874.47        1449655.        6833488.
      1449302.54      6832432.37
#Sta/Elev= 30
  3131.3  2280.6  3361.9 2271.45  3673.3 2266.29  3878.6 2259.57  3984.6 2259.48
  4522.8 2249.52    4728 2239.45  4855.1 2239.16  4876.6 2235.95  4979.2 2230.85
  4979.7 2230.35    4986 2230.85  5065.5 2234.82  5160.3 2233.22  5228.9 2239.05
  5376.2 2239.97  5460.2 2243.24  5597.5 2252.52  5634.3 2257.68  5665.9 2266.19
  5823.9 2327.01  5881.9 2351.58  5924.8 2372.97  6008.3 2402.45  6019.6 2409.42
  6039.9 2413.37  6047.3  2417.9  6076.8 2430.91  6093.4  2443.8    6131 2446.25
#Mann= 6 ,-1 , 0
  3131.3     .16       0  3361.9     .07       0  4979.2     .07       0
    4986     .07       0  5460.2     .16       0  6047.3     .07       0
Bank Sta=4979.2,4986
XS Rating Curve= 0 ,0
Exp/Cntr=0.3,0.1

Type RM Length L Ch R = 1 ,18985   ,139,139,139
BEGIN DESCRIPTION:
WEAVER SPRINGS CREEK TRIB 1 28.0
END DESCRIPTION:
XS GIS Cut Line= 4
      1450182.25      6834694.07      1450093.71      6833496.13
        1449905.        6833138.      1449449.08      6832339.62
#Sta/Elev= 30
  3398.3 2276.44  3538.9 2275.77  3795.5 2270.53  3885.7 2266.87  3945.9 2262.06
    4006 2261.34  4026.1  2258.6  4375.3  2248.1  4518.3 2237.25  4675.6 2233.61
  4802.5 2231.41  4873.9 2230.94    4968 2227.54  4968.5 2227.04  4980.1 2227.54
  5039.6 2232.19  5091.1 2232.84  5291.6 2238.68  5362.9 2246.13  5545.6 2281.55
  5555.1 2280.96  5560.8 2284.59  5576.7 2286.04  5582.4 2290.27  5591.6 2291.22
    5604 2296.69  5649.2 2309.63  5700.5  2329.2  5781.2  2369.2  5923.7 2443.61
#Mann= 9 ,-1 , 0
  3398.3     .16       0  3538.9     .07       0  4675.6     .16       0
  4802.5     .07       0  4873.9     .16       0    4968     .07       0
  4980.1     .16       0  5091.1     .07       0  5362.9     .16       0
Bank Sta=4968,4980.1
XS Rating Curve= 0 ,0
Exp/Cntr=0.3,0.1

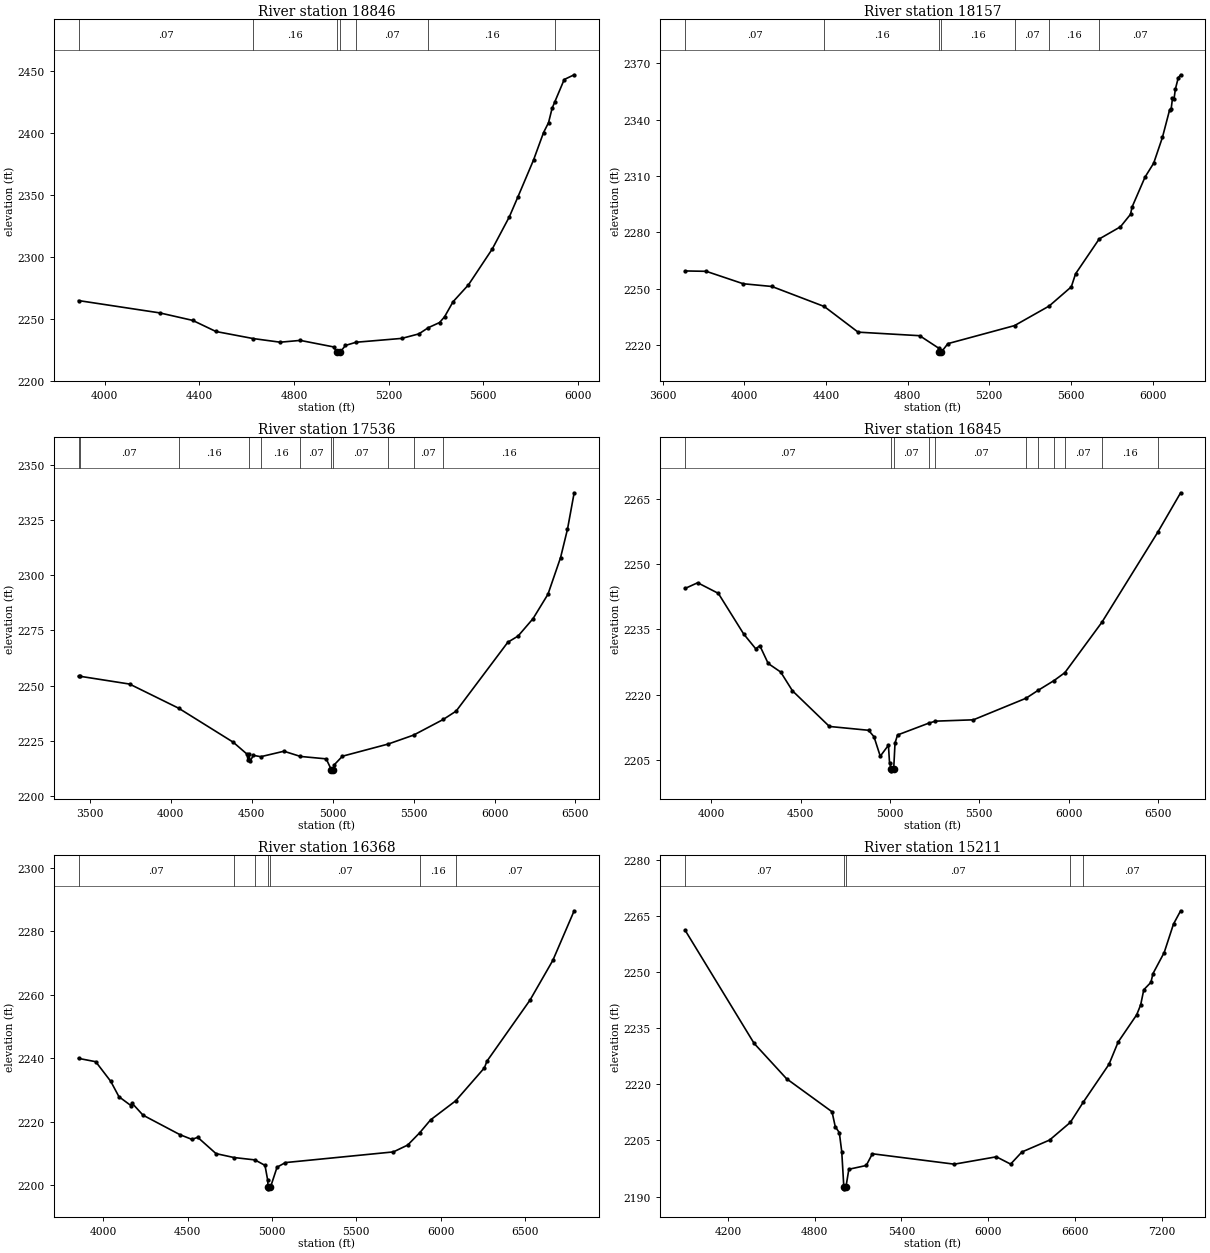
Type RM Length L Ch R = 1 ,18846   ,689,689,689
BEGIN DESCRIPTION:
WEAVER SPRINGS CREEK TRIB 1 27.0
END DESCRIPTION:
XS GIS Cut Line= 4
        1450280.      6834162.98      1450172.51      6833433.23
      1450029.95      6833087.82      1449489.25      6832264.25
#Sta/Elev= 30
  3888.7 2264.49  4232.1 2254.56  4371.5 2248.51  4469.9 2239.55  4627.7 2233.85
  4741.7 2230.92  4826.7 2232.37  4967.4 2227.12  4982.9 2222.84  4983.4 2222.34
    4995 2222.84  5017.9 2228.31  5062.7 2230.88    5256 2233.99  5328.3 2237.62
  5368.6 2242.66  5415.7 2246.76  5436.8 2251.35    5473 2263.56  5538.1 2277.19
  5638.7 2306.06    5711 2332.02  5747.2 2348.07  5813.2 2377.78  5855.7 2399.98
  5876.8 2407.97  5891.9 2419.57  5903.6 2424.88  5943.1 2442.75  5985.2 2446.57
#Mann= 7 ,-1 , 0
  3888.7     .07       0  4627.7     .16       0  4982.9     .07       0
    4995     .16       0  5062.7     .07       0  5368.6     .16       0
  5903.6     .07       0
Bank Sta=4982.9,4995
XS Rating Curve= 0 ,0
Exp/Cntr=0.3,0.1

Type RM Length L Ch R = 1 ,18157   ,621,621,621
BEGIN DESCRIPTION:
WEAVER SPRINGS CREEK TRIB 1 26.0
END DESCRIPTION:
XS GIS Cut Line= 3
      1450425.55      6834021.56        1450555.        6832738.
      1449791.89      6831894.83
#Sta/Elev= 30
  3709.7 2259.46  3813.8 2259.26  3994.7 2252.65  4135.4 2251.19  4391.8 2240.54
  4557.5 2226.89  4859.1    2225  4952.2 2218.36  4953.5 2216.38    4954 2215.88
  4965.6 2216.38  4997.3 2220.78  5323.5 2230.37  5493.1 2240.79  5601.6    2251
  5622.6 2257.96    5738 2276.45  5842.3 2282.96  5891.6  2289.6    5899 2293.43
  5962.6 2309.39  6005.1 2316.83  6047.7 2330.48  6082.9  2345.1  6090.3 2345.45
  6097.1 2351.26  6104.5 2350.82  6111.2 2356.22  6125.4 2362.25    6137 2363.85
#Mann= 7 ,-1 , 0
  3709.7     .07       0  4391.8     .16       0  4953.5     .07       0
  4965.6     .16       0  5323.5     .07       0  5493.1     .16       0
    5738     .07       0
Bank Sta=4953.5,4965.6
XS Rating Curve= 0 ,0
Exp/Cntr=0.3,0.1

Type RM Length L Ch R = 1 ,17536   ,691,691,691
BEGIN DESCRIPTION:
WEAVER SPRINGS CREEK TRIB 1 25.0
END DESCRIPTION:
XS GIS Cut Line= 3
      1450599.15      6833943.47      1451049.03      6832440.14
      1449918.86      6831466.09
#Sta/Elev= 30
  3430.8 2254.23    3440 2254.21  3746.1 2250.69  4049.6 2239.75  4386.4 2224.38
  4469.9 2219.09  4477.6 2216.43  4483.1 2218.97  4490.8 2215.79  4510.7 2218.44
  4556.5 2217.83  4699.5  2220.3  4801.6 2217.94  4960.5 2216.85  4992.4 2211.93
  4992.9 2211.43  5004.6 2211.93  5011.4 2214.25  5060.8 2218.05  5343.6 2223.56
  5500.3  2227.6    5683 2234.66    5763 2238.45  6082.2  2269.6  6145.8 2272.43
    6238 2280.29  6330.2 2291.33  6408.1 2307.93  6450.8 2320.78    6492 2337.23
#Mann= 11 ,-1 , 0
  3430.8     .16       0    3440     .07       0  4049.6     .16       0
  4483.1     .07       0  4556.5     .16       0  4801.6     .07       0
  4992.4     .07       0  5004.6     .07       0  5343.6     .16       0
  5500.3     .07       0    5683     .16       0
Bank Sta=4992.4,5004.6
XS Rating Curve= 0 ,0
Exp/Cntr=0.3,0.1

Type RM Length L Ch R = 1 ,16845   ,477,477,477
BEGIN DESCRIPTION:
WEAVER SPRINGS CREEK TRIB 1 23.0
END DESCRIPTION:
XS GIS Cut Line= 3
      1452118.26      6833538.92        1451655.        6832488.
      1450454.99      6831387.99
#Sta/Elev= 30
  3851.5 2244.42  3922.6 2245.74  4038.3  2243.3  4180.4 2233.95  4247.6 2230.56
    4271 2231.25  4317.6 2227.17  4387.6  2225.2  4453.6 2220.88  4660.5 2212.68
  4879.8  2211.8  4910.2 2210.32  4945.4 2205.83  4991.1 2208.36  4997.3 2204.34
    5007 2202.97  5007.5 2202.47  5020.7 2202.97  5028.1 2208.88  5042.2 2210.72
  5216.3 2213.43  5254.3  2213.9  5467.1 2214.21  5761.7 2219.17  5829.2 2220.98
  5919.2 2223.25  5979.5 2225.06  6186.9 2236.65  6499.1 2257.32  6627.9 2266.44
#Mann= 11 ,-1 , 0
  3851.5     .07       0    5007     .07       0  5020.7     .07       0
  5216.3     .16       0  5254.3     .07       0  5761.7     .16       0
  5829.2     .07       0  5919.2     .16       0  5979.5     .07       0
  6186.9     .16       0  6499.1     .07       0
Bank Sta=5007,5020.7
XS Rating Curve= 0 ,0
Exp/Cntr=0.3,0.1

Type RM Length L Ch R = 1 ,16368   ,1157,1157,1157
BEGIN DESCRIPTION:
WEAVER SPRINGS CREEK TRIB 1 22.0
END DESCRIPTION:
XS GIS Cut Line= 3
      1452213.75      6833417.41        1452055.        6832288.
      1450912.91      6830901.54
#Sta/Elev= 30
  3854.2 2239.97  3956.3 2238.92  4045.5 2232.72  4093.8 2227.91  4165.1 2225.11
  4170.1 2225.96  4236.3 2222.11  4455.2 2215.97  4526.4 2214.48  4560.5 2215.14
    4669 2210.01  4775.2 2208.78  4899.6 2208.03  4959.1 2206.31  4974.5 2201.83
  4977.8 2199.43  4978.3 2198.93  4991.5 2199.43  5030.6 2205.74  5080.1 2207.19
  5719.9 2210.55  5804.6  2212.7    5876 2216.58  5940.1 2220.62  6088.6  2226.6
  6259.4    2237  6273.7 2239.05  6529.1 2258.28  6664.6  2270.8    6791  2286.4
#Mann= 7 ,-1 , 0
  3854.2     .07       0  4775.2     .16       0  4899.6     .07       0
  4977.8     .07       0  4991.5     .07       0    5876     .16       0
  6088.6     .07       0
Bank Sta=4977.8,4991.5
XS Rating Curve= 0 ,0
Exp/Cntr=0.3,0.1

Type RM Length L Ch R = 1 ,15211   ,1971,1971,1971
BEGIN DESCRIPTION:
WEAVER SPRINGS CREEK TRIB 1 21.0
END DESCRIPTION:
XS GIS Cut Line= 3
      1453562.41      6833250.13      1453070.68      6832254.52
       1451349.8      6830703.23
#Sta/Elev= 30
  3903.3 2261.23  4381.3 2230.94  4605.8 2221.49    4920 2212.67  4942.4 2208.69
  4970.5 2207.09  4987.3 2202.02  5001.7 2192.57  5002.2 2192.07  5016.4 2192.57
  5036.3  2197.3  5156.6 2198.31  5199.2 2201.44  5765.7 2198.66  6056.4 2200.63
    6155 2198.68  6233.1 2201.92  6424.1  2205.1  6568.4 2209.85  6658.2 2215.28
  6835.1 2225.34  6898.7 2231.31  7026.5 2238.56  7054.3 2241.23  7075.8 2245.27
  7125.1 2247.25  7139.3 2249.58    7217 2255.22  7281.3 2262.83  7330.6 2266.37
#Mann= 5 ,-1 , 0
  3903.3     .07       0  5001.7     .07       0  5016.4     .07       0
  6568.4     .16       0  6658.2     .07       0
Bank Sta=5001.7,5016.4
XS Rating Curve= 0 ,0
Exp/Cntr=0.3,0.1