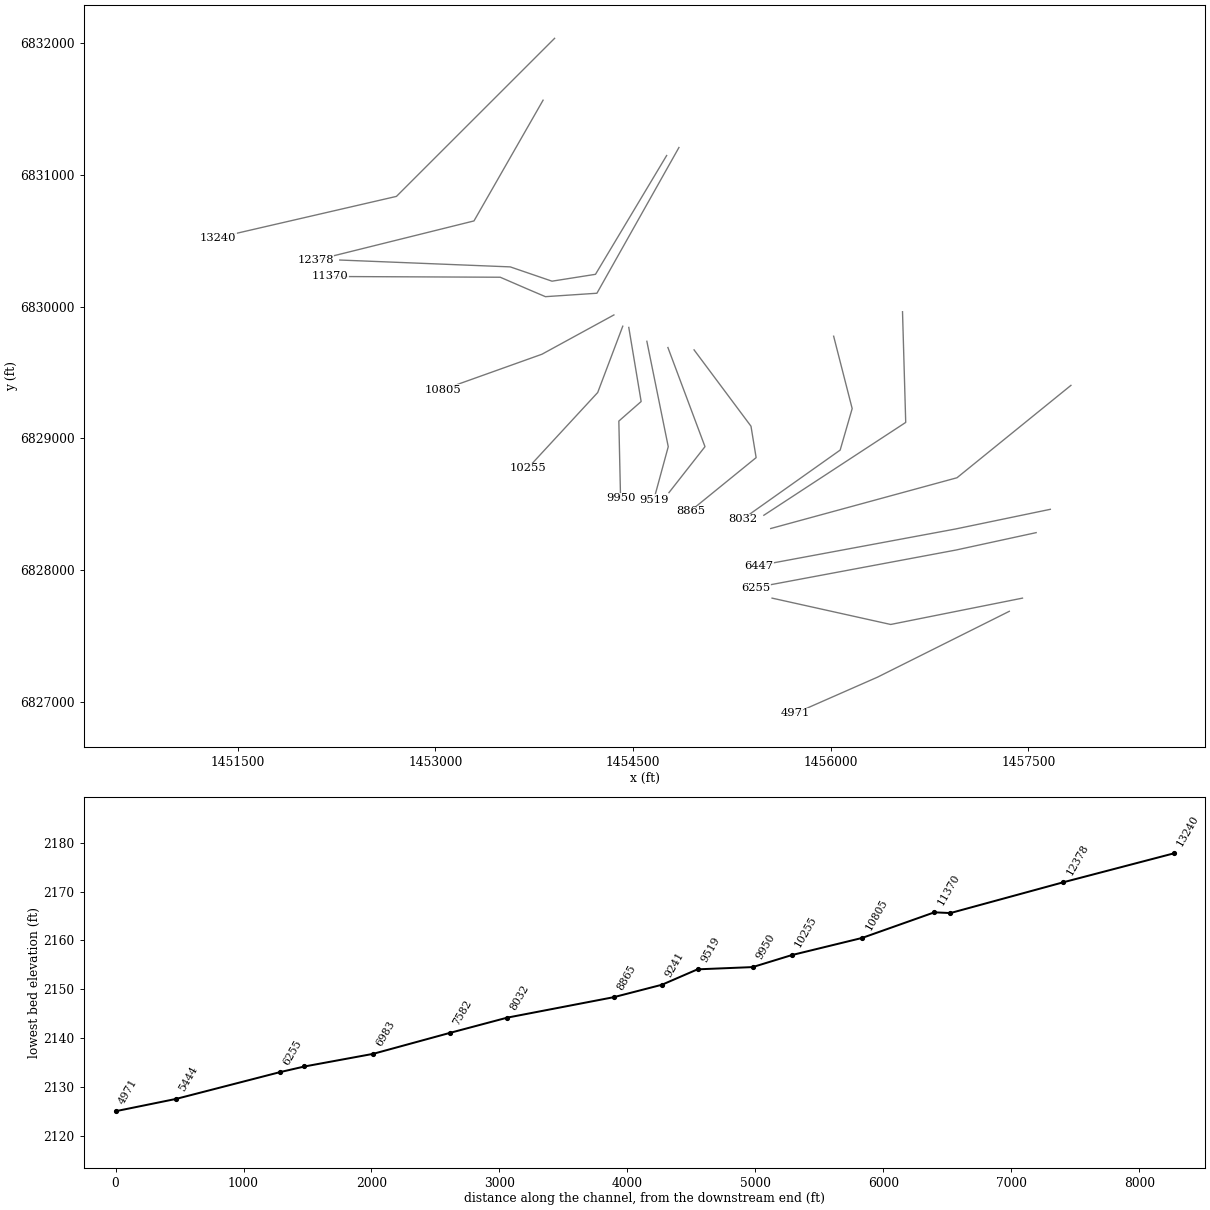
HEC-RAS study WEAVER SPRINGS CREEK TRIB 1.prj: WEAVER SPRINGS CREEK TRIB 1 Base Level Engineering

--- WEAVER SPRINGS CREEK TRIB 1.g01 (geometry) --- (continued)

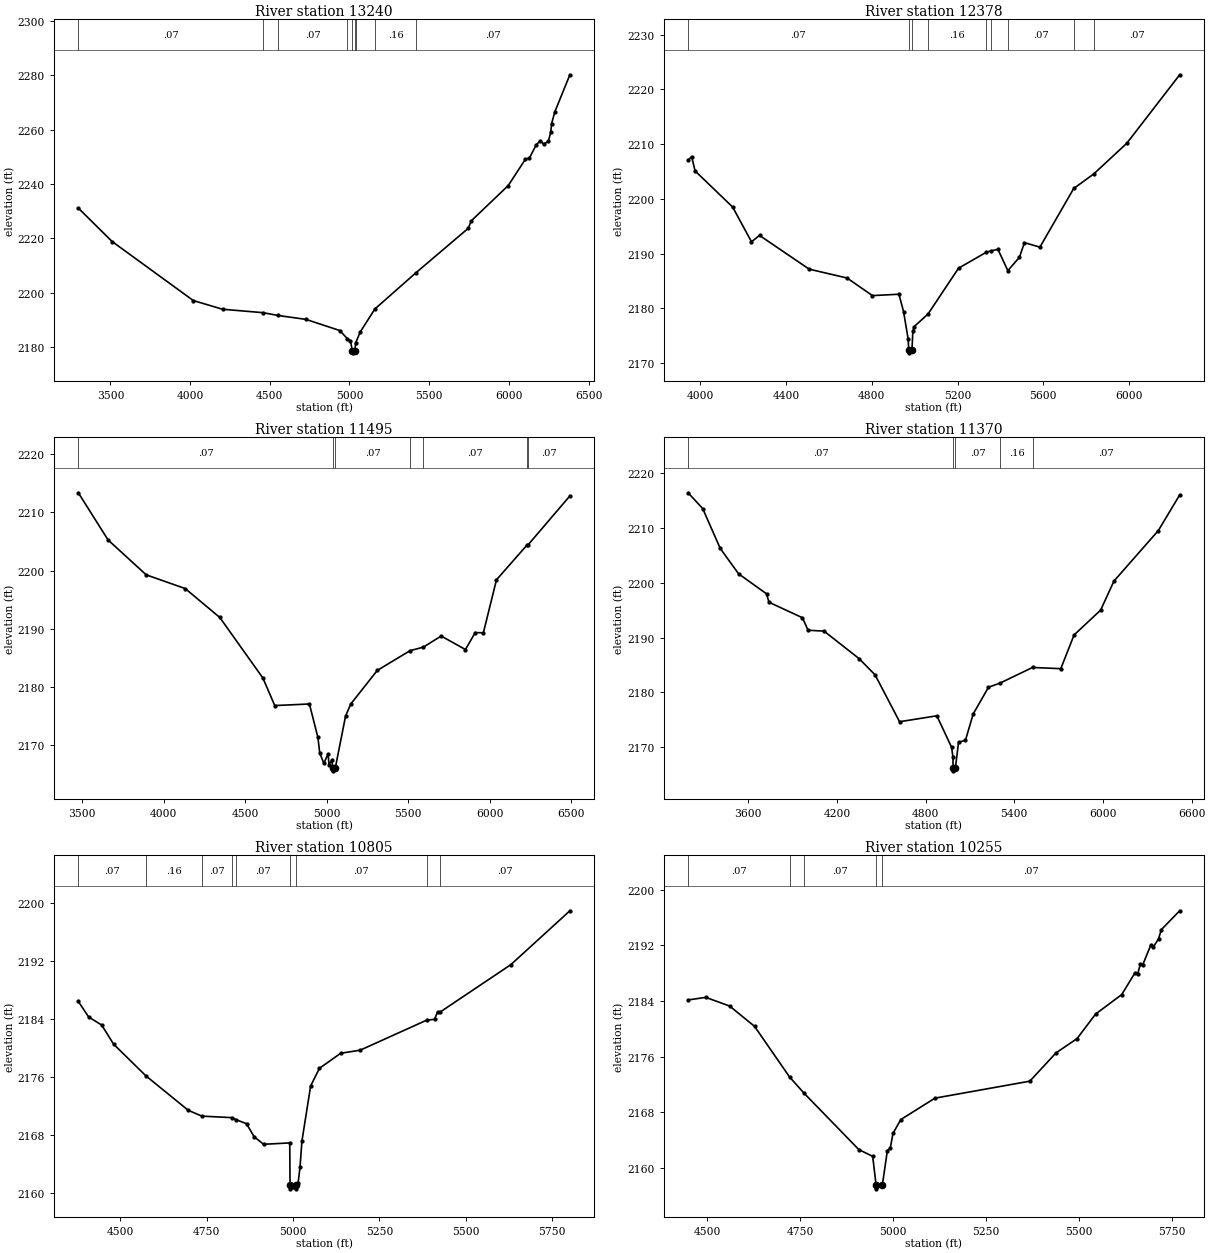
Type RM Length L Ch R = 1 ,13240   ,862,862,862
BEGIN DESCRIPTION:
WEAVER SPRINGS CREEK TRIB 1 20.0
END DESCRIPTION:
XS GIS Cut Line= 3
      1453904.99      6832037.99        1452705.        6830838.
      1451353.24      6830525.75
#Sta/Elev= 30
  3298.7 2231.09  3510.8 2218.79  4019.9 2197.06  4203.8 2193.85    4458 2192.59
  4552.1 2191.55    4727 2190.12  4939.2 2186.01    4986 2183.06    5006 2182.26
    5019  2178.3  5019.5  2177.8    5034  2178.3  5038.4 2181.35  5067.6 2185.47
  5159.5 2193.95  5417.6  2207.3    5745 2223.63  5765.5 2226.46  5995.9 2239.36
  6104.2 2249.09  6129.3 2249.51    6172  2254.4  6196.6 2255.81  6219.9 2254.67
  6247.9 2255.68  6262.6 2258.93  6268.4 2262.18  6288.9 2266.56  6383.1 2280.17
#Mann= 9 ,-1 , 0
  3298.7     .07       0    4458     .16       0  4552.1     .07       0
    4986     .16       0    5019     .07       0    5034     .16       0
  5038.4     .07       0  5159.5     .16       0  5417.6     .07       0
Bank Sta=5019,5034
XS Rating Curve= 0 ,0
Exp/Cntr=0.3,0.1

Type RM Length L Ch R = 1 ,12378   ,883,883,883
BEGIN DESCRIPTION:
Mapping XS 91f88f4e
END DESCRIPTION:
XS GIS Cut Line= 3
      1453817.64      6831568.46      1453293.32      6830651.77
      1452091.92      6830353.16
#Sta/Elev= 30
  3942.8 2207.07  3959.4 2207.73  3975.2 2205.12  4150.7 2198.52  4238.6 2192.17
  4276.1 2193.34  4507.8 2187.18  4684.8 2185.56  4802.9 2182.35  4926.6  2182.6
  4948.2 2179.44  4969.8  2174.4  4972.3  2172.4  4972.8  2171.9  4987.4  2172.4
  4991.7 2175.89  4998.1  2176.7  5062.8 2179.01  5204.7 2187.35  5333.2 2190.24
    5356 2190.52  5388.7 2190.79  5434.9 2186.91  5488.9 2189.34  5512.3 2192.02
  5584.5  2191.2  5742.3 2201.91  5835.4 2204.55  5990.1 2210.17  6236.8 2222.67
#Mann= 9 ,-1 , 0
  3942.8     .07       0  4972.3     .07       0  4987.4     .07       0
  5062.8     .16       0  5333.2     .07       0    5356     .16       0
  5434.9     .07       0  5742.3     .16       0  5835.4     .07       0
Bank Sta=4972.3,4987.4
XS Rating Curve= 0 ,0
Exp/Cntr=0.3,0.1

Type RM Length L Ch R = 1 ,11495   ,125,125,125
BEGIN DESCRIPTION:
WEAVER SPRINGS CREEK TRIB 1 19.0
END DESCRIPTION:
XS GIS Cut Line= 5
      1454755.12      6831148.28       1454215.2      6830246.39
      1453885.34      6830194.31       1453568.5      6830302.81
      1452275.05       6830354.9
#Sta/Elev= 30
  3477.1 2213.35  3660.2 2205.23  3893.5 2199.26  4132.7  2196.9  4344.7 2191.94
  4609.2 2181.53  4681.8 2176.81  4894.3 2177.08  4946.3 2171.35  4957.7 2168.65
  4982.9 2166.88  5008.9 2168.54  5014.2 2166.65  5031.7 2167.44  5037.8  2166.1
  5038.3  2165.6  5053.1  2166.1  5116.2 2175.02    5148 2177.08  5310.7 2182.85
  5511.1 2186.23  5593.6 2186.85  5702.4 2188.75  5851.1 2186.43  5911.2 2189.34
  5961.2 2189.31  6041.3  2198.4  6227.7 2204.34  6236.5 2204.45  6491.6 2212.81
#Mann= 7 ,-1 , 0
  3477.1     .07       0  5037.8     .07       0  5053.1     .07       0
  5511.1     .16       0  5593.6     .07       0  6227.7     .16       0
  6236.5     .07       0
Bank Sta=5037.8,5053.1
XS Rating Curve= 0 ,0
Exp/Cntr=0.3,0.1

Type RM Length L Ch R = 1 ,11370   ,565,565,565
BEGIN DESCRIPTION:
WEAVER SPRINGS CREEK TRIB 1 18.0
END DESCRIPTION:
XS GIS Cut Line= 6
      1454848.39      6831209.21      1454226.05      6830102.73
      1453835.42      6830076.68      1453703.05      6830133.11
      1453492.54      6830224.25      1452200.43       6830229.9
#Sta/Elev= 30
  3192.8 2216.32  3291.6 2213.45  3410.2  2206.2  3534.5 2201.58  3723.8 2197.94
  3739.7 2196.42  3966.6 2193.59  4004.3 2191.32  4112.6 2191.16  4349.7 2186.16
  4458.1  2183.2  4623.7 2174.68    4876 2175.76  4975.6 2170.04  4984.7  2168.3
  4986.1 2166.25  4986.6 2165.75  5001.4 2166.25  5022.7 2170.92  5069.7 2171.32
  5122.1 2176.11  5225.5 2180.95  5306.4 2181.74  5523.4 2184.55  5714.6 2184.33
  5804.6 2190.46  5984.6 2194.99  6074.6 2200.27  6374.6 2209.44  6519.2 2215.93
#Mann= 5 ,-1 , 0
  3192.8     .07       0  4986.1     .07       0  5001.4     .07       0
  5306.4     .16       0  5523.4     .07       0
Bank Sta=4986.1,5001.4
XS Rating Curve= 0 ,0
Exp/Cntr=0.3,0.1

Type RM Length L Ch R = 1 ,10805   ,550,550,550
BEGIN DESCRIPTION:
WEAVER SPRINGS CREEK TRIB 1 17.0
END DESCRIPTION:
XS GIS Cut Line= 3
      1454354.98      6829937.99      1453808.97      6829639.65
      1453054.14      6829369.84
#Sta/Elev= 30
  4377.8 2186.39  4407.7 2184.24  4445.6 2183.12  4480.3 2180.47  4573.8  2176.1
  4696.1 2171.36  4735.5 2170.55  4822.2 2170.34  4834.3 2170.07    4865  2169.5
  4886.8 2167.72  4914.3 2166.66  4990.2 2166.85  4991.1 2161.01  4991.6 2160.51
  5007.2 2160.51  5007.7 2161.01  5014.6 2161.38  5019.9 2163.46  5025.5 2167.11
  5050.7 2174.71  5076.2 2177.15  5137.8 2179.23    5194 2179.65  5386.9  2183.8
  5409.5 2183.91  5418.4 2184.95  5425.6 2184.91  5630.8 2191.47  5801.6  2198.9
#Mann= 9 ,-1 , 0
  4377.8     .07       0  4573.8     .16       0  4735.5     .07       0
  4822.2     .16       0  4834.3     .07       0  4991.1     .07       0
  5007.7     .07       0  5386.9     .16       0  5425.6     .07       0
Bank Sta=4991.1,5007.7
XS Rating Curve= 0 ,0
Exp/Cntr=0.3,0.1

Type RM Length L Ch R = 1 ,10255   ,305,305,305
BEGIN DESCRIPTION:
WEAVER SPRINGS CREEK TRIB 1 16.0
END DESCRIPTION:
XS GIS Cut Line= 3
      1454422.19      6829852.47      1454232.13      6829349.09
      1453700.18      6828772.85
#Sta/Elev= 30
    4448 2184.16  4495.5 2184.53  4559.7 2183.28  4626.6 2180.37  4721.1 2173.07
  4760.3 2170.73  4907.1 2162.65  4944.5 2161.67  4953.8  2157.5  4954.3    2157
  4970.4  2157.5    4984  2162.5  4991.8 2162.84  4999.2 2164.98  5020.1 2166.96
    5112 2170.04  5367.2 2172.48  5437.5 2176.54  5494.2  2178.6  5544.1 2182.13
  5614.4 2184.93  5650.1 2188.06  5656.9 2187.83  5664.3 2189.27  5671.1 2189.23
  5692.6 2192.05  5699.5 2191.77  5713.6 2192.97    5721 2194.27  5770.3 2196.98
#Mann= 5 ,-1 , 0
    4448     .07       0  4721.1     .16       0  4760.3     .07       0
  4953.8     .07       0  4970.4     .07       0
Bank Sta=4953.8,4970.4
XS Rating Curve= 0 ,0
Exp/Cntr=0.3,0.1

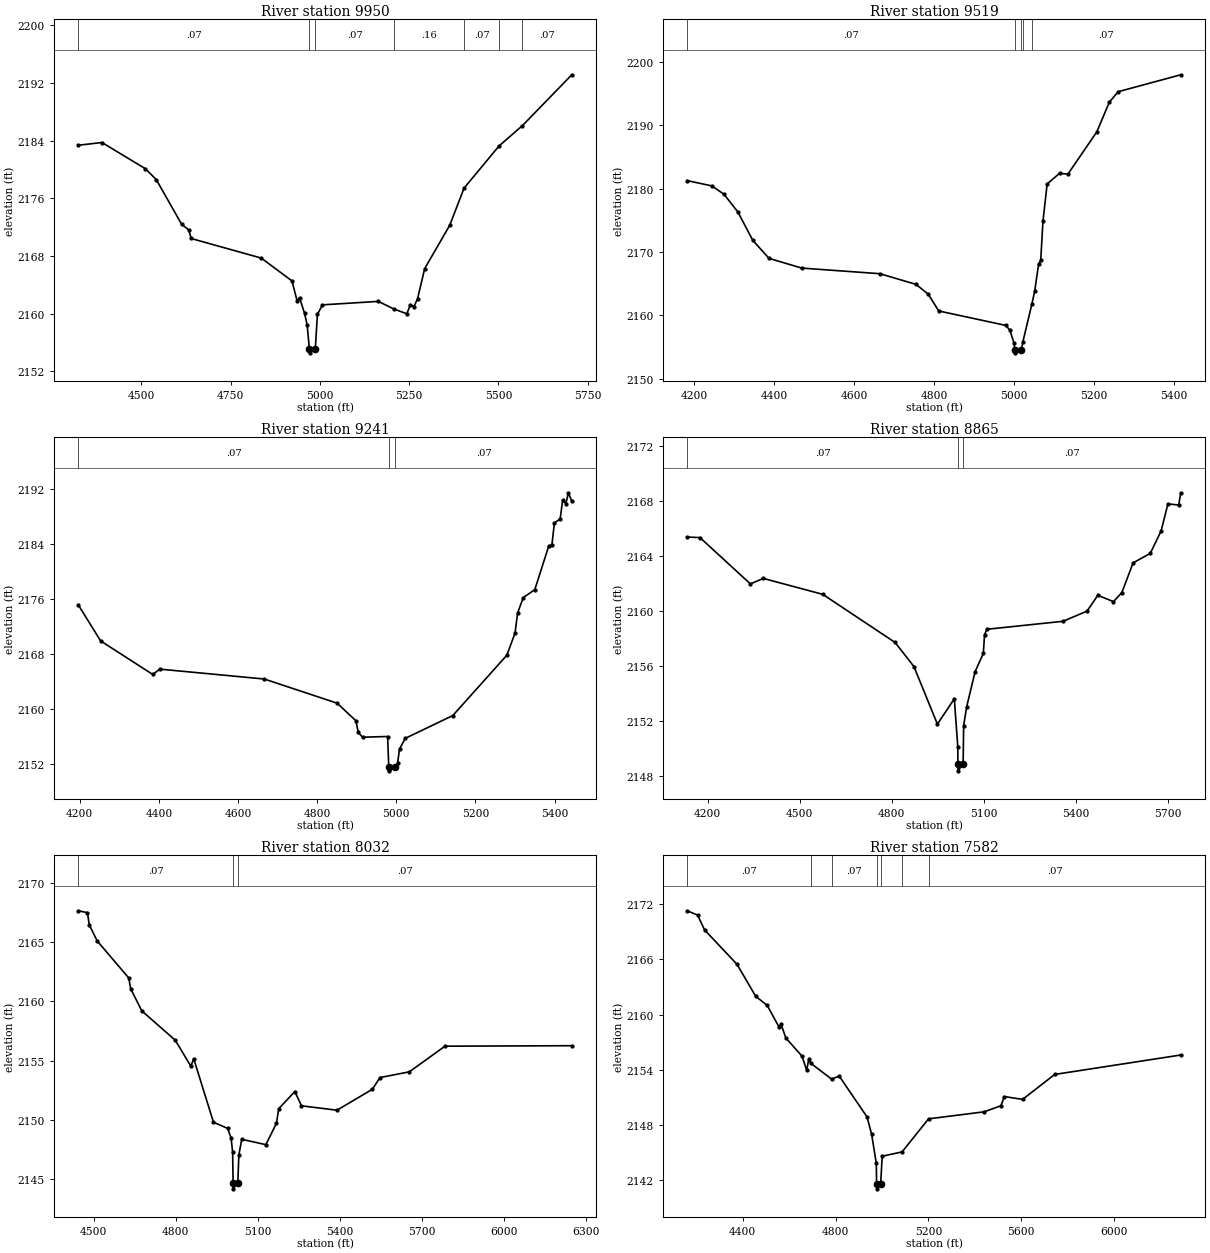
Type RM Length L Ch R = 1 ,9950    ,431,431,431
BEGIN DESCRIPTION:
WEAVER SPRINGS CREEK TRIB 1 15.0
END DESCRIPTION:
XS GIS Cut Line= 4
      1454467.91      6829843.14      1454561.66       6829280.6
      1454392.39      6829132.17      1454405.41      6828546.24
#Sta/Elev= 30
    4324 2183.36    4390 2183.74  4511.7  2180.1  4542.1 2178.59  4613.1 2172.39
  4633.3  2171.6  4639.6 2170.42  4836.1  2167.7    4922 2164.53  4936.3 2161.78
  4943.1 2162.19  4957.2 2160.06  4964.7 2158.36  4970.7 2155.05  4971.2 2154.55
  4987.3 2155.05  4993.2 2159.88  5007.4 2161.21  5163.6 2161.69  5208.1 2160.62
  5243.6 2159.97  5253.6 2161.24  5263.6 2160.96  5273.6 2162.05  5293.6 2166.24
  5363.7 2172.25  5403.9 2177.41  5501.8 2183.26  5567.4 2186.09  5705.5 2193.14
#Mann= 7 ,-1 , 0
    4324     .07       0  4970.7     .07       0  4987.3     .07       0
  5208.1     .16       0  5403.9     .07       0  5501.8     .16       0
  5567.4     .07       0
Bank Sta=4970.7,4987.3
XS Rating Curve= 0 ,0
Exp/Cntr=0.3,0.1

Type RM Length L Ch R = 1 ,9519    ,278,278,278
BEGIN DESCRIPTION:
WEAVER SPRINGS CREEK TRIB 1 14.0
END DESCRIPTION:
XS GIS Cut Line= 3
        1454605.      6829737.98       1454767.3      6828937.67
        1454658.      6828535.77
#Sta/Elev= 30
  4183.4 2181.27  4244.6 2180.44  4275.2 2179.11    4310 2176.29  4346.6 2171.88
  4387.5    2169  4469.1 2167.47  4664.7 2166.58  4754.8  2164.9  4785.4 2163.35
  4811.6  2160.7  4979.3 2158.42  4989.5 2157.66    5000 2155.59  5001.6 2154.59
  5002.1 2154.09  5018.5 2154.59  5021.7 2155.77  5044.2 2161.73  5051.5 2163.82
  5061.3 2168.14  5066.5 2168.67  5072.2  2174.9  5082.6 2180.75  5113.7 2182.43
  5134.4 2182.29  5206.9 2188.99    5238 2193.66  5260.2 2195.31  5416.5 2197.98
#Mann= 5 ,-1 , 0
  4183.4     .07       0  5001.6     .07       0  5018.5     .07       0
  5021.7     .16       0  5044.2     .07       0
Bank Sta=5001.6,5018.5
XS Rating Curve= 0 ,0
Exp/Cntr=0.3,0.1

Type RM Length L Ch R = 1 ,9241    ,376,376,376
BEGIN DESCRIPTION:
Mapping XS 1b87f6dd
END DESCRIPTION:
XS GIS Cut Line= 3
      1454764.78      6829690.55      1455046.04      6828937.99
      1454772.58      6828588.96
#Sta/Elev= 30
  4196.6 2175.13  4252.7  2169.9  4384.5    2165  4402.2 2165.78  4666.1 2164.34
  4850.5 2160.81  4897.8 2158.25  4903.9 2156.54  4914.6 2155.85    4978 2155.95
  4980.9 2151.44  4981.4 2150.94  4997.8 2151.44  5003.2 2152.09  5008.1 2154.12
  5022.5 2155.68  5142.8 2159.01  5279.3 2167.81  5300.1 2171.06  5306.4 2173.96
  5320.9 2176.23  5349.8 2177.36  5385.1 2183.72  5393.2 2183.93  5399.5 2187.12
    5414 2187.68  5420.4 2190.45  5428.5 2189.91  5434.8 2191.51  5443.4 2190.29
#Mann= 3 ,-1 , 0
  4196.6     .07       0  4980.9     .07       0  4997.8     .07       0
Bank Sta=4980.9,4997.8
XS Rating Curve= 0 ,0
Exp/Cntr=0.3,0.1

Type RM Length L Ch R = 1 ,8865    ,833,833,833
BEGIN DESCRIPTION:
Mapping XS 7f3bdc6a
END DESCRIPTION:
XS GIS Cut Line= 4
      1454963.14      6829672.81      1455395.02      6829093.35
      1455434.09      6828854.64      1454934.93       6828448.8
#Sta/Elev= 30
  4133.9 2165.41    4175 2165.37  4339.4    2162  4381.4  2162.4  4575.3 2161.24
  4810.9 2157.74  4872.2 2155.99  4948.7  2151.8  5003.9 2153.64  5015.2 2150.15
  5015.6  2148.9  5016.1  2148.4  5032.6  2148.9  5034.3 2151.69  5044.4 2153.08
  5071.5 2155.61  5098.5 2156.95  5102.4 2158.31  5110.2  2158.7  5358.1 2159.28
  5436.4 2160.02  5471.6 2161.17  5522.6 2160.71  5549.9 2161.37  5586.5 2163.53
  5642.5 2164.22  5677.7 2165.85    5700 2167.82  5735.2 2167.74  5741.8 2168.63
#Mann= 3 ,-1 , 0
  4133.9     .07       0  5015.6     .07       0  5032.6     .07       0
Bank Sta=5015.6,5032.6
XS Rating Curve= 0 ,0
Exp/Cntr=0.3,0.1

Type RM Length L Ch R = 1 ,8032    ,450,450,450
BEGIN DESCRIPTION:
Mapping XS e25ed4b3
END DESCRIPTION:
XS GIS Cut Line= 4
      1456022.19      6829776.53      1456162.82      6829227.03
      1456071.67      6828911.93      1455329.76      6828386.08
#Sta/Elev= 30
  4444.5 2167.62  4477.6 2167.46  4484.3 2166.43  4513.2 2165.08  4628.8 2161.96
  4635.6 2161.06  4676.5 2159.19  4798.9 2156.72  4855.9 2154.53  4866.2 2155.17
  4938.5 2149.82  4990.1  2149.3  5002.9  2148.5  5008.6 2147.32  5010.3 2144.71
  5010.8 2144.21  5027.5 2144.71  5031.5 2147.08  5041.9 2148.38  5130.1 2147.93
  5168.9 2149.73  5177.3 2150.96  5236.1  2152.4  5260.5  2151.2  5390.3 2150.83
  5519.5 2152.59  5547.8 2153.58  5654.8 2154.06  5785.3 2156.22  6249.1 2156.26
#Mann= 3 ,-1 , 0
  4444.5     .07       0  5010.3     .07       0  5027.5     .07       0
Bank Sta=5010.3,5027.5
XS Rating Curve= 0 ,0
Exp/Cntr=0.3,0.1

Type RM Length L Ch R = 1 ,7582    ,599,599,599
BEGIN DESCRIPTION:
Mapping XS 7fe559d7
END DESCRIPTION:
XS GIS Cut Line= 3
      1456544.76      6829962.29      1456569.07        6829122.
      1455492.66      6828417.13
#Sta/Elev= 30
    4161 2171.27  4205.3 2170.79  4235.3 2169.19  4375.4 2165.45  4455.4 2161.99
  4505.4 2160.99  4555.5 2158.68  4565.5 2158.93  4585.5 2157.46  4655.5 2155.48
  4675.5 2153.93  4684.2 2155.15  4692.9 2154.72  4783.1 2152.99  4815.6 2153.33
  4935.6 2148.89  4955.6 2146.99  4975.6 2143.85    4977 2141.58  4977.5 2141.08
  4994.3 2141.58  5001.1 2144.62  5086.7 2145.09  5200.9 2148.68  5440.4 2149.44
  5512.7  2150.1  5527.8  2151.1  5606.2 2150.79  5744.9  2153.5  6288.3 2155.61
#Mann= 7 ,-1 , 0
    4161     .07       0  4692.9     .16       0  4783.1     .07       0
    4977     .07       0  4994.3     .07       0  5086.7    .035       0
  5200.9     .07       0
Bank Sta=4977,4994.3
XS Rating Curve= 0 ,0
Exp/Cntr=0.3,0.1

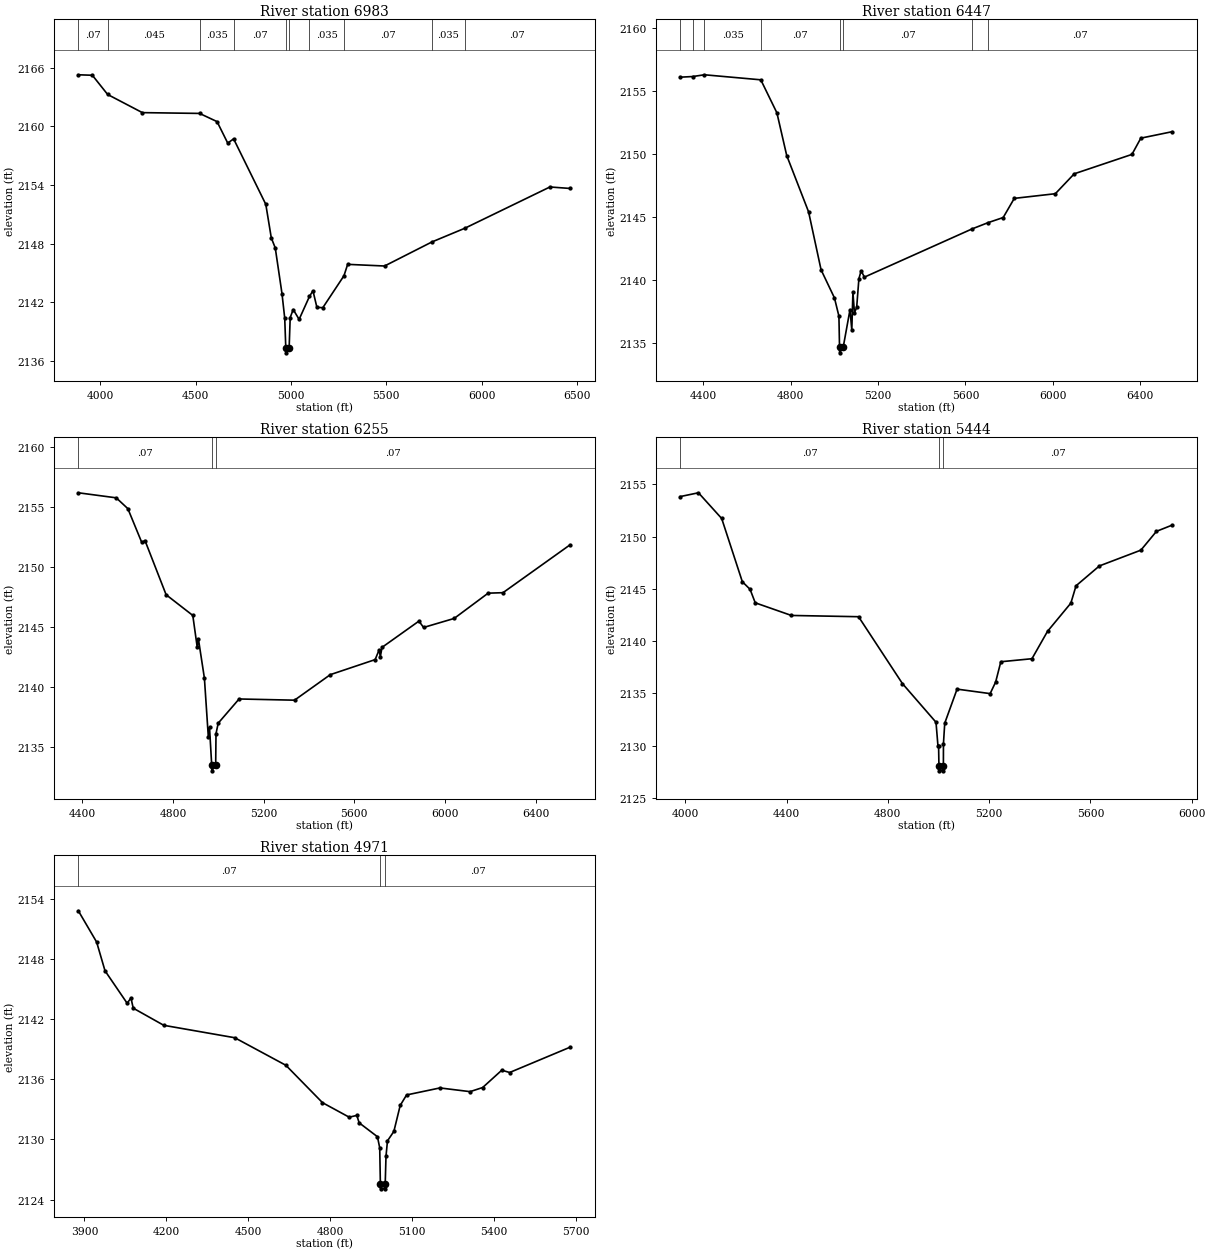
Type RM Length L Ch R = 1 ,6983    ,536,536,536
BEGIN DESCRIPTION:
Mapping XS d0d2b6c0
END DESCRIPTION:
XS GIS Cut Line= 3
      1457822.57      6829403.27      1456957.96      6828701.86
      1455544.81      6828316.45
#Sta/Elev= 30
  3885.1  2165.3  3958.8 2165.25    4039 2163.28    4221 2161.42  4520.9 2161.34
  4612.6  2160.5  4668.6  2158.3  4699.5 2158.73  4868.3 2152.02  4897.1 2148.58
  4917.9 2147.55  4953.1 2142.88  4967.5 2140.35  4973.1  2137.3  4973.6  2136.8
  4990.6  2137.3  4996.2 2140.42  5011.9 2141.24    5043 2140.23  5097.4 2142.59
  5115.5 2143.16  5136.3 2141.46  5167.3 2141.43  5278.1  2144.7  5297.5 2145.87
    5491  2145.7  5739.9 2148.17  5911.9 2149.57  6358.2  2153.8  6463.2 2153.65
#Mann= 10 ,-1 , 0
  3885.1     .07       0    4039    .045       0  4520.9    .035       0
  4699.5     .07       0  4973.1     .07       0  4990.6     .07       0
  5097.4    .035       0  5278.1     .07       0  5739.9    .035       0
  5911.9     .07       0
Bank Sta=4973.1,4990.6
XS Rating Curve= 0 ,0
Exp/Cntr=0.3,0.1

Type RM Length L Ch R = 1 ,6447    ,192,192,192
BEGIN DESCRIPTION:
Mapping XS 70107cef
END DESCRIPTION:
XS GIS Cut Line= 3
      1457666.27      6828462.27      1456947.54      6828312.97
      1455454.53       6828035.2
#Sta/Elev= 30
  4294.1  2156.1  4350.4 2156.15  4404.3 2156.29  4662.6 2155.89  4736.4 2153.27
  4781.4 2149.88  4881.6 2145.41  4938.8 2140.81  5000.1 2138.58  5020.6 2137.13
  5023.3 2134.72  5023.8 2134.22  5040.8 2134.72  5071.4 2137.65  5079.6 2136.02
  5084.7 2139.03  5091.8 2137.39    5102 2137.84  5112.1  2140.1  5122.3 2140.73
  5137.5 2140.23  5631.2 2144.06  5703.5 2144.55  5773.3 2144.96  5824.1 2146.48
  6012.2 2146.85  6098.8 2148.43  6363.2 2149.97  6403.9 2151.26  6546.8 2151.77
#Mann= 8 ,-1 , 0
  4294.1    .035       0  4350.4     .07       0  4404.3    .035       0
  4662.6     .07       0  5023.3     .07       0  5040.8     .07       0
  5631.2    .035       0  5703.5     .07       0
Bank Sta=5023.3,5040.8
XS Rating Curve= 0 ,0
Exp/Cntr=0.3,0.1

Type RM Length L Ch R = 1 ,6255    ,811,811,811
BEGIN DESCRIPTION:
Mapping XS 85909b21
END DESCRIPTION:
XS GIS Cut Line= 3
      1457558.63      6828285.19      1456951.01      6828153.25
      1455430.21      6827868.53
#Sta/Elev= 30
  4382.3 2156.16  4549.7 2155.74  4600.9 2154.84  4662.3 2152.03  4676.5 2152.19
  4769.7 2147.69  4887.4 2145.97  4906.9 2143.33    4912 2144.03  4938.6 2140.76
    4956 2135.85  4961.1 2136.68  4970.7 2133.56  4971.2 2133.06  4988.3 2133.56
  4989.8 2136.15  4999.5 2137.02  5091.6 2139.03  5336.2 2138.93    5494 2141.05
  5691.8  2142.3  5709.5 2143.11  5714.6 2142.54  5722.4 2143.32  5885.1  2145.5
  5905.5 2144.97  6040.4 2145.72  6190.3 2147.82  6255.9 2147.86  6551.3 2151.83
#Mann= 3 ,-1 , 0
  4382.3     .07       0  4970.7     .07       0  4988.3     .07       0
Bank Sta=4970.7,4988.3
XS Rating Curve= 0 ,0
Exp/Cntr=0.3,0.1

Type RM Length L Ch R = 1 ,5444    ,473,473,473
BEGIN DESCRIPTION:
WEAVER SPRINGS CREEK TRIB 1 10.0
END DESCRIPTION:
XS GIS Cut Line= 3
      1457454.99        6827788.        1456455.        6827588.
      1455555.05      6827787.99
#Sta/Elev= 30
  3980.7 2153.84  4052.1  2154.2  4143.9 2151.74  4225.4 2145.69    4256 2144.96
  4276.4 2143.67  4419.2 2142.46  4684.4 2142.34  4857.7 2135.94  4990.3 2132.24
  4997.9 2130.01  5000.5 2130.01  5001.9 2128.09  5002.4 2127.59    5019 2127.59
  5019.5 2128.09  5019.7 2130.18  5024.8 2132.15  5073.5 2135.41  5204.1 2134.98
  5225.9 2136.09  5246.3 2138.03  5369.3 2138.32  5430.7 2140.94  5522.9 2143.64
  5543.4  2145.3  5635.6  2147.2  5799.5 2148.71    5861 2150.51  5922.4  2151.1
#Mann= 3 ,-1 , 0
  3980.7     .07       0  5001.9     .07       0  5019.5     .07       0
Bank Sta=5001.9,5019.5
XS Rating Curve= 0 ,0
Exp/Cntr=0.3,0.1

Type RM Length L Ch R = 1 ,4971    ,746,746,746
BEGIN DESCRIPTION:
WEAVER SPRINGS CREEK TRIB 1 9.0
END DESCRIPTION:
XS GIS Cut Line= 3
      1457354.99      6827687.99        1456355.        6827188.
      1455730.04      6826913.02
#Sta/Elev= 30
  3877.4 2152.82  3944.5  2149.7  3975.2 2146.83  4056.3 2143.59  4070.2 2144.12
  4078.6  2143.1  4190.4 2141.39  4450.4 2140.15  4637.7  2137.4  4771.8 2133.67
  4869.6 2132.22  4897.6  2132.4    4906 2131.66  4973.1 2130.27  4981.4 2129.16
  4983.8 2125.57  4984.3 2125.07    5001 2125.07  5001.5 2125.57  5004.4 2128.32
  5009.8 2129.86  5033.2  2130.8  5056.5  2133.4  5079.8 2134.44    5202 2135.14
  5312.3 2134.77  5358.4 2135.18  5428.5 2136.91  5457.3 2136.68  5678.2  2139.2
#Mann= 3 ,-1 , 0
  3877.4     .07       0  4983.8     .07       0  5001.5     .07       0
Bank Sta=4983.8,5001.5
XS Rating Curve= 0 ,0
Exp/Cntr=0.3,0.1