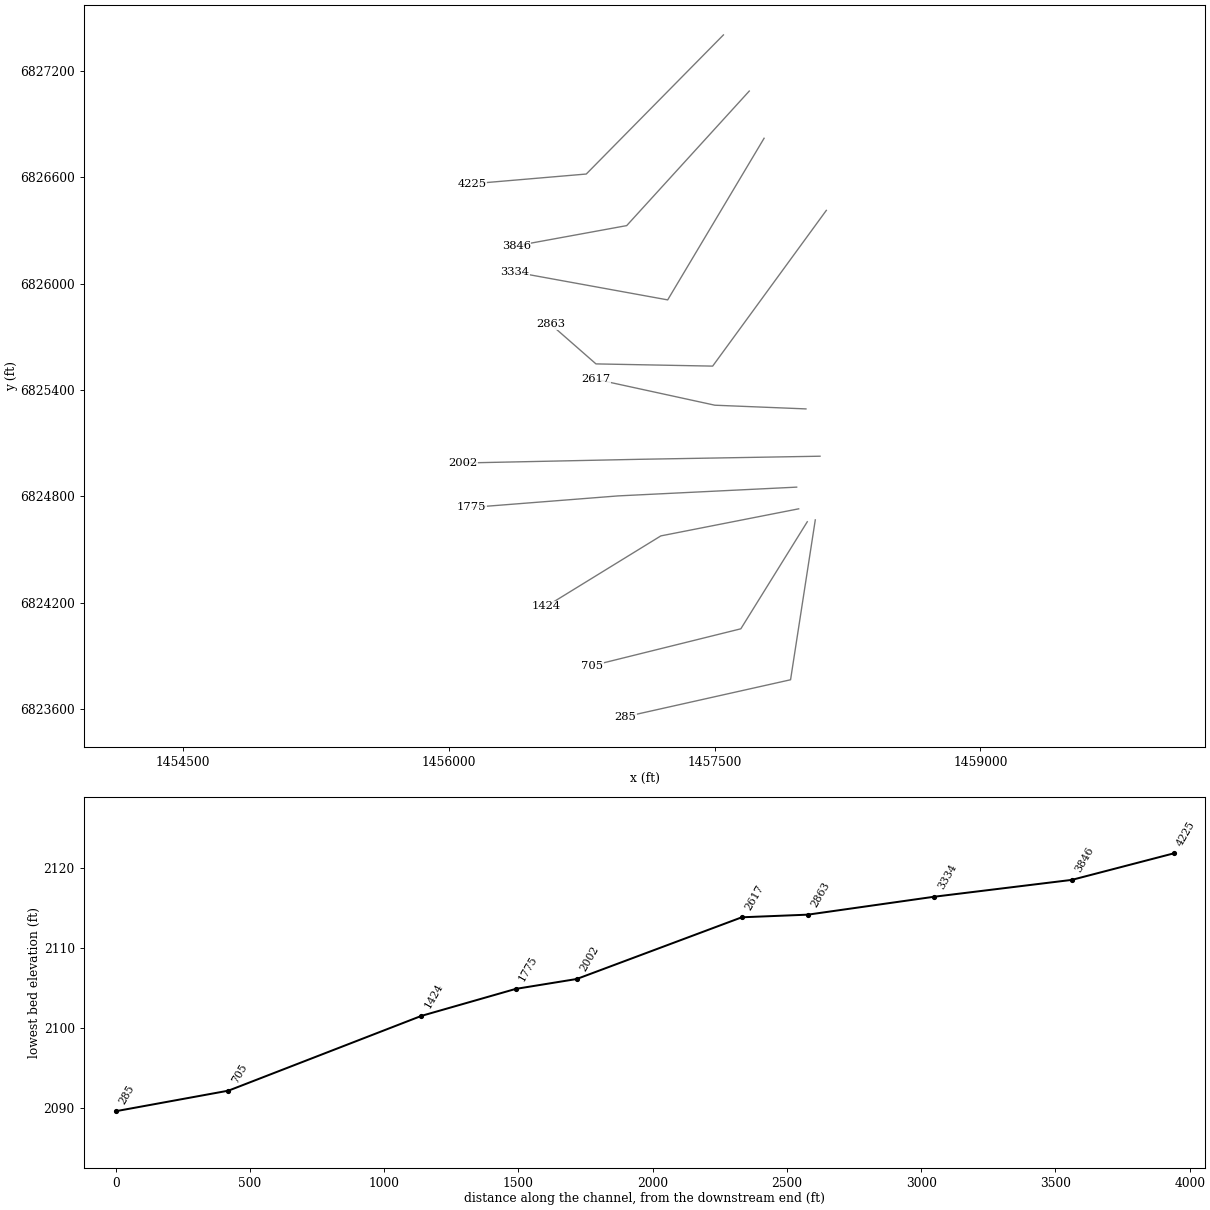
HEC-RAS study WEAVER SPRINGS CREEK TRIB 1.prj: WEAVER SPRINGS CREEK TRIB 1 Base Level Engineering

--- WEAVER SPRINGS CREEK TRIB 1.g01 (geometry) --- (continued)

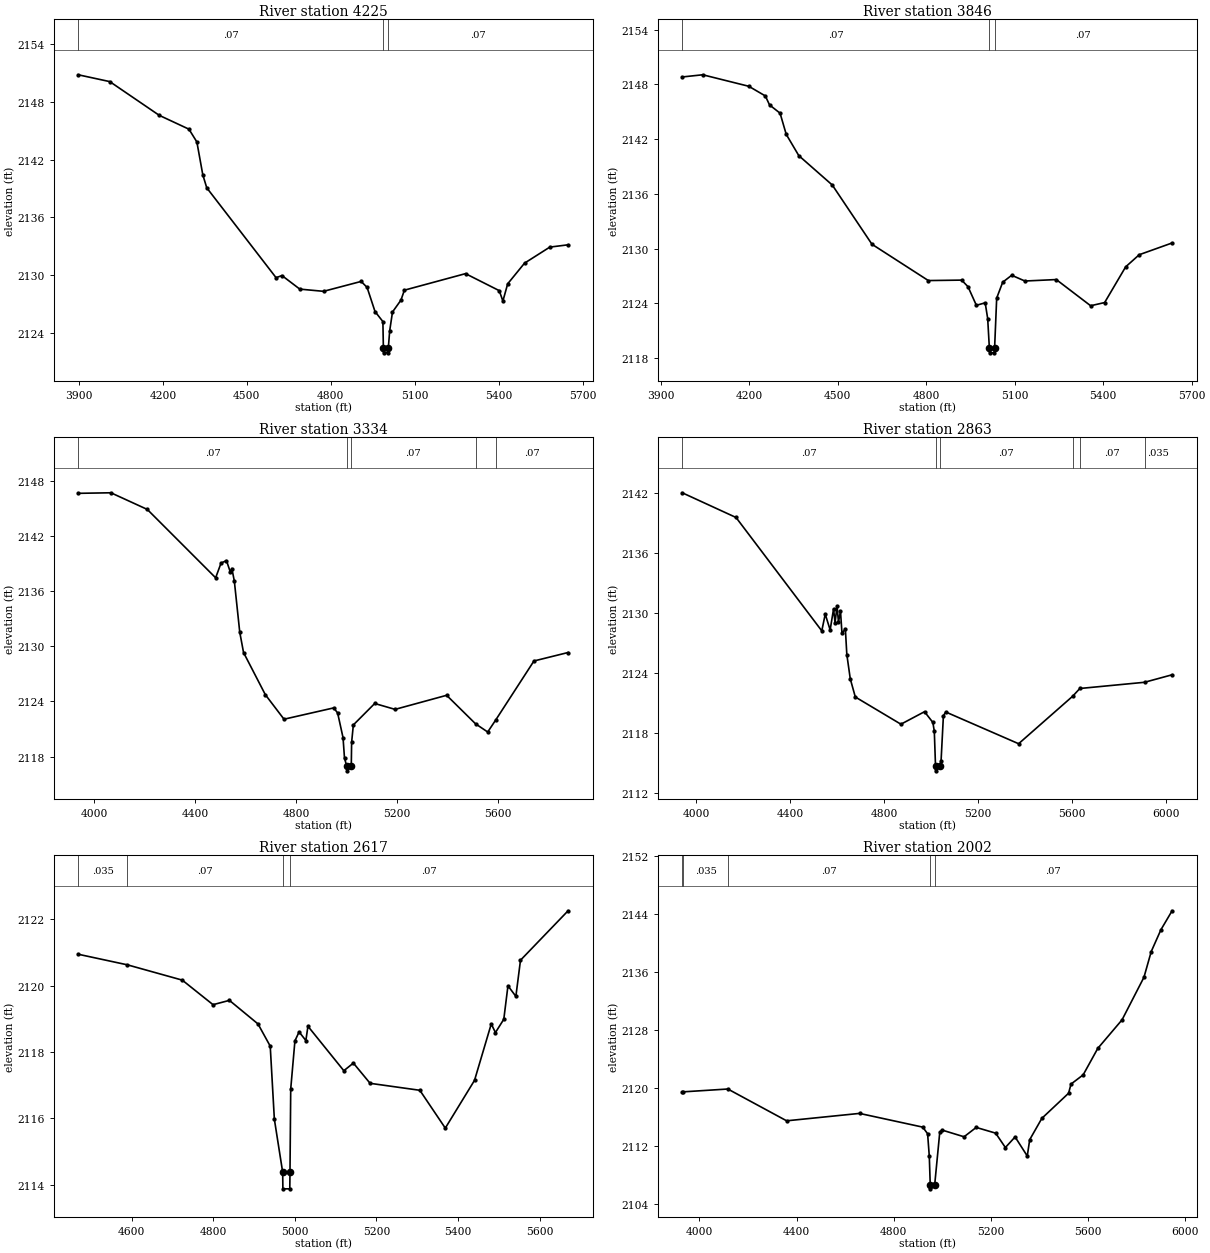
Type RM Length L Ch R = 1 ,4225    ,379,379,379
BEGIN DESCRIPTION:
WEAVER SPRINGS CREEK TRIB 1 8.0
END DESCRIPTION:
XS GIS Cut Line= 3
      1457549.27      6827403.16      1456775.31      6826618.13
      1456129.96        6826563.
#Sta/Elev= 30
  3897.6 2150.82  4010.3 2150.11  4187.1  2146.6  4293.2 2145.16  4321.5 2143.83
  4342.7 2140.41  4356.8 2139.06  4604.4 2129.71  4625.5 2129.93  4689.2 2128.52
  4774.1 2128.29  4908.4 2129.32  4929.6  2128.7  4957.9 2126.19  4986.1 2125.14
  4987.8 2122.39  4988.3 2121.89    5005 2121.89  5005.5 2122.39  5010.3 2124.17
  5020.4 2126.14  5050.5 2127.37  5062.9 2128.41  5281.3 2130.13  5401.8 2128.36
  5414.8 2127.28  5431.9 2129.07  5492.1 2131.22  5582.4 2132.89  5647.7 2133.13
#Mann= 3 ,-1 , 0
  3897.6     .07       0  4987.8     .07       0  5005.5     .07       0
Bank Sta=4987.8,5005.5
XS Rating Curve= 0 ,0
Exp/Cntr=0.3,0.1

Type RM Length L Ch R = 1 ,3846    ,512,512,512
BEGIN DESCRIPTION:
WEAVER SPRINGS CREEK TRIB 1 7.0
END DESCRIPTION:
XS GIS Cut Line= 3
      1457695.08       6827086.3       1457003.4      6826327.02
      1456380.04      6826213.01
#Sta/Elev= 30
  3972.9  2148.8  4042.4 2149.04  4198.5 2147.78  4254.7 2146.72  4268.8 2145.74
  4304.6 2144.83  4325.5 2142.51  4368.1 2140.18  4481.6 2136.96  4616.1 2130.47
  4807.3 2126.49  4920.1 2126.54  4941.7 2125.82  4970.1 2123.78    5000 2124.05
  5008.5 2122.32  5014.2 2119.07  5014.7 2118.57  5031.4 2118.57  5031.9 2119.07
    5039 2124.57  5059.4 2126.31  5089.9 2127.07  5134.6 2126.44    5241  2126.6
  5357.5 2123.73    5405 2124.08  5476.2 2127.99  5522.2 2129.32  5633.7 2130.61
#Mann= 3 ,-1 , 0
  3972.9     .07       0  5014.2     .07       0  5031.9     .07       0
Bank Sta=5014.2,5031.9
XS Rating Curve= 0 ,0
Exp/Cntr=0.3,0.1

Type RM Length L Ch R = 1 ,3334    ,471,471,471
BEGIN DESCRIPTION:
Mapping XS bf107a32
END DESCRIPTION:
XS GIS Cut Line= 3
      1457778.74      6826819.97      1457234.73      6825907.89
      1456372.08      6826064.79
#Sta/Elev= 30
    3938 2146.62  4067.4 2146.68  4211.4 2144.87  4481.9 2137.44  4503.3 2139.04
  4524.7 2139.31  4540.3 2138.04  4546.1 2138.45  4555.9 2137.08  4577.3 2131.53
  4592.3 2129.32  4678.5 2124.74  4752.5 2122.07  4949.1  2123.3  4964.7 2122.75
  4986.1 2120.07  4991.9 2117.83    5001 2116.96  5001.5 2116.46  5018.7 2116.96
  5020.1 2119.56  5026.9 2121.45  5111.5 2123.78    5192 2123.14  5396.1 2124.67
  5510.6 2121.57  5558.7 2120.68  5591.2 2122.02  5741.7  2128.4  5876.8 2129.32
#Mann= 5 ,-1 , 0
    3938     .07       0    5001     .07       0  5018.7     .07       0
  5510.6    .035       0  5591.2     .07       0
Bank Sta=5001,5018.7
XS Rating Curve= 0 ,0
Exp/Cntr=0.3,0.1

Type RM Length L Ch R = 1 ,2863    ,246,246,246
BEGIN DESCRIPTION:
WEAVER SPRINGS CREEK TRIB 1 5.0
END DESCRIPTION:
XS GIS Cut Line= 4
      1458129.98      6826412.98      1457488.55      6825534.17
        1456830.      6825546.67      1456575.52      6825769.33
#Sta/Elev= 30
  3940.5    2142  4169.5 2139.53  4534.4  2128.2  4549.1 2129.87    4570 2128.29
  4584.6 2130.41  4590.8 2128.99  4599.3 2130.67  4605.5 2129.07    4614 2130.18
  4620.2    2128  4634.8 2128.36    4641 2125.83  4655.7  2123.4  4677.1 2121.59
  4871.2 2118.87  4971.6 2120.12  5007.1 2119.05  5013.3 2118.17  5018.4 2114.71
  5018.9 2114.21  5036.2 2114.71    5042 2115.17    5052 2119.72  5062.1 2120.09
  5372.1 2116.92  5602.3 2121.67  5632.7 2122.44    5908 2123.06  6025.3 2123.81
#Mann= 6 ,-1 , 0
  3940.5     .07       0  5018.4     .07       0  5036.2     .07       0
  5602.3    .035       0  5632.7     .07       0    5908    .035       0
Bank Sta=5018.4,5036.2
XS Rating Curve= 0 ,0
Exp/Cntr=0.3,0.1

Type RM Length L Ch R = 1 ,2617    ,615,615,615
BEGIN DESCRIPTION:
Mapping XS 95d72080
END DESCRIPTION:
XS GIS Cut Line= 3
      1458015.06      6825292.69      1457501.19      6825313.52
      1456831.06      6825459.35
#Sta/Elev= 30
  4469.4 2120.95  4590.1 2120.63  4724.3 2120.17  4799.7 2119.43  4839.8 2119.56
  4909.8 2118.85  4939.8 2118.18  4949.9 2115.98  4970.3 2114.38  4970.8 2113.88
  4987.7 2113.88  4988.2 2114.38    4990 2116.89  5000.3 2118.34  5010.5 2118.61
  5027.1 2118.35  5032.2 2118.78  5120.1 2117.44  5143.5 2117.67  5184.5 2117.06
  5306.3 2116.85  5368.7 2115.71  5440.3 2117.15  5481.3 2118.85  5491.5 2118.59
    5512 2118.99  5522.2    2120  5541.6 2119.68  5552.9 2120.77  5669.5 2122.26
#Mann= 4 ,-1 , 0
  4469.4    .035       0  4590.1     .07       0  4970.3     .07       0
  4988.2     .07       0
Bank Sta=4970.3,4988.2
XS Rating Curve= 0 ,0
Exp/Cntr=0.3,0.1

Type RM Length L Ch R = 1 ,2002    ,227,227,227
BEGIN DESCRIPTION:
WEAVER SPRINGS CREEK TRIB 1 3.0
END DESCRIPTION:
XS GIS Cut Line= 3
      1458094.42      6825025.71      1457075.84      6825008.26
      1456079.19      6824987.44
#Sta/Elev= 30
  3929.6 2119.42  3933.6  2119.5  4117.2 2119.89  4359.1 2115.51  4659.1 2116.53
  4919.2 2114.64  4939.2 2113.73  4946.2 2110.61  4950.1 2106.64  4950.6 2106.14
  4968.2 2106.64  4989.2 2113.93  4999.2 2114.23  5089.2 2113.31  5139.2  2114.6
  5219.2 2113.81  5259.2 2111.83  5299.2 2113.29  5349.3 2110.66  5359.3 2112.91
  5409.3 2115.85  5519.3 2119.31  5529.3 2120.57  5579.3 2121.84  5639.3 2125.48
  5739.3 2129.42  5829.4 2135.28  5859.4 2138.83  5899.4 2141.84  5945.2 2144.44
#Mann= 5 ,-1 , 0
  3929.6     .07       0  3933.6    .035       0  4117.2     .07       0
  4950.1     .07       0  4968.2     .07       0
Bank Sta=4950.1,4968.2
XS Rating Curve= 0 ,0
Exp/Cntr=0.3,0.1

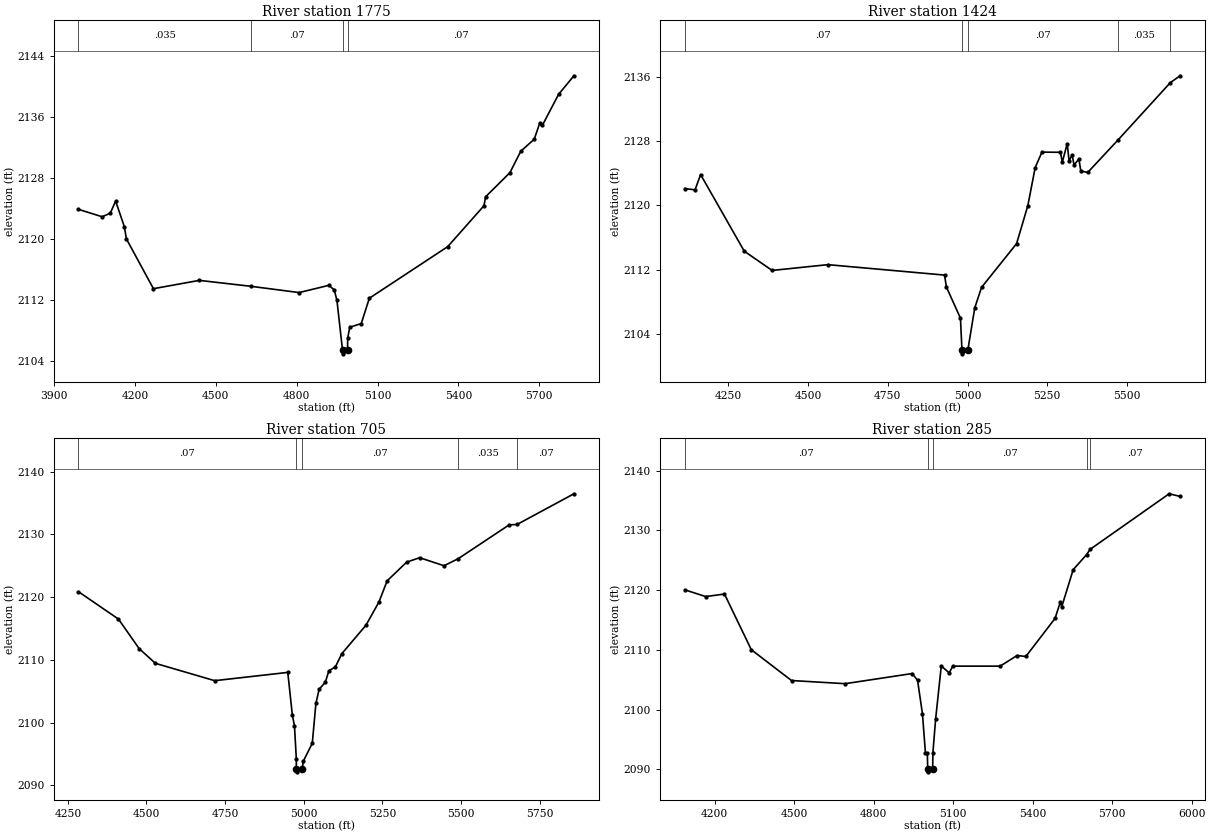
Type RM Length L Ch R = 1 ,1775    ,351,351,351
BEGIN DESCRIPTION:
Mapping XS f1110f41
END DESCRIPTION:
XS GIS Cut Line= 3
      1457962.62      6824851.23      1456954.83      6824801.75
      1456128.39      6824736.78
#Sta/Elev= 30
  3990.4 2123.86  4078.1 2122.89  4108.2 2123.35  4128.2 2124.95  4160.7 2121.56
  4168.2 2119.98  4268.4 2113.45  4438.6 2114.54  4630.7 2113.76    4809 2112.94
  4919.1 2113.89  4939.2 2113.29  4949.2 2111.92  4969.9  2105.4  4970.4  2104.9
  4988.5  2105.4  4989.2 2106.99  4996.8 2108.39  5039.4 2108.87  5069.5  2112.2
  5360.3 2118.97  5494.8 2124.34  5500.8 2125.51  5591.1 2128.68  5631.2 2131.48
  5681.3 2133.07  5701.4 2135.16  5711.4 2134.89  5771.6 2138.95  5828.4 2141.39
#Mann= 4 ,-1 , 0
  3990.4    .035       0  4630.7     .07       0  4969.9     .07       0
  4988.5     .07       0
Bank Sta=4969.9,4988.5
XS Rating Curve= 0 ,0
Exp/Cntr=0.3,0.1

Type RM Length L Ch R = 1 ,1424    ,719,719,719
BEGIN DESCRIPTION:
Mapping XS 1cb97bcf
END DESCRIPTION:
XS GIS Cut Line= 3
      1457973.95      6824728.84      1457196.15      6824576.05
       1456548.4      6824177.71
#Sta/Elev= 30
  4113.4 2122.11  4145.8 2121.95  4163.3 2123.85  4300.1 2114.31  4387.5 2111.91
  4562.3 2112.63    4928 2111.33  4933.9 2109.84  4977.9 2105.96  4982.6 2102.02
  4983.1 2101.52  5001.2 2102.02  5022.7 2107.24    5044  2109.8  5153.9 2115.25
  5189.2 2119.99  5212.1 2124.71  5233.3 2126.65  5291.3 2126.63  5297.2 2125.41
  5312.6  2127.7  5318.5 2125.56    5328 2126.31  5333.9 2125.06  5349.3 2125.78
  5355.2  2124.3    5377 2124.12  5472.7  2128.2    5636 2135.31  5666.5 2136.16
#Mann= 5 ,-1 , 0
  4113.4     .07       0  4982.6     .07       0  5001.2     .07       0
  5472.7    .035       0    5636     .07       0
Bank Sta=4982.6,5001.2
XS Rating Curve= 0 ,0
Exp/Cntr=0.3,0.1

Type RM Length L Ch R = 1 ,705     ,420,420,420
BEGIN DESCRIPTION:
Mapping XS ac4e74bd
END DESCRIPTION:
XS GIS Cut Line= 3
      1458022.52      6824655.88      1457647.54      6824051.75
      1456808.68      6823843.77
#Sta/Elev= 30
  4283.9 2120.85  4410.9 2116.49  4476.9 2111.77  4528.6 2109.43  4716.9 2106.67
  4949.4 2107.99    4964 2101.13  4970.6 2099.52  4976.5 2094.26  4976.6 2092.64
  4977.1 2092.14  4995.3 2092.64  4998.8 2093.84  5027.3 2096.69  5038.8 2103.04
  5049.1 2105.31  5068.7 2106.41    5080 2108.24  5100.6 2108.86  5121.2 2110.97
    5198 2115.51  5239.4 2119.22  5265.4 2122.59  5327.3 2125.56  5368.7 2126.27
  5446.3 2124.99  5491.8 2126.13  5653.2  2131.5  5678.6 2131.57  5859.2 2136.46
#Mann= 5 ,-1 , 0
  4283.9     .07       0  4976.6     .07       0  4995.3     .07       0
  5491.8    .035       0  5678.6     .07       0
Bank Sta=4976.6,4995.3
XS Rating Curve= 0 ,0
Exp/Cntr=0.3,0.1

Type RM Length L Ch R = 1 ,285     ,0,0,0
BEGIN DESCRIPTION:
Mapping XS fb7c7dc8
END DESCRIPTION:
XS GIS Cut Line= 3
      1458067.68      6824666.34      1457928.13      6823764.17
      1456994.73      6823555.21
#Sta/Elev= 30
  4087.1 2120.06  4166.4 2118.93  4237.2 2119.35  4338.5 2110.02  4490.2 2104.86
  4692.6 2104.33  4945.5 2106.03  4965.8  2104.9  4984.3 2099.28  4995.5 2092.72
  5002.7 2092.72  5004.1 2090.06  5004.6 2089.56  5022.8 2090.06  5023.7 2092.77
  5033.9 2098.36  5055.3  2107.3  5085.2 2106.14  5098.7 2107.27  5277.4 2107.27
  5341.4 2109.05  5374.4 2108.89  5484.8 2115.28  5504.5 2118.03  5509.7  2117.2
    5553 2123.43  5603.7 2125.96    5617 2126.84  5915.2 2136.15  5956.5 2135.71
#Mann= 5 ,-1 , 0
  4087.1     .07       0  5004.1     .07       0  5022.8     .07       0
  5603.7    .035       0    5617     .07       0
Bank Sta=5004.1,5022.8
XS Rating Curve= 0 ,0
Exp/Cntr=0.3,0.1

Chan Stop Cuts=-1
Use User Specified Reach Order=0
Composite Channel Slope=5