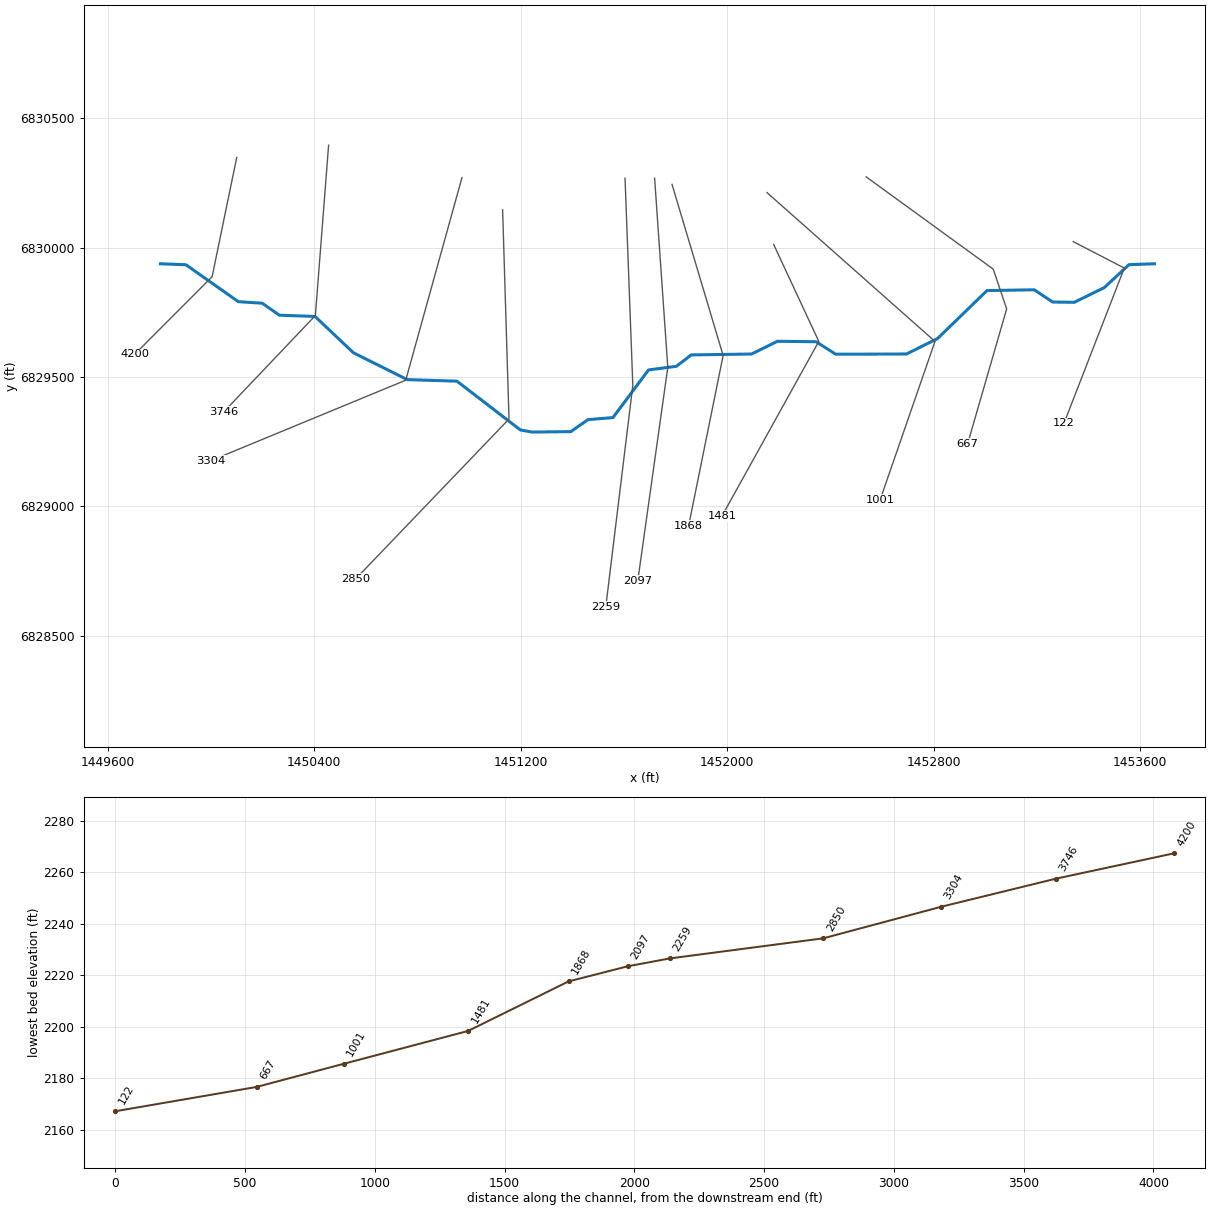
--- WEAVER SPRINGS CREEK TRIB 1_1.prj (project) ---

Proj Title=WEAVER SPRINGS CREEK TRIB 1_1 Base Level Engineering
Current Plan=p01
Default Exp/Contr=0.3,0.1
English Units
Geom File=g01
Flow File=f01
Plan File=p01
Y Axis Title=Elevation
X Axis Title(PF)=Main Channel Distance
X Axis Title(XS)=Station
BEGIN DESCRIPTION:
WEAVER SPRINGS CREEK TRIB 1_1
END DESCRIPTION:
DSS Export Rating Curves= 0
DSS Export Rating Curve Sorted= 0
DSS Export Volume Flow Curves= 0
DXF OffsetX= 0
DXF OffsetY= 0
DXF ScaleX= 1
DXF ScaleY= 10

--- WEAVER SPRINGS CREEK TRIB 1_1.p01 (plan) ---

Plan Title=Multiple Run
Short Identifier=Multiple
Geom File=g01
Flow File=f01
Subcritical Flow
K Sum by GR= 0
Std Step Tol= 0.01
Critical Tol= 0.01
Num of Std Step Trials= 20
Max Error Tol= 0.3
Flow Tol Ratio= 0.001
Split Flow NTrial= 30
Split Flow Tol= 0.02
Split Flow Ratio= 0.02
Log Output Level= 0
Friction Slope Method= 1
Unsteady Friction Slope Method= 2
Unsteady Bridges Friction Slope Method= 1
Parabolic Critical Depth
Global Vel Dist=  1 , 1 , 1
Global Log Level= 0
CheckData=True
Encroach Param= -1, 0, 0, 0
BEGIN DESCRIPTION:
Multiple Run
END DESCRIPTION:

--- WEAVER SPRINGS CREEK TRIB 1_1.f01 (steady flow) ---

Flow Title=Multiple
Program Version=4.10
Number of Profiles= 7
Profile Names=10-year,25-year,50-year,1pct_min,100-year,1pct_plu,500-year
River Rch & RM=WEAVER SPRINGS C,Reach-1         ,4200
     244     347     434     271     541    1080     850
River Rch & RM=WEAVER SPRINGS C,Reach-1         ,3304
     316     455     576     363     724    1445    1158
Boundary for River Rch & Prof#=WEAVER SPRINGS C,Reach-1         , 1
Up Type= 0
Dn Type= 3
Dn Slope=0.017
Boundary for River Rch & Prof#=WEAVER SPRINGS C,Reach-1         , 2
Up Type= 0
Dn Type= 3
Dn Slope=0.017
Boundary for River Rch & Prof#=WEAVER SPRINGS C,Reach-1         , 3
Up Type= 0
Dn Type= 3
Dn Slope=0.017
Boundary for River Rch & Prof#=WEAVER SPRINGS C,Reach-1         , 4
Up Type= 0
Dn Type= 3
Dn Slope=0.017
Boundary for River Rch & Prof#=WEAVER SPRINGS C,Reach-1         , 5
Up Type= 0
Dn Type= 3
Dn Slope=0.017
Boundary for River Rch & Prof#=WEAVER SPRINGS C,Reach-1         , 6
Up Type= 0
Dn Type= 3
Dn Slope=0.017
Boundary for River Rch & Prof#=WEAVER SPRINGS C,Reach-1         , 7
Up Type= 0
Dn Type= 3
Dn Slope=0.017
DSS Import GetInterval= 0
DSS Import GetPeak= 0
DSS Import FillOption= 0

--- WEAVER SPRINGS CREEK TRIB 1_1.g01 (geometry) ---

Geom Title=Existing Conditions

River Reach=WEAVER SPRINGS C,Reach-1
Reach XY= 30
      1449805.00      6829938.00      1449903.50      6829934.37
      1450106.50      6829791.62      1450199.02      6829785.64
      1450265.51      6829739.23      1450403.53      6829734.46
      1450552.70      6829593.83      1450760.93      6829490.24
      1450953.45      6829484.25      1451198.81      6829295.81
      1451244.79      6829287.49      1451394.50      6829289.22
      1451460.98      6829335.64      1451557.67      6829343.42
      1451695.19      6829527.49      1451803.40      6829541.86
      1451860.94      6829585.74      1452094.50      6829589.22
      1452194.82      6829638.46      1452344.49      6829636.78
      1452420.22      6829588.52      1452694.50      6829589.20
      1452814.68      6829648.76      1453006.46      6829834.47
      1453189.78      6829837.48      1453260.98      6829790.17
      1453344.46      6829789.08      1453461.05      6829846.16
      1453556.41      6829934.61      1453655.00      6829938.00

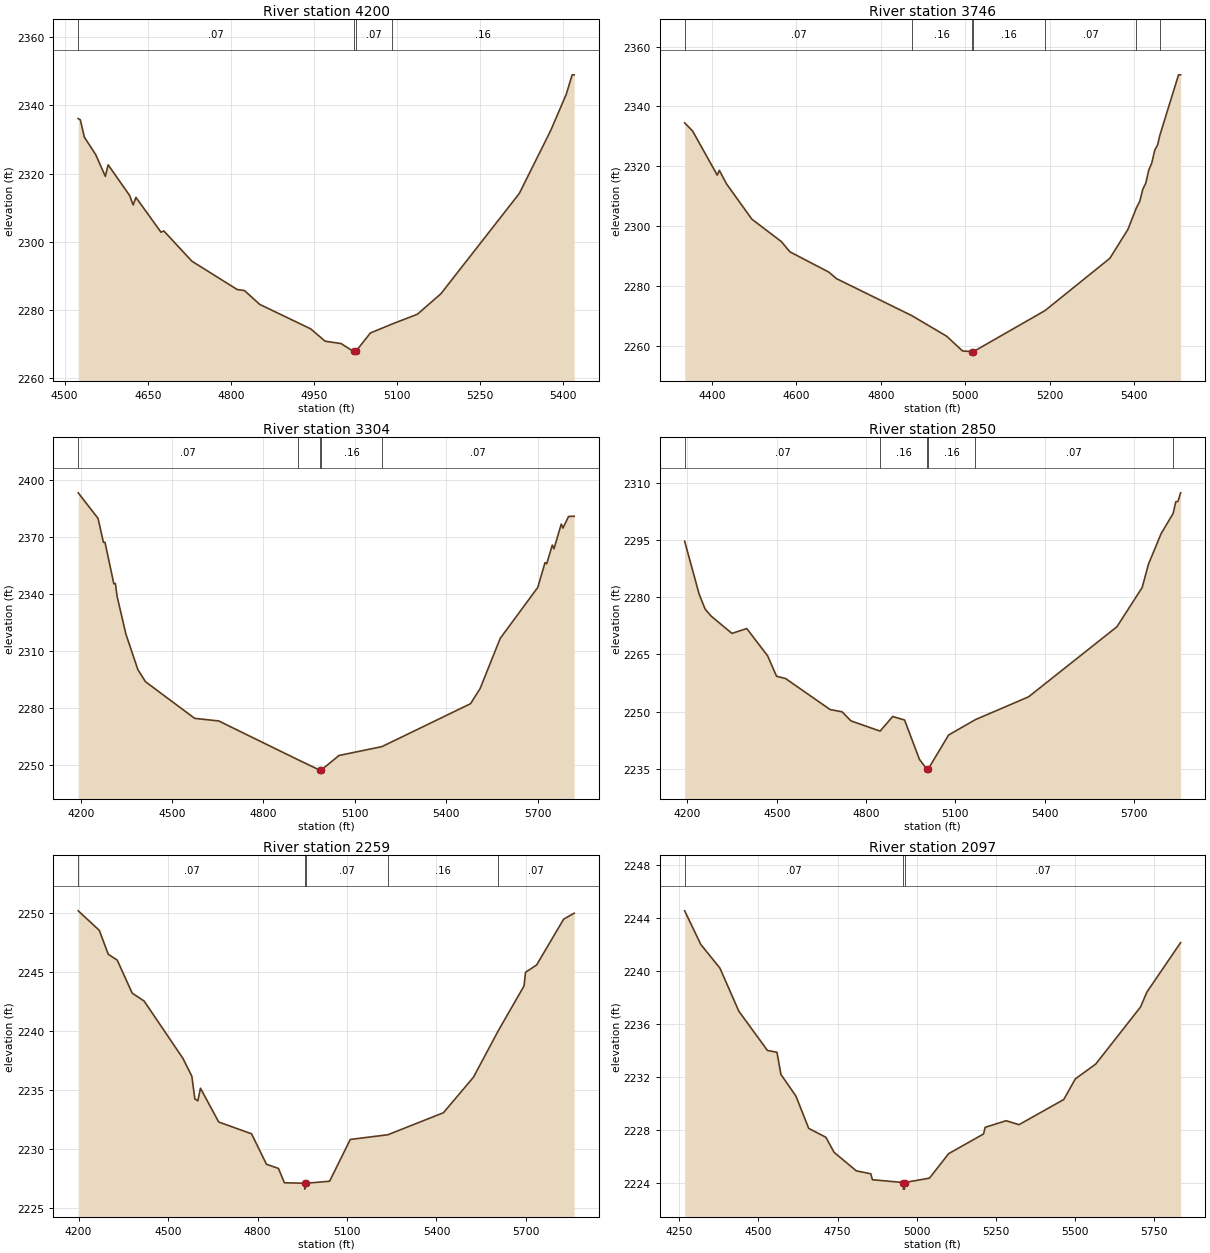
Type RM Length L Ch R = 1,4200,454,454,454
BEGIN DESCRIPTION:
WEAVER SPRINGS CREEK TRIB 1_1 9.0
END DESCRIPTION:
XS GIS Cut Line= 3
      1450100.33      6830348.86      1450005.00      6829888.00
      1449704.99      6829587.99
#Sta/Elev= 30
  4524.6 2336.12  4528.4 2335.77  4535.7 2330.69  4556.1 2325.59  4573.5 2319.20
  4578.6 2322.58  4617.4 2313.59  4623.7 2310.82  4628.8 2313.03  4673.9 2302.84
  4679.1 2303.20  4729.7 2294.34  4811.4 2286.04  4824.6 2285.72  4852.3 2281.66
  4944.2 2274.49  4970.1 2270.89  4998.8 2270.20  5021.5 2267.89  5021.8 2267.39
  5025.5 2267.89  5051.8 2273.29  5091.3 2275.94  5136.6 2278.78  5179.1 2284.80
  5320.5 2314.18  5377.1 2332.60  5405.3 2343.27  5415.9 2348.95  5419.5 2348.95
#Mann=4,-1,0
  4524.6    0.07       0  5021.5    0.07       0  5025.5    0.07       0
  5091.3    0.16       0
Bank Sta=5021.5,5025.5
Exp/Cntr=0.3,0.1

Type RM Length L Ch R = 1,3746,442,442,442
BEGIN DESCRIPTION:
WEAVER SPRINGS CREEK TRIB 1_1 8.0
END DESCRIPTION:
XS GIS Cut Line= 3
      1450456.24      6830396.59      1450405.00      6829738.00
      1450050.44      6829365.83
#Sta/Elev= 30
  4335.2 2334.52  4353.8 2331.84  4412.3 2317.06  4417.3 2318.65  4434.1 2314.17
  4494.3 2302.34  4564.5 2294.80  4584.5 2291.41  4676.6 2284.64  4694.9 2282.44
  4873.5 2270.07  4955.7 2263.21  4993.3 2258.29  5015.0 2258.06  5015.3 2257.56
  5019.0 2258.06  5188.8 2271.79  5342.2 2289.25  5384.7 2298.83  5405.3 2306.18
  5413.0 2308.27  5420.2 2312.33  5427.2 2314.33  5434.4 2318.75  5441.3 2320.99
  5448.6 2325.39  5455.5 2327.23  5460.3 2330.22  5504.9 2350.57  5509.8 2350.57
#Mann=7,-1,0
  4335.2    0.07       0  4873.5    0.16       0  5015.0    0.07       0
  5019.0    0.16       0  5188.8    0.07       0  5405.3    0.16       0
  5460.3    0.07       0
Bank Sta=5015,5019
Exp/Cntr=0.3,0.1

Type RM Length L Ch R = 1,3304,454,454,454
BEGIN DESCRIPTION:
WEAVER SPRINGS CREEK TRIB 1_1 7.0
END DESCRIPTION:
XS GIS Cut Line= 3
      1450972.75      6830270.81      1450755.00      6829488.00
      1450000.51      6829177.01
#Sta/Elev= 30
  4191.6 2393.30  4256.8 2379.83  4274.4 2367.20  4279.6 2367.24  4308.6 2345.33
  4313.8 2345.54  4319.1 2338.92  4348.1 2318.93  4387.5 2300.15  4412.5 2293.77
  4574.2 2274.45  4653.0 2273.09  4913.7 2252.63  4985.0 2247.15  4985.3 2246.65
  4989.0 2247.15  5048.1 2254.90  5189.1 2259.57  5480.0 2282.19  5511.5 2290.21
  5577.4 2316.61  5700.6 2343.43  5724.6 2356.54  5730.0 2355.89  5748.5 2365.80
  5753.9 2363.82  5777.9 2376.84  5783.3 2374.72  5801.8 2380.84  5820.2 2380.97
#Mann=5,-1,0
  4191.6    0.07       0  4913.7    0.16       0  4985.0    0.07       0
  4989.0    0.16       0  5189.1    0.07       0
Bank Sta=4985,4989
Exp/Cntr=0.3,0.1

Type RM Length L Ch R = 1,2850,591,591,591
BEGIN DESCRIPTION:
WEAVER SPRINGS CREEK TRIB 1_1 6.0
END DESCRIPTION:
XS GIS Cut Line= 3
      1451130.28      6830146.68      1451155.00      6829338.00
      1450560.82      6828719.53
#Sta/Elev= 30
  4190.7 2294.62  4239.4 2280.76  4259.4 2276.87  4279.4 2275.03  4349.5 2270.49
  4399.5 2271.75  4469.5 2264.60  4499.5 2259.24  4529.5 2258.67  4679.6 2250.52
  4719.6 2249.94  4749.6 2247.55  4847.5 2244.88  4889.7 2248.70  4929.7 2247.79
  4979.7 2237.47  5004.8 2234.89  5005.1 2234.39  5008.8 2234.89  5077.6 2243.85
  5167.8 2247.89  5346.4 2253.86  5643.3 2272.22  5728.2 2282.51  5749.3 2288.60
  5791.8 2296.62  5832.0 2301.88  5841.4 2304.99  5848.4 2305.06  5857.4 2307.32
#Mann=6,-1,0
  4190.7    0.07       0  4847.5    0.16       0  5004.8    0.07       0
  5008.8    0.16       0  5167.8    0.07       0  5832.0    0.16       0
Bank Sta=5004.8,5008.8
Exp/Cntr=0.3,0.1

Type RM Length L Ch R = 1,2259,162,162,162
BEGIN DESCRIPTION:
WEAVER SPRINGS CREEK TRIB 1_1 5.0
END DESCRIPTION:
XS GIS Cut Line= 3
      1451604.42      6830268.77      1451634.58      6829468.24
      1451530.00      6828613.01
#Sta/Elev= 30
  4198.9 2250.22  4269.7 2248.56  4299.7 2246.53  4329.8 2246.03  4379.8 2243.23
  4419.8 2242.56  4549.9 2237.69  4579.9 2236.17  4589.9 2234.24  4600.0 2234.08
  4608.8 2235.15  4670.0 2232.28  4780.1 2231.28  4830.1 2228.69  4870.1 2228.34
  4890.2 2227.12  4958.2 2227.08  4958.5 2226.58  4962.2 2227.08  5041.7 2227.25
  5111.1 2230.80  5237.2 2231.20  5423.4 2233.07  5524.1 2236.09  5607.1 2240.03
  5693.6 2243.84  5698.6 2245.00  5735.7 2245.62  5826.3 2249.51  5861.6 2250.02
#Mann=5,-1,0
  4198.9    0.07       0  4958.2    0.07       0  4962.2    0.07       0
  5237.2    0.16       0  5607.1    0.07       0
Bank Sta=4958.2,4962.2
Exp/Cntr=0.3,0.1

Type RM Length L Ch R = 1,2097,229,229,229
BEGIN DESCRIPTION:
WEAVER SPRINGS CREEK TRIB 1_1 4.0
END DESCRIPTION:
XS GIS Cut Line= 3
      1451719.00      6830268.79      1451770.05      6829537.87
      1451653.80      6828712.51
#Sta/Elev= 30
  4267.3 2244.57  4318.2 2242.03  4378.4 2240.25  4438.5 2236.98  4528.7 2234.02
  4558.8 2233.88  4571.2 2232.21  4618.9 2230.56  4659.0 2228.13  4713.2 2227.46
  4739.2 2226.32  4809.4 2224.92  4855.1 2224.70  4860.1 2224.25  4957.8 2224.04
  4958.0 2223.54  4961.5 2223.54  4961.8 2224.04  5040.3 2224.37  5100.9 2226.22
  5211.2 2227.71  5216.2 2228.21  5282.4 2228.71  5323.0 2228.41  5464.4 2230.31
  5501.0 2231.87  5565.4 2232.99  5706.8 2237.30  5727.0 2238.43  5833.5 2242.17
#Mann=3,-1,0
  4267.3    0.07       0  4957.8    0.07       0  4961.8    0.07       0
Bank Sta=4957.8,4961.8
Exp/Cntr=0.3,0.1

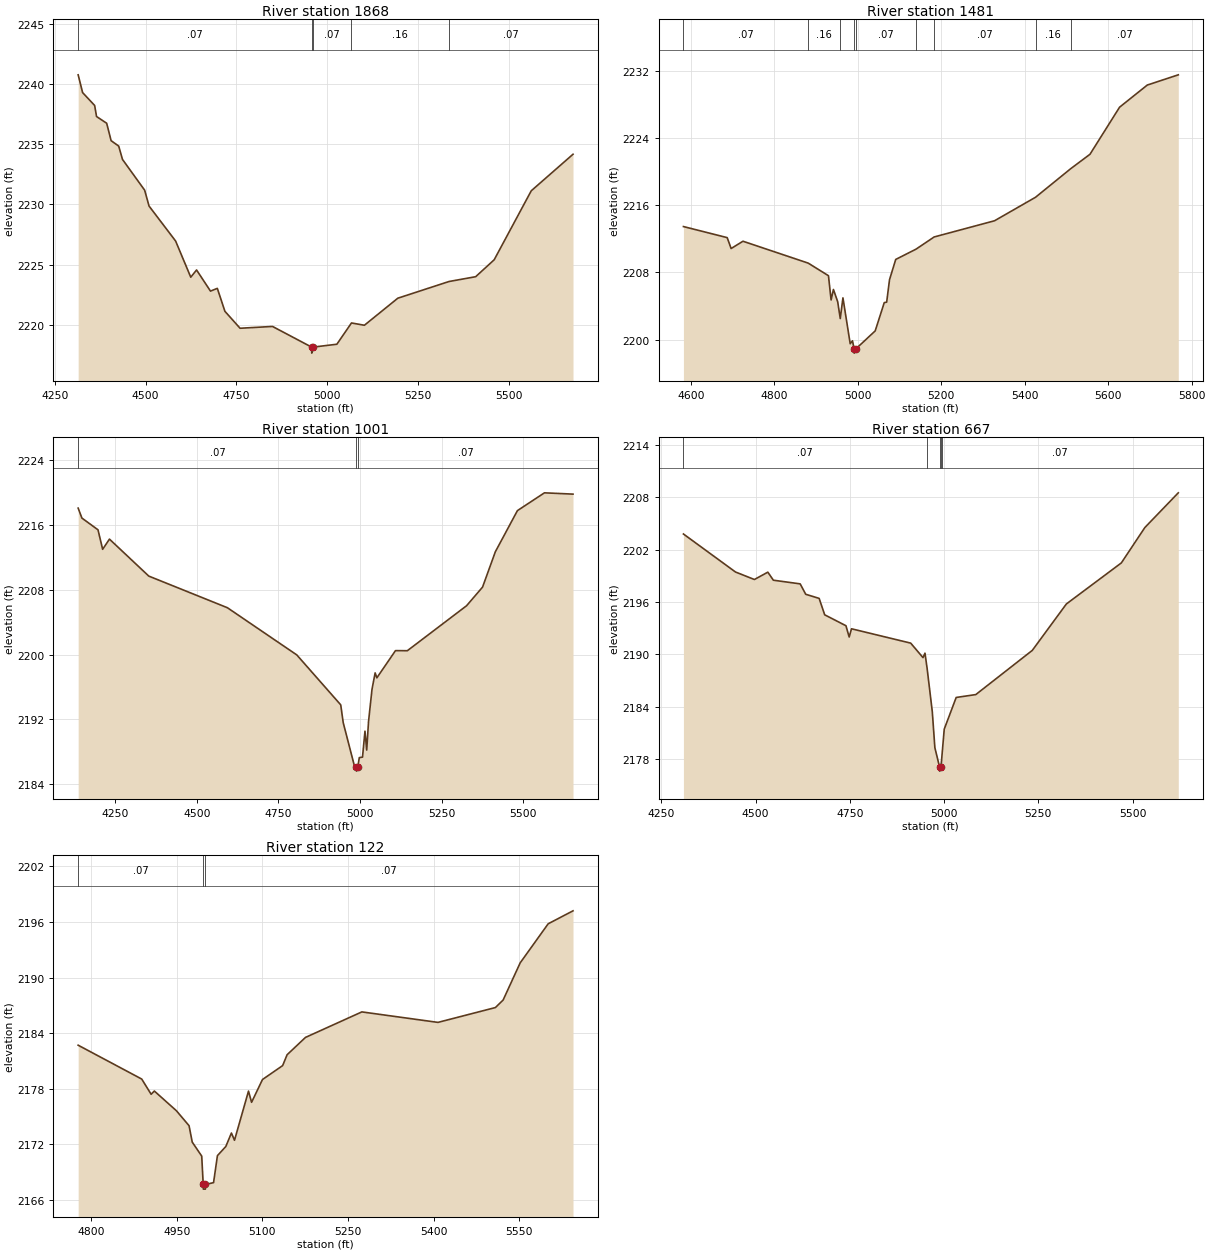
Type RM Length L Ch R = 1,1868,387,387,387
BEGIN DESCRIPTION:
Mapping XS d26f21a9
END DESCRIPTION:
XS GIS Cut Line= 3
      1451786.51      6830244.92      1451984.43      6829583.45
      1451850.74      6828925.44
#Sta/Elev= 30
  4314.3 2240.79  4326.6 2239.31  4359.7 2238.24  4364.9 2237.32  4392.8 2236.76
  4405.0 2235.31  4425.9 2234.86  4436.3 2233.75  4497.3 2231.19  4509.4 2229.87
  4582.5 2226.96  4624.2 2223.95  4640.2 2224.55  4678.5 2222.79  4697.3 2223.02
  4718.2 2221.11  4759.9 2219.70  4849.2 2219.85  4956.9 2218.13  4957.2 2217.63
  4960.9 2218.13  5026.3 2218.37  5066.5 2220.14  5102.1 2219.95  5194.0 2222.20
  5334.9 2223.59  5408.3 2223.99  5459.3 2225.40  5561.3 2231.14  5676.2 2234.18
#Mann=5,-1,0
  4314.3    0.07       0  4956.9    0.07       0  4960.9    0.07       0
  5066.5    0.16       0  5334.9    0.07       0
Bank Sta=4956.9,4960.9
Exp/Cntr=0.3,0.1

Type RM Length L Ch R = 1,1481,480,480,480
BEGIN DESCRIPTION:
WEAVER SPRINGS CREEK TRIB 1_1 3.0
END DESCRIPTION:
XS GIS Cut Line= 3
      1452179.99      6830013.03      1452355.00      6829638.00
      1451980.01      6828963.02
#Sta/Elev= 30
  4582.0 2213.47  4686.9 2212.15  4696.3 2210.85  4724.7 2211.72  4881.1 2209.11
  4929.6 2207.61  4935.9 2204.72  4941.5 2205.97  4951.7 2204.51  4957.9 2202.50
  4964.3 2204.97  4981.7 2199.50  4987.2 2199.85  4991.1 2198.88  4991.3 2198.38
  4995.1 2198.88  5041.6 2201.03  5063.3 2204.40  5069.1 2204.46  5075.9 2207.13
  5090.8 2209.55  5139.6 2210.78  5182.9 2212.23  5327.6 2214.16  5425.8 2216.96
  5510.2 2220.37  5556.4 2222.09  5627.3 2227.70  5693.7 2230.34  5768.0 2231.56
#Mann=9,-1,0
  4582.0    0.07       0  4881.1    0.16       0  4957.9    0.07       0
  4991.1    0.07       0  4995.1    0.07       0  5139.6    0.16       0
  5182.9    0.07       0  5425.8    0.16       0  5510.2    0.07       0
Bank Sta=4991.1,4995.1
Exp/Cntr=0.3,0.1

Type RM Length L Ch R = 1,1001,334,334,334
BEGIN DESCRIPTION:
WEAVER SPRINGS CREEK TRIB 1_1 2.0
END DESCRIPTION:
XS GIS Cut Line= 3
      1452154.40      6830213.23      1452805.00      6829638.00
      1452592.75      6829026.20
#Sta/Elev= 30
  4136.5 2218.10  4148.0 2216.87  4197.3 2215.42  4211.5 2213.01  4232.4 2214.27
  4352.9 2209.70  4593.8 2205.79  4806.3 2199.96  4940.9 2193.79  4948.5 2191.59
  4983.6 2186.12  4989.1 2186.10  4989.4 2185.60  4993.1 2186.10  4997.8 2187.27
  5007.6 2187.33  5015.2 2190.54  5020.5 2188.20  5026.1 2191.74  5036.7 2195.71
  5046.3 2197.74  5051.6 2197.13  5108.6 2200.49  5145.0 2200.48  5326.5 2206.04
  5375.4 2208.34  5414.6 2212.71  5482.2 2217.79  5565.0 2219.99  5652.5 2219.83
#Mann=3,-1,0
  4136.5    0.07       0  4989.1    0.07       0  4993.1    0.07       0
Bank Sta=4989.1,4993.1
Exp/Cntr=0.3,0.1

Type RM Length L Ch R = 1,667,545,545,545
BEGIN DESCRIPTION:
Mapping XS ed7b15f0
END DESCRIPTION:
XS GIS Cut Line= 4
      1452538.45      6830274.09      1453030.60      6829917.34
      1453082.69      6829763.69      1452931.67      6829242.94
#Sta/Elev= 30
  4308.8 2203.78  4446.8 2199.43  4497.0 2198.57  4532.6 2199.41  4547.3 2198.49
  4618.4 2198.07  4633.1 2196.88  4668.7 2196.41  4683.4 2194.53  4739.8 2193.28
  4748.3 2191.99  4754.5 2192.93  4911.5 2191.29  4944.1 2189.63  4949.4 2190.14
  4955.0 2188.41  4968.8 2183.43  4975.6 2179.32  4987.9 2177.14  4988.1 2176.64
  4991.9 2177.14  4993.5 2177.95  5000.4 2181.44  5032.1 2185.07  5084.1 2185.40
  5234.0 2190.46  5324.3 2195.77  5470.1 2200.47  5532.5 2204.52  5621.1 2208.49
#Mann=5,-1,0
  4308.8    0.07       0  4955.0    0.16       0  4987.9    0.07       0
  4991.9    0.16       0  4993.5    0.07       0
Bank Sta=4987.9,4991.9
Exp/Cntr=0.3,0.1

Type RM Length L Ch R = 1,122,0,0,0
BEGIN DESCRIPTION:
WEAVER SPRINGS CREEK TRIB 1_1 1.0
END DESCRIPTION:
XS GIS Cut Line= 3
      1453340.49      6830023.73      1453538.25      6829921.53
      1453304.67      6829321.39
#Sta/Elev= 30
  4777.4 2182.70  4888.7 2179.05  4905.2 2177.41  4910.8 2177.76  4949.5 2175.63
  4971.6 2174.02  4977.2 2172.25  4993.8 2170.74  4996.4 2167.68  4996.7 2167.18
  5000.2 2167.18  5000.4 2167.68  5014.5 2167.88  5021.3 2170.79  5036.0 2171.78
  5045.8 2173.23  5051.2 2172.45  5075.7 2177.75  5081.1 2176.54  5100.2 2179.00
  5135.5 2180.50  5143.3 2181.67  5175.5 2183.54  5274.2 2186.29  5407.5 2185.16
  5508.1 2186.76  5521.6 2187.57  5551.5 2191.58  5600.5 2195.79  5644.0 2197.19
#Mann=3,-1,0
  4777.4    0.07       0  4996.4    0.07       0  5000.4    0.07       0
Bank Sta=4996.4,5000.4
Exp/Cntr=0.3,0.1

Chan Stop Cuts=-1