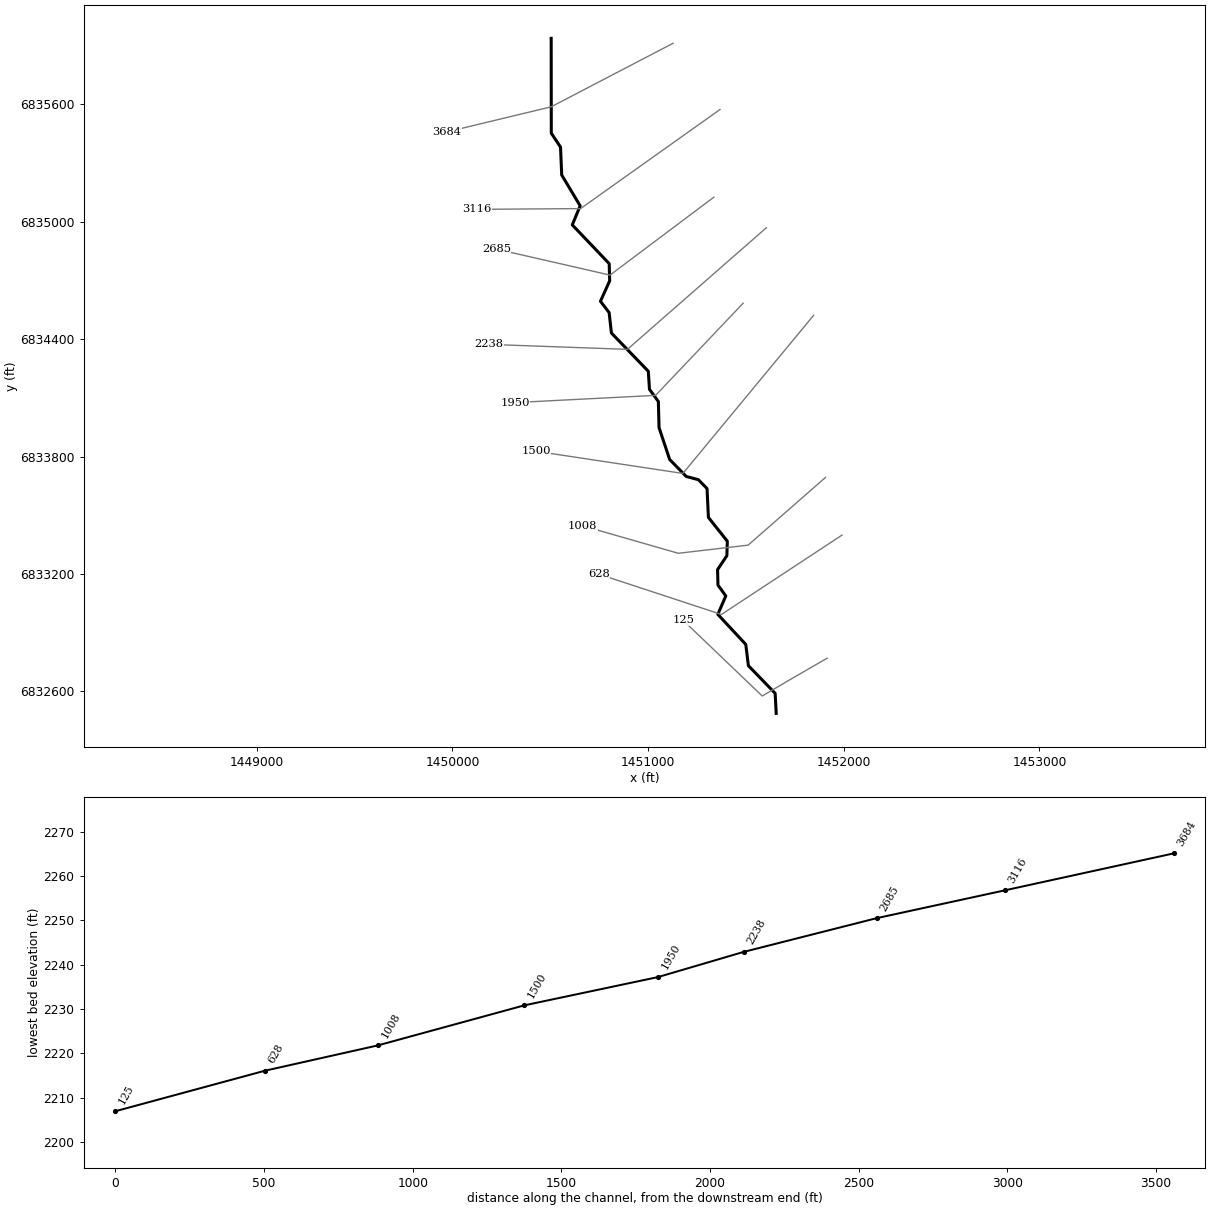
--- WEAVER SPRINGS CREEK TRIB 1_2.prj (project) ---

Proj Title=WEAVER SPRINGS CREEK TRIB 1_2 Base Level Engineering
Current Plan=p01
Default Exp/Contr=0.3,0.1
English Units
Geom File=g01
Flow File=f01
Plan File=p01
Y Axis Title=Elevation
X Axis Title(PF)=Main Channel Distance
X Axis Title(XS)=Station
BEGIN DESCRIPTION:
WEAVER SPRINGS CREEK TRIB 1_2
END DESCRIPTION:
DSS Export Rating Curves= 0
DSS Export Rating Curve Sorted= 0
DSS Export Volume Flow Curves= 0
DXF OffsetX= 0
DXF OffsetY= 0
DXF ScaleX= 1
DXF ScaleY= 10

--- WEAVER SPRINGS CREEK TRIB 1_2.p01 (plan) ---

Plan Title=Multiple Run
Short Identifier=Multiple
Geom File=g01
Flow File=f01
Subcritical Flow
K Sum by GR= 0
Std Step Tol= 0.01
Critical Tol= 0.01
Num of Std Step Trials= 20
Max Error Tol= 0.3
Flow Tol Ratio= 0.001
Split Flow NTrial= 30
Split Flow Tol= 0.02
Split Flow Ratio= 0.02
Log Output Level= 0
Friction Slope Method= 1
Unsteady Friction Slope Method= 2
Unsteady Bridges Friction Slope Method= 1
Parabolic Critical Depth
Global Vel Dist=  1 , 1 , 1
Global Log Level= 0
CheckData=True
Encroach Param= -1, 0, 0, 0
BEGIN DESCRIPTION:
Multiple Run
END DESCRIPTION:

--- WEAVER SPRINGS CREEK TRIB 1_2.f01 (steady flow) ---

Flow Title=Multiple
Program Version=4.10
Number of Profiles= 7
Profile Names=10-year,25-year,50-year,1pct_min,100-year,1pct_plu,500-year
River Rch & RM=WEAVER SPRINGS C,Reach-1         ,3684
     313     451     570     359     716    1428    1143
River Rch & RM=WEAVER SPRINGS C,Reach-1         ,2685
     342     495     626     395     788    1572    1262
Boundary for River Rch & Prof#=WEAVER SPRINGS C,Reach-1         , 1
Up Type= 0
Dn Type= 3
Dn Slope=0.018
Boundary for River Rch & Prof#=WEAVER SPRINGS C,Reach-1         , 2
Up Type= 0
Dn Type= 3
Dn Slope=0.018
Boundary for River Rch & Prof#=WEAVER SPRINGS C,Reach-1         , 3
Up Type= 0
Dn Type= 3
Dn Slope=0.018
Boundary for River Rch & Prof#=WEAVER SPRINGS C,Reach-1         , 4
Up Type= 0
Dn Type= 3
Dn Slope=0.018
Boundary for River Rch & Prof#=WEAVER SPRINGS C,Reach-1         , 5
Up Type= 0
Dn Type= 3
Dn Slope=0.018
Boundary for River Rch & Prof#=WEAVER SPRINGS C,Reach-1         , 6
Up Type= 0
Dn Type= 3
Dn Slope=0.018
Boundary for River Rch & Prof#=WEAVER SPRINGS C,Reach-1         , 7
Up Type= 0
Dn Type= 3
Dn Slope=0.018
DSS Import GetInterval= 0
DSS Import GetPeak= 0
DSS Import FillOption= 0

--- WEAVER SPRINGS CREEK TRIB 1_2.g01 (geometry) ---

Geom Title=Existing Conditions

River Reach=WEAVER SPRINGS C,Reach-1
Reach XY= 30
      1450505.00      6835938.00      1450505.52      6835453.22
      1450552.73      6835382.06      1450558.76      6835239.56
      1450653.16      6835081.87      1450612.82      6834984.59
      1450801.54      6834786.50      1450803.88      6834698.55
      1450756.82      6834594.12      1450801.11      6834536.41
      1450812.86      6834431.83      1451001.39      6834236.50
      1451007.36      6834143.98      1451052.73      6834082.06
      1451056.23      6833948.51      1451110.52      6833785.56
      1451195.32      6833698.78      1451257.57      6833682.26
      1451301.54      6833636.75      1451308.56      6833489.47
      1451405.21      6833367.95      1451402.83      6833293.98
      1451355.39      6833222.72      1451357.36      6833143.89
      1451397.40      6833087.99      1451356.66      6832994.05
      1451499.48      6832840.43      1451512.86      6832731.83
      1451649.65      6832590.50      1451655.00      6832488.00

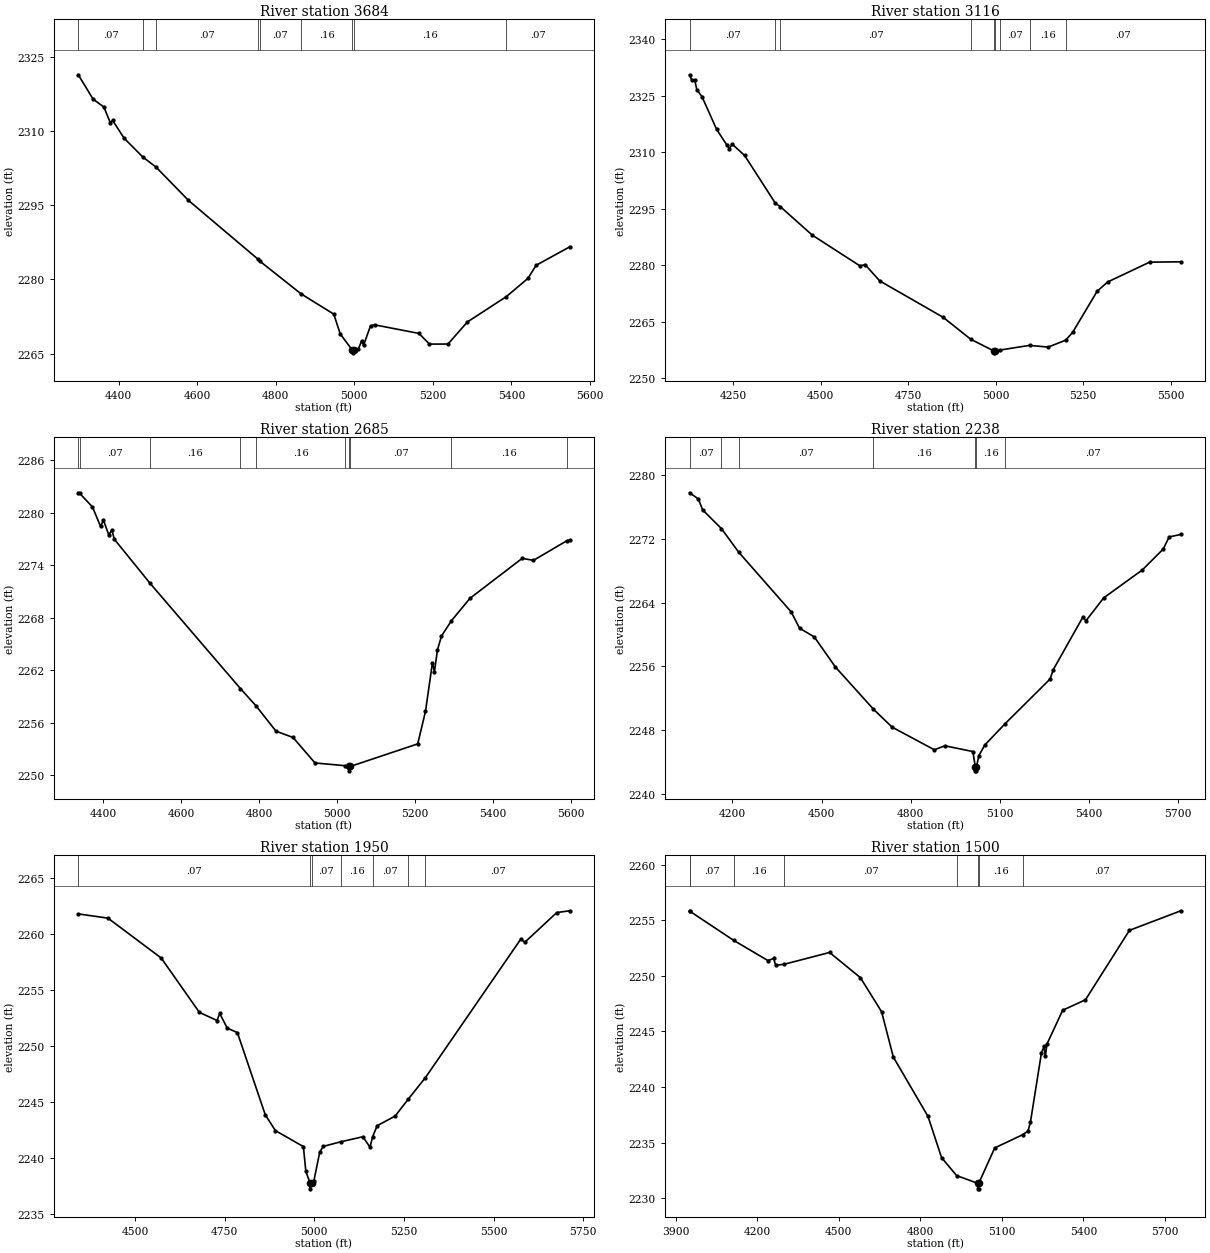
Type RM Length L Ch R = 1,3684,568,568,568
BEGIN DESCRIPTION:
WEAVER SPRINGS CREEK TRIB 1_2 8.0
END DESCRIPTION:
XS GIS Cut Line= 3
      1451128.37      6835912.95      1450505.00      6835588.00
      1449972.08      6835459.82
#Sta/Elev= 30
  4297.0 2321.42  4334.6 2316.50  4362.3 2314.88  4378.8 2311.64  4384.4 2312.18
  4413.6 2308.59  4461.2 2304.78  4495.0 2302.73  4577.6 2295.99  4754.1 2284.13
  4759.2 2283.70  4864.1 2277.09  4947.6 2272.97  4964.0 2268.98  4995.2 2265.64
  4995.4 2265.14  4999.2 2265.64  5010.3 2265.93  5018.4 2267.53  5023.5 2266.67
  5041.1 2270.59  5051.4 2270.81  5164.5 2269.07  5191.3 2266.91  5238.4 2266.92
  5288.0 2271.40  5386.7 2276.50  5442.2 2280.22  5462.8 2282.86  5548.1 2286.58
#Mann=9,-1,0
  4297.0    0.07       0  4461.2    0.16       0  4495.0    0.07       0
  4754.1    0.16       0  4759.2    0.07       0  4864.1    0.16       0
  4995.2    0.07       0  4999.2    0.16       0  5386.7    0.07       0
Bank Sta=4995.2,4999.2
Exp/Cntr=0.3,0.1

Type RM Length L Ch R = 1,3116,431,431,431
BEGIN DESCRIPTION:
WEAVER SPRINGS CREEK TRIB 1_2 7.0
END DESCRIPTION:
XS GIS Cut Line= 3
      1451367.92      6835574.39      1450655.22      6835067.80
      1450125.73      6835063.99
#Sta/Elev= 30
  4125.6 2330.57  4131.7 2329.16  4140.3 2329.17  4146.4 2326.62  4161.2 2324.76
  4203.0 2316.08  4232.5 2311.88  4239.6 2311.00  4247.3 2312.19  4282.9 2309.17
  4371.0 2296.47  4384.8 2295.60  4476.0 2288.05  4612.5 2279.87  4627.3 2280.20
  4669.1 2275.88  4849.9 2266.25  4929.2 2260.40  4995.1 2257.30  4995.3 2256.80
  4999.1 2257.30  5012.1 2257.53  5097.1 2258.78  5150.2 2258.32  5200.2 2260.15
  5220.2 2262.21  5290.2 2273.13  5320.2 2275.59  5440.2 2280.86  5529.5 2280.95
#Mann=9,-1,0
  4125.6    0.07       0  4371.0    0.16       0  4384.8    0.07       0
  4929.2    0.16       0  4995.1    0.07       0  4999.1    0.16       0
  5012.1    0.07       0  5097.1    0.16       0  5200.2    0.07       0
Bank Sta=4995.1,4999.1
Exp/Cntr=0.3,0.1

Type RM Length L Ch R = 1,2685,447,447,447
BEGIN DESCRIPTION:
WEAVER SPRINGS CREEK TRIB 1_2 6.0
END DESCRIPTION:
XS GIS Cut Line= 3
      1451336.66      6835126.47      1450805.79      6834727.95
      1450224.70      6834860.87
#Sta/Elev= 30
  4336.2 2282.28  4339.5 2282.23  4372.4 2280.67  4393.2 2278.45  4400.8 2279.15
  4414.1 2277.49  4422.4 2278.00  4428.7 2276.97  4520.6 2271.92  4751.9 2259.92
  4792.2 2257.93  4843.2 2255.05  4886.9 2254.33  4943.2 2251.42  5019.7 2251.11
  5029.6 2251.02  5029.8 2250.52  5033.6 2251.02  5206.6 2253.60  5226.5 2257.30
  5244.4 2262.87  5249.5 2261.86  5257.3 2264.34  5267.5 2265.91  5293.0 2267.66
  5340.5 2270.22  5474.5 2274.79  5503.5 2274.56  5589.0 2276.80  5596.1 2276.87
#Mann=10,-1,0
  4336.2    0.16       0  4339.5    0.07       0  4520.6    0.16       0
  4751.9    0.07       0  4792.2    0.16       0  5019.7    0.07       0
  5029.6    0.07       0  5033.6    0.07       0  5293.0    0.16       0
  5589.0    0.07       0
Bank Sta=5029.6,5033.6
Exp/Cntr=0.3,0.1

Type RM Length L Ch R = 1,2238,288,288,288
BEGIN DESCRIPTION:
WEAVER SPRINGS CREEK TRIB 1_2 5.0
END DESCRIPTION:
XS GIS Cut Line= 3
      1451604.93      6834970.25      1450894.54      6834348.41
      1450185.60      6834373.89
#Sta/Elev= 30
  4055.9 2277.78  4085.6 2277.01  4099.8 2275.64  4163.4 2273.28  4221.8 2270.31
  4397.8 2262.85  4426.3 2260.79  4475.6 2259.71  4546.8 2255.93  4674.8 2250.64
  4737.6 2248.39  4879.8 2245.55  4915.1 2246.05  5009.5 2245.33  5017.6 2243.41
  5017.8 2242.91  5021.3 2242.91  5021.6 2243.41  5029.6 2244.82  5049.6 2246.15
  5117.9 2248.82  5269.7 2254.44  5279.7 2255.58  5379.8 2262.20  5389.8 2261.72
  5449.8 2264.60  5579.9 2268.11  5650.0 2270.72  5670.0 2272.24  5709.4 2272.56
#Mann=7,-1,0
  4055.9    0.07       0  4163.4    0.16       0  4221.8    0.07       0
  4674.8    0.16       0  5017.6    0.07       0  5021.6    0.16       0
  5117.9    0.07       0
Bank Sta=5017.6,5021.6
Exp/Cntr=0.3,0.1

Type RM Length L Ch R = 1,1950,450,450,450
BEGIN DESCRIPTION:
Mapping XS 459a9e9f
END DESCRIPTION:
XS GIS Cut Line= 3
      1451485.88      6834584.22      1451038.82      6834113.29
      1450319.21      6834076.44
#Sta/Elev= 30
  4342.0 2261.83  4424.8 2261.45  4573.3 2257.88  4679.6 2253.02  4729.0 2252.29
  4736.2 2252.93  4757.3 2251.61  4785.6 2251.21  4863.3 2243.86  4891.6 2242.44
  4969.6 2241.01  4976.5 2238.79  4988.5 2237.73  4988.7 2237.23  4992.5 2237.73
  4998.6 2237.89  5015.2 2240.52  5025.2 2241.03  5073.9 2241.44  5135.4 2241.89
  5155.4 2240.96  5162.8 2241.90  5175.4 2242.88  5225.5 2243.74  5261.8 2245.25
  5310.1 2247.19  5575.9 2259.58  5587.3 2259.30  5676.1 2261.95  5711.9 2262.11
#Mann=7,-1,0
  4342.0    0.07       0  4988.5    0.07       0  4992.5    0.07       0
  5073.9    0.16       0  5162.8    0.07       0  5261.8    0.16       0
  5310.1    0.07       0
Bank Sta=4988.5,4992.5
Exp/Cntr=0.3,0.1

Type RM Length L Ch R = 1,1500,492,492,492
BEGIN DESCRIPTION:
WEAVER SPRINGS CREEK TRIB 1_2 3.0
END DESCRIPTION:
XS GIS Cut Line= 3
      1451846.23      6834522.35      1451178.12      6833714.27
      1450428.03      6833827.58
#Sta/Elev= 30
  3951.5 2255.82  3952.5 2255.82  4113.7 2253.20  4239.9 2251.38  4260.8 2251.57
  4268.5 2250.95  4300.1 2251.05  4466.6 2252.11  4580.0 2249.84  4658.0 2246.77
  4701.0 2242.70  4828.7 2237.35  4878.4 2233.65  4934.0 2232.03  5011.3 2231.34
  5011.5 2230.84  5015.0 2230.84  5015.3 2231.34  5073.9 2234.52  5176.9 2235.71
  5196.4 2236.04  5205.4 2236.85  5245.9 2243.08  5255.1 2243.66  5260.2 2242.75
  5266.1 2243.87  5324.0 2246.91  5407.7 2247.85  5569.5 2254.10  5758.6 2255.86
#Mann=8,-1,0
  3951.5    0.16       0  3952.5    0.07       0  4113.7    0.16       0
  4300.1    0.07       0  4934.0    0.16       0  5011.3    0.07       0
  5015.3    0.16       0  5176.9    0.07       0
Bank Sta=5011.3,5015.3
Exp/Cntr=0.3,0.1

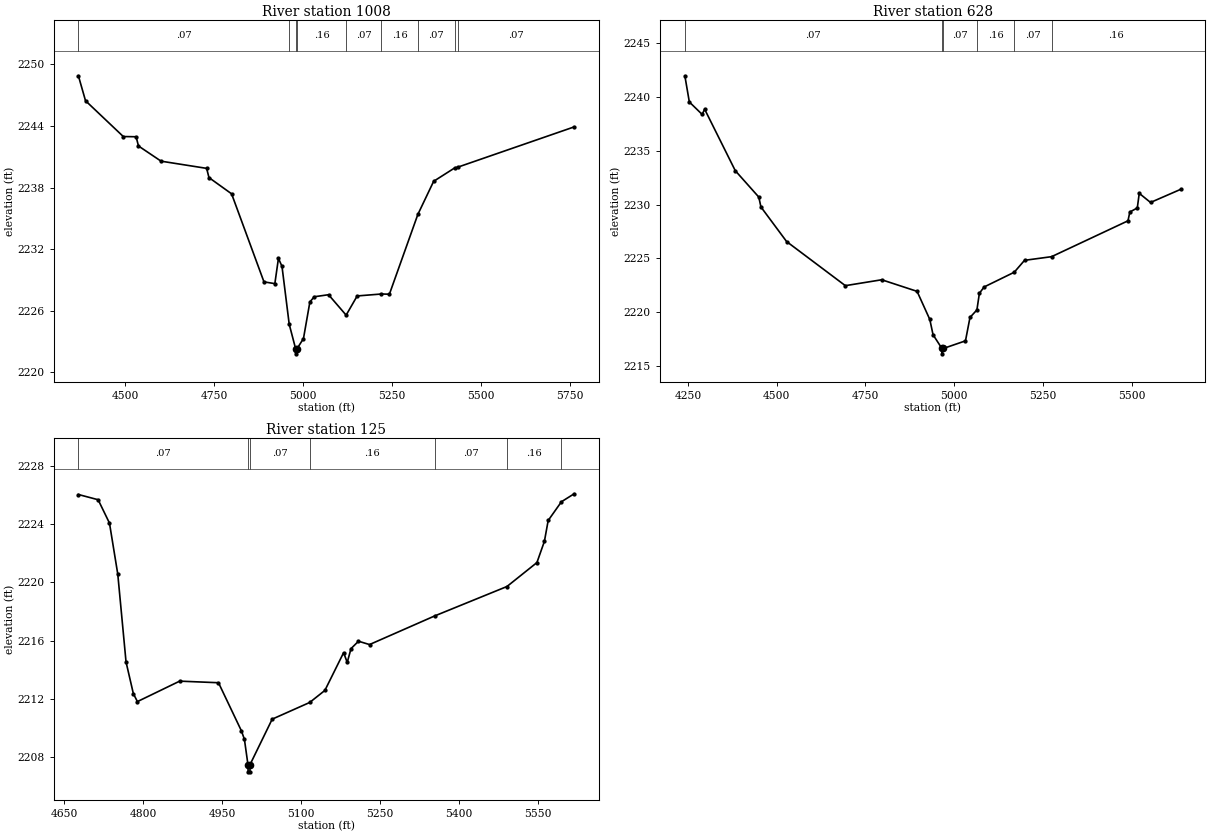
Type RM Length L Ch R = 1,1008,380,380,380
BEGIN DESCRIPTION:
Mapping XS ba19b87a
END DESCRIPTION:
XS GIS Cut Line= 4
      1451907.29      6833694.17      1451511.49      6833347.84
      1451154.72      6833306.18      1450665.13      6833446.80
#Sta/Elev= 30
  4367.7 2248.90  4387.7 2246.47  4494.0 2242.98  4530.0 2242.96  4536.7 2242.06
  4600.3 2240.58  4728.4 2239.88  4735.0 2238.98  4798.6 2237.40  4889.7 2228.82
  4920.3 2228.65  4930.4 2231.11  4940.4 2230.33  4960.7 2224.69  4978.7 2222.31
  4978.9 2221.81  4982.7 2222.31  5000.8 2223.30  5018.8 2226.86  5031.0 2227.37
  5071.3 2227.57  5120.8 2225.58  5151.9 2227.45  5220.2 2227.64  5242.5 2227.62
  5322.5 2235.39  5367.0 2238.62  5426.4 2239.93  5434.3 2239.99  5762.2 2243.92
#Mann=9,-1,0
  4367.7    0.07       0  4960.7    0.16       0  4978.7    0.07       0
  4982.7    0.16       0  5120.8    0.07       0  5220.2    0.16       0
  5322.5    0.07       0  5426.4    0.16       0  5434.3    0.07       0
Bank Sta=4978.7,4982.7
Exp/Cntr=0.3,0.1

Type RM Length L Ch R = 1,628,503,503,503
BEGIN DESCRIPTION:
Mapping XS a973e788
END DESCRIPTION:
XS GIS Cut Line= 3
      1451991.52      6833399.32      1451375.19      6832993.49
      1450748.99      6833199.34
#Sta/Elev= 30
  4241.3 2241.99  4253.9 2239.55  4290.1 2238.39  4297.0 2238.88  4383.4 2233.15
  4449.7 2230.69  4455.7 2229.77  4528.0 2226.55  4693.6 2222.44  4796.1 2222.99
  4895.7 2221.91  4931.6 2219.29  4940.7 2217.87  4965.7 2216.59  4966.0 2216.09
  4969.7 2216.59  5032.1 2217.30  5044.8 2219.48  5064.3 2220.18  5071.3 2221.73
  5084.7 2222.32  5169.5 2223.69  5198.5 2224.80  5274.7 2225.14  5490.0 2228.48
  5495.3 2229.30  5516.3 2229.68  5521.8 2231.04  5553.6 2230.19  5638.4 2231.41
#Mann=6,-1,0
  4241.3    0.07       0  4965.7    0.07       0  4969.7    0.07       0
  5064.3    0.16       0  5169.5    0.07       0  5274.7    0.16       0
Bank Sta=4965.7,4969.7
Exp/Cntr=0.3,0.1

Type RM Length L Ch R = 1,125,0,0,0
BEGIN DESCRIPTION:
WEAVER SPRINGS CREEK TRIB 1_2 1.0
END DESCRIPTION:
XS GIS Cut Line= 4
      1451915.57      6832769.98      1451730.00      6832663.00
      1451583.52      6832576.83      1451179.98      6832963.01
#Sta/Elev= 30
  4676.6 2226.06  4714.1 2225.70  4735.7 2224.09  4751.5 2220.57  4767.2 2214.52
  4781.1 2212.34  4788.8 2211.79  4869.2 2213.20  4943.0 2213.09  4986.5 2209.78
  4992.3 2209.19  4999.0 2207.45  4999.3 2206.95  5002.8 2206.95  5003.0 2207.45
  5045.1 2210.58  5116.4 2211.73  5145.3 2212.56  5180.9 2215.16  5187.8 2214.49
  5195.0 2215.44  5209.2 2215.95  5230.2 2215.72  5353.9 2217.69  5491.5 2219.72
  5548.5 2221.37  5562.7 2222.83  5569.9 2224.27  5595.1 2225.56  5619.3 2226.11
#Mann=7,-1,0
  4676.6    0.07       0  4999.0    0.07       0  5003.0    0.07       0
  5116.4    0.16       0  5353.9    0.07       0  5491.5    0.16       0
  5595.1    0.07       0
Bank Sta=4999,5003
Exp/Cntr=0.3,0.1

Chan Stop Cuts=-1