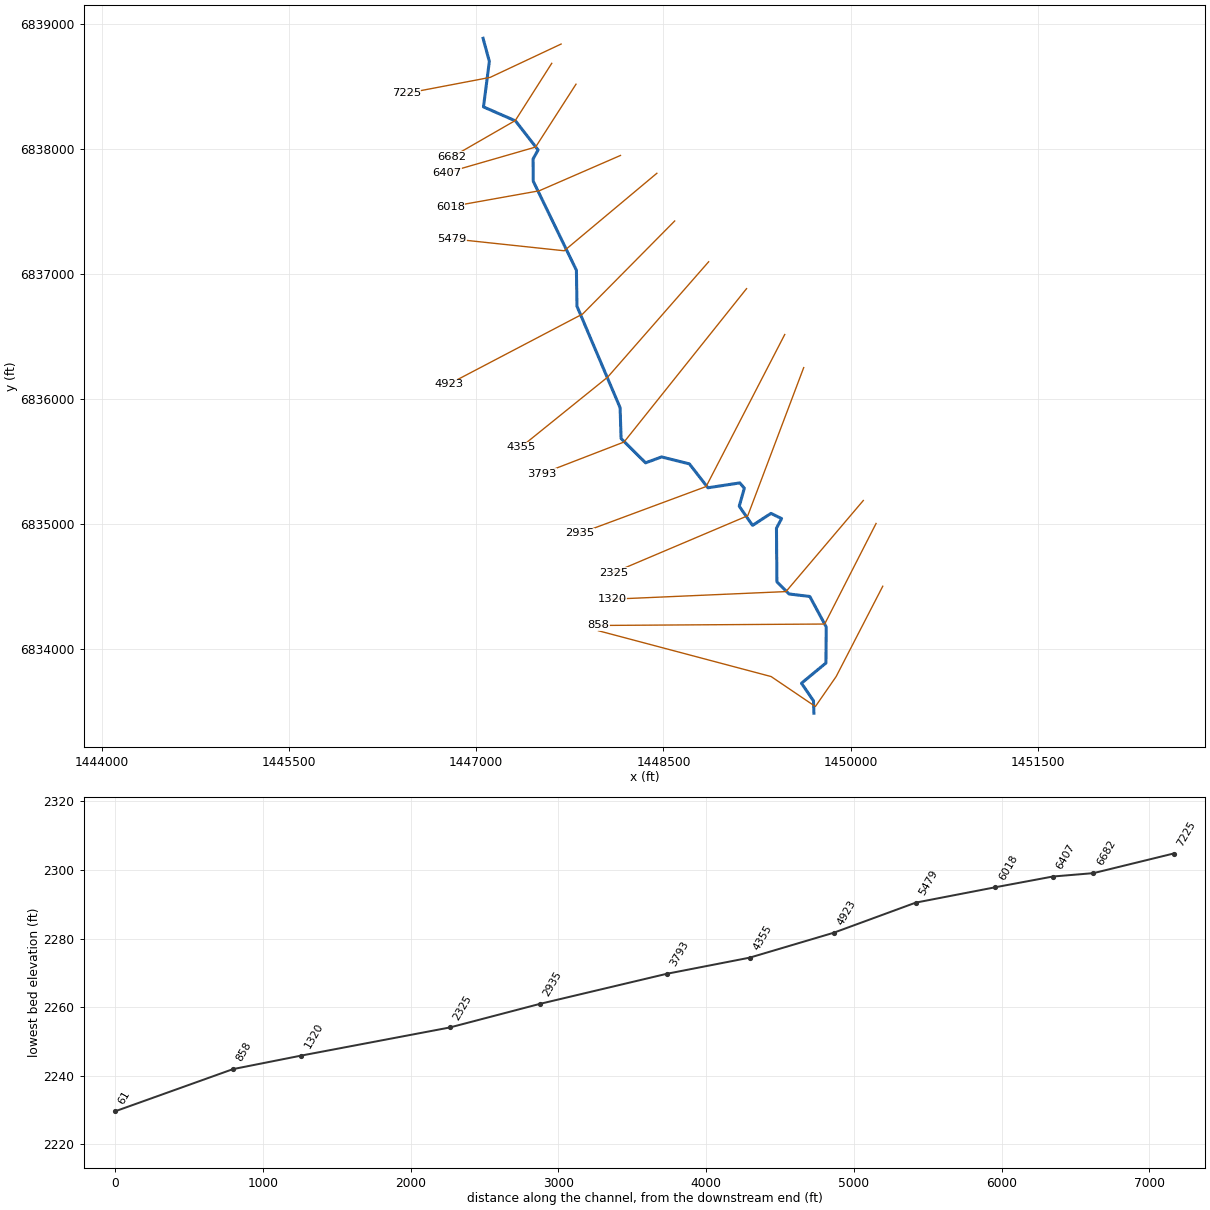
--- WEAVER SPRINGS CREEK TRIB 1_3.prj (project) ---

Proj Title=WEAVER SPRINGS CREEK TRIB 1_3 Base Level Engineering
Current Plan=p01
Default Exp/Contr=0.3,0.1
English Units
Geom File=g01
Flow File=f01
Plan File=p01
Y Axis Title=Elevation
X Axis Title(PF)=Main Channel Distance
X Axis Title(XS)=Station
BEGIN DESCRIPTION:
WEAVER SPRINGS CREEK TRIB 1_3
END DESCRIPTION:
DSS Export Rating Curves= 0
DSS Export Rating Curve Sorted= 0
DSS Export Volume Flow Curves= 0
DXF OffsetX= 0
DXF OffsetY= 0
DXF ScaleX= 1
DXF ScaleY= 10

--- WEAVER SPRINGS CREEK TRIB 1_3.p01 (plan) ---

Plan Title=Multiple Run
Short Identifier=Multiple
Geom File=g01
Flow File=f01
Subcritical Flow
K Sum by GR= 0
Std Step Tol= 0.01
Critical Tol= 0.01
Num of Std Step Trials= 20
Max Error Tol= 0.3
Flow Tol Ratio= 0.001
Split Flow NTrial= 30
Split Flow Tol= 0.02
Split Flow Ratio= 0.02
Log Output Level= 0
Friction Slope Method= 1
Unsteady Friction Slope Method= 2
Unsteady Bridges Friction Slope Method= 1
Parabolic Critical Depth
Global Vel Dist=  1 , 1 , 1
Global Log Level= 0
CheckData=True
Encroach Param= -1, 0, 0, 0
BEGIN DESCRIPTION:
Multiple Run
END DESCRIPTION:

--- WEAVER SPRINGS CREEK TRIB 1_3.f01 (steady flow) ---

Flow Title=Multiple
Program Version=4.10
Number of Profiles= 7
Profile Names=10-year,25-year,50-year,1pct_min,100-year,1pct_plu,500-year
River Rch & RM=WEAVER SPRINGS C,Reach-1         ,7225
     672    1009    1310     845    1687    3365    2833
River Rch & RM=WEAVER SPRINGS C,Reach-1         ,4355
     689    1031    1336     860    1717    3425    2869
Boundary for River Rch & Prof#=WEAVER SPRINGS C,Reach-1         , 1
Up Type= 0
Dn Type= 3
Dn Slope=0.01548
Boundary for River Rch & Prof#=WEAVER SPRINGS C,Reach-1         , 2
Up Type= 0
Dn Type= 3
Dn Slope=0.01548
Boundary for River Rch & Prof#=WEAVER SPRINGS C,Reach-1         , 3
Up Type= 0
Dn Type= 3
Dn Slope=0.01548
Boundary for River Rch & Prof#=WEAVER SPRINGS C,Reach-1         , 4
Up Type= 0
Dn Type= 3
Dn Slope=0.01548
Boundary for River Rch & Prof#=WEAVER SPRINGS C,Reach-1         , 5
Up Type= 0
Dn Type= 3
Dn Slope=0.01548
Boundary for River Rch & Prof#=WEAVER SPRINGS C,Reach-1         , 6
Up Type= 0
Dn Type= 3
Dn Slope=0.01548
Boundary for River Rch & Prof#=WEAVER SPRINGS C,Reach-1         , 7
Up Type= 0
Dn Type= 3
Dn Slope=0.01548
DSS Import GetInterval= 0
DSS Import GetPeak= 0
DSS Import FillOption= 0

--- WEAVER SPRINGS CREEK TRIB 1_3.g01 (geometry) ---

Geom Title=Existing Conditions

River Reach=WEAVER SPRINGS C,Reach-1
Reach XY= 30
      1447055.00      6838888.00      1447105.43      6838703.18
      1447058.36      6838339.25      1447314.71      6838227.25
      1447495.85      6837994.73      1447455.66      6837922.84
      1447457.26      6837743.94      1447802.76      6837032.07
      1447807.26      6836743.94      1448152.76      6835932.07
      1448160.46      6835685.55      1448356.63      6835491.13
      1448484.82      6835538.28      1448707.70      6835482.64
      1448856.46      6835291.52      1449111.70      6835330.53
      1449147.77      6835288.38      1449106.97      6835143.89
      1449213.50      6834990.59      1449361.13      6835086.41
      1449445.99      6835045.12      1449405.19      6834968.02
      1449408.53      6834539.45      1449506.46      6834441.54
      1449672.14      6834421.72      1449803.80      6834177.50
      1449801.47      6833889.45      1449605.49      6833727.51
      1449701.60      6833586.59      1449705.00      6833488.00

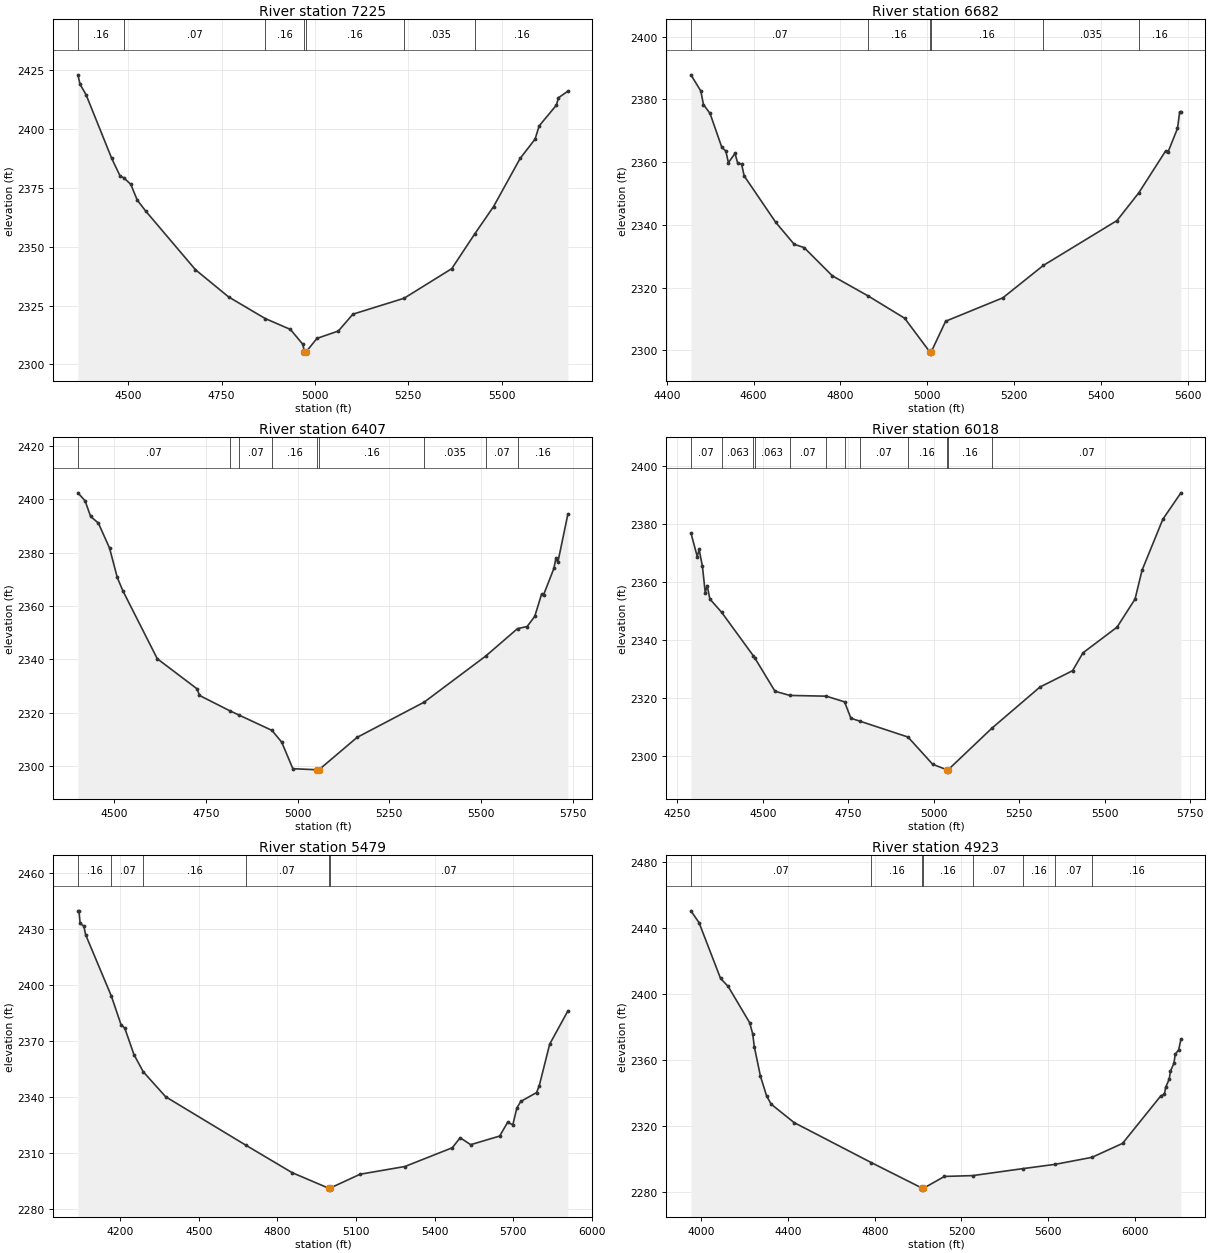
Type RM Length L Ch R = 1,7225,543,543,543
BEGIN DESCRIPTION:
WEAVER SPRINGS CREEK TRIB 1_3 15.0
END DESCRIPTION:
XS GIS Cut Line= 3
      1447680.09      6838842.24      1447111.50      6838575.31
      1446439.40      6838447.39
#Sta/Elev= 30
  4365.4 2422.90  4371.0 2418.95  4387.4 2414.40  4455.8 2387.48  4478.6 2379.88
  4488.0 2379.26  4507.0 2376.43  4524.2 2369.77  4547.1 2365.07  4680.3 2340.19
  4768.9 2328.67  4867.0 2319.49  4934.4 2314.88  4967.6 2308.59  4972.2 2305.31
  4972.5 2304.81  4976.4 2305.31  5005.5 2311.06  5062.8 2314.18  5101.9 2321.34
  5238.9 2328.09  5366.6 2340.65  5428.8 2355.55  5478.6 2367.01  5549.8 2387.44
  5589.8 2395.63  5600.7 2401.23  5647.1 2410.08  5652.2 2413.16  5677.7 2415.96
#Mann=7,-1,0
  4365.4    0.16       0  4488.0    0.07       0  4867.0    0.16       0
  4972.2    0.07       0  4976.4    0.16       0  5238.9   0.035       0
  5428.8    0.16       0
Bank Sta=4972.2,4976.4
Exp/Cntr=0.3,0.1

Type RM Length L Ch R = 1,6682,275,275,275
BEGIN DESCRIPTION:
WEAVER SPRINGS CREEK TRIB 1_3 14.0
END DESCRIPTION:
XS GIS Cut Line= 3
      1447605.02      6838688.03      1447313.33      6838230.25
      1446804.97      6837937.98
#Sta/Elev= 30
  4455.4 2387.80  4478.3 2382.62  4484.2 2378.34  4499.4 2375.51  4526.6 2364.68
  4535.8 2363.53  4541.8 2359.80  4557.0 2362.76  4562.9 2359.78  4572.2 2359.29
  4578.2 2355.56  4651.0 2340.75  4693.3 2333.79  4716.3 2332.72  4781.3 2323.73
  4864.1 2317.29  4948.0 2310.20  5005.3 2299.58  5005.6 2299.08  5009.5 2299.58
  5042.4 2309.25  5174.2 2316.71  5267.5 2327.03  5437.2 2341.33  5487.6 2350.20
  5549.3 2363.52  5555.1 2363.25  5576.7 2370.72  5581.7 2375.94  5584.6 2375.94
#Mann=6,-1,0
  4455.4    0.07       0  4864.1    0.16       0  5005.3    0.07       0
  5009.5    0.16       0  5267.5   0.035       0  5487.6    0.16       0
Bank Sta=5005.3,5009.5
Exp/Cntr=0.3,0.1

Type RM Length L Ch R = 1,6407,389,389,389
BEGIN DESCRIPTION:
WEAVER SPRINGS CREEK TRIB 1_3 13.0
END DESCRIPTION:
XS GIS Cut Line= 3
      1447799.42      6838521.02      1447475.87      6838017.99
      1446768.25      6837814.11
#Sta/Elev= 30
  4401.9 2402.36  4421.3 2399.39  4436.5 2393.52  4457.6 2391.02  4488.0 2381.68
  4509.1 2370.64  4524.3 2365.66  4618.1 2340.19  4726.5 2328.91  4733.0 2326.45
  4817.0 2320.60  4840.3 2319.12  4930.4 2313.35  4956.9 2308.95  4987.3 2299.00
  5054.0 2298.59  5054.3 2298.09  5058.2 2298.59  5162.3 2310.74  5345.1 2323.95
  5512.6 2341.21  5599.2 2351.49  5625.3 2352.27  5646.1 2356.08  5664.9 2364.47
  5670.1 2364.13  5698.2 2374.03  5703.8 2377.91  5709.0 2376.31  5736.4 2394.47
#Mann=9,-1,0
  4401.9    0.07       0  4817.0    0.16       0  4840.3    0.07       0
  4930.4    0.16       0  5054.0    0.07       0  5058.2    0.16       0
  5345.1   0.035       0  5512.6    0.07       0  5599.2    0.16       0
Bank Sta=5054,5058.2
Exp/Cntr=0.3,0.1

Type RM Length L Ch R = 1,6018,539,539,539
BEGIN DESCRIPTION:
WEAVER SPRINGS CREEK TRIB 1_3 12.0
END DESCRIPTION:
XS GIS Cut Line= 3
      1448155.84      6837950.83      1447504.76      6837667.90
      1446793.04      6837540.69
#Sta/Elev= 30
  4290.1 2376.93  4308.6 2368.79  4314.0 2371.25  4323.7 2365.48  4332.0 2356.34
  4337.5 2358.83  4345.5 2354.19  4379.7 2349.64  4472.8 2334.62  4477.0 2333.89
  4536.0 2322.44  4579.4 2321.01  4686.0 2320.75  4739.4 2318.79  4757.9 2313.15
  4785.3 2312.11  4924.9 2306.69  4997.1 2297.31  5038.1 2295.46  5038.4 2294.96
  5042.6 2295.46  5170.2 2309.73  5310.8 2323.89  5406.1 2329.51  5436.6 2335.67
  5536.2 2344.49  5588.9 2354.18  5609.3 2364.07  5670.2 2381.65  5723.0 2390.72
#Mann=12,-1,0
  4290.1    0.07       0  4379.7   0.063       0  4472.8    0.16       0
  4477.0   0.063       0  4579.4    0.07       0  4686.0   0.035       0
  4739.4    0.16       0  4785.3    0.07       0  4924.9    0.16       0
  5038.1    0.07       0  5042.6    0.16       0  5170.2    0.07       0
Bank Sta=5038.1,5042.6
Exp/Cntr=0.3,0.1

Type RM Length L Ch R = 1,5479,556,556,556
BEGIN DESCRIPTION:
WEAVER SPRINGS CREEK TRIB 1_3 11.0
END DESCRIPTION:
XS GIS Cut Line= 3
      1448446.95      6837808.04      1447705.00      6837188.00
      1446805.89      6837283.57
#Sta/Elev= 30
  4037.9 2439.85  4041.8 2439.85  4046.4 2433.15  4060.7 2431.55  4067.2 2427.07
  4165.9 2393.99  4202.5 2378.75  4216.8 2376.90  4252.0 2362.67  4287.2 2353.50
  4373.0 2340.05  4679.0 2314.07  4855.8 2299.32  4995.4 2290.97  4995.7 2290.47
  4999.9 2290.97  5115.4 2298.46  5286.4 2302.61  5467.4 2312.67  5497.6 2318.06
  5537.8 2314.33  5648.4 2318.96  5678.6 2326.27  5698.7 2325.03  5714.1 2334.03
  5728.9 2337.52  5789.2 2342.29  5799.3 2345.84  5839.5 2368.32  5909.0 2386.14
#Mann=6,-1,0
  4037.9    0.16       0  4165.9    0.07       0  4287.2    0.16       0
  4679.0    0.07       0  4995.4    0.07       0  4999.9    0.07       0
Bank Sta=4995.4,4999.9
Exp/Cntr=0.3,0.1

Type RM Length L Ch R = 1,4923,568,568,568
BEGIN DESCRIPTION:
WEAVER SPRINGS CREEK TRIB 1_3 10.0
END DESCRIPTION:
XS GIS Cut Line= 3
      1448589.85      6837426.33      1447852.64      6836682.02
      1446778.64      6836119.72
#Sta/Elev= 30
  3952.4 2450.41  3990.0 2443.20  4089.0 2409.45  4124.3 2404.55  4223.3 2382.59
  4237.5 2375.71  4244.6 2368.13  4272.9 2350.23  4301.2 2338.30  4322.3 2333.20
  4428.4 2322.01  4785.2 2297.70  5020.2 2282.17  5020.6 2281.67  5024.8 2282.17
  5121.5 2289.36  5251.6 2289.87  5481.8 2294.07  5633.1 2296.72  5802.1 2300.95
  5943.2 2309.41  6119.7 2338.25  6136.1 2339.14  6141.8 2343.40  6158.2 2348.31
  6163.9 2353.12  6180.3 2358.09  6185.9 2363.34  6202.3 2366.32  6212.3 2372.50
#Mann=8,-1,0
  3952.4    0.07       0  4785.2    0.16       0  5020.2    0.07       0
  5024.8    0.16       0  5251.6    0.07       0  5481.8    0.16       0
  5633.1    0.07       0  5802.1    0.16       0
Bank Sta=5020.2,5024.8
Exp/Cntr=0.3,0.1

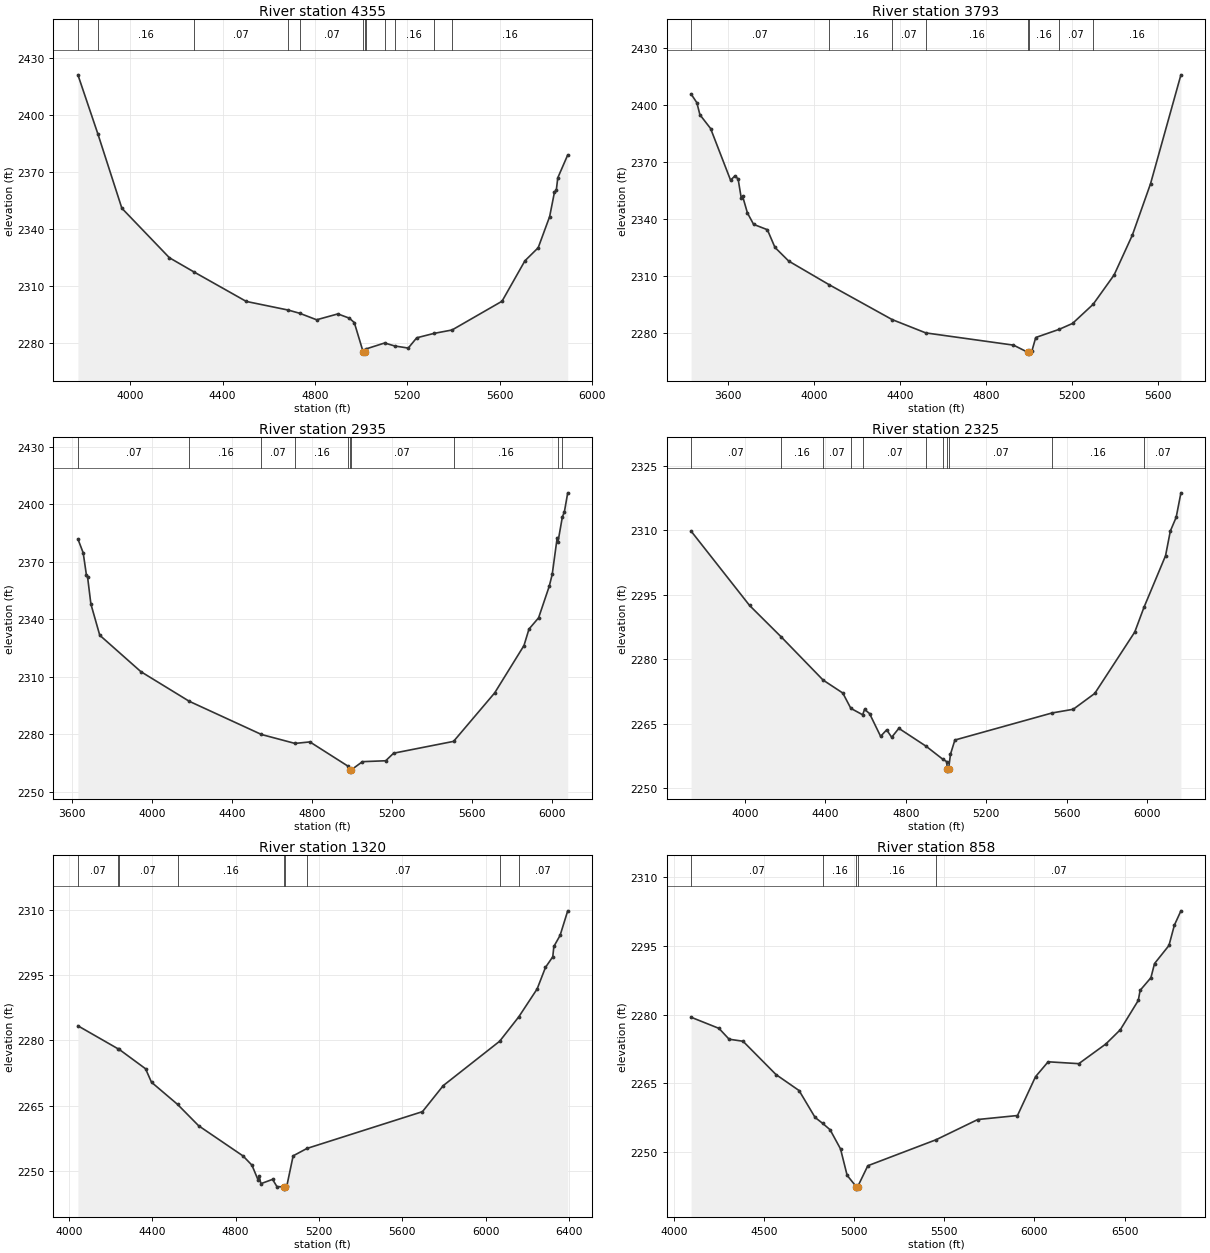
Type RM Length L Ch R = 1,4355,562,562,562
BEGIN DESCRIPTION:
WEAVER SPRINGS CREEK TRIB 1_3 9.0
END DESCRIPTION:
XS GIS Cut Line= 3
      1448862.05      6837100.12      1448053.67      6836177.45
      1447356.79      6835615.70
#Sta/Elev= 30
  3773.3 2420.96  3860.2 2389.70  3963.7 2350.71  4169.6 2324.64  4278.1 2317.02
  4502.7 2301.63  4684.1 2297.09  4733.9 2295.40  4807.4 2291.97  4899.4 2295.06
  4948.8 2292.83  4970.6 2290.50  5009.3 2274.91  5009.8 2274.41  5015.3 2274.91
  5021.2 2276.61  5102.1 2279.75  5145.5 2278.18  5204.3 2277.08  5241.0 2282.48
  5315.4 2284.79  5394.1 2286.60  5610.5 2301.74  5709.7 2323.03  5767.2 2329.91
  5816.8 2346.31  5837.6 2359.13  5845.6 2360.16  5852.0 2366.70  5895.1 2378.77
#Mann=12,-1,0
  3773.3    0.07       0  3860.2    0.16       0  4278.1    0.07       0
  4684.1    0.16       0  4733.9    0.07       0  5009.3    0.07       0
  5015.3    0.07       0  5021.2    0.16       0  5102.1    0.07       0
  5145.5    0.16       0  5315.4    0.07       0  5394.1    0.16       0
Bank Sta=5009.3,5015.3
Exp/Cntr=0.3,0.1

Type RM Length L Ch R = 1,3793,858,858,858
BEGIN DESCRIPTION:
WEAVER SPRINGS CREEK TRIB 1_3 8.0
END DESCRIPTION:
XS GIS Cut Line= 3
      1449165.62      6836885.02      1448184.51      6835657.80
      1447525.02      6835403.27
#Sta/Elev= 30
  3428.8 2405.65  3455.4 2401.12  3469.8 2394.78  3519.4 2387.56  3612.3 2360.45
  3633.1 2362.74  3647.5 2361.02  3661.9 2351.11  3668.3 2352.04  3690.7 2343.25
  3719.5 2337.26  3783.5 2334.45  3818.8 2325.16  3882.8 2317.99  4069.6 2305.67
  4363.7 2287.30  4520.3 2280.30  4928.2 2273.89  4993.6 2270.19  4994.1 2269.69
  4999.8 2270.19  5014.4 2271.04  5031.6 2277.89  5141.0 2282.19  5202.8 2285.27
  5298.4 2295.29  5396.1 2310.70  5481.0 2331.62  5565.5 2358.57  5706.9 2415.73
#Mann=8,-1,0
  3428.8    0.07       0  4069.6    0.16       0  4363.7    0.07       0
  4520.3    0.16       0  4993.6    0.07       0  4999.8    0.16       0
  5141.0    0.07       0  5298.4    0.16       0
Bank Sta=4993.6,4999.8
Exp/Cntr=0.3,0.1

Type RM Length L Ch R = 1,2935,610,610,610
BEGIN DESCRIPTION:
WEAVER SPRINGS CREEK TRIB 1_3 6.0
END DESCRIPTION:
XS GIS Cut Line= 3
      1449471.39      6836517.82      1448841.66      6835301.36
      1447828.26      6834925.64
#Sta/Elev= 30
  3630.2 2381.83  3656.6 2374.66  3673.1 2362.85  3678.7 2361.94  3695.2 2347.95
  3739.5 2331.71  3945.3 2312.73  4187.3 2297.30  4548.7 2280.00  4716.3 2275.35
  4790.8 2276.14  4983.7 2263.36  4989.3 2261.42  4989.8 2260.92  4995.7 2261.42
  5053.9 2265.85  5170.1 2266.32  5209.7 2270.26  5509.7 2276.42  5715.4 2301.68
  5862.0 2326.35  5887.0 2334.93  5935.0 2340.77  5988.3 2357.20  6003.2 2363.40
  6028.2 2382.59  6032.1 2380.32  6054.0 2393.33  6064.0 2395.94  6080.8 2405.89
#Mann=10,-1,0
  3630.2    0.07       0  4187.3    0.16       0  4548.7    0.07       0
  4716.3    0.16       0  4983.7    0.07       0  4989.3    0.07       0
  4995.7    0.07       0  5509.7    0.16       0  6032.1    0.07       0
  6054.0    0.16       0
Bank Sta=4989.3,4995.7
Exp/Cntr=0.3,0.1

Type RM Length L Ch R = 1,2325,1005,1005,1005
BEGIN DESCRIPTION:
WEAVER SPRINGS CREEK TRIB 1_3 4.0
END DESCRIPTION:
XS GIS Cut Line= 3
      1449623.33      6836253.13      1449175.26      6835068.01
      1448100.61      6834612.77
#Sta/Elev= 30
  3733.0 2309.83  4023.5 2292.55  4182.0 2285.18  4389.0 2275.20  4486.8 2272.19
  4526.7 2268.63  4585.5 2267.13  4594.9 2268.39  4619.7 2267.42  4674.7 2262.12
  4704.9 2263.63  4729.7 2261.90  4765.3 2263.98  4901.0 2259.81  4985.2 2256.74
  5002.9 2256.25  5006.1 2254.53  5006.6 2254.03  5012.5 2254.53  5022.0 2257.97
  5043.8 2261.26  5527.2 2267.56  5631.9 2268.41  5738.8 2272.09  5937.7 2286.37
  5983.4 2292.11  6090.7 2304.12  6114.4 2309.84  6143.5 2313.05  6167.1 2318.74
#Mann=11,-1,0
  3733.0    0.07       0  4182.0    0.16       0  4389.0    0.07       0
  4526.7    0.16       0  4585.5    0.07       0  4901.0    0.16       0
  4985.2    0.07       0  5006.1    0.07       0  5012.5    0.07       0
  5527.2    0.16       0  5983.4    0.07       0
Bank Sta=5006.1,5012.5
Exp/Cntr=0.3,0.1

Type RM Length L Ch R = 1,1320,462,462,462
BEGIN DESCRIPTION:
WEAVER SPRINGS CREEK TRIB 1_3 3.0
END DESCRIPTION:
XS GIS Cut Line= 3
      1450100.76      6835189.74      1449481.42      6834460.84
      1448088.45      6834399.86
#Sta/Elev= 30
  4043.5 2283.33  4236.1 2278.05  4238.7 2278.02  4368.1 2273.47  4396.7 2270.37
  4521.5 2265.30  4623.2 2260.37  4836.0 2253.45  4878.8 2251.33  4907.4 2248.03
  4914.0 2248.73  4921.7 2247.08  4977.7 2248.07  4998.6 2246.42  5033.2 2246.33
  5033.7 2245.83  5039.7 2246.33  5046.5 2246.63  5076.5 2253.47  5142.7 2255.17
  5697.1 2263.62  5797.2 2269.61  6067.7 2279.79  6159.4 2285.39  6247.6 2291.80
  6287.6 2296.75  6322.6 2299.18  6327.7 2301.54  6357.7 2304.09  6394.3 2309.73
#Mann=9,-1,0
  4043.5    0.07       0  4236.1    0.16       0  4238.7    0.07       0
  4521.5    0.16       0  5033.2    0.07       0  5039.7    0.16       0
  5142.7    0.07       0  6067.7    0.16       0  6159.4    0.07       0
Bank Sta=5033.2,5039.7
Exp/Cntr=0.3,0.1

Type RM Length L Ch R = 1,858,797,797,797
BEGIN DESCRIPTION:
WEAVER SPRINGS CREEK TRIB 1_3 2.0
END DESCRIPTION:
XS GIS Cut Line= 3
      1450202.89      6835005.69      1449791.28      6834201.17
      1447978.61      6834189.73
#Sta/Elev= 30
  4096.3 2279.43  4250.8 2277.00  4307.1 2274.63  4384.1 2274.19  4567.4 2266.90
  4695.0 2263.42  4783.9 2257.54  4826.1 2256.24  4867.1 2254.85  4924.9 2250.67
  4961.6 2244.89  5013.0 2242.38  5013.5 2241.88  5019.6 2242.38  5076.3 2246.99
  5455.4 2252.68  5686.3 2257.09  5906.3 2257.96  6006.3 2266.44  6076.3 2269.70
  6246.3 2269.29  6396.3 2273.59  6476.3 2276.69  6576.3 2283.11  6586.3 2285.30
  6646.3 2288.07  6666.3 2291.16  6746.3 2295.11  6776.3 2299.54  6812.7 2302.68
#Mann=5,-1,0
  4096.3    0.07       0  4826.1    0.16       0  5013.0    0.07       0
  5019.6    0.16       0  5455.4    0.07       0
Bank Sta=5013,5019.6
Exp/Cntr=0.3,0.1

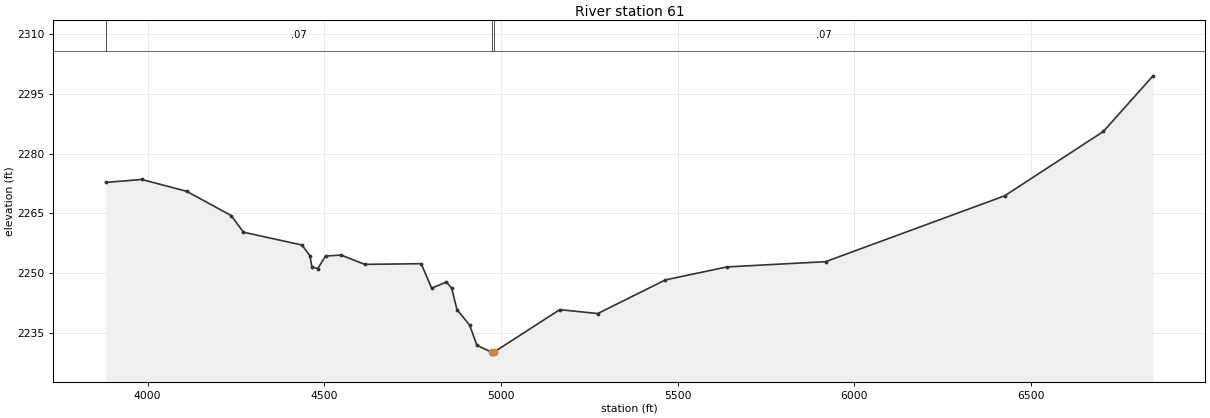
Type RM Length L Ch R = 1,61,0,0,0
BEGIN DESCRIPTION:
WEAVER SPRINGS CREEK TRIB 1_3 1.0
END DESCRIPTION:
XS GIS Cut Line= 5
      1450256.50      6834503.52      1449883.25      6833780.89
      1449716.96      6833541.15      1449362.41      6833780.89
      1447979.12      6834147.34
#Sta/Elev= 30
  3881.4 2272.76  3983.0 2273.50  4110.3 2270.53  4236.5 2264.41  4271.0 2260.24
  4436.9 2257.01  4459.1 2254.32  4464.7 2251.56  4481.2 2251.07  4503.4 2254.24
  4547.7 2254.49  4614.1 2252.15  4774.0 2252.32  4803.7 2246.18  4845.6 2247.70
  4860.4 2246.15  4875.3 2240.80  4911.1 2236.89  4932.0 2231.78  4973.3 2230.08
  4973.8 2229.58  4980.0 2230.08  5166.1 2240.76  5274.0 2239.79  5465.2 2248.24
  5639.4 2251.51  5918.7 2252.83  6425.6 2269.39  6704.9 2285.57  6845.5 2299.56
#Mann=3,-1,0
  3881.4    0.07       0  4973.3    0.07       0  4980.0    0.07       0
Bank Sta=4973.3,4980
Exp/Cntr=0.3,0.1

Chan Stop Cuts=-1