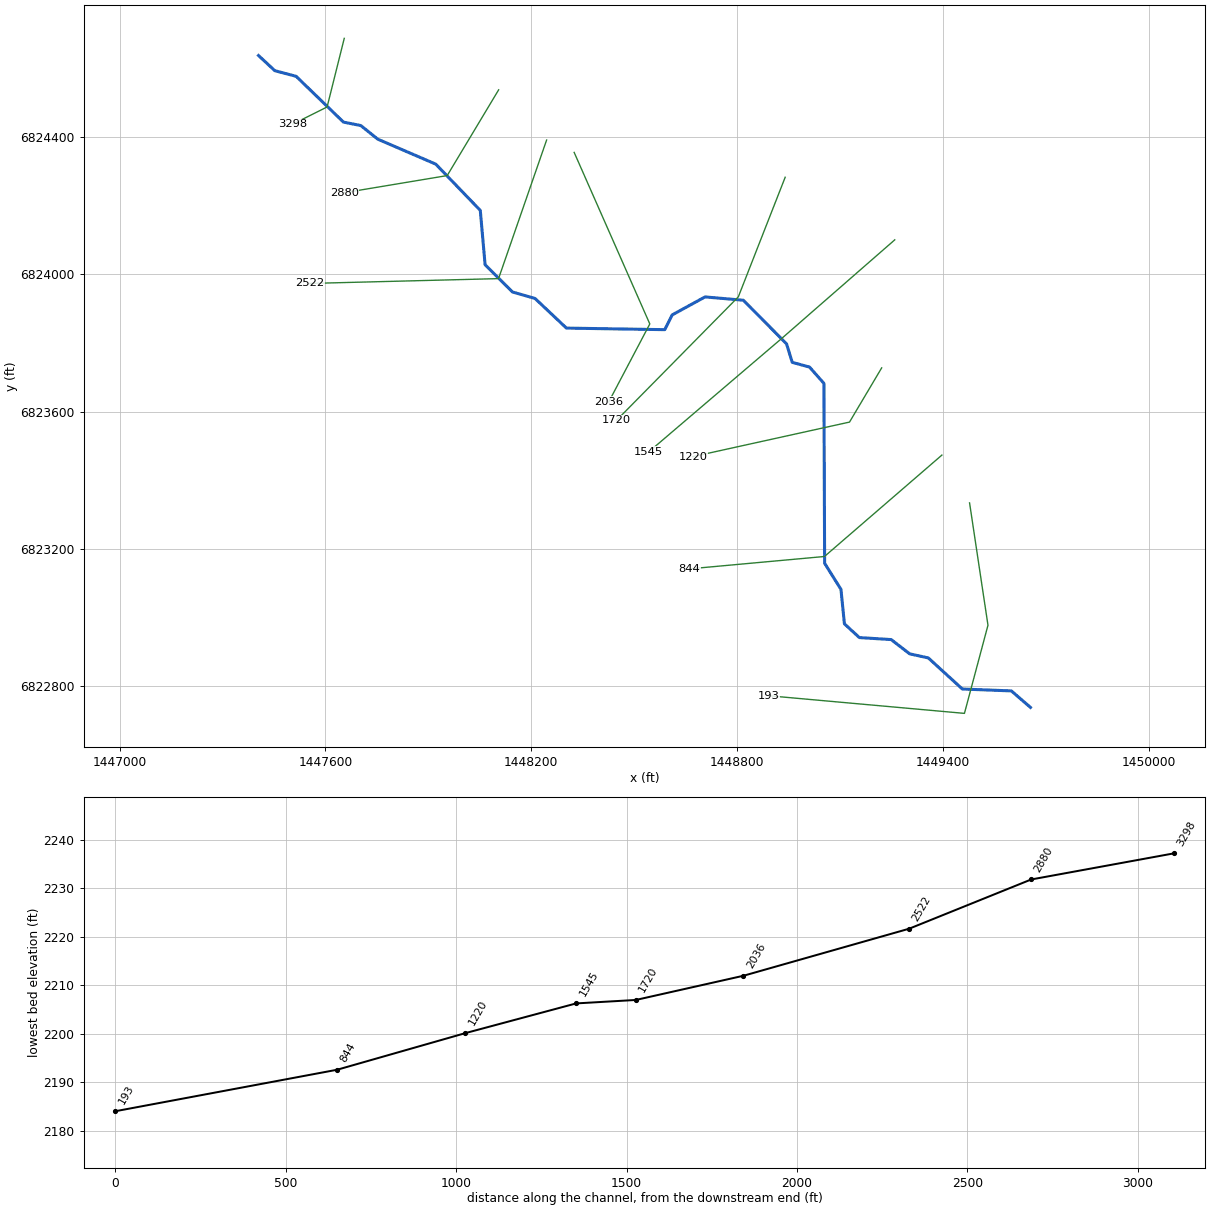
--- WEAVER SPRINGS CREEK TRIB 2.prj (project) ---

Proj Title=WEAVER SPRINGS CREEK TRIB 2 Base Level Engineering
Current Plan=p01
Default Exp/Contr=0.3,0.1
English Units
Geom File=g01
Flow File=f01
Plan File=p01
Y Axis Title=Elevation
X Axis Title(PF)=Main Channel Distance
X Axis Title(XS)=Station
BEGIN DESCRIPTION:
WEAVER SPRINGS CREEK TRIB 2
END DESCRIPTION:
DSS Export Rating Curves= 0
DSS Export Rating Curve Sorted= 0
DSS Export Volume Flow Curves= 0
DXF OffsetX= 0
DXF OffsetY= 0
DXF ScaleX= 1
DXF ScaleY= 10

--- WEAVER SPRINGS CREEK TRIB 2.p01 (plan) ---

Plan Title=Multiple Run
Short Identifier=Multiple
Geom File=g01
Flow File=f01
Subcritical Flow
K Sum by GR= 0
Std Step Tol= 0.01
Critical Tol= 0.01
Num of Std Step Trials= 20
Max Error Tol= 0.3
Flow Tol Ratio= 0.001
Split Flow NTrial= 30
Split Flow Tol= 0.02
Split Flow Ratio= 0.02
Log Output Level= 0
Friction Slope Method= 1
Unsteady Friction Slope Method= 2
Unsteady Bridges Friction Slope Method= 1
Parabolic Critical Depth
Global Vel Dist=  1 , 1 , 1
Global Log Level= 0
CheckData=True
Encroach Param= -1, 0, 0, 0
BEGIN DESCRIPTION:
Multiple Run
END DESCRIPTION:

--- WEAVER SPRINGS CREEK TRIB 2.f01 (steady flow) ---

Flow Title=Multiple
Program Version=4.10
Number of Profiles= 7
Profile Names=10-year,25-year,50-year,1pct_min,100-year,1pct_plu,500-year
River Rch & RM=WEAVER SPRINGS C,Reach-1         ,3298
     582     868    1123     722    1441    2875    2403
Boundary for River Rch & Prof#=WEAVER SPRINGS C,Reach-1         , 1
Up Type= 0
Dn Type= 3
Dn Slope=0.016
Boundary for River Rch & Prof#=WEAVER SPRINGS C,Reach-1         , 2
Up Type= 0
Dn Type= 3
Dn Slope=0.016
Boundary for River Rch & Prof#=WEAVER SPRINGS C,Reach-1         , 3
Up Type= 0
Dn Type= 3
Dn Slope=0.016
Boundary for River Rch & Prof#=WEAVER SPRINGS C,Reach-1         , 4
Up Type= 0
Dn Type= 3
Dn Slope=0.016
Boundary for River Rch & Prof#=WEAVER SPRINGS C,Reach-1         , 5
Up Type= 0
Dn Type= 3
Dn Slope=0.016
Boundary for River Rch & Prof#=WEAVER SPRINGS C,Reach-1         , 6
Up Type= 0
Dn Type= 3
Dn Slope=0.016
Boundary for River Rch & Prof#=WEAVER SPRINGS C,Reach-1         , 7
Up Type= 0
Dn Type= 3
Dn Slope=0.016
DSS Import GetInterval= 0
DSS Import GetPeak= 0
DSS Import FillOption= 0

--- WEAVER SPRINGS CREEK TRIB 2.g01 (geometry) ---

Geom Title=Existing Conditions

River Reach=WEAVER SPRINGS C,Reach-1
Reach XY= 30
      1447405.00      6824638.00      1447452.65      6824593.71
      1447514.71      6824577.30      1447652.70      6824443.83
      1447703.26      6824433.81      1447752.80      6824394.08
      1447921.68      6824321.36      1448051.46      6824186.53
      1448065.47      6824028.18      1448145.30      6823948.77
      1448211.04      6823929.82      1448302.55      6823843.47
      1448589.06      6823838.92      1448610.79      6823881.97
      1448706.56      6823934.34      1448818.30      6823924.66
      1448944.11      6823797.42      1448960.65      6823743.64
      1449011.08      6823729.85      1449053.00      6823682.32
      1449055.07      6823158.03      1449102.64      6823082.02
      1449112.73      6822981.50      1449156.25      6822941.51
      1449249.03      6822935.66      1449302.83      6822894.14
      1449357.29      6822882.15      1449456.47      6822791.55
      1449599.21      6822786.09      1449655.00      6822738.00

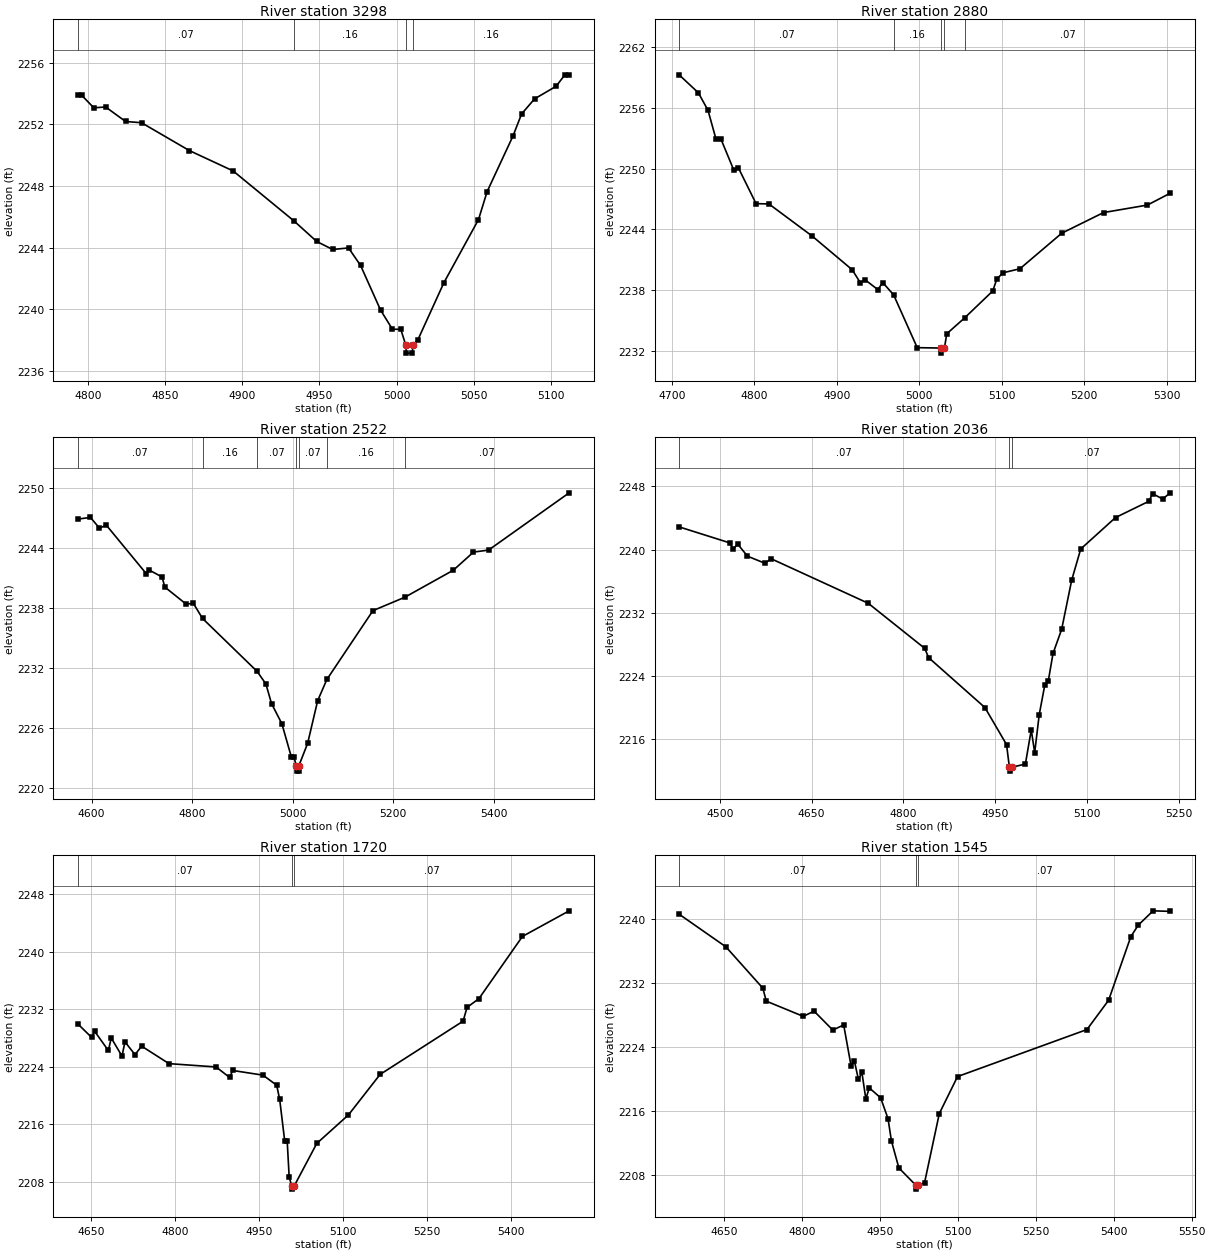
Type RM Length L Ch R = 1,3298,418,418,418
BEGIN DESCRIPTION:
WEAVER SPRINGS CREEK TRIB 2 7.0
END DESCRIPTION:
XS GIS Cut Line= 3
      1447655.00      6824688.01      1447605.00      6824488.00
      1447504.97      6824437.99
#Sta/Elev= 30
  4793.6 2253.88  4796.2 2253.88  4803.9 2253.08  4811.6 2253.13  4824.5 2252.19
  4834.8 2252.11  4865.8 2250.30  4894.1 2248.98  4933.4 2245.74  4948.2 2244.40
  4958.5 2243.88  4968.8 2243.98  4976.6 2242.84  4989.5 2239.95  4997.2 2238.70
  5002.6 2238.70  5005.9 2237.65  5006.2 2237.15  5010.1 2237.15  5010.4 2237.65
  5013.7 2238.02  5030.5 2241.72  5052.9 2245.82  5058.5 2247.64  5075.2 2251.24
  5080.8 2252.68  5089.2 2253.66  5103.2 2254.48  5108.8 2255.22  5111.6 2255.22
#Mann=4,-1,0
  4793.6    0.07       0  4933.4    0.16       0  5005.9    0.07       0
  5010.4    0.16       0
Bank Sta=5005.9,5010.4
Exp/Cntr=0.3,0.1

Type RM Length L Ch R = 1,2880,358,358,358
BEGIN DESCRIPTION:
WEAVER SPRINGS CREEK TRIB 2 6.0
END DESCRIPTION:
XS GIS Cut Line= 3
      1448105.01      6824538.02      1447955.00      6824288.00
      1447655.01      6824238.00
#Sta/Elev= 30
  4708.7 2259.26  4732.0 2257.49  4743.7 2255.76  4753.4 2252.92  4759.3 2252.94
  4774.8 2249.89  4780.6 2250.07  4802.0 2246.54  4817.6 2246.51  4870.0 2243.34
  4918.6 2240.01  4928.4 2238.73  4934.2 2239.02  4949.7 2238.05  4955.6 2238.75
  4968.8 2237.53  4997.4 2232.32  5025.9 2232.28  5026.2 2231.78  5030.4 2232.28
  5033.2 2233.69  5054.9 2235.26  5089.0 2237.92  5094.0 2239.12  5101.7 2239.72
  5121.9 2240.11  5172.6 2243.62  5223.3 2245.66  5276.5 2246.40  5304.4 2247.58
#Mann=5,-1,0
  4708.7    0.07       0  4968.8    0.16       0  5025.9    0.07       0
  5030.4    0.16       0  5054.9    0.07       0
Bank Sta=5025.9,5030.4
Exp/Cntr=0.3,0.1

Type RM Length L Ch R = 1,2522,486,486,486
BEGIN DESCRIPTION:
WEAVER SPRINGS CREEK TRIB 2 5.0
END DESCRIPTION:
XS GIS Cut Line= 3
      1448244.75      6824391.58      1448104.67      6823987.68
      1447554.65      6823973.64
#Sta/Elev= 30
  4572.5 2246.86  4597.5 2247.03  4615.4 2245.96  4629.2 2246.25  4708.8 2241.39
  4714.1 2241.77  4740.0 2241.07  4745.6 2240.06  4788.0 2238.35  4802.2 2238.44
  4820.6 2236.92  4929.4 2231.61  4946.7 2230.36  4957.9 2228.40  4978.5 2226.38
  4997.2 2223.08  5002.3 2223.08  5007.4 2222.14  5007.7 2221.64  5011.7 2221.64
  5012.0 2222.14  5029.7 2224.41  5049.7 2228.69  5068.0 2230.81  5159.7 2237.70
  5223.1 2239.04  5319.8 2241.75  5359.8 2243.56  5389.8 2243.76  5550.2 2249.49
#Mann=7,-1,0
  4572.5    0.07       0  4820.6    0.16       0  4929.4    0.07       0
  5007.4    0.07       0  5012.0    0.07       0  5068.0    0.16       0
  5223.1    0.07       0
Bank Sta=5007.4,5012
Exp/Cntr=0.3,0.1

Type RM Length L Ch R = 1,2036,316,316,316
BEGIN DESCRIPTION:
WEAVER SPRINGS CREEK TRIB 2 4.0
END DESCRIPTION:
XS GIS Cut Line= 3
      1448325.05      6824355.59      1448545.54      6823855.59
      1448425.75      6823628.16
#Sta/Elev= 30
  4433.3 2242.87  4516.3 2240.84  4521.7 2240.04  4529.0 2240.70  4545.1 2239.16
  4573.8 2238.26  4583.7 2238.84  4742.6 2233.20  4835.0 2227.49  4841.3 2226.32
  4933.4 2220.00  4968.8 2215.31  4973.4 2212.45  4973.7 2211.95  4978.1 2212.45
  4999.6 2212.85  5009.2 2217.18  5014.8 2214.28  5022.2 2219.09  5031.2 2222.80
  5036.9 2223.30  5044.8 2226.85  5058.9 2229.90  5075.3 2236.12  5090.1 2240.07
  5147.0 2244.05  5201.8 2246.12  5207.5 2247.09  5223.9 2246.40  5236.8 2247.18
#Mann=3,-1,0
  4433.3    0.07       0  4973.4    0.07       0  4978.1    0.07       0
Bank Sta=4973.4,4978.1
Exp/Cntr=0.3,0.1

Type RM Length L Ch R = 1,1720,175,175,175
BEGIN DESCRIPTION:
WEAVER SPRINGS CREEK TRIB 2 3.0
END DESCRIPTION:
XS GIS Cut Line= 3
      1448940.09      6824283.14      1448803.50      6823934.54
      1448449.35      6823575.38
#Sta/Elev= 30
  4625.6 2229.93  4650.2 2228.06  4655.6 2228.91  4680.1 2226.24  4685.4 2227.97
  4704.5 2225.46  4709.9 2227.44  4727.8 2225.66  4739.7 2226.84  4788.6 2224.41
  4872.7 2223.95  4897.1 2222.49  4902.5 2223.46  4956.7 2222.81  4981.2 2221.41
  4986.6 2219.44  4995.5 2213.71  5000.0 2213.71  5003.6 2208.60  5008.1 2207.46
  5008.5 2206.96  5013.0 2207.46  5053.0 2213.32  5109.6 2217.28  5166.2 2222.91
  5314.7 2230.32  5321.7 2232.23  5343.0 2233.45  5420.8 2242.10  5504.4 2245.66
#Mann=3,-1,0
  4625.6    0.07       0  5008.1    0.07       0  5013.0    0.07       0
Bank Sta=5008.1,5013
Exp/Cntr=0.3,0.1

Type RM Length L Ch R = 1,1545,325,325,325
BEGIN DESCRIPTION:
Mapping XS f2639a01
END DESCRIPTION:
XS GIS Cut Line= 3
      1449259.50      6824100.80      1448933.13      6823816.09
      1448542.67      6823482.90
#Sta/Elev= 30
  4562.7 2240.62  4652.8 2236.54  4724.0 2231.37  4730.6 2229.75  4801.8 2227.85
  4822.7 2228.50  4858.8 2226.13  4879.7 2226.78  4893.9 2221.67  4900.5 2222.22
  4908.1 2219.96  4914.8 2220.83  4922.4 2217.52  4929.0 2218.91  4950.9 2217.66
  4965.1 2215.06  4971.7 2212.27  4986.0 2208.90  5018.5 2206.75  5018.9 2206.25
  5023.6 2206.75  5035.4 2207.03  5063.9 2215.70  5099.0 2220.32  5348.3 2226.20
  5390.0 2229.86  5432.8 2237.81  5447.1 2239.25  5475.7 2241.04  5509.1 2240.97
#Mann=3,-1,0
  4562.7    0.07       0  5018.5    0.07       0  5023.6    0.07       0
Bank Sta=5018.5,5023.6
Exp/Cntr=0.3,0.1

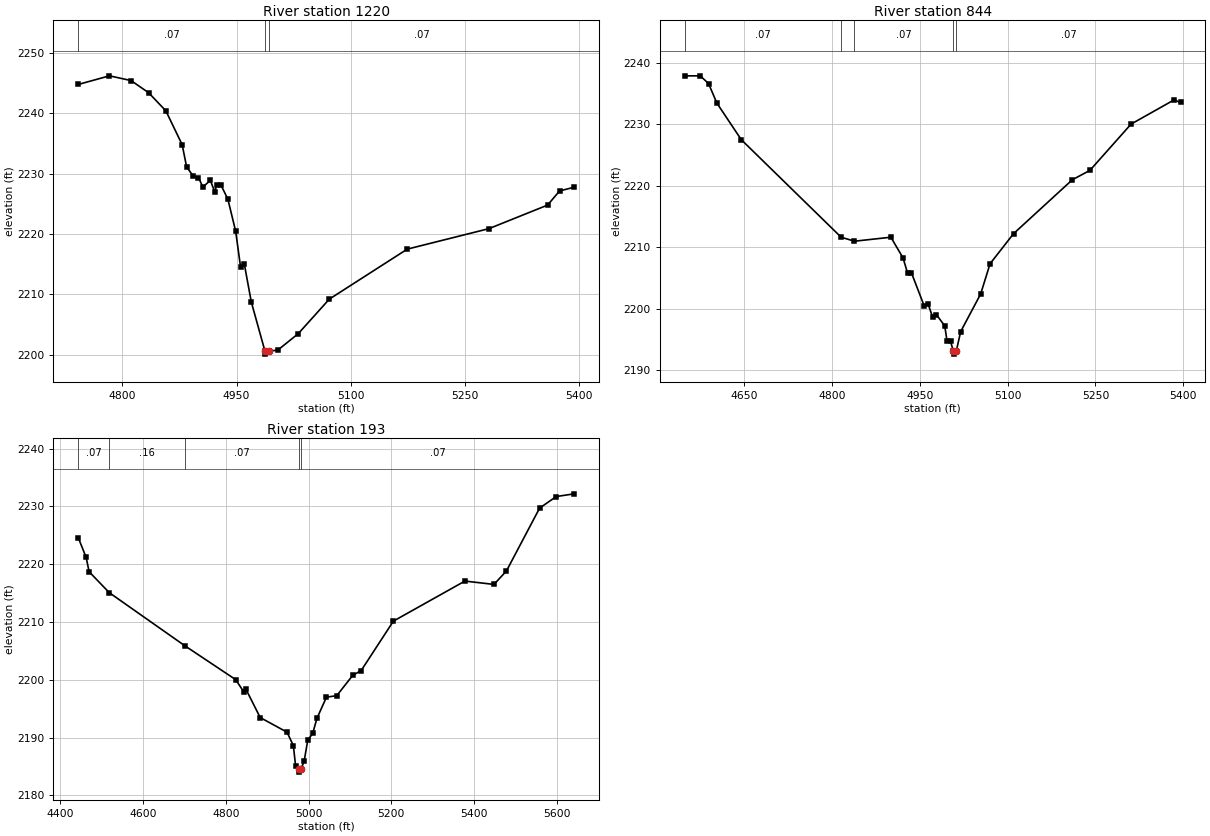
Type RM Length L Ch R = 1,1220,376,376,376
BEGIN DESCRIPTION:
Mapping XS 6ac083cf
END DESCRIPTION:
XS GIS Cut Line= 3
      1449221.33      6823727.56      1449127.57      6823569.56
      1448670.97      6823468.86
#Sta/Elev= 30
  4742.0 2244.76  4783.0 2246.19  4811.3 2245.41  4834.5 2243.39  4857.1 2240.39
  4878.5 2234.79  4884.3 2231.14  4892.7 2229.64  4899.9 2229.36  4905.7 2227.79
  4915.5 2228.88  4921.3 2226.98  4923.7 2228.08  4929.6 2228.08  4938.6 2225.74
  4948.8 2220.43  4955.1 2214.62  4960.2 2214.98  4969.3 2208.75  4987.2 2200.63
  4987.6 2200.13  4992.3 2200.63  5003.9 2200.78  5030.8 2203.50  5071.7 2209.23
  5174.1 2217.51  5281.4 2220.90  5358.4 2224.80  5374.0 2227.13  5393.3 2227.76
#Mann=3,-1,0
  4742.0    0.07       0  4987.2    0.07       0  4992.3    0.07       0
Bank Sta=4987.2,4992.3
Exp/Cntr=0.3,0.1

Type RM Length L Ch R = 1,844,651,651,651
BEGIN DESCRIPTION:
WEAVER SPRINGS CREEK TRIB 2 2.0
END DESCRIPTION:
XS GIS Cut Line= 3
      1449396.81      6823473.35      1449054.55      6823177.81
      1448660.69      6823141.78
#Sta/Elev= 30
  4547.8 2237.88  4574.5 2237.89  4588.7 2236.63  4603.0 2233.44  4644.7 2227.49
  4815.3 2211.62  4838.1 2210.97  4900.3 2211.62  4921.1 2208.25  4928.8 2205.80
  4935.4 2205.84  4957.3 2200.42  4963.9 2200.77  4971.6 2198.62  4978.2 2199.02
  4992.4 2197.17  4996.4 2194.68  5002.3 2194.68  5007.0 2193.09  5007.4 2192.59
  5012.1 2193.09  5019.6 2196.26  5053.8 2202.39  5069.8 2207.30  5110.0 2212.20
  5210.4 2220.97  5240.5 2222.50  5310.8 2230.03  5384.1 2233.96  5395.5 2233.55
#Mann=5,-1,0
  4547.8    0.07       0  4815.3    0.16       0  4838.1    0.07       0
  5007.0    0.07       0  5012.1    0.07       0
Bank Sta=5007,5012.1
Exp/Cntr=0.3,0.1

Type RM Length L Ch R = 1,193,0,0,0
BEGIN DESCRIPTION:
WEAVER SPRINGS CREEK TRIB 2 1.0
END DESCRIPTION:
XS GIS Cut Line= 4
      1449477.47      6823334.16      1449531.12      6822977.52
      1449462.55      6822720.58      1448891.64      6822771.99
#Sta/Elev= 30
  4442.9 2224.62  4462.1 2221.17  4469.3 2218.70  4518.1 2215.08  4701.2 2205.88
  4823.8 2200.04  4843.0 2197.96  4848.2 2198.44  4883.1 2193.48  4948.0 2190.95
  4963.3 2188.63  4968.7 2185.16  4976.4 2184.54  4976.8 2184.04  4981.6 2184.54
  4989.4 2185.93  4998.2 2189.58  5010.1 2190.74  5020.4 2193.35  5043.4 2197.01
  5068.2 2197.26  5107.2 2200.80  5127.3 2201.60  5205.3 2210.16  5378.3 2217.09
  5448.6 2216.51  5478.7 2218.83  5559.0 2229.71  5599.2 2231.71  5642.7 2232.18
#Mann=5,-1,0
  4442.9    0.07       0  4518.1    0.16       0  4701.2    0.07       0
  4976.4    0.07       0  4981.6    0.07       0
Bank Sta=4976.4,4981.6
Exp/Cntr=0.3,0.1

Chan Stop Cuts=-1