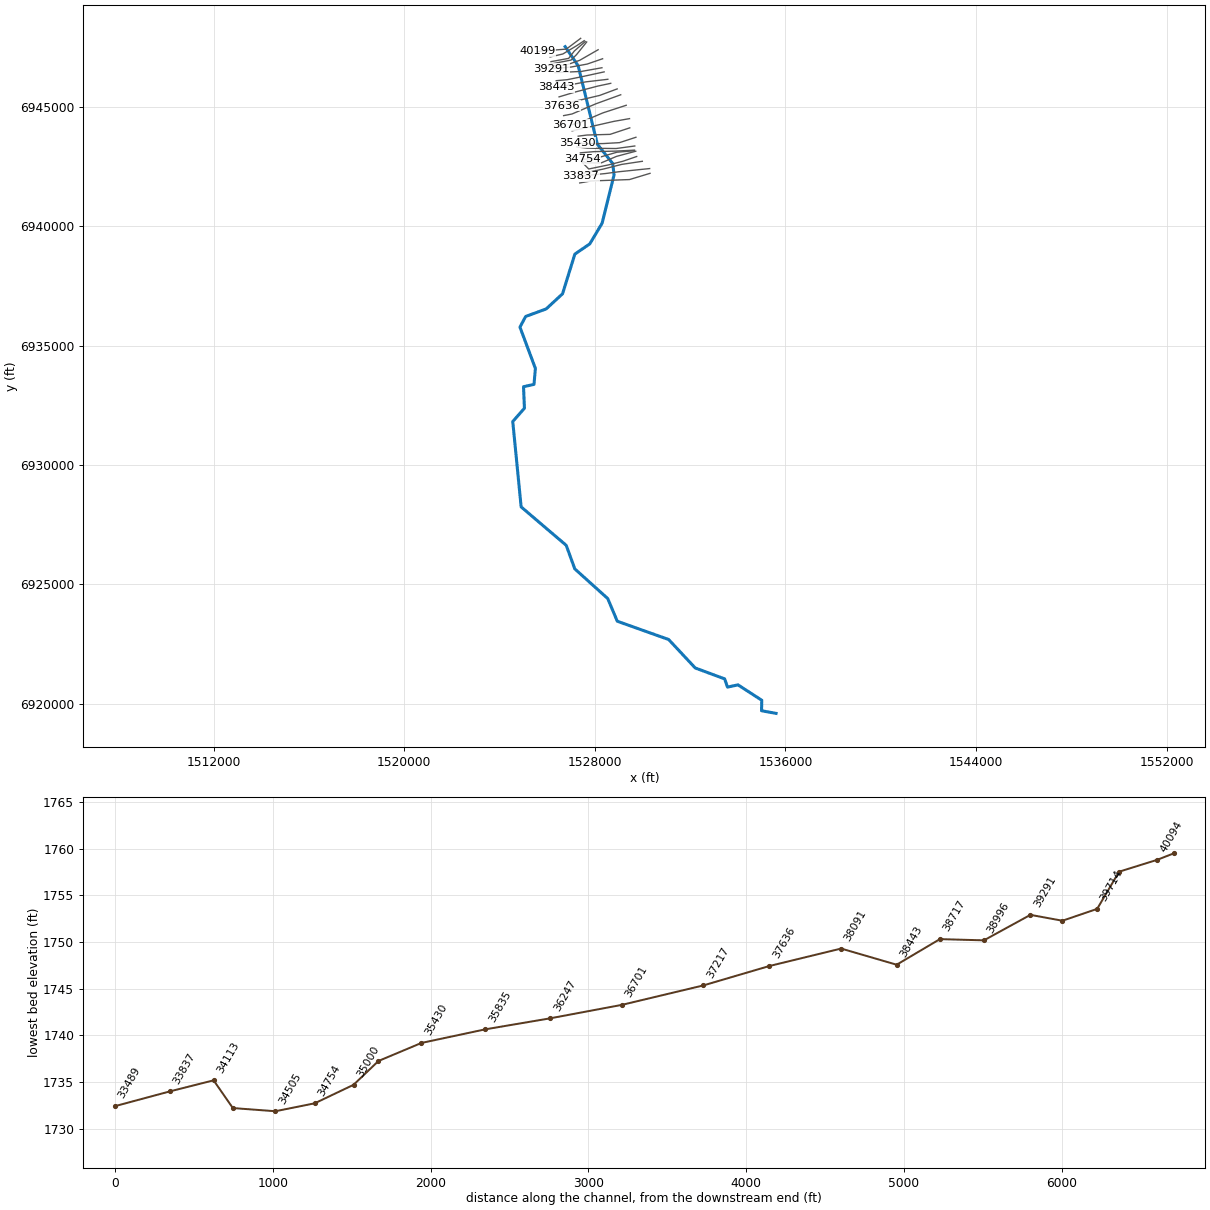
--- Dark Hollow Branch.prj (project) ---

Proj Title=Dark Hollow Branch Base Level Engineering
Current Plan=p01
Default Exp/Contr=0.3,0.1
English Units
Geom File=g01
Flow File=f01
Plan File=p01
Y Axis Title=Elevation
X Axis Title(PF)=Main Channel Distance
X Axis Title(XS)=Station
BEGIN DESCRIPTION:
Dark Hollow Branch
END DESCRIPTION:
DSS Export Rating Curves= 0
DSS Export Rating Curve Sorted= 0
DSS Export Volume Flow Curves= 0
DXF OffsetX= 0
DXF OffsetY= 0
DXF ScaleX= 1
DXF ScaleY= 10

--- Dark Hollow Branch.p01 (plan) ---

Plan Title=Multiple Run
Short Identifier=Multiple
Geom File=g01
Flow File=f01
Subcritical Flow
K Sum by GR= 0
Std Step Tol= 0.01
Critical Tol= 0.01
Num of Std Step Trials= 20
Max Error Tol= 0.3
Flow Tol Ratio= 0.001
Split Flow NTrial= 30
Split Flow Tol= 0.02
Split Flow Ratio= 0.02
Log Output Level= 0
Friction Slope Method= 1
Unsteady Friction Slope Method= 2
Unsteady Bridges Friction Slope Method= 1
Parabolic Critical Depth
Global Vel Dist=  1 , 1 , 1
Global Log Level= 0
CheckData=True
Encroach Param= -1, 0, 0, 0
BEGIN DESCRIPTION:
Multiple Run
END DESCRIPTION:

--- Dark Hollow Branch.f01 (steady flow) ---

Flow Title=Multiple
Program Version=4.10
Number of Profiles= 7
Profile Names=10-year,25-year,50-year,1pct_min,100-year,1pct_plu,500-year
River Rch & RM=Dark Hollow Bran,Reach-1         ,40199
     236     322     391     237     472     942     697
River Rch & RM=Dark Hollow Bran,Reach-1         ,39853
     324     452     559     343     685    1367    1044
River Rch & RM=Dark Hollow Bran,Reach-1         ,35158
     411     578     717     443     883    1763    1358
River Rch & RM=Dark Hollow Bran,Reach-1         ,33837
     482     684     855     531    1059    2112    1645
River Rch & RM=Dark Hollow Bran,Reach-1         ,32772
     515     736     923     575    1147    2288    1797
River Rch & RM=Dark Hollow Bran,Reach-1         ,32056
     629     905    1140     712    1422    2836    2243
River Rch & RM=Dark Hollow Bran,Reach-1         ,31314
     629     905    1140     712    1422    2836    2243
River Rch & RM=Dark Hollow Bran,Reach-1         ,28852
     757    1098    1391     874    1744    3480    2780
River Rch & RM=Dark Hollow Bran,Reach-1         ,27133
     757    1098    1391     874    1744    3480    2780
River Rch & RM=Dark Hollow Bran,Reach-1         ,24972
     825    1199    1522     958    1911    3813    3056
River Rch & RM=Dark Hollow Bran,Reach-1         ,23589
     955    1393    1772    1116    2227    4443    3570
River Rch & RM=Dark Hollow Bran,Reach-1         ,23107
     955    1393    1772    1116    2227    4443    3570
River Rch & RM=Dark Hollow Bran,Reach-1         ,17521
    1085    1588    2025    1279    2552    5092    4111
River Rch & RM=Dark Hollow Bran,Reach-1         ,15493
    1085    1588    2025    1279    2552    5092    4111
River Rch & RM=Dark Hollow Bran,Reach-1         ,11039
    1083    1582    2014    1270    2534    5057    4069
River Rch & RM=Dark Hollow Bran,Reach-1         ,8398
    1125    1646    2097    1323    2640    5267    4243
River Rch & RM=Dark Hollow Bran,Reach-1         ,6703
    1131    1652    2103    1326    2645    5278    4244
River Rch & RM=Dark Hollow Bran,Reach-1         ,4782
    1179    1724    2196    1385    2764    5514    4440
River Rch & RM=Dark Hollow Bran,Reach-1         ,3883
    1172    1711    2178    1372    2738    5464    4390
River Rch & RM=Dark Hollow Bran,Reach-1         ,918
    1262    1849    2358    1488    2969    5925    4777
Boundary for River Rch & Prof#=Dark Hollow Bran,Reach-1         , 1
Up Type= 0
Dn Type= 3
Dn Slope=0.001
Boundary for River Rch & Prof#=Dark Hollow Bran,Reach-1         , 2
Up Type= 0
Dn Type= 3
Dn Slope=0.001
Boundary for River Rch & Prof#=Dark Hollow Bran,Reach-1         , 3
Up Type= 0
Dn Type= 3
Dn Slope=0.001
Boundary for River Rch & Prof#=Dark Hollow Bran,Reach-1         , 4
Up Type= 0
Dn Type= 3
Dn Slope=0.001
Boundary for River Rch & Prof#=Dark Hollow Bran,Reach-1         , 5
Up Type= 0
Dn Type= 3
Dn Slope=0.001
Boundary for River Rch & Prof#=Dark Hollow Bran,Reach-1         , 6
Up Type= 0
Dn Type= 3
Dn Slope=0.001
Boundary for River Rch & Prof#=Dark Hollow Bran,Reach-1         , 7
Up Type= 0
Dn Type= 3
Dn Slope=0.001
DSS Import GetInterval= 0
DSS Import GetPeak= 0
DSS Import FillOption= 0

--- Dark Hollow Branch.g01 (geometry) ---

Geom Title=Existing Conditions

River Reach=Dark Hollow Bran,Reach-1
Reach XY= 30
      1526755.00      6947538.00      1527301.33      6946736.41
      1528107.25      6943443.93      1528749.27      6942640.55
      1528805.09      6942158.10      1528305.00      6940138.00
      1527788.36      6939271.32      1527160.36      6938840.70
      1526643.91      6937177.63      1525957.45      6936543.46
      1525095.32      6936227.24      1524856.80      6935781.89
      1525505.46      6934048.19      1525446.86      6933381.91
      1525007.06      6933282.17      1525045.71      6932381.33
      1524555.31      6931822.96      1524907.22      6928243.92
      1526799.38      6926632.38      1527158.16      6925646.34
      1528541.37      6924401.21      1528941.27      6923451.20
      1531096.66      6922684.84      1532213.30      6921491.07
      1533446.54      6921034.50      1533566.49      6920689.47
      1534007.31      6920782.92      1535005.00      6920138.00
      1534994.76      6919698.34      1535605.00      6919588.00

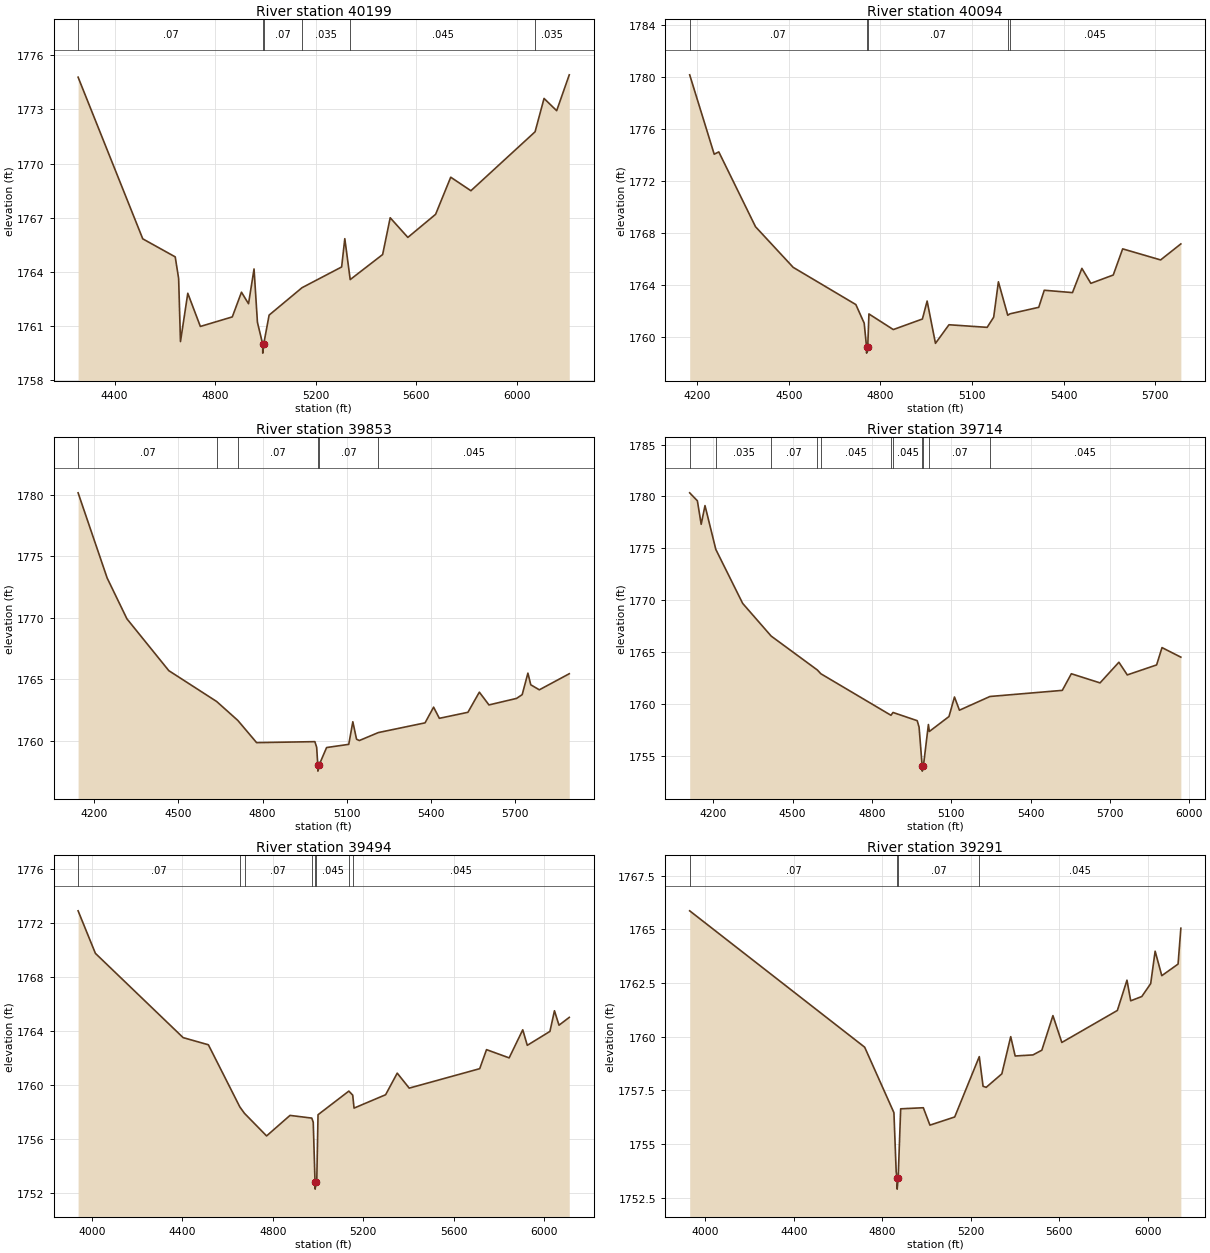
Type RM Length L Ch R = 1,40199,105,105,105
BEGIN DESCRIPTION:
Dark Hollow Branch 48.0
END DESCRIPTION:
XS GIS Cut Line= 3
      1527404.99      6947887.99      1526805.00      6947438.00
      1525605.05      6947338.00
#Sta/Elev= 30
  4254.6 1774.79  4511.9 1765.82  4641.0 1764.82  4654.6 1763.62  4661.9 1760.12
  4691.0 1762.80  4741.0 1760.96  4868.1 1761.49  4904.6 1762.86  4932.7 1762.22
  4954.6 1764.15  4968.1 1761.19  4989.0 1759.98  4989.3 1759.48  4993.0 1759.98
  5014.6 1761.59  5145.5 1763.11  5303.1 1764.26  5315.7 1765.83  5337.2 1763.56
  5466.2 1764.95  5496.3 1766.99  5566.5 1765.90  5676.9 1767.18  5737.1 1769.24
  5817.4 1768.49  6072.7 1771.76  6108.4 1773.61  6158.6 1772.93  6208.7 1774.92
#Mann=6,-1,0
  4254.6    0.07       0  4989.0    0.07       0  4993.0    0.07       0
  5145.5   0.035       0  5337.2   0.045       0  6072.7   0.035       0
Bank Sta=4989,4993
Exp/Cntr=0.3,0.1

Type RM Length L Ch R = 1,40094,241,241,241
BEGIN DESCRIPTION:
Mapping XS b409fe57
END DESCRIPTION:
XS GIS Cut Line= 4
      1527554.33      6947789.20      1527248.81      6947586.09
      1526656.79      6947231.92      1526119.34      6947107.10
#Sta/Elev= 30
  4175.7 1780.17  4256.0 1774.07  4271.0 1774.25  4391.3 1768.50  4514.6 1765.38
  4719.9 1762.52  4747.2 1761.09  4754.8 1759.29  4755.0 1758.79  4758.8 1759.29
  4762.7 1761.80  4842.5 1760.60  4937.8 1761.41  4953.3 1762.79  4980.6 1759.54
  5024.8 1760.97  5149.8 1760.77  5171.2 1761.55  5186.7 1764.27  5217.3 1761.70
  5224.7 1761.81  5318.8 1762.31  5336.9 1763.62  5429.3 1763.44  5460.1 1765.30
  5489.4 1764.15  5562.8 1764.79  5593.6 1766.80  5717.9 1765.95  5784.2 1767.18
#Mann=5,-1,0
  4175.7    0.07       0  4754.8    0.07       0  4758.8    0.07       0
  5217.3   0.035       0  5224.7   0.045       0
Bank Sta=4754.8,4758.8
Exp/Cntr=0.3,0.1

Type RM Length L Ch R = 1,39853,139,139,139
BEGIN DESCRIPTION:
Mapping XS 0a3719b9
END DESCRIPTION:
XS GIS Cut Line= 4
      1527596.01      6947752.75      1527139.43      6947356.92
      1526901.58      6947047.90      1526160.29      6946910.75
#Sta/Elev= 30
  4143.7 1780.18  4247.2 1773.24  4317.5 1769.92  4466.6 1765.70  4636.8 1763.19
  4712.1 1761.65  4779.0 1759.84  4986.4 1759.92  4992.8 1759.46  4996.8 1758.02
  4997.1 1757.52  5001.5 1758.02  5028.1 1759.44  5107.0 1759.70  5121.5 1761.54
  5134.7 1760.12  5144.6 1760.01  5212.4 1760.66  5378.5 1761.45  5409.0 1762.73
  5429.4 1761.82  5531.1 1762.31  5571.8 1763.95  5606.0 1762.91  5704.0 1763.44
  5724.3 1763.75  5744.6 1765.50  5754.8 1764.55  5785.3 1764.14  5891.8 1765.45
#Mann=6,-1,0
  4143.7    0.07       0  4636.8    0.16       0  4712.1    0.07       0
  4996.8    0.07       0  5001.5    0.07       0  5212.4   0.045       0
Bank Sta=4996.8,5001.5
Exp/Cntr=0.3,0.1

Type RM Length L Ch R = 1,39714,220,220,220
BEGIN DESCRIPTION:
Mapping XS c6e8e386
END DESCRIPTION:
XS GIS Cut Line= 4
      1527658.11      6947735.85      1527232.75      6947206.32
      1527000.54      6946976.28      1526165.02      6946813.52
#Sta/Elev= 30
  4111.2 1780.35  4140.3 1779.58  4154.7 1777.32  4169.1 1779.12  4210.0 1774.90
  4311.5 1769.70  4419.3 1766.55  4594.1 1763.28  4607.2 1762.92  4872.3 1758.92
  4880.1 1759.19  4971.5 1758.40  4978.6 1757.78  4990.3 1754.04  4990.6 1753.54
  4995.0 1754.04  5013.9 1758.03  5017.5 1757.36  5091.7 1758.80  5112.5 1760.68
  5131.2 1759.41  5246.5 1760.73  5520.2 1761.32  5554.4 1762.92  5662.9 1762.04
  5734.2 1764.03  5765.9 1762.81  5876.8 1763.77  5897.2 1765.44  5968.5 1764.52
#Mann=11,-1,0
  4111.2    0.07       0  4210.0   0.035       0  4419.3    0.07       0
  4594.1    0.16       0  4607.2   0.045       0  4872.3    0.07       0
  4880.1   0.045       0  4990.3   0.045       0  4995.0   0.045       0
  5017.5    0.07       0  5246.5   0.045       0
Bank Sta=4990.3,4995
Exp/Cntr=0.3,0.1

Type RM Length L Ch R = 1,39494,203,203,203
BEGIN DESCRIPTION:
Mapping XS 1c943ff1
END DESCRIPTION:
XS GIS Cut Line= 4
      1528137.68      6947410.30      1527365.12      6946967.60
      1526805.23      6946770.12      1526119.71      6946739.75
#Sta/Elev= 30
  3939.9 1772.88  4016.4 1769.73  4404.0 1763.49  4515.6 1762.96  4654.5 1758.36
  4675.2 1757.88  4772.8 1756.21  4876.2 1757.73  4972.4 1757.53  4978.9 1757.23
  4986.9 1752.77  4987.3 1752.27  4991.7 1752.77  4994.6 1752.95  5000.1 1757.78
  5136.3 1759.53  5153.4 1759.23  5159.2 1758.27  5298.7 1759.26  5350.0 1760.86
  5403.0 1759.75  5714.5 1761.19  5744.6 1762.60  5844.6 1761.99  5904.7 1764.07
  5924.7 1762.92  6024.8 1763.95  6044.8 1765.48  6064.9 1764.41  6110.2 1764.99
#Mann=8,-1,0
  3939.9    0.07       0  4654.5    0.16       0  4675.2    0.07       0
  4972.4   0.045       0  4986.9   0.045       0  4991.7   0.045       0
  5136.3    0.07       0  5153.4   0.045       0
Bank Sta=4986.9,4991.7
Exp/Cntr=0.3,0.1

Type RM Length L Ch R = 1,39291,295,295,295
BEGIN DESCRIPTION:
Mapping XS 1949f1d1
END DESCRIPTION:
XS GIS Cut Line= 4
      1528326.48      6947032.70      1527677.62      6946809.18
      1527007.05      6946685.48      1526159.22      6946611.76
#Sta/Elev= 30
  3929.5 1765.86  4720.1 1759.51  4852.3 1756.46  4862.5 1753.71  4866.6 1753.40
  4866.9 1752.90  4871.4 1753.40  4882.8 1756.64  4985.1 1756.69  5015.0 1755.88
  5126.9 1756.26  5237.9 1759.07  5255.1 1757.69  5269.2 1757.64  5339.9 1758.27
  5380.0 1760.00  5400.1 1759.10  5480.4 1759.15  5520.6 1759.37  5570.7 1760.98
  5610.9 1759.73  5861.8 1761.22  5905.3 1762.63  5922.1 1761.67  5972.3 1761.87
  6012.4 1762.47  6032.5 1763.98  6062.6 1762.84  6136.1 1763.38  6148.7 1765.05
#Mann=4,-1,0
  3929.5    0.07       0  4866.6    0.07       0  4871.4    0.07       0
  5237.9   0.045       0
Bank Sta=4866.6,4871.4
Exp/Cntr=0.3,0.1

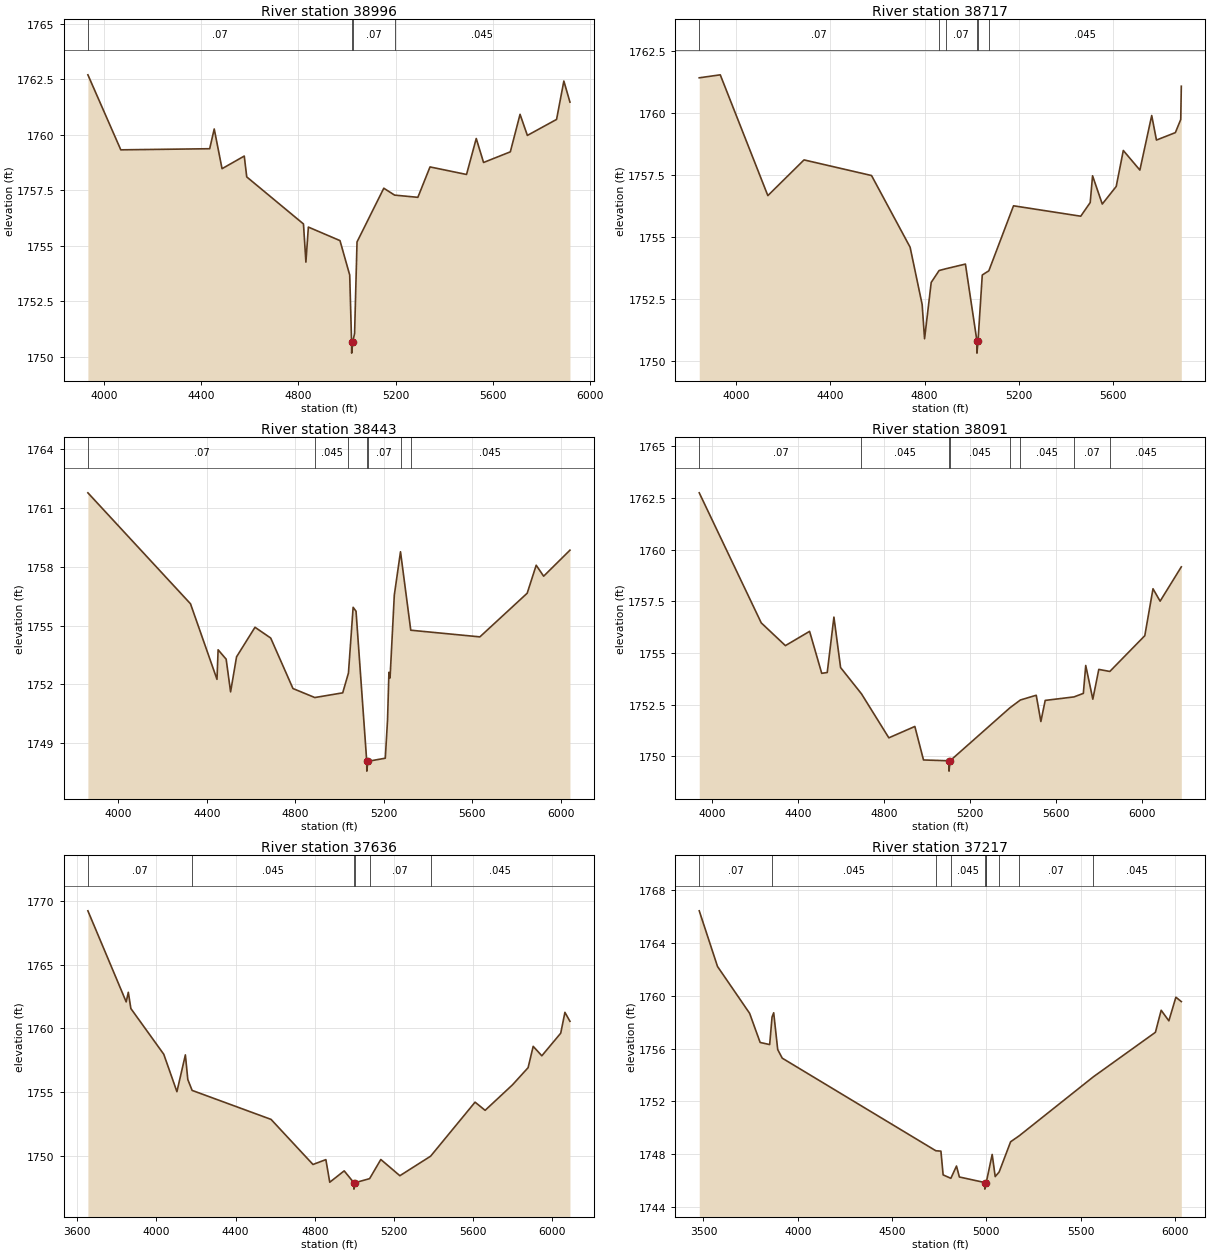
Type RM Length L Ch R = 1,38996,279,279,279
BEGIN DESCRIPTION:
Mapping XS 5144e35e
END DESCRIPTION:
XS GIS Cut Line= 3
      1528298.26      6946655.10      1527436.74      6946501.02
      1526329.95      6946448.94
#Sta/Elev= 30
  3934.0 1762.71  4069.4 1759.33  4435.1 1759.38  4453.7 1760.27  4485.9 1758.48
  4577.3 1759.05  4587.5 1758.11  4820.9 1755.99  4830.9 1754.27  4841.0 1755.85
  4971.1 1755.24  5011.1 1753.69  5018.8 1750.67  5019.1 1750.17  5023.6 1750.67
  5031.2 1751.06  5041.2 1755.18  5151.3 1757.60  5195.7 1757.29  5291.5 1757.19
  5341.5 1758.56  5491.7 1758.22  5531.7 1759.84  5561.8 1758.76  5671.9 1759.24
  5711.9 1760.93  5742.0 1759.98  5862.1 1760.70  5892.1 1762.43  5917.2 1761.48
#Mann=4,-1,0
  3934.0    0.07       0  5018.8    0.07       0  5023.6    0.07       0
  5195.7   0.045       0
Bank Sta=5018.8,5023.6
Exp/Cntr=0.3,0.1

Type RM Length L Ch R = 1,38717,274,274,274
BEGIN DESCRIPTION:
Mapping XS a1da0813
END DESCRIPTION:
XS GIS Cut Line= 4
      1528389.41      6946481.49      1527532.23      6946294.86
      1526837.78      6946153.80      1526379.92      6946112.57
#Sta/Elev= 30
  3843.8 1761.40  3933.0 1761.52  4134.9 1756.65  4288.4 1758.09  4574.9 1757.46
  4738.6 1754.57  4789.7 1752.26  4799.9 1750.88  4828.1 1753.15  4861.6 1753.63
  4889.5 1753.70  4973.3 1753.89  5022.0 1750.80  5022.3 1750.30  5026.8 1750.80
  5044.8 1753.45  5072.7 1753.62  5177.4 1756.24  5462.6 1755.82  5502.8 1756.37
  5512.8 1757.45  5554.0 1756.31  5613.2 1757.02  5643.3 1758.47  5713.6 1757.68
  5763.8 1759.88  5783.9 1758.89  5864.2 1759.19  5887.0 1759.72  5889.4 1761.06
#Mann=6,-1,0
  3843.8    0.07       0  4861.6   0.045       0  4889.5    0.07       0
  5022.0    0.07       0  5026.8    0.07       0  5072.7   0.045       0
Bank Sta=5022,5026.8
Exp/Cntr=0.3,0.1

Type RM Length L Ch R = 1,38443,352,352,352
BEGIN DESCRIPTION:
Mapping XS e3862cce
END DESCRIPTION:
XS GIS Cut Line= 3
      1528545.69      6946171.16      1527616.86      6946062.65
      1526395.07      6945830.45
#Sta/Elev= 30
  3862.6 1761.78  4326.4 1756.11  4446.1 1752.25  4451.2 1753.76  4487.5 1753.28
  4507.6 1751.61  4534.5 1753.40  4617.9 1754.91  4688.9 1754.36  4789.5 1751.78
  4888.2 1751.32  5014.3 1751.56  5040.2 1752.57  5061.4 1755.93  5074.5 1755.73
  5122.9 1748.06  5123.3 1747.56  5127.8 1748.06  5206.8 1748.22  5217.0 1750.19
  5223.2 1752.61  5228.3 1752.32  5247.5 1756.55  5275.5 1758.77  5321.9 1754.76
  5634.3 1754.42  5848.1 1756.65  5888.8 1758.08  5922.5 1757.52  6041.4 1758.85
#Mann=7,-1,0
  3862.6    0.07       0  4888.2   0.045       0  5040.2    0.07       0
  5122.9   0.045       0  5127.8    0.07       0  5275.5   0.035       0
  5321.9   0.045       0
Bank Sta=5122.9,5127.8
Exp/Cntr=0.3,0.1

Type RM Length L Ch R = 1,38091,455,455,455
BEGIN DESCRIPTION:
Mapping XS 1cf17d43
END DESCRIPTION:
XS GIS Cut Line= 4
      1528667.16      6946001.88      1528115.99      6945884.70
      1527176.32      6945637.31      1526498.51      6945433.75
#Sta/Elev= 30
  3939.6 1762.75  4228.1 1756.46  4340.5 1755.36  4453.0 1756.05  4509.5 1754.02
  4535.1 1754.06  4566.2 1756.74  4597.2 1754.30  4694.3 1753.03  4821.7 1750.90
  4942.7 1751.45  4983.0 1749.83  5101.3 1749.79  5101.7 1749.29  5106.6 1749.79
  5384.7 1752.35  5433.7 1752.73  5507.5 1752.96  5529.1 1751.69  5549.2 1752.71
  5683.4 1752.88  5726.7 1753.05  5737.8 1754.40  5770.8 1752.77  5798.6 1754.21
  5849.8 1754.11  6012.6 1755.84  6050.8 1758.11  6083.9 1757.51  6182.5 1759.17
#Mann=8,-1,0
  3939.6    0.07       0  4694.3   0.045       0  5101.3   0.045       0
  5106.6   0.045       0  5384.7   0.035       0  5433.7   0.045       0
  5683.4    0.07       0  5849.8   0.045       0
Bank Sta=5101.3,5106.6
Exp/Cntr=0.3,0.1

Type RM Length L Ch R = 1,37636,419,419,419
BEGIN DESCRIPTION:
Mapping XS 0cb87176
END DESCRIPTION:
XS GIS Cut Line= 4
      1528936.32      6945767.52      1528200.63      6945494.08
      1527096.03      6945233.66      1526611.06      6945062.62
#Sta/Elev= 30
  3654.2 1769.21  3847.6 1762.08  3858.3 1762.83  3871.2 1761.56  4037.3 1757.98
  4103.7 1755.05  4146.4 1757.93  4158.7 1756.00  4180.5 1755.15  4579.0 1752.88
  4790.7 1749.35  4855.8 1749.73  4875.4 1747.96  4948.3 1748.85  4997.0 1747.92
  4997.4 1747.42  5002.4 1747.92  5076.6 1748.24  5133.2 1749.74  5229.5 1748.47
  5384.7 1750.00  5609.1 1754.23  5659.9 1753.59  5797.7 1755.58  5876.9 1756.93
  5902.6 1758.60  5946.2 1757.86  6041.6 1759.63  6062.8 1761.26  6088.2 1760.56
#Mann=6,-1,0
  3654.2    0.07       0  4180.5   0.045       0  4997.0   0.045       0
  5002.4   0.045       0  5076.6    0.07       0  5384.7   0.045       0
Bank Sta=4997,5002.4
Exp/Cntr=0.3,0.1

Type RM Length L Ch R = 1,37217,516,516,516
BEGIN DESCRIPTION:
Mapping XS 06c4c544
END DESCRIPTION:
XS GIS Cut Line= 4
      1529086.09      6945522.31      1528046.55      6945144.69
      1527043.94      6944717.17      1526690.24      6944647.73
#Sta/Elev= 30
  3477.6 1766.44  3574.5 1762.22  3744.7 1758.67  3800.5 1756.46  3851.1 1756.30
  3863.7 1758.39  3872.4 1758.71  3893.7 1755.92  3917.6 1755.27  4732.1 1748.25
  4759.2 1748.22  4770.9 1746.42  4811.9 1746.16  4841.8 1747.09  4857.1 1746.26
  4991.5 1745.84  4992.0 1745.34  4997.3 1745.84  5000.0 1745.87  5031.0 1747.97
  5047.1 1746.29  5068.0 1746.64  5128.8 1748.93  5175.0 1749.39  5567.1 1753.85
  5896.7 1757.23  5927.2 1758.90  5968.0 1758.10  6005.2 1759.89  6034.0 1759.56
#Mann=10,-1,0
  3477.6    0.07       0  3863.7   0.045       0  4732.1    0.07       0
  4811.9   0.045       0  4991.5    0.07       0  4997.3   0.045       0
  5000.0    0.07       0  5068.0   0.045       0  5175.0    0.07       0
  5567.1   0.045       0
Bank Sta=4991.5,4997.3
Exp/Cntr=0.3,0.1

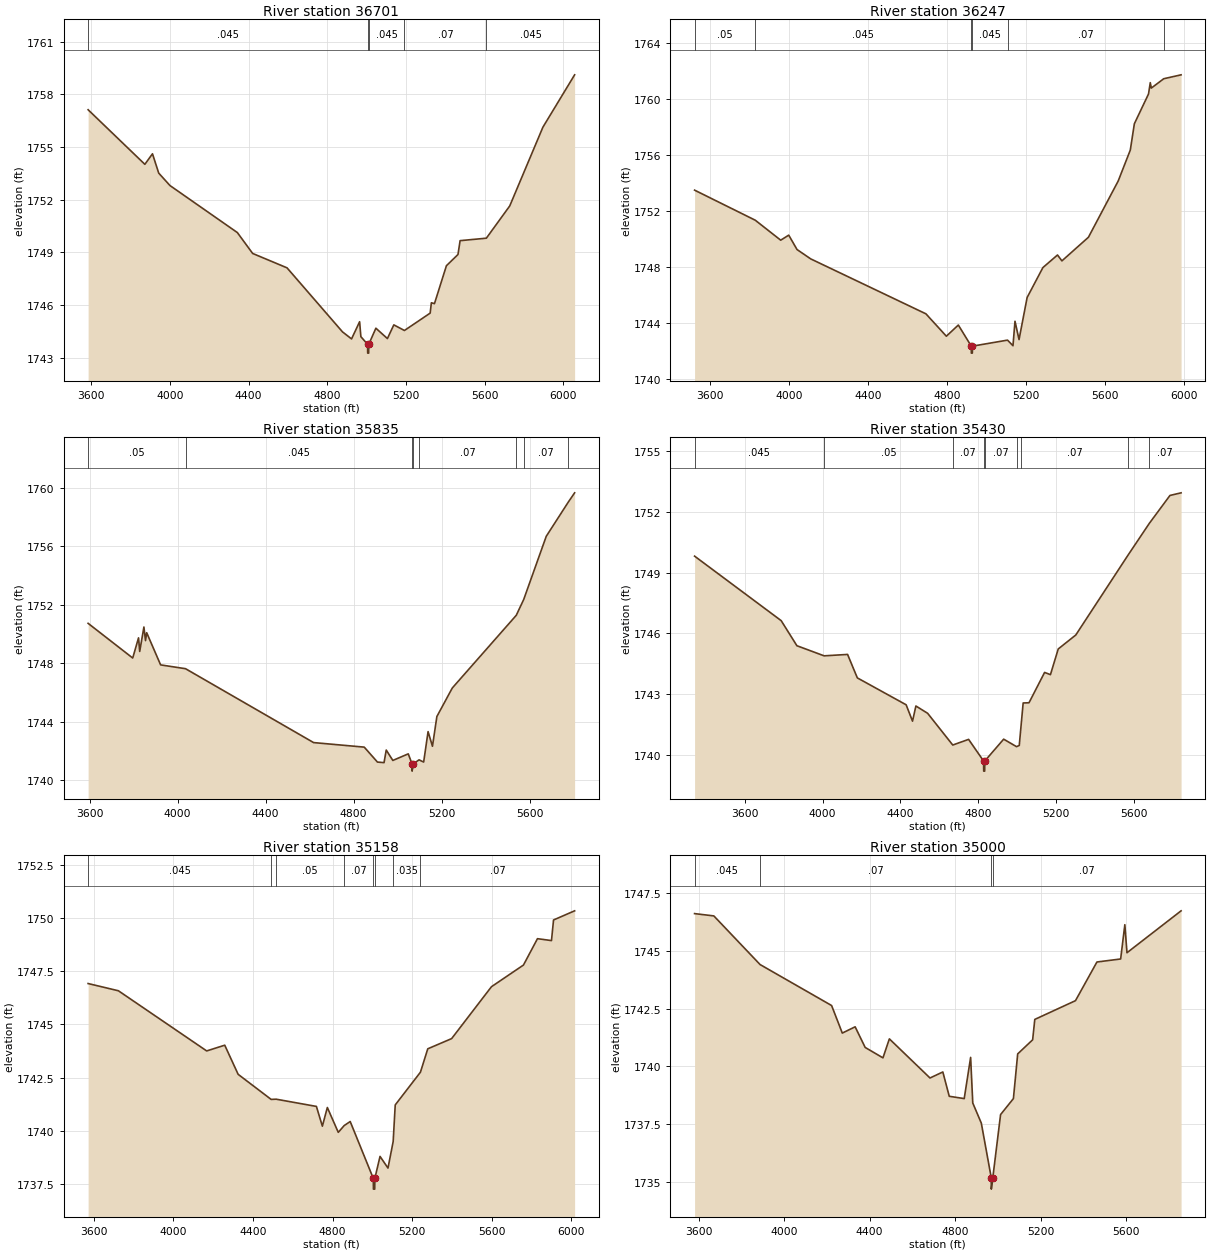
Type RM Length L Ch R = 1,36701,454,454,454
BEGIN DESCRIPTION:
Mapping XS 84498a01
END DESCRIPTION:
XS GIS Cut Line= 4
      1529316.04      6945081.74      1528337.35      6944762.74
      1527443.25      6944382.97      1526990.23      6944252.91
#Sta/Elev= 30
  3584.8 1757.13  3873.1 1754.02  3911.9 1754.62  3943.5 1753.52  4000.8 1752.81
  4343.2 1750.13  4420.9 1748.94  4595.6 1748.12  4877.5 1744.47  4923.4 1744.07
  4964.4 1745.05  4970.7 1744.20  5004.9 1743.76  5005.4 1743.26  5010.3 1743.26
  5010.8 1743.76  5047.1 1744.68  5105.6 1744.09  5138.2 1744.87  5192.1 1744.55
  5322.9 1745.54  5329.0 1746.13  5344.7 1746.08  5405.4 1748.24  5464.2 1748.88
  5475.0 1749.67  5608.4 1749.81  5727.3 1751.65  5895.9 1756.14  6056.9 1759.12
#Mann=5,-1,0
  3584.8   0.045       0  5004.9   0.045       0  5010.8   0.045       0
  5192.1    0.07       0  5608.4   0.045       0
Bank Sta=5004.9,5010.8
Exp/Cntr=0.3,0.1

Type RM Length L Ch R = 1,36247,412,412,412
BEGIN DESCRIPTION:
Mapping XS 5fa0613d
END DESCRIPTION:
XS GIS Cut Line= 4
      1529454.96      6944521.85      1528797.42      6944406.84
      1527441.08      6944098.68      1527043.96      6944009.71
#Sta/Elev= 30
  3521.2 1753.48  3828.6 1751.33  3957.7 1749.90  3998.3 1750.26  4040.4 1749.23
  4110.0 1748.56  4693.7 1744.63  4797.1 1743.03  4857.8 1743.83  4923.3 1742.32
  4923.8 1741.82  4928.8 1741.82  4929.3 1742.32  5107.0 1742.75  5134.7 1742.35
  5144.9 1744.10  5165.4 1742.79  5206.4 1745.80  5286.3 1747.94  5360.3 1748.84
  5382.7 1748.42  5517.1 1750.11  5667.8 1754.13  5729.3 1756.35  5749.8 1758.23
  5821.6 1760.36  5830.5 1761.17  5835.6 1760.78  5898.7 1761.45  5986.6 1761.73
#Mann=6,-1,0
  3521.2    0.05       0  3828.6   0.045       0  4923.3   0.045       0
  4929.3   0.045       0  5107.0    0.07       0  5898.7   0.045       0
Bank Sta=4923.3,4929.3
Exp/Cntr=0.3,0.1

Type RM Length L Ch R = 1,35835,405,405,405
BEGIN DESCRIPTION:
Mapping XS 7eff7870
END DESCRIPTION:
XS GIS Cut Line= 4
      1529465.78      6944135.56      1528639.00      6943862.13
      1527664.60      6943833.92      1527302.16      6943786.17
#Sta/Elev= 30
  3593.4 1750.74  3796.1 1748.37  3822.6 1749.75  3827.9 1748.82  3847.0 1750.49
  3854.3 1749.56  3859.6 1750.10  3923.0 1747.90  4036.2 1747.64  4618.3 1742.59
  4848.4 1742.28  4908.4 1741.26  4938.4 1741.22  4948.4 1742.08  4978.4 1741.37
  5048.5 1741.82  5065.5 1741.14  5066.0 1740.64  5071.5 1741.14  5097.5 1741.41
  5118.5 1741.26  5138.5 1743.34  5158.5 1742.34  5178.5 1744.37  5248.6 1746.32
  5539.4 1751.29  5573.2 1752.37  5675.7 1756.69  5776.0 1759.03  5804.6 1759.66
#Mann=8,-1,0
  3593.4    0.05       0  4036.2   0.045       0  5065.5   0.045       0
  5071.5   0.045       0  5097.5    0.07       0  5539.4   0.045       0
  5573.2    0.07       0  5776.0   0.045       0
Bank Sta=5065.5,5071.5
Exp/Cntr=0.3,0.1

Type RM Length L Ch R = 1,35430,272,272,272
BEGIN DESCRIPTION:
Mapping XS 786a3b90
END DESCRIPTION:
XS GIS Cut Line= 5
      1529724.05      6943740.60      1529033.96      6943514.91
      1528339.52      6943475.85      1527571.29      6943469.34
      1527268.70      6943519.05
#Sta/Elev= 30
  3343.5 1749.81  3787.9 1746.62  3868.6 1745.38  4008.4 1744.88  4128.6 1744.95
  4178.7 1743.79  4429.1 1742.46  4461.9 1741.65  4479.2 1742.40  4539.3 1742.04
  4668.3 1740.47  4749.6 1740.75  4826.6 1739.68  4827.1 1739.18  4832.2 1739.18
  4832.7 1739.68  4929.6 1740.76  4995.7 1740.39  5009.6 1740.45  5017.0 1741.23
  5029.6 1742.55  5059.6 1742.56  5139.6 1744.06  5169.6 1743.95  5209.6 1745.22
  5299.6 1745.91  5568.5 1749.87  5677.0 1751.43  5782.9 1752.81  5840.0 1752.94
#Mann=9,-1,0
  3343.5   0.045       0  4008.4    0.05       0  4668.3    0.07       0
  4826.6   0.035       0  4832.7    0.07       0  4995.7   0.035       0
  5017.0    0.07       0  5568.5   0.045       0  5677.0    0.07       0
Bank Sta=4826.6,4832.7
Exp/Cntr=0.3,0.1

Type RM Length L Ch R = 1,35158,158,158,158
BEGIN DESCRIPTION:
Mapping XS 60cbced7
END DESCRIPTION:
XS GIS Cut Line= 6
      1529675.89      6943374.72      1528892.47      6943268.38
      1528310.87      6943274.89      1528137.26      6943274.89
      1527675.02      6943285.74      1527239.38      6943335.59
#Sta/Elev= 30
  3570.9 1746.92  3723.2 1746.58  4167.2 1743.75  4258.0 1744.02  4325.4 1742.65
  4491.4 1741.47  4516.7 1741.48  4719.0 1741.14  4749.0 1740.21  4774.0 1741.09
  4829.0 1739.92  4858.8 1740.24  4889.0 1740.43  5005.3 1737.75  5005.8 1737.25
  5012.3 1737.25  5012.8 1737.75  5039.0 1738.79  5079.0 1738.24  5105.1 1739.49
  5115.4 1741.21  5242.2 1742.75  5279.1 1743.85  5399.1 1744.33  5599.3 1746.77
  5760.3 1747.79  5830.8 1749.03  5901.2 1748.94  5911.6 1749.91  6017.6 1750.34
#Mann=8,-1,0
  3570.9   0.045       0  4491.4    0.07       0  4516.7    0.05       0
  4858.8    0.07       0  5005.3    0.07       0  5012.8    0.07       0
  5105.1   0.035       0  5242.2    0.07       0
Bank Sta=5005.3,5012.8
Exp/Cntr=0.3,0.1

Type RM Length L Ch R = 1,35000,246,246,246
BEGIN DESCRIPTION:
Mapping XS 61937a4b
END DESCRIPTION:
XS GIS Cut Line= 4
      1529665.01      6943201.11      1528866.43      6943159.88
      1527970.16      6943138.17      1527392.89      6943088.26
#Sta/Elev= 30
  3581.2 1746.60  3671.3 1746.50  3887.5 1744.40  4222.1 1742.63  4272.1 1741.44
  4332.2 1741.71  4379.1 1740.82  4462.3 1740.37  4492.3 1741.19  4682.4 1739.50
  4742.4 1739.76  4772.4 1738.71  4842.4 1738.61  4872.4 1740.39  4882.4 1738.42
  4922.4 1737.55  4968.7 1735.20  4969.2 1734.70  4976.2 1735.20  5012.5 1737.92
  5072.5 1738.61  5092.5 1740.54  5162.5 1741.15  5172.5 1742.03  5362.9 1742.84
  5463.2 1744.51  5574.1 1744.64  5593.7 1746.12  5603.7 1744.91  5856.8 1746.72
#Mann=4,-1,0
  3581.2   0.045       0  3887.5    0.07       0  4968.7    0.07       0
  4976.2    0.07       0
Bank Sta=4968.7,4976.2
Exp/Cntr=0.3,0.1

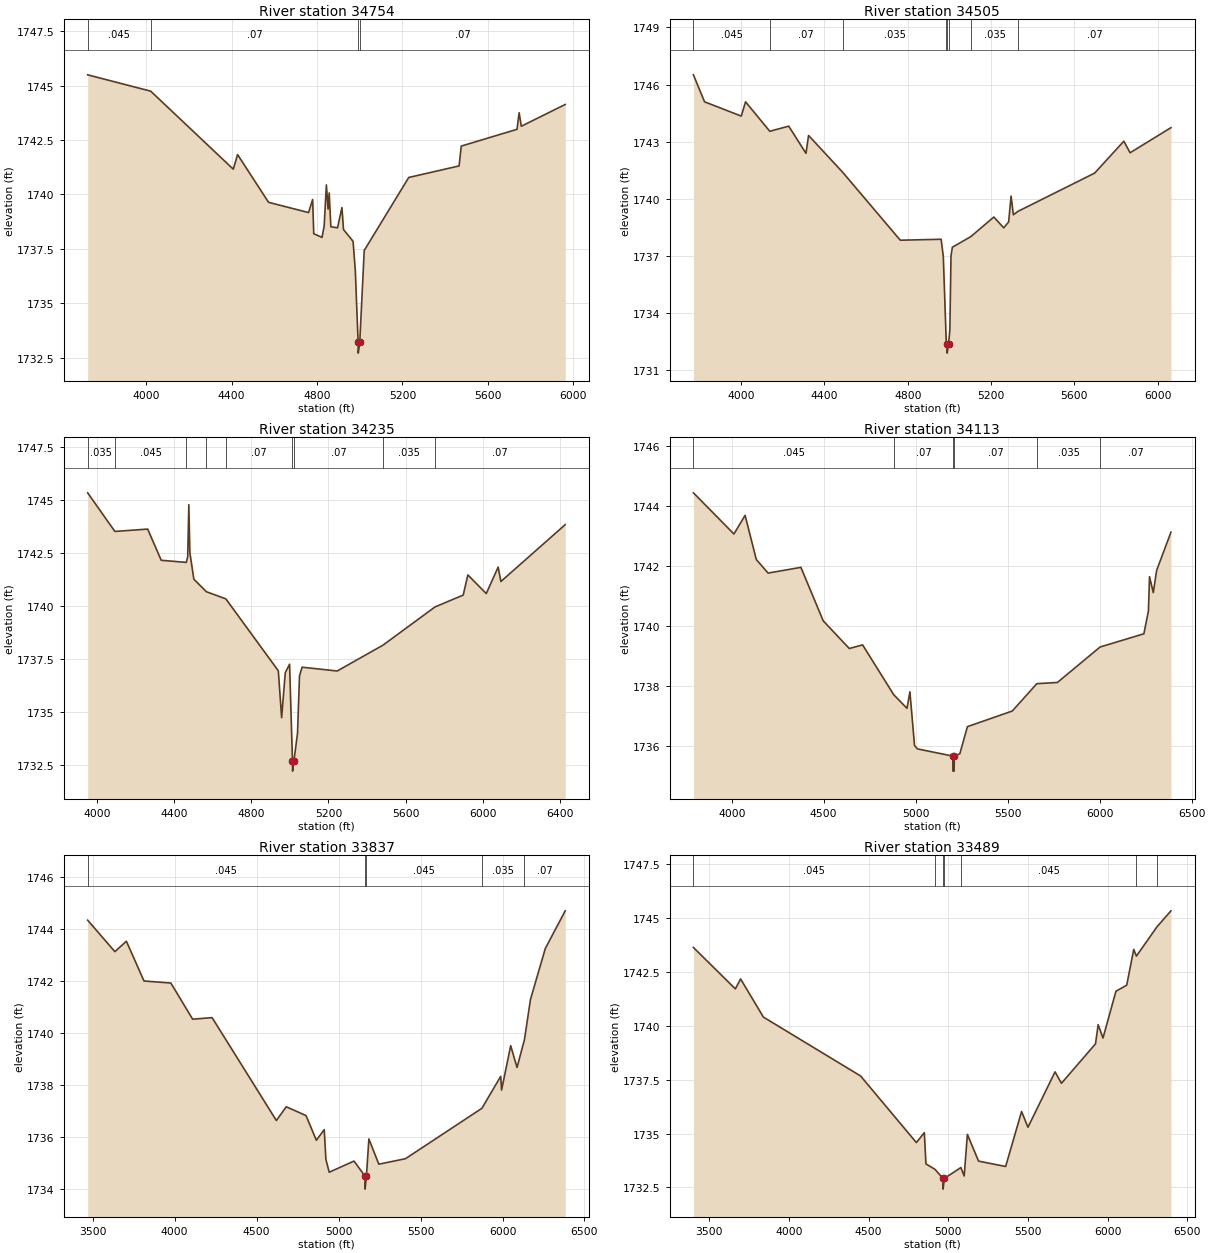
Type RM Length L Ch R = 1,34754,249,249,249
BEGIN DESCRIPTION:
Mapping XS 81f19cc7
END DESCRIPTION:
XS GIS Cut Line= 4
      1529654.15      6943175.06      1528927.19      6943114.30
      1528054.80      6942860.40      1527460.17      6942810.48
#Sta/Elev= 30
  3726.8 1745.49  4021.9 1744.74  4408.3 1741.16  4428.4 1741.83  4573.3 1739.64
  4760.6 1739.17  4779.6 1739.77  4784.8 1738.20  4823.6 1738.03  4833.5 1738.55
  4843.9 1740.44  4851.9 1739.33  4857.1 1740.07  4864.8 1738.52  4896.0 1738.47
  4916.8 1739.40  4924.1 1738.39  4968.9 1737.85  4979.3 1736.51  4992.5 1733.22
  4993.0 1732.72  5000.1 1733.22  5021.0 1737.43  5229.3 1740.78  5465.0 1741.31
  5475.1 1742.22  5736.0 1742.99  5746.0 1743.75  5756.1 1743.13  5961.6 1744.13
#Mann=4,-1,0
  3726.8   0.045       0  4021.9    0.07       0  4992.5    0.07       0
  5000.1    0.07       0
Bank Sta=4992.5,5000.1
Exp/Cntr=0.3,0.1

Type RM Length L Ch R = 1,34505,270,270,270
BEGIN DESCRIPTION:
Mapping XS 826de1fd
END DESCRIPTION:
XS GIS Cut Line= 5
      1529716.70      6943155.11      1528909.40      6942938.96
      1528271.37      6942668.12      1527641.17      6942662.91
      1527519.43      6942714.72
#Sta/Elev= 30
  3771.8 1746.51  3825.3 1745.09  4001.3 1744.34  4022.0 1745.09  4138.3 1743.54
  4229.1 1743.81  4311.9 1742.38  4324.3 1743.32  4488.4 1741.38  4764.4 1737.81
  4960.4 1737.86  4970.8 1736.97  4984.9 1732.50  4988.7 1732.37  4989.2 1731.87
  4996.3 1732.37  5002.3 1733.10  5007.8 1736.99  5014.3 1737.44  5103.0 1738.00
  5213.3 1739.03  5260.7 1738.46  5284.3 1738.77  5296.0 1740.13  5307.0 1739.15
  5329.5 1739.33  5697.1 1741.34  5837.1 1743.02  5867.1 1742.41  6063.2 1743.73
#Mann=8,-1,0
  3771.8   0.045       0  4138.3    0.07       0  4488.4   0.035       0
  4984.9    0.07       0  4988.7    0.07       0  4996.3    0.07       0
  5103.0   0.035       0  5329.5    0.07       0
Bank Sta=4988.7,4996.3
Exp/Cntr=0.3,0.1

Type RM Length L Ch R = 1,34235,122,122,122
BEGIN DESCRIPTION:
Mapping XS 66ed3bbd
END DESCRIPTION:
XS GIS Cut Line= 5
      1529755.75      6942933.75      1529172.42      6942733.23
      1528550.02      6942576.98      1527742.73      6942410.31
      1527466.72      6942691.53
#Sta/Elev= 30
  3951.2 1745.33  4092.4 1743.51  4262.5 1743.62  4332.7 1742.15  4462.8 1742.05
  4470.1 1742.32  4475.9 1744.77  4481.2 1742.52  4501.9 1741.26  4566.6 1740.67
  4668.0 1740.33  4940.1 1736.94  4957.2 1734.73  4976.1 1736.85  4998.4 1737.25
  5013.5 1732.71  5014.0 1732.21  5021.2 1732.71  5039.6 1733.99  5050.0 1736.71
  5063.6 1737.11  5245.5 1736.93  5483.2 1738.15  5752.7 1739.95  5899.0 1740.51
  5923.2 1741.46  6018.6 1740.58  6080.3 1741.83  6094.5 1741.15  6428.1 1743.83
#Mann=9,-1,0
  3951.2   0.035       0  4092.4   0.045       0  4462.8    0.07       0
  4566.6   0.035       0  4668.0    0.07       0  5013.5    0.07       0
  5021.2    0.07       0  5483.2   0.035       0  5752.7    0.07       0
Bank Sta=5013.5,5021.2
Exp/Cntr=0.3,0.1

Type RM Length L Ch R = 1,34113,276,276,276
BEGIN DESCRIPTION:
Mapping XS df4a4256
END DESCRIPTION:
XS GIS Cut Line= 4
      1529992.73      6942733.23      1529128.15      6942603.02
      1528354.71      6942407.71      1527451.04      6942217.60
#Sta/Elev= 30
  3792.0 1744.44  4012.2 1743.07  4072.9 1743.69  4133.9 1742.22  4197.8 1741.77
  4376.2 1741.96  4497.6 1740.18  4639.2 1739.26  4711.6 1739.38  4881.0 1737.72
  4952.8 1737.27  4968.7 1737.82  4993.8 1736.03  5009.9 1735.92  5202.0 1735.68
  5202.5 1735.18  5209.2 1735.18  5209.7 1735.68  5240.1 1735.76  5281.2 1736.66
  5525.1 1737.18  5658.6 1738.09  5770.3 1738.13  6002.3 1739.31  6240.4 1739.75
  6265.0 1740.51  6271.0 1741.65  6291.5 1741.12  6309.7 1741.86  6387.5 1743.13
#Mann=6,-1,0
  3792.0   0.045       0  4881.0    0.07       0  5202.0    0.07       0
  5209.7    0.07       0  5658.6   0.035       0  6002.3    0.07       0
Bank Sta=5202,5209.7
Exp/Cntr=0.3,0.1

Type RM Length L Ch R = 1,33837,348,348,348
BEGIN DESCRIPTION:
Mapping XS 758790be
END DESCRIPTION:
XS GIS Cut Line= 4
      1530299.97      6942428.53      1528990.12      6942293.12
      1528454.63      6942220.89      1527404.19      6942113.44
#Sta/Elev= 30
  3469.4 1744.35  3635.3 1743.14  3705.6 1743.54  3813.1 1742.01  3977.1 1741.93
  4109.7 1740.54  4228.4 1740.60  4620.5 1736.64  4680.8 1737.17  4801.5 1736.83
  4864.5 1735.88  4912.5 1736.29  4922.6 1735.15  4942.8 1734.65  5094.1 1735.08
  5161.1 1734.50  5161.6 1734.00  5169.9 1734.50  5184.9 1735.93  5245.5 1734.96
  5407.9 1735.17  5874.2 1737.11  5989.2 1738.34  5994.2 1737.81  6050.0 1739.52
  6088.6 1738.68  6134.1 1739.76  6170.6 1741.30  6261.1 1743.26  6382.5 1744.71
#Mann=5,-1,0
  3469.4   0.045       0  5161.1   0.045       0  5169.9   0.045       0
  5874.2   0.035       0  6134.1    0.07       0
Bank Sta=5161.1,5169.9
Exp/Cntr=0.3,0.1

Type RM Length L Ch R = 1,33489,384,384,384
BEGIN DESCRIPTION:
Mapping XS 662fb494
END DESCRIPTION:
XS GIS Cut Line= 4
      1530315.62      6942228.01      1529453.67      6941967.60
      1527831.27      6941907.71      1527365.09      6941824.37
#Sta/Elev= 30
  3400.8 1743.63  3664.0 1741.71  3697.0 1742.17  3840.2 1740.40  4450.0 1737.67
  4800.2 1734.58  4850.3 1735.04  4860.3 1733.59  4916.8 1733.34  4967.3 1732.92
  4967.8 1732.42  4976.1 1732.92  5079.7 1733.42  5100.4 1733.03  5120.5 1734.96
  5190.5 1733.72  5360.6 1733.47  5460.7 1736.02  5500.7 1735.29  5670.8 1737.86
  5710.9 1737.33  5924.7 1739.16  5941.3 1740.05  5971.7 1739.43  6053.0 1741.60
  6120.5 1741.88  6164.7 1743.54  6181.5 1743.23  6310.7 1744.59  6398.3 1745.33
#Mann=7,-1,0
  3400.8   0.045       0  4916.8    0.07       0  4967.3    0.07       0
  4976.1    0.07       0  5079.7   0.045       0  6181.5   0.035       0
  6310.7    0.07       0
Bank Sta=4967.3,4976.1
Exp/Cntr=0.3,0.1