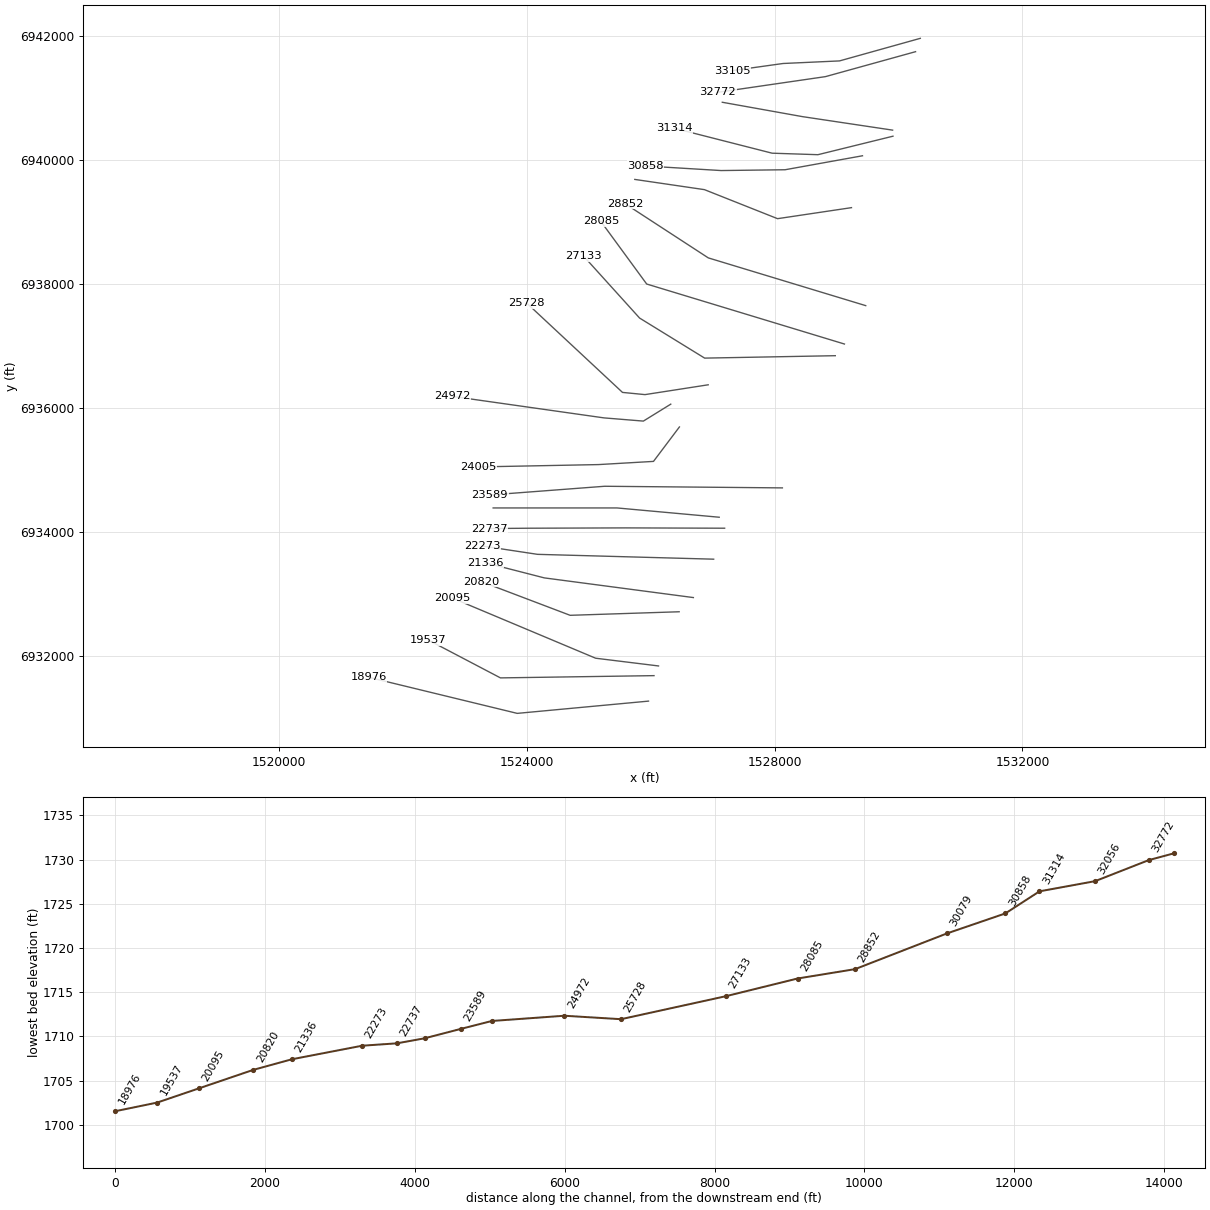
HEC-RAS study Dark Hollow Branch.prj: Dark Hollow Branch Base Level Engineering

--- Dark Hollow Branch.g01 (geometry) --- (continued)

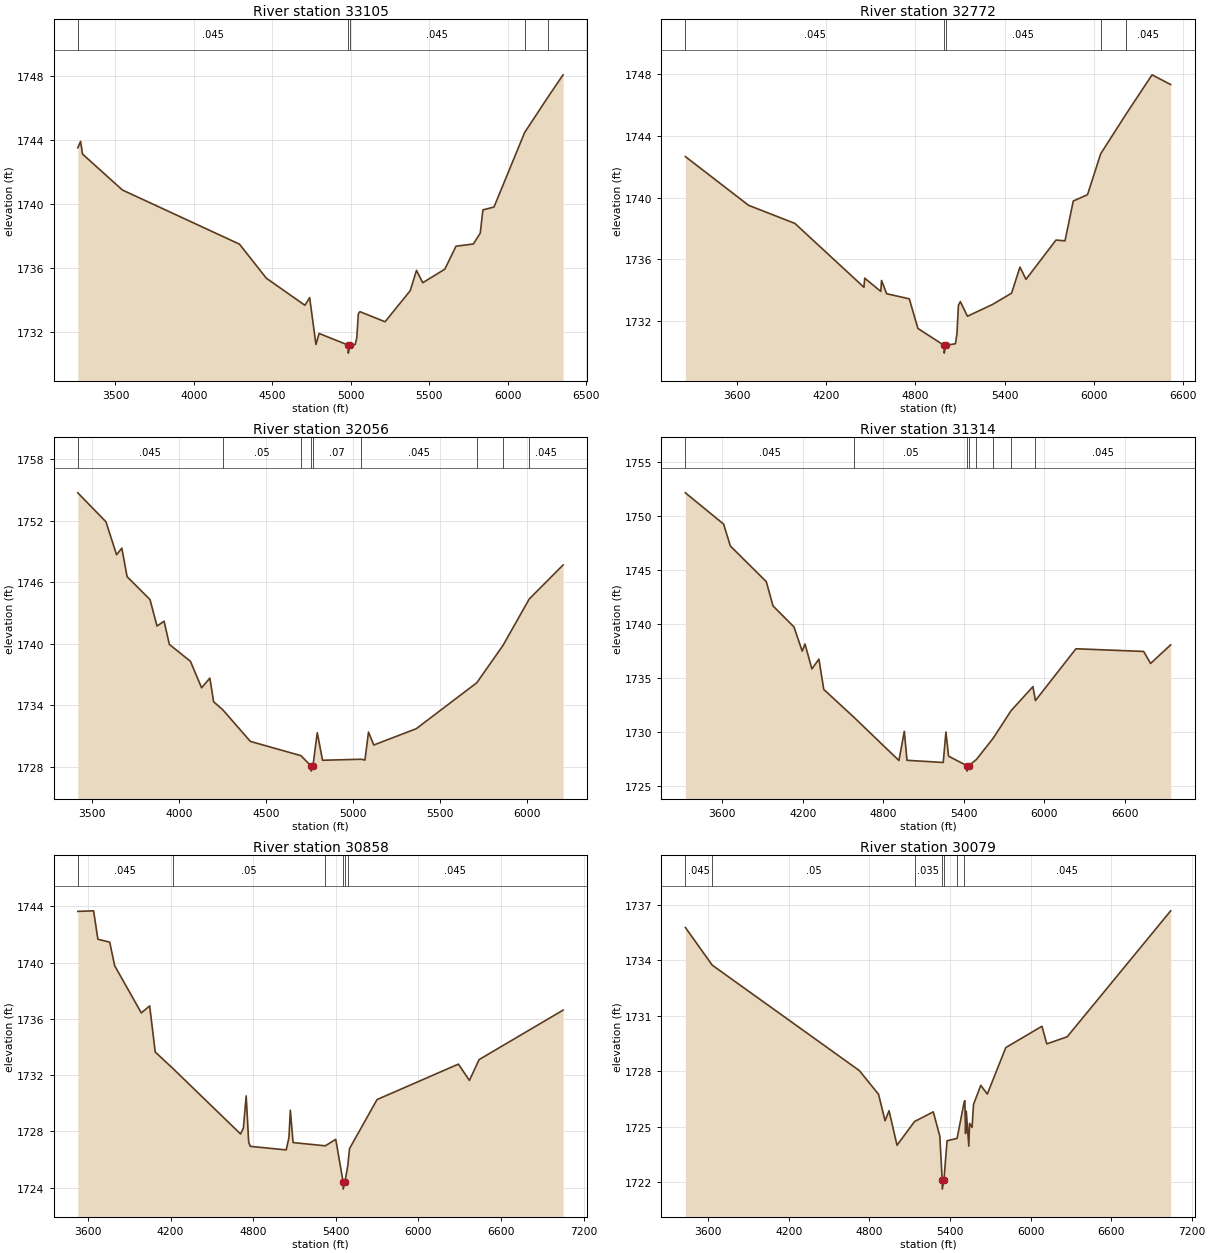
Type RM Length L Ch R = 1,33105,333,333,333
BEGIN DESCRIPTION:
Mapping XS 43e7c223
END DESCRIPTION:
XS GIS Cut Line= 4
      1530352.09      6941970.20      1529047.42      6941605.62
      1528135.96      6941563.96      1527319.10      6941449.49
#Sta/Elev= 30
  3260.1 1743.52  3277.8 1743.92  3290.1 1743.13  3544.8 1740.88  4290.1 1737.50
  4461.5 1735.37  4707.3 1733.68  4737.3 1734.16  4777.3 1731.23  4797.4 1731.92
  4983.1 1731.19  4983.6 1730.69  4992.0 1731.19  5027.6 1731.23  5037.6 1731.65
  5047.6 1733.15  5057.6 1733.28  5217.8 1732.65  5378.0 1734.59  5418.0 1735.86
  5458.0 1735.09  5598.8 1735.94  5669.5 1737.37  5780.6 1737.51  5824.2 1738.19
  5841.2 1739.64  5911.8 1739.82  6107.3 1744.48  6257.1 1746.71  6352.0 1748.08
#Mann=5,-1,0
  3260.1   0.045       0  4983.1   0.045       0  4992.0   0.045       0
  6107.3   0.035       0  6257.1   0.045       0
Bank Sta=4983.1,4992
Exp/Cntr=0.3,0.1

Type RM Length L Ch R = 1,32772,716,716,716
BEGIN DESCRIPTION:
Mapping XS 57886cc5
END DESCRIPTION:
XS GIS Cut Line= 3
      1530275.38      6941754.72      1528820.49      6941351.93
      1527080.88      6941098.46
#Sta/Elev= 30
  3251.2 1742.67  3677.0 1739.51  3988.3 1738.34  4453.5 1734.20  4458.7 1734.79
  4566.8 1733.93  4572.0 1734.64  4606.3 1733.78  4758.8 1733.45  4816.9 1731.53
  4993.5 1730.43  4994.0 1729.93  5004.1 1730.43  5069.5 1730.54  5079.6 1731.17
  5089.7 1733.03  5102.5 1733.27  5150.4 1732.32  5322.2 1733.10  5447.7 1733.82
  5504.1 1735.51  5544.5 1734.71  5746.6 1737.26  5807.2 1737.21  5863.0 1739.79
  5958.8 1740.20  6047.5 1742.85  6217.5 1745.41  6393.4 1747.97  6518.8 1747.34
#Mann=5,-1,0
  3251.2   0.045       0  4993.5   0.045       0  5004.1   0.045       0
  6047.5   0.035       0  6217.5   0.045       0
Bank Sta=4993.5,5004.1
Exp/Cntr=0.3,0.1

Type RM Length L Ch R = 1,32056,742,742,742
BEGIN DESCRIPTION:
Dark Hollow Branch 36.0
END DESCRIPTION:
XS GIS Cut Line= 3
      1529905.02      6940488.00      1528448.96      6940706.10
      1527154.98      6940938.00
#Sta/Elev= 30
  3419.0 1754.71  3580.8 1751.88  3641.5 1748.67  3671.8 1749.31  3702.1 1746.53
  3833.6 1744.29  3874.0 1741.71  3914.5 1742.18  3944.8 1739.92  4066.2 1738.26
  4129.9 1735.68  4177.4 1736.63  4199.0 1734.32  4252.6 1733.52  4410.0 1730.45
  4700.5 1729.06  4758.5 1728.05  4759.0 1727.55  4769.2 1728.05  4794.2 1731.30
  4824.5 1728.61  5046.4 1728.71  5068.0 1728.63  5088.4 1731.36  5118.8 1730.10
  5362.7 1731.69  5710.6 1736.18  5861.2 1739.83  6011.5 1744.35  6205.9 1747.67
#Mann=9,-1,0
  3419.0   0.045       0  4252.6    0.05       0  4700.5    0.07       0
  4758.5    0.07       0  4769.2    0.07       0  5046.4   0.045       0
  5710.6    0.05       0  5861.2   0.035       0  6011.5   0.045       0
Bank Sta=4758.5,4769.2
Exp/Cntr=0.3,0.1

Type RM Length L Ch R = 1,31314,456,456,456
BEGIN DESCRIPTION:
Mapping XS 2ba3789b
END DESCRIPTION:
XS GIS Cut Line= 4
      1529910.81      6940390.14      1528698.96      6940091.52
      1527959.38      6940115.82      1526379.79      6940518.53
#Sta/Elev= 30
  3324.7 1752.12  3609.6 1749.23  3660.3 1747.20  3928.0 1743.91  3977.9 1741.67
  4134.0 1739.73  4195.8 1737.49  4216.4 1738.15  4267.9 1735.85  4320.2 1736.75
  4356.5 1733.95  4582.8 1731.36  4916.9 1727.38  4957.0 1730.08  4977.0 1727.40
  5247.1 1727.20  5267.1 1730.01  5287.1 1727.78  5424.4 1726.90  5424.9 1726.40
  5437.2 1726.90  5494.9 1727.48  5620.6 1729.46  5751.8 1731.97  5915.9 1734.21
  5934.3 1732.92  6236.6 1737.71  6741.4 1737.46  6793.0 1736.35  6942.9 1738.07
#Mann=8,-1,0
  3324.7   0.045       0  4582.8    0.05       0  5424.4    0.05       0
  5437.2    0.05       0  5494.9   0.045       0  5620.6    0.05       0
  5751.8   0.035       0  5934.3   0.045       0
Bank Sta=5424.4,5437.2
Exp/Cntr=0.3,0.1

Type RM Length L Ch R = 1,30858,779,779,779
BEGIN DESCRIPTION:
Mapping XS 060d0fdf
END DESCRIPTION:
XS GIS Cut Line= 4
      1529418.56      6940074.15      1528168.58      6939848.46
      1527135.60      6939835.44      1525915.99      6939909.22
#Sta/Elev= 30
  3526.0 1743.65  3640.7 1743.69  3671.9 1741.67  3757.9 1741.46  3793.8 1739.79
  3987.4 1736.43  4047.9 1736.93  4088.5 1733.65  4217.9 1732.47  4708.4 1727.82
  4728.7 1728.24  4749.0 1730.53  4767.5 1727.22  4779.5 1726.94  5039.8 1726.69
  5059.8 1727.57  5069.8 1729.51  5089.8 1727.21  5323.8 1726.98  5399.8 1727.44
  5453.4 1724.40  5453.9 1723.90  5466.2 1724.40  5486.9 1725.55  5499.8 1726.78
  5699.8 1730.27  6290.7 1732.79  6370.8 1731.63  6441.0 1733.11  7051.1 1736.63
#Mann=6,-1,0
  3526.0   0.045       0  4217.9    0.05       0  5323.8   0.035       0
  5453.4    0.05       0  5466.2   0.035       0  5486.9   0.045       0
Bank Sta=5453.4,5466.2
Exp/Cntr=0.3,0.1

Type RM Length L Ch R = 1,30079,1227,1227,1227
BEGIN DESCRIPTION:
Mapping XS c8efc804
END DESCRIPTION:
XS GIS Cut Line= 4
      1529240.65      6939236.49      1528047.05      6939058.53
      1526866.50      6939527.28      1525742.34      6939692.22
#Sta/Elev= 30
  3430.1 1735.76  3629.7 1733.73  4725.0 1728.04  4868.1 1726.76  4916.7 1725.33
  4946.4 1725.87  5005.8 1724.01  5136.6 1725.29  5275.8 1725.81  5324.4 1724.50
  5342.2 1722.14  5342.7 1721.64  5355.1 1722.14  5378.4 1724.25  5453.1 1724.38
  5505.1 1726.32  5510.6 1726.41  5516.1 1724.64  5521.4 1725.85  5540.4 1723.96
  5545.8 1725.19  5564.4 1724.97  5575.4 1726.21  5629.4 1727.24  5678.1 1726.77
  5815.7 1729.28  6084.9 1730.43  6120.9 1729.48  6272.5 1729.86  7043.3 1736.66
#Mann=7,-1,0
  3430.1   0.045       0  3629.7    0.05       0  5136.6   0.035       0
  5342.2    0.05       0  5355.1   0.035       0  5453.1    0.07       0
  5505.1   0.045       0
Bank Sta=5342.2,5355.1
Exp/Cntr=0.3,0.1

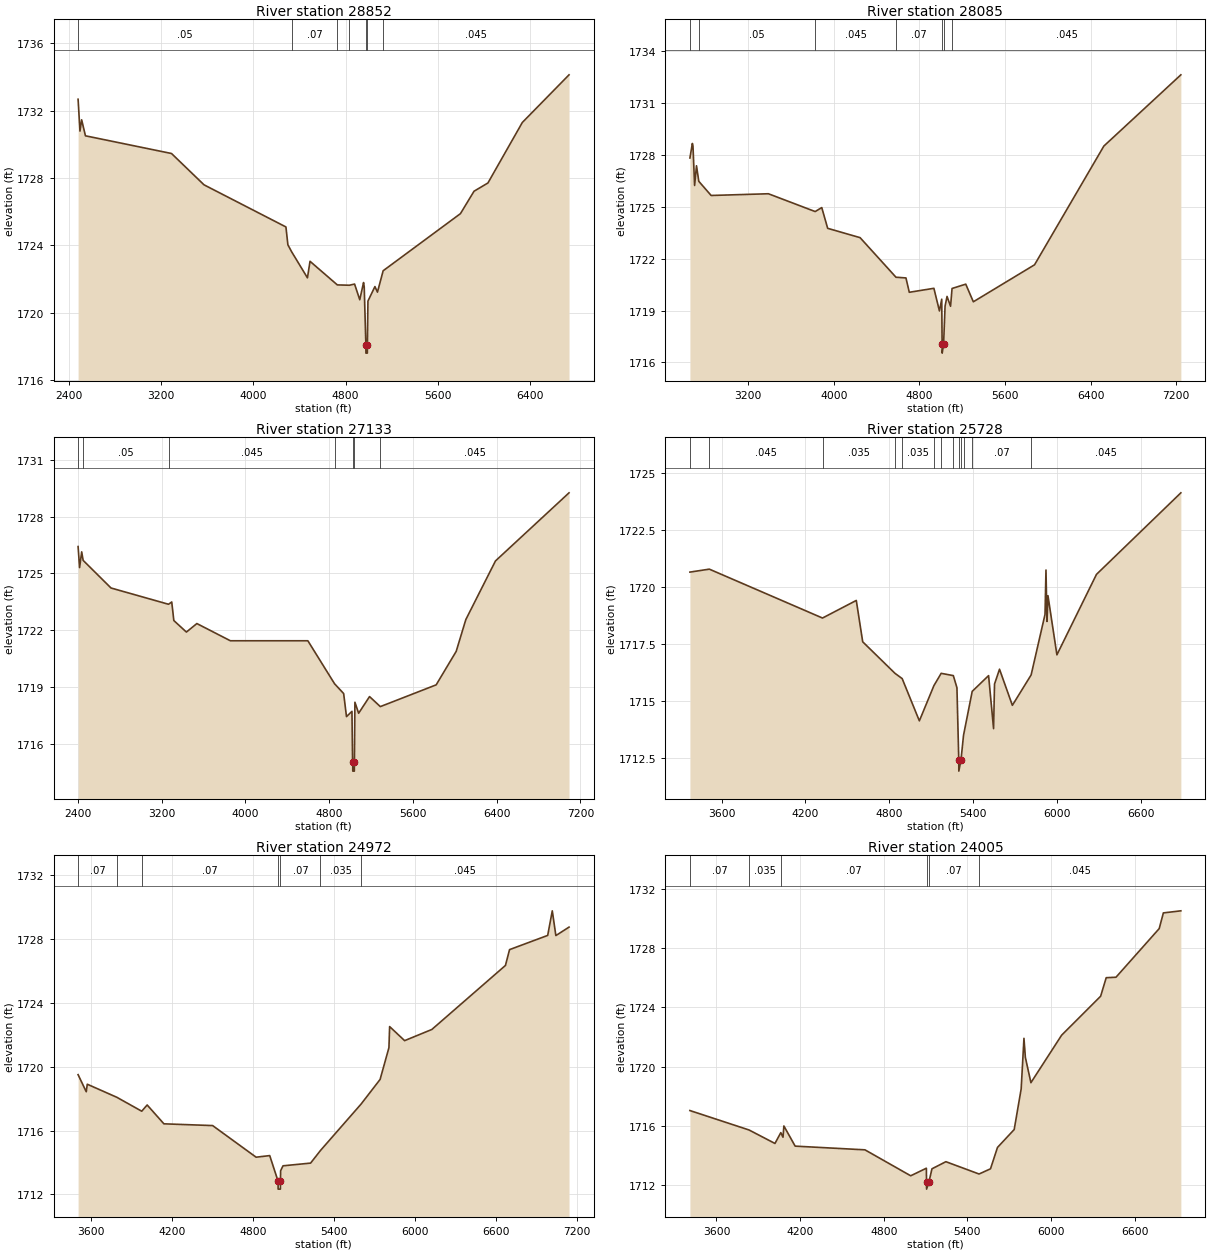
Type RM Length L Ch R = 1,28852,767,767,767
BEGIN DESCRIPTION:
Dark Hollow Branch 35.0
END DESCRIPTION:
XS GIS Cut Line= 3
      1529470.65      6937654.37      1526929.00      6938425.20
      1525585.24      6939300.20
#Sta/Elev= 30
  2479.9 1732.67  2496.3 1730.78  2510.8 1731.45  2543.7 1730.50  3290.4 1729.45
  3572.6 1727.59  4283.2 1725.09  4300.1 1724.03  4332.4 1723.62  4469.8 1722.07
  4492.2 1723.05  4729.1 1721.65  4833.5 1721.63  4878.8 1721.70  4923.7 1720.77
  4956.6 1721.79  4962.4 1721.53  4976.8 1718.10  4977.3 1717.60  4989.4 1717.60
  4989.9 1718.10  4994.7 1720.69  5055.3 1721.55  5077.3 1721.22  5126.7 1722.49
  5797.3 1725.88  5915.1 1727.21  6035.7 1727.70  6334.0 1731.29  6739.4 1734.12
#Mann=7,-1,0
  2479.9    0.05       0  4332.4    0.07       0  4729.1   0.035       0
  4833.5    0.07       0  4976.8    0.07       0  4989.9    0.07       0
  5126.7   0.045       0
Bank Sta=4976.8,4989.9
Exp/Cntr=0.3,0.1

Type RM Length L Ch R = 1,28085,952,952,952
BEGIN DESCRIPTION:
Dark Hollow Branch 34.0
END DESCRIPTION:
XS GIS Cut Line= 3
      1529126.91      6937034.57      1525934.21      6938003.32
      1525194.87      6939013.41
#Sta/Elev= 30
  2654.8 1727.83  2677.7 1728.67  2683.4 1728.52  2698.6 1726.24  2716.3 1727.38
  2737.7 1726.48  2853.1 1725.66  3388.3 1725.76  3825.4 1724.73  3887.0 1724.96
  3942.2 1723.76  4245.2 1723.22  4580.7 1720.93  4673.7 1720.89  4705.0 1720.06
  4934.9 1720.29  4986.7 1718.98  5008.1 1719.66  5011.8 1717.04  5012.3 1716.54
  5025.3 1717.04  5039.4 1719.26  5057.7 1719.82  5090.6 1719.25  5104.6 1720.28
  5232.6 1720.53  5303.6 1719.51  5875.5 1721.65  6523.5 1728.52  7243.0 1732.64
#Mann=7,-1,0
  2654.8    0.07       0  2737.7    0.05       0  3825.4   0.045       0
  4580.7    0.07       0  5011.8    0.07       0  5025.3    0.07       0
  5104.6   0.045       0
Bank Sta=5011.8,5025.3
Exp/Cntr=0.3,0.1

Type RM Length L Ch R = 1,27133,1405,1405,1405
BEGIN DESCRIPTION:
Mapping XS 0b9538c2
END DESCRIPTION:
XS GIS Cut Line= 4
      1528979.35      6936846.20      1526869.97      6936807.14
      1525819.62      6937453.84      1524916.88      6938452.07
#Sta/Elev= 30
  2402.9 1726.42  2417.3 1725.31  2437.3 1726.14  2451.2 1725.69  2717.3 1724.23
  3266.5 1723.37  3297.4 1723.49  3317.4 1722.51  3437.4 1721.90  3537.4 1722.35
  3857.5 1721.44  4597.5 1721.44  4852.3 1719.17  4939.4 1718.65  4966.5 1717.43
  5018.6 1717.71  5024.5 1715.15  5026.1 1715.05  5026.6 1714.55  5041.6 1714.55
  5042.1 1715.05  5046.9 1718.19  5082.5 1717.61  5186.7 1718.49  5289.7 1717.96
  5823.0 1719.11  6014.3 1720.88  6106.2 1722.56  6389.4 1725.66  7092.0 1729.26
#Mann=7,-1,0
  2402.9    0.07       0  2451.2    0.05       0  3266.5   0.045       0
  4852.3    0.07       0  5026.1    0.07       0  5042.1    0.07       0
  5289.7   0.045       0
Bank Sta=5026.1,5042.1
Exp/Cntr=0.3,0.1

Type RM Length L Ch R = 1,25728,756,756,756
BEGIN DESCRIPTION:
Dark Hollow Branch 33.0
END DESCRIPTION:
XS GIS Cut Line= 4
      1526927.25      6936376.28      1525906.68      6936217.75
      1525543.65      6936253.39      1523998.49      6937694.39
#Sta/Elev= 30
  3373.7 1720.65  3512.4 1720.78  4321.7 1718.64  4563.3 1719.41  4609.2 1717.60
  4840.0 1716.22  4891.3 1715.99  5014.3 1714.14  5118.2 1715.68  5170.2 1716.22
  5257.2 1716.12  5283.0 1715.59  5296.0 1712.44  5296.5 1711.94  5312.1 1712.44
  5330.1 1713.51  5392.1 1715.43  5509.2 1716.12  5544.9 1713.80  5551.7 1715.75
  5587.4 1716.40  5679.3 1714.82  5813.5 1716.15  5912.8 1718.80  5919.6 1720.74
  5926.9 1718.49  5933.8 1719.62  5997.8 1717.03  6280.6 1720.55  6884.1 1724.12
#Mann=13,-1,0
  3373.7    0.07       0  3512.4   0.045       0  4321.7   0.035       0
  4840.0    0.07       0  4891.3   0.035       0  5118.2    0.07       0
  5170.2   0.035       0  5257.2    0.07       0  5296.0   0.035       0
  5312.1    0.07       0  5330.1   0.035       0  5392.1    0.07       0
  5813.5   0.045       0
Bank Sta=5296,5312.1
Exp/Cntr=0.3,0.1

Type RM Length L Ch R = 1,24972,967,967,967
BEGIN DESCRIPTION:
Dark Hollow Branch 32.0
END DESCRIPTION:
XS GIS Cut Line= 4
      1526323.05      6936063.78      1525880.55      6935790.23
      1525245.04      6935841.94      1522788.40      6936190.65
#Sta/Elev= 30
  3504.5 1719.50  3565.0 1718.43  3572.7 1718.90  3792.1 1718.08  3976.3 1717.21
  4016.5 1717.60  4140.7 1716.42  4501.8 1716.31  4824.0 1714.33  4925.0 1714.43
  4986.8 1712.83  4987.3 1712.33  5004.1 1712.33  5004.6 1712.83  5005.8 1713.48
  5023.3 1713.79  5228.0 1713.96  5301.2 1714.75  5602.4 1717.66  5743.1 1719.20
  5808.6 1721.19  5813.8 1722.51  5924.9 1721.63  6126.9 1722.33  6672.3 1726.34
  6702.6 1727.33  6985.4 1728.22  7019.4 1729.76  7046.0 1728.21  7143.6 1728.74
#Mann=7,-1,0
  3504.5    0.07       0  3792.1   0.035       0  3976.3    0.07       0
  4986.8    0.07       0  5004.6    0.07       0  5301.2   0.035       0
  5602.4   0.045       0
Bank Sta=4986.8,5004.6
Exp/Cntr=0.3,0.1

Type RM Length L Ch R = 1,24005,416,416,416
BEGIN DESCRIPTION:
Dark Hollow Branch 31.0
END DESCRIPTION:
XS GIS Cut Line= 4
      1526462.54      6935695.44      1526043.97      6935139.49
      1525155.00      6935088.00      1523219.53      6935050.28
#Sta/Elev= 30
  3409.7 1717.04  3833.8 1715.73  4019.8 1714.82  4061.8 1715.55  4077.6 1715.24
  4083.8 1716.00  4164.7 1714.64  4665.5 1714.39  4993.6 1712.64  5106.1 1713.15
  5107.1 1712.24  5107.6 1711.74  5125.0 1712.24  5146.1 1713.11  5246.1 1713.59
  5484.0 1712.76  5566.2 1713.11  5616.2 1714.55  5736.2 1715.76  5786.2 1718.50
  5806.2 1721.91  5816.2 1720.63  5856.2 1718.92  6076.3 1722.12  6356.3 1724.75
  6396.3 1726.00  6466.3 1726.03  6776.4 1729.31  6806.4 1730.37  6931.9 1730.51
#Mann=6,-1,0
  3409.7    0.07       0  3833.8   0.035       0  4061.8    0.07       0
  5107.1    0.07       0  5125.0    0.07       0  5484.0   0.045       0
Bank Sta=5107.1,5125
Exp/Cntr=0.3,0.1

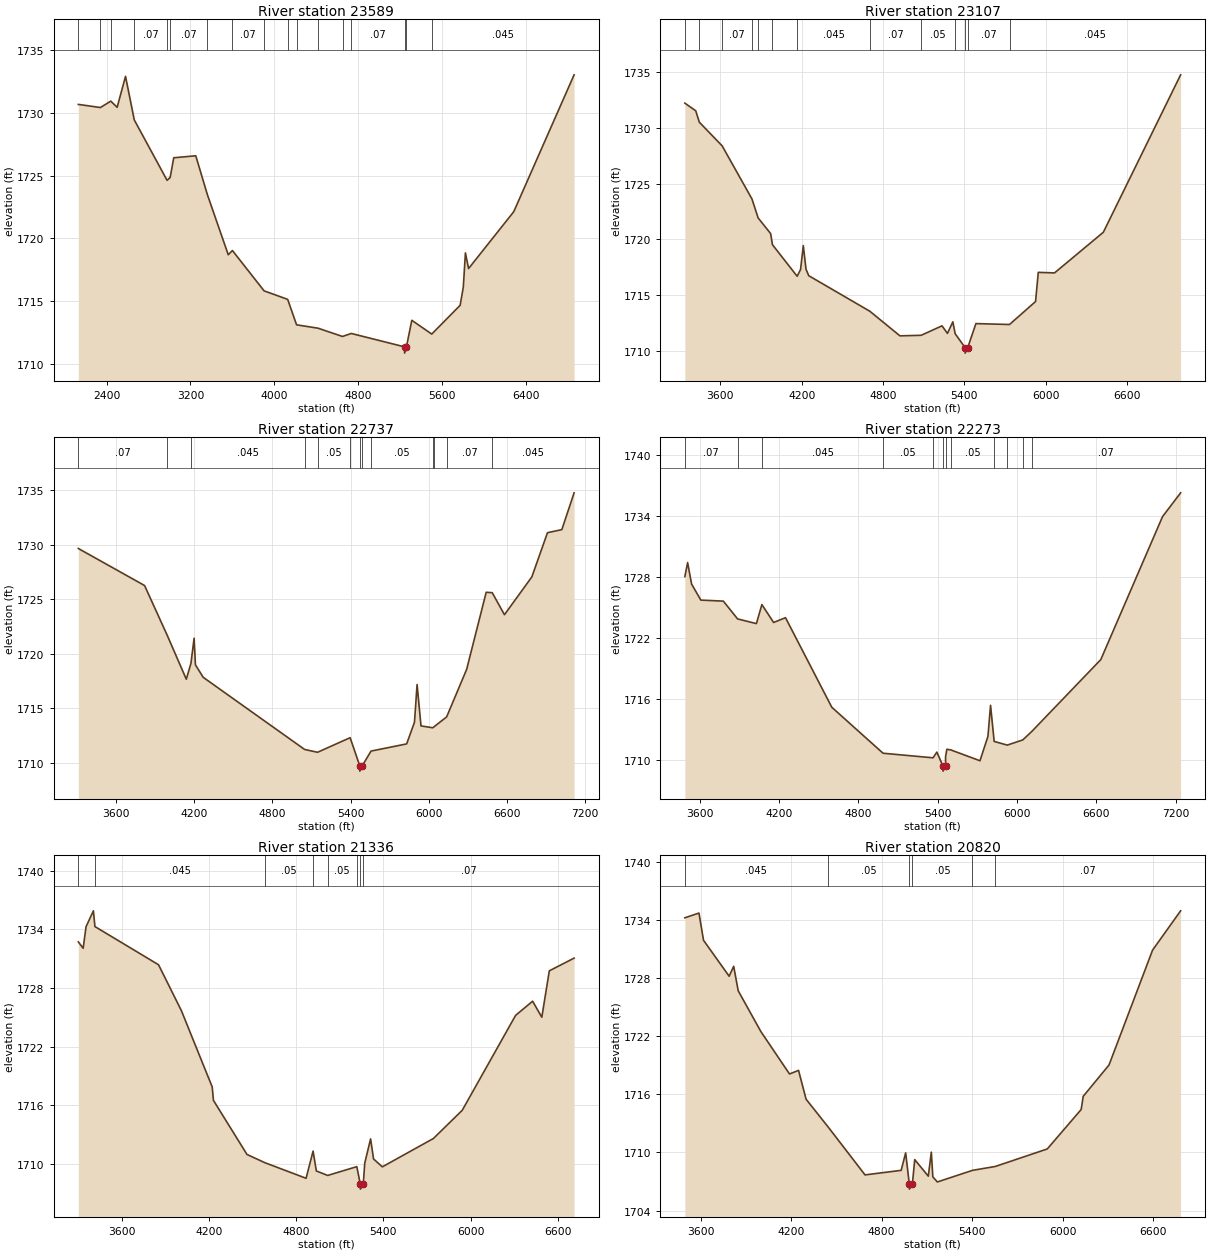
Type RM Length L Ch R = 1,23589,482,482,482
BEGIN DESCRIPTION:
Dark Hollow Branch 30.0
END DESCRIPTION:
XS GIS Cut Line= 3
      1528125.28      6934711.73      1525255.00      6934738.00
      1523401.25      6934597.14
#Sta/Elev= 30
  2130.0 1730.69  2340.5 1730.44  2439.5 1730.95  2500.3 1730.46  2580.3 1732.93
  2663.8 1729.45  2976.7 1724.63  3006.2 1724.86  3040.3 1726.43  3250.3 1726.59
  3361.1 1723.49  3560.3 1718.69  3599.8 1719.03  3902.1 1715.81  4127.2 1715.13
  4212.0 1713.10  4416.5 1712.83  4650.2 1712.17  4733.8 1712.41  5242.2 1711.34
  5242.7 1710.84  5260.1 1711.34  5311.3 1713.46  5501.6 1712.36  5772.6 1714.66
  5802.7 1716.12  5822.8 1718.84  5852.9 1717.59  6284.1 1722.13  6859.5 1733.05
#Mann=17,-1,0
  2130.0   0.035       0  2340.5    0.07       0  2439.5   0.035       0
  2663.8    0.07       0  2976.7   0.035       0  3006.2    0.07       0
  3361.1   0.035       0  3599.8    0.07       0  3902.1   0.035       0
  4127.2    0.07       0  4212.0   0.045       0  4416.5    0.07       0
  4650.2   0.035       0  4733.8    0.07       0  5242.2    0.07       0
  5260.1    0.07       0  5501.6   0.045       0
Bank Sta=5242.2,5260.1
Exp/Cntr=0.3,0.1

Type RM Length L Ch R = 1,23107,370,370,370
BEGIN DESCRIPTION:
Dark Hollow Branch 29.0
END DESCRIPTION:
XS GIS Cut Line= 3
      1527105.03      6934238.00      1525455.00      6934388.00
      1523455.03      6934388.00
#Sta/Elev= 30
  3338.7 1732.22  3419.1 1731.53  3445.3 1730.51  3614.1 1728.38  3833.6 1723.62
  3879.1 1721.92  3971.3 1720.51  3985.0 1719.51  4167.0 1716.68  4192.2 1717.29
  4212.3 1719.43  4232.4 1717.31  4252.5 1716.73  4703.1 1713.54  4925.2 1711.33
  5081.7 1711.38  5235.5 1712.23  5275.5 1711.55  5315.5 1712.59  5332.6 1711.52
  5405.6 1710.28  5406.1 1709.78  5425.4 1710.28  5485.5 1712.43  5733.3 1712.35
  5925.5 1714.41  5945.5 1717.03  6065.5 1716.98  6425.5 1720.63  6995.5 1734.76
#Mann=13,-1,0
  3338.7    0.07       0  3445.3   0.035       0  3614.1    0.07       0
  3833.6   0.035       0  3879.1    0.07       0  3985.0   0.035       0
  4167.0   0.045       0  4703.1    0.07       0  5081.7    0.05       0
  5332.6    0.07       0  5405.6    0.07       0  5425.4    0.07       0
  5733.3   0.045       0
Bank Sta=5405.6,5425.4
Exp/Cntr=0.3,0.1

Type RM Length L Ch R = 1,22737,464,464,464
BEGIN DESCRIPTION:
Mapping XS 3dc00a17
END DESCRIPTION:
XS GIS Cut Line= 4
      1527192.96      6934060.69      1525594.00      6934065.89
      1524047.13      6934060.69      1523390.90      6934055.48
#Sta/Elev= 30
  3312.1 1729.65  3820.1 1726.25  3993.5 1721.69  4140.1 1717.65  4175.5 1719.09
  4200.1 1721.41  4210.1 1718.97  4270.1 1717.82  5047.6 1711.20  5146.6 1710.94
  5396.5 1712.28  5470.2 1709.71  5470.7 1709.21  5490.0 1709.71  5556.9 1711.05
  5830.1 1711.71  5890.1 1713.70  5910.1 1717.16  5940.1 1713.36  6030.3 1713.19
  6037.8 1713.26  6136.8 1714.19  6290.1 1718.55  6440.1 1725.63  6486.4 1725.59
  6580.1 1723.57  6790.1 1727.04  6910.1 1731.10  7020.1 1731.38  7114.2 1734.76
#Mann=13,-1,0
  3312.1    0.07       0  3993.5   0.035       0  4175.5   0.045       0
  5047.6    0.07       0  5146.6    0.05       0  5396.5    0.07       0
  5470.2   0.045       0  5490.0    0.07       0  5556.9    0.05       0
  6030.3    0.07       0  6037.8    0.05       0  6136.8    0.07       0
  6486.4   0.045       0
Bank Sta=5470.2,5490
Exp/Cntr=0.3,0.1

Type RM Length L Ch R = 1,22273,937,937,937
BEGIN DESCRIPTION:
Mapping XS 76a6978d
END DESCRIPTION:
XS GIS Cut Line= 3
      1527015.87      6933560.69      1524172.13      6933638.81
      1523278.10      6933773.95
#Sta/Elev= 30
  3488.6 1728.07  3509.5 1729.45  3539.5 1727.34  3609.5 1725.76  3779.6 1725.66
  3887.4 1723.91  4029.7 1723.45  4071.1 1725.32  4159.7 1723.56  4249.8 1724.03
  4599.9 1715.22  4987.3 1710.70  5365.3 1710.25  5394.3 1710.81  5440.3 1709.44
  5440.8 1708.94  5460.1 1709.44  5460.2 1710.38  5470.2 1711.09  5499.0 1711.03
  5720.3 1709.96  5780.3 1712.35  5800.3 1715.41  5827.7 1711.86  5926.8 1711.50
  6044.0 1712.01  6112.7 1712.85  6634.0 1719.91  7100.8 1733.97  7237.6 1736.31
#Mann=12,-1,0
  3488.6    0.07       0  3887.4   0.035       0  4071.1   0.045       0
  4987.3    0.05       0  5365.3    0.07       0  5440.3    0.05       0
  5460.1    0.07       0  5499.0    0.05       0  5827.7   0.035       0
  5926.8    0.07       0  6044.0   0.035       0  6112.7    0.07       0
Bank Sta=5440.3,5460.1
Exp/Cntr=0.3,0.1

Type RM Length L Ch R = 1,21336,516,516,516
BEGIN DESCRIPTION:
Mapping XS 3dc48740
END DESCRIPTION:
XS GIS Cut Line= 3
      1526687.79      6932940.89      1524281.50      6933258.60
      1523329.95      6933502.99
#Sta/Elev= 30
  3302.8 1732.71  3335.9 1732.06  3356.0 1734.27  3406.5 1735.89  3417.0 1734.28
  3854.5 1730.37  4011.7 1725.67  4223.5 1717.87  4232.1 1716.49  4462.7 1710.96
  4584.9 1710.12  4869.1 1708.52  4917.3 1711.30  4939.7 1709.27  5017.6 1708.81
  5218.1 1709.71  5242.3 1707.91  5242.8 1707.41  5262.5 1707.91  5272.5 1710.06
  5312.9 1712.55  5333.1 1710.50  5393.6 1709.69  5744.7 1712.59  5943.2 1715.48
  6310.1 1725.19  6427.2 1726.64  6490.4 1725.00  6542.0 1729.75  6712.4 1731.05
#Mann=8,-1,0
  3302.8   0.035       0  3417.0   0.045       0  4584.9    0.05       0
  4917.3    0.07       0  5017.6    0.05       0  5218.1    0.07       0
  5242.3    0.07       0  5262.5    0.07       0
Bank Sta=5242.3,5262.5
Exp/Cntr=0.3,0.1

Type RM Length L Ch R = 1,20820,725,725,725
BEGIN DESCRIPTION:
Mapping XS f7c8af25
END DESCRIPTION:
XS GIS Cut Line= 3
      1526458.60      6932711.73      1524698.17      6932654.44
      1523271.07      6933196.11
#Sta/Elev= 30
  3495.4 1734.25  3589.0 1734.74  3619.1 1731.93  3789.2 1728.21  3819.2 1729.24
  3849.2 1726.71  3999.3 1722.50  4189.4 1718.11  4249.4 1718.48  4299.4 1715.50
  4442.3 1712.70  4690.3 1707.68  4929.8 1708.15  4959.8 1709.96  4984.0 1706.71
  4984.5 1706.21  5004.2 1706.71  5019.8 1709.26  5109.9 1707.55  5129.9 1710.03
  5139.9 1707.48  5169.9 1706.95  5402.9 1708.15  5553.7 1708.55  5898.7 1710.36
  6123.7 1714.44  6137.2 1715.80  6308.4 1719.04  6597.2 1730.91  6783.2 1734.97
#Mann=6,-1,0
  3495.4   0.045       0  4442.3    0.05       0  4984.0    0.07       0
  5004.2    0.05       0  5402.9   0.035       0  5553.7    0.07       0
Bank Sta=4984,5004.2
Exp/Cntr=0.3,0.1

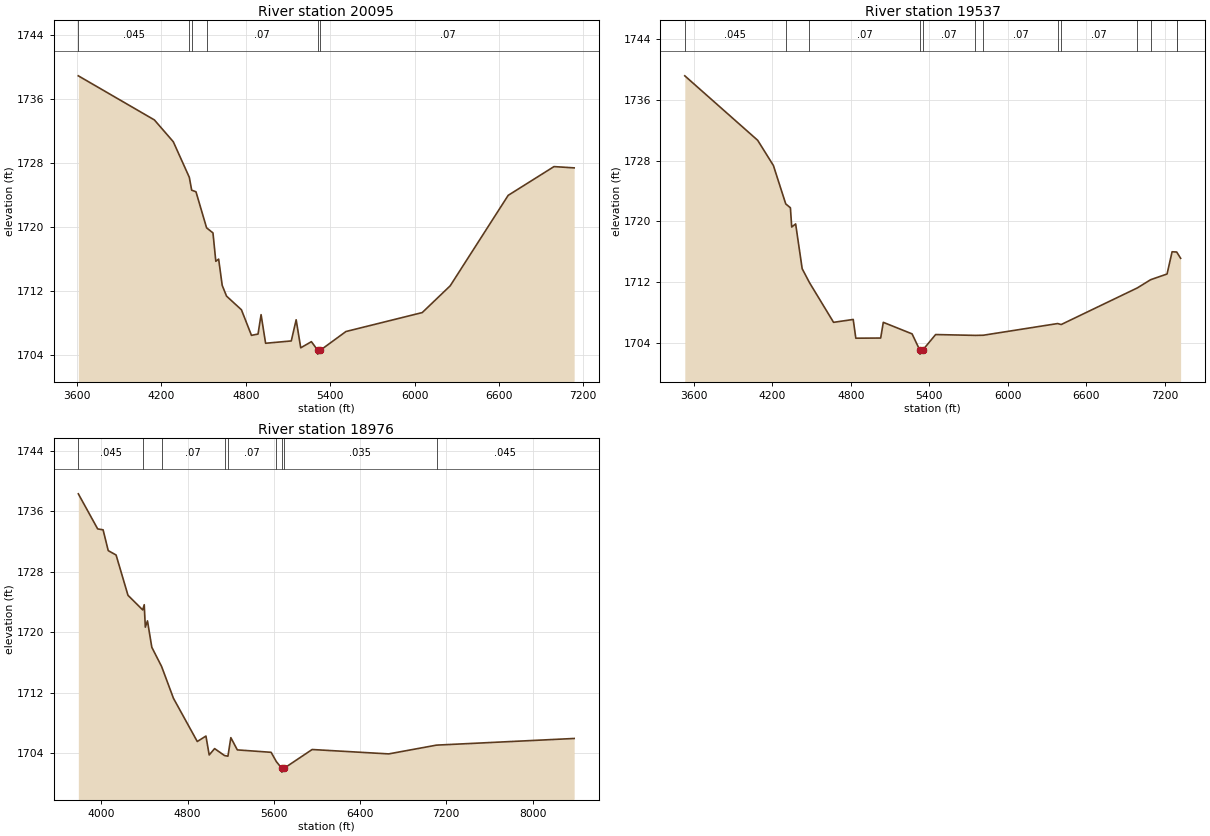
Type RM Length L Ch R = 1,20095,558,558,558
BEGIN DESCRIPTION:
Mapping XS 772ed7c9
END DESCRIPTION:
XS GIS Cut Line= 3
      1526125.27      6931836.73      1525109.63      6931961.73
      1522802.36      6932930.47
#Sta/Elev= 30
  3609.4 1738.95  4150.3 1733.43  4284.7 1730.70  4398.6 1726.25  4415.4 1724.64
  4445.9 1724.44  4521.3 1719.93  4566.8 1719.29  4587.0 1715.74  4607.1 1716.01
  4632.5 1712.72  4663.3 1711.38  4769.2 1709.67  4840.5 1706.47  4887.2 1706.63
  4908.9 1709.06  4941.0 1705.48  5123.6 1705.77  5158.3 1708.42  5190.9 1704.91
  5266.8 1705.68  5310.9 1704.62  5311.4 1704.12  5331.2 1704.62  5512.5 1706.95
  6054.9 1709.32  6253.7 1712.67  6665.9 1723.99  6991.7 1727.59  7135.1 1727.43
#Mann=6,-1,0
  3609.4   0.045       0  4398.6   0.035       0  4415.4   0.045       0
  4521.3    0.07       0  5310.9    0.07       0  5331.2    0.07       0
Bank Sta=5310.9,5331.2
Exp/Cntr=0.3,0.1

Type RM Length L Ch R = 1,19537,561,561,561
BEGIN DESCRIPTION:
Mapping XS 96dfe0c9
END DESCRIPTION:
XS GIS Cut Line= 3
      1526052.31      6931680.48      1523573.17      6931644.02
      1522412.08      6932253.20
#Sta/Elev= 30
  3531.3 1739.19  4088.7 1730.69  4208.7 1727.37  4303.0 1722.31  4338.7 1721.80
  4348.7 1719.26  4378.7 1719.67  4428.7 1713.77  4484.3 1711.94  4668.7 1706.70
  4818.8 1707.08  4838.8 1704.61  5028.8 1704.63  5048.8 1706.70  5268.8 1705.18
  5328.7 1703.01  5329.2 1702.51  5349.0 1703.01  5448.8 1705.09  5752.9 1704.98
  5813.5 1705.00  6381.8 1706.54  6408.8 1706.41  6991.4 1711.24  7092.7 1712.32
  7218.2 1713.07  7256.7 1716.00  7291.2 1715.97  7293.0 1715.94  7321.9 1715.14
#Mann=13,-1,0
  3531.3   0.045       0  4303.0   0.035       0  4484.3    0.07       0
  5328.7    0.07       0  5349.0    0.07       0  5752.9   0.035       0
  5813.5    0.07       0  6381.8   0.035       0  6408.8    0.07       0
  6991.4   0.035       0  7092.7    0.07       0  7291.2   0.045       0
  7293.0   0.035       0
Bank Sta=5328.7,5349
Exp/Cntr=0.3,0.1

Type RM Length L Ch R = 1,18976,593,593,593
BEGIN DESCRIPTION:
Mapping XS 6e1e2c8b
END DESCRIPTION:
XS GIS Cut Line= 3
      1525963.75      6931269.02      1523844.00      6931071.10
      1521442.92      6931654.45
#Sta/Elev= 30
  3786.0 1738.33  3965.5 1733.69  4015.7 1733.57  4063.4 1730.82  4136.3 1730.24
  4246.7 1724.91  4383.3 1722.98  4397.4 1723.67  4407.4 1720.70  4427.5 1721.53
  4467.7 1718.04  4558.5 1715.50  4668.6 1711.29  4889.5 1705.58  4969.9 1706.30
  5000.0 1703.80  5050.2 1704.64  5142.3 1703.72  5173.9 1703.64  5200.9 1706.09
  5261.1 1704.47  5574.7 1704.15  5622.6 1702.93  5673.6 1702.03  5674.1 1701.53
  5693.9 1702.03  5955.1 1704.52  6665.2 1703.94  7108.9 1705.10  8385.9 1705.98
#Mann=9,-1,0
  3786.0   0.045       0  4383.3   0.035       0  4558.5    0.07       0
  5142.3   0.035       0  5173.9    0.07       0  5622.6   0.035       0
  5673.6    0.07       0  5693.9   0.035       0  7108.9   0.045       0
Bank Sta=5673.6,5693.9
Exp/Cntr=0.3,0.1