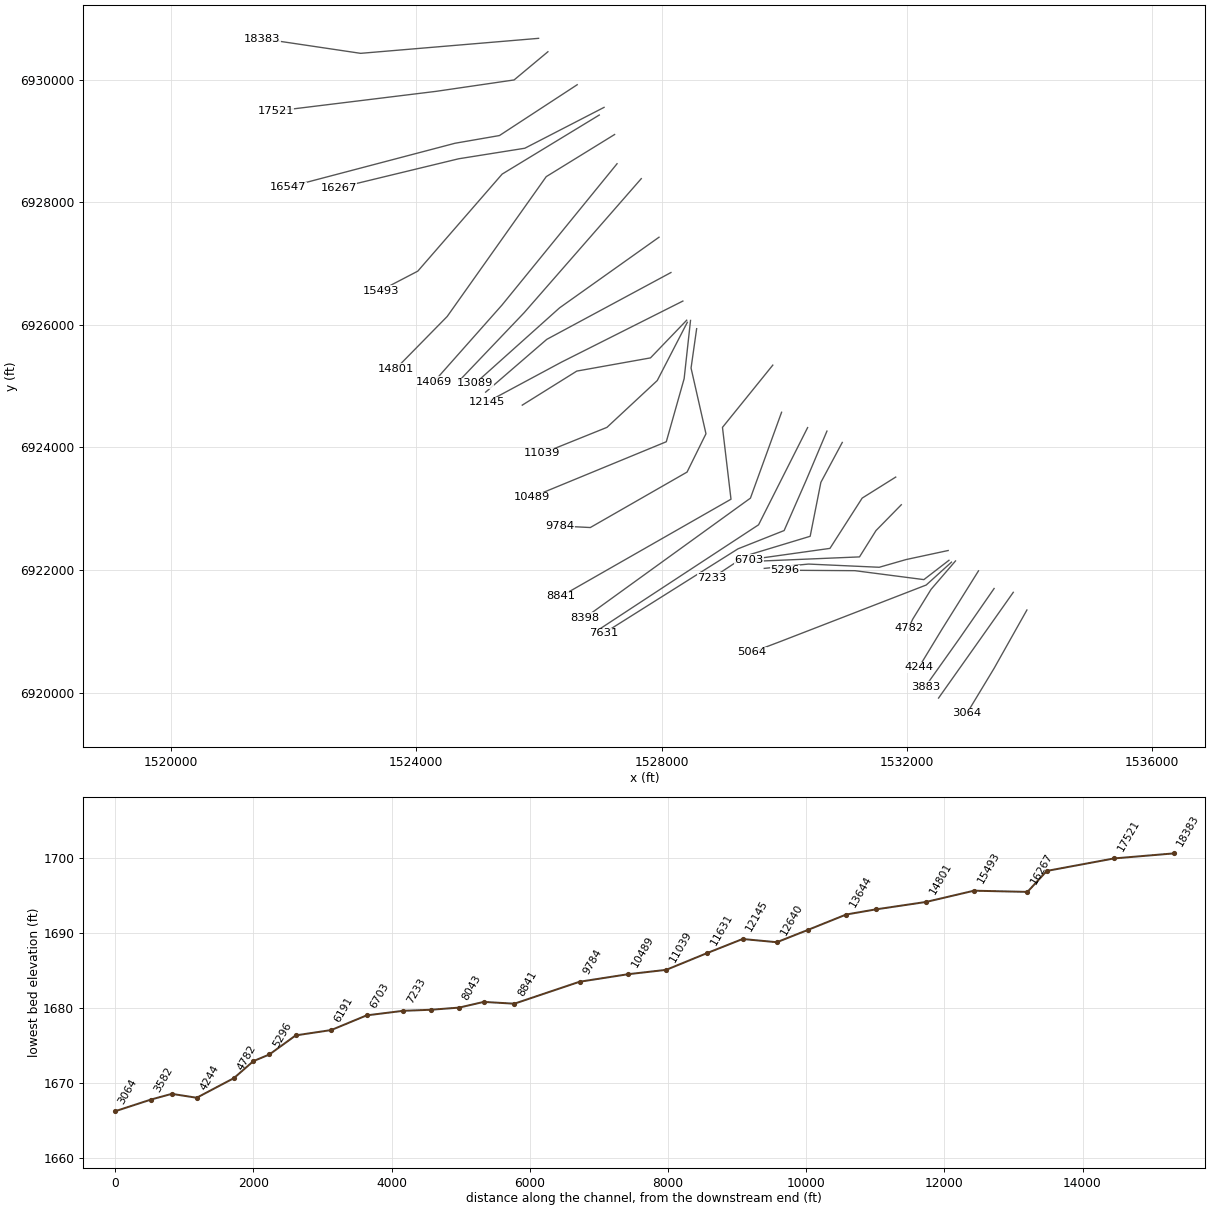
HEC-RAS study Dark Hollow Branch.prj: Dark Hollow Branch Base Level Engineering

--- Dark Hollow Branch.g01 (geometry) --- (continued)

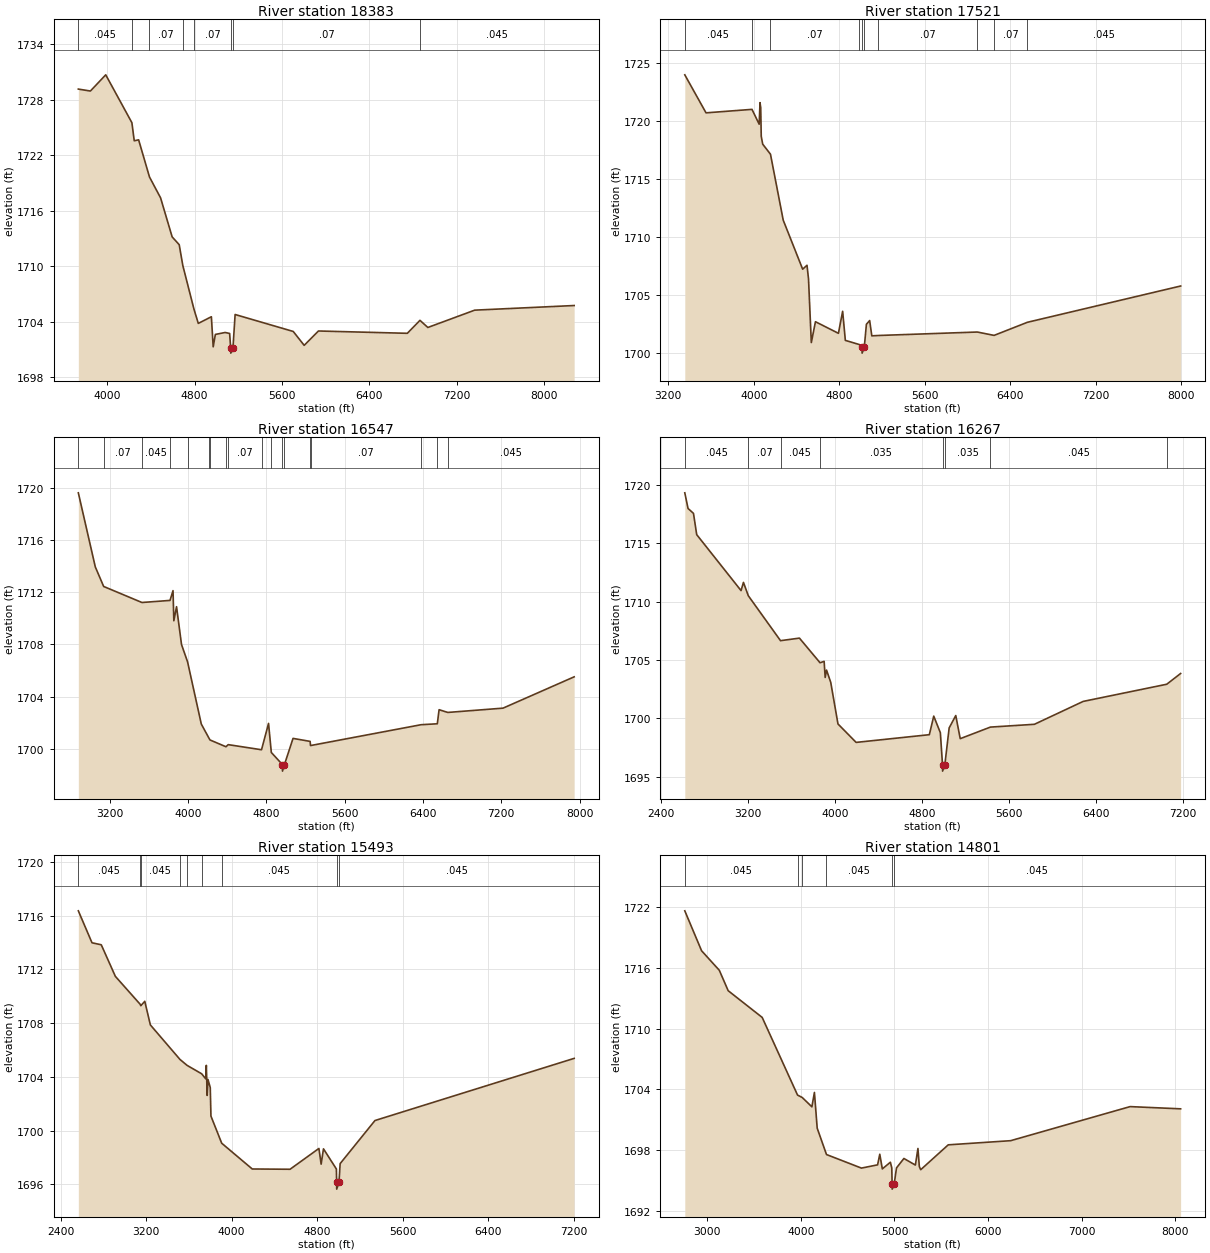
Type RM Length L Ch R = 1,18383,862,862,862
BEGIN DESCRIPTION:
Mapping XS 54274285
END DESCRIPTION:
XS GIS Cut Line= 3
      1525995.00      6930675.27      1523094.00      6930430.48
      1521484.64      6930670.06
#Sta/Elev= 30
  3736.1 1729.13  3846.5 1728.92  3987.0 1730.67  4226.4 1725.50  4247.9 1723.55
  4288.1 1723.65  4387.4 1719.64  4488.8 1717.39  4594.9 1713.17  4659.4 1712.33
  4692.5 1710.08  4794.2 1705.38  4834.2 1703.83  4953.9 1704.55  4970.5 1701.30
  4990.5 1702.64  5080.9 1702.85  5121.0 1702.74  5130.9 1701.12  5131.4 1700.62
  5151.2 1701.12  5171.2 1704.79  5703.1 1702.96  5803.4 1701.46  5933.9 1703.01
  6747.5 1702.76  6863.1 1704.16  6935.4 1703.39  7364.2 1705.26  8274.5 1705.76
#Mann=8,-1,0
  3736.1   0.045       0  4226.4   0.035       0  4387.4    0.07       0
  4692.5    0.16       0  4794.2    0.07       0  5130.9    0.07       0
  5151.2    0.07       0  6863.1   0.045       0
Bank Sta=5130.9,5151.2
Exp/Cntr=0.3,0.1

Type RM Length L Ch R = 1,17521,974,974,974
BEGIN DESCRIPTION:
Mapping XS e1273b60
END DESCRIPTION:
XS GIS Cut Line= 4
      1526146.93      6930456.50      1525595.74      6929996.45
      1524319.70      6929809.82      1521708.43      6929488.83
#Sta/Elev= 30
  3355.3 1723.96  3553.9 1720.68  3983.9 1720.98  4051.1 1719.70  4058.9 1721.56
  4065.4 1721.13  4070.5 1718.66  4084.1 1717.98  4156.9 1717.11  4276.1 1711.42
  4458.0 1707.19  4498.5 1707.53  4512.7 1706.35  4538.9 1700.86  4577.5 1702.66
  4792.4 1701.66  4832.0 1703.56  4857.2 1701.05  4988.2 1700.69  5013.8 1700.45
  5014.3 1699.95  5034.2 1700.45  5054.3 1702.44  5084.6 1702.76  5104.9 1701.44
  5162.1 1701.47  6091.4 1701.77  6248.6 1701.48  6560.2 1702.61  7993.8 1705.74
#Mann=10,-1,0
  3355.3   0.045       0  3983.9   0.035       0  4156.9    0.07       0
  4988.2   0.035       0  5013.8   0.035       0  5034.2   0.035       0
  5162.1    0.07       0  6091.4   0.035       0  6248.6    0.07       0
  6560.2   0.045       0
Bank Sta=5013.8,5034.2
Exp/Cntr=0.3,0.1

Type RM Length L Ch R = 1,16547,280,280,280
BEGIN DESCRIPTION:
Mapping XS 399ff3e1
END DESCRIPTION:
XS GIS Cut Line= 4
      1526624.35      6929918.30      1525357.02      6929089.33
      1524632.20      6928963.46      1521910.89      6928247.33
#Sta/Elev= 30
  2880.1 1719.62  3053.4 1713.94  3138.8 1712.44  3529.8 1711.21  3816.5 1711.37
  3847.2 1712.12  3855.6 1709.81  3883.1 1710.89  3933.9 1707.99  3995.8 1706.66
  4136.0 1701.89  4214.2 1700.81  4224.9 1700.67  4387.8 1700.15  4411.1 1700.31
  4751.2 1699.92  4822.8 1701.94  4851.2 1699.71  4964.8 1698.78  4965.3 1698.28
  4985.2 1698.78  5072.9 1700.79  5247.5 1700.56  5251.7 1700.24  6381.7 1701.84
  6546.6 1701.91  6564.6 1702.99  6653.7 1702.78  7217.9 1703.11  7944.1 1705.51
#Mann=18,-1,0
  2880.1   0.045       0  3138.8    0.07       0  3529.8   0.045       0
  3816.5   0.035       0  3995.8    0.07       0  4214.2   0.035       0
  4224.9    0.07       0  4387.8   0.035       0  4411.1    0.07       0
  4751.2   0.035       0  4851.2    0.07       0  4964.8    0.07       0
  4985.2    0.07       0  5247.5   0.035       0  5251.7    0.07       0
  6381.7   0.045       0  6546.6   0.035       0  6653.7   0.045       0
Bank Sta=4964.8,4985.2
Exp/Cntr=0.3,0.1

Type RM Length L Ch R = 1,16267,774,774,774
BEGIN DESCRIPTION:
Mapping XS b7c0184a
END DESCRIPTION:
XS GIS Cut Line= 4
      1527062.32      6929548.93      1525770.62      6928882.24
      1524692.50      6928710.37      1522734.17      6928236.41
#Sta/Elev= 30
  2619.3 1719.31  2649.2 1717.97  2699.2 1717.55  2728.8 1715.73  3136.6 1710.94
  3158.8 1711.64  3203.3 1710.50  3499.7 1706.65  3673.6 1706.87  3863.2 1704.76
  3900.8 1704.88  3910.4 1703.50  3923.0 1704.13  3961.6 1703.08  4028.1 1699.52
  4195.1 1697.94  4868.4 1698.60  4908.9 1700.19  4969.7 1698.77  4989.9 1695.98
  4990.4 1695.48  5010.3 1695.98  5050.7 1699.18  5111.5 1700.24  5152.5 1698.26
  5430.0 1699.25  5834.8 1699.49  6283.5 1701.45  7051.9 1702.92  7179.5 1703.84
#Mann=8,-1,0
  2619.3   0.045       0  3203.3    0.07       0  3499.7   0.045       0
  3863.2   0.035       0  4989.9   0.035       0  5010.3   0.035       0
  5430.0   0.045       0  7051.9   0.035       0
Bank Sta=4989.9,5010.3
Exp/Cntr=0.3,0.1

Type RM Length L Ch R = 1,15493,692,692,692
BEGIN DESCRIPTION:
Mapping XS a0e73f8d
END DESCRIPTION:
XS GIS Cut Line= 4
      1526984.19      6929423.92      1525400.83      6928460.37
      1524025.83      6926877.03      1523418.20      6926560.23
#Sta/Elev= 30
  2566.4 1716.37  2694.2 1713.99  2780.9 1713.84  2912.6 1711.49  3145.5 1709.40
  3150.1 1709.30  3187.7 1709.63  3240.0 1707.87  3516.8 1705.30  3582.9 1704.86
  3719.8 1704.23  3757.2 1703.86  3763.1 1704.86  3771.2 1702.62  3778.5 1703.81
  3799.9 1703.20  3806.3 1701.08  3906.9 1699.06  4192.6 1697.14  4546.0 1697.12
  4815.7 1698.67  4836.6 1697.50  4858.5 1698.64  4979.1 1697.14  4981.6 1696.14
  4982.1 1695.64  5003.5 1696.14  5014.2 1697.54  5339.9 1700.75  7202.2 1705.38
#Mann=9,-1,0
  2566.4   0.045       0  3145.5    0.07       0  3150.1   0.045       0
  3516.8    0.07       0  3582.9   0.045       0  3719.8   0.035       0
  3906.9   0.045       0  4981.6   0.045       0  5003.5   0.045       0
Bank Sta=4981.6,5003.5
Exp/Cntr=0.3,0.1

Type RM Length L Ch R = 1,14801,732,732,732
BEGIN DESCRIPTION:
Mapping XS 8f08914e
END DESCRIPTION:
XS GIS Cut Line= 4
      1527234.16      6929106.20      1526119.58      6928418.70
      1524505.00      6926137.45      1523671.65      6925288.48
#Sta/Elev= 30
  2761.6 1721.66  2940.9 1717.71  3130.2 1715.78  3224.8 1713.76  3587.9 1711.12
  3965.5 1703.44  4015.6 1703.20  4118.6 1702.28  4145.7 1703.70  4175.2 1700.17
  4274.5 1697.56  4647.8 1696.22  4820.1 1696.54  4843.5 1697.59  4870.6 1696.14
  4956.7 1696.80  4971.5 1696.25  4975.3 1694.64  4975.8 1694.14  4997.2 1694.64
  5022.0 1696.24  5101.1 1697.17  5223.6 1696.52  5250.9 1698.16  5265.7 1696.37
  5280.4 1696.06  5574.6 1698.52  6240.5 1698.93  7516.1 1702.30  8055.6 1702.08
#Mann=6,-1,0
  2761.6   0.045       0  3965.5    0.07       0  4015.6   0.035       0
  4274.5   0.045       0  4975.3   0.045       0  4997.2   0.045       0
Bank Sta=4975.3,4997.2
Exp/Cntr=0.3,0.1

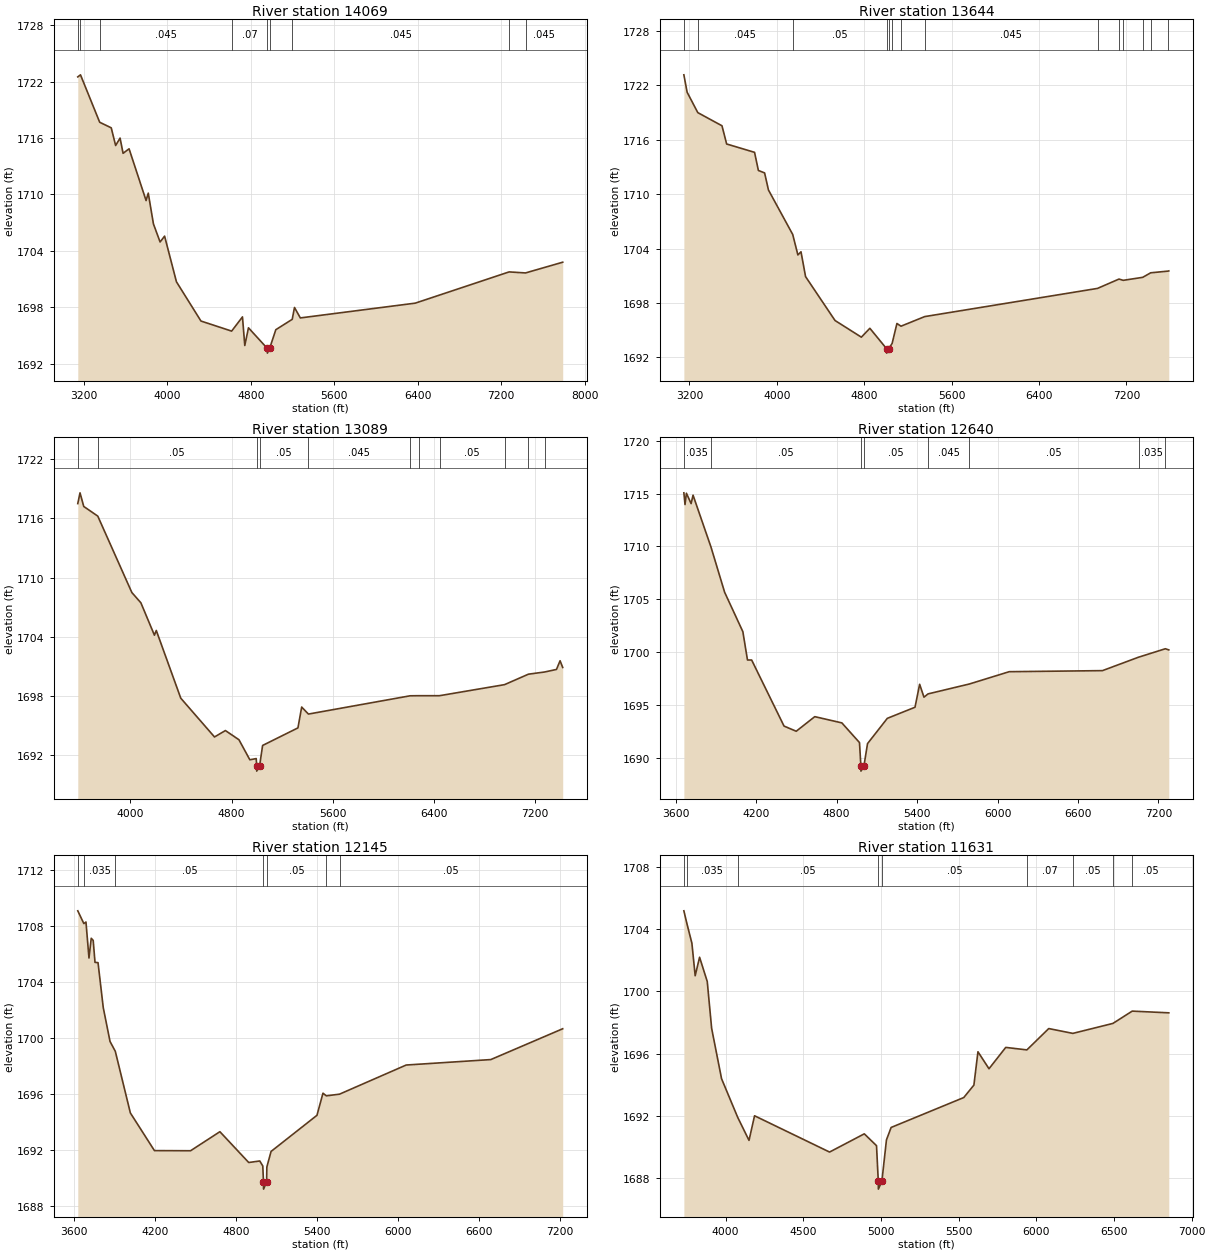
Type RM Length L Ch R = 1,14069,425,425,425
BEGIN DESCRIPTION:
Mapping XS 7319eeb8
END DESCRIPTION:
XS GIS Cut Line= 3
      1527274.12      6928629.38      1525399.09      6926324.66
      1524287.98      6925070.31
#Sta/Elev= 30
  3141.4 1722.49  3167.3 1722.71  3351.3 1717.67  3461.9 1717.08  3504.1 1715.20
  3546.7 1715.99  3575.4 1714.37  3632.9 1714.85  3795.9 1709.35  3816.7 1710.14
  3866.3 1706.87  3930.2 1704.95  3973.3 1705.57  4086.8 1700.72  4321.6 1696.55
  4615.8 1695.48  4719.5 1696.99  4741.7 1693.95  4777.0 1695.83  4957.7 1693.64
  4958.2 1693.14  4979.7 1693.64  5039.1 1695.63  5196.2 1696.73  5218.0 1697.99
  5274.0 1696.88  6375.2 1698.45  7274.7 1701.77  7431.7 1701.66  7788.2 1702.80
#Mann=9,-1,0
  3141.4   0.045       0  3167.3   0.035       0  3351.3   0.045       0
  4615.8    0.07       0  4957.7    0.07       0  4979.7    0.07       0
  5196.2   0.045       0  7274.7   0.035       0  7431.7   0.045       0
Bank Sta=4957.7,4979.7
Exp/Cntr=0.3,0.1

Type RM Length L Ch R = 1,13644,555,555,555
BEGIN DESCRIPTION:
Mapping XS 076300be
END DESCRIPTION:
XS GIS Cut Line= 3
      1527669.05      6928386.28      1525759.34      6926198.79
      1524700.29      6925087.66
#Sta/Elev= 30
  3149.0 1723.16  3178.9 1721.24  3276.5 1718.99  3497.9 1717.54  3540.6 1715.53
  3796.0 1714.61  3831.1 1712.61  3888.0 1712.34  3923.2 1710.46  4145.4 1705.55
  4192.7 1703.29  4221.2 1703.64  4263.0 1700.90  4532.6 1696.06  4773.7 1694.22
  4851.5 1695.20  5003.8 1692.96  5004.3 1692.46  5025.8 1692.96  5055.6 1693.54
  5099.3 1695.73  5136.5 1695.43  5353.3 1696.49  6935.5 1699.60  7132.0 1700.63
  7170.6 1700.49  7349.2 1700.82  7421.8 1701.32  7582.6 1701.51  7587.8 1701.53
#Mann=14,-1,0
  3149.0   0.035       0  3276.5   0.045       0  4145.4    0.05       0
  5003.8    0.05       0  5025.8    0.05       0  5055.6    0.07       0
  5136.5    0.05       0  5353.3   0.045       0  6935.5    0.07       0
  7132.0   0.045       0  7170.6    0.07       0  7349.2   0.035       0
  7421.8    0.07       0  7582.6   0.035       0
Bank Sta=5003.8,5025.8
Exp/Cntr=0.3,0.1

Type RM Length L Ch R = 1,13089,449,449,449
BEGIN DESCRIPTION:
Mapping XS 5e71ad2a
END DESCRIPTION:
XS GIS Cut Line= 3
      1527958.10      6927430.55      1526336.59      6926277.79
      1524965.09      6925048.64
#Sta/Elev= 30
  3585.5 1717.50  3603.1 1718.59  3632.6 1717.21  3743.5 1716.23  4012.7 1708.49
  4084.0 1707.45  4191.0 1704.17  4205.7 1704.65  4399.1 1697.79  4665.7 1693.86
  4751.8 1694.51  4858.8 1693.58  4944.9 1691.55  4995.3 1691.67  4998.7 1690.90
  4999.2 1690.40  5021.5 1690.90  5045.7 1693.00  5324.9 1694.78  5354.4 1696.89
  5407.7 1696.18  6211.0 1698.03  6282.5 1698.04  6443.5 1698.04  6957.1 1699.16
  7146.0 1700.22  7273.1 1700.44  7367.5 1700.70  7395.9 1701.58  7416.7 1700.90
#Mann=11,-1,0
  3585.5   0.035       0  3743.5    0.05       0  4998.7    0.05       0
  5021.5    0.05       0  5407.7   0.045       0  6211.0    0.05       0
  6282.5   0.045       0  6443.5    0.05       0  6957.1    0.07       0
  7146.0   0.035       0  7273.1    0.07       0
Bank Sta=4998.7,5021.5
Exp/Cntr=0.3,0.1

Type RM Length L Ch R = 1,12640,495,495,495
BEGIN DESCRIPTION:
Mapping XS 1099aa24
END DESCRIPTION:
XS GIS Cut Line= 3
      1528152.61      6926854.20      1526128.26      6925763.90
      1525131.83      6924902.87
#Sta/Elev= 30
  3661.1 1715.07  3669.7 1713.96  3680.1 1715.03  3715.2 1714.05  3729.5 1714.85
  3863.2 1709.95  3965.1 1705.67  4101.1 1701.94  4135.4 1699.27  4166.8 1699.26
  4408.0 1693.02  4498.9 1692.53  4637.3 1693.91  4839.3 1693.32  4970.7 1691.46
  4981.1 1689.26  4981.6 1688.76  5004.0 1689.26  5030.7 1691.36  5178.3 1693.75
  5384.8 1694.80  5419.3 1696.97  5451.7 1695.75  5481.7 1696.06  5791.0 1697.00
  6087.2 1698.16  6782.6 1698.26  7051.6 1699.53  7251.9 1700.33  7277.3 1700.22
#Mann=8,-1,0
  3661.1   0.035       0  3863.2    0.05       0  4981.1    0.05       0
  5004.0    0.05       0  5481.7   0.045       0  5791.0    0.05       0
  7051.6   0.035       0  7251.9    0.05       0
Bank Sta=4981.1,5004
Exp/Cntr=0.3,0.1

Type RM Length L Ch R = 1,12145,514,514,514
BEGIN DESCRIPTION:
Mapping XS b8dc41b0
END DESCRIPTION:
XS GIS Cut Line= 3
      1528347.02      6926388.90      1526367.84      6925392.37
      1525152.56      6924739.59
#Sta/Elev= 30
  3627.9 1709.06  3672.8 1708.15  3688.6 1708.26  3710.9 1705.69  3727.6 1707.10
  3742.1 1706.95  3755.6 1705.38  3777.9 1705.36  3816.9 1702.14  3867.1 1699.73
  3906.1 1699.03  4017.7 1694.63  4196.2 1691.94  4464.0 1691.93  4681.6 1693.29
  4895.3 1691.09  4977.2 1691.20  4999.6 1690.84  5004.8 1689.69  5005.3 1689.19
  5027.8 1689.69  5029.7 1690.77  5060.9 1691.88  5401.2 1694.46  5445.8 1696.04
  5470.7 1695.85  5568.4 1695.97  6062.7 1698.05  6690.2 1698.44  7223.3 1700.64
#Mann=7,-1,0
  3627.9   0.045       0  3672.8   0.035       0  3906.1    0.05       0
  5004.8    0.05       0  5027.8    0.05       0  5470.7   0.045       0
  5568.4    0.05       0
Bank Sta=5004.8,5027.8
Exp/Cntr=0.3,0.1

Type RM Length L Ch R = 1,11631,592,592,592
BEGIN DESCRIPTION:
Mapping XS ecf3895c
END DESCRIPTION:
XS GIS Cut Line= 4
      1528409.53      6926076.41      1527819.23      6925461.82
      1526617.84      6925246.54      1525728.96      6924690.98
#Sta/Elev= 30
  3731.9 1705.18  3752.0 1704.34  3783.6 1703.10  3804.7 1701.01  3833.0 1702.20
  3882.4 1700.64  3910.7 1697.63  3974.5 1694.40  4077.9 1691.93  4151.2 1690.44
  4186.8 1692.02  4669.6 1689.69  4893.1 1690.86  4971.8 1690.10  4983.2 1687.81
  4983.7 1687.31  5006.2 1687.81  5035.7 1690.47  5065.8 1691.27  5533.2 1693.19
  5598.5 1693.99  5624.6 1696.13  5695.7 1695.04  5803.5 1696.41  5939.5 1696.25
  6080.2 1697.62  6235.2 1697.31  6493.2 1697.95  6617.4 1698.74  6852.8 1698.63
#Mann=9,-1,0
  3731.9   0.045       0  3752.0   0.035       0  4077.9    0.05       0
  4983.2    0.05       0  5006.2    0.05       0  5939.5    0.07       0
  6235.2    0.05       0  6493.2    0.07       0  6617.4    0.05       0
Bank Sta=4983.2,5006.2
Exp/Cntr=0.3,0.1

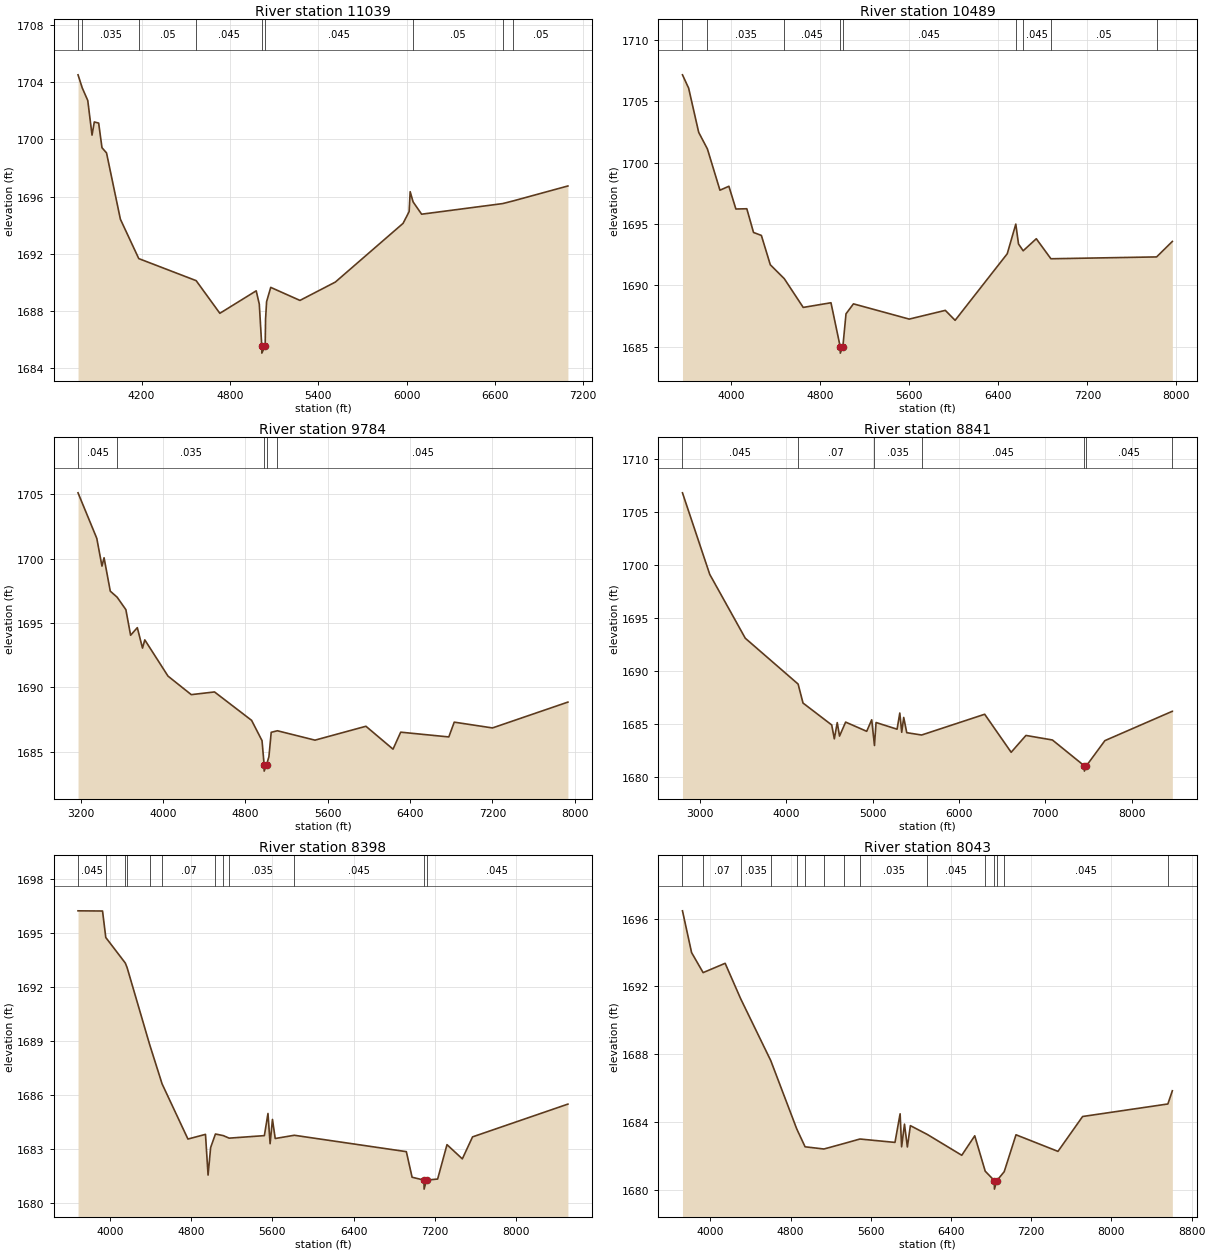
Type RM Length L Ch R = 1,11039,550,550,550
BEGIN DESCRIPTION:
Mapping XS c2dabdea
END DESCRIPTION:
XS GIS Cut Line= 4
      1528419.93      6926042.55      1527929.48      6925092.02
      1527109.16      6924328.13      1526054.79      6923902.91
#Sta/Elev= 30
  3768.7 1704.50  3797.6 1703.58  3834.8 1702.71  3863.8 1700.29  3879.2 1701.21
  3908.8 1701.13  3931.4 1699.41  3962.2 1699.05  4056.4 1694.42  4181.2 1691.67
  4571.1 1690.13  4732.0 1687.85  4978.9 1689.42  4999.9 1688.49  5016.7 1685.57
  5017.2 1685.07  5039.8 1685.57  5042.4 1687.42  5049.4 1688.66  5077.6 1689.66
  5276.0 1688.75  5516.3 1690.03  5976.4 1694.13  6017.6 1694.95  6024.7 1696.34
  6044.5 1695.63  6102.5 1694.77  6652.8 1695.51  6725.6 1695.70  7096.1 1696.74
#Mann=9,-1,0
  3768.7   0.045       0  3797.6   0.035       0  4181.2    0.05       0
  4571.1   0.045       0  5016.7   0.045       0  5039.8   0.045       0
  6044.5    0.05       0  6652.8    0.07       0  6725.6    0.05       0
Bank Sta=5016.7,5039.8
Exp/Cntr=0.3,0.1

Type RM Length L Ch R = 1,10489,705,705,705
BEGIN DESCRIPTION:
Mapping XS 34e9ad57
END DESCRIPTION:
XS GIS Cut Line= 4
      1528472.01      6926072.93      1528367.84      6925122.41
      1528077.05      6924093.76      1525878.22      6923187.34
#Sta/Elev= 30
  3559.9 1707.14  3615.2 1706.06  3705.7 1702.46  3783.9 1701.11  3896.8 1697.75
  3977.3 1698.07  4040.0 1696.22  4138.3 1696.24  4198.6 1694.31  4269.1 1694.07
  4349.5 1691.68  4475.0 1690.55  4645.4 1688.21  4894.8 1688.59  4978.2 1684.99
  4978.7 1684.49  5001.4 1684.99  5029.9 1687.69  5096.9 1688.50  5598.1 1687.26
  5922.6 1687.97  6010.7 1687.16  6479.4 1692.58  6556.1 1694.99  6580.6 1693.37
  6622.6 1692.82  6740.4 1693.80  6871.7 1692.17  7821.9 1692.32  7963.4 1693.58
#Mann=9,-1,0
  3559.9   0.045       0  3783.9   0.035       0  4475.0   0.045       0
  4978.2   0.045       0  5001.4   0.045       0  6556.1    0.05       0
  6622.6   0.045       0  6871.7    0.05       0  7821.9   0.045       0
Bank Sta=4978.2,5001.4
Exp/Cntr=0.3,0.1

Type RM Length L Ch R = 1,9784,943,943,943
BEGIN DESCRIPTION:
Mapping XS aea6b7d9
END DESCRIPTION:
XS GIS Cut Line= 6
      1528571.84      6925938.36      1528480.69      6925296.02
      1528723.75      6924223.97      1528415.59      6923598.97
      1526838.09      6922694.09      1526341.52      6922719.52
#Sta/Elev= 30
  3173.3 1705.13  3355.5 1701.59  3406.0 1699.43  3426.2 1700.08  3486.8 1697.48
  3553.3 1697.01  3638.3 1696.04  3684.2 1694.05  3749.4 1694.64  3799.9 1693.05
  3822.1 1693.69  4047.9 1690.87  4273.8 1689.43  4499.6 1689.64  4860.0 1687.43
  4961.4 1685.85  4981.7 1683.98  4982.2 1683.48  5005.3 1683.98  5028.3 1684.60
  5050.6 1686.50  5110.8 1686.62  5476.2 1685.89  5971.2 1686.97  6234.4 1685.19
  6309.1 1686.51  6776.6 1686.14  6829.3 1687.29  7200.9 1686.84  7934.0 1688.85
#Mann=5,-1,0
  3173.3   0.045       0  3553.3   0.035       0  4981.7   0.035       0
  5005.3   0.035       0  5110.8   0.045       0
Bank Sta=4981.7,5005.3
Exp/Cntr=0.3,0.1

Type RM Length L Ch R = 1,8841,443,443,443
BEGIN DESCRIPTION:
Mapping XS bdfb0b84
END DESCRIPTION:
XS GIS Cut Line= 4
      1529813.13      6925343.72      1528992.84      6924328.13
      1529131.73      6923156.26      1526363.73      6921573.96
#Sta/Elev= 30
  2798.5 1706.83  3114.4 1699.13  3525.9 1693.10  4138.0 1688.77  4194.7 1686.98
  4527.1 1684.91  4557.3 1683.60  4591.1 1685.13  4617.7 1683.86  4688.2 1685.18
  4932.2 1684.31  4990.3 1685.40  5022.3 1682.97  5040.6 1685.14  5284.1 1684.51
  5315.7 1686.04  5337.9 1684.22  5360.9 1685.62  5396.3 1684.18  5568.3 1683.96
  6298.9 1685.92  6605.5 1682.33  6776.8 1683.92  7083.5 1683.49  7453.1 1681.05
  7453.6 1680.55  7476.7 1681.05  7691.0 1683.43  8471.6 1686.20  8472.4 1686.20
#Mann=7,-1,0
  2798.5   0.045       0  4138.0    0.07       0  5022.3   0.035       0
  5568.3   0.045       0  7453.1    0.07       0  7476.7   0.045       0
  8471.6   0.035       0
Bank Sta=7453.1,7476.7
Exp/Cntr=0.3,0.1

Type RM Length L Ch R = 1,8398,355,355,355
BEGIN DESCRIPTION:
Mapping XS 9dad3561
END DESCRIPTION:
XS GIS Cut Line= 3
      1529956.37      6924574.62      1529448.57      6923173.62
      1526750.40      6921222.68
#Sta/Elev= 30
  3687.8 1696.24  3928.9 1696.23  3960.8 1694.76  4153.1 1693.34  4171.1 1693.08
  4392.2 1688.82  4515.0 1686.63  4769.1 1683.57  4941.8 1683.83  4967.2 1681.57
  4992.5 1683.10  5039.7 1683.85  5117.5 1683.76  5174.5 1683.62  5521.1 1683.76
  5556.6 1684.99  5577.5 1683.31  5600.8 1684.66  5627.8 1683.60  5815.7 1683.78
  6918.0 1682.87  6974.5 1681.45  7092.2 1681.29  7092.7 1680.79  7116.7 1681.29
  7225.9 1681.35  7317.9 1683.26  7468.8 1682.47  7569.3 1683.69  8507.6 1685.51
#Mann=12,-1,0
  3687.8   0.045       0  3960.8    0.07       0  4153.1   0.035       0
  4171.1    0.07       0  4392.2   0.035       0  4515.0    0.07       0
  5039.7   0.035       0  5117.5    0.07       0  5174.5   0.035       0
  5815.7   0.045       0  7092.2    0.07       0  7116.7   0.045       0
Bank Sta=7092.2,7116.7
Exp/Cntr=0.3,0.1

Type RM Length L Ch R = 1,8043,412,412,412
BEGIN DESCRIPTION:
Mapping XS e4d353a7
END DESCRIPTION:
XS GIS Cut Line= 3
      1530380.86      6924324.66      1529581.39      6922738.72
      1526981.23      6921032.20
#Sta/Elev= 30
  3721.3 1696.47  3812.4 1694.00  3927.3 1692.82  4147.0 1693.37  4301.5 1691.28
  4602.1 1687.62  4860.9 1683.59  4944.4 1682.53  5132.1 1682.40  5335.3 1682.73
  5491.2 1682.99  5840.9 1682.79  5892.1 1684.48  5907.2 1682.53  5935.6 1683.87
  5964.5 1682.52  5994.6 1683.78  6163.4 1683.26  6507.0 1682.03  6636.5 1683.18
  6740.9 1681.09  6832.4 1680.53  6832.9 1680.03  6857.0 1680.53  6930.4 1681.06
  7048.0 1683.24  7466.7 1682.26  7712.4 1684.32  8562.8 1685.06  8607.5 1685.84
#Mann=15,-1,0
  3721.3   0.035       0  3927.3    0.07       0  4301.5   0.035       0
  4602.1    0.07       0  4860.9   0.035       0  4944.4    0.07       0
  5132.1   0.035       0  5335.3    0.07       0  5491.2   0.035       0
  6163.4   0.045       0  6740.9    0.07       0  6832.4    0.07       0
  6857.0    0.07       0  6930.4   0.045       0  8562.8   0.035       0
Bank Sta=6832.4,6857
Exp/Cntr=0.3,0.1

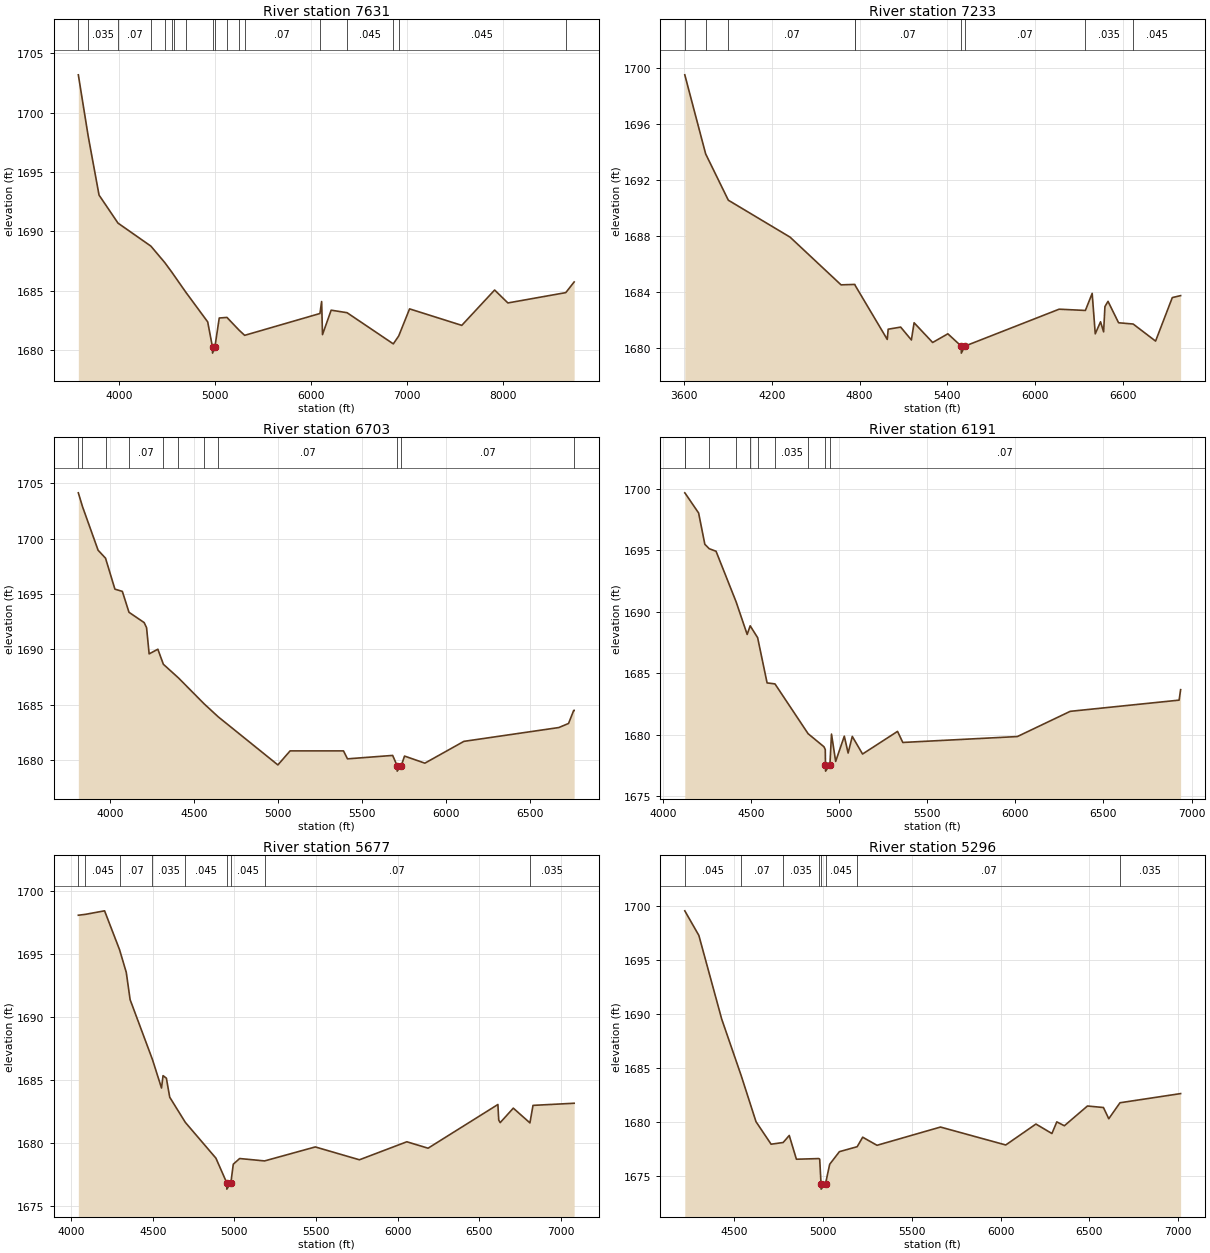
Type RM Length L Ch R = 1,7631,398,398,398
BEGIN DESCRIPTION:
Mapping XS d86f9079
END DESCRIPTION:
XS GIS Cut Line= 5
      1530695.96      6924267.35      1530357.43      6923465.29
      1529998.05      6922644.97      1529245.63      6922346.50
      1527053.81      6920966.30
#Sta/Elev= 30
  3575.4 1703.20  3677.8 1698.05  3791.4 1693.06  3988.7 1690.70  4331.3 1688.76
  4476.3 1687.37  4552.6 1686.53  4570.5 1686.32  4694.9 1684.88  4923.4 1682.37
  4973.3 1680.24  4973.8 1679.74  4997.9 1680.24  5043.5 1682.70  5123.8 1682.75
  5249.6 1681.68  5308.3 1681.24  6092.7 1683.08  6110.2 1684.09  6119.4 1681.30
  6209.4 1683.36  6374.8 1683.15  6857.0 1680.52  6913.5 1681.19  7026.5 1683.47
  7570.4 1682.08  7912.6 1685.06  8050.8 1683.97  8653.8 1684.84  8741.2 1685.74
#Mann=18,-1,0
  3575.4    0.07       0  3677.8   0.035       0  3988.7    0.07       0
  4331.3   0.035       0  4476.3    0.07       0  4552.6   0.035       0
  4570.5    0.07       0  4694.9   0.035       0  4973.3   0.035       0
  4997.9   0.035       0  5123.8    0.07       0  5249.6   0.035       0
  5308.3    0.07       0  6092.7   0.035       0  6374.8   0.045       0
  6857.0    0.07       0  6913.5   0.045       0  8653.8   0.035       0
Bank Sta=4973.3,4997.9
Exp/Cntr=0.3,0.1

Type RM Length L Ch R = 1,7233,530,530,530
BEGIN DESCRIPTION:
Mapping XS 1f276a38
END DESCRIPTION:
XS GIS Cut Line= 5
      1530945.95      6924082.44      1530597.01      6923431.43
      1530422.53      6922551.22      1529374.68      6922233.84
      1528824.15      6921870.59
#Sta/Elev= 30
  3605.1 1699.49  3747.7 1693.84  3902.7 1690.53  4324.9 1687.89  4673.5 1684.48
  4767.4 1684.51  4771.2 1684.42  4989.5 1680.58  4995.8 1681.31  5081.2 1681.46
  5154.5 1680.54  5173.0 1681.77  5299.9 1680.36  5403.9 1680.98  5495.6 1680.10
  5496.1 1679.60  5520.2 1680.10  6164.8 1682.74  6344.3 1682.65  6390.7 1683.87
  6411.8 1680.98  6447.9 1681.84  6468.9 1681.12  6478.0 1682.93  6499.1 1683.30
  6571.3 1681.77  6671.0 1681.68  6824.2 1680.46  6938.6 1683.57  6995.5 1683.71
#Mann=9,-1,0
  3605.1    0.07       0  3747.7   0.035       0  3902.7    0.07       0
  4767.4   0.035       0  4771.2    0.07       0  5495.6    0.07       0
  5520.2    0.07       0  6344.3   0.035       0  6671.0   0.045       0
Bank Sta=5495.6,5520.2
Exp/Cntr=0.3,0.1

Type RM Length L Ch R = 1,6703,512,512,512
BEGIN DESCRIPTION:
Mapping XS e2df6ad0
END DESCRIPTION:
XS GIS Cut Line= 4
      1531817.09      6923517.17      1531270.19      6923174.27
      1530745.01      6922353.96      1529424.57      6922168.73
#Sta/Elev= 30
  3810.3 1704.15  3835.0 1702.91  3928.0 1698.96  3972.3 1698.24  4028.2 1695.44
  4072.4 1695.24  4112.0 1693.35  4202.3 1692.42  4216.7 1691.96  4232.0 1689.59
  4283.9 1690.01  4316.8 1688.65  4406.4 1687.42  4560.4 1685.06  4643.4 1683.90
  4998.8 1679.55  5071.5 1680.82  5389.4 1680.82  5413.2 1680.10  5682.3 1680.41
  5708.7 1679.49  5709.2 1678.99  5733.7 1679.49  5753.0 1680.35  5874.2 1679.71
  6106.4 1681.68  6671.9 1682.93  6729.9 1683.30  6760.5 1684.48  6763.2 1684.48
#Mann=11,-1,0
  3810.3   0.045       0  3835.0    0.07       0  3972.3   0.035       0
  4112.0    0.07       0  4316.8   0.035       0  4406.4    0.07       0
  4560.4   0.035       0  4643.4    0.07       0  5708.7    0.07       0
  5733.7    0.07       0  6760.5   0.035       0
Bank Sta=5708.7,5733.7
Exp/Cntr=0.3,0.1

Type RM Length L Ch R = 1,6191,514,514,514
BEGIN DESCRIPTION:
Mapping XS cfb5fd8e
END DESCRIPTION:
XS GIS Cut Line= 4
      1531908.20      6923065.76      1531495.88      6922644.76
      1531226.79      6922215.07      1529508.58      6922142.75
#Sta/Elev= 30
  4122.2 1699.65  4123.1 1699.64  4200.7 1698.01  4236.0 1695.47  4260.7 1695.11
  4299.7 1694.90  4413.9 1690.78  4476.5 1688.14  4493.5 1688.84  4535.8 1687.88
  4589.6 1684.20  4634.3 1684.12  4822.7 1680.07  4912.6 1679.01  4920.0 1678.78
  4921.2 1677.53  4921.7 1677.03  4946.3 1677.53  4955.4 1680.04  4979.0 1677.82
  5028.1 1679.87  5049.8 1678.50  5073.4 1679.85  5131.8 1678.42  5330.4 1680.26
  5360.4 1679.36  6011.0 1679.84  6311.2 1681.89  6929.6 1682.80  6938.2 1683.65
#Mann=10,-1,0
  4122.2   0.045       0  4123.1    0.07       0  4260.7   0.035       0
  4413.9    0.07       0  4493.5   0.035       0  4535.8    0.07       0
  4634.3   0.035       0  4822.7    0.07       0  4921.2    0.07       0
  4946.3    0.07       0
Bank Sta=4921.2,4946.3
Exp/Cntr=0.3,0.1

Type RM Length L Ch R = 1,5677,381,381,381
BEGIN DESCRIPTION:
Mapping XS 848be0fa
END DESCRIPTION:
XS GIS Cut Line= 5
      1532672.08      6922319.23      1531986.33      6922171.67
      1531547.97      6922045.80      1530394.69      6922098.10
      1529674.21      6922027.68
#Sta/Elev= 30
  4044.2 1698.07  4087.4 1698.14  4204.9 1698.42  4296.7 1695.33  4337.8 1693.53
  4361.2 1691.37  4498.1 1686.61  4553.5 1684.35  4562.9 1685.33  4583.3 1685.13
  4603.8 1683.62  4699.4 1681.62  4886.6 1678.78  4953.0 1676.82  4953.5 1676.32
  4978.1 1676.82  4993.0 1678.30  5031.9 1678.75  5184.6 1678.56  5495.0 1679.67
  5765.3 1678.65  6055.6 1680.08  6185.7 1679.57  6613.2 1683.04  6618.2 1681.81
  6627.2 1681.60  6707.5 1682.75  6809.3 1681.58  6828.1 1682.97  7080.1 1683.14
#Mann=9,-1,0
  4044.2    0.07       0  4087.4   0.045       0  4296.7    0.07       0
  4498.1   0.035       0  4699.4   0.045       0  4953.0   0.045       0
  4978.1   0.045       0  5184.6    0.07       0  6809.3   0.035       0
Bank Sta=4953,4978.1
Exp/Cntr=0.3,0.1

Type RM Length L Ch R = 1,5296,232,232,232
BEGIN DESCRIPTION:
Mapping XS eb337355
END DESCRIPTION:
XS GIS Cut Line= 4
      1532685.09      6922159.49      1532276.26      6921844.41
      1531151.26      6921990.24      1530010.55      6921997.29
#Sta/Elev= 30
  4221.9 1699.55  4301.1 1697.27  4429.7 1689.52  4539.3 1684.29  4622.7 1680.02
  4707.8 1677.93  4775.7 1678.09  4809.9 1678.74  4850.3 1676.54  4976.1 1676.60
  4981.3 1676.55  4988.9 1674.27  4989.4 1673.77  5014.1 1674.27  5037.5 1676.07
  5092.3 1677.24  5192.4 1677.70  5223.3 1678.58  5304.0 1677.83  5661.3 1679.52
  6028.7 1677.86  6198.7 1679.80  6288.7 1678.92  6316.1 1680.00  6358.7 1679.64
  6488.7 1681.47  6578.7 1681.33  6608.7 1680.29  6671.8 1681.77  7013.2 1682.62
#Mann=8,-1,0
  4221.9   0.045       0  4539.3    0.07       0  4775.7   0.035       0
  4976.1   0.045       0  4988.9   0.045       0  5014.1   0.045       0
  5192.4    0.07       0  6671.8   0.035       0
Bank Sta=4988.9,5014.1
Exp/Cntr=0.3,0.1

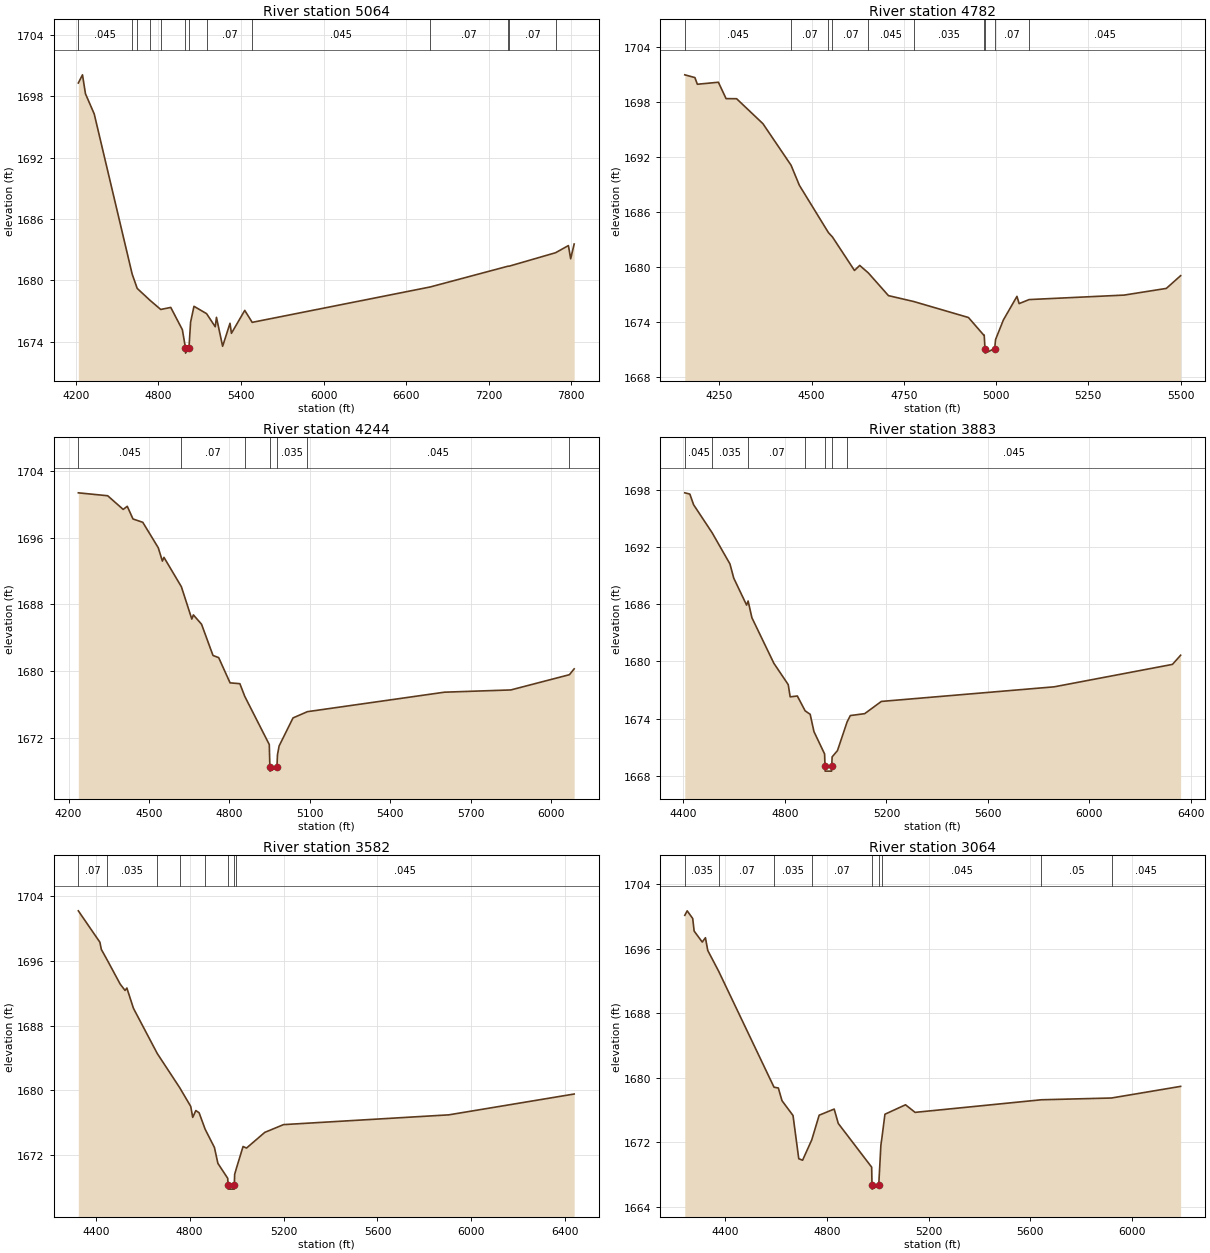
Type RM Length L Ch R = 1,5064,282,282,282
BEGIN DESCRIPTION:
Mapping XS b8bae8a8
END DESCRIPTION:
XS GIS Cut Line= 5
      1532726.55      6922129.50      1532314.21      6921756.23
      1531307.27      6921365.60      1529918.38      6920827.41
      1529471.32      6920658.13
#Sta/Elev= 30
  4218.0 1699.30  4248.2 1700.10  4269.8 1698.25  4333.4 1696.28  4609.3 1680.61
  4645.9 1679.21  4739.5 1678.04  4816.9 1677.15  4889.8 1677.35  4974.2 1675.17
  4996.9 1673.38  4997.4 1672.88  5022.1 1673.38  5034.0 1675.91  5058.6 1677.46
  5150.2 1676.74  5213.1 1675.46  5222.0 1676.38  5266.8 1673.55  5320.4 1675.80
  5330.9 1674.82  5427.6 1677.06  5481.7 1675.89  6775.2 1679.35  7340.3 1681.38
  7350.7 1681.39  7686.8 1682.70  7780.1 1683.40  7796.5 1682.11  7821.8 1683.55
#Mann=13,-1,0
  4218.0   0.045       0  4609.3    0.07       0  4645.9   0.045       0
  4739.5    0.07       0  4816.9   0.035       0  4996.9   0.035       0
  5022.1   0.035       0  5150.2    0.07       0  5481.7   0.045       0
  6775.2    0.07       0  7340.3   0.035       0  7350.7    0.07       0
  7686.8   0.035       0
Bank Sta=4996.9,5022.1
Exp/Cntr=0.3,0.1

Type RM Length L Ch R = 1,4782,538,538,538
BEGIN DESCRIPTION:
Mapping XS 5d347212
END DESCRIPTION:
XS GIS Cut Line= 4
      1532791.89      6922149.09      1532393.45      6921685.56
      1532093.97      6921198.58      1532026.32      6921052.85
#Sta/Elev= 30
  4156.4 1701.01  4183.8 1700.71  4190.4 1699.98  4247.4 1700.20  4268.3 1698.41
  4296.8 1698.40  4368.2 1695.67  4444.3 1691.14  4466.9 1688.94  4545.7 1683.77
  4556.5 1683.30  4616.2 1679.64  4630.4 1680.19  4653.8 1679.37  4708.3 1676.89
  4776.5 1676.25  4925.1 1674.50  4966.2 1672.59  4967.7 1672.59  4969.9 1671.11
  4970.4 1670.61  4996.2 1671.11  4998.5 1672.09  5019.8 1674.24  5056.5 1676.81
  5062.4 1676.02  5089.6 1676.46  5347.1 1676.95  5461.3 1677.68  5500.0 1679.07
#Mann=10,-1,0
  4156.4   0.045       0  4444.3    0.07       0  4545.7   0.045       0
  4556.5    0.07       0  4653.8   0.045       0  4776.5   0.035       0
  4966.2    0.07       0  4969.9    0.07       0  4996.2    0.07       0
  5089.6   0.045       0
Bank Sta=4969.9,4996.2
Exp/Cntr=0.3,0.1

Type RM Length L Ch R = 1,4244,361,361,361
BEGIN DESCRIPTION:
Mapping XS 749311ec
END DESCRIPTION:
XS GIS Cut Line= 3
      1533166.86      6921987.60      1532567.93      6921029.31
      1532195.52      6920414.69
#Sta/Elev= 30
  4236.4 1701.41  4345.8 1701.06  4403.6 1699.42  4418.9 1699.79  4440.2 1698.27
  4476.7 1697.87  4534.5 1694.81  4549.8 1693.21  4555.7 1693.66  4620.7 1690.13
  4659.5 1686.25  4665.4 1686.75  4695.8 1685.63  4738.5 1681.88  4759.7 1681.62
  4802.2 1678.59  4838.7 1678.49  4857.1 1676.96  4948.4 1671.18  4950.6 1668.49
  4951.1 1667.99  4976.9 1668.49  4978.9 1669.95  4985.0 1671.01  5036.9 1674.38
  5090.5 1675.13  5601.8 1677.47  5849.1 1677.74  6067.4 1679.57  6085.1 1680.27
#Mann=7,-1,0
  4236.4   0.045       0  4620.7    0.07       0  4857.1   0.035       0
  4950.6    0.07       0  4976.9   0.035       0  5090.5   0.045       0
  6067.4    0.07       0
Bank Sta=4950.6,4976.9
Exp/Cntr=0.3,0.1

Type RM Length L Ch R = 1,3883,301,301,301
BEGIN DESCRIPTION:
Mapping XS b87bd8ad
END DESCRIPTION:
XS GIS Cut Line= 3
      1533421.25      6921699.47      1532858.73      6920886.95
      1532299.85      6920098.96
#Sta/Elev= 30
  4405.2 1697.66  4425.1 1697.53  4440.0 1696.41  4512.9 1693.48  4583.2 1690.21
  4598.1 1688.73  4648.8 1685.90  4654.8 1686.33  4669.7 1684.58  4756.2 1679.81
  4812.9 1677.57  4820.5 1676.29  4848.8 1676.38  4879.4 1674.83  4899.4 1674.46
  4914.3 1672.65  4956.2 1670.31  4957.9 1669.01  4958.4 1668.51  4983.8 1668.51
  4984.3 1669.01  4985.9 1670.00  5006.9 1670.66  5045.0 1673.67  5057.6 1674.33
  5114.3 1674.53  5179.9 1675.81  5861.1 1677.34  6327.3 1679.69  6359.5 1680.65
#Mann=7,-1,0
  4405.2   0.045       0  4512.9   0.035       0  4654.8    0.07       0
  4879.4   0.035       0  4957.9   0.035       0  4984.3   0.035       0
  5045.0   0.045       0
Bank Sta=4957.9,4984.3
Exp/Cntr=0.3,0.1

Type RM Length L Ch R = 1,3582,518,518,518
BEGIN DESCRIPTION:
Mapping XS 4a8db87c
END DESCRIPTION:
XS GIS Cut Line= 3
      1533733.75      6921636.97      1533202.48      6920883.47
      1532515.62      6919912.15
#Sta/Elev= 30
  4326.0 1702.22  4417.9 1698.33  4424.0 1697.44  4449.0 1696.13  4504.1 1693.15
  4525.0 1692.36  4532.7 1692.66  4560.7 1690.15  4662.3 1684.54  4757.4 1680.33
  4804.6 1678.00  4813.2 1676.64  4826.4 1677.48  4840.3 1677.21  4866.4 1675.15
  4905.6 1672.91  4920.4 1670.94  4962.2 1669.09  4963.7 1668.25  4964.2 1667.75
  4989.7 1667.75  4990.2 1668.25  4991.8 1669.58  4999.3 1670.34  5027.5 1673.03
  5042.3 1672.84  5120.1 1674.78  5199.9 1675.74  5903.8 1676.95  6437.6 1679.53
#Mann=8,-1,0
  4326.0    0.07       0  4449.0   0.035       0  4662.3   0.045       0
  4757.4    0.07       0  4866.4   0.035       0  4963.7   0.045       0
  4990.2   0.035       0  4999.3   0.045       0
Bank Sta=4963.7,4990.2
Exp/Cntr=0.3,0.1

Type RM Length L Ch R = 1,3064,504,504,504
BEGIN DESCRIPTION:
Mapping XS 1a61cd61
END DESCRIPTION:
XS GIS Cut Line= 3
      1533955.96      6921348.76      1533421.23      6920397.36
      1532977.33      6919662.15
#Sta/Elev= 30
  4241.3 1700.11  4250.7 1700.67  4272.4 1699.72  4278.1 1698.16  4310.0 1696.80
  4322.5 1697.34  4331.6 1695.76  4374.6 1693.18  4592.2 1678.82  4609.2 1678.72
  4623.6 1677.15  4667.0 1675.31  4689.5 1669.96  4704.6 1669.77  4740.6 1672.29
  4769.8 1675.35  4828.9 1676.11  4844.9 1674.33  4976.3 1668.91  4977.6 1666.69
  4978.1 1666.19  5004.1 1666.69  5012.6 1671.64  5016.7 1672.56  5028.5 1675.47
  5109.5 1676.64  5147.1 1675.70  5643.5 1677.26  5919.7 1677.48  6191.5 1678.92
#Mann=9,-1,0
  4241.3   0.035       0  4374.6    0.07       0  4592.2   0.035       0
  4740.6    0.07       0  4977.6    0.07       0  5004.1    0.07       0
  5016.7   0.045       0  5643.5    0.05       0  5919.7   0.045       0
Bank Sta=4977.6,5004.1
Exp/Cntr=0.3,0.1