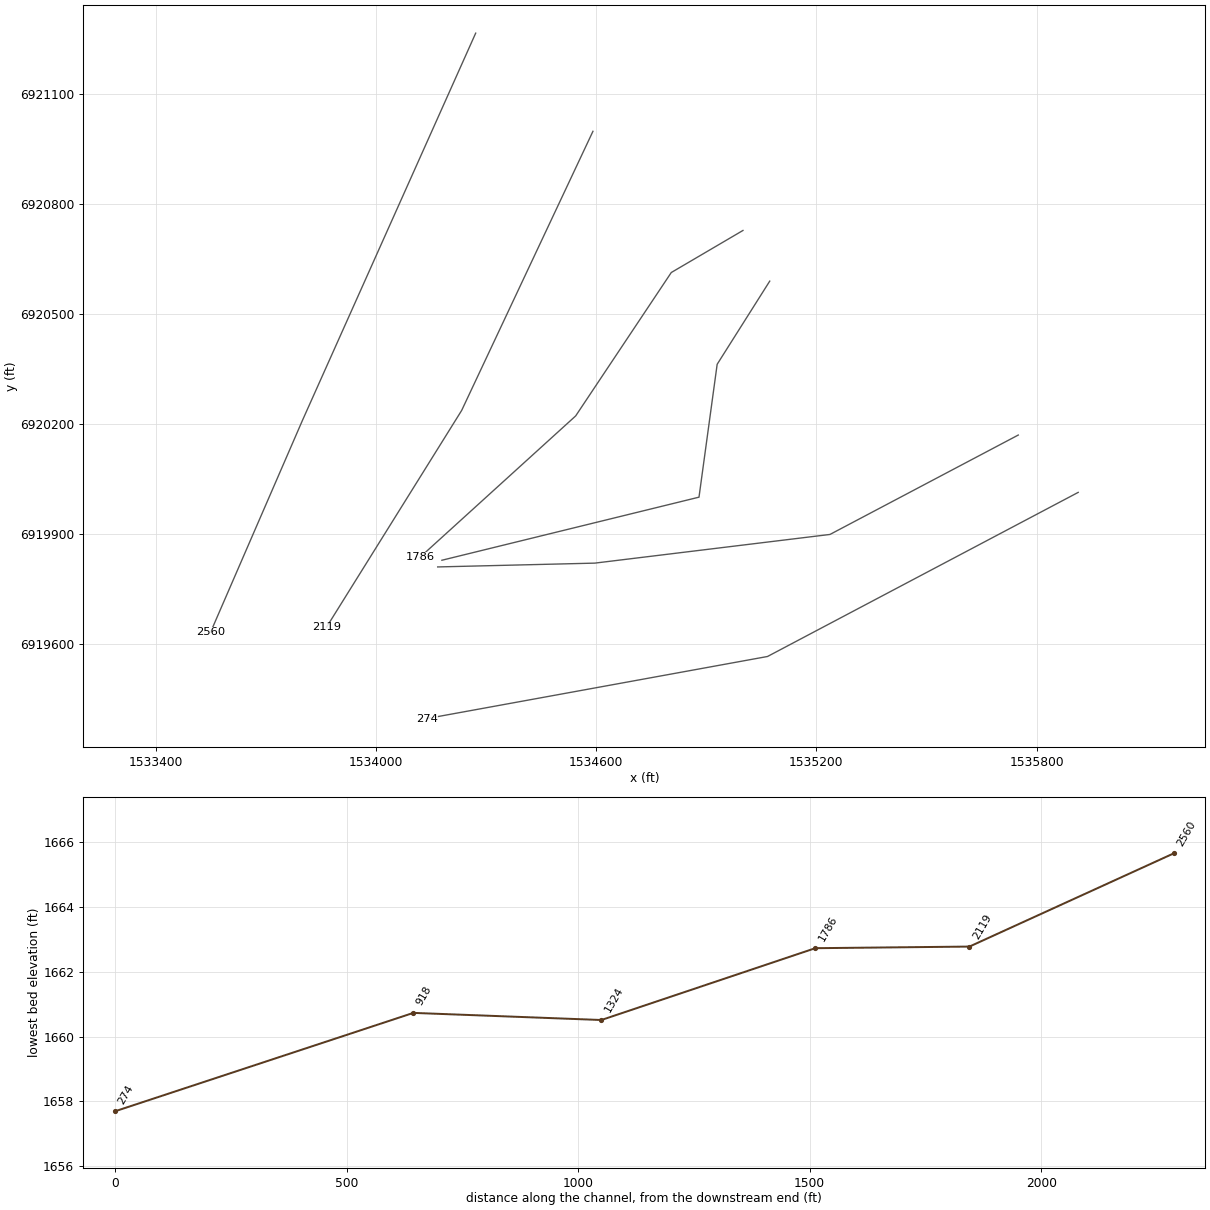
HEC-RAS study Dark Hollow Branch.prj: Dark Hollow Branch Base Level Engineering

--- Dark Hollow Branch.g01 (geometry) --- (continued)

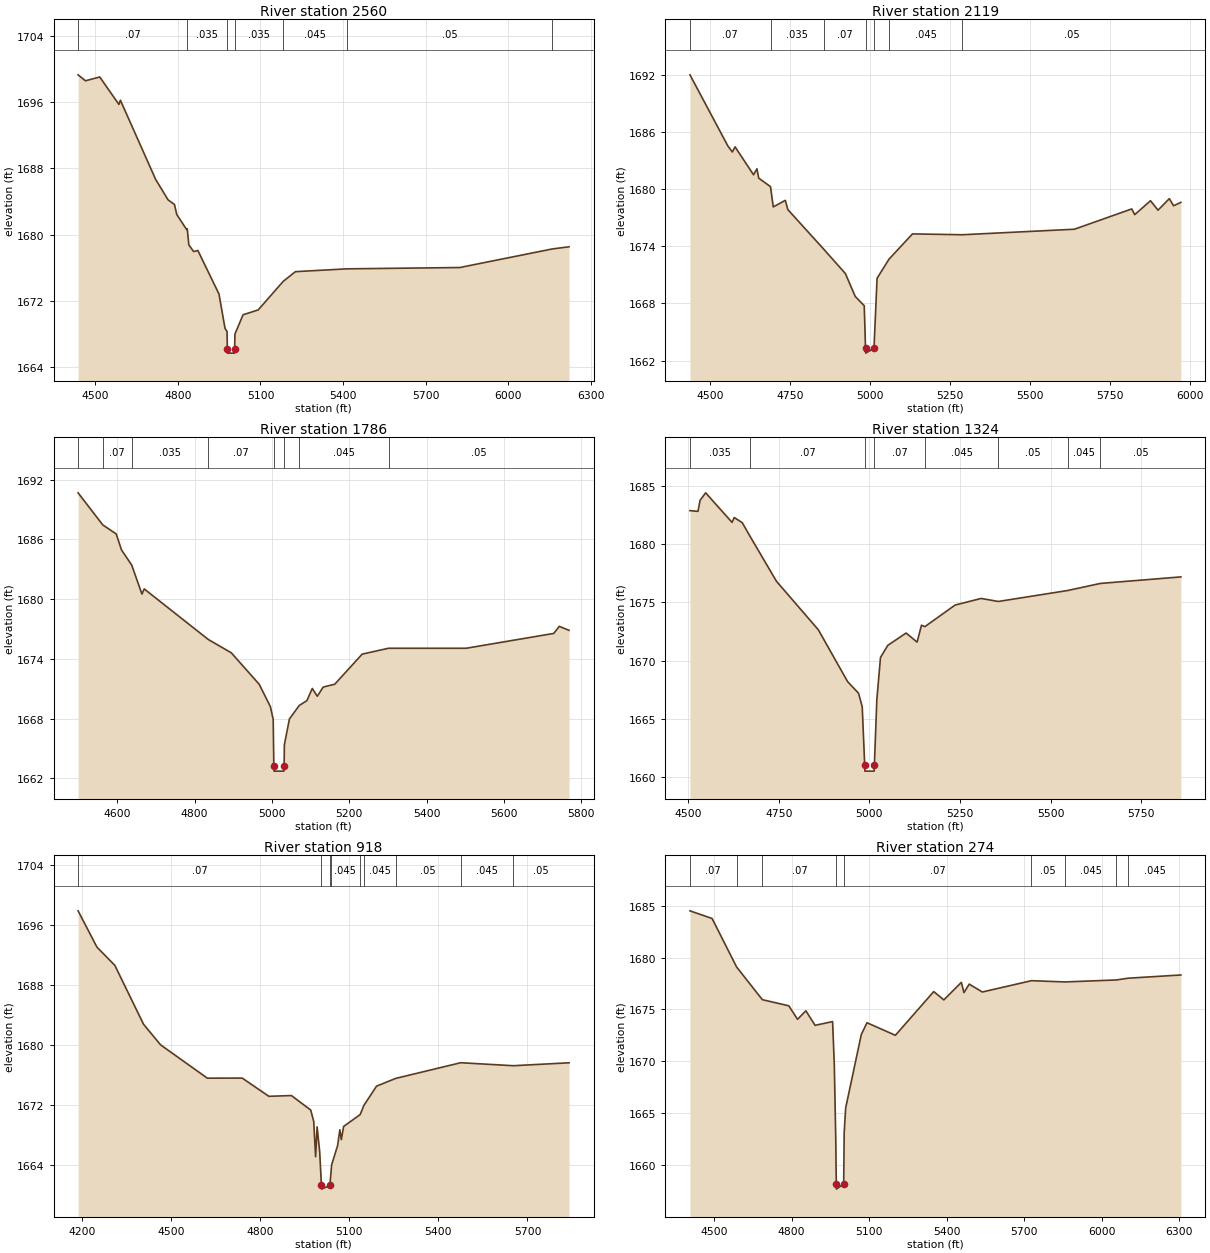
Type RM Length L Ch R = 1,2560,441,441,441
BEGIN DESCRIPTION:
Mapping XS cc6f245d
END DESCRIPTION:
XS GIS Cut Line= 3
      1534271.93      6921265.42      1533799.70      6920209.86
      1533549.84      6919633.79
#Sta/Elev= 30
  4437.2 1699.31  4464.1 1698.59  4516.0 1699.05  4585.6 1695.73  4591.0 1696.24
  4719.2 1686.66  4764.4 1684.19  4787.6 1683.63  4795.9 1682.42  4832.0 1680.59
  4834.0 1680.69  4839.7 1678.75  4857.2 1677.94  4872.6 1678.07  4949.3 1672.81
  4971.2 1668.66  4978.6 1668.28  4979.8 1666.16  4980.3 1665.66  5005.8 1665.66
  5006.3 1666.16  5007.3 1667.97  5036.9 1670.30  5091.7 1670.88  5182.8 1674.34
  5227.1 1675.51  5413.3 1675.85  5824.5 1676.01  6159.9 1678.25  6221.5 1678.52
#Mann=7,-1,0
  4437.2    0.07       0  4832.0   0.035       0  4979.8    0.07       0
  5006.3   0.035       0  5182.8   0.045       0  5413.3    0.05       0
  6159.9   0.045       0
Bank Sta=4979.8,5006.3
Exp/Cntr=0.3,0.1

Type RM Length L Ch R = 1,2119,333,333,333
BEGIN DESCRIPTION:
Mapping XS 165dd7a5
END DESCRIPTION:
XS GIS Cut Line= 3
      1534591.35      6920998.02      1534233.73      6920237.64
      1533865.68      6919647.37
#Sta/Elev= 30
  4436.7 1691.98  4555.1 1684.53  4569.3 1683.88  4577.9 1684.42  4635.6 1681.49
  4646.3 1682.12  4651.8 1681.14  4688.7 1680.25  4697.4 1678.12  4735.1 1678.81
  4743.0 1677.84  4854.6 1673.71  4923.0 1671.13  4953.7 1668.73  4982.0 1667.75
  4986.0 1663.28  4986.5 1662.78  5012.5 1663.28  5022.1 1670.63  5059.5 1672.64
  5132.9 1675.29  5288.5 1675.20  5639.6 1675.78  5818.9 1677.91  5828.3 1677.31
  5877.6 1678.77  5901.1 1677.78  5936.5 1678.99  5949.9 1678.24  5972.6 1678.60
#Mann=7,-1,0
  4436.7    0.07       0  4688.7   0.035       0  4854.6    0.07       0
  4986.0    0.07       0  5012.5    0.07       0  5059.5   0.045       0
  5288.5    0.05       0
Bank Sta=4986,5012.5
Exp/Cntr=0.3,0.1

Type RM Length L Ch R = 1,1786,462,462,462
BEGIN DESCRIPTION:
Mapping XS 46bc0415
END DESCRIPTION:
XS GIS Cut Line= 4
      1535000.07      6920727.93      1534804.74      6920613.33
      1534544.32      6920222.71      1534119.91      6919837.35
#Sta/Elev= 30
  4499.0 1690.68  4562.8 1687.46  4597.6 1686.55  4611.3 1684.94  4637.7 1683.42
  4664.1 1680.51  4669.9 1681.03  4835.7 1675.95  4895.2 1674.61  4967.3 1671.45
  4996.3 1669.19  5003.4 1667.94  5005.1 1663.23  5005.6 1662.73  5031.2 1662.73
  5031.7 1663.23  5032.3 1665.37  5045.4 1667.97  5070.7 1669.32  5090.5 1669.81
  5104.5 1671.03  5117.5 1670.25  5132.6 1671.17  5162.6 1671.46  5233.5 1674.48
  5301.6 1675.07  5502.4 1675.07  5728.8 1676.56  5743.0 1677.27  5768.2 1676.87
#Mann=8,-1,0
  4499.0   0.035       0  4562.8    0.07       0  4637.7   0.035       0
  4835.7    0.07       0  5005.1    0.07       0  5031.7    0.07       0
  5070.7   0.045       0  5301.6    0.05       0
Bank Sta=5005.1,5031.7
Exp/Cntr=0.3,0.1

Type RM Length L Ch R = 1,1324,406,406,406
BEGIN DESCRIPTION:
Mapping XS 2e0344de
END DESCRIPTION:
XS GIS Cut Line= 4
      1535072.96      6920589.88      1534929.74      6920363.33
      1534880.26      6920001.35      1534179.90      6919829.52
#Sta/Elev= 30
  4505.0 1682.88  4527.1 1682.82  4533.0 1683.77  4548.3 1684.41  4621.2 1681.87
  4627.1 1682.29  4649.2 1681.85  4670.7 1680.68  4743.8 1676.81  4859.2 1672.65
  4939.9 1668.20  4970.2 1667.20  4980.3 1666.04  4987.2 1661.01  4987.7 1660.51
  5013.3 1660.51  5013.8 1661.01  5020.6 1666.62  5030.7 1670.27  5050.9 1671.31
  5101.4 1672.37  5131.7 1671.59  5143.8 1673.04  5153.3 1672.92  5236.5 1674.77
  5308.5 1675.34  5355.8 1675.08  5547.0 1676.02  5637.7 1676.63  5859.5 1677.19
#Mann=8,-1,0
  4505.0   0.035       0  4670.7    0.07       0  4987.2    0.07       0
  5013.8    0.07       0  5153.3   0.045       0  5355.8    0.05       0
  5547.0   0.045       0  5637.7    0.05       0
Bank Sta=4987.2,5013.8
Exp/Cntr=0.3,0.1

Type RM Length L Ch R = 1,918,644,644,644
BEGIN DESCRIPTION:
Mapping XS 4aa4aa76
END DESCRIPTION:
XS GIS Cut Line= 4
      1535750.01      6920170.60      1535237.03      6919899.79
      1534596.40      6919821.67      1534168.38      6919811.29
#Sta/Elev= 30
  4186.3 1697.85  4249.8 1693.01  4310.2 1690.57  4406.8 1682.72  4464.3 1679.97
  4621.7 1675.53  4739.2 1675.54  4828.9 1673.11  4904.8 1673.21  4969.9 1671.28
  4980.0 1669.77  4986.4 1665.05  4991.4 1669.04  5000.1 1665.73  5006.0 1661.23
  5006.5 1660.73  5034.5 1661.23  5037.0 1662.39  5040.4 1663.97  5060.6 1666.56
  5068.0 1668.65  5073.0 1667.33  5080.7 1669.09  5136.4 1670.67  5149.1 1671.90
  5191.5 1674.46  5256.2 1675.50  5475.2 1677.59  5652.2 1677.19  5839.9 1677.58
#Mann=9,-1,0
  4186.3    0.07       0  5006.0    0.07       0  5034.5    0.07       0
  5037.0   0.045       0  5136.4    0.07       0  5149.1   0.045       0
  5256.2    0.05       0  5475.2   0.045       0  5652.2    0.05       0
Bank Sta=5006,5034.5
Exp/Cntr=0.3,0.1

Type RM Length L Ch R = 1,274,0,0,0
BEGIN DESCRIPTION:
Dark Hollow Branch 1.0
END DESCRIPTION:
XS GIS Cut Line= 3
      1535913.29      6920014.40      1535066.89      6919567.33
      1534138.99      6919398.22
#Sta/Elev= 30
  4406.8 1684.50  4492.6 1683.76  4587.4 1679.09  4687.1 1675.94  4789.4 1675.35
  4823.3 1674.05  4855.5 1674.87  4891.2 1673.47  4959.0 1673.83  4965.6 1669.68
  4971.2 1662.56  4973.3 1658.19  4973.8 1657.69  5001.9 1658.19  5003.9 1663.15
  5009.6 1665.51  5070.0 1672.57  5092.0 1673.72  5202.1 1672.51  5350.5 1676.72
  5389.7 1675.92  5457.4 1677.61  5467.6 1676.62  5487.9 1677.44  5538.7 1676.68
  5728.7 1677.77  5857.8 1677.65  6057.6 1677.84  6103.3 1678.01  6307.2 1678.32
#Mann=9,-1,0
  4406.8    0.07       0  4587.4   0.035       0  4687.1    0.07       0
  4973.3   0.045       0  5001.9    0.07       0  5728.7    0.05       0
  5857.8   0.045       0  6057.6    0.05       0  6103.3   0.045       0
Bank Sta=4973.3,5001.9
Exp/Cntr=0.3,0.1

Chan Stop Cuts=-1