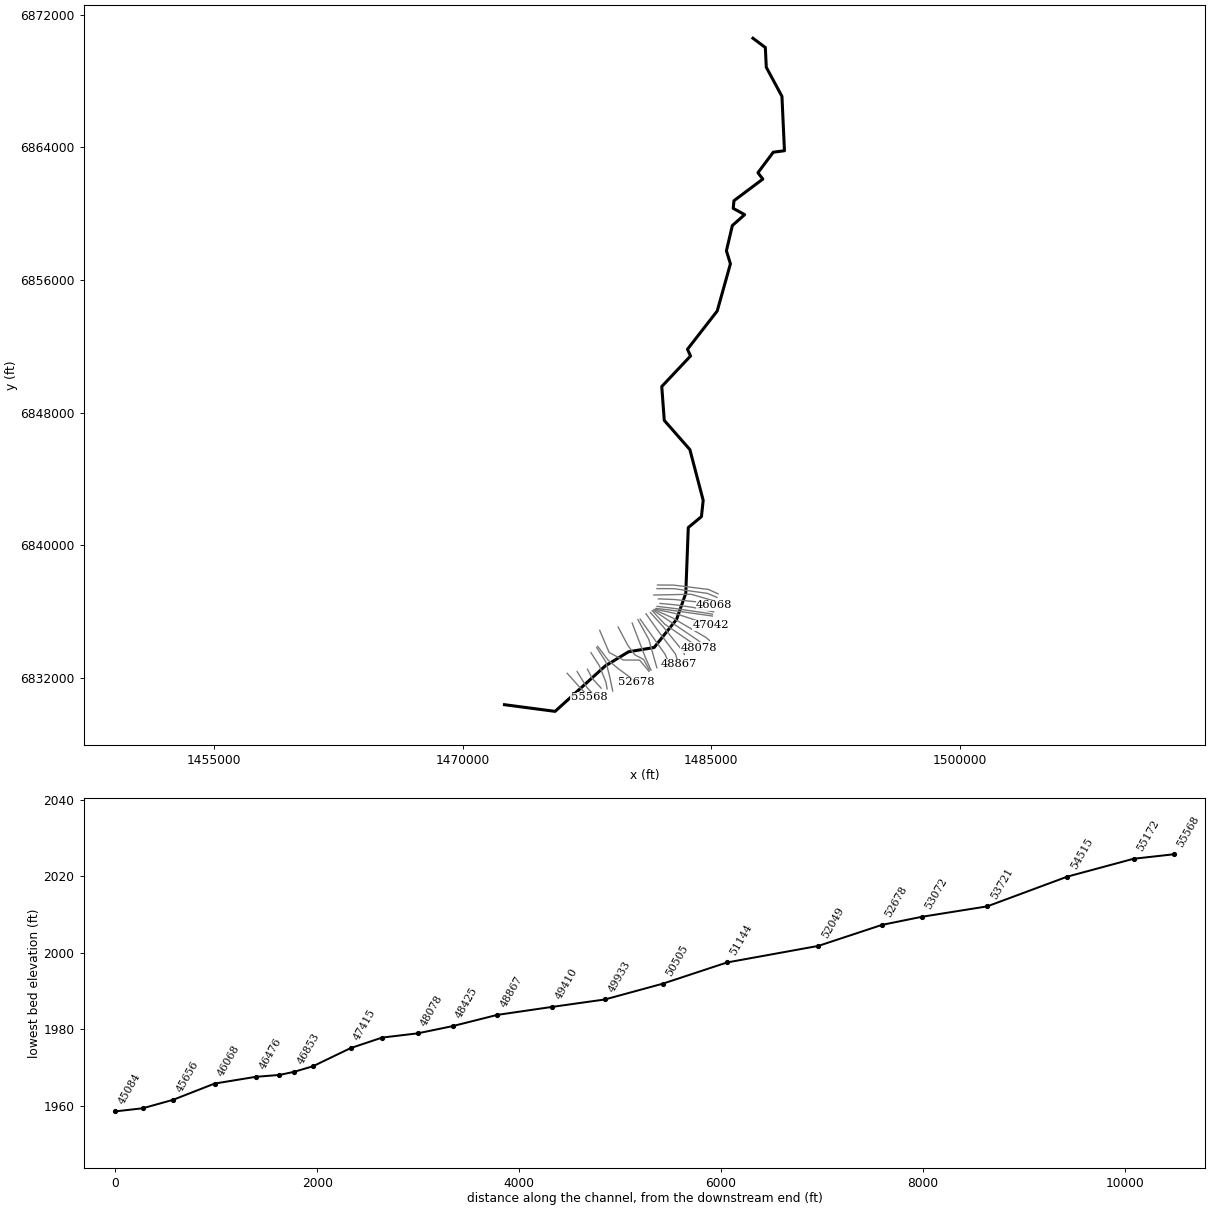
--- Little Bitter Creek.prj (project) ---

Proj Title=Little Bitter Creek Base Level Engineering
Current Plan=p01
Default Exp/Contr=0.3,0.1
English Units
Geom File=g01
Flow File=f01
Plan File=p01
Y Axis Title=Elevation
X Axis Title(PF)=Main Channel Distance
X Axis Title(XS)=Station
BEGIN DESCRIPTION:
Little Bitter Creek
END DESCRIPTION:
DSS Export Rating Curves= 0
DSS Export Rating Curve Sorted= 0
DSS Export Volume Flow Curves= 0
DXF OffsetX= 0
DXF OffsetY= 0
DXF ScaleX= 1
DXF ScaleY= 10

--- Little Bitter Creek.p01 (plan) ---

Plan Title=Multiple Run
Short Identifier=Multiple
Geom File=g01
Flow File=f01
Subcritical Flow
K Sum by GR= 0
Std Step Tol= 0.01
Critical Tol= 0.01
Num of Std Step Trials= 20
Max Error Tol= 0.3
Flow Tol Ratio= 0.001
Split Flow NTrial= 30
Split Flow Tol= 0.02
Split Flow Ratio= 0.02
Log Output Level= 0
Friction Slope Method= 1
Unsteady Friction Slope Method= 2
Unsteady Bridges Friction Slope Method= 1
Parabolic Critical Depth
Global Vel Dist=  1 , 1 , 1
Global Log Level= 0
CheckData=True
Encroach Param= -1, 0, 0, 0
BEGIN DESCRIPTION:
Multiple Run
END DESCRIPTION:

--- Little Bitter Creek.f01 (steady flow) ---

Flow Title=Multiple
Program Version=4.10
Number of Profiles= 7
Profile Names=10-year,25-year,50-year,1pct_min,100-year,1pct_plu,500-year
River Rch & RM=Little Bitter Cr,Reach-1         ,55568
     294     414     514     318     634    1266     977
River Rch & RM=Little Bitter Cr,Reach-1         ,53721
     427     611     766     478     953    1902    1494
River Rch & RM=Little Bitter Cr,Reach-1         ,49933
     524     755     952     596    1188    2371    1876
River Rch & RM=Little Bitter Cr,Reach-1         ,42077
     623     903    1143     718    1432    2858    2275
River Rch & RM=Little Bitter Cr,Reach-1         ,39062
     846    1241    1583    1001    1997    3984    3218
River Rch & RM=Little Bitter Cr,Reach-1         ,37094
     846    1241    1583    1001    1997    3984    3218
River Rch & RM=Little Bitter Cr,Reach-1         ,28649
     879    1286    1637    1032    2060    4109    3302
River Rch & RM=Little Bitter Cr,Reach-1         ,18710
     892    1303    1658    1044    2084    4157    3333
River Rch & RM=Little Bitter Cr,Reach-1         ,12765
    1346    1999    2572    1636    3265    6514    5331
River Rch & RM=Little Bitter Cr,Reach-1         ,5824
    1340    1986    2552    1621    3235    6455    5265
Boundary for River Rch & Prof#=Little Bitter Cr,Reach-1         , 1
Up Type= 0
Dn Type= 3
Dn Slope=0.005
Boundary for River Rch & Prof#=Little Bitter Cr,Reach-1         , 2
Up Type= 0
Dn Type= 3
Dn Slope=0.005
Boundary for River Rch & Prof#=Little Bitter Cr,Reach-1         , 3
Up Type= 0
Dn Type= 3
Dn Slope=0.005
Boundary for River Rch & Prof#=Little Bitter Cr,Reach-1         , 4
Up Type= 0
Dn Type= 3
Dn Slope=0.005
Boundary for River Rch & Prof#=Little Bitter Cr,Reach-1         , 5
Up Type= 0
Dn Type= 3
Dn Slope=0.005
Boundary for River Rch & Prof#=Little Bitter Cr,Reach-1         , 6
Up Type= 0
Dn Type= 3
Dn Slope=0.005
Boundary for River Rch & Prof#=Little Bitter Cr,Reach-1         , 7
Up Type= 0
Dn Type= 3
Dn Slope=0.005
DSS Import GetInterval= 0
DSS Import GetPeak= 0
DSS Import FillOption= 0

--- Little Bitter Creek.g01 (geometry) ---

Geom Title=Existing Conditions
Program Version=4.10

River Reach=Little Bitter Cr,Reach-1
Reach XY= 30
      1472525.62       6830393.3      1475577.14      6829990.53
      1478598.81      6832730.15      1480006.47      6833584.45
      1481549.89       6833843.1      1482901.17      6835539.58
       1483454.9      6837108.35      1483606.19      6841077.52
      1484399.17       6841735.7      1484504.93      6842717.97
      1483701.91      6845779.69      1482158.55      6847539.47
      1482007.25      6849582.06       1483741.5      6851424.59
       1483557.9      6851830.09      1485351.56      6854139.25
      1486147.23      6856984.58      1485904.91      6857768.12
      1486262.68      6859291.71      1487004.07      6859948.48
      1486315.32      6860327.82      1486360.47      6860790.45
      1488100.08      6862093.02      1487806.49      6862476.14
      1488731.03       6863715.2      1489405.05      6863803.34
      1489253.02      6867082.33      1488308.53      6868839.45
      1488252.43      6870029.48        1487505.        6870588.

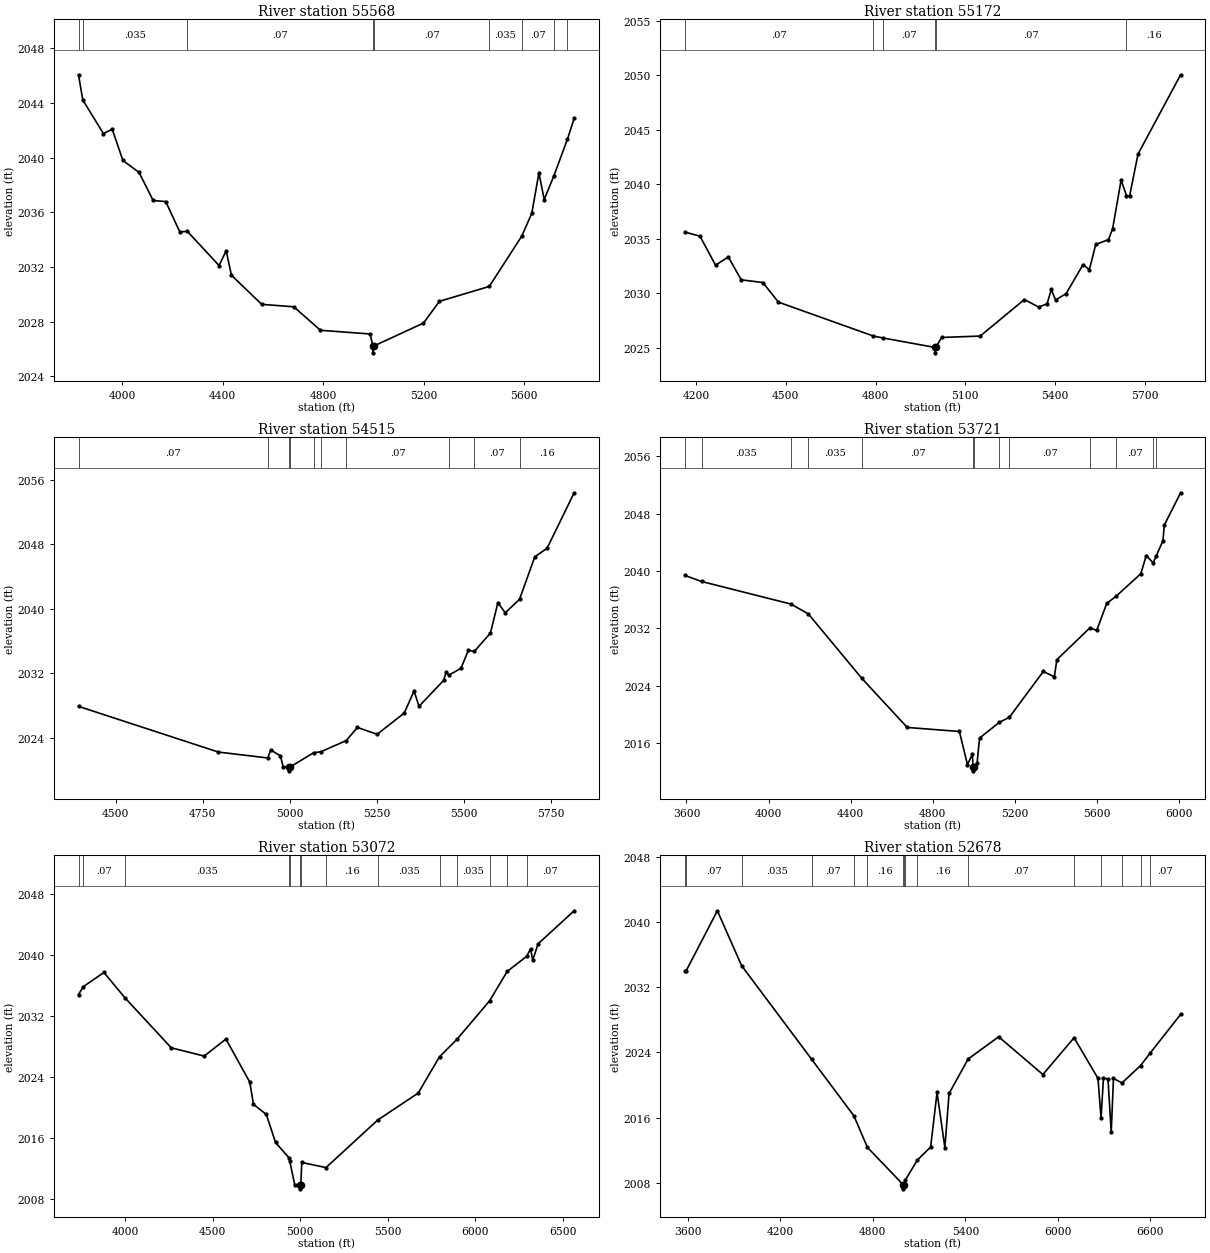
Type RM Length L Ch R = 1 ,55568   ,396,396,396
BEGIN DESCRIPTION:
Little Bitter Creek 51.0
END DESCRIPTION:
XS GIS Cut Line= 3
        1476305.        6832288.      1477086.39      6831413.44
      1477643.45      6830837.85
#Sta/Elev= 30
    3826 2046.06  3843.1 2044.21  3925.1 2041.76  3960.2 2042.07  4002.8 2039.79
  4067.2 2038.91  4123.2 2036.86  4173.3 2036.78  4229.4 2034.56  4259.5  2034.6
  4385.7  2032.1  4414.1 2033.18    4435 2031.39  4555.4 2029.26  4683.3 2029.08
  4789.4 2027.36  4987.6 2027.09    4998 2026.21  4998.3 2025.71    5002 2026.21
  5199.8 2027.89  5263.3 2029.48  5461.8 2030.57  5590.7 2034.24  5631.1 2035.92
  5659.4 2038.88  5680.5 2036.93  5718.8 2038.65  5773.1 2041.35  5799.8 2042.87
#Mann= 9 ,-1 , 0
    3826     .07       0  3843.1    .035       0  4259.5     .07       0
    4998     .07       0    5002     .07       0  5461.8    .035       0
  5590.7     .07       0  5718.8     .16       0  5773.1     .07       0
Bank Sta=4998,5002
XS Rating Curve= 0 ,0
Exp/Cntr=0.3,0.1

Type RM Length L Ch R = 1 ,55172   ,657,657,657
BEGIN DESCRIPTION:
Little Bitter Creek 50.0
END DESCRIPTION:
XS GIS Cut Line= 3
        1476905.        6832388.      1477502.37      6831421.64
      1477866.97      6831048.35
#Sta/Elev= 30
  4162.6 2035.63  4212.8 2035.25  4264.9 2032.59  4307.4 2033.35  4350.7 2031.25
  4423.2    2031  4475.3  2029.2  4791.9  2026.1  4825.5 2025.91    4998 2025.05
  4998.3 2024.55    5002 2025.05  5020.8 2025.96  5150.1 2026.09  5297.9 2029.44
  5345.6 2028.75  5373.8 2029.05  5387.9 2030.37  5402.1  2029.4  5437.5 2029.98
  5494.1 2032.65  5515.2 2032.18  5536.5 2034.49    5579 2034.94  5593.1 2035.94
  5621.4  2040.4  5639.4 2038.97  5649.7 2038.92    5678 2042.79  5820.5 2050.06
#Mann= 6 ,-1 , 0
  4162.6     .07       0  4791.9     .16       0  4825.5     .07       0
    4998     .07       0    5002     .07       0  5639.4     .16       0
Bank Sta=4998,5002
XS Rating Curve= 0 ,0
Exp/Cntr=0.3,0.1

Type RM Length L Ch R = 1 ,54515   ,794,794,794
BEGIN DESCRIPTION:
Little Bitter Creek 49.0
END DESCRIPTION:
XS GIS Cut Line= 3
      1477528.41      6832532.76        1477805.        6831988.
        1478355.        6831388.
#Sta/Elev= 30
    4393 2027.89  4795.3 2022.21  4937.1 2021.48  4945.5 2022.48  4973.4 2021.74
  4981.5 2020.38    4998 2020.38  4998.3 2019.88    5002 2020.38  5068.6 2022.12
  5090.3 2022.26  5162.6 2023.64  5194.8 2025.27  5251.5 2024.42  5329.5 2027.06
  5357.6 2029.81  5371.8 2027.89  5442.7 2031.12  5450.1 2032.18  5457.3 2031.76
  5492.3 2032.61  5513.6 2034.83    5531 2034.72  5577.1 2036.99  5598.7 2040.77
  5619.7 2039.51  5660.8 2041.18  5704.7 2046.47  5739.9 2047.52  5817.9 2054.42
#Mann= 10 ,-1 , 0
    4393     .07       0  4937.1    .035       0    4998     .07       0
    5002    .035       0  5068.6     .07       0  5090.3    .035       0
  5162.6     .07       0  5457.3     .16       0    5531     .07       0
  5660.8     .16       0
Bank Sta=4998,5002
XS Rating Curve= 0 ,0
Exp/Cntr=0.3,0.1

Type RM Length L Ch R = 1 ,53721   ,649,649,649
BEGIN DESCRIPTION:
Mapping XS 95bbf595
END DESCRIPTION:
XS GIS Cut Line= 4
      1477740.93      6833530.06      1478244.38       6832744.5
      1478643.68      6831746.24       1478713.1      6831342.77
#Sta/Elev= 30
  3592.6 2039.36  3673.3 2038.52  4109.2 2035.37  4194.2    2034  4455.4    2025
  4676.7 2018.16  4931.2  2017.6  4970.2 2012.99  4994.5  2014.4  4997.6 2012.61
  4997.9 2012.11  5002.5 2012.61  5017.3 2013.17  5029.5 2016.68  5126.5 2018.89
  5174.6 2019.57  5340.4 2025.97  5394.3 2025.22  5406.4 2027.61  5567.9 2032.06
  5600.8 2031.69  5649.8 2035.47  5694.3 2036.43  5816.1  2039.6  5842.5 2042.14
  5876.2 2041.11  5890.7 2042.05  5923.7 2044.19  5930.9 2046.41  6010.2 2050.89
#Mann= 13 ,-1 , 0
  3592.6     .07       0  3673.3    .035       0  4109.2     .07       0
  4194.2    .035       0  4455.4     .07       0  4997.6     .07       0
  5002.5     .07       0  5126.5    .035       0  5174.6     .07       0
  5567.9     .16       0  5694.3     .07       0  5876.2     .16       0
  5890.7     .07       0
Bank Sta=4997.6,5002.5
XS Rating Curve= 0 ,0
Exp/Cntr=0.3,0.1

Type RM Length L Ch R = 1 ,53072   ,394,394,394
BEGIN DESCRIPTION:
Mapping XS b9eecdeb
END DESCRIPTION:
XS GIS Cut Line= 4
       1478083.8      6833838.23        1478635.      6832974.54
        1478839.      6832210.65      1479051.68       6831216.7
#Sta/Elev= 30
  3732.7  2034.8  3759.5 2035.82  3877.8 2037.69  3996.9  2034.4  4262.8 2027.83
  4450.6 2026.75    4575 2028.98  4711.2 2023.34  4732.4 2020.43  4805.5 2019.12
  4858.3 2015.45  4937.5 2013.38  4938.9 2013.08  4968.2 2009.88  4997.5 2009.88
  4997.9 2009.38  5002.5 2009.88  5008.3 2012.83  5146.5 2012.16  5442.6 2018.39
  5673.4 2021.91  5795.1 2026.66  5894.6 2028.94  6080.8 2033.96  6181.6 2037.82
  6292.9  2039.8    6315 2040.76  6327.9 2039.32  6358.5 2041.44  6564.4 2045.76
#Mann= 14 ,-1 , 0
  3732.7    .035       0  3759.5     .07       0  3996.9    .035       0
  4937.5     .16       0  4938.9    .035       0  4997.5     .07       0
  5002.5    .035       0  5146.5     .16       0  5442.6    .035       0
  5795.1     .07       0  5894.6    .035       0  6080.8     .07       0
  6181.6    .035       0  6292.9     .07       0
Bank Sta=4997.5,5002.5
XS Rating Curve= 0 ,0
Exp/Cntr=0.3,0.1

Type RM Length L Ch R = 1 ,52678   ,629,629,629
BEGIN DESCRIPTION:
Mapping XS f95a1bbc
END DESCRIPTION:
XS GIS Cut Line= 4
      1478144.55      6833912.04      1478778.23      6833074.37
      1479372.85      6832575.23      1480491.35      6831755.87
#Sta/Elev= 30
  3582.4 2033.97  3588.6 2033.97  3792.3 2041.39  3949.4 2034.66  4403.3 2023.17
  4677.5 2016.23    4765 2012.36  4997.5 2007.77  4997.9 2007.27  5002.6 2007.77
  5009.8 2008.31  5089.4 2010.82  5174.8 2012.39  5216.5  2019.1  5267.2 2012.34
  5294.5 2018.97    5418  2023.2  5616.1 2025.93  5902.5  2021.3  6104.8 2025.81
  6259.9 2020.82  6279.6 2015.91  6295.4 2020.92  6324.8  2020.7  6345.6 2014.25
  6360.3 2020.82  6415.2 2020.26  6536.1  2022.4    6597  2023.9  6795.6 2028.68
#Mann= 16 ,-1 , 0
  3582.4    .035       0  3588.6     .07       0  3949.4    .035       0
  4403.3     .07       0  4677.5    .035       0    4765     .16       0
  4997.5     .05       0  5002.6     .16       0  5009.8    .035       0
  5089.4     .16       0    5418     .07       0  6104.8    .035       0
  6279.6     .16       0  6415.2     .07       0  6536.1     .16       0
    6597     .07       0
Bank Sta=4997.5,5002.6
XS Rating Curve= 0 ,0
Exp/Cntr=0.3,0.1

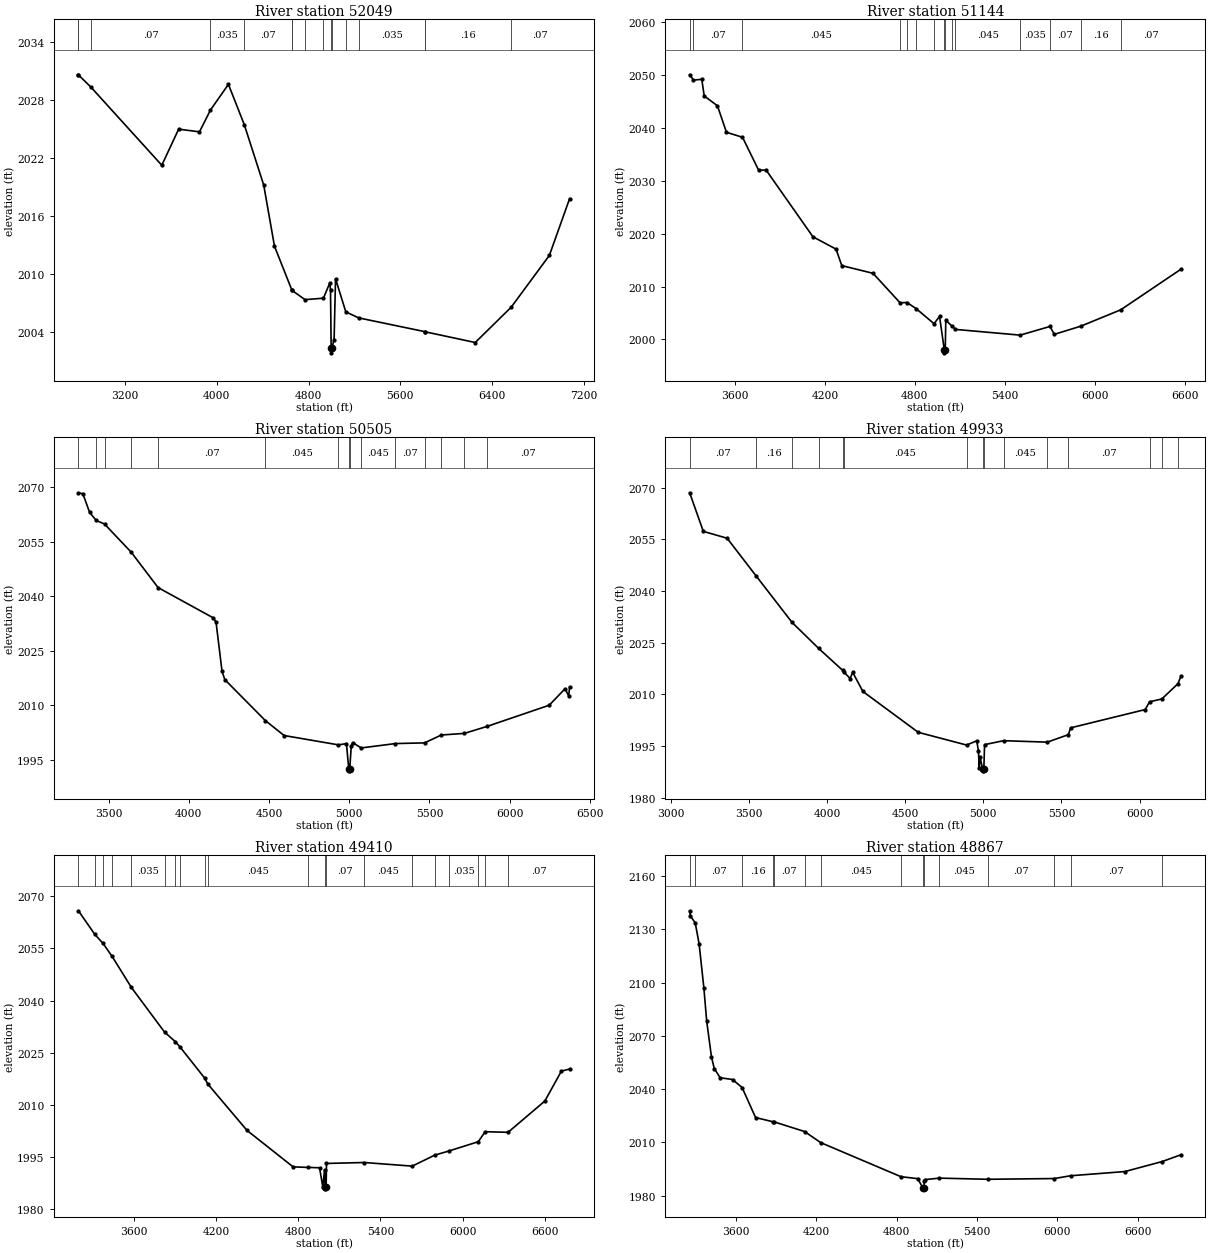
Type RM Length L Ch R = 1 ,52049   ,905,905,905
BEGIN DESCRIPTION:
Mapping XS 754941d8
END DESCRIPTION:
XS GIS Cut Line= 5
      1478266.09      6834875.57      1478834.66      6833543.12
      1479694.03      6833087.39      1480670.59      6833083.05
      1481238.61       6832402.3
#Sta/Elev= 30
  2792.8 2030.59    2793 2030.58  2900.5 2029.33  3520.1 2021.22  3667.2 2024.96
  3848.8 2024.68  3944.7 2026.94  4101.3  2029.6  4240.3  2025.4  4409.3 2019.16
  4502.9 2012.84  4655.6 2008.26  4656.9 2008.25  4769.2  2007.3    4930 2007.45
    4986 2009.04  4991.7 2008.27  4997.4 2002.29  4997.8 2001.79  5002.6 2002.29
  5022.9 2003.13  5035.7 2009.46  5125.3 2006.03  5237.4 2005.41  5816.7 2003.98
    5817 2003.97  6254.1 2002.86  6567.9 2006.52  6900.7 2011.88  7077.4 2017.76
#Mann= 16 ,-1 , 0
  2792.8    .035       0    2793    .045       0  2900.5     .07       0
  3944.7    .035       0  4240.3     .07       0  4655.6    .045       0
  4656.9     .07       0  4769.2    .045       0    4930     .07       0
  4997.4     .07       0  5002.6     .07       0  5125.3    .045       0
  5237.4    .035       0  5816.7     .07       0    5817     .16       0
  6567.9     .07       0
Bank Sta=4997.4,5002.6
XS Rating Curve= 0 ,0
Exp/Cntr=0.3,0.1

Type RM Length L Ch R = 1 ,51144   ,639,639,639
BEGIN DESCRIPTION:
Mapping XS 53b5c175
END DESCRIPTION:
XS GIS Cut Line= 5
      1479374.34      6835078.74      1479962.88      6833969.38
      1480384.75      6833401.67      1480905.58      6833125.63
      1481259.76      6832495.41
#Sta/Elev= 30
  3298.6 2050.06  3324.2 2049.05  3379.5  2049.2  3395.8 2046.05  3483.8  2044.2
  3544.1 2039.18    3651 2038.24  3758.3 2032.03  3808.8 2032.02  4120.8 2019.41
  4274.8 2017.08  4313.1 2013.96  4521.6  2012.5  4701.6 2006.93  4747.6 2006.98
  4808.7 2005.83  4928.3 2002.97  4964.9 2004.35  4997.1 1997.96  4997.5 1997.46
    5003 1997.96  5006.6 2003.63  5047.9 2002.51  5071.2 2001.89  5502.6 2000.81
  5701.4 2002.45  5730.2 2000.96  5906.7  2002.5  6173.4  2005.6  6574.1 2013.27
#Mann= 15 ,-1 , 0
  3298.6     .16       0  3324.2     .07       0    3651    .045       0
  4701.6     .07       0  4747.6    .045       0  4808.7     .07       0
  4928.3    .045       0  4997.1    .045       0    5003    .045       0
  5047.9     .07       0  5071.2    .045       0  5502.6    .035       0
  5701.4     .07       0  5906.7     .16       0  6173.4     .07       0
Bank Sta=4997.1,5003
XS Rating Curve= 0 ,0
Exp/Cntr=0.3,0.1

Type RM Length L Ch R = 1 ,50505   ,572,572,572
BEGIN DESCRIPTION:
Mapping XS df81483c
END DESCRIPTION:
XS GIS Cut Line= 3
      1480223.53      6835313.99      1481009.14        6833261.
      1481359.93       6832472.8
#Sta/Elev= 30
  3312.3 2068.48  3340.1 2068.21    3382 2063.09  3423.3 2060.85  3474.9 2059.88
  3641.7 2052.09  3808.8 2042.37  4153.9    2034  4169.9 2032.86  4207.4 2019.26
  4224.6 2017.02  4476.8 2005.76  4593.9 2001.63  4932.9 1999.05  4982.5 1999.41
    4997  1992.4  4997.5  1991.9    5003  1992.4  5012.5 1998.76  5021.1 1999.67
    5075 1998.21    5288 1999.41    5469  1999.6    5574 2001.77  5716.8 2002.21
  5857.5 2004.12    6246 2009.97  6344.5 2014.51  6367.5 2012.53  6373.2 2015.03
#Mann= 15 ,-1 , 0
  3312.3     .07       0  3423.3    .035       0  3474.9     .07       0
  3641.7     .16       0  3808.8     .07       0  4476.8    .045       0
  4932.9     .07       0    4997     .07       0    5003     .07       0
    5075    .045       0    5288     .07       0    5469    .035       0
    5574     .07       0  5716.8     .16       0  5857.5     .07       0
Bank Sta=4997,5003
XS Rating Curve= 0 ,0
Exp/Cntr=0.3,0.1

Type RM Length L Ch R = 1 ,49933   ,523,523,523
BEGIN DESCRIPTION:
Mapping XS 88651f41
END DESCRIPTION:
XS GIS Cut Line= 3
      1480566.19      6835526.65      1481227.63      6834328.76
      1481711.64      6832621.73
#Sta/Elev= 30
  3121.5 2068.51  3208.9 2057.31  3361.3 2055.31  3546.9 2044.36  3776.8 2030.87
  3946.9 2023.33  4101.1 2016.94  4109.9  2016.4  4148.4 2014.59  4164.5  2016.4
  4229.8 2010.83  4584.2 1998.97    4893 1995.28  4958.4  1996.5  4968.8 1993.63
  4974.6 1988.54  4979.8 1991.69  4996.5 1988.29    4997 1987.79  5003.6 1988.29
  5008.5  1995.4  5130.2 1996.54  5409.4 1996.12  5544.6 1998.29  5558.9 2000.27
  6036.2 2005.58  6063.8 2007.83  6142.8 2008.66  6245.7  2013.1  6264.2 2015.23
#Mann= 15 ,-1 , 0
  3121.5     .07       0  3546.9     .16       0  3776.8    .035       0
  3946.9     .07       0  4101.1    .035       0  4109.9    .045       0
    4893     .07       0  4996.5     .07       0  5003.6     .07       0
  5130.2    .045       0  5409.4    .035       0  5544.6     .07       0
  6063.8    .035       0  6142.8     .07       0  6245.7    .035       0
Bank Sta=4996.5,5003.6
XS Rating Curve= 0 ,0
Exp/Cntr=0.3,0.1

Type RM Length L Ch R = 1 ,49410   ,543,543,543
BEGIN DESCRIPTION:
Mapping XS 48004c29
END DESCRIPTION:
XS GIS Cut Line= 3
      1480705.31      6835552.67      1482198.37      6833447.63
      1482610.07      6832533.22
#Sta/Elev= 30
  3196.4  2065.8  3316.3    2059    3376 2056.42  3442.2 2052.68  3582.4 2043.78
  3824.9 2030.91  3904.4 2028.14  3938.9 2026.58  4117.1  2017.7  4140.9 2015.95
  4426.9 2002.63  4762.7 1992.17    4870 1992.01  4955.9 1991.91  4979.3 1986.35
  4992.1 1991.34  4996.5 1986.35    4997 1985.85  5003.6 1986.35  5006.3 1993.15
    5282 1993.42  5631.6 1992.38  5795.5 1995.53  5901.6 1996.76  6113.8  1999.4
  6163.7 2002.28  6330.8  2002.1  6599.3 2011.09  6719.9  2019.7    6780 2020.29
#Mann= 20 ,-1 , 0
  3196.4     .07       0  3316.3    .035       0    3376     .07       0
  3442.2    .035       0  3582.4    .035       0  3824.9     .07       0
  3904.4    .035       0  3938.9     .07       0  4117.1    .035       0
  4140.9    .045       0    4870     .07       0  4996.5     .07       0
  5003.6     .07       0    5282    .045       0  5631.6    .035       0
  5795.5     .07       0  5901.6    .035       0  6113.8     .07       0
  6163.7    .035       0  6330.8     .07       0
Bank Sta=4996.5,5003.6
XS Rating Curve= 0 ,0
Exp/Cntr=0.3,0.1

Type RM Length L Ch R = 1 ,48867   ,442,442,442
BEGIN DESCRIPTION:
Mapping XS 1e6ddc13
END DESCRIPTION:
XS GIS Cut Line= 4
      1481055.74      6835875.66      1481821.38      6834797.51
      1482837.01      6833443.34      1483029.72      6832818.34
#Sta/Elev= 30
  3253.6 2140.43  3258.9  2137.5  3295.2 2133.63  3324.1 2121.88  3359.8 2096.94
  3380.7 2078.37  3416.4 2058.18  3437.3 2051.56  3481.6 2046.35  3573.8 2045.36
  3645.4 2040.84    3746 2023.92  3876.5 2021.55  3882.8 2021.53  4112.1 2016.06
  4232.2 2009.81  4832.5 1990.59  4956.8 1989.51  4996.4 1984.26  4996.9 1983.76
  5003.6 1984.26  5006.8 1988.42    5013 1988.97  5119.5  1989.8  5479.7 1989.14
  5976.9 1989.56    6099 1991.13  6504.5  1993.5  6782.4 1999.12  6922.7 2002.95
#Mann= 15 ,-1 , 0
  3253.6     .16       0  3295.2     .07       0  3645.4     .16       0
  3876.5    .035       0  3882.8     .07       0  4112.1    .035       0
  4232.2    .045       0  4832.5     .07       0  4996.4     .07       0
  5003.6     .07       0  5119.5    .045       0  5479.7     .07       0
  5976.9    .035       0    6099     .07       0  6782.4    .035       0
Bank Sta=4996.4,5003.6
XS Rating Curve= 0 ,0
Exp/Cntr=0.3,0.1

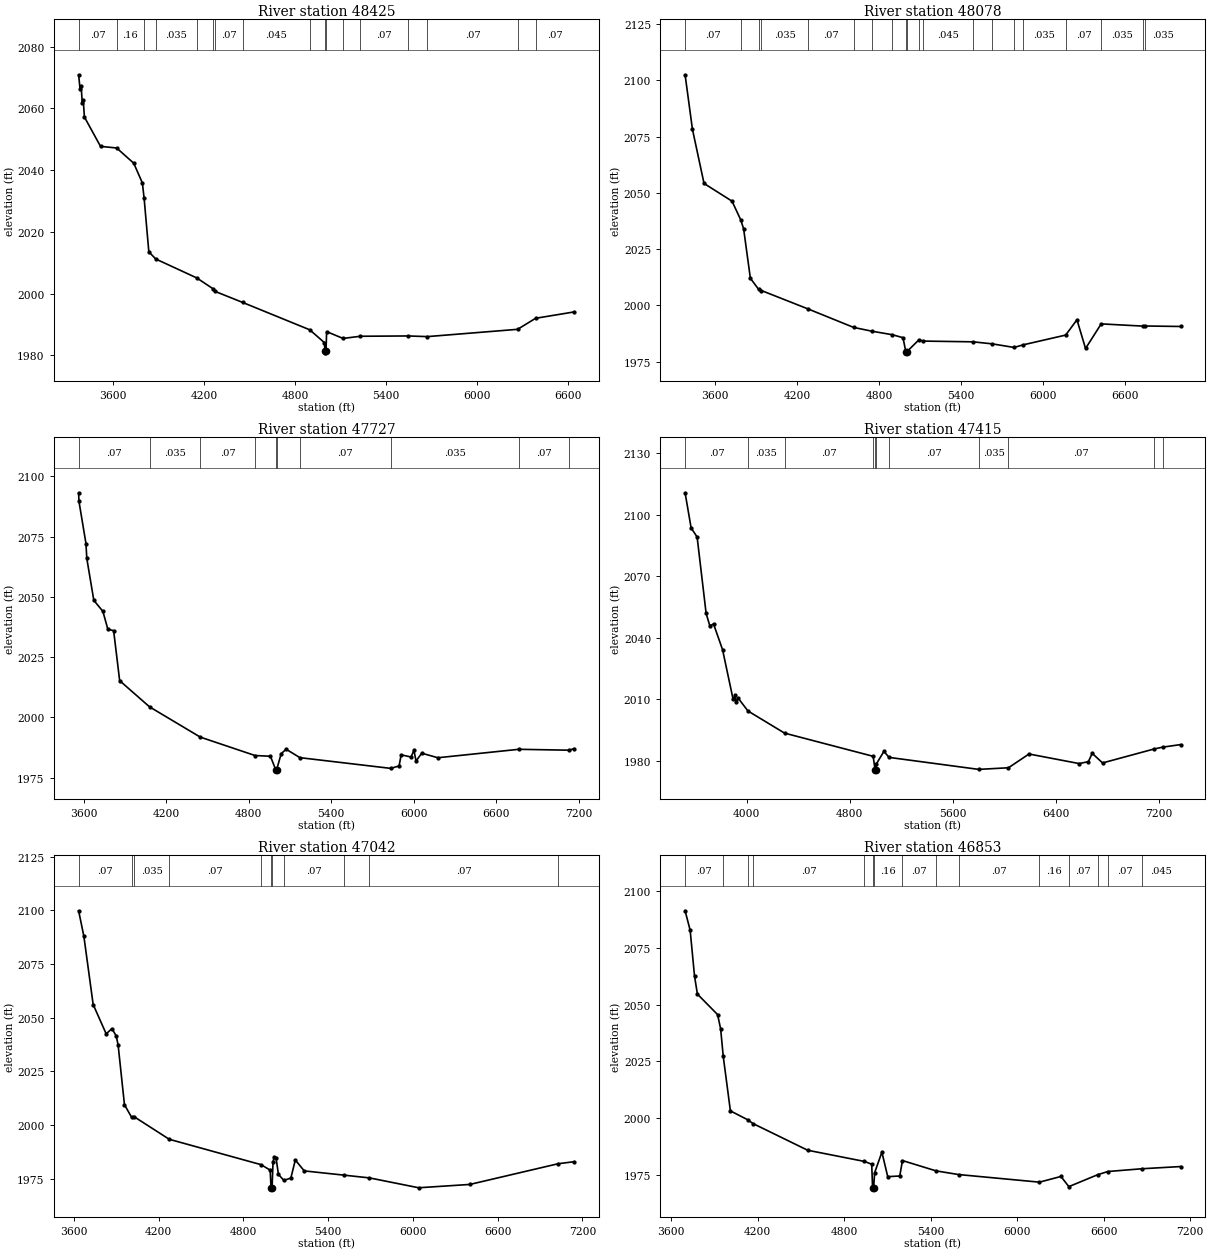
Type RM Length L Ch R = 1 ,48425   ,347,347,347
BEGIN DESCRIPTION:
Mapping XS ba6e20c0
END DESCRIPTION:
XS GIS Cut Line= 4
      1481320.51      6835946.82      1482093.08      6835096.12
      1483308.36       6833585.7      1483373.03      6833421.89
#Sta/Elev= 30
  3374.3 2070.92  3383.9 2066.18  3390.7 2067.43  3398.1 2061.86  3404.9 2062.67
  3412.3 2057.24  3518.4 2047.73  3624.7  2047.2  3737.4 2042.26  3794.1 2035.87
  3805.7 2030.87  3836.7 2013.55  3882.8 2011.22  4151.6 2005.12  4261.6 2001.53
    4270  2000.8  4454.2 1997.17  4896.2  1988.3  4993.3 1984.13  4996.4 1981.33
  4996.9 1980.83  5003.7 1981.33  5007.7 1987.71  5115.9  1985.5  5229.9  1986.2
  5543.6  1986.3  5671.3 1986.09  6265.6 1988.45    6384 1992.02  6638.2 1994.09
#Mann= 17 ,-1 , 0
  3374.3     .07       0  3624.7     .16       0  3805.7     .07       0
  3882.8    .035       0  4151.6     .07       0  4261.6    .045       0
    4270     .07       0  4454.2    .045       0  4896.2     .07       0
  4996.4     .07       0  5003.7     .07       0  5115.9    .045       0
  5229.9     .07       0  5543.6    .045       0  5671.3     .07       0
  6265.6    .035       0    6384     .07       0
Bank Sta=4996.4,5003.7
XS Rating Curve= 0 ,0
Exp/Cntr=0.3,0.1

Type RM Length L Ch R = 1 ,48078   ,351,351,351
BEGIN DESCRIPTION:
Mapping XS 6b7d4d09
END DESCRIPTION:
XS GIS Cut Line= 3
      1481425.78      6836064.84      1482181.01      6835257.53
      1484259.99      6833825.24
#Sta/Elev= 30
  3379.3 2102.43    3433 2078.25    3518 2054.17  3723.2 2046.29  3786.6 2038.03
  3808.1 2033.99  3857.5 2012.05  3917.4 2007.18  3938.3 2006.61  4282.3 1998.38
  4613.6 1990.24    4747 1988.56    4898 1986.98  4975.4 1985.67  4996.3 1979.44
  4996.8 1978.94  5003.7 1979.44  5092.3 1984.72  5124.2 1984.16  5488.3 1983.83
  5630.3 1982.92  5789.2 1981.33    5855 1982.48  6167.3 1986.83  6249.9 1993.62
  6312.8 1980.87  6427.4  1991.8  6735.5  1990.8  6749.8 1990.86  7009.4 1990.65
#Mann= 20 ,-1 , 0
  3379.3     .07       0  3786.6     .16       0  3917.4     .07       0
  3938.3    .035       0  4282.3     .07       0  4613.6    .045       0
    4747     .07       0    4898     .16       0  4996.3     .07       0
  5003.7     .16       0  5092.3     .07       0  5124.2    .045       0
  5488.3     .07       0  5630.3    .035       0  5789.2     .07       0
    5855    .035       0  6167.3     .07       0  6427.4    .035       0
  6735.5     .07       0  6749.8    .035       0
Bank Sta=4996.3,5003.7
XS Rating Curve= 0 ,0
Exp/Cntr=0.3,0.1

Type RM Length L Ch R = 1 ,47727   ,312,312,312
BEGIN DESCRIPTION:
Mapping XS ec7f1b14
END DESCRIPTION:
XS GIS Cut Line= 4
      1481537.56      6836063.98      1482531.45       6835395.6
      1484180.76      6834280.14        1484501.      6834020.49
#Sta/Elev= 30
  3564.5 2093.13  3566.8 2089.62  3617.8 2072.08  3623.9  2065.9  3674.8 2048.54
  3740.8 2043.96  3776.8 2036.55  3818.8 2035.97  3862.7 2015.23  4079.7 2004.38
  4448.3 1991.83  4846.7 1984.19  4958.4 1983.89  4996.3 1978.34  4996.8 1977.84
  5003.7 1978.34  5036.4 1984.95  5072.3  1986.8  5172.9  1983.3  5832.5 1978.86
  5893.3 1979.88  5908.3 1984.48  5980.2 1983.57  6001.2 1986.38  6016.2  1981.9
  6058.2 1985.15    6175 1983.27  6763.3 1986.77  7128.7  1986.4  7165.6 1987.07
#Mann= 10 ,-1 , 0
  3564.5     .07       0  4079.7    .035       0  4448.3     .07       0
  4846.7     .16       0  4996.3     .07       0  5003.7     .16       0
  5172.9     .07       0  5832.5    .035       0  6763.3     .07       0
  7128.7    .035       0
Bank Sta=4996.3,5003.7
XS Rating Curve= 0 ,0
Exp/Cntr=0.3,0.1

Type RM Length L Ch R = 1 ,47415   ,373,373,373
BEGIN DESCRIPTION:
Mapping XS 08d8e8b8
END DESCRIPTION:
XS GIS Cut Line= 4
      1481534.89      6836130.86      1482628.67      6835646.46
      1484670.34      6834448.55      1484883.91      6834266.23
#Sta/Elev= 30
  3522.1  2110.8  3568.8 2093.66  3615.4  2089.2  3685.2 2051.93    3714 2045.84
  3742.7 2046.78  3812.6 2034.25  3894.1 2010.13  3911.2  2011.9  3916.7 2008.66
  3934.5 2010.51  4009.5 2004.32  4293.6  1993.5  4980.9 1982.18  4996.3 1975.59
  4996.8 1975.09  5003.8 1975.59  5005.8 1978.44  5064.4 1984.59  5104.4 1981.65
  5799.6  1975.8  6030.6 1976.59  6189.9 1983.31  6578.8 1978.64  6650.3 1979.56
  6680.4 1983.64  6760.5 1978.94  7159.8 1985.75  7227.5 1986.66  7366.3  1987.9
#Mann= 11 ,-1 , 0
  3522.1     .07       0  4009.5    .035       0  4293.6     .07       0
  4980.9     .16       0  4996.3     .07       0  5003.8     .16       0
  5104.4     .07       0  5799.6    .035       0  6030.6     .07       0
  7159.8    .045       0  7227.5     .07       0
Bank Sta=4996.3,5003.8
XS Rating Curve= 0 ,0
Exp/Cntr=0.3,0.1

Type RM Length L Ch R = 1 ,47042   ,189,189,189
BEGIN DESCRIPTION:
Mapping XS dd981d3a
END DESCRIPTION:
XS GIS Cut Line= 3
      1481624.35       6836150.8      1482787.53      6835903.41
      1484991.07      6835183.35
#Sta/Elev= 30
  3634.6 2099.75  3671.6 2087.91  3737.5 2056.12  3829.5 2042.49  3870.4 2044.92
  3901.1 2041.42  3914.4 2037.11  3958.9 2009.53  4009.8 2003.62  4025.7 2003.98
    4276 1993.41  4925.7  1981.6  4990.4 1979.05  4996.3 1970.85  4996.8 1970.35
  5003.8 1970.85  5010.5 1982.81    5017 1984.94  5031.5 1984.84  5048.9 1977.08
  5087.3 1974.27  5136.8 1975.38  5168.3 1983.77  5231.4  1978.7  5514.5 1976.71
  5693.3 1975.44  6041.5 1970.85  6403.6  1972.4    7029 1982.04    7142 1982.98
#Mann= 11 ,-1 , 0
  3634.6     .07       0  4009.8     .16       0  4025.7    .035       0
    4276     .07       0  4925.7     .16       0  4996.3     .07       0
  5003.8     .16       0  5087.3     .07       0  5514.5    .035       0
  5693.3     .07       0    7029    .045       0
Bank Sta=4996.3,5003.8
XS Rating Curve= 0 ,0
Exp/Cntr=0.3,0.1

Type RM Length L Ch R = 1 ,46853   ,143,143,143
BEGIN DESCRIPTION:
Mapping XS f4a48d65
END DESCRIPTION:
XS GIS Cut Line= 4
      1481660.15      6836199.37      1482523.89      6836099.54
      1483934.48      6835899.89      1485067.31      6835739.29
#Sta/Elev= 30
  3695.5 2091.27  3730.6  2082.7  3760.8 2062.57  3780.9 2054.59    3921 2045.57
    3942 2039.34  3960.2 2027.17  4009.8 2003.19  4128.9 1999.31  4166.4 1997.62
    4546 1985.87  4938.5 1980.96  4990.3 1979.72  4996.3 1969.38  4996.8 1968.88
  5003.8 1969.38  5010.5 1975.95    5061 1985.04  5101.4 1974.25  5184.9 1974.53
  5203.7 1981.33  5436.4 1976.79  5592.7 1975.17  6154.4 1971.82  6303.3 1974.33
  6358.1 1969.85  6557.6 1975.08  6629.4 1976.51  6867.3 1977.73  7133.8 1978.69
#Mann= 15 ,-1 , 0
  3695.5     .07       0  3960.2     .16       0  4128.9    .035       0
  4166.4     .07       0  4938.5     .16       0  4996.3     .07       0
  5003.8     .16       0  5203.7     .07       0  5436.4    .035       0
  5592.7     .07       0  6154.4     .16       0  6358.1     .07       0
  6557.6     .16       0  6629.4     .07       0  6867.3    .045       0
Bank Sta=4996.3,5003.8
XS Rating Curve= 0 ,0
Exp/Cntr=0.3,0.1

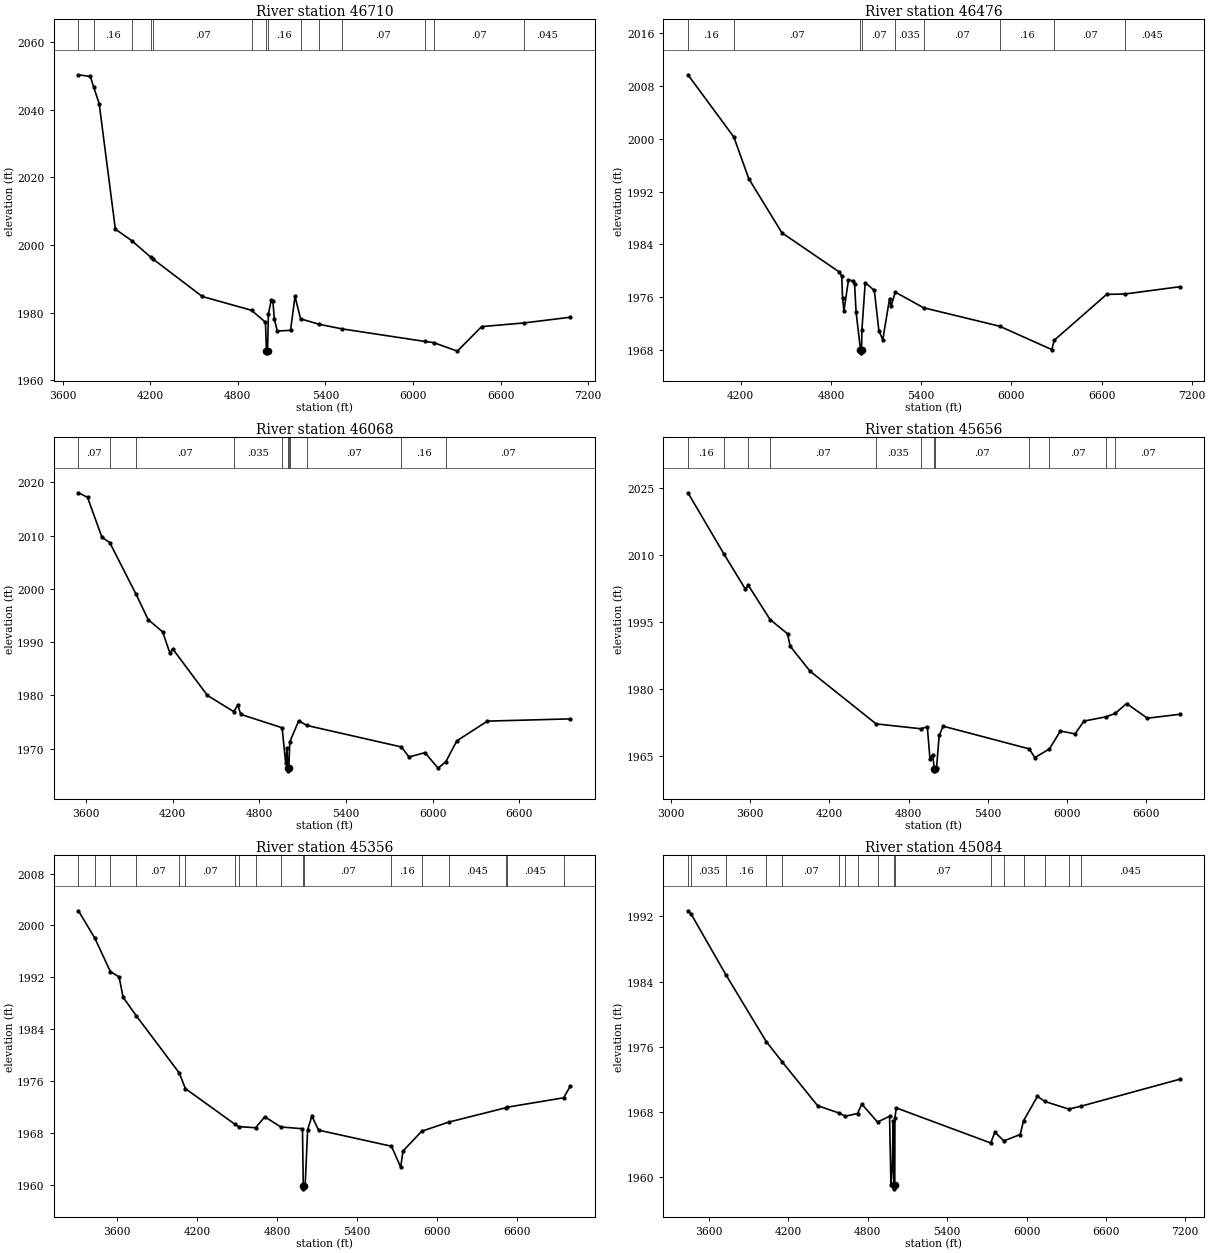
Type RM Length L Ch R = 1 ,46710   ,234,234,234
BEGIN DESCRIPTION:
Mapping XS 3d12b9a7
END DESCRIPTION:
XS GIS Cut Line= 4
      1481724.16      6836324.41      1482835.27      6836189.87
      1484740.65      6835912.09      1485057.48      6835846.99
#Sta/Elev= 30
    3709 2050.39  3790.4 2049.89  3812.1  2046.9  3850.9 2041.85  3961.7 2004.69
  4074.4 2001.28  4204.4 1996.38  4221.8 1995.77  4556.8 1984.76  4894.4 1980.67
  4989.6 1977.14  4996.3 1968.58  4996.8 1968.08  5003.8 1968.58  5009.6 1979.62
  5030.1 1983.73  5040.2 1983.52  5050.3 1978.06  5070.5 1974.54  5161.4 1974.74
  5191.8 1984.77  5230.1 1978.14  5358.2 1976.53    5511 1975.19    6083 1971.44
  6140.5 1971.12  6303.4 1968.58  6470.1 1975.85  6760.1 1976.93  7077.2 1978.62
#Mann= 14 ,-1 , 0
    3709     .07       0  3812.1     .16       0  4074.4     .07       0
  4204.4     .16       0  4221.8     .07       0  4894.4     .16       0
  4996.3     .07       0  5003.8     .16       0  5230.1     .07       0
  5358.2    .035       0    5511     .07       0    6083     .16       0
  6140.5     .07       0  6760.1    .045       0
Bank Sta=4996.3,5003.8
XS Rating Curve= 0 ,0
Exp/Cntr=0.3,0.1

Type RM Length L Ch R = 1 ,46476   ,408,408,408
BEGIN DESCRIPTION:
Mapping XS da6d6fe9
END DESCRIPTION:
XS GIS Cut Line= 4
      1481902.14      6836502.36      1482865.65      6836411.22
      1483920.34      6836254.97      1485130.64      6835990.35
#Sta/Elev= 30
  3848.3 2009.69    4154 2000.25    4253 1993.96  4473.8 1985.76  4855.9 1979.82
  4871.6 1979.18  4876.7 1975.96  4886.2 1973.97  4916.5 1978.62  4946.9  1978.5
    4957 1977.98  4967.1 1973.74  4996.2 1968.09  4996.7 1967.59  5003.8 1968.09
  5005.6 1971.01  5027.7 1978.21  5088.4 1977.04  5118.7 1970.94  5144.6 1969.58
  5189.5 1975.74  5199.6 1974.61  5227.8 1976.78  5415.6 1974.42  5921.9 1971.62
  6268.5 1968.09  6286.6 1969.52  6634.3 1976.44  6756.6  1976.5  7121.2  1977.6
#Mann= 9 ,-1 , 0
  3848.3     .16       0    4154     .07       0  4996.2     .07       0
  5003.8     .07       0  5227.8    .035       0  5415.6     .07       0
  5921.9     .16       0  6286.6     .07       0  6756.6    .045       0
Bank Sta=4996.2,5003.8
XS Rating Curve= 0 ,0
Exp/Cntr=0.3,0.1

Type RM Length L Ch R = 1 ,46068   ,412,412,412
BEGIN DESCRIPTION:
Mapping XS 88432126
END DESCRIPTION:
XS GIS Cut Line= 4
      1481802.26       6836775.8      1482765.83      6836736.74
       1484788.4      6836524.07      1485174.71      6836385.17
#Sta/Elev= 30
  3546.3 2018.06  3609.1 2017.21  3709.2 2009.69    3763 2008.72  3944.1 1999.07
  4029.4 1994.24  4129.5 1991.94  4179.6 1987.99  4199.6 1988.74  4439.8    1980
  4622.4 1976.95  4650.6 1978.22  4670.7 1976.44  4957.5 1973.92  4982.4 1967.33
  4992.5 1970.07  4996.2 1966.33  4996.7 1965.83  5003.8 1966.33    5011 1971.27
  5072.9 1975.25  5128.4 1974.36  5783.9 1970.32  5837.1 1968.43  5947.7 1969.25
  6038.2 1966.33  6092.2 1967.55    6168 1971.46  6380.1 1975.17  6954.9 1975.59
#Mann= 11 ,-1 , 0
  3546.3     .07       0    3763     .16       0  3944.1     .07       0
  4622.4    .035       0  4957.5     .07       0  4996.2     .07       0
  5003.8     .07       0    5011    .035       0  5128.4     .07       0
  5783.9     .16       0  6092.2     .07       0
Bank Sta=4996.2,5003.8
XS Rating Curve= 0 ,0
Exp/Cntr=0.3,0.1

Type RM Length L Ch R = 1 ,45656   ,300,300,300
BEGIN DESCRIPTION:
Mapping XS db6d060a
END DESCRIPTION:
XS GIS Cut Line= 3
      1481529.99      6837006.66      1483773.89       6837054.4
      1485201.84      6836642.07
#Sta/Elev= 30
  3126.9 2024.03  3401.9 2010.18    3562 2002.41  3585.6 2003.21  3750.3 1995.55
  3882.1 1992.36  3902.1 1989.58  4052.1 1983.99  4553.7 1972.13  4893.8 1971.03
  4942.3 1971.47  4962.3 1964.35  4982.3 1965.16  4996.2 1962.08  4996.7 1961.58
  5003.8 1962.08  5012.3 1962.23  5032.3 1969.52  5062.4 1971.61  5715.5 1966.51
  5757.6 1964.56  5868.3 1966.49  5951.6 1970.52  6062.9 1969.88  6130.2 1972.75
  6300.2 1973.73  6368.7  1974.5  6453.8  1976.7  6611.1  1973.4  6857.6 1974.28
#Mann= 12 ,-1 , 0
  3126.9     .16       0  3401.9     .07       0  3585.6     .16       0
  3750.3     .07       0  4553.7    .035       0  4893.8     .07       0
  4996.2     .07       0  5003.8     .07       0  5715.5     .16       0
  5868.3     .07       0  6300.2    .045       0  6368.7     .07       0
Bank Sta=4996.2,5003.8
XS Rating Curve= 0 ,0
Exp/Cntr=0.3,0.1

Type RM Length L Ch R = 1 ,45356   ,272,272,272
BEGIN DESCRIPTION:
Mapping XS 7e1e1082
END DESCRIPTION:
XS GIS Cut Line= 4
      1481719.83      6837392.12      1482735.45      6837392.12
      1484762.35      6837105.66      1485343.48      6836862.81
#Sta/Elev= 30
  3308.5 2002.26  3432.1 1998.01  3547.9 1992.88  3613.7 1992.06  3643.7 1988.92
  3743.1 1986.06  4065.5 1977.24  4111.2 1974.84  4484.5 1969.32  4510.2 1968.98
  4638.3  1968.8  4707.4 1970.49  4827.6 1968.92  4990.2 1968.65  4996.2 1959.88
  4996.7 1959.38  5003.8 1959.88  5010.4 1959.88    5029 1968.51  5060.9 1970.59
  5111.4 1968.43  5658.2 1965.95  5727.5 1962.72  5744.8 1965.21    5885 1968.26
  6086.6 1969.66  6519.3  1971.9  6524.2 1971.96  6951.1 1973.42    7001 1975.24
#Mann= 18 ,-1 , 0
  3308.5     .16       0  3432.1    .035       0  3547.9     .16       0
  3743.1     .07       0  4065.5    .035       0  4111.2     .07       0
  4484.5    .035       0  4510.2     .07       0  4638.3    .035       0
  4827.6     .07       0  4996.2     .07       0  5003.8     .07       0
  5658.2     .16       0    5885     .07       0  6086.6    .045       0
  6519.3     .07       0  6524.2    .045       0  6951.1     .07       0
Bank Sta=4996.2,5003.8
XS Rating Curve= 0 ,0
Exp/Cntr=0.3,0.1

Type RM Length L Ch R = 1 ,45084   ,396,396,396
BEGIN DESCRIPTION:
Mapping XS 0cf10d5d
END DESCRIPTION:
XS GIS Cut Line= 4
      1481754.55      6837613.48      1482726.76       6837604.8
      1484823.12      6837344.38      1485400.19      6837079.71
#Sta/Elev= 30
  3439.7  1992.7  3464.4 1992.28    3729 1984.78  4031.4 1976.65  4151.8 1974.16
  4420.3 1968.77  4585.5 1967.85  4627.9 1967.47  4722.5 1967.81  4754.4 1968.96
  4873.3 1966.76  4964.4 1967.47  4974.5 1959.06  4984.6 1961.23    4992 1966.89
  4996.2 1959.06  4996.7 1958.56  5003.8 1959.06  5004.7 1967.22  5014.8  1968.5
  5729.1 1964.19  5760.5 1965.51  5829.2 1964.45  5951.9 1965.23  5977.7 1966.93
  6082.9 1969.92  6138.6 1969.29  6318.9 1968.35    6413 1968.71  7159.3 1972.02
#Mann= 17 ,-1 , 0
  3439.7     .16       0  3464.4    .035       0    3729     .16       0
  4031.4    .035       0  4151.8     .07       0  4585.5    .035       0
  4627.9     .07       0  4722.5    .035       0  4873.3     .07       0
  4996.2     .07       0  5003.8     .07       0  5729.1    .045       0
  5829.2     .16       0  5977.7     .07       0  6138.6    .045       0
  6318.9     .07       0    6413    .045       0
Bank Sta=4996.2,5003.8
XS Rating Curve= 0 ,0
Exp/Cntr=0.3,0.1