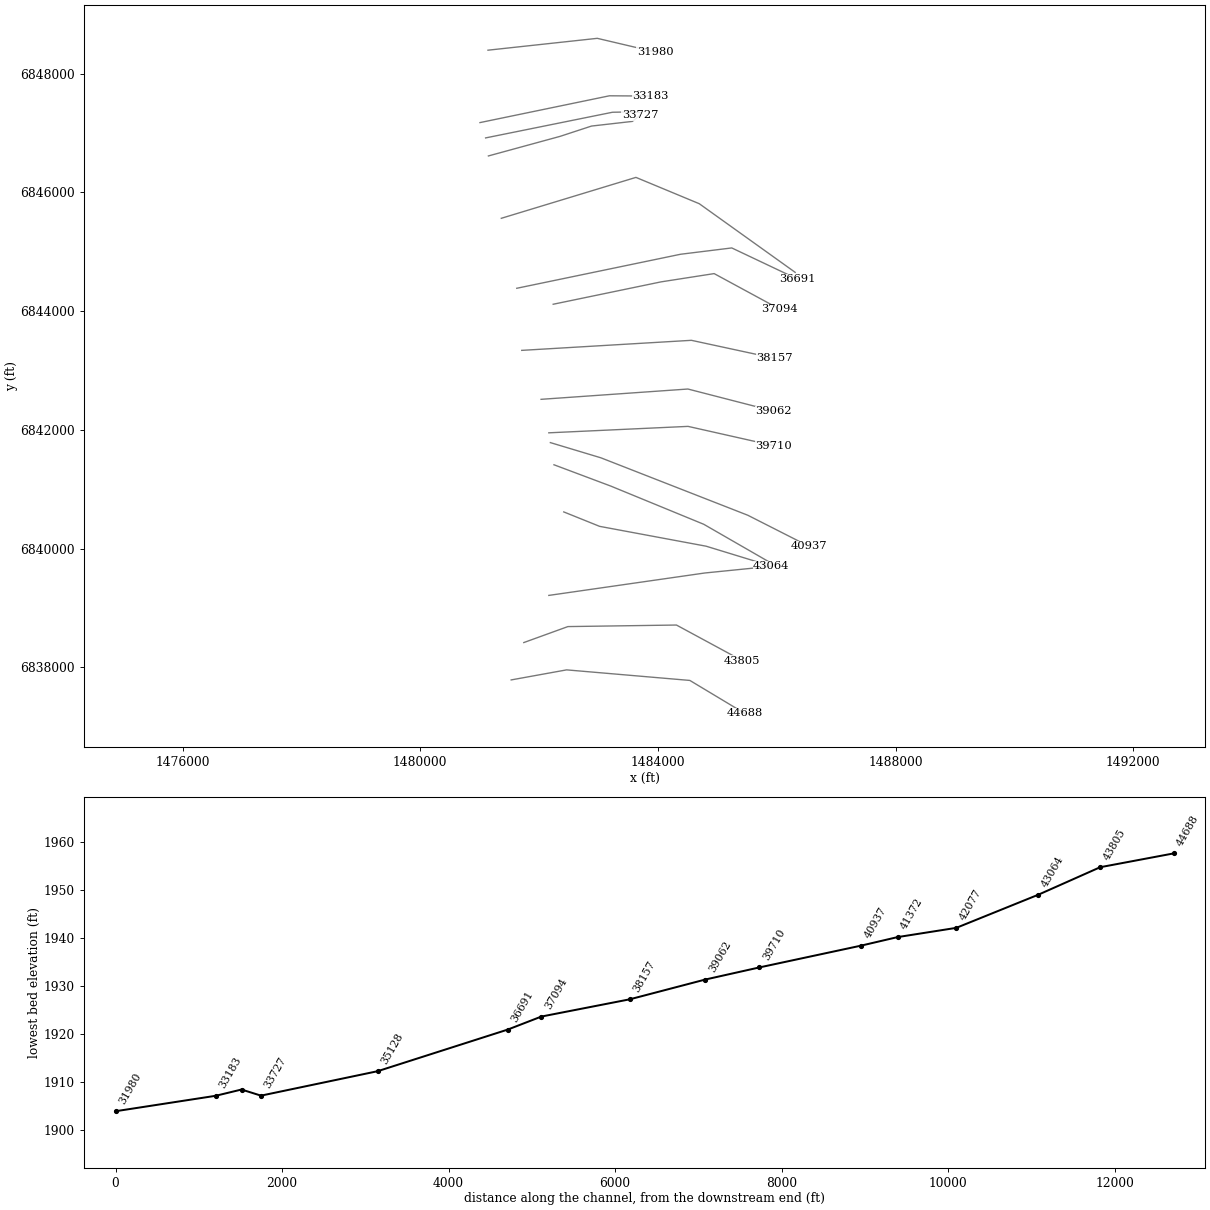
HEC-RAS study Little Bitter Creek.prj: Little Bitter Creek Base Level Engineering

--- Little Bitter Creek.g01 (geometry) --- (continued)

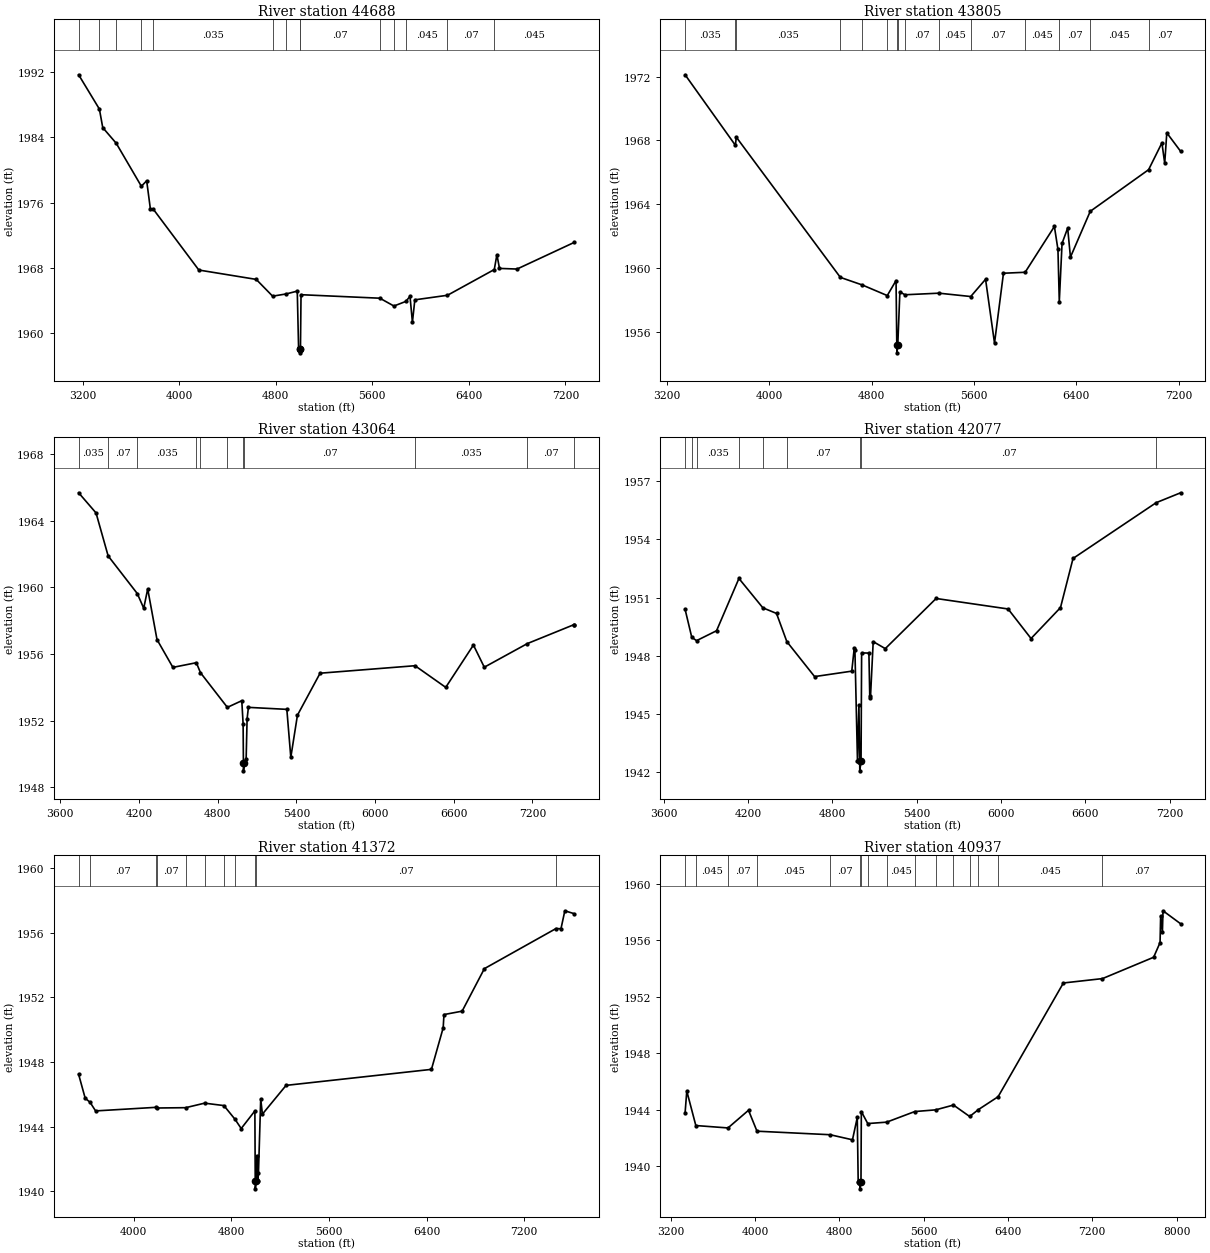
Type RM Length L Ch R = 1 ,44688   ,883,883,883
BEGIN DESCRIPTION:
Mapping XS 67e9ea58
END DESCRIPTION:
XS GIS Cut Line= 4
      1481529.93       6837787.9      1482463.13      6837957.18
      1484537.78      6837779.23      1485461.09      6837224.37
#Sta/Elev= 30
    3165  1991.7    3337 1987.49    3365 1985.21  3476.6 1983.29    3685 1978.01
  3729.1 1978.68  3759.6 1975.24  3785.1 1975.17  4161.4 1967.72  4637.2 1966.57
  4773.1 1964.51  4884.3 1964.78  4977.4 1965.13  4988.5 1958.05  4996.2 1958.05
  4996.7 1957.55  5003.9 1958.05  5008.6 1964.69    5662 1964.26  5778.7  1963.3
  5878.3 1963.87  5911.9  1964.5    5932 1961.31    5952 1964.06  6222.7 1964.62
  6610.6 1967.78  6632.4  1969.6  6653.8 1967.92  6799.1 1967.84  7272.9 1971.11
#Mann= 14 ,-1 , 0
    3165     .16       0    3337    .035       0  3476.6     .16       0
    3685     .07       0  3785.1    .035       0  4773.1     .16       0
  4884.3     .07       0  4996.2     .07       0  5003.9     .07       0
    5662    .045       0  5778.7     .07       0  5878.3    .045       0
  6222.7     .07       0  6610.6    .045       0
Bank Sta=4996.2,5003.9
XS Rating Curve= 0 ,0
Exp/Cntr=0.3,0.1

Type RM Length L Ch R = 1 ,43805   ,741,741,741
BEGIN DESCRIPTION:
Mapping XS 8738e7a3
END DESCRIPTION:
XS GIS Cut Line= 4
      1481742.64      6838417.25      1482484.83      6838686.34
      1484312.09      6838712.39      1485418.89      6838113.41
#Sta/Elev= 30
  3340.6 1972.11  3733.9 1967.69    3741  1968.2  4554.8 1959.41  4727.6 1958.93
  4921.6 1958.27  4990.3 1959.21  4996.2 1955.18  4996.7 1954.68  5003.9 1955.18
  5020.3  1958.5  5059.8 1958.32  5325.6 1958.42  5574.4 1958.21  5690.4 1959.29
  5760.4 1955.29  5830.4 1959.67  5999.9 1959.73  6228.7  1962.6  6256.5 1961.16
    6267 1957.89  6288.6 1961.54  6332.4  1962.5  6354.3 1960.68  6509.1 1963.55
  6965.4 1966.16  7069.6 1967.84  7091.5 1966.56  7107.7 1968.47    7216 1967.31
#Mann= 15 ,-1 , 0
  3340.6    .035       0  3733.9     .07       0    3741    .035       0
  4554.8     .16       0  4727.6     .07       0  4921.6     .16       0
  4996.2     .07       0  5003.9     .16       0  5059.8     .07       0
  5325.6    .045       0  5574.4     .07       0  5999.9    .045       0
    6267     .07       0  6509.1    .045       0  6965.4     .07       0
Bank Sta=4996.2,5003.9
XS Rating Curve= 0 ,0
Exp/Cntr=0.3,0.1

Type RM Length L Ch R = 1 ,43064   ,987,987,987
BEGIN DESCRIPTION:
Mapping XS 2c2bd02a
END DESCRIPTION:
XS GIS Cut Line= 3
      1482163.63      6839211.52      1484789.52      6839589.12
      1485909.34      6839701.97
#Sta/Elev= 30
  3739.6 1965.67  3872.3 1964.46  3964.6 1961.88  4186.9 1959.62    4236 1958.74
  4266.3  1959.9  4337.1 1956.86  4458.3 1955.19  4637.1 1955.47  4668.7 1954.87
  4873.7 1952.79  4983.6 1953.19  4993.7 1951.81    4996 1949.48  4996.5 1948.98
  5004.1 1949.48  5016.8 1949.67  5024.1  1952.1  5034.2 1952.79  5327.1 1952.67
  5357.4 1949.79    5408 1952.32  5580.7 1954.84  6304.4 1955.29  6538.7 1953.99
  6749.8 1956.53  6832.7  1955.2  7161.5 1956.62    7515 1957.75    7518 1957.75
#Mann= 11 ,-1 , 0
  3739.6    .035       0  3964.6     .07       0  4186.9    .035       0
  4637.1     .07       0  4668.7    .035       0  4873.7     .07       0
    4996     .07       0  5004.1     .07       0  6304.4    .035       0
  7161.5     .07       0    7515    .035       0
Bank Sta=4996,5004.1
XS Rating Curve= 0 ,0
Exp/Cntr=0.3,0.1

Type RM Length L Ch R = 1 ,42077   ,705,705,705
BEGIN DESCRIPTION:
Mapping XS 62555ff9
END DESCRIPTION:
XS GIS Cut Line= 4
      1482415.35      6840617.78      1483018.68      6840374.71
      1484811.22      6840040.51      1485817.09      6839732.68
#Sta/Elev= 30
  3752.9 1950.39  3800.4 1948.95  3834.6 1948.78  3976.7 1949.29  4135.9 1951.98
  4306.1 1950.47  4403.4 1950.18  4476.8 1948.73  4674.3 1946.93  4938.7 1947.21
  4956.2 1948.38  4961.2 1948.29  4979.4 1942.58  4989.6 1945.45  4995.3 1942.58
  4995.8 1942.08  5004.8 1942.58  5008.9 1948.15  5060.8 1948.14  5066.7 1945.94
  5071.7 1945.84  5091.3 1948.73  5177.2 1948.37  5538.9 1950.95  6051.1 1950.41
  6214.3 1948.89  6423.8 1950.48  6513.1 1953.01  7104.5 1955.88  7278.7 1956.39
#Mann= 9 ,-1 , 0
  3752.9    .035       0  3800.4     .07       0  3834.6    .035       0
  4135.9     .07       0  4306.1    .035       0  4476.8     .07       0
  4995.3     .07       0  5004.8     .07       0  7104.5    .035       0
Bank Sta=4995.3,5004.8
XS Rating Curve= 0 ,0
Exp/Cntr=0.3,0.1

Type RM Length L Ch R = 1 ,41372   ,435,435,435
BEGIN DESCRIPTION:
Mapping XS e66fa82d
END DESCRIPTION:
XS GIS Cut Line= 4
      1482250.41      6841412.05      1483209.66       6841051.8
      1484772.16      6840409.44      1485939.66      6839736.71
#Sta/Elev= 30
  3547.8 1947.24  3601.4 1945.77  3641.7 1945.51  3686.8 1944.98    4178  1945.2
  4186.9 1945.16    4425 1945.18  4580.2 1945.46  4738.4 1945.31  4829.8 1944.46
  4880.2 1943.89  4992.3 1944.98  4995.3 1940.66  4995.8 1940.16  5004.8 1940.66
  5010.7 1942.19  5016.3 1940.66  5021.7 1941.13  5040.2 1945.73    5054 1944.78
  5248.1 1946.56  6439.5 1947.55  6535.7 1950.12  6542.1 1950.94  6690.9 1951.15
  6873.3 1953.78  7460.2 1956.26  7501.2 1956.25  7532.8 1957.36  7609.3 1957.18
#Mann= 11 ,-1 , 0
  3547.8    .035       0  3641.7     .07       0    4178    .035       0
  4186.9     .07       0    4425    .035       0  4580.2     .07       0
  4738.4    .035       0  4829.8     .07       0  4995.3     .07       0
  5004.8     .07       0  7460.2    .035       0
Bank Sta=4995.3,5004.8
XS Rating Curve= 0 ,0
Exp/Cntr=0.3,0.1

Type RM Length L Ch R = 1 ,40937   ,1227,1227,1227
BEGIN DESCRIPTION:
Mapping XS 6854ea4d
END DESCRIPTION:
XS GIS Cut Line= 4
      1482189.68      6841785.31      1483040.39      6841529.23
      1485514.34      6840561.34      1486547.34      6840036.16
#Sta/Elev= 30
  3335.4 1943.78  3351.4 1945.32  3437.3 1942.88  3742.5 1942.71  3937.3 1943.96
  4017.8 1942.48  4712.6 1942.23  4924.2 1941.87  4969.7 1943.45  4978.5  1938.9
  4995.2  1938.9  4995.7  1938.4  5004.9  1938.9  5008.3 1943.87  5069.2 1943.02
  5248.8 1943.12  5515.3 1943.87  5714.2 1943.99  5882.9 1944.33  6036.6 1943.52
  6119.9 1944.01  6306.6 1944.92  6926.2 1952.97  7297.3 1953.28  7782.8 1954.79
  7843.9 1955.83  7849.5 1957.73  7866.2 1956.59  7871.8 1958.08  8039.2 1957.16
#Mann= 16 ,-1 , 0
  3335.4    .035       0  3437.3    .045       0  3742.5     .07       0
  4017.8    .045       0  4712.6     .07       0  4995.2     .07       0
  5004.9     .07       0  5069.2     .16       0  5248.8    .045       0
  5515.3     .16       0  5714.2    .045       0  5882.9     .16       0
  6036.6    .045       0  6119.9     .07       0  6306.6    .045       0
  7297.3     .07       0
Bank Sta=4995.2,5004.9
XS Rating Curve= 0 ,0
Exp/Cntr=0.3,0.1

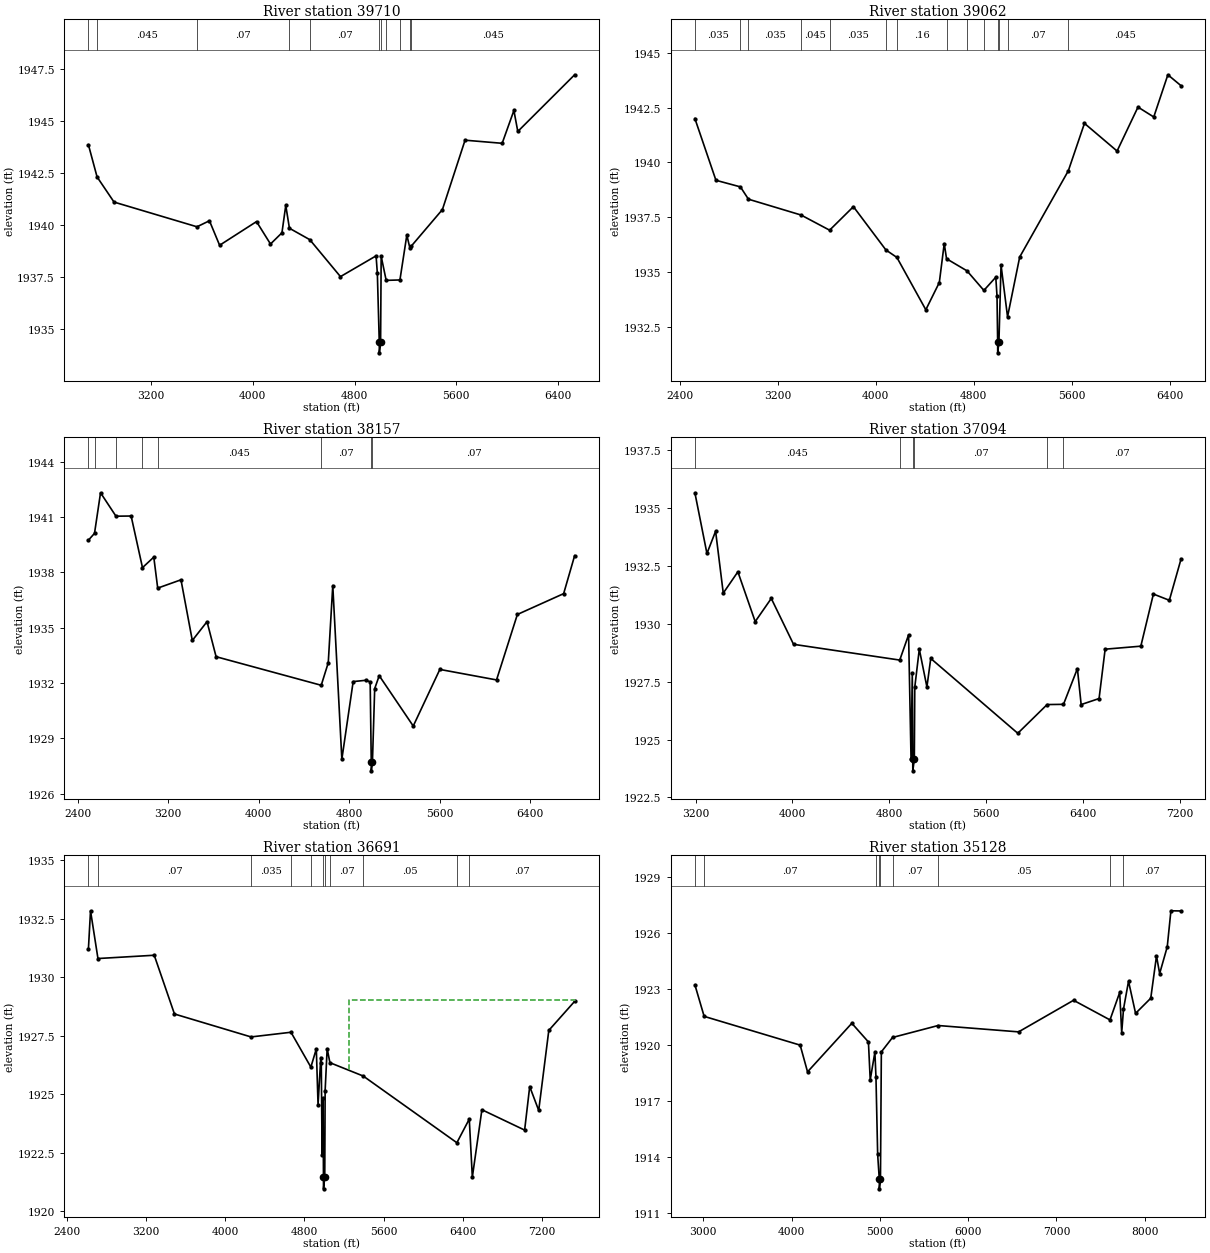
Type RM Length L Ch R = 1 ,39710   ,648,648,648
BEGIN DESCRIPTION:
Little Bitter Creek 21.0
END DESCRIPTION:
XS GIS Cut Line= 3
      1482163.61      6841950.23       1484507.4      6842058.74
      1485951.33      6841733.53
#Sta/Elev= 30
  2705.9 1943.87  2774.1 1942.32  2907.5 1941.11  3560.3 1939.92  3658.3 1940.21
  3738.4 1939.03  4028.7 1940.17  4138.8 1939.09  4228.9 1939.63    4259 1940.95
  4287.7 1939.85  4447.9  1939.3  4689.4 1937.52  4969.7 1938.52  4979.7 1937.68
  4994.9 1934.35  4995.4 1933.85  5005.2 1934.35  5009.8  1938.5  5049.2 1937.34
  5157.4 1937.36  5211.7 1939.52  5235.9 1938.89  5245.6 1938.98  5491.8 1940.75
  5669.9 1944.09    5962 1943.94  6054.3 1945.52    6085 1944.51  6532.3 1947.24
#Mann= 11 ,-1 , 0
  2705.9    .035       0  2774.1    .045       0  3560.3     .07       0
  4287.7    .045       0  4447.9     .07       0  4994.9     .07       0
  5005.2     .07       0  5049.2     .16       0  5157.4    .045       0
  5235.9     .07       0  5245.6    .045       0
Bank Sta=4994.9,5005.2
XS Rating Curve= 0 ,0
Exp/Cntr=0.3,0.1

Type RM Length L Ch R = 1 ,39062   ,905,905,905
BEGIN DESCRIPTION:
Little Bitter Creek 20.0
END DESCRIPTION:
XS GIS Cut Line= 3
       1482033.4      6842514.47        1484505.        6842688.
      1485951.34      6842315.17
#Sta/Elev= 30
  2521.9    1942  2693.9 1939.19  2893.8 1938.89  2959.3 1938.33    3389 1937.61
  3622.3 1936.92  3816.7 1937.99  4082.2 1936.02  4171.9 1935.68  4408.1  1933.3
  4518.4 1934.54  4558.5 1936.31  4577.4 1935.62  4744.5 1935.07  4882.3 1934.18
  4979.5 1934.78  4989.6 1933.93  4994.8 1931.84  4995.3 1931.34  5005.3 1931.84
  5022.5 1935.33  5075.6 1932.98  5174.9  1935.7  5571.9 1939.62  5703.8 1941.78
  5970.3 1940.52    6141 1942.52  6269.8 1942.07  6385.1 1943.99  6493.2 1943.49
#Mann= 14 ,-1 , 0
  2521.9    .035       0  2893.8     .07       0  2959.3    .035       0
    3389    .045       0  3622.3    .035       0  4082.2    .045       0
  4171.9     .16       0  4577.4    .045       0  4744.5     .07       0
  4882.3    .045       0  4994.8    .045       0  5005.3    .045       0
  5075.6     .07       0  5571.9    .045       0
Bank Sta=4994.8,5005.3
XS Rating Curve= 0 ,0
Exp/Cntr=0.3,0.1

Type RM Length L Ch R = 1 ,38157   ,1063,1063,1063
BEGIN DESCRIPTION:
Little Bitter Creek 19.0
END DESCRIPTION:
XS GIS Cut Line= 3
      1481707.96      6843339.12      1484563.82      6843508.39
        1485970.      6843204.59
#Sta/Elev= 30
  2493.7 1939.75  2547.6 1940.12  2600.9 1942.32  2737.4 1941.05  2871.4 1941.06
  2971.8 1938.26  3071.8 1938.83  3106.4 1937.15  3312.2  1937.6  3412.4 1934.31
  3542.6 1935.33  3622.7 1933.43  4552.4 1931.88  4614.5  1933.1  4654.5 1937.29
  4734.7 1927.87  4834.8 1932.08    4945 1932.15  4985.1 1932.07  4994.8 1927.74
  4995.3 1927.24  5005.3 1927.74  5025.2  1931.7  5065.2  1932.4    5366 1929.67
  5601.3 1932.74  6102.6 1932.17  6286.8 1935.72    6696 1936.85  6793.2 1938.91
#Mann= 8 ,-1 , 0
  2493.7    .045       0  2547.6    .035       0  2737.4    .045       0
  2971.8     .07       0  3106.4    .045       0  4552.4     .07       0
  4994.8     .07       0  5005.3     .07       0
Bank Sta=4994.8,5005.3
XS Rating Curve= 0 ,0
Exp/Cntr=0.3,0.1

Type RM Length L Ch R = 1 ,37094   ,403,403,403
BEGIN DESCRIPTION:
Mapping XS e6beed92
END DESCRIPTION:
XS GIS Cut Line= 4
      1482237.44      6844116.03      1484054.02      6844493.13
      1484946.55      6844632.25      1486050.39      6844033.46
#Sta/Elev= 30
  3194.7 1935.65  3294.3 1933.03  3365.8 1933.99    3429 1931.32  3549.7 1932.24
  3692.7 1930.09  3825.4 1931.09  4009.3 1929.11  4886.1 1928.43  4959.1 1929.52
  4979.5 1924.15  4989.7 1927.88  4993.5 1924.15    4994 1923.65  5006.5 1924.15
  5010.2 1927.26  5047.6  1928.9  5110.4 1927.27  5142.1  1928.5  5860.7 1925.27
  6102.9 1926.51  6238.1 1926.52  6352.8 1928.06  6383.9 1926.51  6531.8 1926.77
  6581.9  1928.9  6876.6 1929.03  6980.3 1931.28    7112 1931.01  7209.1  1932.8
#Mann= 6 ,-1 , 0
  3194.7    .045       0  4886.1     .07       0  4993.5     .07       0
  5006.5     .07       0  6102.9    .035       0  6238.1     .07       0
Bank Sta=4993.5,5006.5
XS Rating Curve= 0 ,0
Exp/Cntr=0.3,0.1

Type RM Length L Ch R = 1 ,36691   ,1563,1563,1563
BEGIN DESCRIPTION:
Mapping XS c3b67d6a
END DESCRIPTION:
XS GIS Cut Line= 4
      1481624.11      6844384.96      1484381.21      6844958.07
      1485243.42      6845064.54      1486351.38      6844539.17
#Sta/Elev= 30
  2619.5  1931.2  2640.8 1932.83  2715.8 1930.79  3284.3 1930.93  3488.6 1928.42
    4262 1927.44  4665.4 1927.64  4866.4 1926.15  4921.4 1926.93  4938.9 1924.54
  4966.4 1926.56  4971.5 1926.32  4979.8 1922.41    4990 1924.81  4993.5 1921.45
    4994 1920.95  5006.6 1921.45  5010.4 1925.15  5030.9 1926.94  5058.8 1926.34
  5394.9 1925.77    6341 1922.92  6466.3 1923.93  6497.2 1921.45  6593.8 1924.33
  7025.4 1923.46  7076.7 1925.32  7167.6  1924.3  7269.6 1927.72  7530.5 1928.96
#Mann= 11 ,-1 , 0
  2619.5    .035       0  2715.8     .07       0    4262    .035       0
  4665.4     .07       0  4866.4     .16       0  4993.5     .07       0
  5006.6     .16       0  5058.8     .07       0  5394.9     .05       0
    6341    .035       0  6466.3     .07       0
#XS Ineff= 2 , 0
       0                  5255.6       0    1929
Permanent Ineff=
       F       F
Bank Sta=4993.5,5006.6
XS Rating Curve= 0 ,0
Exp/Cntr=0.3,0.1

Type RM Length L Ch R = 1 ,35128   ,1401,1401,1401
BEGIN DESCRIPTION:
Mapping XS b3ab3ae0
END DESCRIPTION:
XS GIS Cut Line= 4
      1481363.67      6845563.78      1483630.19       6846252.8
      1484696.55      6845809.33      1486310.54       6844653.5
#Sta/Elev= 30
  2903.9 1923.22  3008.8 1921.53  4096.8 1919.99  4180.4 1918.56  4682.1 1921.16
  4870.2 1920.16  4890.6 1918.13  4943.4 1919.61  4955.5  1918.3  4974.8 1914.14
  4993.5  1912.8    4994  1912.3  5006.6  1912.8  5016.6 1919.63  5143.2  1920.4
  5660.1 1921.04  6571.6  1920.7  7194.4 1922.39  7607.2 1921.34  7717.3 1922.81
  7739.8 1920.65  7760.2 1921.92  7817.2 1923.41  7897.1 1921.69    8069  1922.5
  8134.1 1924.76  8169.8 1923.82  8255.8 1925.25  8297.5 1927.18  8412.9 1927.17
#Mann= 9 ,-1 , 0
  2903.9    .035       0  3008.8     .07       0  4955.5     .16       0
  4993.5     .07       0  5006.6     .16       0  5143.2     .07       0
  5660.1     .05       0  7607.2    .035       0  7760.2     .07       0
Bank Sta=4993.5,5006.6
XS Rating Curve= 0 ,0
Exp/Cntr=0.3,0.1

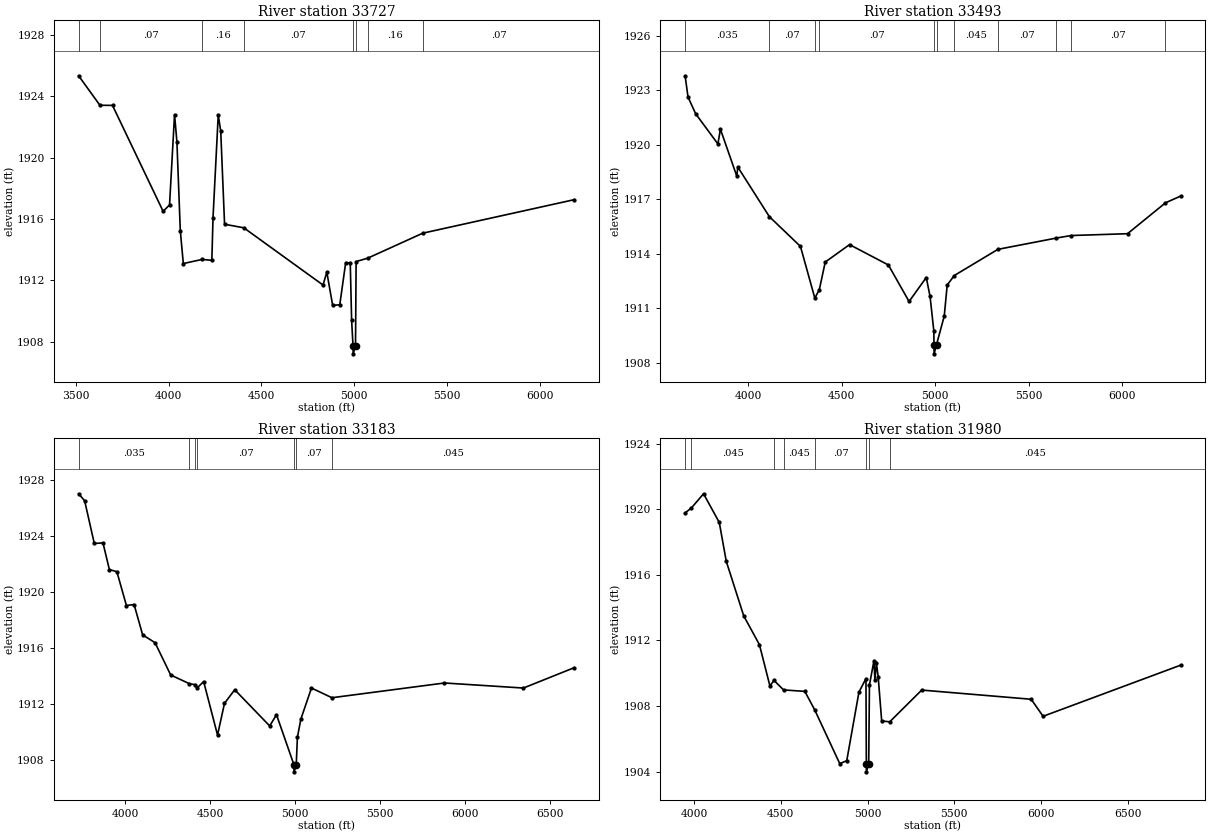
Type RM Length L Ch R = 1 ,33727   ,234,234,234
BEGIN DESCRIPTION:
Mapping XS 405905f2
END DESCRIPTION:
XS GIS Cut Line= 5
       1481146.7      6846614.13      1482353.27      6846943.99
      1482882.78       6847117.6      1483568.54      6847195.72
      1483703.47      6847300.63
#Sta/Elev= 30
  3515.3 1925.33  3629.9 1923.41  3697.8  1923.4  3970.5  1916.5    4005 1916.92
  4031.9  1922.8  4044.7 1921.02    4063 1915.23  4079.2  1913.1    4181 1913.37
  4232.8 1913.31  4239.2 1916.09  4267.3 1922.78  4280.7 1921.72  4301.4 1915.66
  4404.8 1915.43  4831.8  1911.7  4852.2 1912.54  4883.7 1910.37    4922 1910.42
  4953.8 1913.16  4978.4 1913.13  4985.7 1909.41  4993.4 1907.72  4993.9 1907.22
  5006.7 1907.72    5010 1913.23  5072.1 1913.45  5369.4 1915.08  6184.5 1917.26
#Mann= 8 ,-1 , 0
  3515.3    .035       0  3629.9     .07       0    4181     .16       0
  4404.8     .07       0  4993.4     .07       0  5006.7     .07       0
  5072.1     .16       0  5369.4     .07       0
Bank Sta=4993.4,5006.7
XS Rating Curve= 0 ,0
Exp/Cntr=0.3,0.1

Type RM Length L Ch R = 1 ,33493   ,310,310,310
BEGIN DESCRIPTION:
Mapping XS 79afadac
END DESCRIPTION:
XS GIS Cut Line= 4
      1481099.62      6846917.81      1483235.07       6847350.1
      1483521.53      6847355.31      1483709.07      6847344.89
#Sta/Elev= 30
  3660.8 1923.79  3676.5 1922.62  3717.3  1921.7  3836.4 1920.04  3849.9 1920.85
  3937.8 1918.26  3942.9 1918.77  4111.8 1916.04  4278.5  1914.4  4355.2 1911.56
  4379.2 1912.01  4411.1 1913.54  4541.2  1914.5  4749.1 1913.38    4860 1911.37
    4952 1912.69  4972.3 1911.65  4992.5 1909.75  4993.3 1908.99  4993.8 1908.49
  5006.8 1908.99  5048.3 1910.57  5064.1 1912.28  5102.2  1912.8  5335.6 1914.24
    5648 1914.86  5727.7    1915  6029.5  1915.1  6232.8  1916.8  6313.9 1917.17
#Mann= 11 ,-1 , 0
  3660.8    .035       0  4111.8     .07       0  4355.2     .16       0
  4379.2     .07       0  4993.3     .07       0  5006.8     .07       0
  5102.2    .045       0  5335.6     .07       0    5648    .045       0
  5727.7     .07       0  6232.8    .045       0
Bank Sta=4993.3,5006.8
XS Rating Curve= 0 ,0
Exp/Cntr=0.3,0.1

Type RM Length L Ch R = 1 ,33183   ,1203,1203,1203
BEGIN DESCRIPTION:
Mapping XS 63cae055
END DESCRIPTION:
XS GIS Cut Line= 3
      1481004.78      6847175.92      1483183.61      6847627.32
       1483873.7      6847622.98
#Sta/Elev= 30
  3726.6    1927    3762  1926.5  3818.7 1923.46  3869.8  1923.5  3907.5  1921.6
  3951.5 1921.45  4007.8 1919.04  4052.9 1919.11  4103.1 1916.95  4176.2 1916.39
  4268.1 1914.09  4378.4 1913.47    4411  1913.4    4423 1913.16  4462.1 1913.62
  4543.8 1909.81  4584.7 1912.07  4644.8 1913.04  4850.6 1910.46  4890.6 1911.26
  4993.3 1907.69  4993.8 1907.19  5006.8 1907.69  5013.6 1909.65    5034 1910.95
  5096.4 1913.16  5216.8 1912.47  5878.8 1913.52  6343.1 1913.16  6641.8 1914.61
#Mann= 7 ,-1 , 0
  3726.6    .035       0  4378.4     .07       0    4411    .035       0
    4423     .07       0  4993.3     .07       0  5006.8     .07       0
  5216.8    .045       0
Bank Sta=4993.3,5006.8
XS Rating Curve= 0 ,0
Exp/Cntr=0.3,0.1

Type RM Length L Ch R = 1 ,31980   ,1043,1043,1043
BEGIN DESCRIPTION:
Mapping XS fe512323
END DESCRIPTION:
XS GIS Cut Line= 3
      1481139.29      6848395.54      1482979.62       6848595.2
      1483956.17      6848365.17
#Sta/Elev= 30
  3949.2 1919.78  3985.9 1920.09  4055.5 1920.95  4146.1  1919.2  4186.3 1916.83
  4286.9  1913.5  4377.4 1911.74  4437.8 1909.22    4461 1909.56  4516.5 1908.98
  4638.9 1908.89  4695.9 1907.76  4840.1 1904.48  4880.3 1904.66  4950.7 1908.85
    4991 1909.67  4993.2 1904.48  4993.7 1903.98  5006.8 1904.48  5011.1 1909.28
  5037.2 1910.77  5042.3 1909.58  5051.3  1910.6  5061.4 1909.78  5081.5 1907.09
  5127.7 1907.03  5312.1 1908.97  5942.7 1908.41  6011.3 1907.37  6803.6 1910.49
#Mann= 8 ,-1 , 0
  3949.2     .07       0  3985.9    .045       0    4461     .07       0
  4516.5    .045       0  4695.9     .07       0  4993.2     .07       0
  5006.8     .07       0  5127.7    .045       0
Bank Sta=4993.2,5006.8
XS Rating Curve= 0 ,0
Exp/Cntr=0.3,0.1