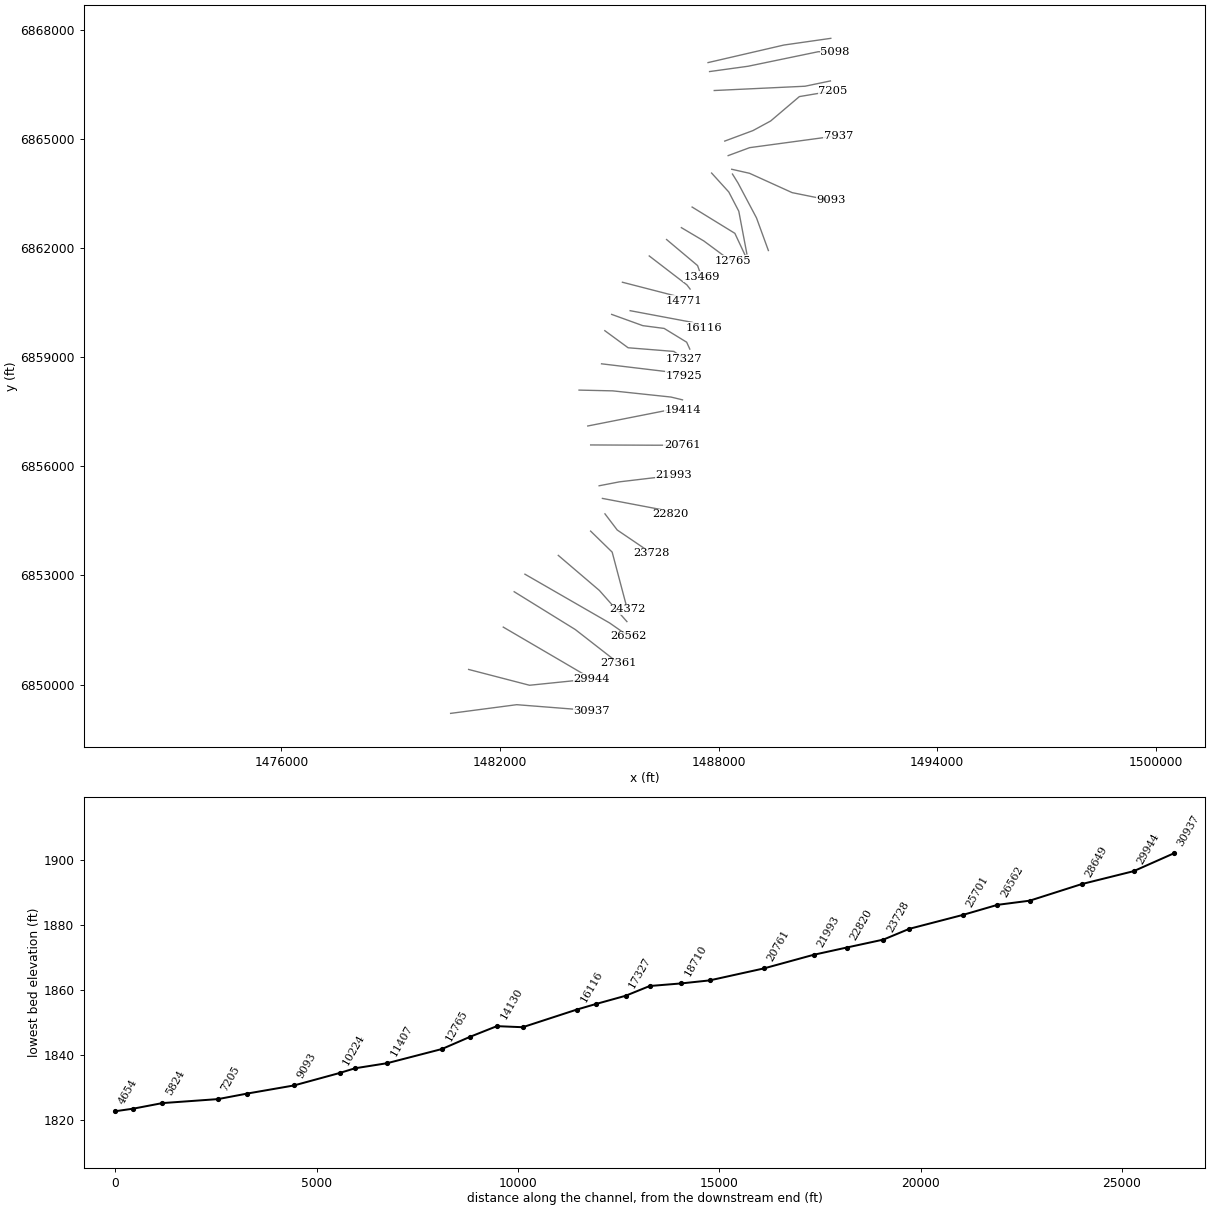
HEC-RAS study Little Bitter Creek.prj: Little Bitter Creek Base Level Engineering

--- Little Bitter Creek.g01 (geometry) --- (continued)

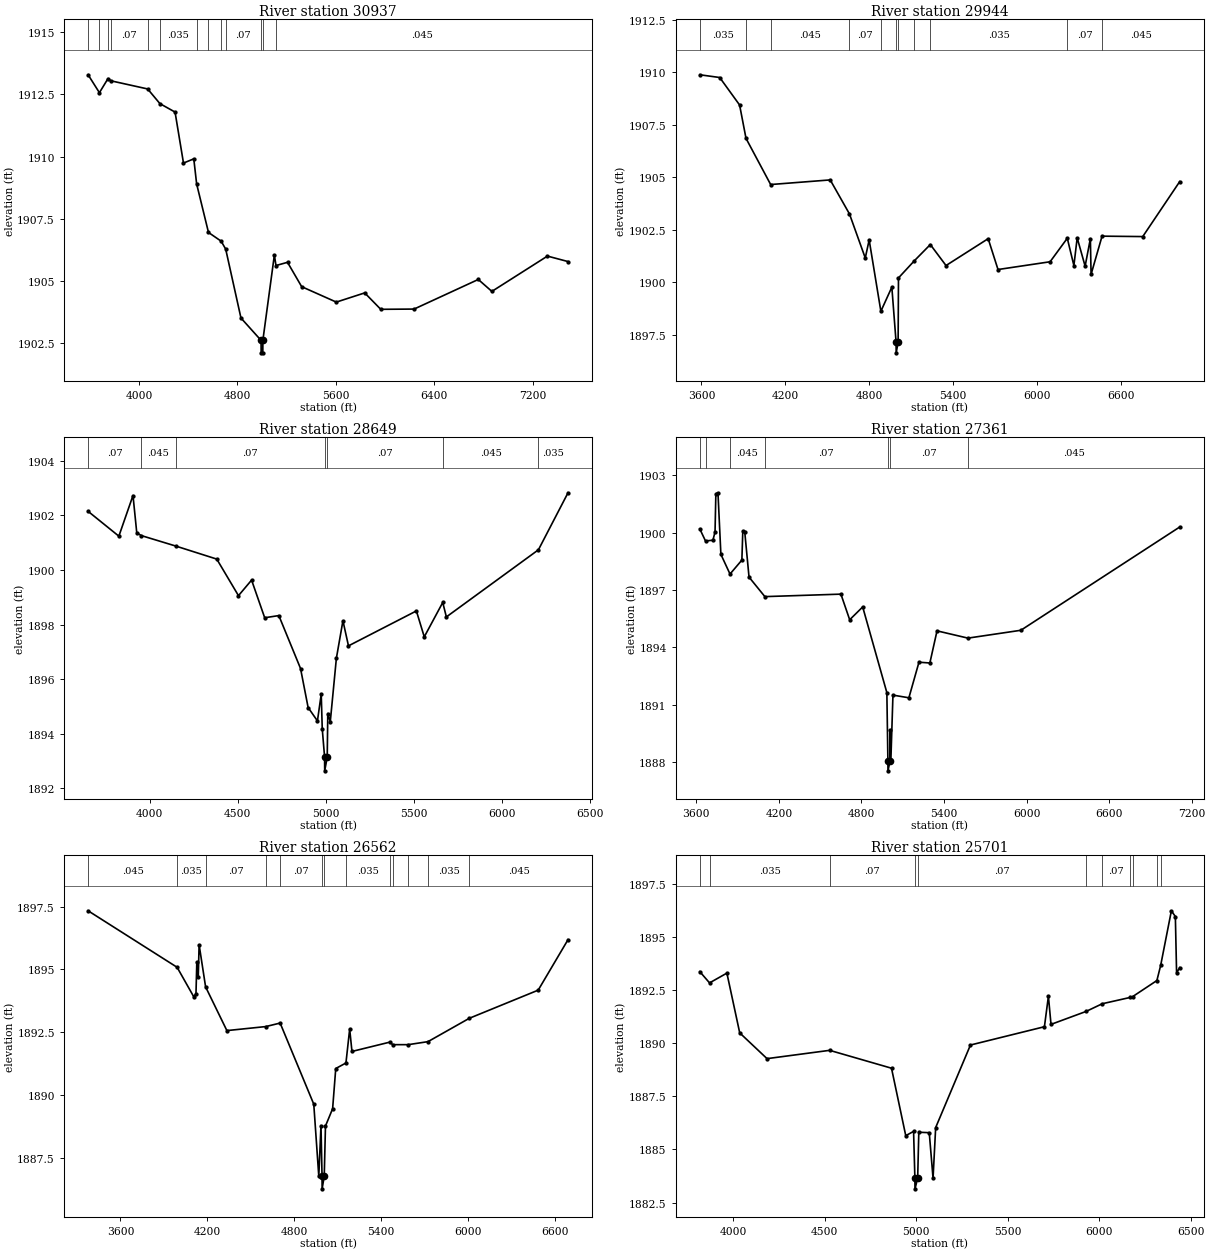
Type RM Length L Ch R = 1 ,30937   ,993,993,993
BEGIN DESCRIPTION:
Mapping XS 825bf045
END DESCRIPTION:
XS GIS Cut Line= 3
      1480644.51      6849211.51      1482458.79      6849450.23
      1484521.81      6849288.18
#Sta/Elev= 30
  3587.3 1913.29  3679.2 1912.57  3749.4 1913.14  3770.4 1913.05  4071.3 1912.72
  4170.8 1912.13  4293.8 1911.79  4362.3 1909.74    4446 1909.91  4469.2  1908.9
  4565.4 1906.95  4668.2  1906.6  4705.3 1906.28  4829.3 1903.51  4992.8 1902.61
  4993.3 1902.11  5006.7 1902.11  5007.2 1902.61  5100.7 1906.04  5113.8 1905.62
  5207.5 1905.75  5322.6 1904.77    5604 1904.15  5834.7 1904.52  5965.1 1903.86
  6235.9 1903.87  6757.5 1905.06  6867.9 1904.58  7319.3    1906  7486.6 1905.78
#Mann= 13 ,-1 , 0
  3587.3    .035       0  3679.2     .07       0  3749.4    .045       0
  3770.4     .07       0  4071.3    .045       0  4170.8    .035       0
  4469.2    .045       0  4565.4    .035       0  4668.2    .045       0
  4705.3     .07       0  4992.8     .07       0  5007.2     .07       0
  5113.8    .045       0
Bank Sta=4992.8,5007.2
XS Rating Curve= 0 ,0
Exp/Cntr=0.3,0.1

Type RM Length L Ch R = 1 ,29944   ,1295,1295,1295
BEGIN DESCRIPTION:
Mapping XS ce366d4f
END DESCRIPTION:
XS GIS Cut Line= 3
      1481139.35      6850418.11      1482810.35      6849984.09
      1484508.04      6850157.83
#Sta/Elev= 30
  3588.6 1909.89  3731.1 1909.76  3873.4 1908.45  3919.2 1906.86  4095.5 1904.66
  4521.5 1904.88  4659.2 1903.26  4772.3 1901.16  4800.2 1902.02  4883.9 1898.62
  4962.4 1899.77  4992.8 1897.14  4993.3 1896.64  5007.3 1897.14  5009.9 1900.21
  5123.8 1901.03  5237.7  1901.8  5349.9  1900.8  5651.4 1902.08  5721.8 1900.61
  6094.5 1900.98  6217.4  1902.1  6264.6  1900.8  6288.2 1902.12    6345 1900.77
  6382.5 1902.08  6387.6 1900.38  6466.1  1902.2  6757.2 1902.18  7021.6  1904.8
#Mann= 11 ,-1 , 0
  3588.6    .035       0  3919.2     .07       0  4095.5    .045       0
  4659.2     .07       0  4883.9    .035       0  4992.8    .035       0
  5007.3    .035       0  5123.8     .07       0  5237.7    .035       0
  6217.4     .07       0  6466.1    .045       0
Bank Sta=4992.8,5007.3
XS Rating Curve= 0 ,0
Exp/Cntr=0.3,0.1

Type RM Length L Ch R = 1 ,28649   ,1288,1288,1288
BEGIN DESCRIPTION:
Mapping XS 7c161b33
END DESCRIPTION:
XS GIS Cut Line= 3
      1482089.85      6851581.32      1483691.43      6850643.81
      1484437.94      6850205.45
#Sta/Elev= 30
  3651.5 1902.15  3825.9 1901.24  3906.1 1902.73  3927.5 1901.36  3953.9 1901.26
  4147.5 1900.88  4381.1  1900.4  4504.2 1899.06  4578.6 1899.63  4652.9 1898.25
  4733.1 1898.33  4856.2 1896.39  4899.2 1894.96    4952 1894.47  4973.5 1895.45
  4979.3 1894.18  4992.6 1893.14  4993.1 1892.64  5007.5 1893.14  5010.7 1894.74
  5024.8 1894.44  5059.5 1896.77  5096.6 1898.14    5128 1897.22  5513.1  1898.5
  5557.8 1897.55  5662.6 1898.81  5683.1 1898.28  6205.1 1900.74    6373 1902.83
#Mann= 7 ,-1 , 0
  3651.5     .07       0  3953.9    .045       0  4147.5     .07       0
  4992.6     .07       0  5007.5     .07       0  5662.6    .045       0
  6205.1    .035       0
Bank Sta=4992.6,5007.5
XS Rating Curve= 0 ,0
Exp/Cntr=0.3,0.1

Type RM Length L Ch R = 1 ,27361   ,799,799,799
BEGIN DESCRIPTION:
Mapping XS 4905ee3b
END DESCRIPTION:
XS GIS Cut Line= 3
      1482389.33      6852553.54      1484064.69      6851516.21
      1485261.27      6850584.09
#Sta/Elev= 30
  3625.6 1900.19  3667.1 1899.56    3721  1899.6  3736.4 1900.03  3742.3 1902.02
  3757.7 1902.08  3778.9 1898.86  3845.2 1897.83  3931.4 1898.56  3938.1 1900.07
  3952.6 1900.01  3983.4 1897.67  4098.5 1896.65    4651 1896.78  4714.8 1895.44
  4809.3 1896.11  4984.9 1891.63  4992.5 1888.04    4993 1887.54  5007.6 1888.04
  5007.9 1889.65  5013.8 1888.04  5029.2  1891.5    5145 1891.36  5218.2 1893.22
  5297.4 1893.18  5349.4 1894.86  5574.1 1894.48  5958.5 1894.89  7112.9 1900.29
#Mann= 7 ,-1 , 0
  3625.6    .045       0  3667.1    .035       0  3845.2    .045       0
  4098.5     .07       0  4992.5     .07       0  5007.6     .07       0
  5574.1    .045       0
Bank Sta=4992.5,5007.6
XS Rating Curve= 0 ,0
Exp/Cntr=0.3,0.1

Type RM Length L Ch R = 1 ,26562   ,861,861,861
BEGIN DESCRIPTION:
Mapping XS 4f67818f
END DESCRIPTION:
XS GIS Cut Line= 3
      1482684.51      6853035.29      1485010.87      6851694.16
      1485527.39       6851333.9
#Sta/Elev= 30
  3376.5 1897.33  3991.3 1895.08    4106 1893.91  4121.7 1894.03  4127.5  1895.3
  4137.5 1894.71  4143.3 1895.98  4188.1  1894.3  4335.1 1892.56  4603.8 1892.72
  4702.9 1892.86  4935.3 1889.63    4970 1886.76  4985.1 1888.78  4992.4 1886.76
  4992.9 1886.26  5007.6 1886.76  5016.1 1888.76  5065.5 1889.45  5087.1 1891.05
  5157.5 1891.27  5183.3 1892.62  5199.1 1891.73  5460.2  1892.1  5480.8    1892
  5587.6    1892  5724.2 1892.12  6009.8 1893.05  6485.4 1894.17  6691.5 1896.18
#Mann= 13 ,-1 , 0
  3376.5    .045       0  3991.3    .035       0  4188.1     .07       0
  4603.8    .035       0  4702.9     .07       0  4992.4     .07       0
  5007.6     .07       0  5157.5    .035       0  5460.2     .07       0
  5480.8    .035       0  5587.6     .07       0  5724.2    .035       0
  6009.8    .045       0
Bank Sta=4992.4,5007.6
XS Rating Curve= 0 ,0
Exp/Cntr=0.3,0.1

Type RM Length L Ch R = 1 ,25701   ,1329,1329,1329
BEGIN DESCRIPTION:
Mapping XS da9769cb
END DESCRIPTION:
XS GIS Cut Line= 3
      1483600.29      6853551.79      1484728.75      6852588.25
      1485483.99      6851733.19
#Sta/Elev= 30
    3816 1893.36  3869.4 1892.83  3964.2 1893.29  4034.4 1890.48  4183.8 1889.27
  4526.2 1889.66  4864.5 1888.82  4942.4 1885.65  4985.2 1885.85  4992.4 1883.65
  4992.9 1883.15  5007.6 1883.65  5013.8 1885.81  5070.9 1885.79  5091.7 1883.65
    5106 1886.03  5296.2 1889.91  5700.8 1890.77  5722.6  1892.2  5736.8 1890.88
    5929 1891.49    6017 1891.85  6171.5 1892.15  6184.1 1892.19  6315.8 1892.94
  6336.5 1893.65  6395.1 1896.22  6416.9 1895.95  6423.6  1893.3  6440.7 1893.55
#Mann= 11 ,-1 , 0
    3816    .045       0  3869.4    .035       0  4526.2     .07       0
  4992.4     .07       0  5007.6     .07       0    5929    .035       0
    6017     .07       0  6171.5    .035       0  6184.1     .07       0
  6315.8    .045       0  6336.5    .035       0
Bank Sta=4992.4,5007.6
XS Rating Curve= 0 ,0
Exp/Cntr=0.3,0.1

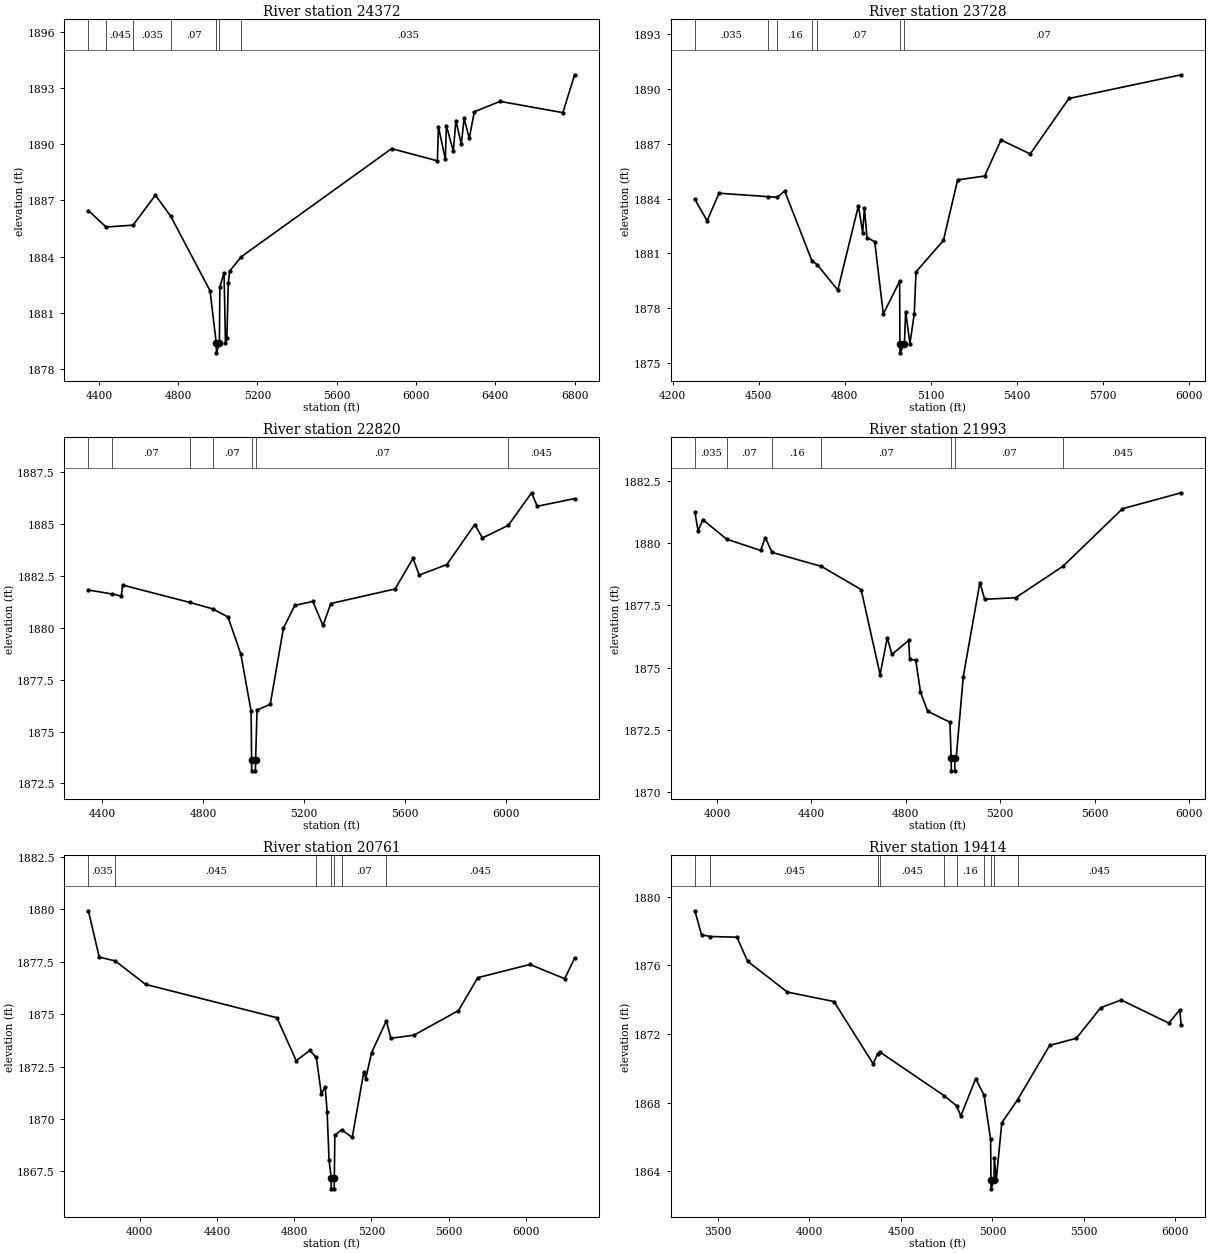
Type RM Length L Ch R = 1 ,24372   ,644,644,644
BEGIN DESCRIPTION:
Mapping XS facb2125
END DESCRIPTION:
XS GIS Cut Line= 3
      1484487.84      6854218.89      1485079.45      6853641.64
      1485496.11      6852068.75
#Sta/Elev= 30
  4346.9 1886.46    4436 1885.58  4572.3 1885.68  4684.9 1887.28  4762.5 1886.15
  4960.7 1882.18  4992.3 1879.37  4992.8 1878.87  5007.8 1879.37  5010.3 1882.38
  5031.4 1883.14  5038.6 1879.37  5045.6 1879.66  5052.7 1882.58  5059.7 1883.23
  5118.9    1884    5877 1889.76    6108 1889.11  6113.2 1890.92  6148.2  1889.2
  6153.4 1890.98  6188.4 1889.63  6201.4 1891.26  6228.6    1890  6242.8 1891.37
  6268.8 1890.31  6294.5 1891.73  6424.5 1892.28  6741.1 1891.68  6800.6  1893.7
#Mann= 7 ,-1 , 0
  4346.9     .07       0    4436    .045       0  4572.3    .035       0
  4762.5     .07       0  4992.3     .07       0  5007.8     .07       0
  5118.9    .035       0
Bank Sta=4992.3,5007.8
XS Rating Curve= 0 ,0
Exp/Cntr=0.3,0.1

Type RM Length L Ch R = 1 ,23728   ,908,908,908
BEGIN DESCRIPTION:
Mapping XS ee1bb0bc
END DESCRIPTION:
XS GIS Cut Line= 3
      1484881.34      6854693.05      1485218.34      6854249.28
      1486159.31      6853610.39
#Sta/Elev= 30
  4277.6 1883.96  4320.2 1882.79  4361.8  1884.3  4532.2 1884.11  4564.9 1884.08
  4590.6 1884.42  4685.3  1880.6  4704.1 1880.38  4775.7 1878.99  4847.5 1883.61
  4862.4 1882.14  4868.5 1883.49  4877.4 1881.87  4904.4 1881.64  4934.3 1877.68
  4991.2 1879.47  4992.2 1876.05  4992.7 1875.55  5007.8 1876.05  5012.2 1877.81
  5027.1 1876.05  5042.1 1877.68  5048.4 1879.99  5143.8 1881.71  5193.4 1885.03
  5287.6 1885.24  5344.5 1887.22  5446.2 1886.45  5581.1 1889.49  5972.2 1890.79
#Mann= 7 ,-1 , 0
  4277.6    .035       0  4532.2     .07       0  4564.9     .16       0
  4685.3    .035       0  4704.1     .07       0  4992.2     .07       0
  5007.8     .07       0
Bank Sta=4992.2,5007.8
XS Rating Curve= 0 ,0
Exp/Cntr=0.3,0.1

Type RM Length L Ch R = 1 ,22820   ,827,827,827
BEGIN DESCRIPTION:
Mapping XS bdd633e3
END DESCRIPTION:
XS GIS Cut Line= 3
      1484812.09      6855117.33      1486419.73      6854811.78
      1486676.71      6854679.82
#Sta/Elev= 30
    4346 1881.83  4439.1 1881.64  4476.3 1881.54  4481.4 1882.07    4748 1881.23
  4838.6 1880.92  4898.6 1880.53  4949.5 1878.74  4990.2 1875.99  4992.2 1873.61
  4992.7 1873.11  5007.4 1873.11  5007.9 1873.61  5013.8 1876.04    5066 1876.32
  5118.2 1879.99  5163.3 1881.09  5234.5 1881.28  5274.9 1880.12  5305.8 1881.18
  5560.3 1881.88  5631.5 1883.36  5655.8 1882.55  5765.3 1883.06  5875.8 1884.99
  5906.4 1884.34  6008.8 1884.95  6100.8 1886.52  6123.2 1885.87  6271.3 1886.24
#Mann= 7 ,-1 , 0
    4346    .035       0  4439.1     .07       0    4748     .16       0
  4838.6     .07       0  4992.2     .07       0  5007.9     .07       0
  6008.8    .045       0
Bank Sta=4992.2,5007.9
XS Rating Curve= 0 ,0
Exp/Cntr=0.3,0.1

Type RM Length L Ch R = 1 ,21993   ,1232,1232,1232
BEGIN DESCRIPTION:
Mapping XS 842188bc
END DESCRIPTION:
XS GIS Cut Line= 3
      1484721.84      6855464.56      1485277.36       6855572.2
       1486761.7      6855749.07
#Sta/Elev= 30
  3905.9 1881.25  3919.3 1880.48  3939.7 1880.93  4040.5 1880.15  4184.1  1879.7
  4204.5 1880.21  4232.9 1879.62  4441.8 1879.06  4610.4 1878.13  4690.9 1874.72
  4721.1 1876.19  4741.3 1875.53  4811.7 1876.09  4816.7 1875.33    4842  1875.3
  4862.1 1874.02  4892.3 1873.25  4986.8 1872.81  4992.2 1871.36  4992.7 1870.86
  5007.4 1870.86  5007.9 1871.36  5013.2 1871.36  5043.4 1874.64  5113.9 1878.41
    5134 1877.74    5265  1877.8  5465.5 1879.06  5718.2 1881.37  5966.6 1882.01
#Mann= 7 ,-1 , 0
  3905.9    .035       0  4040.5     .07       0  4232.9     .16       0
  4441.8     .07       0  4992.2     .07       0  5007.9     .07       0
  5465.5    .045       0
Bank Sta=4992.2,5007.9
XS Rating Curve= 0 ,0
Exp/Cntr=0.3,0.1

Type RM Length L Ch R = 1 ,20761   ,1347,1347,1347
BEGIN DESCRIPTION:
Mapping XS 163e8254
END DESCRIPTION:
XS GIS Cut Line= 3
      1484489.12      6856586.08      1486221.81      6856579.14
      1487006.51      6856579.14
#Sta/Elev= 30
    3735 1879.93  3790.9 1877.72  3873.6 1877.54  4030.9 1876.42  4710.9 1874.83
  4810.9 1872.78  4880.9 1873.27  4914.9 1872.94  4940.9  1871.2  4960.9 1871.53
  4970.9 1870.34  4980.9 1868.05    4992 1867.17  4992.5 1866.67  5007.6 1866.67
  5008.1 1867.17  5010.9 1869.22  5045.7 1869.49  5100.9 1869.12  5160.9 1872.25
  5170.9 1871.93  5200.9 1873.16  5277.5 1874.68  5300.9 1873.85  5420.9    1874
  5650.9 1875.17  5750.9 1876.74  6020.9 1877.37  6200.9 1876.69  6252.4 1877.67
#Mann= 7 ,-1 , 0
    3735    .035       0  3873.6    .045       0  4914.9     .16       0
    4992     .07       0  5008.1     .16       0  5045.7     .07       0
  5277.5    .045       0
Bank Sta=4992,5008.1
XS Rating Curve= 0 ,0
Exp/Cntr=0.3,0.1

Type RM Length L Ch R = 1 ,19414   ,704,704,704
BEGIN DESCRIPTION:
Mapping XS 63ad1713
END DESCRIPTION:
XS GIS Cut Line= 3
      1484409.31      6857106.92      1486711.39      6857561.78
      1487021.94      6857551.43
#Sta/Elev= 30
  3373.6 1879.19    3410 1877.79  3458.9 1877.69  3603.6 1877.65  3661.3 1876.25
  3878.9 1874.45  4133.7  1873.9  4347.8 1870.27  4371.9 1870.84  4383.1 1870.97
  4735.7 1868.41    4804 1867.82  4826.8 1867.23  4908.4  1869.4  4953.9 1868.44
  4989.9 1865.86  4991.9 1863.48  4992.4 1862.98  5008.1 1863.48  5010.3 1864.77
  5020.5 1863.48  5050.9 1866.83  5137.1 1868.17  5312.4 1871.34  5458.8 1871.76
  5591.3 1873.54  5703.5 1873.99  5963.9 1872.64    6024 1873.42  6030.9 1872.54
#Mann= 10 ,-1 , 0
  3373.6    .035       0  3458.9    .045       0  4371.9     .07       0
  4383.1    .045       0  4735.7     .07       0    4804     .16       0
  4953.9     .07       0  4991.9     .07       0  5008.1     .07       0
  5137.1    .045       0
Bank Sta=4991.9,5008.1
XS Rating Curve= 0 ,0
Exp/Cntr=0.3,0.1

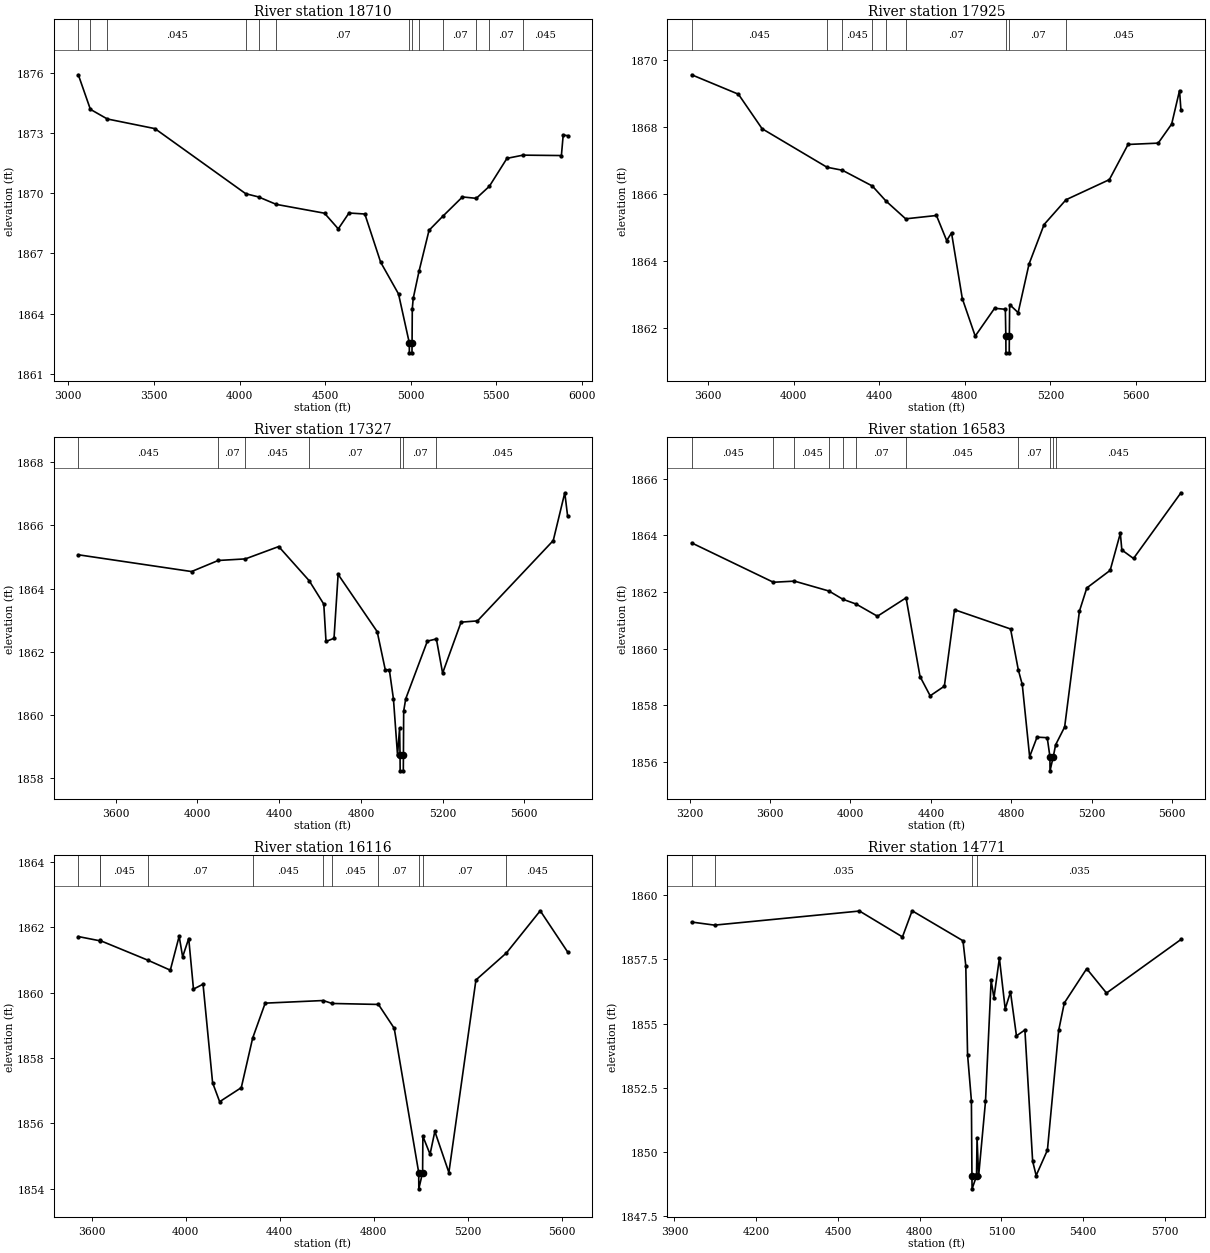
Type RM Length L Ch R = 1 ,18710   ,785,785,785
BEGIN DESCRIPTION:
Mapping XS 6aa6f7a7
END DESCRIPTION:
XS GIS Cut Line= 4
      1484169.68      6858093.03      1485093.34       6858072.2
      1486694.03      6857902.06      1487010.03      6857825.66
#Sta/Elev= 30
  3058.2 1875.89  3128.7 1874.17  3227.8 1873.69  3505.8 1873.21  4036.4 1869.97
  4111.2 1869.81  4214.5 1869.44  4496.6    1869  4577.1 1868.22  4639.6 1869.01
  4732.2 1868.96  4824.7 1866.56  4929.1 1864.98  4991.9 1862.55  4992.4 1862.05
  5007.7 1862.05  5008.2 1862.55  5009.5 1864.25  5014.9 1864.76  5048.8 1866.11
  5107.4 1868.15    5188 1868.85  5302.6 1869.81  5383.4 1869.74  5459.8 1870.34
  5562.6 1871.73  5656.5 1871.89  5880.7 1871.87  5891.2 1872.89  5916.9 1872.86
#Mann= 13 ,-1 , 0
  3058.2    .035       0  3128.7     .07       0  3227.8    .045       0
  4036.4     .07       0  4111.2    .045       0  4214.5     .07       0
  4991.9     .07       0  5008.2     .07       0  5048.8    .045       0
    5188     .07       0  5383.4    .045       0  5459.8     .07       0
  5656.5    .045       0
Bank Sta=4991.9,5008.2
XS Rating Curve= 0 ,0
Exp/Cntr=0.3,0.1

Type RM Length L Ch R = 1 ,17925   ,598,598,598
BEGIN DESCRIPTION:
Mapping XS 8c34e96d
END DESCRIPTION:
XS GIS Cut Line= 3
      1484787.81      6858815.25      1486961.39      6858554.83
       1487040.2      6858493.16
#Sta/Elev= 30
  3521.9 1869.55  3740.6 1868.97  3851.4 1867.94  4155.1 1866.79  4227.1  1866.7
  4367.1 1866.23  4431.2 1865.78  4523.2 1865.25  4667.2 1865.35  4715.1  1864.6
  4737.7 1864.83  4788.1 1862.87  4848.5 1861.75  4939.2 1862.58  4989.5 1862.55
  4991.8 1861.75  4992.3 1861.25  5007.7 1861.25  5008.2 1861.75  5009.7 1862.69
  5049.4 1862.45  5100.3  1863.9  5170.8 1865.08  5273.4 1865.82  5476.1 1866.42
  5563.6 1867.47  5704.6 1867.51  5767.7 1868.08  5804.5 1869.08  5811.1 1868.49
#Mann= 9 ,-1 , 0
  3521.9    .045       0  4155.1     .07       0  4227.1    .045       0
  4367.1     .07       0  4431.2    .045       0  4523.2     .07       0
  4991.8     .07       0  5008.2     .07       0  5273.4    .045       0
Bank Sta=4991.8,5008.2
XS Rating Curve= 0 ,0
Exp/Cntr=0.3,0.1

Type RM Length L Ch R = 1 ,17327   ,744,744,744
BEGIN DESCRIPTION:
Mapping XS 944693dc
END DESCRIPTION:
XS GIS Cut Line= 4
      1484878.04      6859724.98      1485516.95      6859256.22
      1486773.89      6859155.53      1487050.86      6858954.72
#Sta/Elev= 30
  3416.6 1865.07    3971 1864.54  4101.6 1864.89  4234.6 1864.94  4397.7 1865.33
    4547 1864.25  4618.4 1863.51  4629.3 1862.33  4668.5 1862.43  4688.6 1864.45
  4879.9 1862.64  4919.3 1861.44  4939.4 1861.43  4959.5 1860.51  4979.5 1858.74
  4989.6  1859.6  4991.8 1858.74  4992.3 1858.24  5007.8 1858.24  5008.3 1858.74
  5009.6 1860.13  5019.7 1860.52  5125.5 1862.34  5169.6 1862.41  5200.2 1861.33
  5290.5 1862.94  5370.8 1862.98  5741.9 1865.52  5798.3 1867.03  5812.1  1866.3
#Mann= 7 ,-1 , 0
  3416.6    .045       0  4101.6     .07       0  4234.6    .045       0
    4547     .07       0  4991.8     .07       0  5008.3     .07       0
  5169.6    .045       0
Bank Sta=4991.8,5008.3
XS Rating Curve= 0 ,0
Exp/Cntr=0.3,0.1

Type RM Length L Ch R = 1 ,16583   ,467,467,467
BEGIN DESCRIPTION:
Mapping XS a1660e8f
END DESCRIPTION:
XS GIS Cut Line= 5
      1485065.58      6860172.88      1485919.73      6859863.86
      1486506.53      6859787.47      1487124.59        6859409.
      1487210.69      6859219.57
#Sta/Elev= 30
  3210.3 1863.73  3616.6 1862.34  3721.4 1862.38    3893 1862.03  3961.9 1861.74
    4028 1861.57    4134 1861.14  4276.4 1861.79  4345.8 1859.01  4396.2 1858.33
  4466.8 1858.67  4517.5 1861.37    4796 1860.69  4834.6 1859.24  4854.1 1858.73
  4890.8 1856.18  4927.6 1856.87  4978.3 1856.85  4991.7 1856.18  4992.2 1855.68
  5008.3 1856.18  5020.1  1856.6  5064.9 1857.23  5138.4 1861.32  5175.1 1862.14
  5291.2 1862.76  5341.8 1864.07  5349.3 1863.48  5407.3 1863.18  5643.2  1865.5
#Mann= 11 ,-1 , 0
  3210.3    .045       0  3616.6     .07       0  3721.4    .045       0
    3893     .07       0  3961.9    .045       0    4028     .07       0
  4276.4    .045       0  4834.6     .07       0  4991.7     .07       0
  5008.3     .07       0  5020.1    .045       0
Bank Sta=4991.7,5008.3
XS Rating Curve= 0 ,0
Exp/Cntr=0.3,0.1

Type RM Length L Ch R = 1 ,16116   ,1345,1345,1345
BEGIN DESCRIPTION:
Mapping XS 13f35810
END DESCRIPTION:
XS GIS Cut Line= 3
      1485572.98      6860274.88      1487274.33      6859955.44
      1487590.14      6859799.27
#Sta/Elev= 30
  3542.3 1861.72  3634.2 1861.59  3634.6  1861.6  3837.2    1861    3934 1860.69
  3971.7 1861.73  3986.5  1861.1  4012.4 1861.66  4032.7 1860.11  4073.4 1860.26
  4114.1 1857.24  4144.1 1856.66  4236.2 1857.09  4284.7 1858.61    4338 1859.68
    4585 1859.76  4622.7 1859.67  4820.3 1859.64  4887.4 1858.91  4991.7 1854.49
  4992.2 1853.99  5008.3 1854.49  5009.5  1855.6    5040 1855.05  5060.4 1855.75
  5120.2 1854.49  5235.4 1860.39  5365.5 1861.22  5509.2 1862.51  5625.7 1861.25
#Mann= 11 ,-1 , 0
  3542.3    .045       0  3634.2     .07       0  3634.6    .045       0
  3837.2     .07       0  4284.7    .045       0    4585     .07       0
  4622.7    .045       0  4820.3     .07       0  4991.7     .07       0
  5008.3     .07       0  5365.5    .045       0
Bank Sta=4991.7,5008.3
XS Rating Curve= 0 ,0
Exp/Cntr=0.3,0.1

Type RM Length L Ch R = 1 ,14771   ,641,641,641
BEGIN DESCRIPTION:
Mapping XS f44c217c
END DESCRIPTION:
XS GIS Cut Line= 3
      1485361.09      6861056.15      1487003.49      6860632.53
      1487062.43      6860552.79
#Sta/Elev= 30
  3963.2 1858.96  4047.2 1858.84    4579 1859.39  4736.6 1858.38  4772.1  1859.4
  4958.7 1858.23    4969 1857.26  4975.5 1853.79  4989.6 1851.99  4991.6 1849.05
  4992.1 1848.55  5008.4 1849.05  5010.3 1850.53  5016.1 1849.05  5041.3 1851.96
    5062 1856.69  5072.3    1856  5092.3 1857.55  5113.6 1855.57    5133 1856.23
  5154.9 1854.52  5185.9 1854.75  5214.3 1849.63  5227.2 1849.07  5268.5 1850.06
  5309.8 1854.73  5330.4  1855.8  5412.6 1857.14  5485.3 1856.19  5758.5 1858.28
#Mann= 4 ,-1 , 0
  3963.2    .045       0  4047.2    .035       0  4991.6    .035       0
  5008.4    .035       0
Bank Sta=4991.6,5008.4
XS Rating Curve= 0 ,0
Exp/Cntr=0.3,0.1

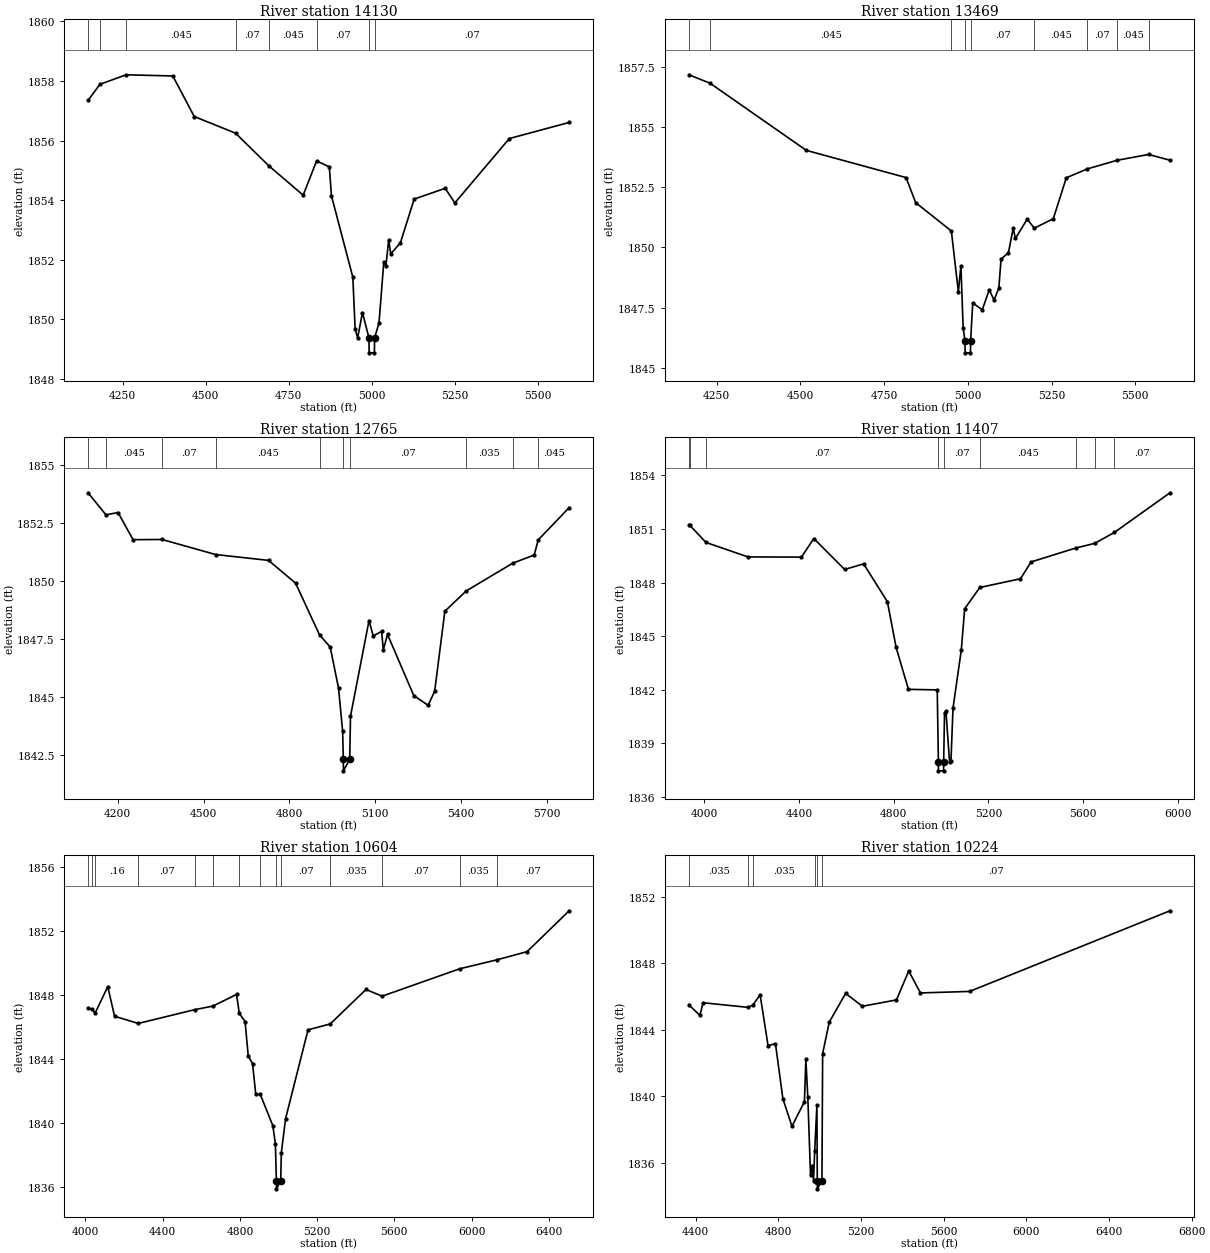
Type RM Length L Ch R = 1 ,14130   ,661,661,661
BEGIN DESCRIPTION:
Mapping XS e0ce9cce
END DESCRIPTION:
XS GIS Cut Line= 3
      1486097.25      6861778.35      1487131.97      6860983.22
      1487218.78      6860868.63
#Sta/Elev= 30
  4145.7 1857.35  4181.5 1857.89  4260.3 1858.21    4401 1858.17  4465.4 1856.81
  4589.9 1856.25  4689.7 1855.16  4793.4 1854.17    4834 1855.32  4872.3 1855.12
  4878.6 1854.15    4943 1851.42    4950 1849.68  4957.5 1849.38    4972 1850.23
  4991.6 1849.38  4992.1 1848.88    5008 1848.88  5008.5 1849.38  5021.8 1849.88
  5036.3 1851.93  5042.6 1851.79  5050.9 1852.66  5057.2  1852.2  5086.2 1852.57
  5127.8 1854.04  5221.2  1854.4  5250.2 1853.91  5414.2 1856.07  5594.4 1856.61
#Mann= 8 ,-1 , 0
  4145.7    .045       0  4181.5     .07       0  4260.3    .045       0
  4589.9     .07       0  4689.7    .045       0    4834     .07       0
  4991.6     .07       0  5008.5     .07       0
Bank Sta=4991.6,5008.5
XS Rating Curve= 0 ,0
Exp/Cntr=0.3,0.1

Type RM Length L Ch R = 1 ,13469   ,704,704,704
BEGIN DESCRIPTION:
Mapping XS d5d978e6
END DESCRIPTION:
XS GIS Cut Line= 3
      1486572.94      6862229.74      1487423.63      6861514.47
      1487534.75      6861208.88
#Sta/Elev= 30
  4167.2 1857.17  4230.4 1856.82  4517.8 1854.03  4815.7  1852.9  4844.3 1851.86
    4951 1850.68  4971.8 1848.16  4979.5 1849.24  4986.1 1846.67  4991.5 1846.12
    4992 1845.62    5008 1845.62  5008.5 1846.12  5014.7 1847.69  5043.3 1847.41
  5064.1 1848.24  5078.4 1847.81  5092.7 1848.31  5099.3 1849.51  5121.3 1849.78
  5135.6 1850.79  5142.2 1850.37  5177.3 1851.17  5198.7  1850.8  5255.3 1851.19
  5294.1 1852.89  5356.8 1853.26  5446.5 1853.62  5539.7 1853.86  5603.8 1853.62
#Mann= 9 ,-1 , 0
  4167.2     .07       0  4230.4    .045       0    4951     .07       0
  4991.5     .07       0  5008.5     .07       0  5198.7    .045       0
  5356.8     .07       0  5446.5    .045       0  5539.7     .07       0
Bank Sta=4991.5,5008.5
XS Rating Curve= 0 ,0
Exp/Cntr=0.3,0.1

Type RM Length L Ch R = 1 ,12765   ,1358,1358,1358
BEGIN DESCRIPTION:
Mapping XS 8095cafa
END DESCRIPTION:
XS GIS Cut Line= 4
      1486979.21      6862556.12      1487593.77      6862191.55
      1488166.69      6861767.94      1488391.23      6861647.03
#Sta/Elev= 30
  4096.3  1853.8    4159 1852.85  4201.1 1852.95  4253.8 1851.78  4354.7 1851.79
  4542.8 1851.14  4727.3 1850.89  4821.9 1849.91  4905.7 1847.68    4943 1847.16
  4972.2 1845.38  4986.5 1843.53  4988.8 1842.33  4989.3 1841.83  5011.2 1842.33
  5013.9 1844.18  5078.7  1848.3  5093.3 1847.64  5122.5 1847.83  5128.8 1847.05
  5143.4  1847.7  5235.2 1845.07  5285.3 1844.65  5308.3 1845.26  5343.8  1848.7
    5418 1849.57  5581.2 1850.77  5656.2 1851.12  5670.1 1851.77  5778.4 1853.16
#Mann= 10 ,-1 , 0
  4096.3     .07       0    4159    .045       0  4354.7     .07       0
  4542.8    .045       0  4905.7     .07       0  4988.8     .07       0
  5011.2     .07       0    5418    .035       0  5581.2     .07       0
  5670.1    .045       0
Bank Sta=4988.8,5011.2
XS Rating Curve= 0 ,0
Exp/Cntr=0.3,0.1

Type RM Length L Ch R = 1 ,11407   ,803,803,803
BEGIN DESCRIPTION:
Mapping XS 45f07670
END DESCRIPTION:
XS GIS Cut Line= 3
      1487274.33       6863122.1      1488447.94      6862399.89
       1488725.7      6861806.17
#Sta/Elev= 30
  3934.3 1851.22  3937.5 1851.22  4006.6 1850.25  4184.1 1849.44  4410.1 1849.43
  4462.2 1850.47  4592.6 1848.74  4672.8 1849.05  4773.4 1846.93  4810.1 1844.38
  4862.2 1842.03    4984    1842  4988.8 1837.97  4989.3 1837.47  5010.7 1837.47
  5011.2 1837.97  5014.8 1840.72  5020.7  1840.8  5036.1 1837.97    5042 1838.03
  5050.6 1840.97  5085.8 1844.24  5099.9 1846.54    5164 1847.73  5335.9 1848.22
  5380.6 1849.16  5569.7 1849.94  5649.7  1850.2  5732.6 1850.81  5967.8 1853.03
#Mann= 9 ,-1 , 0
  3934.3     .07       0  3937.5    .045       0  4006.6     .07       0
  4988.8     .07       0  5011.2     .07       0    5164    .045       0
  5569.7     .07       0  5649.7    .045       0  5732.6     .07       0
Bank Sta=4988.8,5011.2
XS Rating Curve= 0 ,0
Exp/Cntr=0.3,0.1

Type RM Length L Ch R = 1 ,10604   ,380,380,380
BEGIN DESCRIPTION:
Mapping XS e5a53fb3
END DESCRIPTION:
XS GIS Cut Line= 4
      1487809.03      6864056.15      1488281.27       6863535.3
      1488555.58      6863007.53      1488777.79      6861833.94
#Sta/Elev= 30
  4013.2 1847.15  4031.8  1847.1  4050.1 1846.86  4115.4 1848.51  4150.5 1846.66
  4273.3 1846.21  4565.6 1847.07  4659.8 1847.29  4782.5 1848.02  4796.7 1846.84
  4826.7 1846.33  4843.2 1844.17  4865.3 1843.71  4881.8 1841.81  4905.5 1841.78
  4970.3 1839.84  4983.7 1838.71  4988.8 1836.39  4989.3 1835.89  5011.3 1836.39
  5014.5 1838.14  5036.6 1840.27  5152.8 1845.81  5267.9 1846.18  5453.1 1848.33
  5536.3 1847.91  5938.2 1849.62  6131.2 1850.18  6287.6 1850.69  6505.5 1853.24
#Mann= 14 ,-1 , 0
  4013.2     .07       0  4031.8    .045       0  4050.1     .16       0
  4273.3     .07       0  4565.6    .045       0  4659.8     .07       0
  4796.7    .035       0  4905.5     .07       0  4988.8     .07       0
  5011.3     .07       0  5267.9    .035       0  5536.3     .07       0
  5938.2    .035       0  6131.2     .07       0
Bank Sta=4988.8,5011.3
XS Rating Curve= 0 ,0
Exp/Cntr=0.3,0.1

Type RM Length L Ch R = 1 ,10224   ,1131,1131,1131
BEGIN DESCRIPTION:
Mapping XS 1d92b62b
END DESCRIPTION:
XS GIS Cut Line= 4
      1488381.98      6864028.34      1488534.74      6863781.83
      1489041.69       6862823.5      1489368.08      6861927.67
#Sta/Elev= 30
  4367.6  1845.5  4420.9 1844.87  4436.2 1845.63  4655.8 1845.35  4677.9 1845.51
  4712.2 1846.11  4750.6 1843.05  4786.4 1843.17  4822.3 1839.86  4866.3  1838.2
  4926.6 1839.68  4933.5 1842.23    4943 1839.95  4956.1 1835.26    4965 1835.83
  4970.7 1834.94  4976.3 1836.74    4987 1839.48  4988.8 1834.94  4989.3 1834.44
  5011.3 1834.94  5014.7 1842.57  5046.6 1844.46  5125.8 1846.19  5207.1 1845.42
  5371.8  1845.8  5431.2 1847.54  5487.8 1846.22  5725.4 1846.31  6695.2 1851.16
#Mann= 6 ,-1 , 0
  4367.6    .035       0  4655.8     .07       0  4677.9    .035       0
  4976.3     .07       0  4988.8     .07       0  5011.3     .07       0
Bank Sta=4988.8,5011.3
XS Rating Curve= 0 ,0
Exp/Cntr=0.3,0.1

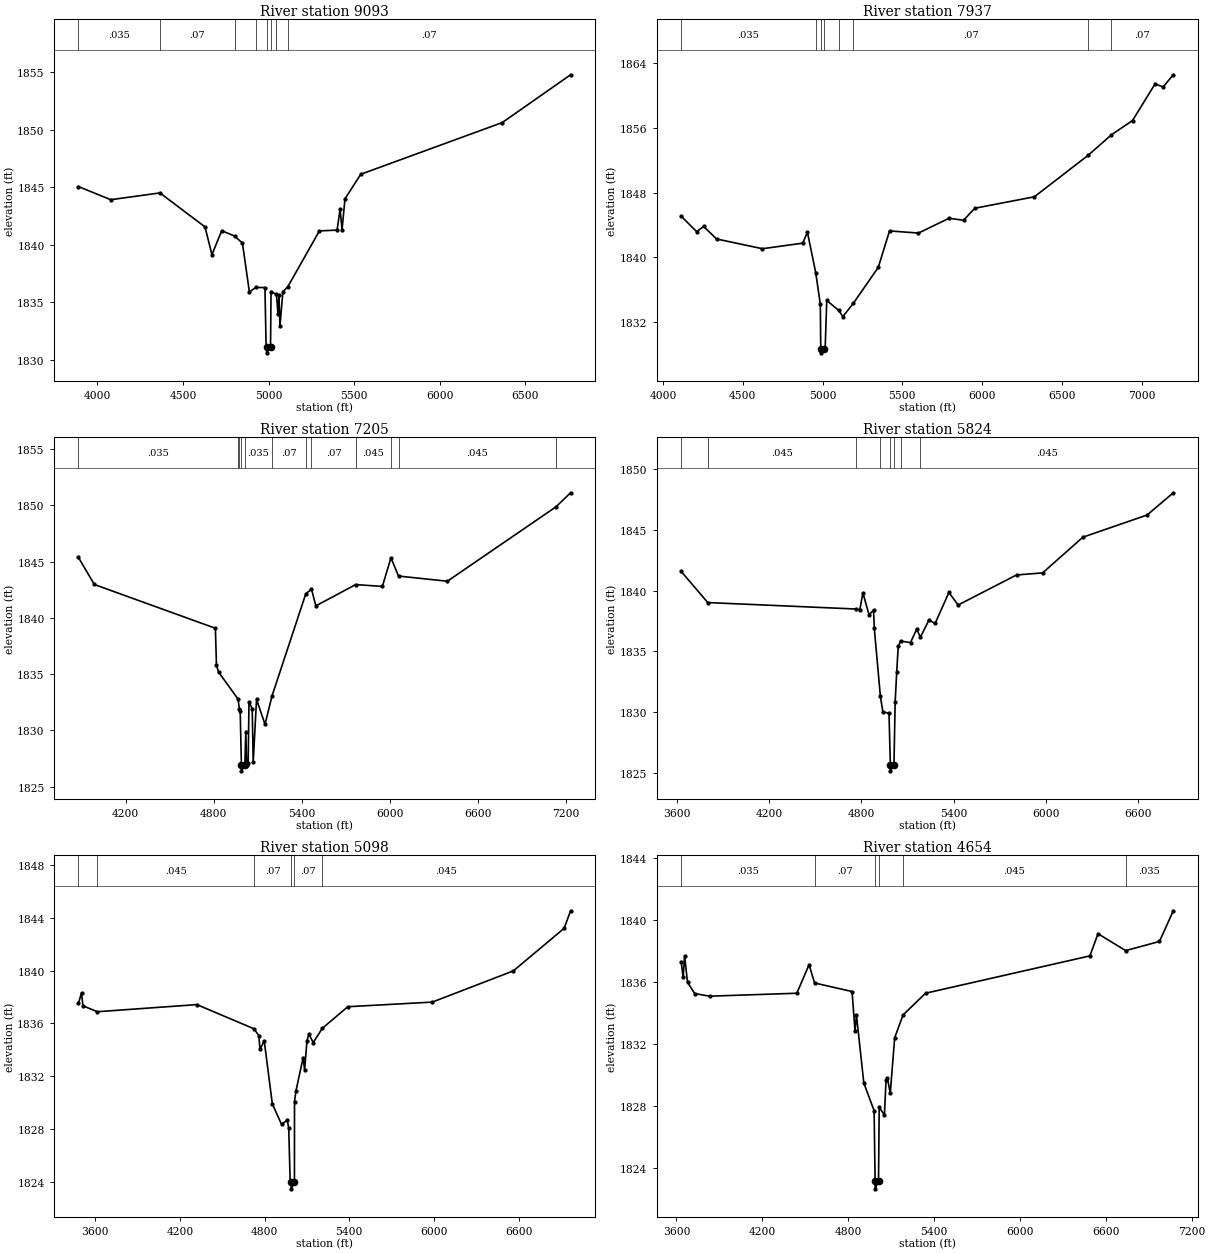
Type RM Length L Ch R = 1 ,9093    ,1156,1156,1156
BEGIN DESCRIPTION:
Mapping XS f658e8e9
END DESCRIPTION:
XS GIS Cut Line= 4
      1488361.16       6864160.3      1488850.72      6864049.19
      1490020.85      6863517.94      1491085.96      6863302.84
#Sta/Elev= 30
  3890.1 1845.05  4078.6 1843.91  4365.9  1844.5  4628.9 1841.55  4669.5 1839.14
  4726.7 1841.22  4802.1 1840.75  4847.5 1840.14  4888.2  1835.9  4925.9 1836.29
  4978.9 1836.28    4986 1831.11  4988.4 1831.11  4988.9 1830.61  5011.7 1831.11
  5014.6 1835.93  5046.2 1835.68  5055.2 1833.98  5060.7 1835.63  5066.7 1832.93
  5083.8 1835.92  5112.5 1836.35    5297  1841.2  5400.3 1841.27  5417.9 1843.08
  5429.2  1841.3  5446.4 1843.99  5538.7 1846.12  6364.9 1850.61  6763.8 1854.76
#Mann= 8 ,-1 , 0
  3890.1    .035       0  4365.9     .07       0  4802.1     .16       0
  4925.9     .07       0  4988.4     .07       0  5011.7     .07       0
  5046.2     .16       0  5112.5     .07       0
Bank Sta=4988.4,5011.7
XS Rating Curve= 0 ,0
Exp/Cntr=0.3,0.1

Type RM Length L Ch R = 1 ,7937    ,732,732,732
BEGIN DESCRIPTION:
Mapping XS 8729c66c
END DESCRIPTION:
XS GIS Cut Line= 3
      1488263.91       6864535.3      1488854.19      6864754.05
      1491288.23      6865083.92
#Sta/Elev= 30
  4113.1 1845.06  4210.2 1843.15  4254.3 1843.79  4334.8 1842.24  4622.6 1841.03
  4874.6 1841.72  4904.9 1843.06  4956.7 1838.07  4985.6 1834.16  4988.4 1828.62
  4988.9 1828.12  5011.7 1828.62  5015.9 1828.62    5026 1834.62  5101.2 1833.38
  5126.9 1832.61  5193.2 1834.28  5348.9 1838.71  5419.5 1843.24  5601.2 1842.97
  5792.9 1844.81  5883.8 1844.56  5954.4 1846.05  6327.8 1847.47  6664.6 1852.61
  6811.3 1855.16  6943.4 1856.93  7084.6 1861.47  7135.1 1861.09  7198.9  1862.6
#Mann= 8 ,-1 , 0
  4113.1    .035       0  4956.7     .07       0  4988.4     .07       0
  5011.7     .07       0  5101.2    .035       0  5193.2     .07       0
  6664.6    .045       0  6811.3     .07       0
Bank Sta=4988.4,5011.7
XS Rating Curve= 0 ,0
Exp/Cntr=0.3,0.1

Type RM Length L Ch R = 1 ,7205    ,1381,1381,1381
BEGIN DESCRIPTION:
Mapping XS bb02d1ba
END DESCRIPTION:
XS GIS Cut Line= 5
       1488170.2      6864934.62      1488944.47       6865222.8
      1489430.58      6865486.69      1490218.77      6866156.83
      1491145.66      6866313.05
#Sta/Elev= 30
  3877.8 1845.36    3986 1842.96  4810.9 1839.07  4818.3 1835.79  4832.8 1835.17
  4965.8 1832.77  4974.6 1831.87  4980.1 1831.68  4988.3  1826.9  4988.8  1826.4
  5011.8  1826.9  5018.1 1829.89  5023.8 1826.92  5034.3 1827.14    5040 1832.54
  5061.8 1831.92  5068.7 1827.18  5091.4 1832.74  5149.3 1830.53  5196.5 1833.04
    5427 1842.13  5465.9 1842.55  5495.5 1841.06  5766.8 1842.95    5949 1842.79
  6007.4 1845.33  6058.9 1843.71  6391.6 1843.25  7130.9 1849.85  7231.6 1851.11
#Mann= 12 ,-1 , 0
  3877.8    .035       0  4965.8     .07       0  4974.6    .035       0
  4988.3    .035       0  5011.8    .035       0  5196.5     .07       0
    5427    .045       0  5465.9     .07       0  5766.8    .045       0
  6007.4     .07       0  6058.9    .045       0  7130.9     .07       0
Bank Sta=4988.3,5011.8
XS Rating Curve= 0 ,0
Exp/Cntr=0.3,0.1

Type RM Length L Ch R = 1 ,5824    ,726,726,726
BEGIN DESCRIPTION:
Mapping XS 74c001ba
END DESCRIPTION:
XS GIS Cut Line= 3
      1487881.98       6866323.5      1490375.02      6866441.55
      1491071.44      6866587.07
#Sta/Elev= 30
    3625 1841.57  3798.4 1839.01  4763.7 1838.48  4789.3 1838.41  4809.3 1839.81
  4849.4    1838  4878.7 1838.39  4883.7 1836.88  4923.2 1831.31  4939.5 1830.02
  4979.5  1829.9  4988.2 1825.67  4988.7 1825.17  5011.8 1825.67  5019.6 1830.81
  5029.6 1833.28  5039.6 1835.41  5055.4 1835.84  5119.7 1835.72  5159.7 1836.82
  5184.4 1836.17  5239.8 1837.57  5279.9 1837.29    5370 1839.84    5430 1838.81
  5810.5 1841.28  5980.7 1841.45  6243.4 1844.39  6661.4 1846.21  6832.3 1848.04
#Mann= 8 ,-1 , 0
    3625    .035       0  3798.4    .045       0  4763.7     .07       0
  4923.2    .045       0  4988.2    .045       0  5011.8    .045       0
  5055.4     .07       0  5184.4    .045       0
Bank Sta=4988.2,5011.8
XS Rating Curve= 0 ,0
Exp/Cntr=0.3,0.1

Type RM Length L Ch R = 1 ,5098    ,444,444,444
BEGIN DESCRIPTION:
Mapping XS 33013bc2
END DESCRIPTION:
XS GIS Cut Line= 4
      1487753.51      6866844.33      1488809.05      6866990.16
      1490736.13      6867389.47       1491190.5      6867382.53
#Sta/Elev= 30
    3481 1837.53  3502.7 1838.32  3512.8 1837.34  3614.3 1836.89  4320.4 1837.43
  4723.9  1835.6  4759.8 1835.08  4767.1 1834.03  4797.7 1834.68  4855.1 1829.89
  4920.3 1828.35  4961.1 1828.66  4971.3 1828.06  4981.6 1823.95  4988.2 1823.95
  4988.7 1823.45  5011.8 1823.95  5012.2 1830.06  5022.4 1830.87  5073.5 1833.41
  5083.7 1832.48  5100.8  1834.7  5114.3 1835.19    5145 1834.55  5209.4 1835.63
  5390.1 1837.27  5988.7 1837.62  6563.5 1839.99  6923.5 1843.22    6969 1844.55
#Mann= 6 ,-1 , 0
    3481    .035       0  3614.3    .045       0  4723.9     .07       0
  4988.2    .035       0  5011.8     .07       0  5209.4    .045       0
Bank Sta=4988.2,5011.8
XS Rating Curve= 0 ,0
Exp/Cntr=0.3,0.1

Type RM Length L Ch R = 1 ,4654    ,871,871,871
BEGIN DESCRIPTION:
Mapping XS 0dcb3f24
END DESCRIPTION:
XS GIS Cut Line= 3
      1487711.87      6867090.87      1489795.16       6867573.5
      1491081.63      6867757.28
#Sta/Elev= 30
  3633.3 1837.32  3647.3  1836.3    3657 1837.69  3677.6 1835.99  3727.6 1835.26
  3831.5 1835.09  4441.3 1835.28  4526.7 1837.12  4565.6 1835.94  4827.2 1835.39
  4847.8 1832.84    4858 1833.86  4909.4 1829.48  4981.2  1827.7  4988.1 1823.16
  4988.6 1822.66    5012 1823.16  5016.7 1827.91  5053.1 1827.43  5064.5 1829.65
  5073.6 1829.82  5094.1 1828.84  5124.9 1832.41  5183.5 1833.88  5340.5 1835.28
  6488.8 1837.69  6545.2 1839.12  6738.4 1838.03  6974.5 1838.62  7071.3  1840.6
#Mann= 6 ,-1 , 0
  3633.3    .035       0  4565.6     .07       0  4988.1     .07       0
    5012     .07       0  5183.5    .045       0  6738.4    .035       0
Bank Sta=4988.1,5012
XS Rating Curve= 0 ,0
Exp/Cntr=0.3,0.1