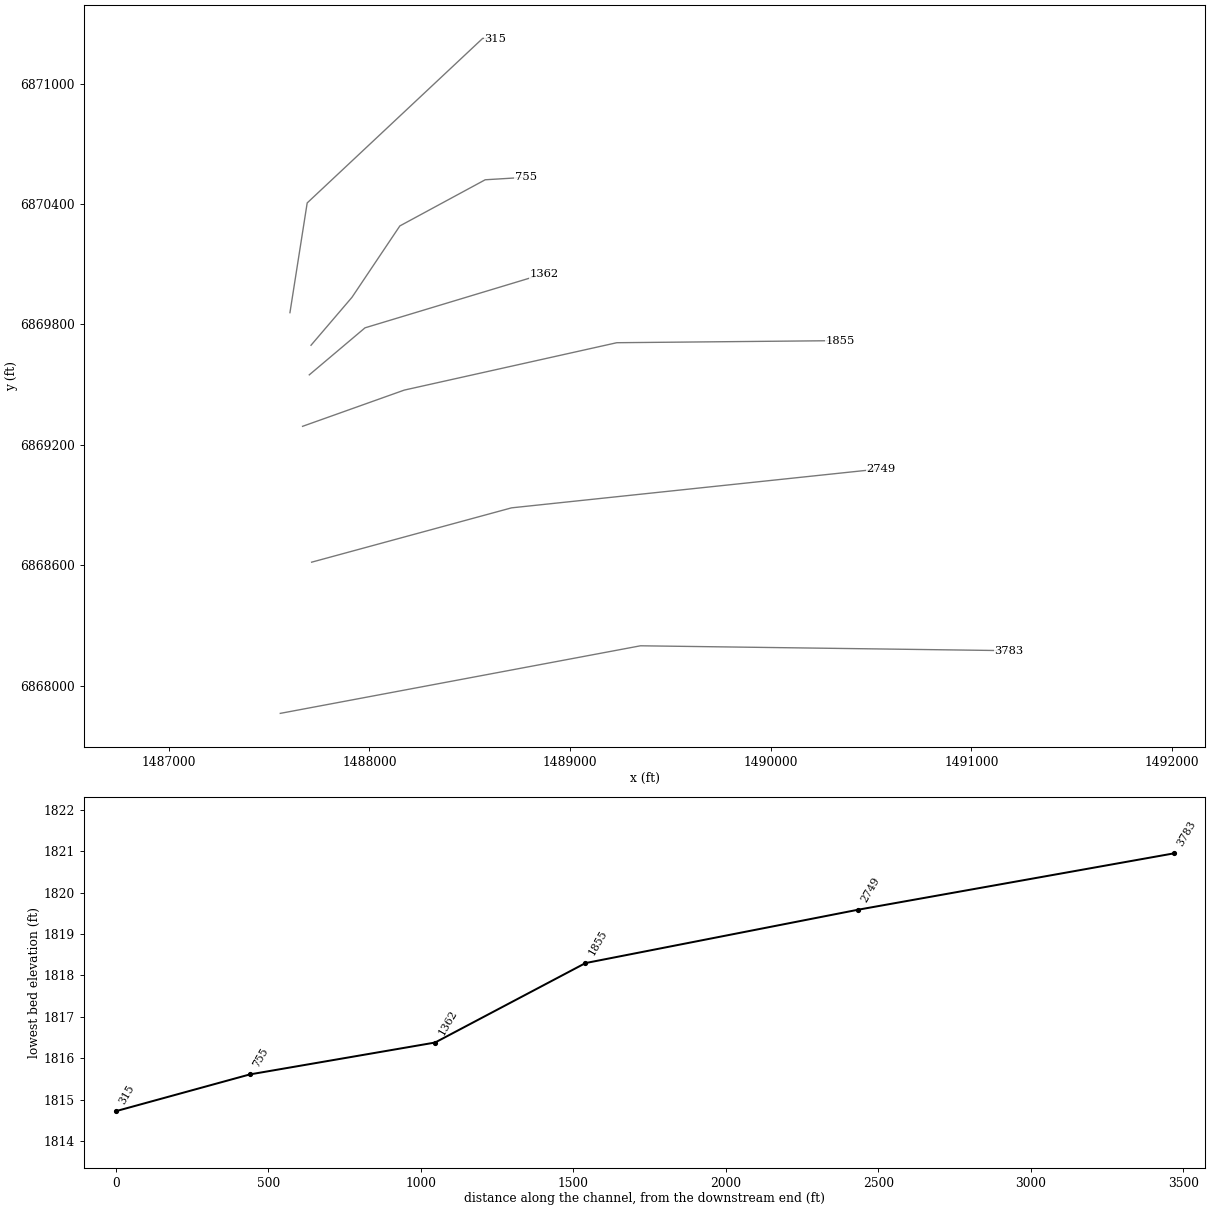
HEC-RAS study Little Bitter Creek.prj: Little Bitter Creek Base Level Engineering

--- Little Bitter Creek.g01 (geometry) --- (continued)

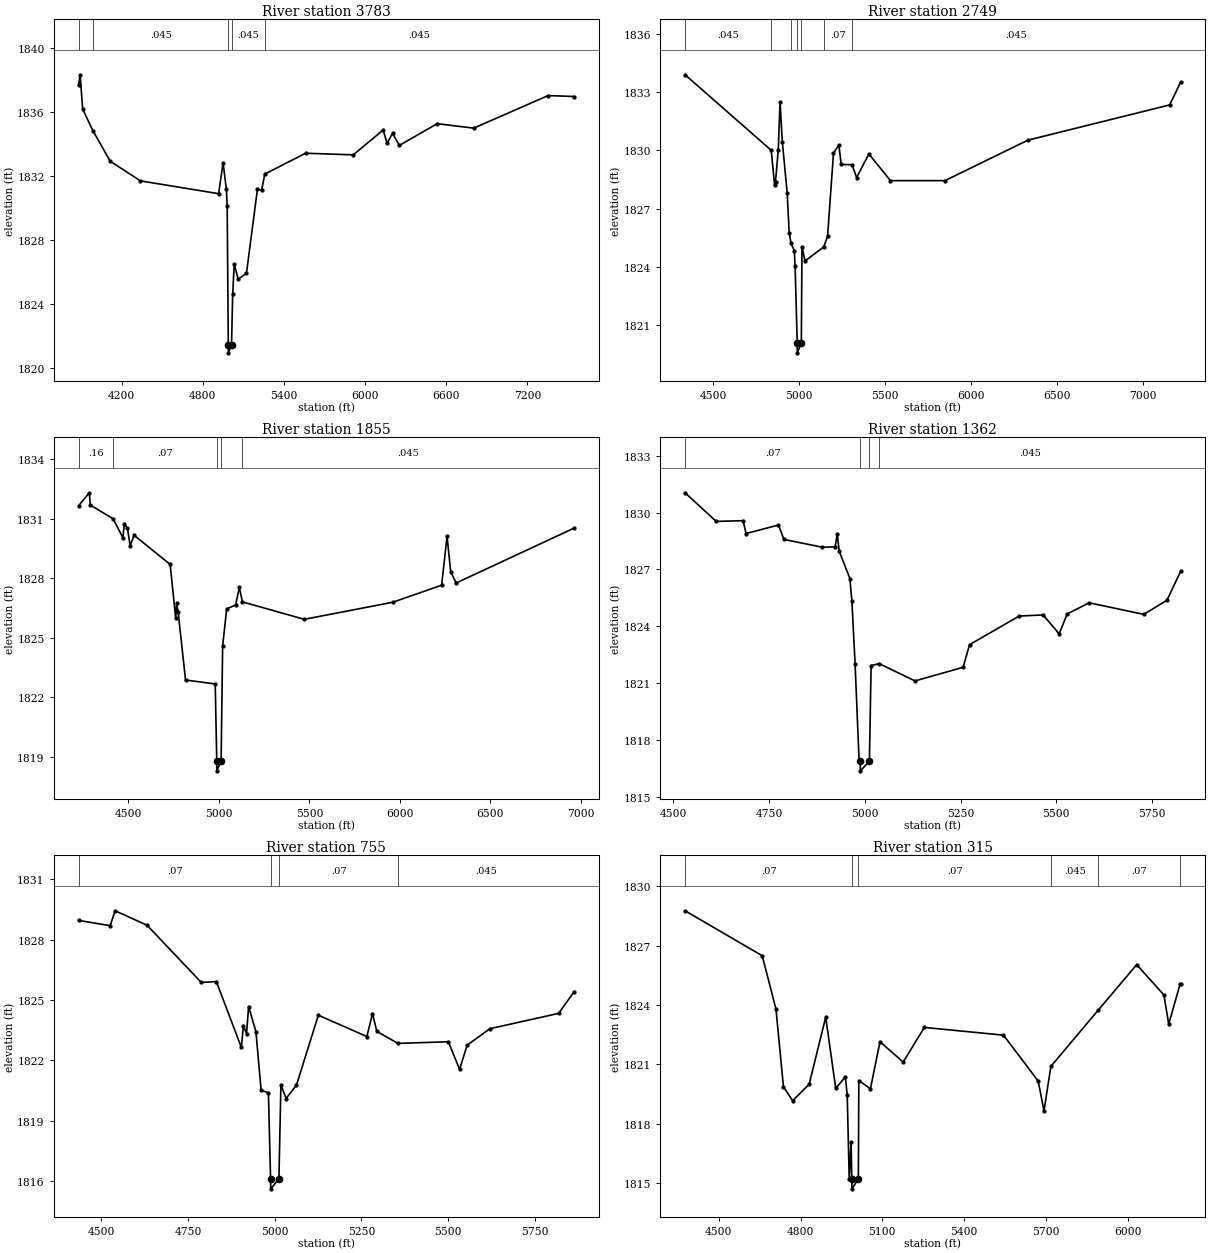
Type RM Length L Ch R = 1 ,3783    ,1034,1034,1034
BEGIN DESCRIPTION:
Mapping XS 60ec3e82
END DESCRIPTION:
XS GIS Cut Line= 3
       1487555.6       6867861.7      1489350.72       6868198.5
      1491187.51      6868174.19
#Sta/Elev= 30
  3881.7 1837.69  3892.6 1838.35  3911.6  1836.2    3988 1834.84  4115.1 1832.94
  4338.9 1831.71  4916.5 1830.91  4949.4 1832.84  4974.1 1831.18  4979.9 1830.14
  4988.1 1821.45  4988.6 1820.95    5012 1821.45  5020.6 1824.61  5031.7  1826.5
  5061.3 1825.56  5122.4 1825.93  5203.8 1831.21  5234.3 1831.11  5258.1 1832.14
  5559.9 1833.44  5912.4 1833.34  6132.5 1834.89  6162.5 1834.06  6202.5 1834.69
  6252.5 1833.93  6532.5 1835.29  6802.5 1835.01  7352.6 1837.05  7545.1 1836.99
#Mann= 5 ,-1 , 0
  3881.7    .035       0    3988    .045       0  4988.1    .045       0
    5012    .045       0  5258.1    .045       0
Bank Sta=4988.1,5012
XS Rating Curve= 0 ,0
Exp/Cntr=0.3,0.1

Type RM Length L Ch R = 1 ,2749    ,894,894,894
BEGIN DESCRIPTION:
Mapping XS f03eed53
END DESCRIPTION:
XS GIS Cut Line= 3
      1487711.86      6868615.17      1488708.35        6868886.
      1490548.66      6869080.45
#Sta/Elev= 30
  4335.7 1833.88  4836.8    1830  4856.6 1828.19  4861.8 1828.39  4877.8 1830.02
  4888.2 1832.47  4901.5 1830.43  4929.6 1827.81  4941.3 1825.76  4952.3 1825.22
  4970.8 1824.84  4975.9 1824.03  4988.1 1820.09  4988.6 1819.59    5012 1820.09
  5015.7 1825.05  5033.3 1824.31  5141.9 1825.03  5164.5 1825.57  5199.1 1829.84
  5230.2 1830.28  5244.1 1829.27  5306.5 1829.26  5333.8  1828.6  5405.2 1829.81
  5530.5 1828.44  5847.6 1828.44  6330.3 1830.52  7154.9 1832.33  7218.9  1833.5
#Mann= 7 ,-1 , 0
  4335.7    .045       0  4836.8     .07       0  4952.3    .045       0
  4988.1    .045       0    5012    .045       0  5141.9     .07       0
  5306.5    .045       0
Bank Sta=4988.1,5012
XS Rating Curve= 0 ,0
Exp/Cntr=0.3,0.1

Type RM Length L Ch R = 1 ,1855    ,493,493,493
BEGIN DESCRIPTION:
Mapping XS 1a70b560
END DESCRIPTION:
XS GIS Cut Line= 4
      1487666.72      6869292.26      1488173.63       6869472.8
      1489232.66      6869708.91      1490347.28      6869719.33
#Sta/Elev= 30
  4224.9 1831.67  4284.1 1832.32  4289.4  1831.7  4415.5 1831.01    4469 1830.06
  4477.8 1830.77  4494.6 1830.53  4509.7 1829.64  4530.9 1830.18  4730.5 1828.71
  4761.1    1826  4766.7 1826.75  4774.6 1826.31  4815.6 1822.88  4979.6 1822.68
    4988  1818.8  4988.5  1818.3  5012.1  1818.8  5020.5  1824.6  5042.9 1826.47
  5092.3 1826.66  5112.7 1827.55  5129.8 1826.82  5471.3 1825.94  5960.4  1826.8
  6230.4 1827.66  6260.4 1830.13  6280.3 1828.35  6310.4 1827.77  6962.7 1830.54
#Mann= 5 ,-1 , 0
  4224.9     .16       0  4415.5     .07       0    4988     .07       0
  5012.1     .07       0  5129.8    .045       0
Bank Sta=4988,5012.1
XS Rating Curve= 0 ,0
Exp/Cntr=0.3,0.1

Type RM Length L Ch R = 1 ,1362    ,607,607,607
BEGIN DESCRIPTION:
Mapping XS d0c851bf
END DESCRIPTION:
XS GIS Cut Line= 3
      1487700.15      6869548.75       1487977.9      6869783.11
      1488868.68      6870052.02
#Sta/Elev= 30
  4530.9 1831.04  4612.1 1829.53  4682.4 1829.57  4690.1 1828.89  4774.7 1829.34
    4789 1828.58  4889.1 1828.17  4922.6 1828.19  4928.2 1828.85  4933.4 1827.95
  4961.2 1826.52  4966.4 1825.33  4974.8 1822.01  4985.3 1816.88    4988 1816.88
  4988.5 1816.38  5012.1 1816.88  5016.6 1821.93  5037.8 1822.03  5131.2 1821.12
  5256.9 1821.84  5273.6 1823.03  5403.1 1824.54  5465.8  1824.6  5507.6  1823.6
  5528.5 1824.65  5585.9 1825.24  5728.3 1824.63    5789 1825.37  5824.8  1826.9
#Mann= 4 ,-1 , 0
  4530.9     .07       0    4988     .07       0  5012.1     .07       0
  5037.8    .045       0
Bank Sta=4988,5012.1
XS Rating Curve= 0 ,0
Exp/Cntr=0.3,0.1

Type RM Length L Ch R = 1 ,755     ,440,440,440
BEGIN DESCRIPTION:
Mapping XS 9e0116c3
END DESCRIPTION:
XS GIS Cut Line= 5
      1487708.81      6869696.31      1487912.79      6869935.02
      1488151.51      6870290.92      1488576.86      6870520.95
      1488779.68      6870533.26
#Sta/Elev= 30
  4434.4 1828.95  4525.4 1828.69  4539.6 1829.43  4631.8 1828.71  4788.1 1825.87
  4831.7 1825.91  4903.7 1822.64  4909.7  1823.7  4918.7 1823.33  4924.7 1824.67
  4945.8 1823.42  4960.7 1820.51  4981.8 1820.39    4988 1816.11  4988.5 1815.61
  5012.1 1816.11  5017.8 1820.78  5032.8  1820.1  5062.8 1820.77  5125.8 1824.24
  5265.8 1823.18    5282 1824.32  5294.6 1823.43  5355.5 1822.84  5500.8 1822.92
  5533.2 1821.55    5555 1822.75  5620.7 1823.57  5818.9 1824.33  5863.7 1825.41
#Mann= 4 ,-1 , 0
  4434.4     .07       0    4988     .07       0  5012.1     .07       0
  5355.5    .045       0
Bank Sta=4988,5012.1
XS Rating Curve= 0 ,0
Exp/Cntr=0.3,0.1

Type RM Length L Ch R = 1 ,315     ,0,0,0
BEGIN DESCRIPTION:
Little Bitter Creek 1.0
END DESCRIPTION:
XS GIS Cut Line= 4
      1487603.76      6869858.61       1487689.7       6870405.5
      1488564.54       6871225.8      1488628.59      6871222.54
#Sta/Elev= 30
  4376.8 1828.76  4659.6 1826.49  4710.2 1823.78  4737.3 1819.88    4771 1819.17
  4831.7    1820  4892.4 1823.39  4929.1 1819.79  4964.4 1820.37  4971.3 1819.45
  4978.6 1815.22  4985.4 1817.09    4988 1815.22  4988.5 1814.72  5012.1 1815.22
  5013.8 1820.19  5056.3 1819.77  5091.4 1822.15  5176.4 1821.12  5254.1 1822.87
  5544.2 1822.48  5671.7 1820.16  5692.7 1818.65  5717.9  1820.9  5892.6 1823.76
  6032.7 1826.04  6132.4 1824.51  6150.2 1823.04  6191.6 1825.05  6193.8 1825.05
#Mann= 6 ,-1 , 0
  4376.8     .07       0    4988     .07       0  5012.1     .07       0
  5717.9    .045       0  5892.6     .07       0  6191.6    .045       0
Bank Sta=4988,5012.1
XS Rating Curve= 0 ,0
Exp/Cntr=0.3,0.1

Chan Stop Cuts=-1
Use User Specified Reach Order=0
Composite Channel Slope=5