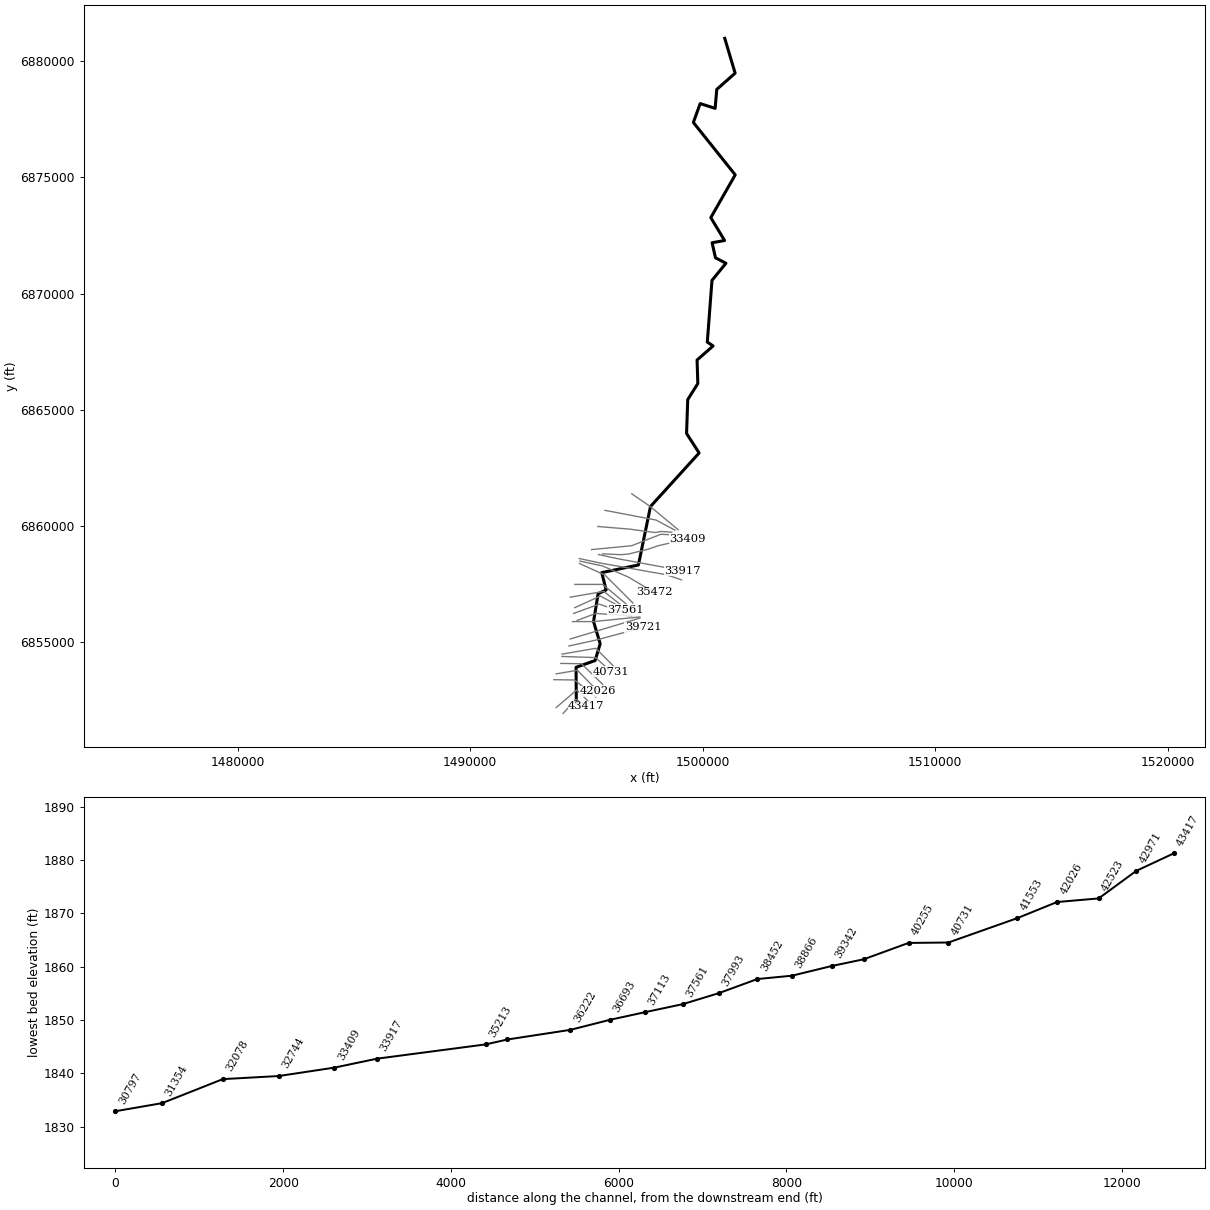
--- NC Unknown Stream 01.prj (project) ---

Proj Title=NC Unknown Stream 01 Base Level Engineering
Current Plan=p01
Default Exp/Contr=0.3,0.1
English Units
Geom File=g01
Flow File=f01
Plan File=p01
Y Axis Title=Elevation
X Axis Title(PF)=Main Channel Distance
X Axis Title(XS)=Station
BEGIN DESCRIPTION:
NC Unknown Stream 01
END DESCRIPTION:
DSS Export Rating Curves= 0
DSS Export Rating Curve Sorted= 0
DSS Export Volume Flow Curves= 0
DXF OffsetX= 0
DXF OffsetY= 0
DXF ScaleX= 1
DXF ScaleY= 10

--- NC Unknown Stream 01.p01 (plan) ---

Plan Title=Multiple Run
Short Identifier=Multiple
Geom File=g01
Flow File=f01
Subcritical Flow
K Sum by GR= 0
Std Step Tol= 0.01
Critical Tol= 0.01
Num of Std Step Trials= 20
Max Error Tol= 0.3
Flow Tol Ratio= 0.001
Split Flow NTrial= 30
Split Flow Tol= 0.02
Split Flow Ratio= 0.02
Log Output Level= 0
Friction Slope Method= 1
Unsteady Friction Slope Method= 2
Unsteady Bridges Friction Slope Method= 1
Parabolic Critical Depth
Global Vel Dist=  1 , 1 , 1
Global Log Level= 0
CheckData=True
Encroach Param= -1, 0, 0, 0
BEGIN DESCRIPTION:
Multiple Run
END DESCRIPTION:

--- NC Unknown Stream 01.f01 (steady flow) ---

Flow Title=Multiple
Program Version=4.10
Number of Profiles= 7
Profile Names=10-year,25-year,50-year,1pct_min,100-year,1pct_plu,500-year
River Rch & RM=NC Unknown Strea,Reach-1         ,43417
     236     325     397     242     482     962     719
River Rch & RM=NC Unknown Strea,Reach-1         ,42026
     377     531     661     408     814    1623    1250
River Rch & RM=NC Unknown Strea,Reach-1         ,32078
     485     691     865     537    1072    2139    1666
River Rch & RM=NC Unknown Strea,Reach-1         ,26704
     550     788     991     617    1231    2456    1926
River Rch & RM=NC Unknown Strea,Reach-1         ,22489
     638     920    1161     726    1448    2888    2282
River Rch & RM=NC Unknown Strea,Reach-1         ,19801
     711    1029    1300     814    1625    3242    2570
River Rch & RM=NC Unknown Strea,Reach-1         ,13803
     781    1132    1434     899    1793    3578    2842
River Rch & RM=NC Unknown Strea,Reach-1         ,9985
     781    1132    1432     897    1789    3570    2831
River Rch & RM=NC Unknown Strea,Reach-1         ,8691
     890    1292    1637    1026    2047    4084    3242
River Rch & RM=NC Unknown Strea,Reach-1         ,8241
     890    1292    1637    1026    2047    4084    3242
Boundary for River Rch & Prof#=NC Unknown Strea,Reach-1         , 1
Up Type= 0
Dn Type= 3
Dn Slope=0.001
Boundary for River Rch & Prof#=NC Unknown Strea,Reach-1         , 2
Up Type= 0
Dn Type= 3
Dn Slope=0.001
Boundary for River Rch & Prof#=NC Unknown Strea,Reach-1         , 3
Up Type= 0
Dn Type= 3
Dn Slope=0.001
Boundary for River Rch & Prof#=NC Unknown Strea,Reach-1         , 4
Up Type= 0
Dn Type= 3
Dn Slope=0.001
Boundary for River Rch & Prof#=NC Unknown Strea,Reach-1         , 5
Up Type= 0
Dn Type= 3
Dn Slope=0.001
Boundary for River Rch & Prof#=NC Unknown Strea,Reach-1         , 6
Up Type= 0
Dn Type= 3
Dn Slope=0.001
Boundary for River Rch & Prof#=NC Unknown Strea,Reach-1         , 7
Up Type= 0
Dn Type= 3
Dn Slope=0.001
DSS Import GetInterval= 0
DSS Import GetPeak= 0
DSS Import FillOption= 0

--- NC Unknown Stream 01.g01 (geometry) ---

Geom Title=Existing Conditions

River Reach=NC Unknown Strea,Reach-1
Reach XY= 30
      1494570.03      6852403.80      1494560.54      6853921.51
      1495378.64      6854210.86      1495597.42      6854934.68
      1495312.34      6855888.10      1495507.98      6857086.57
      1495854.52      6857248.49      1495663.89      6857994.51
      1497241.82      6858324.36      1497760.83      6860840.30
      1499852.95      6863143.86      1499312.67      6863984.34
      1499362.30      6865438.08      1499797.16      6866134.77
      1499764.28      6867144.68      1500453.20      6867750.00
      1500204.39      6867917.39      1500405.56      6870572.50
      1501005.40      6871308.13      1500556.58      6871544.05
      1500410.28      6872190.72      1500947.92      6872287.98
      1500355.24      6873272.78      1501405.50      6875113.04
      1499604.91      6877368.13      1499898.81      6878180.18
      1500541.37      6877974.79      1500610.80      6878790.29
      1501401.25      6879489.55      1500955.00      6880988.00

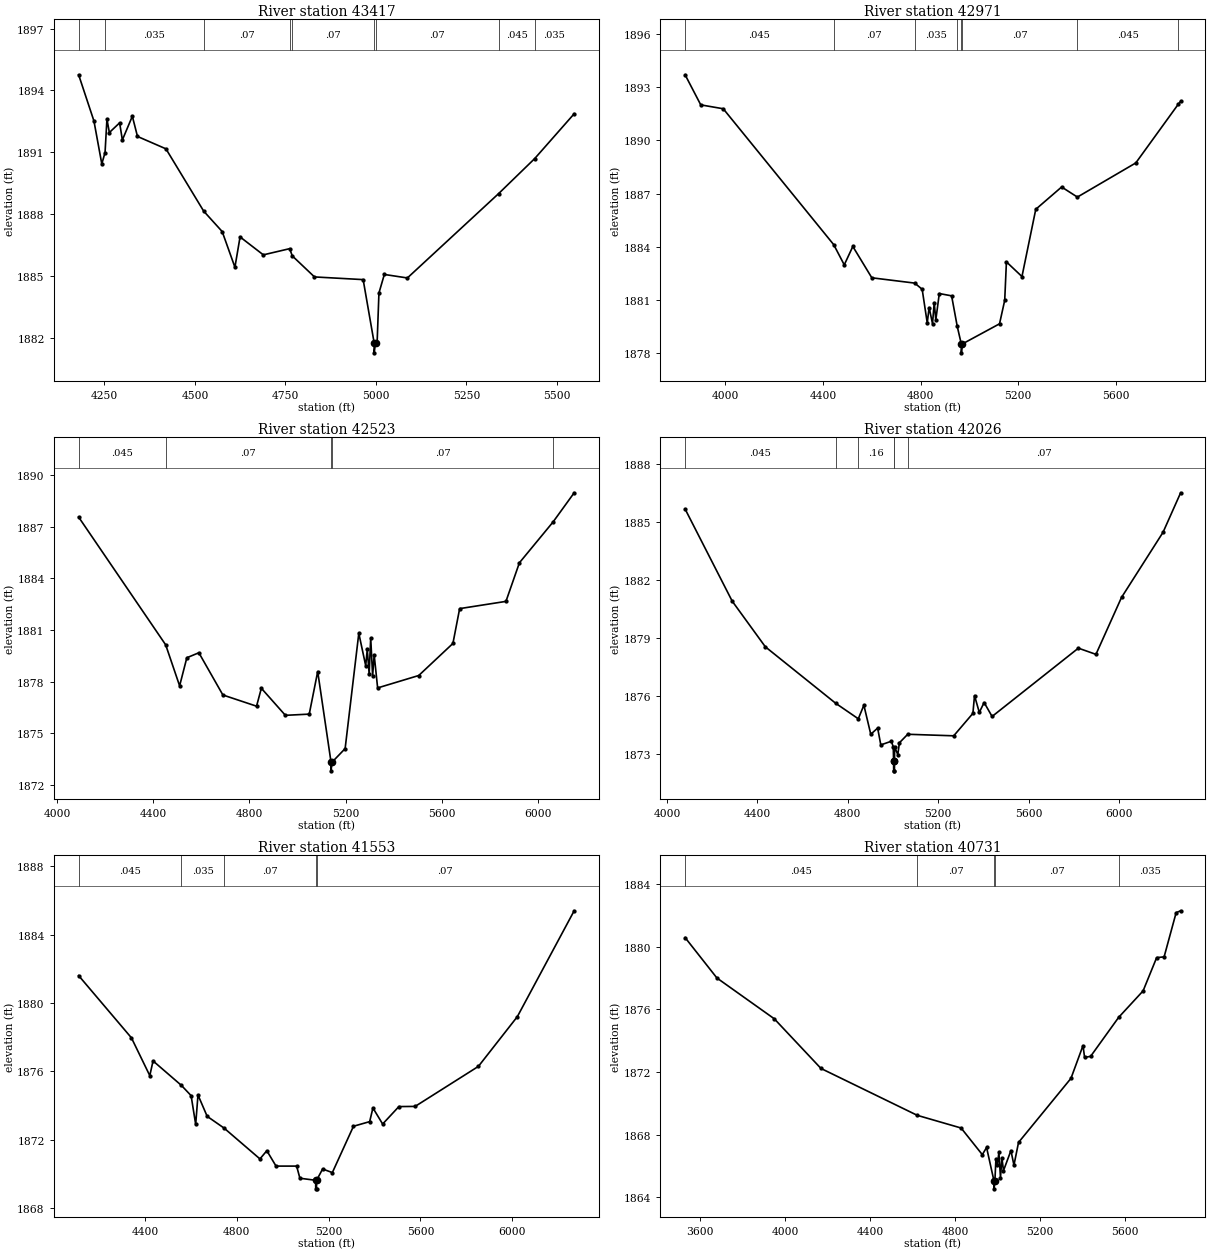
Type RM Length L Ch R = 1,43417,446,446,446
BEGIN DESCRIPTION:
NC Unknown Stream 01 59.0
END DESCRIPTION:
XS GIS Cut Line= 3
      1494004.97      6851937.97      1494552.24      6852548.63
      1495005.01      6852237.99
#Sta/Elev= 30
  4178.6 1894.76  4220.9 1892.52  4242.6 1890.44  4251.6 1890.99  4256.8 1892.61
  4263.5 1891.96  4291.9 1892.43  4299.4 1891.60  4327.0 1892.75  4341.2 1891.77
  4419.8 1891.17  4524.1 1888.15  4575.2 1887.16  4610.4 1885.43  4624.6 1886.90
  4688.9 1886.03  4761.6 1886.33  4768.9 1885.98  4830.2 1884.96  4964.7 1884.83
  4994.9 1881.78  4995.2 1881.28  4998.9 1881.78  5003.3 1881.78  5008.3 1884.18
  5023.2 1885.08  5086.9 1884.91  5339.0 1889.00  5438.8 1890.70  5547.7 1892.87
#Mann=9,-1,0
  4178.6   0.045       0  4251.6   0.035       0  4524.1    0.07       0
  4761.6   0.035       0  4768.9    0.07       0  4994.9    0.07       0
  4998.9    0.07       0  5339.0   0.045       0  5438.8   0.035       0
Bank Sta=4994.9,4998.9
Exp/Cntr=0.3,0.1

Type RM Length L Ch R = 1,42971,448,448,448
BEGIN DESCRIPTION:
NC Unknown Stream 01 58.0
END DESCRIPTION:
XS GIS Cut Line= 3
      1493705.00      6852188.00      1494590.26      6852947.07
      1495204.99      6852338.01
#Sta/Elev= 30
  3834.4 1893.71  3898.6 1892.01  3990.8 1891.79  4443.8 1884.11  4486.9 1882.97
  4522.0 1884.01  4599.9 1882.24  4775.8 1881.94  4806.3 1881.59  4827.1 1879.69
  4834.8 1880.56  4848.7 1879.65  4855.7 1880.84  4862.2 1879.86  4876.5 1881.35
  4927.0 1881.22  4950.0 1879.50  4966.7 1878.50  4967.0 1878.00  4970.7 1878.50
  5123.4 1879.64  5144.7 1880.97  5151.7 1883.14  5215.4 1882.31  5272.0 1886.11
  5378.0 1887.37  5442.6 1886.80  5682.1 1888.73  5855.9 1892.04  5865.9 1892.21
#Mann=8,-1,0
  3834.4   0.045       0  4443.8    0.07       0  4775.8   0.035       0
  4950.0    0.07       0  4966.7    0.07       0  4970.7    0.07       0
  5442.6   0.045       0  5855.9   0.035       0
Bank Sta=4966.7,4970.7
Exp/Cntr=0.3,0.1

Type RM Length L Ch R = 1,42523,497,497,497
BEGIN DESCRIPTION:
NC Unknown Stream 01 57.0
END DESCRIPTION:
XS GIS Cut Line= 3
      1493604.97      6853388.00      1494496.25      6853374.93
      1495405.02      6852637.98
#Sta/Elev= 30
  4089.4 1887.55  4451.5 1880.14  4509.5 1877.76  4539.5 1879.39  4589.5 1879.68
  4689.5 1877.23  4829.5 1876.58  4849.5 1877.62  4949.5 1876.05  5048.7 1876.12
  5083.9 1878.59  5139.4 1873.33  5139.6 1872.83  5143.4 1873.33  5198.0 1874.12
  5254.9 1880.81  5283.6 1878.93  5290.1 1879.87  5298.0 1878.44  5304.4 1880.54
  5312.4 1878.34  5318.8 1879.56  5333.2 1877.64  5504.2 1878.36  5646.4 1880.22
  5674.4 1882.24  5867.0 1882.66  5923.0 1884.90  6063.2 1887.27  6150.8 1888.96
#Mann=5,-1,0
  4089.4   0.045       0  4451.5    0.07       0  5139.4    0.07       0
  5143.4    0.07       0  6063.2   0.045       0
Bank Sta=5139.4,5143.4
Exp/Cntr=0.3,0.1

Type RM Length L Ch R = 1,42026,473,473,473
BEGIN DESCRIPTION:
NC Unknown Stream 01 56.0
END DESCRIPTION:
XS GIS Cut Line= 3
      1493704.97      6853637.99      1494616.75      6853793.05
      1495505.01      6852887.99
#Sta/Elev= 30
  4079.8 1885.68  4288.2 1880.92  4434.9 1878.56  4746.4 1875.64  4846.3 1874.84
  4871.0 1875.54  4901.5 1874.04  4931.9 1874.36  4945.9 1873.49  4992.8 1873.68
  5001.1 1873.38  5002.5 1872.65  5002.8 1872.15  5006.3 1872.15  5006.5 1872.65
  5007.0 1873.38  5021.2 1872.99  5028.2 1873.60  5065.1 1874.04  5268.6 1873.96
  5353.5 1875.12  5360.6 1876.04  5381.8 1875.17  5403.1 1875.68  5438.4 1874.96
  5820.2 1878.49  5898.0 1878.17  6011.1 1881.11  6195.0 1884.48  6272.8 1886.52
#Mann=6,-1,0
  4079.8   0.045       0  4746.4    0.07       0  4846.3    0.16       0
  5002.5    0.07       0  5006.5    0.16       0  5065.1    0.07       0
Bank Sta=5002.5,5006.5
Exp/Cntr=0.3,0.1

Type RM Length L Ch R = 1,41553,822,822,822
BEGIN DESCRIPTION:
NC Unknown Stream 01 55.0
END DESCRIPTION:
XS GIS Cut Line= 3
      1493904.95      6854088.00      1494791.23      6854074.30
      1495705.02      6853187.98
#Sta/Elev= 30
  4110.5 1881.60  4340.6 1877.96  4420.6 1875.75  4434.8 1876.61  4558.3 1875.18
  4600.6 1874.58  4620.6 1872.90  4630.6 1874.62  4670.6 1873.37  4744.5 1872.68
  4900.6 1870.88  4930.6 1871.36  4970.7 1870.46  5060.5 1870.46  5074.7 1869.75
  5143.4 1869.63  5143.6 1869.13  5147.1 1869.13  5147.4 1869.63  5173.7 1870.29
  5216.1 1870.08  5308.2 1872.79  5378.7 1873.06  5392.9 1873.86  5435.3 1872.92
  5506.0 1873.94  5576.8 1873.95  5852.5 1876.29  6022.3 1879.20  6269.9 1885.39
#Mann=5,-1,0
  4110.5   0.045       0  4558.3   0.035       0  4744.5    0.07       0
  5143.4    0.07       0  5147.4    0.07       0
Bank Sta=5143.4,5147.4
Exp/Cntr=0.3,0.1

Type RM Length L Ch R = 1,40731,476,476,476
BEGIN DESCRIPTION:
NC Unknown Stream 01 54.0
END DESCRIPTION:
XS GIS Cut Line= 3
      1493955.00      6854388.00      1495405.00      6854338.00
      1496054.96      6853738.03
#Sta/Elev= 30
  3528.5 1880.58  3678.6 1878.00  3948.7 1875.40  4168.9 1872.23  4622.6 1869.24
  4829.3 1868.43  4929.3 1866.73  4949.3 1867.19  4984.3 1865.05  4984.6 1864.55
  4988.5 1865.05  4993.3 1866.43  5000.6 1866.10  5007.4 1866.88  5014.8 1865.27
  5021.6 1866.52  5029.0 1865.71  5064.1 1866.99  5078.3 1866.06  5099.9 1867.51
  5347.1 1871.60  5403.8 1873.69  5411.2 1872.94  5439.5 1873.00  5571.8 1875.49
  5687.0 1877.18  5750.8 1879.30  5786.0 1879.35  5842.7 1882.17  5863.9 1882.29
#Mann=5,-1,0
  3528.5   0.045       0  4622.6    0.07       0  4984.3    0.07       0
  4988.5    0.07       0  5571.8   0.035       0
Bank Sta=4984.3,4988.5
Exp/Cntr=0.3,0.1

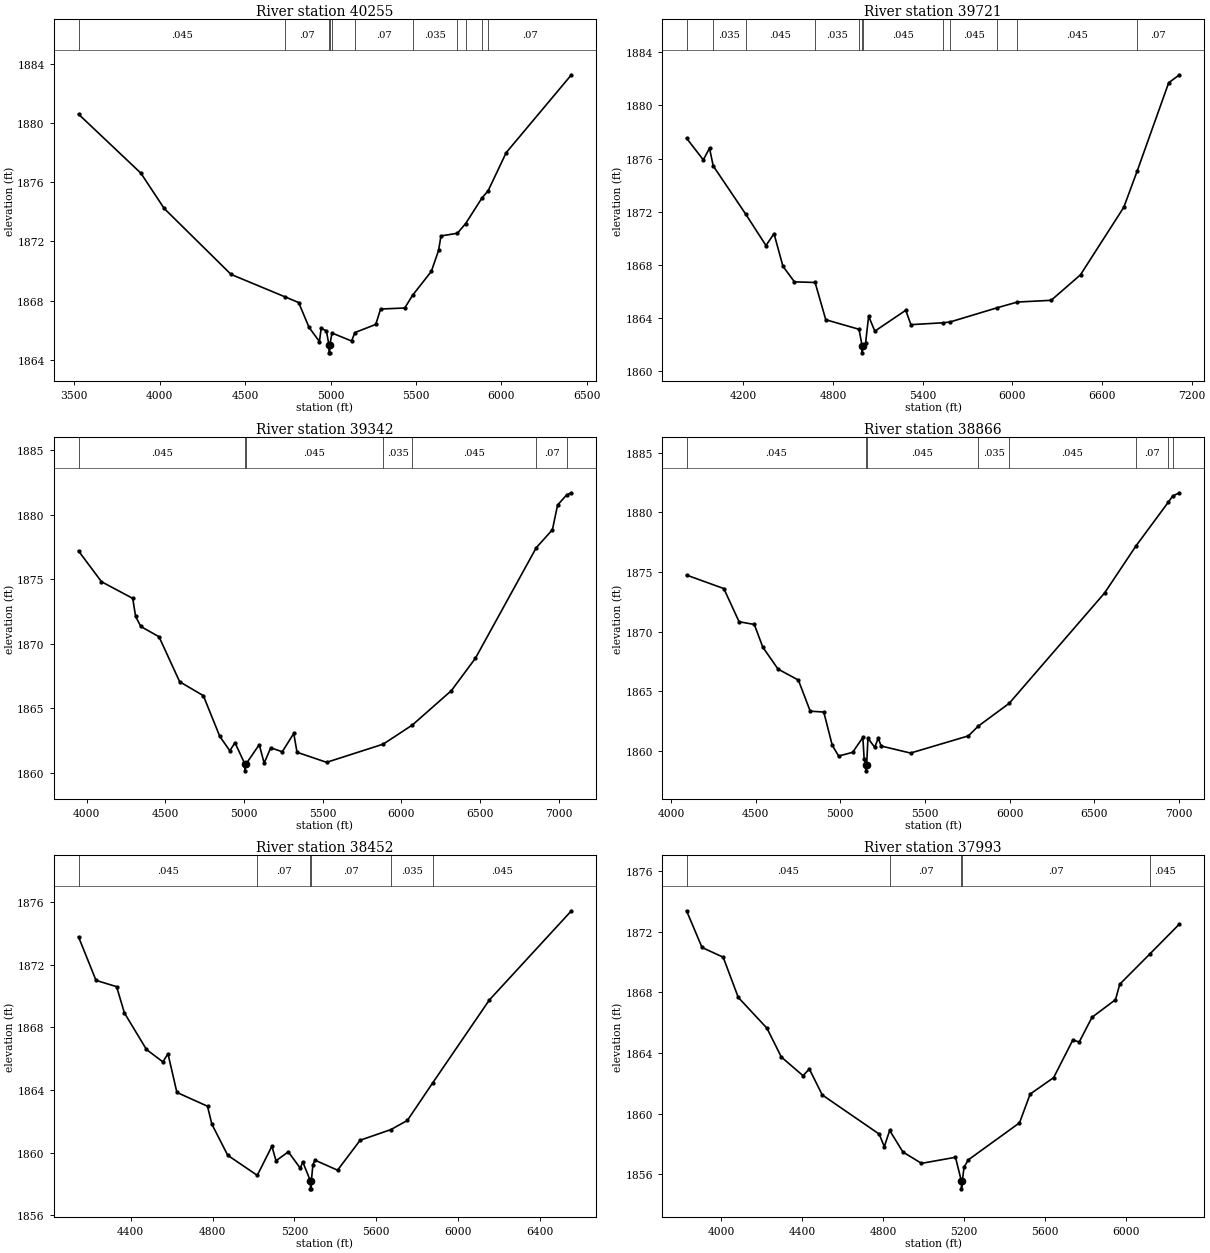
Type RM Length L Ch R = 1,40255,534,534,534
BEGIN DESCRIPTION:
NC Unknown Stream 01 53.0
END DESCRIPTION:
XS GIS Cut Line= 3
      1493955.02      6854488.00      1495405.00      6854738.00
      1496405.01      6853737.99
#Sta/Elev= 30
  3524.7 1880.60  3890.0 1876.61  4026.0 1874.23  4417.7 1869.77  4734.4 1868.25
  4813.4 1867.87  4874.3 1866.19  4935.2 1865.23  4945.3 1866.13  4975.8 1865.95
  4991.4 1864.97  4991.7 1864.47  4995.4 1864.47  4995.7 1864.97  5008.4 1865.81
  5123.4 1865.27  5142.6 1865.84  5264.8 1866.39  5293.1 1867.43  5434.5 1867.50
  5481.0 1868.37  5590.0 1869.97  5632.5 1871.39  5646.6 1872.37  5742.8 1872.55
  5791.2 1873.21  5886.9 1874.94  5922.5 1875.42  6028.5 1878.00  6410.3 1883.26
#Mann=11,-1,0
  3524.7   0.045       0  4734.4    0.07       0  4991.4    0.07       0
  4995.7    0.07       0  5008.4    0.16       0  5142.6    0.07       0
  5481.0   0.035       0  5742.8   0.045       0  5791.2    0.07       0
  5886.9   0.045       0  5922.5    0.07       0
Bank Sta=4991.4,4995.7
Exp/Cntr=0.3,0.1

Type RM Length L Ch R = 1,39721,379,379,379
BEGIN DESCRIPTION:
NC Unknown Stream 01 52.0
END DESCRIPTION:
XS GIS Cut Line= 3
      1494255.01      6854838.00      1495430.95      6855096.52
      1497454.96      6855637.99
#Sta/Elev= 30
  3819.3 1877.54  3931.3 1875.91  3972.9 1876.79  3997.6 1875.46  4214.1 1871.85
  4350.7 1869.47  4404.7 1870.36  4464.3 1867.91  4541.1 1866.74  4679.6 1866.69
  4751.0 1863.89  4973.8 1863.17  4994.6 1861.90  4994.9 1861.40  4998.9 1861.90
  5017.2 1862.11  5037.9 1864.16  5079.3 1863.03  5286.3 1864.60  5320.9 1863.52
  5535.2 1863.66  5582.8 1863.72  5898.2 1864.79  6033.4 1865.22  6259.4 1865.35
  6456.0 1867.27  6745.8 1872.35  6835.6 1875.08  7046.1 1881.71  7118.5 1882.31
#Mann=12,-1,0
  3819.3   0.045       0  3997.6   0.035       0  4214.1   0.045       0
  4679.6   0.035       0  4973.8   0.045       0  4994.6   0.045       0
  4998.9   0.045       0  5535.2   0.035       0  5582.8   0.045       0
  5898.2   0.035       0  6033.4   0.045       0  6835.6    0.07       0
Bank Sta=4994.6,4998.9
Exp/Cntr=0.3,0.1

Type RM Length L Ch R = 1,39342,476,476,476
BEGIN DESCRIPTION:
NC Unknown Stream 01 51.0
END DESCRIPTION:
XS GIS Cut Line= 3
      1494305.02      6855138.00      1495305.00      6855438.00
      1497305.02      6856038.01
#Sta/Elev= 30
  3947.7 1877.21  4093.8 1874.82  4292.2 1873.53  4310.5 1872.13  4343.5 1871.35
  4459.3 1870.55  4590.6 1867.06  4741.1 1865.98  4845.5 1862.82  4909.1 1861.71
  4942.1 1862.33  5006.0 1860.65  5006.3 1860.15  5010.4 1860.65  5096.1 1862.18
  5127.4 1860.75  5169.2 1861.94  5242.3 1861.63  5315.4 1863.05  5336.2 1861.59
  5524.2 1860.81  5883.6 1862.22  6068.6 1863.70  6317.6 1866.38  6469.9 1868.89
  6856.4 1877.46  6958.8 1878.85  6991.9 1880.77  7049.7 1881.56  7079.8 1881.72
#Mann=7,-1,0
  3947.7   0.045       0  5006.0   0.045       0  5010.4   0.045       0
  5883.6   0.035       0  6068.6   0.045       0  6856.4    0.07       0
  7049.7   0.045       0
Bank Sta=5006,5010.4
Exp/Cntr=0.3,0.1

Type RM Length L Ch R = 1,38866,414,414,414
BEGIN DESCRIPTION:
NC Unknown Stream 01 50.0
END DESCRIPTION:
XS GIS Cut Line= 3
      1494404.97      6855888.00      1495305.00      6855888.00
      1497305.00      6856088.00
#Sta/Elev= 30
  4092.5 1874.73  4312.5 1873.60  4402.5 1870.82  4492.5 1870.59  4542.5 1868.69
  4632.5 1866.85  4752.5 1865.93  4822.5 1863.32  4902.5 1863.25  4952.5 1860.47
  4990.0 1859.56  5072.9 1859.87  5133.2 1861.12  5140.8 1859.33  5151.1 1858.82
  5151.4 1858.32  5155.5 1858.82  5163.4 1861.05  5203.6 1860.29  5223.7 1861.06
  5241.3 1860.40  5414.6 1859.81  5756.3 1861.25  5813.9 1862.06  5997.3 1863.98
  6560.3 1873.23  6744.3 1877.15  6936.3 1880.84  6963.3 1881.37  7002.5 1881.63
#Mann=8,-1,0
  4092.5   0.045       0  5151.1   0.045       0  5155.5   0.045       0
  5813.9   0.035       0  5997.3   0.045       0  6744.3    0.07       0
  6936.3   0.045       0  6963.3    0.07       0
Bank Sta=5151.1,5155.5
Exp/Cntr=0.3,0.1

Type RM Length L Ch R = 1,38452,459,459,459
BEGIN DESCRIPTION:
NC Unknown Stream 01 49.0
END DESCRIPTION:
XS GIS Cut Line= 3
      1494604.98      6855937.99      1495405.00      6856238.00
      1496954.95      6856138.00
#Sta/Elev= 30
  4145.5 1873.77  4231.0 1870.99  4331.5 1870.59  4369.8 1868.91  4477.5 1866.58
  4557.6 1865.79  4582.5 1866.31  4626.1 1863.84  4775.6 1862.96  4797.0 1861.81
  4874.4 1859.83  5018.7 1858.55  5090.1 1860.41  5110.2 1859.48  5170.3 1860.05
  5229.1 1859.00  5240.4 1859.42  5278.3 1858.19  5278.6 1857.69  5282.4 1857.69
  5282.8 1858.19  5290.5 1859.24  5300.5 1859.52  5410.8 1858.88  5521.0 1860.79
  5671.1 1861.47  5751.5 1862.05  5876.0 1864.46  6152.3 1869.74  6553.1 1875.43
#Mann=6,-1,0
  4145.5   0.045       0  5018.7    0.07       0  5278.3   0.045       0
  5282.8    0.07       0  5671.1   0.035       0  5876.0   0.045       0
Bank Sta=5278.3,5282.8
Exp/Cntr=0.3,0.1

Type RM Length L Ch R = 1,37993,432,432,432
BEGIN DESCRIPTION:
NC Unknown Stream 01 48.0
END DESCRIPTION:
XS GIS Cut Line= 3
      1494454.96      6856237.99      1495555.00      6856638.00
      1496754.98      6856238.01
#Sta/Elev= 30
  3829.9 1873.37  3906.4 1870.95  4010.8 1870.31  4085.3 1867.66  4227.0 1865.63
  4298.1 1863.73  4405.2 1862.50  4436.5 1862.94  4500.3 1861.23  4781.6 1858.65
  4806.9 1857.82  4833.4 1858.89  4898.7 1857.47  4990.4 1856.72  5158.5 1857.12
  5187.9 1855.54  5188.2 1855.04  5192.4 1855.54  5200.7 1856.46  5221.8 1856.95
  5474.8 1859.39  5527.5 1861.29  5643.4 1862.37  5738.3 1864.85  5769.9 1864.72
  5833.1 1866.35  5949.1 1867.51  5970.2 1868.53  6120.9 1870.55  6265.3 1872.50
#Mann=5,-1,0
  3829.9   0.045       0  4833.4    0.07       0  5187.9    0.07       0
  5192.4    0.07       0  6120.9   0.045       0
Bank Sta=5187.9,5192.4
Exp/Cntr=0.3,0.1

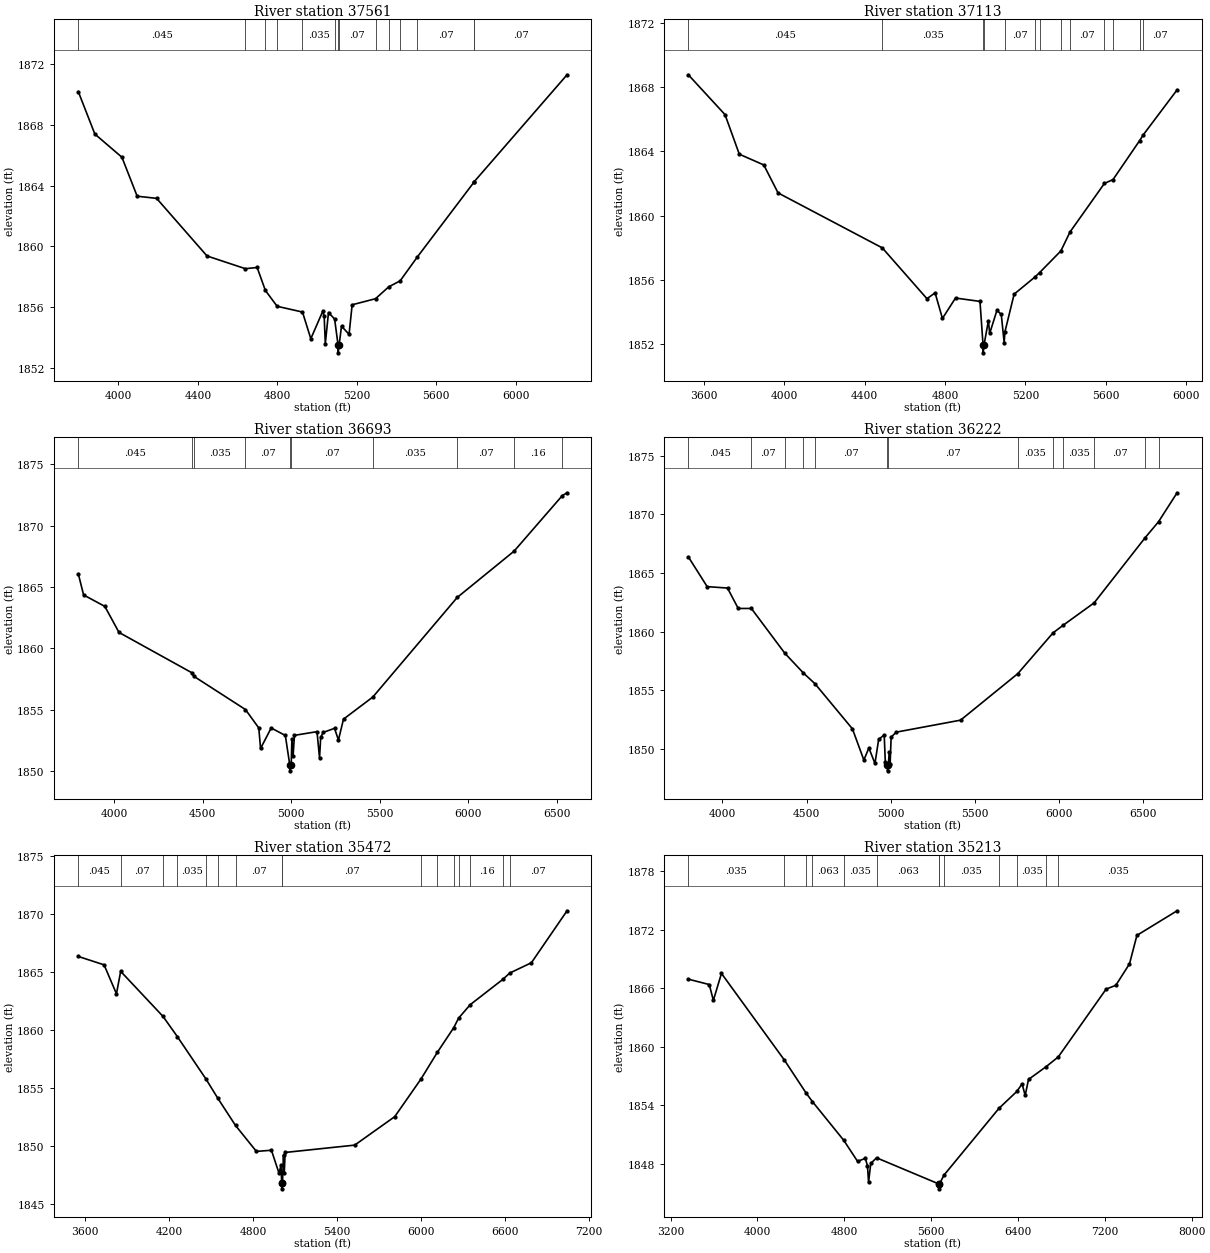
Type RM Length L Ch R = 1,37561,448,448,448
BEGIN DESCRIPTION:
NC Unknown Stream 01 47.0
END DESCRIPTION:
XS GIS Cut Line= 3
      1494505.03      6856488.02      1495605.00      6856988.00
      1496705.03      6856387.98
#Sta/Elev= 30
  3797.9 1870.20  3881.3 1867.40  4017.6 1865.87  4094.4 1863.30  4192.2 1863.16
  4446.0 1859.36  4639.3 1858.52  4698.6 1858.60  4739.8 1857.09  4799.2 1856.04
  4926.9 1855.66  4968.8 1853.90  5028.9 1855.71  5036.1 1855.38  5041.8 1853.58
  5057.9 1855.63  5088.7 1855.20  5106.2 1853.47  5106.5 1852.97  5111.2 1853.47
  5123.4 1854.73  5161.4 1854.19  5177.0 1856.14  5294.7 1856.54  5360.9 1857.32
  5418.8 1857.72  5503.9 1859.27  5791.8 1864.25  5792.4 1864.27  6259.2 1871.31
#Mann=14,-1,0
  3797.9   0.045       0  4639.3    0.07       0  4739.8   0.045       0
  4799.2    0.07       0  4926.9   0.035       0  5088.7    0.07       0
  5106.2   0.035       0  5111.2    0.07       0  5294.7   0.045       0
  5360.9    0.07       0  5418.8   0.045       0  5503.9    0.07       0
  5791.8   0.035       0  5792.4    0.07       0
Bank Sta=5106.2,5111.2
Exp/Cntr=0.3,0.1

Type RM Length L Ch R = 1,37113,420,420,420
BEGIN DESCRIPTION:
NC Unknown Stream 01 46.0
END DESCRIPTION:
XS GIS Cut Line= 3
      1494305.04      6856938.01      1495755.00      6857188.00
      1496504.98      6856588.01
#Sta/Elev= 30
  3523.2 1868.77  3705.8 1866.29  3776.8 1863.83  3898.6 1863.16  3969.7 1861.42
  4488.3 1858.00  4710.4 1854.84  4751.0 1855.20  4787.5 1853.61  4852.5 1854.88
  4974.3 1854.67  4989.5 1851.97  4989.9 1851.47  4994.6 1851.97  5016.2 1853.47
  5022.6 1852.68  5058.6 1854.11  5080.2 1853.86  5094.6 1852.11  5098.5 1852.78
  5144.2 1855.12  5247.0 1856.18  5270.8 1856.46  5376.8 1857.81  5422.3 1858.99
  5593.4 1862.01  5636.2 1862.25  5769.0 1864.68  5786.5 1865.03  5955.0 1867.83
#Mann=13,-1,0
  3523.2   0.045       0  4488.3   0.035       0  4989.5   0.035       0
  4994.6   0.035       0  5098.5    0.07       0  5247.0   0.035       0
  5270.8   0.045       0  5376.8   0.035       0  5422.3    0.07       0
  5593.4   0.035       0  5636.2    0.07       0  5769.0   0.035       0
  5786.5    0.07       0
Bank Sta=4989.5,4994.6
Exp/Cntr=0.3,0.1

Type RM Length L Ch R = 1,36693,471,471,471
BEGIN DESCRIPTION:
NC Unknown Stream 01 45.0
END DESCRIPTION:
XS GIS Cut Line= 3
      1494505.03      6857488.00      1495705.00      6857488.00
      1496904.98      6856488.01
#Sta/Elev= 30
  3796.3 1866.07  3826.3 1864.35  3946.3 1863.42  4026.3 1861.30  4436.4 1858.03
  4449.2 1857.73  4741.0 1855.02  4816.3 1853.52  4826.3 1851.85  4886.3 1853.52
  4966.3 1852.91  4991.2 1850.53  4991.6 1850.03  4996.3 1850.53  4999.5 1850.53
  5003.4 1852.66  5009.9 1851.20  5017.8 1852.92  5145.3 1853.22  5159.6 1851.07
  5166.1 1852.76  5180.5 1853.16  5244.2 1853.49  5266.4 1852.54  5295.0 1854.24
  5460.8 1856.04  5937.8 1864.15  6259.2 1867.92  6531.4 1872.44  6558.3 1872.67
#Mann=10,-1,0
  3796.3   0.045       0  4436.4    0.07       0  4449.2   0.035       0
  4741.0    0.07       0  4991.2    0.07       0  4996.3    0.07       0
  5460.8   0.035       0  5937.8    0.07       0  6259.2    0.16       0
  6531.4    0.07       0
Bank Sta=4991.2,4996.3
Exp/Cntr=0.3,0.1

Type RM Length L Ch R = 1,36222,750,750,750
BEGIN DESCRIPTION:
NC Unknown Stream 01 44.0
END DESCRIPTION:
XS GIS Cut Line= 3
      1494705.00      6858388.00      1495805.00      6857888.00
      1497005.03      6856687.97
#Sta/Elev= 30
  3797.4 1866.39  3909.4 1863.85  4030.3 1863.73  4094.0 1861.99  4172.1 1861.99
  4371.3 1858.17  4481.4 1856.49  4549.9 1855.58  4772.8 1851.73  4840.9 1849.07
  4870.6 1850.10  4906.8 1848.78  4928.8 1850.83  4961.8 1851.21  4968.4 1848.87
  4981.1 1848.65  4981.5 1848.15  4986.4 1848.65  4991.4 1849.72  4996.9 1848.71
  5003.0 1851.03  5034.0 1851.45  5415.8 1852.47  5756.3 1856.44  5965.4 1859.91
  6024.7 1860.55  6209.9 1862.47  6512.3 1868.01  6592.4 1869.38  6702.8 1871.85
#Mann=13,-1,0
  3797.4   0.045       0  4172.1    0.07       0  4371.3   0.035       0
  4481.4    0.16       0  4549.9    0.07       0  4981.1    0.07       0
  4986.4    0.07       0  5756.3   0.035       0  5965.4    0.07       0
  6024.7   0.035       0  6209.9    0.07       0  6512.3   0.035       0
  6592.4    0.07       0
Bank Sta=4981.1,4986.4
Exp/Cntr=0.3,0.1

Type RM Length L Ch R = 1,35472,259,259,259
BEGIN DESCRIPTION:
Mapping XS 7a429b17
END DESCRIPTION:
XS GIS Cut Line= 4
      1494727.94      6858491.34      1495696.66      6858283.01
      1496811.24      6857803.85      1497919.77      6857142.89
#Sta/Elev= 30
  3549.7 1866.33  3734.0 1865.61  3822.5 1863.12  3852.7 1865.05  4155.7 1861.17
  4257.6 1859.44  4461.3 1855.81  4545.8 1854.16  4673.9 1851.79  4823.2 1849.56
  4930.6 1849.66  4985.0 1847.68  4998.9 1848.37  5004.1 1846.84  5004.6 1846.34
  5009.5 1846.84  5017.0 1849.23  5022.4 1847.71  5028.6 1849.47  5525.9 1850.10
  5812.3 1852.55  6000.1 1855.79  6117.3 1858.09  6234.6 1860.21  6268.7 1861.02
  6351.8 1862.18  6586.3 1864.37  6634.3 1864.90  6789.4 1865.79  7044.4 1870.26
#Mann=16,-1,0
  3549.7   0.045       0  3852.7    0.07       0  4155.7    0.16       0
  4257.6   0.035       0  4461.3    0.07       0  4545.8    0.16       0
  4673.9    0.07       0  5004.1    0.07       0  5009.5    0.07       0
  6000.1    0.16       0  6117.3    0.07       0  6234.6   0.035       0
  6268.7    0.07       0  6351.8    0.16       0  6586.3   0.035       0
  6634.3    0.07       0
Bank Sta=5004.1,5009.5
Exp/Cntr=0.3,0.1

Type RM Length L Ch R = 1,35213,1296,1296,1296
BEGIN DESCRIPTION:
Mapping XS 850467d7
END DESCRIPTION:
XS GIS Cut Line= 4
      1494696.52      6858601.74      1495576.87      6858413.22
      1498446.66      6857902.81      1499097.66      6857684.07
#Sta/Elev= 30
  3364.1 1866.91  3556.8 1866.36  3594.8 1864.74  3669.3 1867.50  4248.8 1858.62
  4451.3 1855.20  4506.5 1854.37  4796.0 1850.39  4922.7 1848.24  4993.8 1848.54
  5014.1 1847.81  5024.3 1846.10  5044.6 1848.02  5097.9 1848.60  5671.6 1845.92
  5672.0 1845.42  5677.0 1845.92  5719.2 1846.83  6224.5 1853.66  6389.5 1855.40
  6438.5 1856.18  6466.6 1854.99  6497.5 1856.63  6660.6 1857.95  6771.6 1858.94
  7212.2 1865.89  7301.5 1866.28  7427.6 1868.48  7495.9 1871.40  7866.0 1873.92
#Mann=13,-1,0
  3364.1   0.035       0  4248.8   0.063       0  4451.3    0.07       0
  4506.5   0.063       0  4796.0   0.035       0  5097.9   0.063       0
  5671.6   0.035       0  5677.0   0.063       0  5719.2   0.035       0
  6224.5    0.07       0  6389.5   0.035       0  6660.6    0.07       0
  6771.6   0.035       0
Bank Sta=5671.6,5677
Exp/Cntr=0.3,0.1

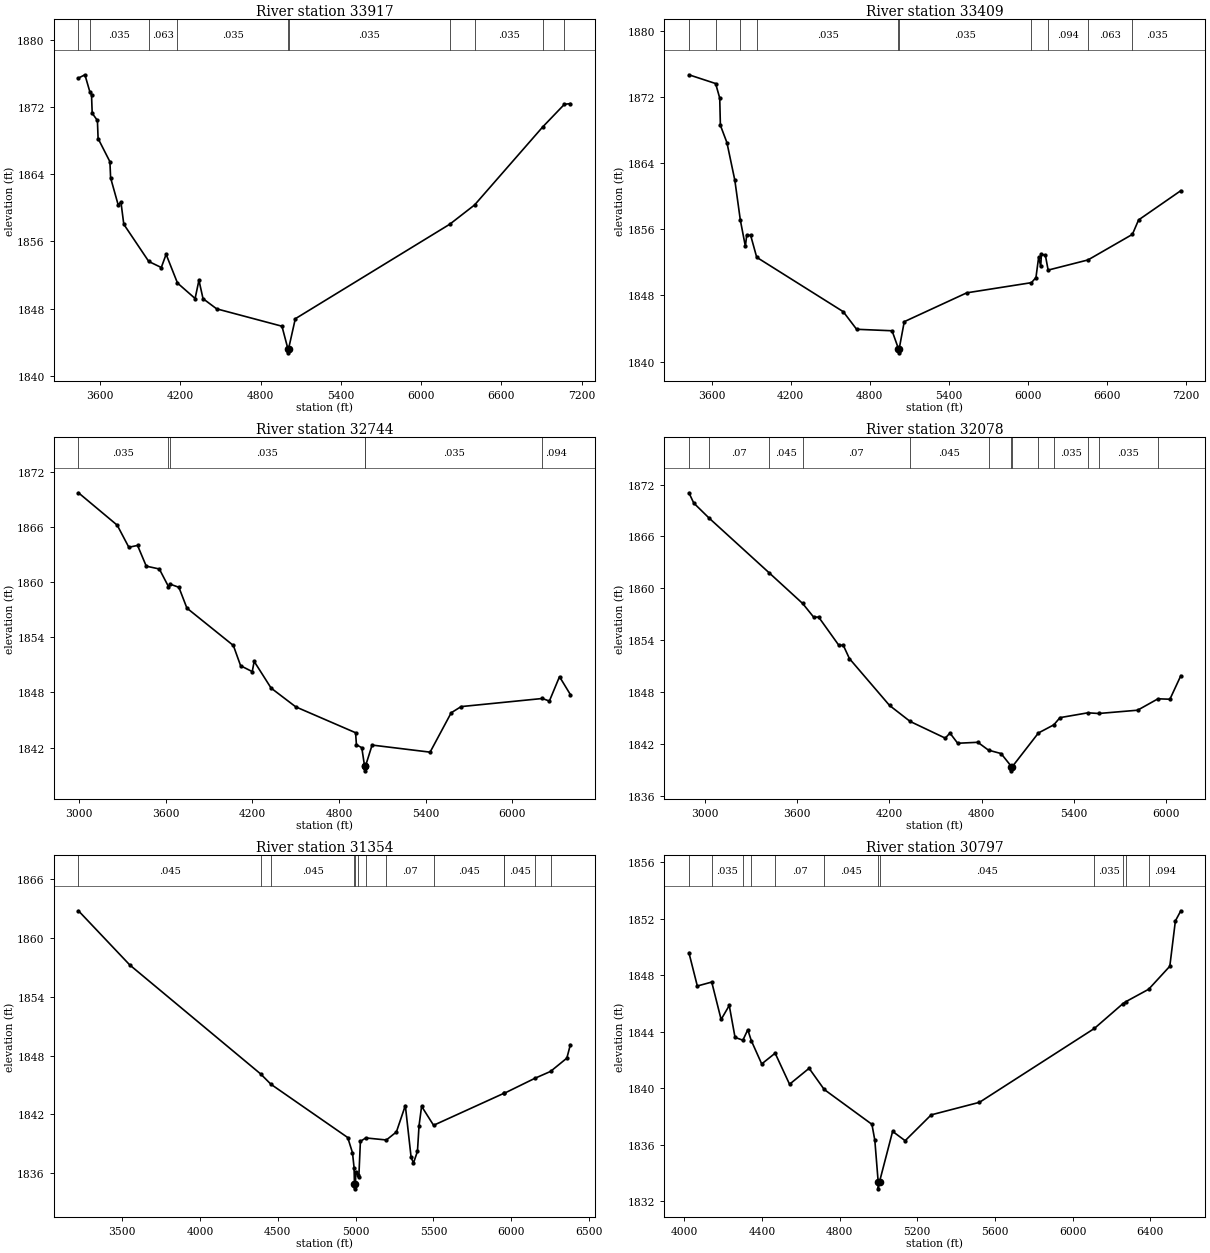
Type RM Length L Ch R = 1,33917,508,508,508
BEGIN DESCRIPTION:
Mapping XS 018e935d
END DESCRIPTION:
XS GIS Cut Line= 3
      1495524.71      6858773.60      1496373.74      6858590.31
      1499134.16      6858079.89
#Sta/Elev= 30
  3439.2 1875.46  3487.5 1875.85  3525.0 1873.79  3536.8 1873.50  3541.9 1871.27
  3580.9 1870.41  3586.0 1868.26  3674.3 1865.50  3679.5 1863.58  3736.2 1860.35
  3756.6 1860.71  3778.0 1858.05  3964.7 1853.62  4058.3 1852.90  4094.2 1854.47
  4179.3 1851.05  4311.0 1849.21  4339.6 1851.39  4370.1 1849.19  4471.8 1847.98
  4959.9 1845.91  5004.0 1843.24  5004.4 1842.74  5009.7 1843.24  5059.7 1846.80
  6214.4 1858.06  6399.4 1860.35  6909.0 1869.65  7070.3 1872.33  7115.0 1872.42
#Mann=10,-1,0
  3439.2   0.063       0  3525.0   0.035       0  3964.7   0.063       0
  4179.3   0.035       0  5004.0   0.035       0  5009.7   0.035       0
  6214.4   0.063       0  6399.4   0.035       0  6909.0   0.063       0
  7070.3   0.094       0
Bank Sta=5004,5009.7
Exp/Cntr=0.3,0.1

Type RM Length L Ch R = 1,33409,665,665,665
BEGIN DESCRIPTION:
Mapping XS 49f8a9a4
END DESCRIPTION:
XS GIS Cut Line= 6
      1495696.62      6858803.85      1496483.12      6858767.39
      1496806.04      6858793.43      1497654.99      6859001.76
      1498113.33      6859158.01      1499347.70      6859439.26
#Sta/Elev= 30
  3426.3 1874.70  3629.1 1873.64  3660.3 1871.88  3665.3 1868.59  3715.0 1866.49
  3775.1 1861.93  3816.7 1857.13  3855.1 1853.94  3865.2 1855.28  3895.2 1855.27
  3941.1 1852.62  4598.3 1846.04  4699.9 1843.91  4969.0 1843.73  5017.6 1841.56
  5018.1 1841.06  5023.4 1841.56  5061.7 1844.83  5536.4 1848.32  6027.7 1849.55
  6061.8 1850.17  6082.3 1852.63  6098.1 1851.52  6103.2 1853.01  6133.6 1852.84
  6154.4 1851.07  6457.1 1852.30  6794.1 1855.39  6841.3 1857.14  7162.0 1860.68
#Mann=10,-1,0
  3426.3   0.063       0  3629.1   0.035       0  3816.7   0.063       0
  3941.1   0.035       0  5017.6   0.035       0  5023.4   0.035       0
  6027.7   0.063       0  6154.4   0.094       0  6457.1   0.063       0
  6794.1   0.035       0
Bank Sta=5017.6,5023.4
Exp/Cntr=0.3,0.1

Type RM Length L Ch R = 1,32744,666,666,666
BEGIN DESCRIPTION:
Mapping XS e3f02934
END DESCRIPTION:
XS GIS Cut Line= 4
      1495227.93      6858986.14      1496951.87      6859152.81
      1498212.29      6859647.60      1498529.93      6859627.77
#Sta/Elev= 30
  2996.1 1869.69  3264.4 1866.17  3344.8 1863.77  3405.1 1863.97  3465.4 1861.72
  3555.8 1861.41  3619.1 1859.50  3631.3 1859.76  3691.2 1859.42  3746.7 1857.16
  4068.1 1853.10  4118.4 1850.90  4198.8 1850.26  4212.2 1851.37  4329.4 1848.47
  4500.2 1846.43  4914.1 1843.62  4919.8 1842.32  4957.0 1841.99  4976.4 1839.98
  4976.9 1839.48  4982.4 1839.98  5028.3 1842.28  5429.7 1841.51  5575.9 1845.79
  5644.6 1846.46  6206.8 1847.34  6255.2 1847.06  6325.3 1849.71  6400.4 1847.77
#Mann=6,-1,0
  2996.1   0.035       0  3619.1    0.07       0  3631.3   0.035       0
  4976.4   0.035       0  4982.4   0.035       0  6206.8   0.094       0
Bank Sta=4976.4,4982.4
Exp/Cntr=0.3,0.1

Type RM Length L Ch R = 1,32078,724,724,724
BEGIN DESCRIPTION:
Mapping XS a001a257
END DESCRIPTION:
XS GIS Cut Line= 5
      1495493.50      6859980.93      1496863.33      6859866.35
      1497967.49      6859720.51      1498222.70      6859767.39
      1498675.79      6859736.14
#Sta/Elev= 30
  2894.5 1871.05  2926.1 1869.86  3025.5 1868.13  3417.8 1861.78  3634.9 1858.25
  3706.6 1856.67  3738.9 1856.68  3869.4 1853.44  3899.5 1853.41  3939.6 1851.87
  4200.5 1846.46  4334.7 1844.61  4563.3 1842.68  4593.6 1843.27  4644.0 1842.09
  4775.1 1842.20  4844.7 1841.29  4926.4 1840.90  4993.8 1839.40  4994.3 1838.90
  5000.2 1839.40  5169.7 1843.28  5269.9 1844.22  5309.7 1845.05  5491.7 1845.61
  5561.5 1845.53  5815.0 1845.91  5948.0 1847.23  6025.5 1847.18  6096.5 1849.90
#Mann=13,-1,0
  2894.5   0.045       0  3025.5    0.07       0  3417.8   0.045       0
  3634.9    0.07       0  4334.7   0.045       0  4844.7    0.07       0
  4993.8    0.07       0  5000.2    0.07       0  5169.7   0.045       0
  5269.9   0.035       0  5491.7   0.045       0  5561.5   0.035       0
  5948.0   0.094       0
Bank Sta=4993.8,5000.2
Exp/Cntr=0.3,0.1

Type RM Length L Ch R = 1,31354,557,557,557
BEGIN DESCRIPTION:
Mapping XS a1f2a236
END DESCRIPTION:
XS GIS Cut Line= 3
      1495805.96      6860674.64      1497998.65      6860257.98
      1498816.35      6859820.49
#Sta/Elev= 30
  3219.7 1862.79  3549.7 1857.25  4389.5 1846.13  4456.0 1845.07  4949.1 1839.63
  4979.7 1838.08  4989.9 1836.56  4992.3 1834.89  4992.8 1834.39  4998.9 1834.89
  5000.7 1836.07  5016.8 1835.79  5020.4 1835.59  5030.6 1839.24  5065.0 1839.59
  5197.4 1839.38  5261.8 1840.20  5319.1 1842.90  5356.3 1837.60  5371.4 1837.02
  5397.0 1838.22  5407.2 1840.84  5423.6 1842.82  5500.6 1840.88  5953.8 1844.16
  5954.9 1844.15  6152.4 1845.69  6251.6 1846.38  6356.5 1847.74  6379.0 1849.11
#Mann=13,-1,0
  3219.7   0.045       0  4389.5    0.07       0  4456.0   0.045       0
  4992.3   0.045       0  4998.9   0.045       0  5016.8    0.07       0
  5065.0   0.045       0  5197.4    0.07       0  5500.6   0.045       0
  5953.8   0.035       0  5954.9   0.045       0  6152.4   0.035       0
  6251.6   0.094       0
Bank Sta=4992.3,4998.9
Exp/Cntr=0.3,0.1

Type RM Length L Ch R = 1,30797,495,495,495
BEGIN DESCRIPTION:
NC Unknown Stream 01 38.0
END DESCRIPTION:
XS GIS Cut Line= 3
      1496955.00      6861388.00      1497755.00      6860838.00
      1498955.02      6859837.98
#Sta/Elev= 30
  4024.6 1849.60  4067.9 1847.24  4142.1 1847.52  4190.4 1844.87  4232.3 1845.86
  4262.1 1843.60  4302.4 1843.40  4327.7 1844.14  4346.1 1843.36  4399.4 1841.72
  4468.6 1842.48  4542.8 1840.28  4643.5 1841.41  4721.2 1839.91  4967.0 1837.44
  4981.9 1836.31  4999.1 1833.37  4999.6 1832.87  5006.0 1833.37  5073.5 1836.94
  5138.0 1836.28  5272.0 1838.11  5520.7 1839.00  6112.1 1844.23  6260.2 1846.00
  6275.7 1846.14  6391.9 1847.01  6500.8 1848.64  6529.5 1851.85  6557.5 1852.57
#Mann=12,-1,0
  4024.6    0.07       0  4142.1   0.035       0  4302.4    0.07       0
  4346.1   0.035       0  4468.6    0.07       0  4721.2   0.045       0
  4999.1   0.045       0  5006.0   0.045       0  6112.1   0.035       0
  6260.2   0.045       0  6275.7   0.035       0  6391.9   0.094       0
Bank Sta=4999.1,5006
Exp/Cntr=0.3,0.1