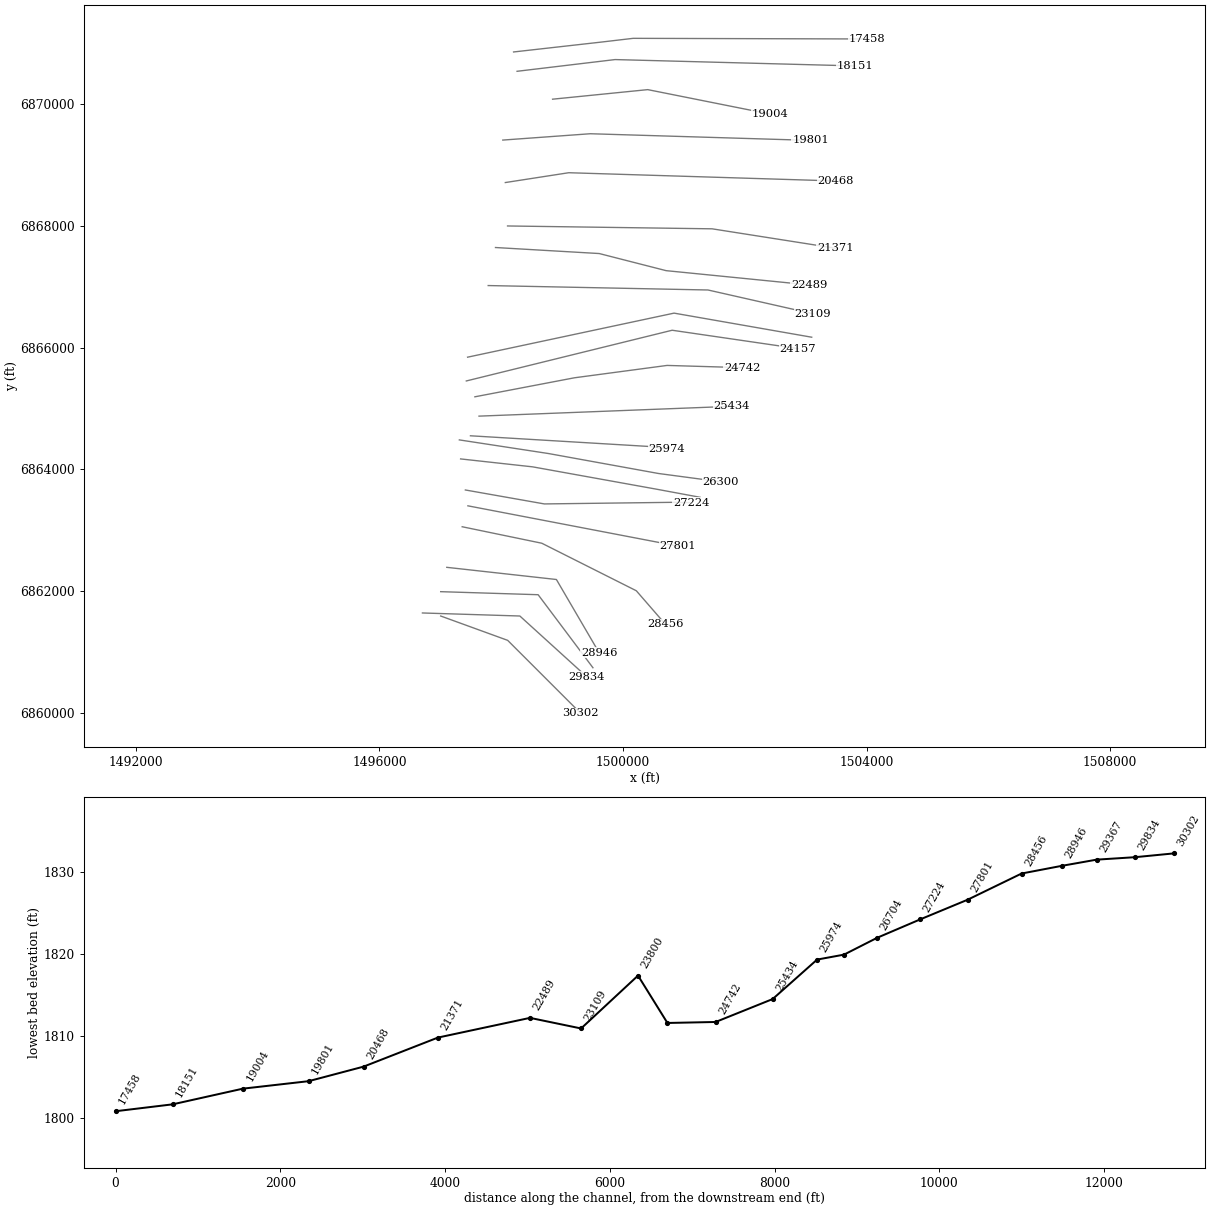
HEC-RAS study NC Unknown Stream 01.prj: NC Unknown Stream 01 Base Level Engineering

--- NC Unknown Stream 01.g01 (geometry) --- (continued)

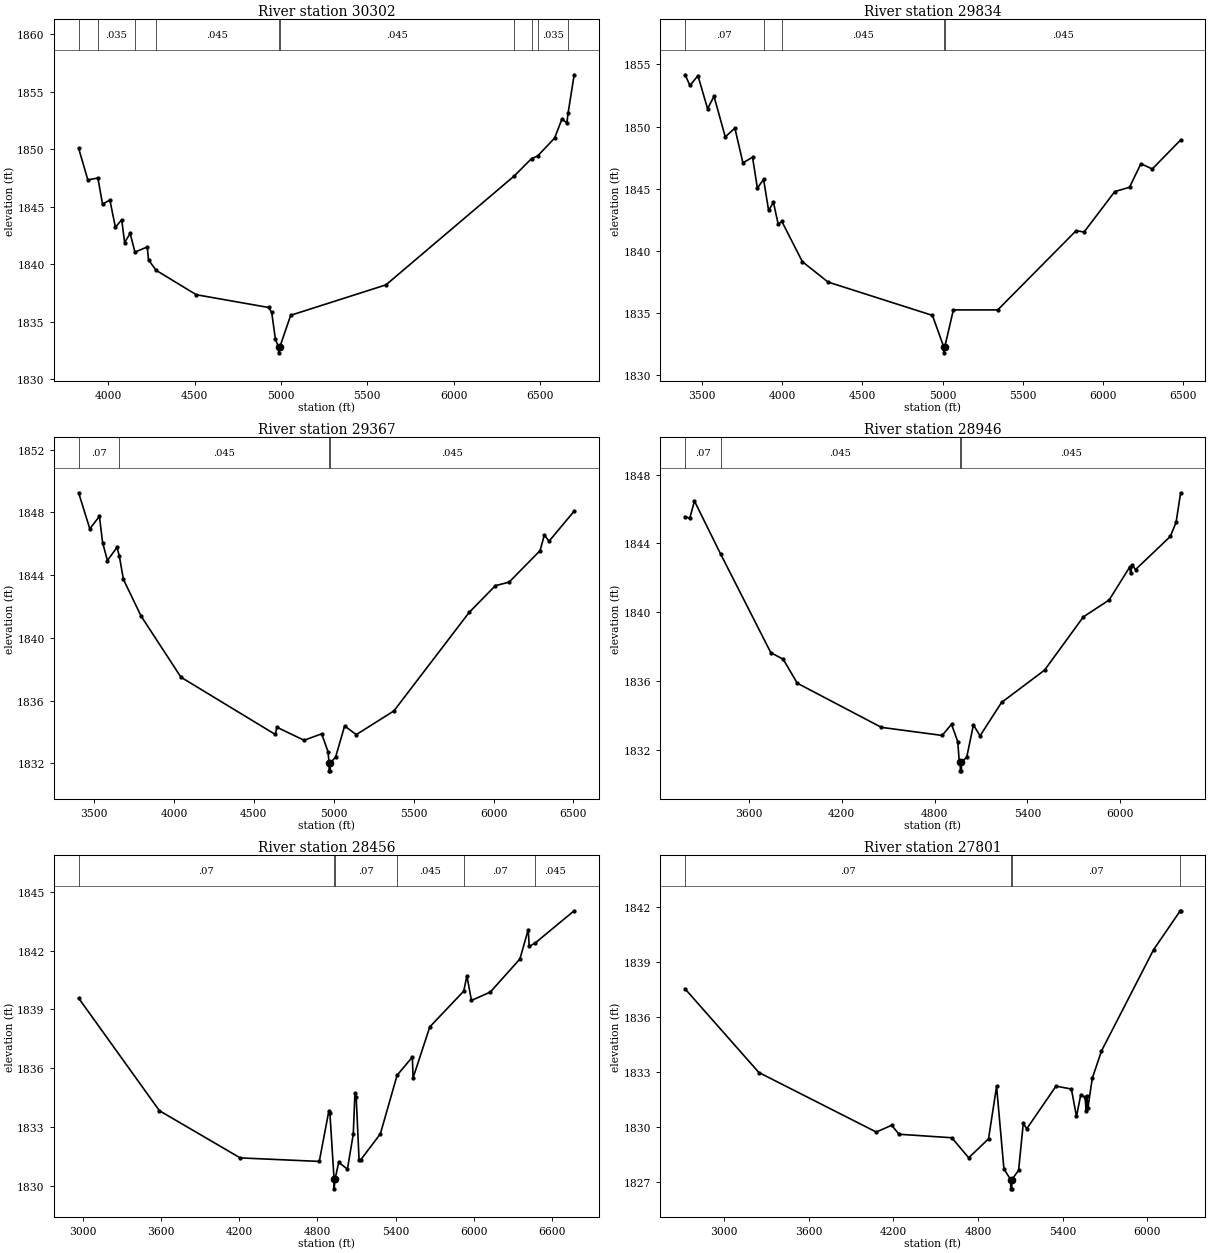
Type RM Length L Ch R = 1,30302,468,468,468
BEGIN DESCRIPTION:
NC Unknown Stream 01 37.0
END DESCRIPTION:
XS GIS Cut Line= 3
      1497004.99      6861588.01      1498105.00      6861188.00
      1499304.97      6859988.03
#Sta/Elev= 30
  3829.3 1850.09  3882.5 1847.34  3940.7 1847.50  3967.6 1845.23  4010.2 1845.58
  4042.1 1843.21  4078.7 1843.87  4095.3 1841.88  4127.3 1842.68  4155.2 1841.05
  4226.3 1841.50  4233.7 1840.37  4278.2 1839.46  4510.3 1837.34  4928.6 1836.23
  4946.6 1835.80  4967.9 1833.47  4986.3 1832.78  4986.8 1832.28  4993.4 1832.78
  5056.4 1835.55  5607.9 1838.20  6350.0 1847.68  6450.0 1849.19  6484.7 1849.41
  6583.7 1850.98  6626.1 1852.64  6654.4 1852.30  6662.1 1853.20  6696.8 1856.49
#Mann=10,-1,0
  3829.3    0.07       0  3940.7   0.035       0  4155.2    0.07       0
  4278.2   0.045       0  4986.3   0.045       0  4993.4   0.045       0
  6350.0   0.035       0  6450.0   0.045       0  6484.7   0.035       0
  6662.1   0.094       0
Bank Sta=4986.3,4993.4
Exp/Cntr=0.3,0.1

Type RM Length L Ch R = 1,29834,467,467,467
BEGIN DESCRIPTION:
NC Unknown Stream 01 36.0
END DESCRIPTION:
XS GIS Cut Line= 3
      1496704.96      6861638.00      1498305.00      6861588.00
      1499404.98      6860588.02
#Sta/Elev= 30
  3394.9 1854.17  3425.0 1853.31  3475.0 1854.10  3535.0 1851.44  3575.0 1852.44
  3645.1 1849.18  3705.1 1849.88  3755.1 1847.09  3815.1 1847.54  3845.2 1845.06
  3883.9 1845.76  3915.2 1843.27  3945.2 1843.92  3975.2 1842.15  3997.4 1842.39
  4125.3 1839.15  4285.4 1837.51  4935.7 1834.83  5005.8 1832.32  5006.3 1831.82
  5013.3 1832.32  5066.3 1835.27  5342.7 1835.27  5831.3 1841.64  5880.6 1841.53
  6071.8 1844.78  6163.7 1845.13  6234.7 1847.02  6305.6 1846.60  6482.3 1848.93
#Mann=5,-1,0
  3394.9    0.07       0  3883.9   0.035       0  3997.4   0.045       0
  5005.8   0.045       0  5013.3   0.045       0
Bank Sta=5005.8,5013.3
Exp/Cntr=0.3,0.1

Type RM Length L Ch R = 1,29367,421,421,421
BEGIN DESCRIPTION:
NC Unknown Stream 01 35.0
END DESCRIPTION:
XS GIS Cut Line= 3
      1497004.99      6861988.00      1498605.00      6861938.00
      1499505.00      6860738.00
#Sta/Elev= 30
  3403.9 1849.25  3473.9 1846.95  3534.0 1847.75  3554.0 1846.07  3584.0 1844.93
  3644.0 1845.77  3658.6 1845.21  3684.1 1843.73  3794.1 1841.40  4044.2 1837.49
  4634.5 1833.84  4644.5 1834.30  4814.6 1833.47  4924.7 1833.88  4964.7 1832.73
  4970.9 1832.02  4971.4 1831.52  4977.9 1831.52  4978.4 1832.02  5012.0 1832.40
  5068.2 1834.38  5141.2 1833.83  5376.6 1835.34  5847.4 1841.62  6012.0 1843.33
  6097.4 1843.55  6291.2 1845.56  6318.2 1846.56  6347.4 1846.16  6504.7 1848.08
#Mann=4,-1,0
  3403.9    0.07       0  3658.6   0.045       0  4970.9   0.045       0
  4978.4   0.045       0
Bank Sta=4970.9,4978.4
Exp/Cntr=0.3,0.1

Type RM Length L Ch R = 1,28946,490,490,490
BEGIN DESCRIPTION:
NC Unknown Stream 01 34.0
END DESCRIPTION:
XS GIS Cut Line= 3
      1497104.96      6862388.00      1498905.00      6862188.00
      1499605.02      6860987.97
#Sta/Elev= 30
  3188.9 1845.56  3219.1 1845.47  3249.3 1846.47  3417.6 1843.40  3742.3 1837.65
  3822.8 1837.26  3913.4 1835.87  4456.7 1833.30  4849.1 1832.83  4909.5 1833.48
  4949.7 1832.47  4959.8 1831.29  4966.0 1831.27  4966.5 1830.77  4973.2 1830.77
  4973.7 1831.27  5007.9 1831.57  5050.9 1833.44  5093.9 1832.81  5232.8 1834.75
  5510.6 1836.63  5761.2 1839.73  5927.4 1840.71  6060.6 1842.63  6066.3 1842.26
  6076.3 1842.75  6097.8 1842.48  6322.7 1844.41  6359.9 1845.23  6389.3 1846.95
#Mann=4,-1,0
  3188.9    0.07       0  3417.6   0.045       0  4966.0   0.045       0
  4973.7   0.045       0
Bank Sta=4966,4973.7
Exp/Cntr=0.3,0.1

Type RM Length L Ch R = 1,28456,655,655,655
BEGIN DESCRIPTION:
Mapping XS 49c2781b
END DESCRIPTION:
XS GIS Cut Line= 4
      1497357.99      6863054.86      1498665.32      6862784.02
      1500217.40      6862002.77      1500695.56      6861451.85
#Sta/Elev= 30
  2968.0 1839.57  3587.9 1833.82  4207.7 1831.41  4814.5 1831.23  4887.1 1833.78
  4896.1 1833.68  4927.8 1830.33  4928.3 1829.83  4935.7 1830.33  4963.3 1831.18
  5030.4 1830.84  5075.2 1832.62  5087.9 1834.70  5097.6 1834.52  5120.0 1831.28
  5132.5 1831.31  5283.2 1832.64  5411.5 1835.63  5528.6 1836.56  5534.2 1835.50
  5662.5 1838.10  5923.2 1839.93  5947.1 1840.71  5982.0 1839.45  6127.0 1839.88
  6354.0 1841.57  6417.8 1843.07  6425.2 1842.21  6472.1 1842.39  6770.2 1844.03
#Mann=6,-1,0
  2968.0    0.07       0  4927.8    0.07       0  4935.7    0.07       0
  5411.5   0.045       0  5923.2    0.07       0  6472.1   0.045       0
Bank Sta=4927.8,4935.7
Exp/Cntr=0.3,0.1

Type RM Length L Ch R = 1,27801,577,577,577
BEGIN DESCRIPTION:
Mapping XS 11d46aea
END DESCRIPTION:
XS GIS Cut Line= 2
      1497451.80      6863398.60      1500899.73      6862737.14
#Sta/Elev= 30
  2724.2 1837.52  3246.8 1832.97  4078.7 1829.73  4187.8 1830.10  4239.8 1829.61
  4613.9 1829.42  4733.4 1828.33  4873.9 1829.36  4931.0 1832.21  4983.0 1827.72
  5031.0 1827.14  5031.5 1826.64  5038.5 1826.64  5039.0 1827.14  5087.0 1827.65
  5120.3 1830.22  5144.1 1829.90  5352.0 1832.23  5461.1 1832.07  5497.1 1830.58
  5527.6 1831.77  5558.2 1831.62  5565.1 1830.90  5570.2 1831.69  5578.5 1831.06
  5609.1 1832.66  5674.2 1834.14  6043.2 1839.65  6232.2 1841.77  6235.0 1841.77
#Mann=4,-1,0
  2724.2    0.07       0  5031.0    0.07       0  5039.0    0.07       0
  6232.2   0.035       0
Bank Sta=5031,5039
Exp/Cntr=0.3,0.1

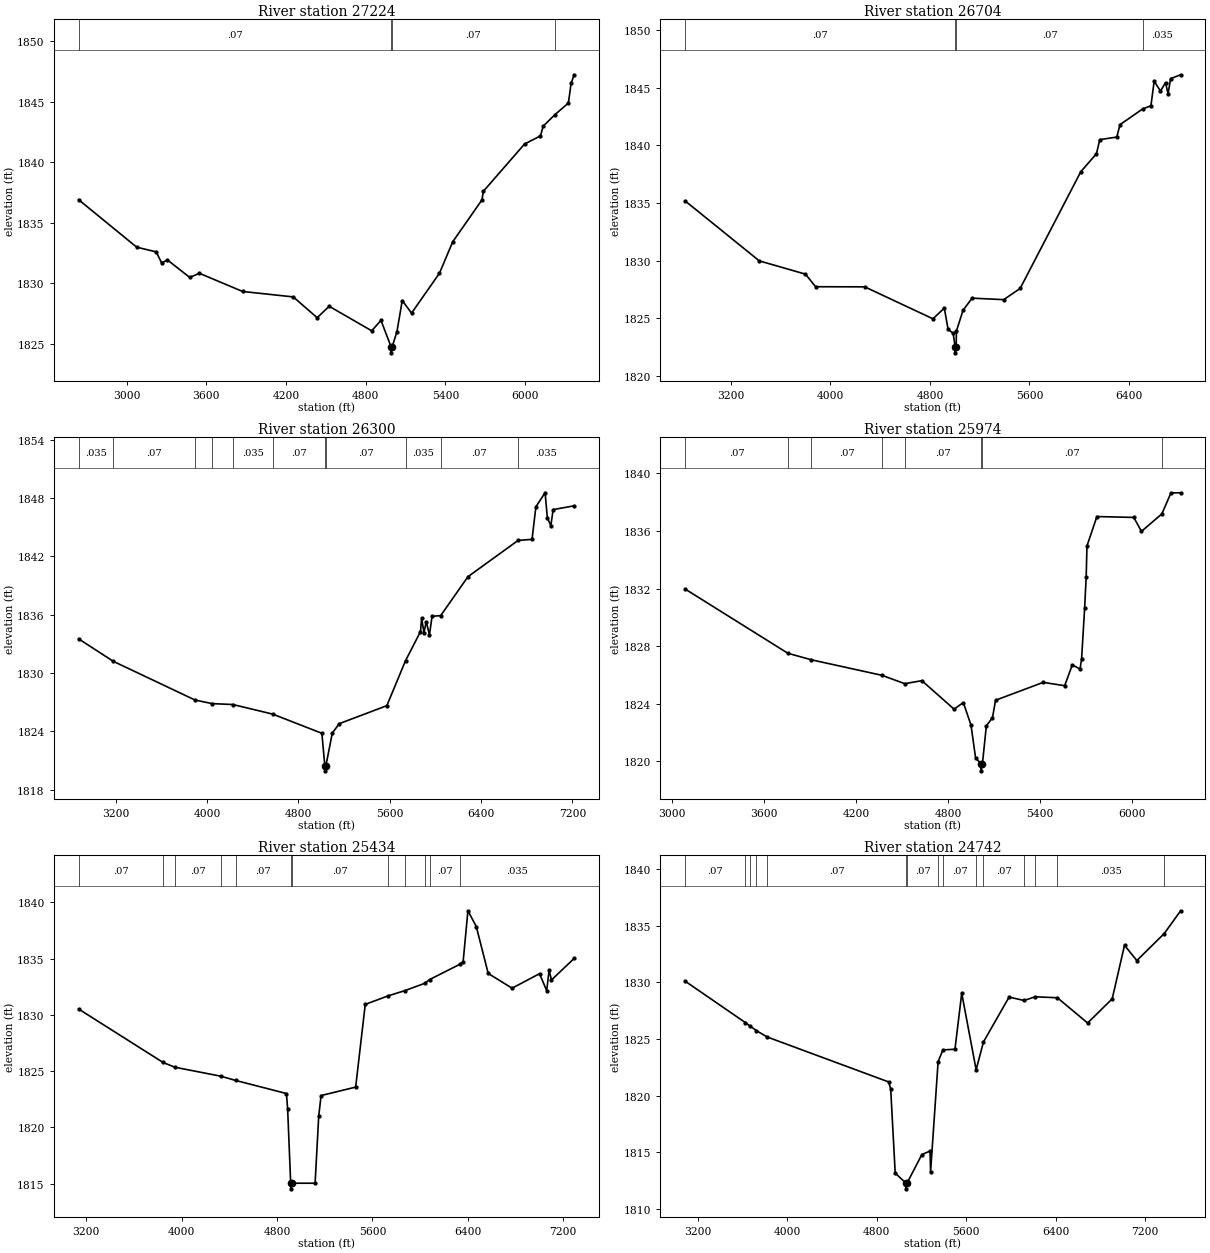
Type RM Length L Ch R = 1,27224,520,520,520
BEGIN DESCRIPTION:
Mapping XS a53f3ba9
END DESCRIPTION:
XS GIS Cut Line= 4
      1497410.14      6863659.02      1498706.99      6863429.86
      1500790.32      6863455.90      1501118.44      6863450.69
#Sta/Elev= 30
  2639.6 1836.89  3076.3 1832.97  3223.4 1832.58  3264.0 1831.67  3308.0 1831.91
  3475.4 1830.47  3548.3 1830.81  3873.3 1829.31  4254.6 1828.86  4434.6 1827.14
  4524.6 1828.09  4844.6 1826.06  4914.6 1826.92  4990.4 1824.74  4990.9 1824.24
  4998.9 1824.74  5034.6 1825.99  5074.6 1828.56  5144.6 1827.52  5354.7 1830.82
  5454.7 1833.42  5674.7 1836.88  5684.7 1837.58  5994.7 1841.49  6114.7 1842.16
  6134.7 1842.96  6220.9 1843.89  6324.8 1844.88  6344.8 1846.49  6368.2 1847.21
#Mann=4,-1,0
  2639.6    0.07       0  4990.4    0.07       0  4998.9    0.07       0
  6220.9   0.035       0
Bank Sta=4990.4,4998.9
Exp/Cntr=0.3,0.1

Type RM Length L Ch R = 1,26704,404,404,404
BEGIN DESCRIPTION:
Mapping XS 35c9cc80
END DESCRIPTION:
XS GIS Cut Line= 4
      1497332.02      6864169.44      1498514.28      6864039.23
      1500535.11      6863674.65      1501264.28      6863539.23
#Sta/Elev= 30
  2831.0 1835.18  3427.6 1829.98  3799.0 1828.83  3880.3 1827.74  4275.2 1827.73
  4823.9 1824.96  4915.3 1825.89  4945.8 1824.04  4986.5 1823.71  5002.5 1822.51
  5003.0 1822.01  5011.1 1822.51  5012.4 1823.89  5066.0 1825.70  5138.9 1826.75
  5392.9 1826.62  5525.0 1827.59  6012.8 1837.71  6138.8 1839.27  6165.3 1840.49
  6302.3 1840.71  6328.0 1841.79  6510.3 1843.15  6576.5 1843.42  6602.6 1845.55
  6653.5 1844.70  6694.2 1845.43  6714.5 1844.46  6734.9 1845.78  6815.5 1846.11
#Mann=4,-1,0
  2831.0    0.07       0  5002.5    0.07       0  5011.1    0.07       0
  6510.3   0.035       0
Bank Sta=5002.5,5011.1
Exp/Cntr=0.3,0.1

Type RM Length L Ch R = 1,26300,326,326,326
BEGIN DESCRIPTION:
Mapping XS 51c4c280
END DESCRIPTION:
XS GIS Cut Line= 4
      1497311.18      6864481.94      1498774.70      6864257.98
      1500581.99      6863929.86      1501597.61      6863794.44
#Sta/Elev= 30
  2873.9 1833.52  3177.6 1831.21  3894.0 1827.23  4045.3 1826.86  4224.9 1826.77
  4575.0 1825.78  5005.2 1823.81  5031.3 1820.45  5031.8 1819.95  5040.1 1820.45
  5096.7 1823.84  5157.7 1824.80  5574.4 1826.65  5738.0 1831.27  5869.1 1834.26
  5879.3 1835.62  5899.6 1834.17  5919.9 1835.29  5947.6 1833.92  5970.8 1835.84
  6046.3 1835.91  6285.1 1839.91  6724.4 1843.64  6846.8 1843.75  6880.3 1847.10
  6961.1 1848.54  6981.2 1845.95  7011.5 1845.16  7031.7 1846.81  7215.9 1847.20
#Mann=11,-1,0
  2873.9   0.035       0  3177.6    0.07       0  3894.0   0.035       0
  4045.3    0.07       0  4224.9   0.035       0  4575.0    0.07       0
  5031.3    0.07       0  5040.1    0.07       0  5738.0   0.035       0
  6046.3    0.07       0  6724.4   0.035       0
Bank Sta=5031.3,5040.1
Exp/Cntr=0.3,0.1

Type RM Length L Ch R = 1,25974,540,540,540
BEGIN DESCRIPTION:
Mapping XS 0ea93222
END DESCRIPTION:
XS GIS Cut Line= 3
      1497493.41      6864549.65      1500451.78      6864372.56
      1500717.37      6864330.90
#Sta/Elev= 30
  3085.1 1831.97  3755.4 1827.51  3907.8 1827.06  4369.1 1825.98  4518.2 1825.40
  4629.4 1825.61  4839.8 1823.63  4899.9 1824.09  4950.0 1822.53  4980.1 1820.24
  5015.5 1819.85  5016.0 1819.35  5024.7 1819.85  5050.2 1822.47  5090.3 1823.04
  5110.3 1824.25  5420.9 1825.49  5561.1 1825.26  5611.2 1826.71  5661.3 1826.41
  5671.3 1827.08  5691.3 1830.64  5701.4 1832.80  5706.6 1834.96  5771.5 1837.00
  6011.9 1836.94  6062.1 1835.97  6194.7 1837.18  6254.5 1838.64  6317.6 1838.65
#Mann=8,-1,0
  3085.1    0.07       0  3755.4   0.035       0  3907.8    0.07       0
  4369.1   0.035       0  4518.2    0.07       0  5015.5    0.07       0
  5024.7    0.07       0  6194.7   0.035       0
Bank Sta=5015.5,5024.7
Exp/Cntr=0.3,0.1

Type RM Length L Ch R = 1,25434,692,692,692
BEGIN DESCRIPTION:
Mapping XS a8e21564
END DESCRIPTION:
XS GIS Cut Line= 2
      1497634.03      6864872.56      1501785.09      6865034.02
#Sta/Elev= 30
  3137.3 1830.52  3843.7 1825.78  3942.4 1825.35  4329.4 1824.55  4454.6 1824.17
  4879.6 1823.01  4889.6 1821.61  4915.0 1815.04  4915.5 1814.54  4924.3 1815.04
  5119.8 1815.04  5149.8 1820.99  5169.8 1822.83  5459.6 1823.58  5540.1 1830.93
  5728.9 1831.68  5871.3 1832.15  6040.5 1832.81  6079.9 1833.14  6332.2 1834.49
  6360.7 1834.73  6400.7 1839.25  6470.8 1837.85  6570.9 1833.68  6771.0 1832.37
  7001.2 1833.66  7061.2 1832.15  7081.2 1833.97  7101.3 1833.10  7291.5 1835.02
#Mann=12,-1,0
  3137.3    0.07       0  3843.7   0.035       0  3942.4    0.07       0
  4329.4   0.035       0  4454.6    0.07       0  4915.0    0.07       0
  4924.3    0.07       0  5728.9   0.035       0  5871.3    0.07       0
  6040.5   0.035       0  6079.9    0.07       0  6332.2   0.035       0
Bank Sta=4915,4924.3
Exp/Cntr=0.3,0.1

Type RM Length L Ch R = 1,24742,585,585,585
BEGIN DESCRIPTION:
Mapping XS ebefa1e4
END DESCRIPTION:
XS GIS Cut Line= 4
      1497566.38      6865190.28      1499201.78      6865502.77
      1500722.61      6865705.90      1501956.95      6865669.44
#Sta/Elev= 30
  3085.4 1830.11  3625.5 1826.44  3667.4 1826.13  3723.1 1825.74  3818.3 1825.18
  4906.6 1821.20  4925.1 1820.59  4965.5 1813.14  5061.7 1812.25  5062.2 1811.75
  5071.0 1812.25  5204.0 1814.78  5277.0 1815.09  5282.1 1813.26  5349.5 1823.00
  5392.4 1824.03  5500.2 1824.09  5560.7 1829.04  5689.7 1822.28  5755.4 1824.74
  5984.5 1828.70  6118.8 1828.40  6218.3 1828.73  6416.8 1828.64  6687.3 1826.41
  6907.4 1828.55  7017.4 1833.28  7127.5 1831.93  7372.2 1834.31  7519.6 1836.33
#Mann=15,-1,0
  3085.4    0.07       0  3625.5   0.035       0  3667.4    0.07       0
  3723.1   0.035       0  3818.3    0.07       0  5061.7    0.07       0
  5071.0    0.07       0  5349.5   0.035       0  5392.4    0.07       0
  5689.7   0.035       0  5755.4    0.07       0  6118.8   0.035       0
  6218.3    0.07       0  6416.8   0.035       0  7372.2    0.07       0
Bank Sta=5061.7,5071
Exp/Cntr=0.3,0.1

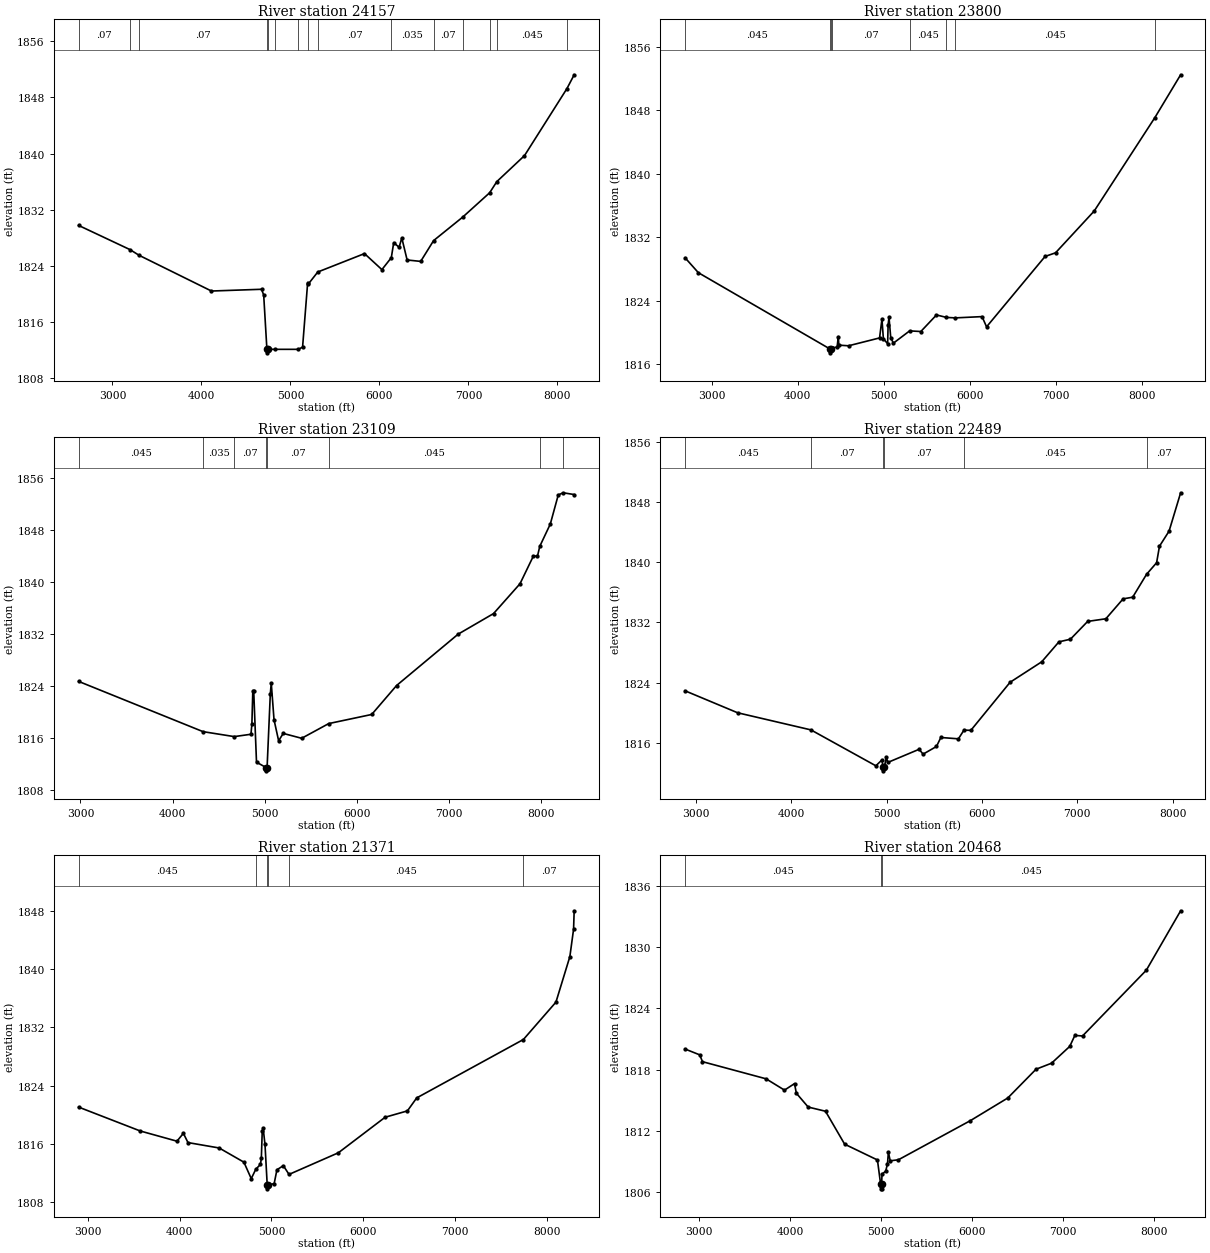
Type RM Length L Ch R = 1,24157,357,357,357
BEGIN DESCRIPTION:
Mapping XS d0b958a7
END DESCRIPTION:
XS GIS Cut Line= 3
      1497425.70      6865450.68      1500805.95      6866284.02
      1502871.86      6865982.20
#Sta/Elev= 30
  2619.4 1829.77  3197.7 1826.32  3298.5 1825.52  4112.1 1820.43  4674.8 1820.68
  4699.2 1819.87  4735.4 1812.13  4735.9 1811.63  4745.4 1812.13  4821.0 1812.13
  5087.6 1812.13  5136.3 1812.44  5193.5 1821.64  5201.6 1821.44  5307.1 1823.14
  5832.1 1825.76  6027.8 1823.48  6133.6 1825.18  6160.5 1827.32  6221.2 1826.66
  6251.5 1827.99  6311.3 1824.85  6463.7 1824.65  6608.8 1827.61  6937.3 1830.97
  7238.7 1834.42  7319.5 1836.01  7630.4 1839.71  8107.2 1849.25  8188.7 1851.22
#Mann=15,-1,0
  2619.4    0.07       0  3197.7   0.035       0  3298.5    0.07       0
  4735.4   0.033       0  4745.4    0.07       0  4821.0   0.033       0
  5087.6    0.07       0  5201.6   0.035       0  5307.1    0.07       0
  6133.6   0.035       0  6608.8    0.07       0  6937.3   0.035       0
  7238.7    0.07       0  7319.5   0.045       0  8107.2    0.07       0
Bank Sta=4735.4,4745.4
Exp/Cntr=0.3,0.1

Type RM Length L Ch R = 1,23800,691,691,691
BEGIN DESCRIPTION:
Mapping XS e48827ce
END DESCRIPTION:
XS GIS Cut Line= 3
      1497446.56      6865841.31      1500837.20      6866565.27
      1503097.64      6866169.44
#Sta/Elev= 30
  2690.8 1829.39  2845.1 1827.51  4373.3 1817.90  4373.8 1817.40  4383.3 1817.90
  4396.7 1818.06  4458.2 1818.10  4472.2 1819.46  4478.7 1818.37  4591.1 1818.29
  4951.9 1819.28  4979.7 1821.65  4996.3 1819.19  5045.8 1818.54  5051.3 1820.90
  5061.5 1821.90  5081.9 1819.33  5112.6 1818.62  5301.7 1820.17  5431.7 1820.09
  5613.7 1822.18  5729.7 1821.87  5832.8 1821.81  6143.6 1821.97  6196.2 1820.68
  6876.4 1829.56  6998.3 1830.02  7448.3 1835.30  8153.8 1847.09  8452.7 1852.48
#Mann=8,-1,0
  2690.8   0.045       0  4373.3    0.07       0  4383.3   0.045       0
  4396.7    0.07       0  5301.7   0.045       0  5729.7    0.07       0
  5832.8   0.045       0  8153.8    0.07       0
Bank Sta=4373.3,4383.3
Exp/Cntr=0.3,0.1

Type RM Length L Ch R = 1,23109,620,620,620
BEGIN DESCRIPTION:
Mapping XS 48421d94
END DESCRIPTION:
XS GIS Cut Line= 3
      1497785.08      6867018.40      1501394.49      6866945.48
      1503118.44      6866554.86
#Sta/Elev= 30
  2980.6 1824.70  4330.9 1816.98  4669.4 1816.22  4850.9 1816.58  4860.9 1818.16
  4870.9 1823.29  4880.9 1823.15  4910.9 1812.29  5015.9 1811.46  5016.4 1810.96
  5025.9 1811.46  5060.9 1822.80  5071.0 1824.45  5101.0 1818.82  5151.0 1815.58
  5201.0 1816.71  5401.0 1815.96  5694.6 1818.22  6161.2 1819.62  6431.2 1824.07
  7099.3 1831.96  7483.3 1835.12  7770.4 1839.70  7916.7 1843.99  7959.8 1843.92
  7985.0 1845.45  8099.5 1848.88  8185.7 1853.35  8239.1 1853.68  8358.4 1853.41
#Mann=8,-1,0
  2980.6   0.045       0  4330.9   0.035       0  4669.4    0.07       0
  5015.9    0.07       0  5025.9    0.07       0  5694.6   0.045       0
  7985.0    0.07       0  8239.1   0.035       0
Bank Sta=5015.9,5025.9
Exp/Cntr=0.3,0.1

Type RM Length L Ch R = 1,22489,1118,1118,1118
BEGIN DESCRIPTION:
Mapping XS 1f913990
END DESCRIPTION:
XS GIS Cut Line= 4
      1497904.91      6867643.40      1499608.03      6867544.44
      1500706.99      6867263.19      1503055.96      6867028.81
#Sta/Elev= 30
  2884.3 1822.90  3435.3 1819.98  4204.9 1817.70  4886.5 1812.92  4948.4 1813.68
  4963.4 1812.75  4963.9 1812.25  4974.8 1812.75  4997.2 1814.05  5010.4 1813.36
  5340.7 1815.12  5382.0 1814.47  5522.5 1815.49  5568.5 1816.69  5752.8 1816.51
  5811.1 1817.67  5883.5 1817.64  6295.5 1824.04  6627.1 1826.76  6808.0 1829.42
  6928.6 1829.77  7109.5 1832.14  7300.5 1832.49  7481.4 1835.14  7581.9 1835.36
  7727.1 1838.40  7833.1 1839.95  7863.2 1842.15  7963.7 1844.15  8085.3 1849.26
#Mann=6,-1,0
  2884.3   0.045       0  4204.9    0.07       0  4963.4    0.07       0
  4974.8    0.07       0  5811.1   0.045       0  7727.1    0.07       0
Bank Sta=4963.4,4974.8
Exp/Cntr=0.3,0.1

Type RM Length L Ch R = 1,21371,903,903,903
BEGIN DESCRIPTION:
Mapping XS 111d7dfd
END DESCRIPTION:
XS GIS Cut Line= 3
      1498102.85      6867997.56      1501462.20      6867950.69
      1503481.42      6867633.23
#Sta/Elev= 30
  2897.9 1821.07  3570.1 1817.79  3970.2 1816.39  4040.2 1817.47  4090.2 1816.20
  4430.2 1815.46  4700.2 1813.51  4780.2 1811.25  4829.4 1812.53  4880.2 1813.20
  4890.2 1814.02  4900.2 1817.80  4910.2 1818.14  4930.2 1815.94  4954.5 1810.35
  4955.0 1809.85  4966.1 1810.35  5030.3 1810.58  5060.3 1812.47  5130.3 1813.03
  5192.2 1811.83  5730.3 1814.80  6240.4 1819.68  6483.1 1820.55  6584.3 1822.33
  7747.9 1830.35  8102.8 1835.48  8254.6 1841.73  8295.1 1845.49  8301.6 1848.02
#Mann=6,-1,0
  2897.9   0.045       0  4829.4    0.07       0  4954.5    0.07       0
  4966.1    0.07       0  5192.2   0.045       0  7747.9    0.07       0
Bank Sta=4954.5,4966.1
Exp/Cntr=0.3,0.1

Type RM Length L Ch R = 1,20468,667,667,667
BEGIN DESCRIPTION:
Mapping XS baabe9ef
END DESCRIPTION:
XS GIS Cut Line= 3
      1498066.36      6868711.11      1499108.03      6868872.56
      1503491.73      6868737.20
#Sta/Elev= 30
  2848.4 1820.02  3008.9 1819.45  3039.3 1818.78  3737.5 1817.10  3939.5 1815.99
  4049.6 1816.63  4069.6 1815.69  4199.6 1814.33  4389.7 1813.92  4599.8 1810.69
  4960.0 1809.14  4994.2 1806.81  4994.7 1806.31  5005.4 1806.31  5005.9 1806.81
  5010.0 1807.75  5050.0 1808.04  5070.0 1808.74  5080.0 1809.90  5100.1 1809.06
  5190.1 1809.16  5980.5 1813.00  6390.7 1815.22  6700.8 1818.04  6870.9 1818.63
  7071.0 1820.28  7127.2 1821.36  7211.1 1821.30  7911.4 1827.75  8288.3 1833.58
#Mann=3,-1,0
  2848.4   0.045       0  4994.2   0.045       0  5005.9   0.045       0
Bank Sta=4994.2,5005.9
Exp/Cntr=0.3,0.1

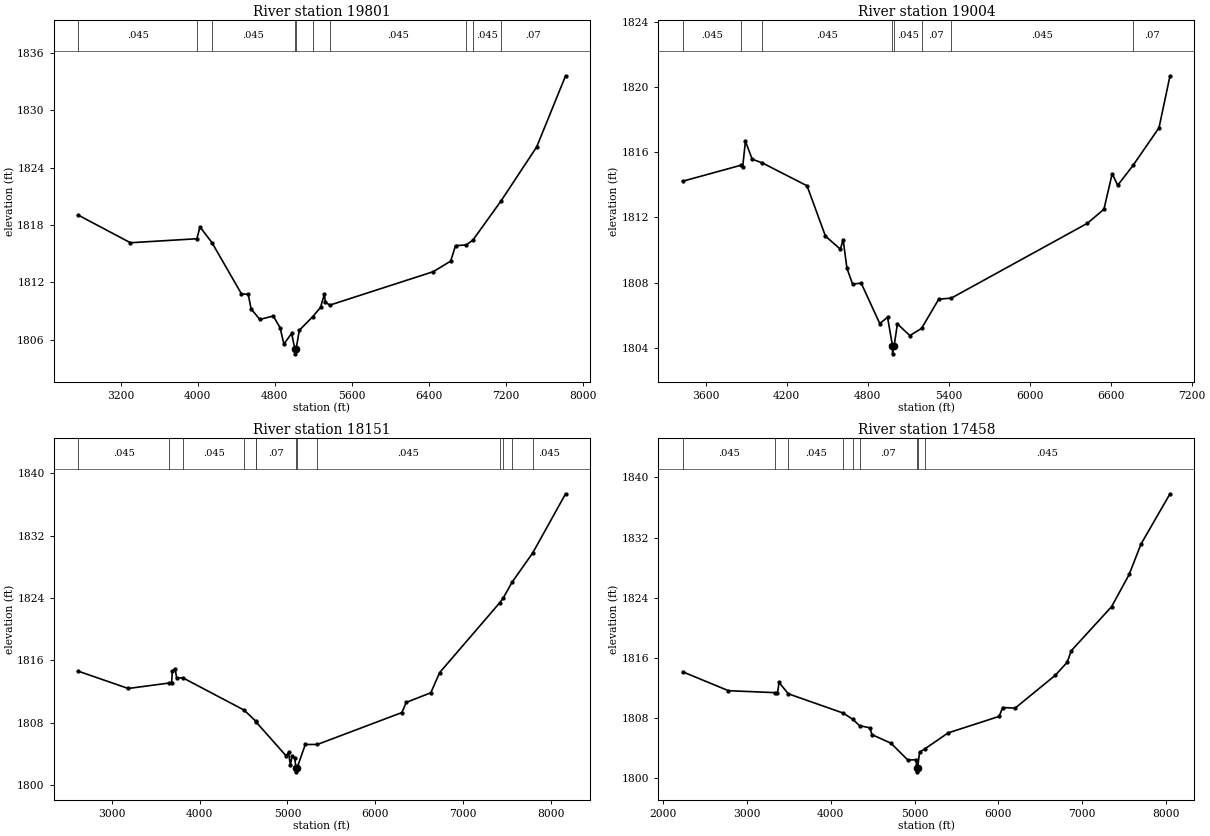
Type RM Length L Ch R = 1,19801,797,797,797
BEGIN DESCRIPTION:
Mapping XS e8f821f2
END DESCRIPTION:
XS GIS Cut Line= 3
      1498024.73      6869409.03      1499462.20      6869513.19
      1503076.81      6869403.81
#Sta/Elev= 30
  2760.5 1819.04  3302.2 1816.15  3991.8 1816.57  4024.1 1817.80  4148.5 1816.16
  4454.7 1810.80  4524.7 1810.76  4554.7 1809.23  4644.7 1808.14  4784.8 1808.49
  4854.8 1807.28  4894.9 1805.56  4974.9 1806.68  5008.6 1805.04  5009.1 1804.54
  5021.2 1805.04  5054.9 1807.00  5193.2 1808.42  5275.0 1809.39  5315.0 1810.79
  5325.1 1809.91  5374.0 1809.64  6445.6 1813.13  6625.6 1814.23  6675.7 1815.85
  6787.1 1815.92  6857.0 1816.44  7147.4 1820.51  7517.7 1826.16  7818.0 1833.60
#Mann=10,-1,0
  2760.5   0.045       0  3991.8   0.035       0  4148.5   0.045       0
  5008.6   0.045       0  5021.2   0.045       0  5193.2   0.035       0
  5374.0   0.045       0  6787.1    0.07       0  6857.0   0.045       0
  7147.4    0.07       0
Bank Sta=5008.6,5021.2
Exp/Cntr=0.3,0.1

Type RM Length L Ch R = 1,19004,853,853,853
BEGIN DESCRIPTION:
NC Unknown Stream 01 19.0
END DESCRIPTION:
XS GIS Cut Line= 3
      1498842.37      6870080.89      1500405.00      6870238.00
      1502404.98      6869838.00
#Sta/Elev= 30
  3429.1 1814.22  3860.6 1815.20  3874.0 1815.11  3894.1 1816.67  3944.3 1815.57
  4017.8 1815.35  4350.6 1813.94  4487.0 1810.85  4597.6 1810.05  4617.7 1810.64
  4646.3 1808.87  4688.0 1807.91  4751.5 1807.97  4889.1 1805.49  4947.0 1805.87
  4983.2 1804.13  4983.7 1803.63  4995.9 1804.13  5020.0 1805.47  5111.8 1804.75
  5198.6 1805.19  5325.9 1806.98  5419.4 1807.05  6427.3 1811.64  6549.7 1812.50
  6610.9 1814.68  6651.7 1813.97  6766.1 1815.20  6957.6 1817.50  7039.2 1820.69
#Mann=8,-1,0
  3429.1   0.045       0  3860.6   0.035       0  4017.8   0.045       0
  4983.2   0.045       0  4995.9   0.045       0  5198.6    0.07       0
  5419.4   0.045       0  6766.1    0.07       0
Bank Sta=4983.2,4995.9
Exp/Cntr=0.3,0.1

Type RM Length L Ch R = 1,18151,693,693,693
BEGIN DESCRIPTION:
Mapping XS dbbd871b
END DESCRIPTION:
XS GIS Cut Line= 3
      1498259.11      6870539.24      1499868.45      6870731.94
      1503800.33      6870627.78
#Sta/Elev= 30
  2615.5 1814.63  3185.4 1812.41  3651.6 1813.11  3678.9 1813.09  3689.0 1814.66
  3719.2 1814.96  3737.5 1813.76  3809.2 1813.77  4507.1 1809.63  4636.5 1808.24
  4641.7 1808.12  4983.1 1803.79  5013.2 1804.21  5033.2 1802.54  5053.2 1803.81
  5083.2 1803.48  5096.8 1802.22  5097.3 1801.72  5109.6 1802.22  5203.2 1805.23
  5340.7 1805.23  6303.6 1809.32  6353.6 1810.63  6633.7 1811.86  6733.8 1814.44
  7417.9 1823.39  7459.8 1824.03  7558.9 1826.03  7794.3 1829.78  8169.6 1837.38
#Mann=13,-1,0
  2615.5   0.045       0  3651.6   0.035       0  3809.2   0.045       0
  4507.1    0.07       0  4636.5    0.16       0  4641.7    0.07       0
  5096.8    0.07       0  5109.6    0.07       0  5340.7   0.045       0
  7417.9    0.07       0  7459.8   0.045       0  7558.9    0.07       0
  7794.3   0.045       0
Bank Sta=5096.8,5109.6
Exp/Cntr=0.3,0.1

Type RM Length L Ch R = 1,17458,1498,1498,1498
BEGIN DESCRIPTION:
Mapping XS d9e341ab
END DESCRIPTION:
XS GIS Cut Line= 4
      1498201.80      6870856.94      1499634.07      6871018.40
      1500165.32      6871080.90      1504001.95      6871070.49
#Sta/Elev= 30
  2233.6 1814.17  2780.2 1811.66  3336.2 1811.40  3363.9 1811.33  3384.0 1812.75
  3493.7 1811.25  4149.9 1808.68  4261.6 1807.87  4345.2 1807.01  4469.5 1806.72
  4489.5 1805.84  4719.5 1804.67  4919.5 1802.45  5019.5 1802.49  5023.0 1801.38
  5023.5 1800.88  5036.0 1801.38  5059.5 1803.49  5123.9 1803.94  5399.5 1806.05
  6009.5 1808.25  6049.5 1809.42  6199.5 1809.35  6679.5 1813.72  6819.5 1815.43
  6869.5 1816.98  7349.6 1822.82  7559.6 1827.11  7699.6 1831.12  8046.5 1837.82
#Mann=9,-1,0
  2233.6   0.045       0  3336.2   0.035       0  3493.7   0.045       0
  4149.9    0.07       0  4261.6    0.16       0  4345.2    0.07       0
  5023.0    0.07       0  5036.0    0.07       0  5123.9   0.045       0
Bank Sta=5023,5036
Exp/Cntr=0.3,0.1