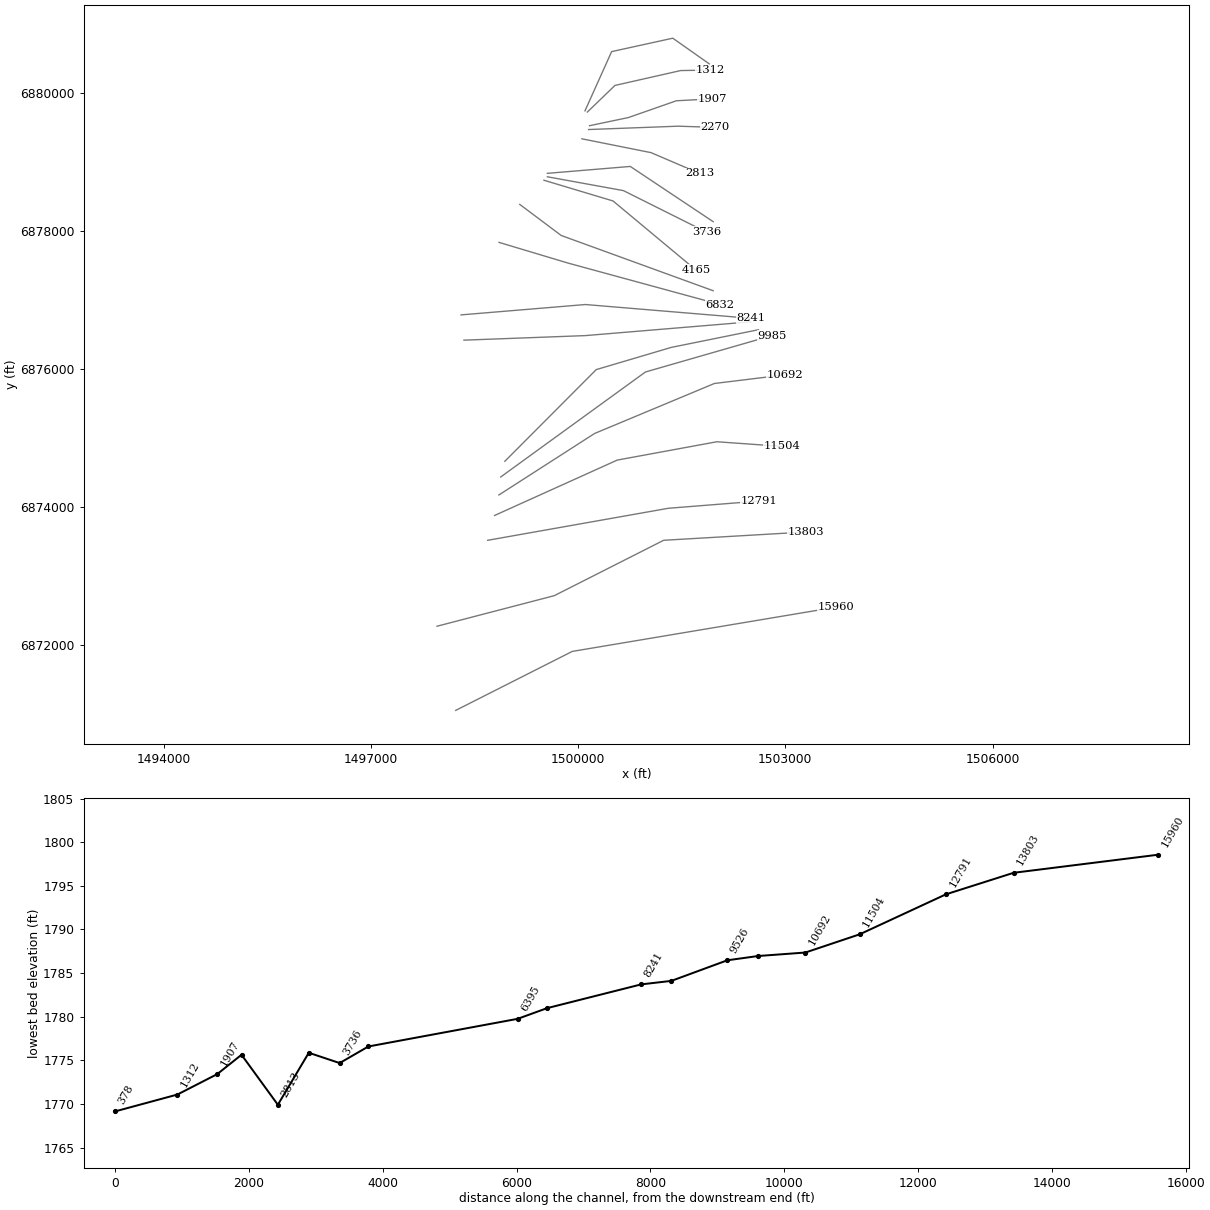
HEC-RAS study NC Unknown Stream 01.prj: NC Unknown Stream 01 Base Level Engineering

--- NC Unknown Stream 01.g01 (geometry) --- (continued)

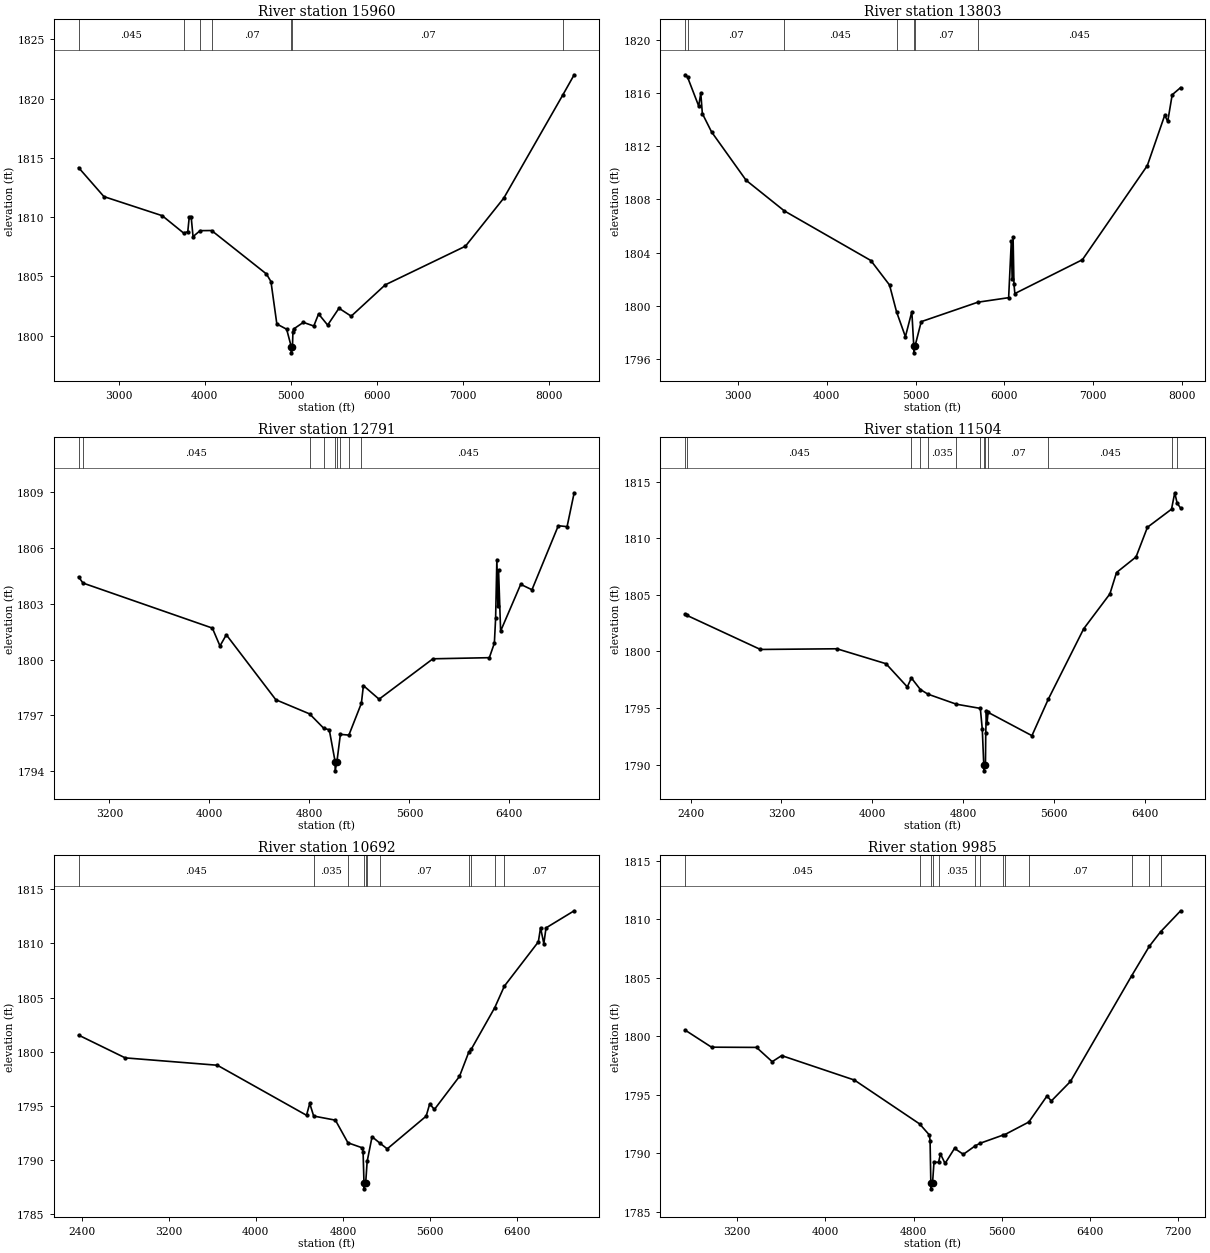
Type RM Length L Ch R = 1,15960,2157,2157,2157
BEGIN DESCRIPTION:
Mapping XS 01b5f1b1
END DESCRIPTION:
XS GIS Cut Line= 3
      1498227.79      6871060.05      1499915.32      6871914.23
      1503731.47      6872554.59
#Sta/Elev= 30
  2532.5 1814.17  2826.6 1811.73  3504.5 1810.12  3752.6 1808.66  3801.3 1808.77
  3818.0 1809.97  3840.3 1810.05  3862.6 1808.36  3945.0 1808.86  4078.5 1808.87
  4715.6 1805.21  4768.3 1804.57  4836.8 1800.99  4950.8 1800.55  5005.1 1799.06
  5005.6 1798.56  5018.3 1799.06  5023.8 1800.33  5032.0 1800.57  5145.1 1801.13
  5266.3 1800.82  5321.9 1801.84  5427.4 1800.90  5559.2 1802.32  5701.2 1801.65
  6096.6 1804.29  7029.5 1807.55  7475.7 1811.61  8160.7 1820.29  8293.4 1822.00
#Mann=7,-1,0
  2532.5   0.045       0  3752.6   0.035       0  3945.0   0.045       0
  4078.5    0.07       0  5005.1    0.07       0  5018.3    0.07       0
  8160.7    0.07       0
Bank Sta=5005.1,5018.3
Exp/Cntr=0.3,0.1

Type RM Length L Ch R = 1,13803,1012,1012,1012
BEGIN DESCRIPTION:
Mapping XS d3441c8c
END DESCRIPTION:
XS GIS Cut Line= 4
      1497956.99      6872278.82      1499654.90      6872721.52
      1501238.24      6873523.61      1503290.16      6873643.39
#Sta/Elev= 30
  2403.2 1817.36  2430.4 1817.19  2556.2 1815.02  2580.2 1815.97  2597.5 1814.45
  2701.6 1813.07  3091.0 1809.44  3522.3 1807.14  4496.5 1803.42  4707.3 1801.58
  4786.3 1799.57  4886.2 1797.70  4958.6 1799.58  4980.6 1796.99  4981.1 1796.49
  4994.4 1796.99  5064.4 1798.83  5702.6 1800.29  6049.7 1800.63  6079.8 1804.87
  6089.4 1802.00  6099.8 1805.16  6109.8 1801.65  6119.9 1800.94  6881.2 1803.48
  7612.4 1810.54  7808.8 1814.32  7842.8 1813.86  7892.9 1815.86  7988.2 1816.40
#Mann=7,-1,0
  2403.2   0.045       0  2430.4    0.07       0  3522.3   0.045       0
  4786.3    0.07       0  4980.6    0.07       0  4994.4    0.07       0
  5702.6   0.045       0
Bank Sta=4980.6,4994.4
Exp/Cntr=0.3,0.1

Type RM Length L Ch R = 1,12791,1287,1287,1287
BEGIN DESCRIPTION:
Mapping XS 372d641d
END DESCRIPTION:
XS GIS Cut Line= 3
      1498691.32      6873523.60      1501305.95      6873987.15
      1502611.61      6874091.18
#Sta/Elev= 30
  2953.2 1804.44  2987.8 1804.11  4023.3 1801.69  4084.2 1800.73  4135.0 1801.33
  4531.1 1797.84  4801.3 1797.08  4915.5 1796.30  4958.7 1796.23  5005.4 1794.52
  5005.9 1794.02  5020.1 1794.52  5047.7 1795.98  5115.6 1795.94  5215.7 1797.65
  5231.9 1798.60  5357.3 1797.87  5788.2 1800.04  6239.6 1800.10  6279.8 1800.88
  6289.8 1802.21  6299.8 1805.37  6308.3 1802.85  6313.3 1804.81  6329.9 1801.53
  6490.4 1804.04  6580.7 1803.75  6791.4 1807.19  6861.6 1807.14  6918.4 1808.96
#Mann=9,-1,0
  2953.2    0.07       0  2987.8   0.045       0  4801.3    0.07       0
  4915.5   0.035       0  5005.4   0.035       0  5020.1   0.035       0
  5047.7    0.07       0  5115.6   0.035       0  5215.7   0.045       0
Bank Sta=5005.4,5020.1
Exp/Cntr=0.3,0.1

Type RM Length L Ch R = 1,11504,812,812,812
BEGIN DESCRIPTION:
Mapping XS e1d3d7bb
END DESCRIPTION:
XS GIS Cut Line= 4
      1498790.29      6873882.97      1500566.36      6874685.06
      1502009.07      6874950.69      1502956.81      6874882.99
#Sta/Elev= 30
  2351.1 1803.28  2363.5 1803.20  3014.6 1800.17  3688.4 1800.23  4121.1 1798.91
  4308.7 1796.86  4344.8 1797.65  4423.8 1796.63  4490.3 1796.22  4741.1 1795.33
  4952.2 1794.96  4969.6 1793.10  4982.6 1789.94  4983.1 1789.44  4997.3 1789.94
  5000.1 1792.81  5005.8 1794.77  5010.9 1793.64  5020.6 1794.61  5406.8 1792.55
  5550.8 1795.77  5863.0 1802.00  6093.6 1805.08  6152.1 1806.97  6324.2 1808.35
  6424.4 1810.97  6636.7 1812.57  6665.1 1814.02  6686.2 1813.10  6717.0 1812.66
#Mann=13,-1,0
  2351.1    0.07       0  2363.5   0.045       0  4344.8   0.035       0
  4423.8   0.045       0  4490.3   0.035       0  4741.1    0.07       0
  4952.2   0.035       0  4982.6   0.035       0  4997.3   0.035       0
  5020.6    0.07       0  5550.8   0.045       0  6636.7    0.07       0
  6686.2   0.045       0
Bank Sta=4982.6,4997.3
Exp/Cntr=0.3,0.1

Type RM Length L Ch R = 1,10692,707,707,707
BEGIN DESCRIPTION:
Mapping XS e09366fa
END DESCRIPTION:
XS GIS Cut Line= 4
      1498852.82      6874179.86      1500238.24      6875070.48
      1501972.61      6875794.44      1502991.70      6875919.23
#Sta/Elev= 30
  2371.6 1801.54  2799.5 1799.44  3646.2 1798.76  4465.6 1794.14  4494.9 1795.24
  4531.1 1794.07  4730.9 1793.69  4846.1 1791.60  4979.5 1791.13  4985.3 1790.73
  4993.6 1787.85  4994.1 1787.35  5008.7 1787.85  5022.6 1789.88  5067.6 1792.16
  5136.9 1791.59  5207.1 1791.04  5564.7 1794.06  5597.2 1795.19  5640.5 1794.68
  5870.9 1797.73  5957.1 1799.99  5979.7 1800.25  6195.1 1804.08  6283.0 1806.06
  6595.6 1810.15  6615.7 1811.46  6645.9 1809.99  6666.1 1811.44  6924.7 1813.02
#Mann=11,-1,0
  2371.6   0.045       0  4531.1   0.035       0  4846.1    0.07       0
  4993.6    0.07       0  5008.7    0.07       0  5022.6   0.035       0
  5136.9    0.07       0  5957.1   0.035       0  5979.7    0.07       0
  6195.1   0.035       0  6283.0    0.07       0
Bank Sta=4993.6,5008.7
Exp/Cntr=0.3,0.1

Type RM Length L Ch R = 1,9985,459,459,459
BEGIN DESCRIPTION:
NC Unknown Stream 01 11.0
END DESCRIPTION:
XS GIS Cut Line= 3
      1498878.84      6874440.26      1500974.38      6875960.99
      1502805.04      6876488.01
#Sta/Elev= 30
  2727.9 1800.52  2967.5 1799.06  3375.7 1799.04  3517.9 1797.82  3603.7 1798.34
  4263.2 1796.25  4854.7 1792.50  4943.5 1791.55  4949.6 1791.08  4956.6 1787.45
  4957.1 1786.95  4972.0 1787.45  4985.2 1789.23  5026.7 1789.22  5044.0 1789.93
  5085.7 1789.12  5171.5 1790.41  5251.2 1789.90  5361.2 1790.64  5404.7 1790.85
  5612.7 1791.55  5626.2 1791.58  5845.0 1792.66  6010.4 1794.89  6049.3 1794.46
  6222.9 1796.13  6776.5 1805.14  6937.6 1807.68  7039.8 1808.92  7222.1 1810.72
#Mann=13,-1,0
  2727.9   0.045       0  4854.7    0.07       0  4956.6    0.07       0
  4972.0    0.07       0  5026.7   0.035       0  5361.2    0.07       0
  5404.7   0.035       0  5612.7    0.07       0  5626.2   0.035       0
  5845.0    0.07       0  6776.5   0.035       0  6937.6    0.07       0
  7039.8   0.045       0
Bank Sta=4956.6,4972
Exp/Cntr=0.3,0.1

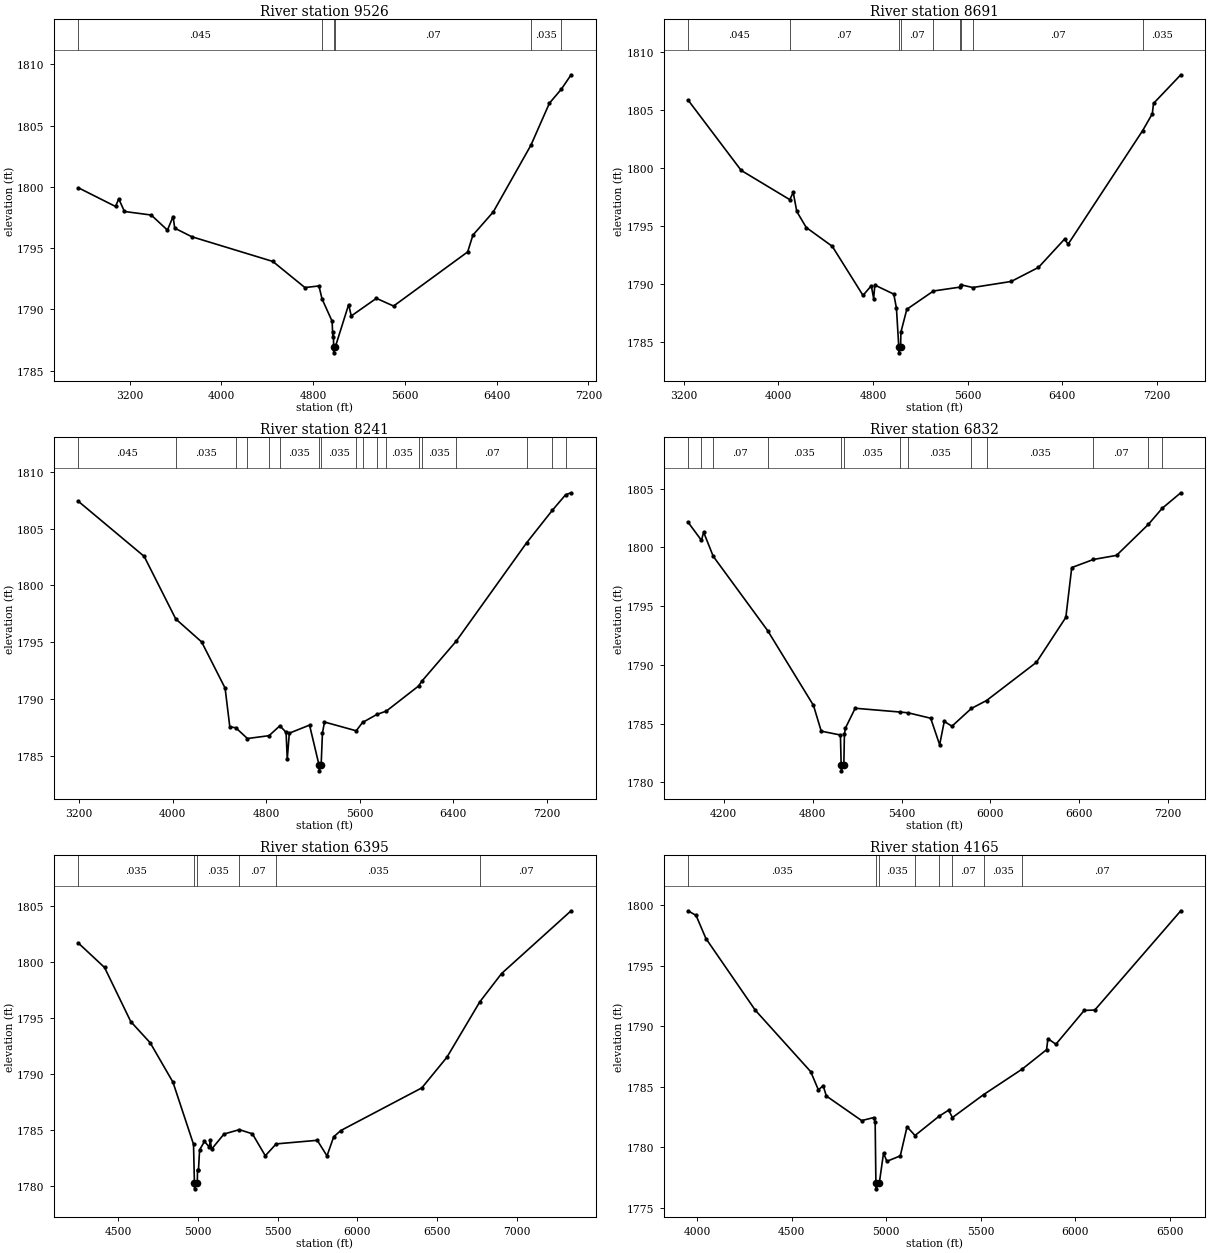
Type RM Length L Ch R = 1,9526,835,835,835
BEGIN DESCRIPTION:
Mapping XS a48910bc
END DESCRIPTION:
XS GIS Cut Line= 4
      1498938.75      6874667.56      1500262.57      6875995.71
      1501347.64      6876316.89      1502610.31      6876572.90
#Sta/Elev= 30
  2753.3 1799.93  3076.2 1798.41  3104.5 1799.03  3154.0 1798.00  3387.4 1797.71
  3528.8 1796.48  3578.3 1797.59  3592.4 1796.64  3740.9 1795.94  4448.0 1793.92
  4727.4 1791.79  4850.1 1791.92  4876.9 1790.86  4964.8 1789.04  4970.6 1787.78
  4975.9 1788.14  4977.9 1786.96  4978.4 1786.46  4993.3 1786.96  5108.9 1790.40
  5131.7 1789.47  5350.7 1790.91  5500.8 1790.28  6146.7 1794.70  6192.3 1796.07
  6369.7 1797.96  6698.1 1803.41  6859.4 1806.84  6964.0 1807.99  7048.5 1809.16
#Mann=6,-1,0
  2753.3   0.045       0  4876.9    0.07       0  4977.9    0.07       0
  4993.3    0.07       0  6698.1   0.035       0  6964.0   0.045       0
Bank Sta=4977.9,4993.3
Exp/Cntr=0.3,0.1

Type RM Length L Ch R = 1,8691,450,450,450
BEGIN DESCRIPTION:
NC Unknown Stream 01 10.0
END DESCRIPTION:
XS GIS Cut Line= 3
      1498346.79      6876421.93      1500105.00      6876488.00
      1502505.03      6876688.00
#Sta/Elev= 30
  3236.6 1805.87  3685.1 1799.82  4096.3 1797.30  4125.4 1797.93  4155.5 1796.28
  4235.5 1794.90  4455.7 1793.28  4715.9 1789.05  4785.9 1789.88  4805.9 1788.78
  4815.9 1789.94  4976.0 1789.16  4998.6 1787.96  5018.5 1784.60  5019.0 1784.10
  5033.9 1784.60  5036.2 1785.87  5086.4 1787.85  5312.0 1789.43  5533.9 1789.76
  5540.8 1789.97  5644.2 1789.73  5969.4 1790.25  6200.2 1791.46  6421.0 1793.90
  6451.1 1793.46  7081.8 1803.25  7163.5 1804.70  7173.6 1805.59  7404.4 1808.06
#Mann=9,-1,0
  3236.6   0.045       0  4096.3    0.07       0  5018.5    0.07       0
  5033.9    0.07       0  5312.0   0.035       0  5533.9    0.07       0
  5540.8   0.035       0  5644.2    0.07       0  7081.8   0.035       0
Bank Sta=5018.5,5033.9
Exp/Cntr=0.3,0.1

Type RM Length L Ch R = 1,8241,1409,1409,1409
BEGIN DESCRIPTION:
NC Unknown Stream 01 9.0
END DESCRIPTION:
XS GIS Cut Line= 3
      1498304.96      6876788.00      1500105.00      6876938.00
      1502505.01      6876738.00
#Sta/Elev= 30
  3193.7 1807.38  3755.7 1802.55  4025.8 1797.05  4247.4 1795.03  4448.1 1790.97
  4488.2 1787.58  4540.0 1787.48  4639.1 1786.54  4823.9 1786.79  4917.0 1787.66
  4969.9 1787.08  4979.9 1784.73  4997.5 1787.01  5170.6 1787.72  5251.9 1784.20
  5252.4 1783.70  5269.8 1784.20  5280.9 1787.02  5298.5 1787.99  5569.9 1787.22
  5623.7 1787.95  5747.4 1788.66  5827.4 1788.95  6103.9 1791.16  6129.8 1791.56
  6425.5 1795.10  7028.3 1803.75  7247.8 1806.60  7361.6 1807.97  7408.3 1808.14
#Mann=18,-1,0
  3193.7   0.045       0  4025.8   0.035       0  4540.0    0.07       0
  4639.1   0.035       0  4823.9    0.07       0  4917.0   0.035       0
  5251.9   0.035       0  5269.8   0.035       0  5569.9    0.07       0
  5623.7   0.035       0  5747.4    0.07       0  5827.4   0.035       0
  6103.9    0.07       0  6129.8   0.035       0  6425.5    0.07       0
  7028.3   0.035       0  7247.8    0.07       0  7361.6   0.035       0
Bank Sta=5251.9,5269.8
Exp/Cntr=0.3,0.1

Type RM Length L Ch R = 1,6832,437,437,437
BEGIN DESCRIPTION:
NC Unknown Stream 01 8.0
END DESCRIPTION:
XS GIS Cut Line= 3
      1498854.97      6877838.01      1499855.00      6877538.00
      1502054.99      6876938.00
#Sta/Elev= 30
  3959.8 1802.13  4049.3 1800.60  4064.2 1801.29  4128.9 1799.24  4495.7 1792.92
  4805.5 1786.54  4857.7 1784.35  4987.3 1784.02  4992.3 1781.47  4992.8 1780.97
  5010.3 1781.47  5014.2 1784.08  5021.1 1784.61  5086.8 1786.30  5387.8 1785.98
  5444.8 1785.91  5596.4 1785.45  5656.9 1783.19  5688.0 1785.18  5739.8 1784.77
  5870.7 1786.28  5973.6 1786.96  6309.9 1790.21  6508.5 1794.04  6548.3 1798.28
  6694.7 1798.97  6850.6 1799.32  7065.5 1801.96  7158.9 1803.33  7284.2 1804.65
#Mann=13,-1,0
  3959.8   0.045       0  4049.3   0.035       0  4128.9    0.07       0
  4495.7   0.035       0  4992.3   0.035       0  5010.3   0.035       0
  5387.8    0.07       0  5444.8   0.035       0  5870.7    0.07       0
  5973.6   0.035       0  6694.7    0.07       0  7065.5   0.035       0
  7158.9    0.07       0
Bank Sta=4992.3,5010.3
Exp/Cntr=0.3,0.1

Type RM Length L Ch R = 1,6395,2230,2230,2230
BEGIN DESCRIPTION:
NC Unknown Stream 01 7.0
END DESCRIPTION:
XS GIS Cut Line= 3
      1499154.97      6878388.02      1499755.00      6877938.00
      1501955.02      6877137.99
#Sta/Elev= 30
  4250.6 1801.67  4414.2 1799.50  4578.8 1794.67  4700.6 1792.78  4843.3 1789.27
  4972.5 1783.72  4978.1 1780.25  4978.6 1779.75  4996.1 1780.25  4997.5 1781.40
  5003.3 1781.40  5010.6 1783.23  5041.2 1783.98  5071.8 1783.47  5077.1 1784.10
  5085.8 1783.29  5163.6 1784.64  5260.2 1785.03  5341.8 1784.66  5422.9 1782.70
  5491.1 1783.76  5748.8 1784.08  5810.0 1782.69  5851.9 1784.39  5896.4 1784.95
  6405.2 1788.76  6562.8 1791.50  6768.6 1796.43  6905.3 1798.96  7341.6 1804.56
#Mann=6,-1,0
  4250.6   0.035       0  4978.1   0.035       0  4996.1   0.035       0
  5260.2    0.07       0  5491.1   0.035       0  6768.6    0.07       0
Bank Sta=4978.1,4996.1
Exp/Cntr=0.3,0.1

Type RM Length L Ch R = 1,4165,429,429,429
BEGIN DESCRIPTION:
NC Unknown Stream 01 6.0
END DESCRIPTION:
XS GIS Cut Line= 3
      1499505.04      6878737.99      1500505.00      6878438.00
      1501704.97      6877438.02
#Sta/Elev= 30
  3951.7 1799.51  3993.4 1799.14  4045.6 1797.23  4306.6 1791.32  4599.8 1786.25
  4640.7 1784.74  4665.9 1785.10  4682.5 1784.24  4869.5 1782.21  4933.0 1782.46
  4940.9 1782.11  4944.8 1777.08  4945.3 1776.58  4963.0 1777.08  4985.2 1779.53
  5002.8 1778.85  5073.8 1779.30  5109.6 1781.70  5151.7 1780.98  5279.7 1782.58
  5329.6 1783.07  5349.6 1782.46  5514.3 1784.35  5719.6 1786.47  5847.7 1788.06
  5854.8 1788.97  5897.1 1788.51  6046.8 1791.30  6102.8 1791.33  6557.7 1799.52
#Mann=8,-1,0
  3951.7   0.035       0  4944.8   0.035       0  4963.0   0.035       0
  5151.7    0.07       0  5279.7   0.035       0  5349.6    0.07       0
  5514.3   0.035       0  5719.6    0.07       0
Bank Sta=4944.8,4963
Exp/Cntr=0.3,0.1

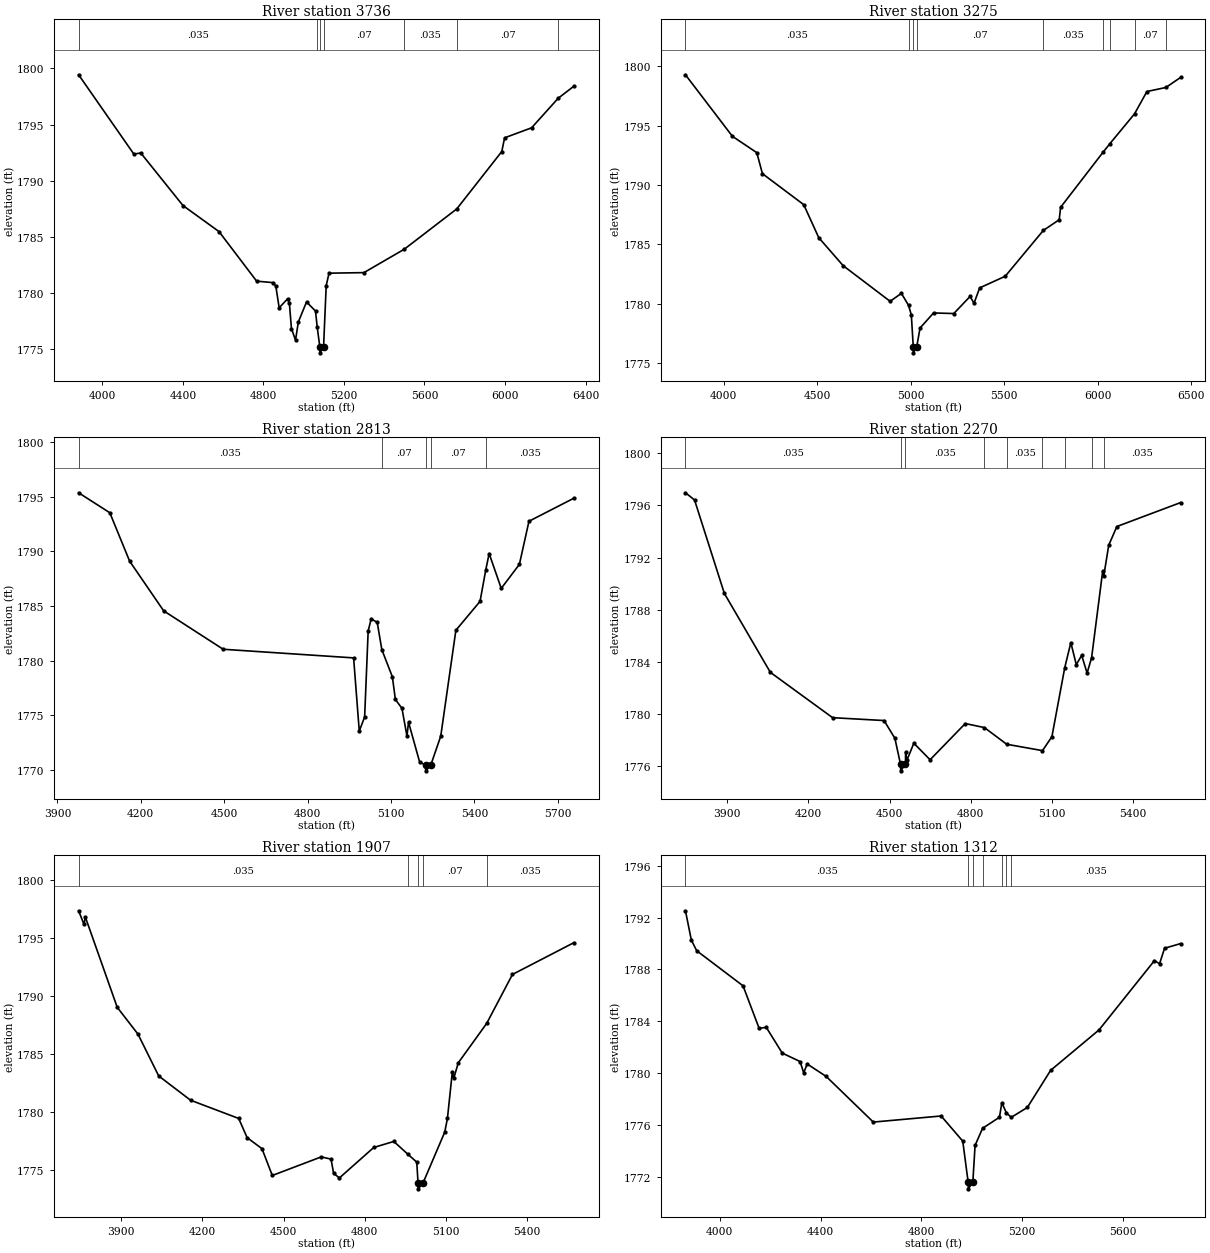
Type RM Length L Ch R = 1,3736,461,461,461
BEGIN DESCRIPTION:
NC Unknown Stream 01 5.0
END DESCRIPTION:
XS GIS Cut Line= 3
      1499555.00      6878788.00      1500655.00      6878588.00
      1501855.02      6877987.99
#Sta/Elev= 30
  3882.0 1799.43  4156.4 1792.37  4190.7 1792.47  4400.4 1787.79  4579.5 1785.47
  4766.3 1781.06  4847.6 1780.93  4861.6 1780.61  4878.1 1778.69  4920.0 1779.49
  4928.9 1779.09  4939.1 1776.84  4959.4 1775.81  4973.4 1777.43  5014.0 1779.21
  5058.7 1778.40  5067.1 1776.97  5080.3 1775.18  5080.8 1774.68  5098.6 1775.18
  5111.8 1780.67  5125.8 1781.77  5299.1 1781.82  5499.3 1783.90  5760.2 1787.49
  5983.9 1792.60  5997.9 1793.82  6132.0 1794.71  6264.0 1797.34  6341.7 1798.41
#Mann=7,-1,0
  3882.0   0.035       0  5067.1    0.07       0  5080.3   0.035       0
  5098.6    0.07       0  5499.3   0.035       0  5760.2    0.07       0
  6264.0   0.035       0
Bank Sta=5080.3,5098.6
Exp/Cntr=0.3,0.1

Type RM Length L Ch R = 1,3275,462,462,462
BEGIN DESCRIPTION:
NC Unknown Stream 01 4.0
END DESCRIPTION:
XS GIS Cut Line= 3
      1499555.02      6878838.00      1500755.00      6878938.00
      1501955.03      6878137.98
#Sta/Elev= 30
  3796.2 1799.28  4047.0 1794.10  4177.5 1792.72  4207.6 1790.95  4428.4 1788.34
  4508.6 1785.56  4639.1 1783.20  4890.0 1780.20  4950.2 1780.87  4988.5 1779.86
  5003.3 1779.05  5013.7 1776.36  5014.2 1775.86  5032.0 1776.36  5049.9 1777.95
  5122.0 1779.22  5230.2 1779.17  5317.3 1780.61  5338.4 1780.04  5368.4 1781.33
  5505.1 1782.31  5708.7 1786.17  5793.6 1787.07  5801.1 1788.12  6028.6 1792.77
  6064.0 1793.47  6196.2 1795.99  6262.3 1797.87  6363.5 1798.21  6442.6 1799.06
#Mann=9,-1,0
  3796.2   0.035       0  4988.5    0.07       0  5013.7    0.07       0
  5032.0    0.07       0  5708.7   0.035       0  6028.6    0.07       0
  6064.0   0.035       0  6196.2    0.07       0  6363.5   0.035       0
Bank Sta=5013.7,5032
Exp/Cntr=0.3,0.1

Type RM Length L Ch R = 1,2813,543,543,543
BEGIN DESCRIPTION:
NC Unknown Stream 01 3.0
END DESCRIPTION:
XS GIS Cut Line= 3
      1500054.97      6879338.01      1501055.00      6879138.00
      1501754.99      6878838.00
#Sta/Elev= 30
  3976.4 1795.38  4088.6 1793.55  4160.0 1789.11  4282.4 1784.56  4496.5 1781.04
  4965.6 1780.25  4986.0 1773.54  5005.3 1774.84  5018.0 1782.72  5028.9 1783.83
  5050.6 1783.50  5067.2 1781.00  5105.0 1778.52  5115.9 1776.44  5139.5 1775.63
  5157.6 1773.08  5163.1 1774.36  5202.9 1770.73  5224.6 1770.40  5225.1 1769.90
  5242.9 1770.40  5279.1 1773.08  5333.5 1782.78  5420.5 1785.43  5441.0 1788.31
  5453.2 1789.81  5496.7 1786.62  5562.0 1788.82  5596.4 1792.77  5757.8 1794.88
#Mann=5,-1,0
  3976.4   0.035       0  5067.2    0.07       0  5224.6   0.035       0
  5242.9    0.07       0  5441.0   0.035       0
Bank Sta=5224.6,5242.9
Exp/Cntr=0.3,0.1

Type RM Length L Ch R = 1,2270,363,363,363
BEGIN DESCRIPTION:
NC Unknown Stream 01 2.0
END DESCRIPTION:
XS GIS Cut Line= 3
      1500151.43      6879472.39      1501450.04      6879521.00
      1501980.64      6879503.66
#Sta/Elev= 30
  3745.2 1796.97  3778.8 1796.42  3888.9 1789.25  4059.0 1783.19  4289.1 1779.71
  4479.3 1779.49  4519.3 1778.13  4540.2 1776.13  4540.7 1775.63  4558.5 1776.13
  4558.9 1777.06  4563.9 1776.45  4589.4 1777.75  4649.4 1776.48  4779.5 1779.26
  4850.2 1778.95  4932.6 1777.67  5064.9 1777.18  5099.7 1778.25  5147.3 1783.56
  5169.7 1785.47  5189.8 1783.78  5209.8 1784.49  5229.8 1783.13  5246.5 1784.32
  5287.3 1790.94  5291.2 1790.56  5309.8 1792.95  5339.8 1794.38  5575.6 1796.22
#Mann=9,-1,0
  3745.2   0.035       0  4540.2   0.035       0  4558.5   0.035       0
  4850.2    0.07       0  4932.6   0.035       0  5064.9    0.07       0
  5147.3   0.035       0  5246.5    0.07       0  5291.2   0.035       0
Bank Sta=4540.2,4558.5
Exp/Cntr=0.3,0.1

Type RM Length L Ch R = 1,1907,595,595,595
BEGIN DESCRIPTION:
Mapping XS 56246174
END DESCRIPTION:
XS GIS Cut Line= 4
      1500165.30      6879527.94      1500727.82      6879646.00
      1501422.26      6879889.06      1501941.50      6879916.75
#Sta/Elev= 30
  3742.6 1797.35  3762.4 1796.18  3767.5 1796.81  3885.3 1789.04  3962.0 1786.73
  4038.6 1783.13  4156.4 1781.04  4334.4 1779.47  4365.4 1777.82  4420.3 1776.87
  4458.5 1774.56  4639.4 1776.16  4675.7 1775.97  4685.2 1774.74  4706.7 1774.35
  4833.5 1776.97  4907.7 1777.49  4958.7 1776.41  4992.5 1775.71  4997.3 1773.91
  4997.8 1773.41  5015.6 1773.91  5095.9 1778.29  5105.9 1779.47  5124.1 1783.49
  5129.1 1782.91  5146.0 1784.26  5250.9 1787.65  5346.3 1791.87  5573.1 1794.60
#Mann=5,-1,0
  3742.6   0.035       0  4958.7    0.07       0  4997.3    0.07       0
  5015.6    0.07       0  5250.9   0.035       0
Bank Sta=4997.3,5015.6
Exp/Cntr=0.3,0.1

Type RM Length L Ch R = 1,1312,934,934,934
BEGIN DESCRIPTION:
Mapping XS 289ea239
END DESCRIPTION:
XS GIS Cut Line= 4
      1500134.05      6879725.85      1500533.38      6880111.28
      1501484.76      6880326.56      1501918.78      6880333.50
#Sta/Elev= 30
  3863.8 1792.52  3887.2 1790.26  3908.3 1789.44  4092.3 1786.73  4156.1 1783.45
  4184.4 1783.53  4247.9 1781.54  4318.6 1780.89  4332.8 1780.02  4346.9 1780.70
  4422.2 1779.74  4609.0 1776.22  4878.2 1776.69  4963.9 1774.75  4985.4 1771.57
  4985.9 1771.07  5003.8 1771.57  5012.8 1774.42  5042.5 1775.74  5109.4 1776.59
  5119.0 1777.71  5137.4 1776.91  5156.8 1776.59  5220.2 1777.35  5312.5 1780.21
  5504.5 1783.33  5724.5 1788.68  5744.5 1788.43  5764.5 1789.63  5828.3 1789.99
#Mann=7,-1,0
  3863.8   0.035       0  4985.4   0.035       0  5003.8   0.035       0
  5042.5    0.07       0  5119.0   0.035       0  5137.4    0.07       0
  5156.8   0.035       0
Bank Sta=4985.4,5003.8
Exp/Cntr=0.3,0.1

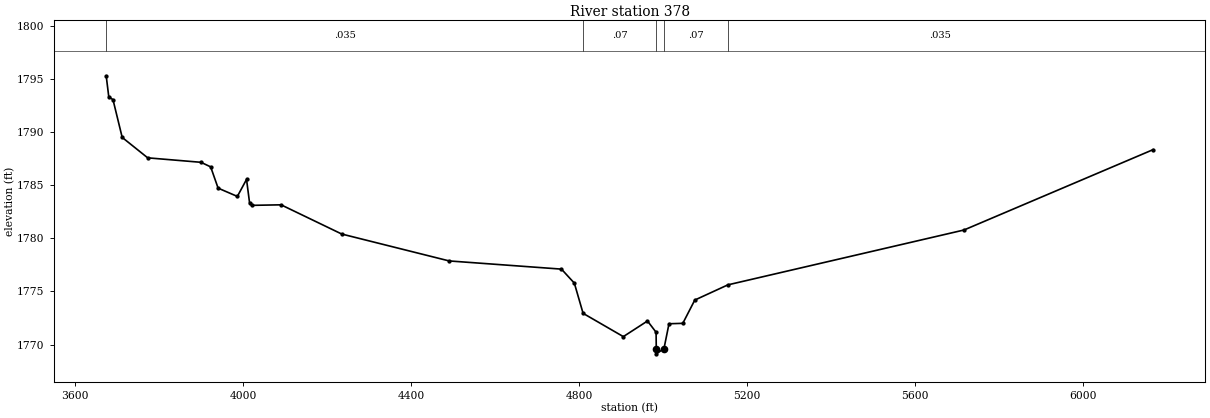
Type RM Length L Ch R = 1,378,0,0,0
BEGIN DESCRIPTION:
NC Unknown Stream 01 1.0
END DESCRIPTION:
XS GIS Cut Line= 4
      1500099.35      6879743.24      1500484.76      6880600.86
      1501370.18      6880795.31      1501897.97      6880423.78
#Sta/Elev= 30
  3674.1 1795.29  3680.2 1793.32  3690.3 1793.04  3712.2 1789.49  3772.9 1787.57
  3899.7 1787.15  3922.8 1786.72  3940.5 1784.72  3986.3 1783.94  4008.2 1785.54
  4015.5 1783.31  4020.9 1783.10  4090.4 1783.15  4234.9 1780.40  4490.6 1777.87
  4757.9 1777.10  4788.6 1775.78  4809.4 1772.94  4905.2 1770.75  4962.7 1772.22
  4983.2 1771.16  4983.6 1769.63  4984.1 1769.13  5002.0 1769.63  5013.9 1771.96
  5046.8 1772.00  5075.3 1774.19  5154.1 1775.62  5716.1 1780.78  6166.3 1788.34
#Mann=5,-1,0
  3674.1   0.035       0  4809.4    0.07       0  4983.6    0.07       0
  5002.0    0.07       0  5154.1   0.035       0
Bank Sta=4983.6,5002
Exp/Cntr=0.3,0.1

Chan Stop Cuts=-1