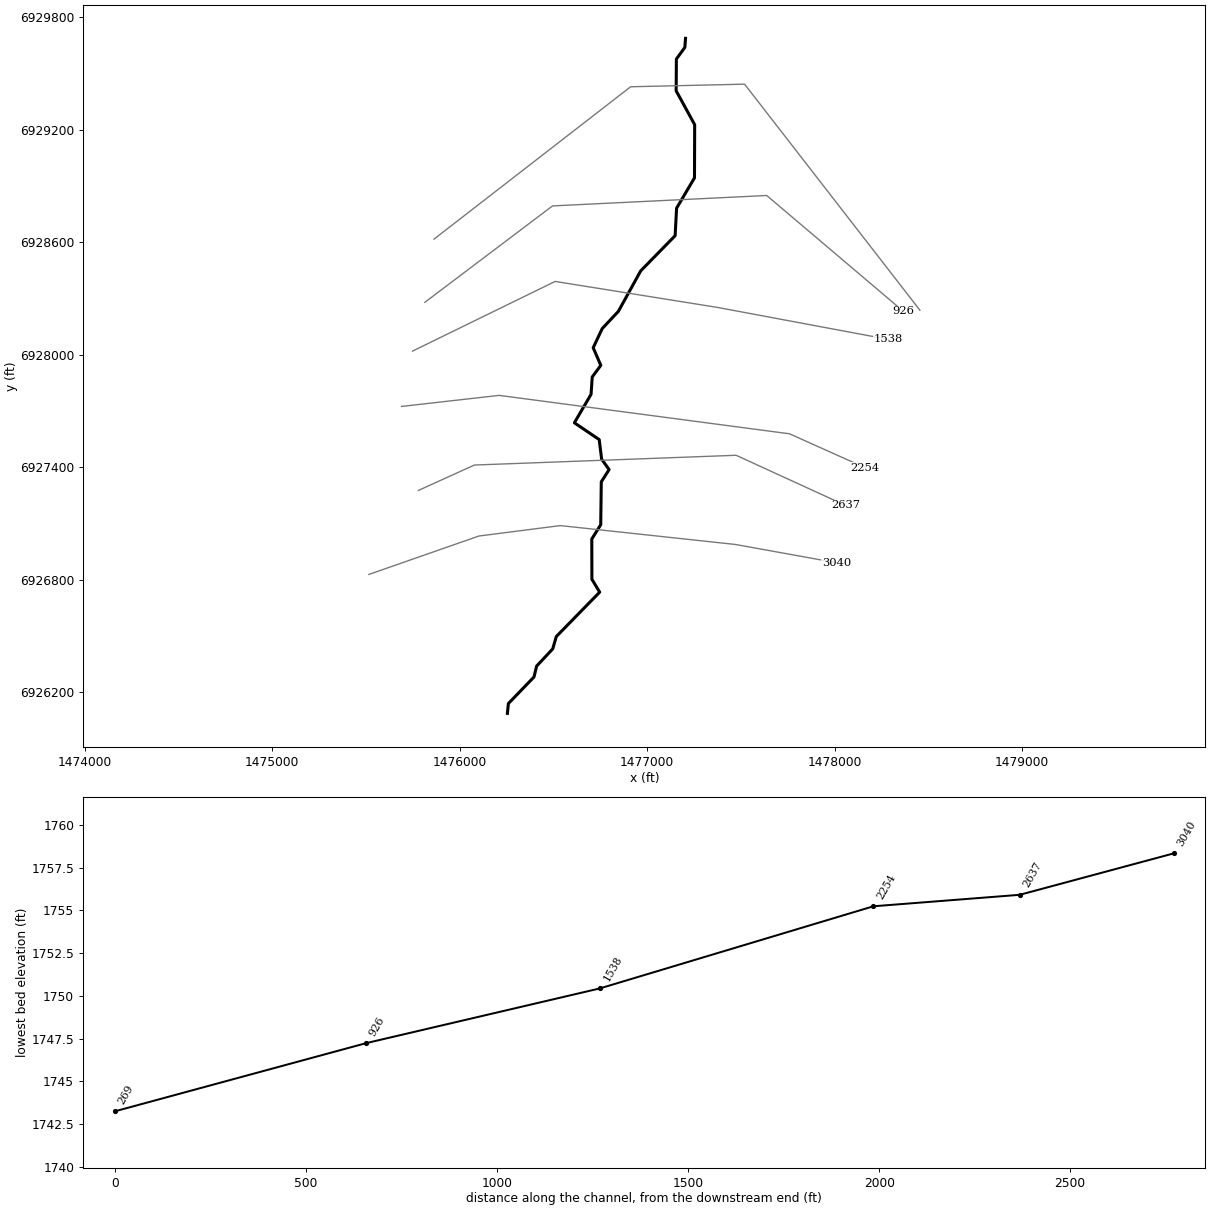
--- NC Unknown Stream 02.prj (project) ---

Proj Title=NC Unknown Stream 02 Base Level Engineering
Current Plan=p01
Default Exp/Contr=0.3,0.1
English Units
Geom File=g01
Flow File=f01
Plan File=p01
BEGIN DESCRIPTION:
NC Unknown Stream 02
END DESCRIPTION:

--- NC Unknown Stream 02.p01 (plan) ---

Plan Title=Multiple Run
Short Identifier=Multiple
Geom File=g01
Flow File=f01
Subcritical Flow
K Sum by GR= 0
Std Step Tol= 0.01
Critical Tol= 0.01
Num of Std Step Trials= 20
Max Error Tol= 0.3
Flow Tol Ratio= 0.001
Split Flow NTrial= 30
Split Flow Tol= 0.02
Split Flow Ratio= 0.02
Log Output Level= 0
Friction Slope Method= 1
Unsteady Friction Slope Method= 2
Unsteady Bridges Friction Slope Method= 1
Parabolic Critical Depth
Global Vel Dist=  1 , 1 , 1
Global Log Level= 0
CheckData=True
Encroach Param= -1, 0, 0, 0
BEGIN DESCRIPTION:
Multiple Run
END DESCRIPTION:

--- NC Unknown Stream 02.f01 (steady flow) ---

Flow Title=Multiple
Number of Profiles=7
Profile Names=10-year,25-year,50-year,1pct_min,100-year,1pct_plu,500-year
River Rch & RM= NC Unknown Strea,Reach-1,3040
     376     533     664     411     819    1635    1265
Boundary for River Rch & Prof#=NC Unknown Strea,Reach-1,1
Up Type=0
Dn Type=3
Dn Slope=0.001
Boundary for River Rch & Prof#=NC Unknown Strea,Reach-1,2
Up Type=0
Dn Type=3
Dn Slope=0.001
Boundary for River Rch & Prof#=NC Unknown Strea,Reach-1,3
Up Type=0
Dn Type=3
Dn Slope=0.001
Boundary for River Rch & Prof#=NC Unknown Strea,Reach-1,4
Up Type=0
Dn Type=3
Dn Slope=0.001
Boundary for River Rch & Prof#=NC Unknown Strea,Reach-1,5
Up Type=0
Dn Type=3
Dn Slope=0.001
Boundary for River Rch & Prof#=NC Unknown Strea,Reach-1,6
Up Type=0
Dn Type=3
Dn Slope=0.001
Boundary for River Rch & Prof#=NC Unknown Strea,Reach-1,7
Up Type=0
Dn Type=3
Dn Slope=0.001

--- NC Unknown Stream 02.g01 (geometry) ---

Geom Title=Existing Conditions

River Reach=NC Unknown Strea,Reach-1
Reach XY= 30
      1476255.00      6926088.00      1476260.31      6926140.52
      1476396.84      6926281.95      1476410.87      6926340.28
      1476496.82      6926431.96      1476515.78      6926497.68
      1476747.21      6926734.58      1476705.66      6926803.16
      1476705.07      6927017.97      1476752.74      6927093.94
      1476755.66      6927322.84      1476797.44      6927388.00
      1476757.56      6927443.90      1476744.61      6927548.10
      1476612.20      6927637.70      1476701.17      6927789.58
      1476707.38      6927882.03      1476753.14      6927944.13
      1476712.56      6928038.00      1476760.82      6928140.28
      1476846.82      6928231.96      1476965.78      6928447.68
      1477149.53      6928635.55      1477157.25      6928782.07
      1477252.76      6928943.93      1477253.80      6929227.50
      1477155.06      6929408.03      1477156.12      6929577.54
      1477201.35      6929639.51      1477205.00      6929688.00

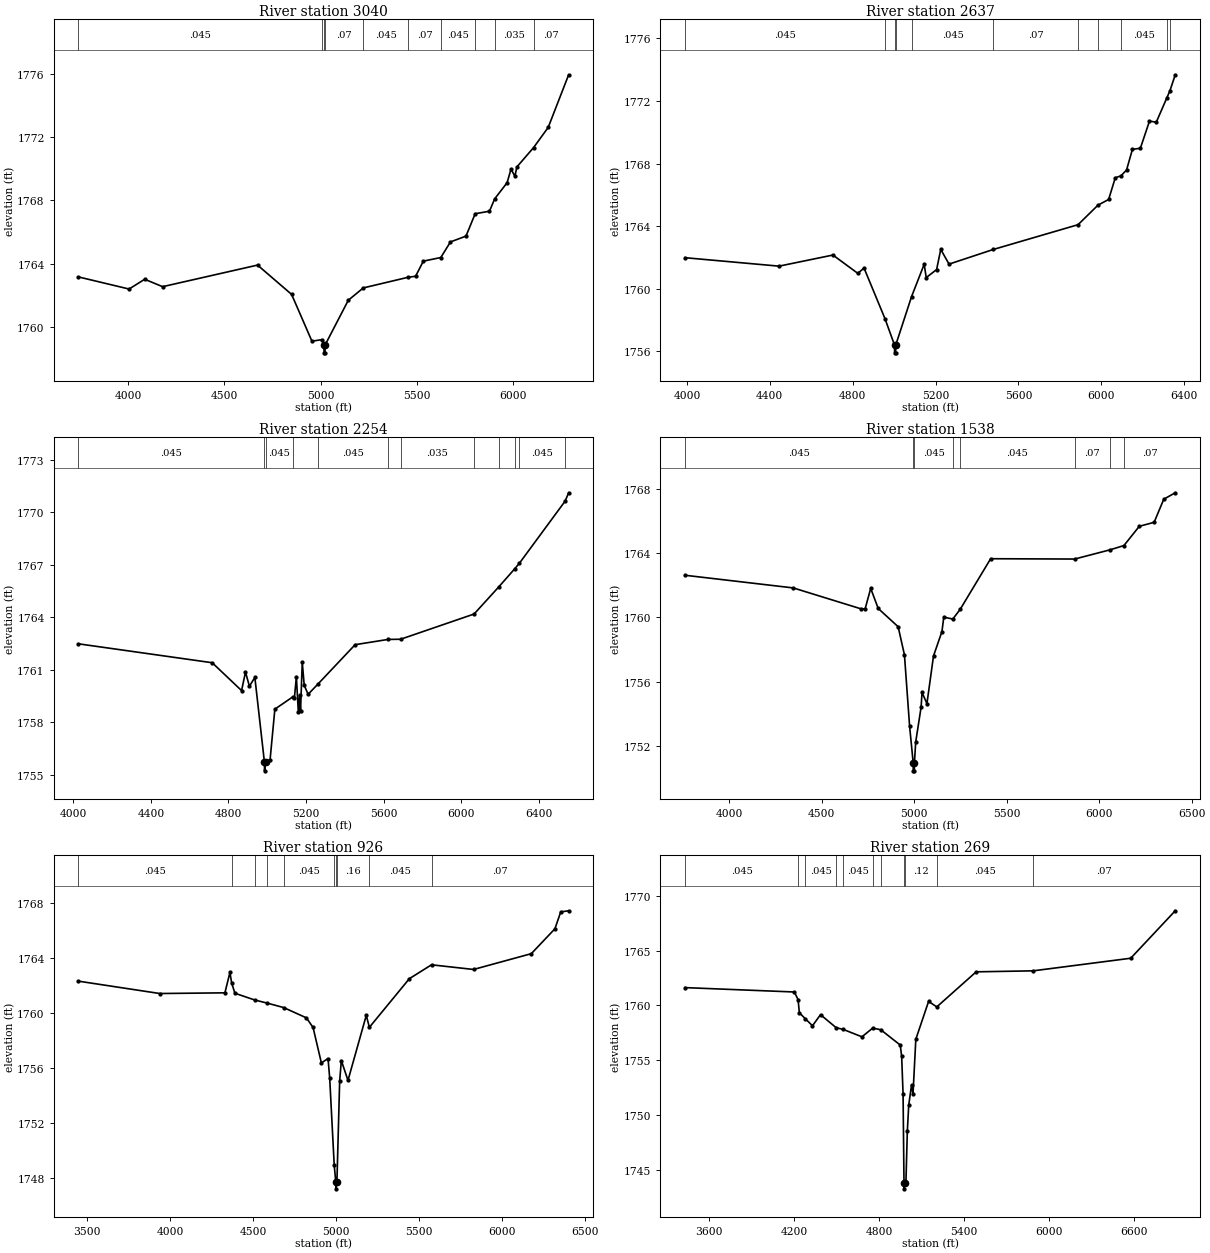
Type RM Length L Ch R = 1,3040,403,403,403
BEGIN DESCRIPTION:
Mapping XS 11f20424
END DESCRIPTION:
XS GIS Cut Line= 5
      1475516.44      6926829.02      1476103.25      6927033.89
      1476537.28      6927089.44      1477471.31      6926988.75
      1478009.55      6926891.52
#Sta/Elev= 30
  3742.1 1763.15  4005.4 1762.38  4086.4 1763.00  4179.5 1762.53  4672.3 1763.90
  4849.2 1762.04  4954.7 1759.07  5007.9 1759.17  5017.2 1758.83  5017.7 1758.33
  5022.7 1758.33  5023.2 1758.83  5143.6 1761.67  5221.3 1762.45  5455.4 1763.13
  5492.9 1763.19  5533.1 1764.15  5623.7 1764.38  5674.0 1765.37  5754.6 1765.74
  5802.2 1767.16  5876.5 1767.32  5903.3 1768.10  5968.0 1769.13  5988.3 1769.99
  6008.6 1769.54  6018.8 1770.13  6105.6 1771.36  6181.4 1772.64  6287.6 1775.98
#Mann=10,-1,0
  3742.1   0.045       0  5007.9    0.07       0  5017.2   0.045       0
  5023.2    0.07       0  5221.3   0.045       0  5455.4    0.07       0
  5623.7   0.045       0  5802.2    0.16       0  5903.3   0.035       0
  6105.6    0.07       0
Bank Sta=5017.2,5023.2
Exp/Cntr=0.3,0.1

Type RM Length L Ch R = 1,2637,383,383,383
BEGIN DESCRIPTION:
Mapping XS 3b167b3a
END DESCRIPTION:
XS GIS Cut Line= 4
      1475780.32      6927276.93      1476078.95      6927412.36
      1477474.78      6927464.44      1478058.12      6927197.07
#Sta/Elev= 30
  3990.6 1761.99  4444.6 1761.45  4704.8 1762.16  4824.9 1760.99  4854.9 1761.33
  4956.1 1758.09  5002.0 1756.41  5002.5 1755.91  5007.5 1755.91  5008.0 1756.41
  5084.2 1759.50  5145.2 1761.57  5155.1 1760.72  5205.2 1761.23  5225.2 1762.52
  5265.2 1761.58  5479.7 1762.52  5888.0 1764.10  5984.2 1765.35  6035.4 1765.71
  6067.6 1767.10  6094.6 1767.22  6121.9 1767.59  6150.4 1768.92  6188.6 1768.98
  6232.6 1770.72  6265.4 1770.65  6315.3 1772.17  6331.4 1772.66  6357.0 1773.68
#Mann=11,-1,0
  3990.6   0.045       0  4956.1    0.07       0  5002.0    0.07       0
  5008.0    0.07       0  5084.2   0.045       0  5479.7    0.07       0
  5888.0   0.035       0  5984.2    0.07       0  6094.6   0.045       0
  6315.3    0.07       0  6331.4   0.035       0
Bank Sta=5002,5008
Exp/Cntr=0.3,0.1

Type RM Length L Ch R = 1,2254,716,716,716
BEGIN DESCRIPTION:
Mapping XS 83883426
END DESCRIPTION:
XS GIS Cut Line= 4
      1475690.07      6927724.86      1476210.89      6927783.89
      1477759.50      6927579.02      1478161.14      6927398.98
#Sta/Elev= 30
  4026.6 1762.49  4716.3 1761.41  4867.6 1759.82  4887.8 1760.88  4907.9 1760.07
  4936.0 1760.57  4985.3 1755.74  4985.8 1755.24  4992.0 1755.74  5014.4 1755.86
  5039.1 1758.76  5131.4 1759.46  5140.0 1759.42  5150.0 1760.62  5160.1 1758.58
  5166.3 1759.57  5171.4 1758.65  5180.3 1761.44  5190.4 1760.12  5210.6 1759.61
  5263.5 1760.22  5452.7 1762.44  5622.4 1762.74  5686.9 1762.75  6065.6 1764.19
  6193.0 1765.74  6274.2 1766.76  6299.3 1767.09  6534.6 1770.63  6553.0 1771.11
#Mann=12,-1,0
  4026.6   0.045       0  4985.3   0.045       0  4992.0   0.045       0
  5131.4    0.07       0  5263.5   0.045       0  5622.4    0.07       0
  5686.9   0.035       0  6065.6    0.07       0  6193.0   0.035       0
  6274.2    0.07       0  6299.3   0.045       0  6534.6    0.07       0
Bank Sta=4985.3,4992
Exp/Cntr=0.3,0.1

Type RM Length L Ch R = 1,1538,612,612,612
BEGIN DESCRIPTION:
Mapping XS 23bdeeb0
END DESCRIPTION:
XS GIS Cut Line= 4
      1475749.05      6928019.98      1476509.50      6928391.52
      1477377.56      6928252.64      1478285.94      6928082.75
#Sta/Elev= 30
  3761.8 1762.63  4347.2 1761.84  4715.0 1760.53  4735.3 1760.53  4765.6 1761.81
  4806.2 1760.56  4913.9 1759.42  4947.9 1757.67  4975.9 1753.21  4995.2 1750.94
  4995.7 1750.44  5001.4 1750.44  5001.9 1750.94  5008.7 1752.23  5038.0 1754.41
  5043.0 1755.33  5069.5 1754.63  5105.0 1757.60  5150.5 1759.12  5160.6 1760.02
  5209.3 1759.90  5249.4 1760.51  5413.8 1763.66  5867.6 1763.64  6057.5 1764.21
  6134.0 1764.48  6217.1 1765.68  6297.3 1765.93  6349.4 1767.37  6411.4 1767.77
#Mann=8,-1,0
  3761.8   0.045       0  4995.2   0.045       0  5001.9   0.045       0
  5209.3    0.07       0  5249.4   0.045       0  5867.6    0.07       0
  6057.5   0.045       0  6134.0    0.07       0
Bank Sta=4995.2,5001.9
Exp/Cntr=0.3,0.1

Type RM Length L Ch R = 1,926,657,657,657
BEGIN DESCRIPTION:
Mapping XS a916ef32
END DESCRIPTION:
XS GIS Cut Line= 4
      1475815.03      6928280.40      1476495.61      6928794.30
      1477637.97      6928849.86      1478366.46      6928232.37
#Sta/Elev= 30
  3448.3 1762.35  3938.5 1761.45  4330.5 1761.50  4360.6 1762.98  4371.3 1762.21
  4390.6 1761.47  4509.7 1760.98  4586.2 1760.75  4683.8 1760.43  4821.1 1759.68
  4861.2 1758.98  4911.2 1756.40  4951.3 1756.72  4961.3 1755.29  4988.5 1748.96
  4997.9 1747.74  4998.4 1747.24  5004.8 1747.74  5021.3 1755.09  5031.4 1756.57
  5071.4 1755.13  5181.5 1759.86  5200.1 1758.99  5440.8 1762.53  5574.2 1763.54
  5827.1 1763.20  6175.0 1764.35  6317.1 1766.16  6352.2 1767.39  6399.8 1767.47
#Mann=10,-1,0
  3448.3   0.045       0  4371.3    0.16       0  4509.7   0.045       0
  4586.2    0.16       0  4683.8   0.045       0  4988.5    0.16       0
  4997.9    0.07       0  5004.8    0.16       0  5200.1   0.045       0
  5574.2    0.07       0
Bank Sta=4997.9,5004.8
Exp/Cntr=0.3,0.1

Type RM Length L Ch R = 1,269,0,0,0
BEGIN DESCRIPTION:
NC Unknown Stream 02 1.0
END DESCRIPTION:
XS GIS Cut Line= 4
      1475863.69      6928617.23      1476912.28      6929429.72
      1477519.92      6929443.61      1478455.02      6928237.97
#Sta/Elev= 30
  3431.1 1761.62  4203.0 1761.22  4229.6 1760.52  4238.3 1759.33  4280.3 1758.78
  4331.0 1758.14  4387.7 1759.15  4498.6 1757.96  4547.2 1757.81  4680.1 1757.13
  4755.3 1757.92  4812.4 1757.78  4950.4 1756.38  4960.4 1755.35  4970.4 1751.91
  4976.9 1743.76  4977.4 1743.26  4983.9 1743.76  4990.4 1743.79  5000.4 1748.51
  5010.4 1750.91  5030.4 1752.76  5040.4 1751.89  5060.4 1756.91  5150.5 1760.36
  5208.3 1759.86  5486.4 1763.06  5888.2 1763.15  6577.0 1764.30  6891.2 1768.63
#Mann=11,-1,0
  3431.1   0.045       0  4229.6    0.16       0  4280.3   0.045       0
  4498.6    0.16       0  4547.2   0.045       0  4755.3    0.16       0
  4812.4    0.12       0  4976.9    0.07       0  4983.9    0.12       0
  5208.3   0.045       0  5888.2    0.07       0
Bank Sta=4976.9,4983.9
Exp/Cntr=0.3,0.1

Chan Stop Cuts=-1