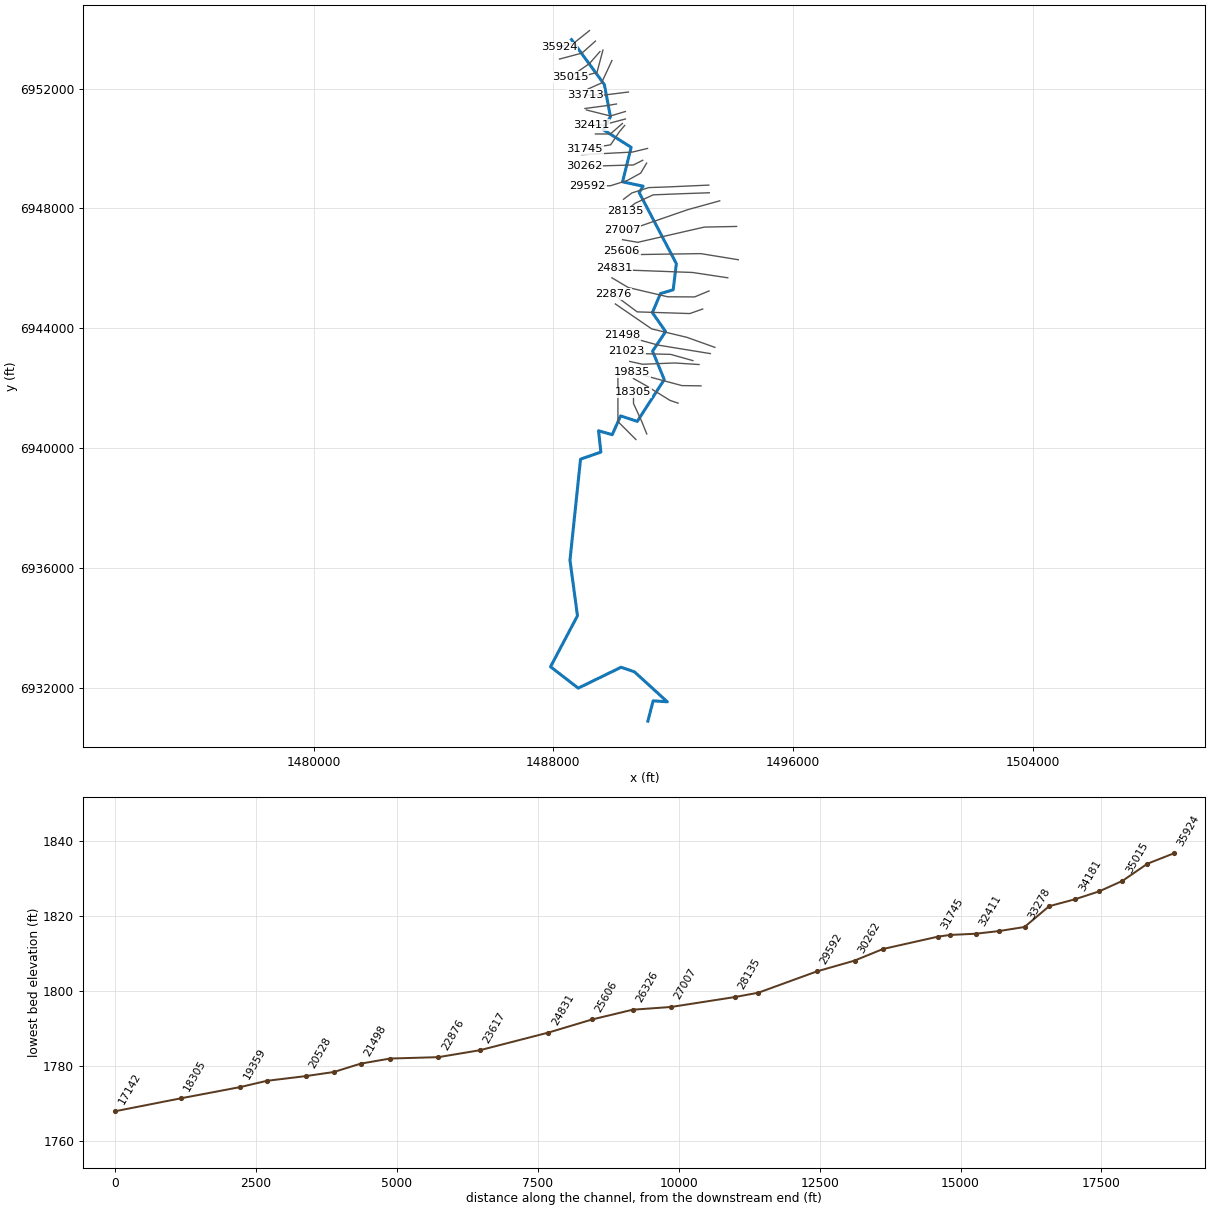
--- NC Unknown Stream 05.prj (project) ---

Proj Title=NC Unknown Stream 05 Base Level Engineering
Current Plan=p01
Default Exp/Contr=0.3,0.1
English Units
Geom File=g01
Flow File=f01
Plan File=p01
BEGIN DESCRIPTION:
NC Unknown Stream 05
END DESCRIPTION:

--- NC Unknown Stream 05.p01 (plan) ---

Plan Title=Multiple Run
Short Identifier=Multiple
Geom File=g01
Flow File=f01
Subcritical Flow
K Sum by GR= 0
Std Step Tol= 0.01
Critical Tol= 0.01
Num of Std Step Trials= 20
Max Error Tol= 0.3
Flow Tol Ratio= 0.001
Split Flow NTrial= 30
Split Flow Tol= 0.02
Split Flow Ratio= 0.02
Log Output Level= 0
Friction Slope Method= 1
Unsteady Friction Slope Method= 2
Unsteady Bridges Friction Slope Method= 1
Parabolic Critical Depth
Global Vel Dist=  1 , 1 , 1
Global Log Level= 0
CheckData=True
Encroach Param= -1, 0, 0, 0
BEGIN DESCRIPTION:
Multiple Run
END DESCRIPTION:

--- NC Unknown Stream 05.f01 (steady flow) ---

Flow Title=Multiple
Number of Profiles=7
Profile Names=10-year,25-year,50-year,1pct_min,100-year,1pct_plu,500-year
River Rch & RM= NC Unknown Strea,Reach-1,35924
     316     445     553     342     682    1361    1049
River Rch & RM= NC Unknown Strea,Reach-1,35459
     335     471     586     362     722    1441    1110
River Rch & RM= NC Unknown Strea,Reach-1,32830
     496     714     899     563    1123    2241    1773
River Rch & RM= NC Unknown Strea,Reach-1,31958
     561     807    1015     634    1265    2525    1989
River Rch & RM= NC Unknown Strea,Reach-1,24831
     627     905    1142     715    1426    2846    2252
River Rch & RM= NC Unknown Strea,Reach-1,22022
     687     995    1260     790    1577    3146    2502
River Rch & RM= NC Unknown Strea,Reach-1,21498
     752    1094    1389     873    1743    3477    2779
River Rch & RM= NC Unknown Strea,Reach-1,21023
     956    1399    1781    1123    2241    4472    3592
River Rch & RM= NC Unknown Strea,Reach-1,12061
    1022    1496    1906    1202    2398    4785    3845
River Rch & RM= NC Unknown Strea,Reach-1,7474
     993    1448    1842    1159    2312    4613    3690
Boundary for River Rch & Prof#=NC Unknown Strea,Reach-1,1
Up Type=0
Dn Type=3
Dn Slope=0.001
Boundary for River Rch & Prof#=NC Unknown Strea,Reach-1,2
Up Type=0
Dn Type=3
Dn Slope=0.001
Boundary for River Rch & Prof#=NC Unknown Strea,Reach-1,3
Up Type=0
Dn Type=3
Dn Slope=0.001
Boundary for River Rch & Prof#=NC Unknown Strea,Reach-1,4
Up Type=0
Dn Type=3
Dn Slope=0.001
Boundary for River Rch & Prof#=NC Unknown Strea,Reach-1,5
Up Type=0
Dn Type=3
Dn Slope=0.001
Boundary for River Rch & Prof#=NC Unknown Strea,Reach-1,6
Up Type=0
Dn Type=3
Dn Slope=0.001
Boundary for River Rch & Prof#=NC Unknown Strea,Reach-1,7
Up Type=0
Dn Type=3
Dn Slope=0.001

--- NC Unknown Stream 05.g01 (geometry) ---

Geom Title=Existing Conditions

River Reach=NC Unknown Strea,Reach-1
Reach XY= 30
      1488605.00      6953638.00      1489701.56      6952136.78
      1489905.54      6951063.12      1489660.35      6950635.30
      1490597.47      6950041.19      1490308.54      6948889.45
      1490997.52      6948744.04      1490864.24      6948531.45
      1492105.30      6946158.18      1491999.66      6945285.26
      1491574.61      6945158.68      1491305.24      6944522.78
      1491747.42      6943891.35      1491311.45      6943237.71
      1491701.69      6942289.74      1490800.41      6940893.17
      1490244.57      6941077.07      1489965.44      6940448.93
      1489507.93      6940580.03      1489585.95      6939867.61
      1488907.05      6939632.16      1488554.64      6936258.15
      1488804.50      6934403.21      1487905.37      6932703.16
      1488829.88      6931987.88      1490260.89      6932686.04
      1490707.45      6932532.54      1491803.26      6931531.84
      1491331.03      6931565.50      1491155.00      6930888.00

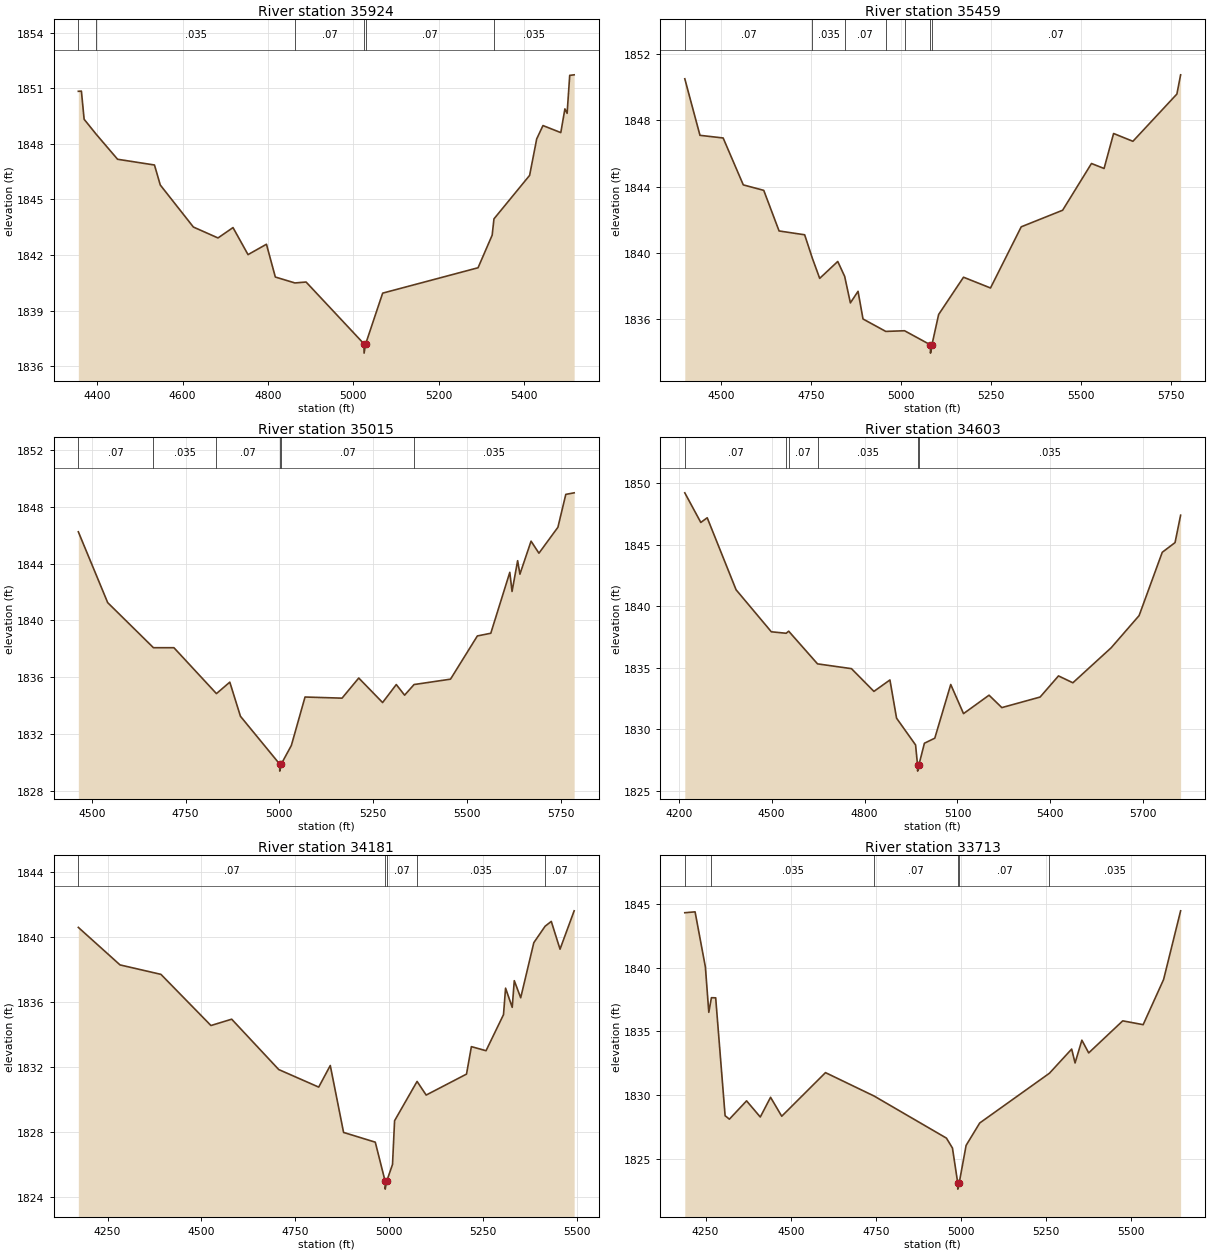
Type RM Length L Ch R = 1,35924,465,465,465
BEGIN DESCRIPTION:
NC Unknown Stream 05 44.0
END DESCRIPTION:
XS GIS Cut Line= 3
      1489205.00      6953938.00      1488705.00      6953538.00
      1488205.03      6953388.01
#Sta/Elev= 30
  4355.4 1850.84  4362.6 1850.85  4369.0 1849.33  4397.3 1848.52  4447.4 1847.17
  4533.9 1846.86  4547.5 1845.78  4625.1 1843.51  4682.8 1842.92  4718.0 1843.48
  4753.2 1842.02  4796.4 1842.58  4817.2 1840.81  4863.1 1840.49  4889.3 1840.54
  5025.0 1837.20  5025.3 1836.70  5029.0 1837.20  5068.8 1839.94  5292.4 1841.31
  5325.5 1843.07  5329.7 1843.95  5413.3 1846.30  5429.9 1848.27  5444.6 1848.99
  5486.4 1848.61  5496.0 1849.89  5501.2 1849.65  5507.3 1851.70  5517.7 1851.73
#Mann=6,-1,0
  4355.4    0.07       0  4397.3   0.035       0  4863.1    0.07       0
  5025.0    0.07       0  5029.0    0.07       0  5329.7   0.035       0
Bank Sta=5025,5029
Exp/Cntr=0.3,0.1

Type RM Length L Ch R = 1,35459,444,444,444
BEGIN DESCRIPTION:
NC Unknown Stream 05 43.0
END DESCRIPTION:
XS GIS Cut Line= 3
      1489404.98      6953587.99      1488955.00      6953188.00
      1488204.97      6952987.99
#Sta/Elev= 30
  4398.4 1850.50  4440.6 1847.09  4505.0 1846.93  4561.0 1844.10  4617.9 1843.77
  4660.5 1841.32  4731.6 1841.09  4752.9 1839.68  4773.4 1838.46  4823.6 1839.48
  4842.8 1838.58  4858.7 1836.98  4880.0 1837.68  4893.8 1836.01  4957.1 1835.26
  5009.3 1835.30  5081.2 1834.45  5081.4 1833.95  5085.4 1834.45  5104.0 1836.28
  5173.2 1838.53  5248.2 1837.88  5333.6 1841.57  5448.7 1842.57  5528.9 1845.39
  5563.9 1845.09  5590.4 1847.20  5644.1 1846.73  5766.3 1849.58  5776.7 1850.74
#Mann=7,-1,0
  4398.4    0.07       0  4752.9   0.035       0  4842.8    0.07       0
  4957.1   0.035       0  5009.3    0.07       0  5081.2   0.035       0
  5085.4    0.07       0
Bank Sta=5081.2,5085.4
Exp/Cntr=0.3,0.1

Type RM Length L Ch R = 1,35015,412,412,412
BEGIN DESCRIPTION:
NC Unknown Stream 05 42.0
END DESCRIPTION:
XS GIS Cut Line= 3
      1489555.01      6953238.01      1489205.00      6952838.00
      1488554.99      6952388.00
#Sta/Elev= 30
  4464.0 1846.26  4542.3 1841.26  4664.3 1838.08  4718.9 1838.08  4832.3 1834.84
  4867.9 1835.65  4896.3 1833.24  5000.8 1829.87  5001.1 1829.37  5005.1 1829.87
  5032.0 1831.18  5068.5 1834.60  5167.2 1834.52  5211.7 1835.94  5275.3 1834.21
  5311.8 1835.48  5334.0 1834.73  5359.2 1835.48  5456.4 1835.86  5528.0 1838.91
  5563.8 1839.10  5614.5 1843.40  5620.5 1842.05  5635.4 1844.22  5641.5 1843.27
  5671.2 1845.60  5692.2 1844.75  5742.8 1846.58  5763.8 1848.90  5786.1 1849.01
#Mann=6,-1,0
  4464.0    0.07       0  4664.3   0.035       0  4832.3    0.07       0
  5000.8    0.07       0  5005.1    0.07       0  5359.2   0.035       0
Bank Sta=5000.8,5005.1
Exp/Cntr=0.3,0.1

Type RM Length L Ch R = 1,34603,422,422,422
BEGIN DESCRIPTION:
NC Unknown Stream 05 41.0
END DESCRIPTION:
XS GIS Cut Line= 3
      1489654.99      6953287.96      1489455.00      6952538.00
      1488654.99      6952338.00
#Sta/Elev= 30
  4219.7 1849.23  4271.4 1846.82  4292.1 1847.20  4385.3 1841.34  4499.1 1837.92
  4547.1 1837.80  4555.1 1837.97  4648.2 1835.31  4757.8 1834.92  4830.3 1833.07
  4882.0 1834.00  4903.4 1830.89  4964.8 1828.71  4971.1 1827.08  4971.4 1826.58
  4975.4 1827.08  4993.3 1828.85  5026.8 1829.26  5078.3 1833.63  5119.6 1831.26
  5202.0 1832.76  5243.3 1831.75  5366.9 1832.61  5426.2 1834.33  5472.6 1833.77
  5596.3 1836.62  5686.5 1839.24  5761.2 1844.39  5802.5 1845.18  5820.5 1847.41
#Mann=6,-1,0
  4219.7    0.07       0  4547.1   0.035       0  4555.1    0.07       0
  4648.2   0.035       0  4971.1   0.035       0  4975.4   0.035       0
Bank Sta=4971.1,4975.4
Exp/Cntr=0.3,0.1

Type RM Length L Ch R = 1,34181,468,468,468
BEGIN DESCRIPTION:
NC Unknown Stream 05 40.0
END DESCRIPTION:
XS GIS Cut Line= 3
      1489954.99      6952937.98      1489605.00      6952188.00
      1489154.98      6951987.99
#Sta/Elev= 30
  4172.1 1840.61  4283.2 1838.30  4392.0 1837.72  4525.2 1834.57  4580.4 1834.96
  4705.7 1831.86  4812.1 1830.78  4842.9 1832.11  4878.3 1827.99  4962.7 1827.39
  4988.8 1825.00  4989.1 1824.50  4993.3 1825.00  5008.6 1826.02  5014.1 1828.71
  5074.0 1831.13  5098.2 1830.29  5205.6 1831.58  5218.6 1833.27  5257.6 1833.02
  5304.1 1835.24  5309.6 1836.87  5327.3 1835.69  5332.8 1837.33  5349.9 1836.28
  5384.8 1839.67  5414.8 1840.68  5431.3 1840.98  5454.6 1839.27  5492.2 1841.63
#Mann=5,-1,0
  4172.1    0.07       0  4988.8    0.07       0  4993.3    0.07       0
  5074.0   0.035       0  5414.8    0.07       0
Bank Sta=4988.8,4993.3
Exp/Cntr=0.3,0.1

Type RM Length L Ch R = 1,33713,435,435,435
BEGIN DESCRIPTION:
NC Unknown Stream 05 39.0
END DESCRIPTION:
XS GIS Cut Line= 3
      1490505.00      6951888.00      1489705.00      6951788.00
      1489055.03      6951788.00
#Sta/Elev= 30
  4189.0 1844.33  4219.2 1844.40  4249.5 1840.06  4259.5 1836.50  4267.2 1837.65
  4279.7 1837.64  4307.4 1828.37  4320.0 1828.10  4370.4 1829.54  4410.7 1828.27
  4440.9 1829.82  4473.7 1828.33  4602.2 1831.76  4744.9 1829.92  4957.4 1826.61
  4975.1 1825.83  4990.5 1823.10  4990.8 1822.60  4995.0 1823.10  5015.2 1826.04
  5055.2 1827.80  5259.9 1831.71  5325.2 1833.61  5335.2 1832.52  5355.2 1834.31
  5375.2 1833.31  5475.2 1835.83  5535.2 1835.53  5595.2 1839.08  5645.2 1844.48
#Mann=6,-1,0
  4189.0    0.07       0  4267.2   0.035       0  4744.9    0.07       0
  4990.5    0.07       0  4995.0    0.07       0  5259.9   0.035       0
Bank Sta=4990.5,4995
Exp/Cntr=0.3,0.1

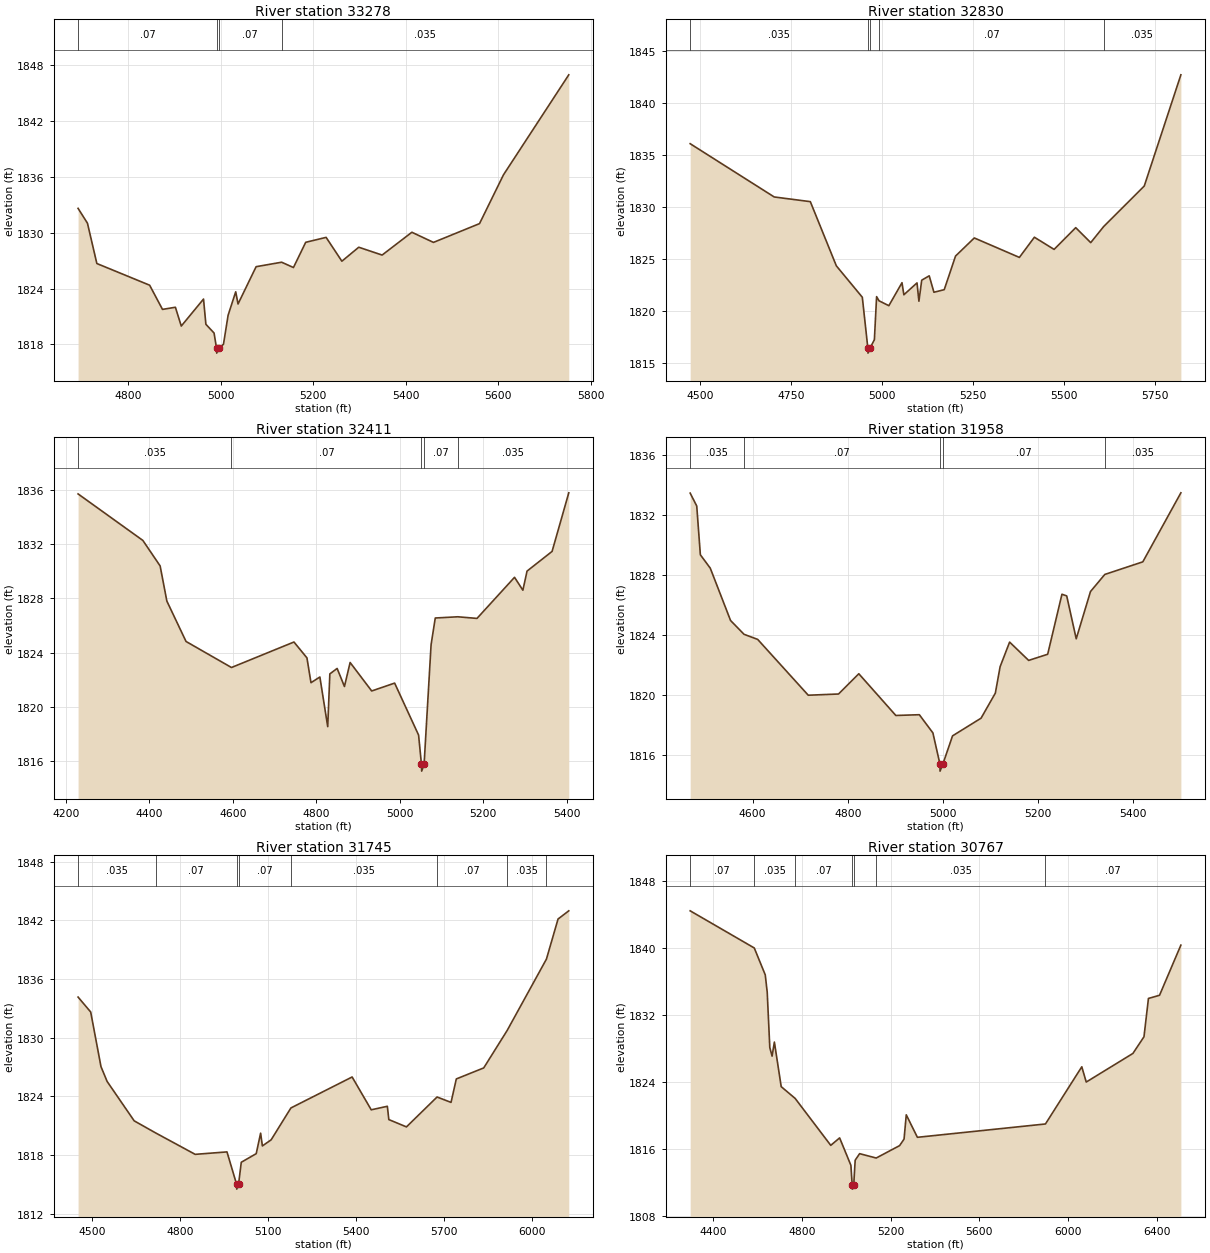
Type RM Length L Ch R = 1,33278,448,448,448
BEGIN DESCRIPTION:
NC Unknown Stream 05 38.0
END DESCRIPTION:
XS GIS Cut Line= 3
      1490105.05      6951488.01      1489805.00      6951438.00
      1489055.02      6951338.00
#Sta/Elev= 30
  4691.5 1832.63  4711.8 1831.03  4732.1 1826.70  4846.2 1824.37  4874.0 1821.77
  4901.9 1822.00  4914.6 1819.98  4962.7 1822.88  4967.8 1820.17  4985.5 1819.23
  4990.9 1817.57  4991.2 1817.07  4995.4 1817.57  5005.8 1818.02  5015.9 1821.15
  5032.3 1823.66  5037.3 1822.35  5076.4 1826.36  5131.6 1826.84  5157.1 1826.27
  5183.6 1828.98  5227.7 1829.51  5261.8 1826.95  5298.3 1828.45  5348.8 1827.61
  5413.1 1830.06  5459.8 1828.97  5559.4 1830.99  5611.1 1836.23  5752.3 1846.98
#Mann=4,-1,0
  4691.5    0.07       0  4990.9    0.07       0  4995.4    0.07       0
  5131.6   0.035       0
Bank Sta=4990.9,4995.4
Exp/Cntr=0.3,0.1

Type RM Length L Ch R = 1,32830,419,419,419
BEGIN DESCRIPTION:
NC Unknown Stream 05 37.0
END DESCRIPTION:
XS GIS Cut Line= 3
      1490405.00      6951238.00      1489905.00      6951088.00
      1489105.03      6951287.99
#Sta/Elev= 30
  4473.6 1836.12  4704.2 1831.00  4803.3 1830.55  4874.7 1824.38  4946.0 1821.36
  4961.1 1816.49  4961.6 1815.99  4967.4 1816.49  4979.1 1817.28  4985.2 1821.42
  4991.8 1821.02  5018.8 1820.55  5054.9 1822.76  5060.0 1821.60  5096.1 1822.74
  5101.3 1820.98  5109.0 1823.00  5129.6 1823.42  5142.5 1821.84  5170.8 1822.09
  5201.8 1825.32  5253.3 1827.06  5377.0 1825.19  5418.2 1827.13  5472.3 1825.96
  5531.6 1828.05  5572.8 1826.61  5608.4 1828.16  5719.7 1832.05  5820.2 1842.74
#Mann=5,-1,0
  4473.6   0.035       0  4961.1    0.07       0  4967.4   0.035       0
  4991.8    0.07       0  5608.4   0.035       0
Bank Sta=4961.1,4967.4
Exp/Cntr=0.3,0.1

Type RM Length L Ch R = 1,32411,453,453,453
BEGIN DESCRIPTION:
NC Unknown Stream 05 36.0
END DESCRIPTION:
XS GIS Cut Line= 3
      1490405.04      6950988.01      1489655.00      6950788.00
      1489255.05      6950788.00
#Sta/Elev= 30
  4228.8 1835.71  4384.1 1832.28  4425.5 1830.40  4441.6 1827.81  4487.6 1824.83
  4596.5 1822.91  4746.3 1824.79  4777.4 1823.62  4787.1 1821.79  4808.4 1822.21
  4827.2 1818.55  4832.3 1822.44  4849.8 1822.84  4867.3 1821.51  4880.9 1823.28
  4932.6 1821.18  4987.6 1821.76  5045.0 1817.93  5051.9 1815.77  5052.4 1815.27
  5058.2 1815.77  5075.0 1824.60  5085.0 1826.56  5138.9 1826.65  5185.0 1826.53
  5275.0 1829.56  5295.0 1828.61  5305.0 1830.02  5365.0 1831.47  5405.0 1835.79
#Mann=5,-1,0
  4228.8   0.035       0  4596.5    0.07       0  5051.9    0.07       0
  5058.2    0.07       0  5138.9   0.035       0
Bank Sta=5051.9,5058.2
Exp/Cntr=0.3,0.1

Type RM Length L Ch R = 1,31958,213,213,213
BEGIN DESCRIPTION:
NC Unknown Stream 05 35.0
END DESCRIPTION:
XS GIS Cut Line= 3
      1490305.00      6950838.00      1489905.00      6950488.00
      1489405.01      6950488.00
#Sta/Elev= 30
  4468.7 1833.48  4482.5 1832.62  4490.1 1829.37  4510.9 1828.48  4553.6 1824.99
  4581.9 1824.07  4610.6 1823.73  4716.9 1820.01  4780.5 1820.09  4823.2 1821.44
  4901.0 1818.66  4950.4 1818.71  4978.9 1817.50  4993.5 1815.45  4994.0 1814.95
  5000.2 1815.45  5020.2 1817.30  5080.2 1818.48  5110.2 1820.15  5120.2 1821.91
  5140.2 1823.55  5180.2 1822.33  5220.2 1822.74  5250.2 1826.74  5260.2 1826.63
  5280.2 1823.77  5310.2 1826.92  5340.3 1828.06  5420.2 1828.90  5500.2 1833.50
#Mann=5,-1,0
  4468.7   0.035       0  4581.9    0.07       0  4993.5    0.07       0
  5000.2    0.07       0  5340.3   0.035       0
Bank Sta=4993.5,5000.2
Exp/Cntr=0.3,0.1

Type RM Length L Ch R = 1,31745,978,978,978
BEGIN DESCRIPTION:
Mapping XS 67f0543d
END DESCRIPTION:
XS GIS Cut Line= 4
      1490380.22      6950772.92      1490206.61      6950564.59
      1489911.47      6950126.22      1489048.92      6949978.85
#Sta/Elev= 30
  4451.4 1834.16  4494.5 1832.63  4529.6 1827.04  4550.4 1825.53  4642.9 1821.49
  4715.7 1820.26  4851.1 1818.06  4959.6 1818.31  4992.4 1815.00  4992.9 1814.50
  4999.1 1815.00  5008.4 1817.25  5059.4 1818.13  5074.4 1820.23  5080.4 1818.92
  5110.4 1819.55  5177.8 1822.81  5386.7 1825.98  5451.9 1822.62  5506.9 1822.98
  5512.0 1821.62  5572.1 1820.87  5676.6 1823.93  5724.3 1823.38  5742.3 1825.78
  5835.9 1826.91  5915.8 1830.74  6049.9 1838.05  6089.5 1842.15  6126.1 1842.99
#Mann=8,-1,0
  4451.4   0.035       0  4715.7    0.07       0  4992.4    0.07       0
  4999.1    0.07       0  5177.8   0.035       0  5676.6    0.07       0
  5915.8   0.035       0  6049.9    0.07       0
Bank Sta=4992.4,4999.1
Exp/Cntr=0.3,0.1

Type RM Length L Ch R = 1,30767,505,505,505
BEGIN DESCRIPTION:
Mapping XS 65b5cdc3
END DESCRIPTION:
XS GIS Cut Line= 3
      1491144.08      6950004.68      1490636.29      6949883.16
      1488948.95      6949796.41
#Sta/Elev= 30
  4297.0 1844.39  4585.9 1839.96  4635.4 1836.75  4644.2 1834.69  4655.9 1828.08
  4666.2 1827.06  4676.5 1828.74  4707.3 1823.42  4770.1 1822.02  4930.6 1816.42
  4970.6 1817.31  5021.4 1814.04  5027.2 1811.70  5027.7 1811.20  5034.1 1811.70
  5040.7 1814.65  5060.7 1815.43  5135.5 1814.91  5241.0 1816.39  5261.0 1817.17
  5271.0 1820.06  5321.1 1817.38  5898.3 1818.97  6062.1 1825.79  6082.1 1823.97
  6292.4 1827.38  6342.4 1829.37  6362.5 1833.94  6412.5 1834.32  6508.7 1840.30
#Mann=7,-1,0
  4297.0    0.07       0  4585.9   0.035       0  4770.1    0.07       0
  5027.2    0.07       0  5034.1    0.07       0  5135.5   0.035       0
  5898.3    0.07       0
Bank Sta=5027.2,5034.1
Exp/Cntr=0.3,0.1

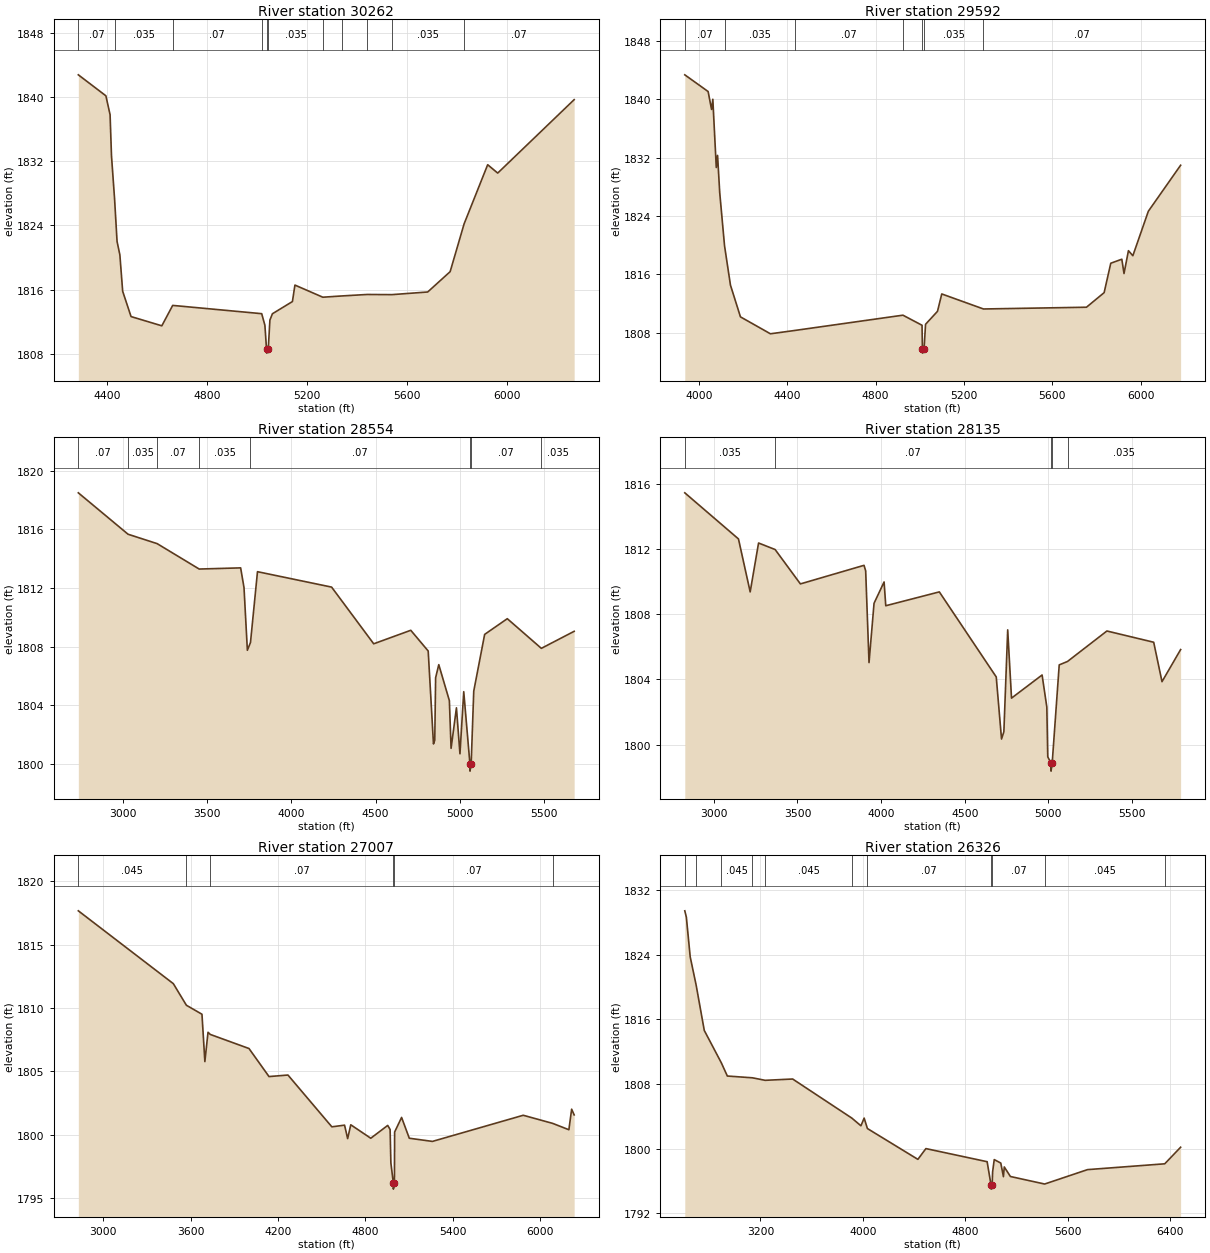
Type RM Length L Ch R = 1,30262,670,670,670
BEGIN DESCRIPTION:
Mapping XS 79028c96
END DESCRIPTION:
XS GIS Cut Line= 3
      1490983.50      6949609.72      1490671.02      6949453.47
      1489039.58      6949405.75
#Sta/Elev= 30
  4286.5 1842.74  4396.6 1840.13  4413.4 1837.77  4419.0 1832.67  4431.3 1827.32
  4441.3 1821.99  4452.5 1820.33  4463.7 1815.80  4497.2 1812.65  4620.2 1811.50
  4663.6 1814.04  5019.3 1813.01  5032.1 1811.57  5038.6 1808.60  5039.1 1808.10
  5045.5 1808.60  5052.1 1812.21  5062.1 1813.00  5142.1 1814.52  5152.1 1816.57
  5263.6 1815.06  5341.3 1815.22  5440.3 1815.40  5539.3 1815.38  5682.7 1815.71
  5772.4 1818.24  5828.2 1824.19  5922.4 1831.55  5962.5 1830.51  6268.0 1839.65
#Mann=11,-1,0
  4286.5    0.07       0  4431.3   0.035       0  4663.6    0.07       0
  5019.3   0.035       0  5038.6    0.07       0  5045.5   0.035       0
  5263.6    0.07       0  5341.3   0.035       0  5440.3    0.07       0
  5539.3   0.035       0  5828.2    0.07       0
Bank Sta=5038.6,5045.5
Exp/Cntr=0.3,0.1

Type RM Length L Ch R = 1,29592,1038,1038,1038
BEGIN DESCRIPTION:
Mapping XS 7d38dea4
END DESCRIPTION:
XS GIS Cut Line= 5
      1491113.74      6949514.27      1490914.07      6949180.04
      1490471.36      6948936.98      1489907.13      6948759.03
      1489148.78      6948750.36
#Sta/Elev= 30
  3936.6 1843.35  4042.2 1841.06  4057.7 1838.61  4063.5 1840.00  4079.1 1830.65
  4084.9 1832.31  4094.7 1827.21  4116.5 1819.92  4143.3 1814.53  4188.5 1810.18
  4324.2 1807.86  4433.2 1808.31  4924.0 1810.41  5010.5 1809.03  5012.2 1805.71
  5012.7 1805.21  5019.5 1805.71  5026.4 1809.16  5080.5 1810.94  5099.8 1813.32
  5288.6 1811.26  5754.8 1811.50  5834.8 1813.50  5864.8 1817.53  5914.8 1818.08
  5924.8 1816.12  5944.8 1819.25  5964.8 1818.56  6034.8 1824.65  6181.0 1830.96
#Mann=7,-1,0
  3936.6    0.07       0  4116.5   0.035       0  4433.2    0.07       0
  4924.0   0.035       0  5012.2   0.035       0  5019.5   0.035       0
  5288.6    0.07       0
Bank Sta=5012.2,5019.5
Exp/Cntr=0.3,0.1

Type RM Length L Ch R = 1,28554,419,419,419
BEGIN DESCRIPTION:
Mapping XS fdac69a1
END DESCRIPTION:
XS GIS Cut Line= 5
      1493188.34      6948780.73      1491725.70      6948715.63
      1491187.51      6948698.27      1490623.27      6948520.31
      1490342.64      6948308.49
#Sta/Elev= 30
  2733.7 1818.48  3029.2 1815.66  3202.0 1815.02  3451.8 1813.29  3698.0 1813.37
  3718.0 1812.03  3738.0 1807.76  3756.5 1808.29  3798.1 1813.11  4238.5 1812.06
  4488.6 1808.20  4708.8 1809.12  4812.3 1807.71  4843.7 1801.38  4851.3 1801.63
  4856.5 1805.89  4875.2 1806.78  4938.1 1804.33  4948.3 1801.08  4980.1 1803.84
  5001.0 1800.71  5023.5 1804.94  5060.2 1800.03  5060.7 1799.53  5067.6 1800.03
  5083.0 1804.98  5147.7 1808.84  5282.3 1809.91  5484.6 1807.89  5679.5 1809.05
#Mann=8,-1,0
  2733.7    0.07       0  3029.2   0.035       0  3202.0    0.07       0
  3451.8   0.035       0  3756.5    0.07       0  5060.2    0.07       0
  5067.6    0.07       0  5484.6   0.035       0
Bank Sta=5060.2,5067.6
Exp/Cntr=0.3,0.1

Type RM Length L Ch R = 1,28135,1128,1128,1128
BEGIN DESCRIPTION:
Mapping XS f0d25df1
END DESCRIPTION:
XS GIS Cut Line= 6
      1493205.72      6948524.65      1492315.98      6948494.27
      1491330.74      6948455.21      1490727.44      6948173.09
      1490429.41      6947935.40      1490409.03      6947900.03
#Sta/Elev= 30
  2826.3 1815.45  3147.2 1812.62  3217.2 1809.37  3267.3 1812.37  3366.3 1811.97
  3517.4 1809.86  3897.7 1811.00  3907.7 1810.66  3927.7 1805.03  3957.7 1808.67
  4017.8 1809.98  4027.8 1808.52  4348.0 1809.37  4688.3 1804.15  4719.9 1800.34
  4733.9 1800.79  4756.8 1807.04  4779.6 1802.85  4962.4 1804.27  4990.7 1802.30
  4996.3 1799.25  5015.4 1798.87  5015.9 1798.37  5022.8 1798.87  5064.8 1804.89
  5114.3 1805.10  5349.9 1806.97  5629.6 1806.28  5679.3 1803.86  5790.6 1805.83
#Mann=5,-1,0
  2826.3   0.035       0  3366.3    0.07       0  5015.4    0.07       0
  5022.8    0.07       0  5114.3   0.035       0
Bank Sta=5015.4,5022.8
Exp/Cntr=0.3,0.1

Type RM Length L Ch R = 1,27007,681,681,681
BEGIN DESCRIPTION:
Mapping XS b3a5f962
END DESCRIPTION:
XS GIS Cut Line= 4
      1493552.98      6948255.56      1492485.25      6947960.42
      1490614.59      6947313.72      1490298.89      6947292.09
#Sta/Elev= 30
  2829.1 1817.66  3481.3 1811.92  3570.8 1810.22  3677.8 1809.51  3697.7 1805.78
  3719.3 1808.09  3734.8 1807.92  4000.6 1806.81  4138.0 1804.60  4268.0 1804.72
  4569.2 1800.64  4656.6 1800.77  4677.8 1799.71  4699.2 1800.80  4836.5 1799.74
  4952.9 1800.75  4969.2 1800.43  4974.5 1797.80  4991.2 1796.23  4991.7 1795.73
  4998.8 1796.23  5000.3 1800.23  5048.1 1801.38  5101.0 1799.74  5259.7 1799.49
  5883.2 1801.55  6085.3 1800.91  6196.4 1800.41  6215.4 1802.03  6232.6 1801.58
#Mann=6,-1,0
  2829.1   0.045       0  3570.8   0.035       0  3734.8    0.07       0
  4991.2    0.07       0  4998.8    0.07       0  6085.3   0.035       0
Bank Sta=4991.2,4998.8
Exp/Cntr=0.3,0.1

Type RM Length L Ch R = 1,26326,720,720,720
BEGIN DESCRIPTION:
Mapping XS 45f63aa1
END DESCRIPTION:
XS GIS Cut Line= 4
      1494117.16      6947400.52      1493036.47      6947378.82
      1490818.59      6946871.01      1490310.74      6946957.82
#Sta/Elev= 30
  2609.9 1829.40  2622.1 1828.61  2652.1 1823.71  2698.7 1820.20  2762.1 1814.61
  2894.3 1810.64  2942.1 1808.98  3138.1 1808.76  3237.1 1808.45  3452.2 1808.61
  3914.1 1803.78  3985.2 1802.83  4010.3 1803.78  4035.7 1802.49  4429.8 1798.68
  4492.5 1800.01  4970.5 1798.39  5001.2 1795.50  5001.7 1795.00  5009.6 1795.50
  5013.4 1797.14  5026.0 1798.65  5077.2 1798.22  5097.8 1796.54  5104.4 1797.74
  5152.4 1796.56  5419.6 1795.63  5754.3 1797.41  6357.4 1798.13  6481.3 1800.18
#Mann=11,-1,0
  2609.9    0.07       0  2698.7   0.035       0  2894.3   0.045       0
  3138.1   0.035       0  3237.1   0.045       0  3914.1   0.035       0
  4035.7    0.07       0  5001.2    0.07       0  5009.6    0.07       0
  5419.6   0.045       0  6357.4   0.035       0
Bank Sta=5001.2,5009.6
Exp/Cntr=0.3,0.1

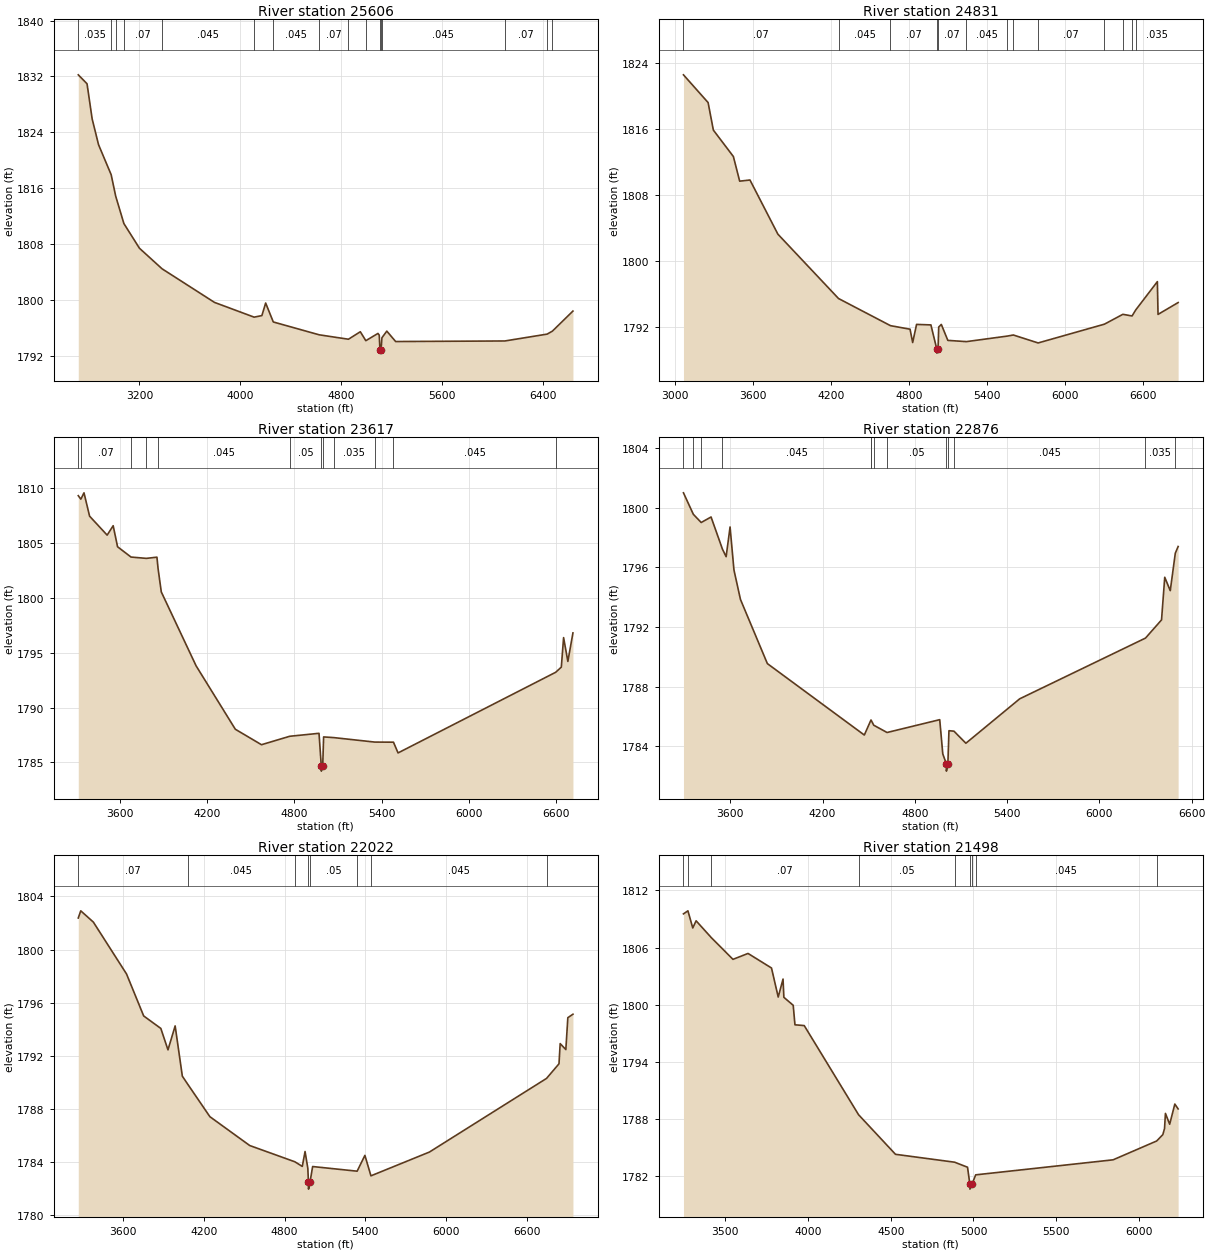
Type RM Length L Ch R = 1,25606,775,775,775
BEGIN DESCRIPTION:
Mapping XS e49a6ab2
END DESCRIPTION:
XS GIS Cut Line= 4
      1494173.59      6946289.42      1492919.28      6946493.41
      1490892.37      6946463.02      1490284.72      6946597.57
#Sta/Elev= 30
  2715.5 1832.23  2785.0 1830.95  2825.5 1825.92  2876.2 1822.23  2976.3 1817.93
  3012.2 1814.86  3077.1 1810.94  3200.4 1807.41  3379.5 1804.47  3795.0 1799.66
  4109.0 1797.55  4170.6 1797.77  4200.6 1799.57  4261.0 1796.86  4625.0 1795.02
  4856.7 1794.39  4950.7 1795.46  4994.5 1794.18  5090.7 1795.22  5100.7 1794.97
  5106.4 1792.90  5106.9 1792.40  5114.9 1792.90  5122.1 1794.60  5160.7 1795.55
  5230.7 1794.06  6096.2 1794.14  6431.0 1795.12  6473.2 1795.55  6635.8 1798.42
#Mann=16,-1,0
  2715.5   0.035       0  2976.3    0.07       0  3012.2   0.035       0
  3077.1    0.07       0  3379.5   0.045       0  4109.0   0.035       0
  4261.0   0.045       0  4625.0    0.07       0  4856.7   0.045       0
  4994.5    0.07       0  5106.4    0.07       0  5114.9    0.07       0
  5122.1   0.045       0  6096.2    0.07       0  6431.0   0.045       0
  6473.2   0.035       0
Bank Sta=5106.4,5114.9
Exp/Cntr=0.3,0.1

Type RM Length L Ch R = 1,24831,1214,1214,1214
BEGIN DESCRIPTION:
Mapping XS 67398253
END DESCRIPTION:
XS GIS Cut Line= 4
      1493822.08      6945686.11      1492645.84      6945864.06
      1490310.77      6945950.87      1490041.67      6946002.95
#Sta/Elev= 30
  3068.2 1822.53  3257.4 1819.18  3297.9 1815.85  3451.6 1812.66  3500.1 1809.68
  3579.1 1809.82  3793.4 1803.28  4259.3 1795.50  4658.5 1792.22  4809.0 1791.79
  4829.1 1790.18  4859.1 1792.37  4969.2 1792.31  5014.2 1789.40  5014.7 1788.90
  5024.1 1789.40  5029.2 1792.05  5049.2 1792.37  5099.2 1790.44  5242.2 1790.29
  5556.7 1790.96  5602.3 1791.09  5792.9 1790.13  6302.5 1792.40  6444.2 1793.59
  6514.4 1793.39  6543.4 1794.13  6709.1 1797.54  6714.2 1793.58  6868.6 1795.01
#Mann=13,-1,0
  3068.2    0.07       0  4259.3   0.045       0  4658.5    0.07       0
  5014.2    0.07       0  5024.1    0.07       0  5242.2   0.045       0
  5556.7    0.07       0  5602.3   0.045       0  5792.9    0.07       0
  6302.5   0.045       0  6444.2   0.035       0  6514.4    0.07       0
  6543.4   0.035       0
Bank Sta=5014.2,5024.1
Exp/Cntr=0.3,0.1

Type RM Length L Ch R = 1,23617,741,741,741
BEGIN DESCRIPTION:
Mapping XS f0921978
END DESCRIPTION:
XS GIS Cut Line= 5
      1493197.10      6945247.76      1492715.29      6945048.09
      1491816.85      6945052.43      1490501.75      6945360.59
      1489954.91      6945686.09
#Sta/Elev= 30
  3310.9 1809.33  3328.5 1809.01  3350.3 1809.59  3388.9 1807.46  3509.8 1805.73
  3551.3 1806.59  3581.5 1804.67  3674.2 1803.73  3780.1 1803.61  3852.7 1803.72
  3860.6 1802.68  3882.7 1800.55  4122.7 1793.80  4392.7 1788.02  4572.7 1786.61
  4767.6 1787.38  4969.0 1787.65  4984.6 1784.70  4985.1 1784.20  4994.6 1784.70
  5000.7 1787.32  5069.3 1787.26  5353.1 1786.85  5481.9 1786.84  5513.4 1785.86
  6599.4 1793.22  6638.0 1793.69  6653.6 1796.38  6683.0 1794.21  6718.0 1796.81
#Mann=12,-1,0
  3310.9   0.035       0  3328.5    0.07       0  3674.2   0.035       0
  3780.1    0.07       0  3860.6   0.045       0  4767.6    0.05       0
  4984.6    0.05       0  4994.6    0.05       0  5069.3   0.035       0
  5353.1    0.07       0  5481.9   0.045       0  6599.4   0.035       0
Bank Sta=4984.6,4994.6
Exp/Cntr=0.3,0.1

Type RM Length L Ch R = 1,22876,854,854,854
BEGIN DESCRIPTION:
Mapping XS 86e1eece
END DESCRIPTION:
XS GIS Cut Line= 4
      1492984.42      6944644.46      1492554.70      6944492.54
      1490796.88      6944548.96      1489993.97      6945147.89
#Sta/Elev= 30
  3296.0 1801.00  3360.2 1799.56  3411.3 1799.01  3475.4 1799.38  3549.6 1797.22
  3573.4 1796.72  3599.0 1798.71  3624.2 1795.83  3666.6 1793.85  3841.5 1789.55
  4471.9 1784.76  4515.2 1785.77  4518.0 1785.72  4533.0 1785.42  4619.8 1784.93
  4962.1 1785.79  4982.1 1783.49  5005.1 1782.84  5005.6 1782.34  5015.1 1782.84
  5022.1 1785.05  5054.5 1785.02  5132.2 1784.21  5482.4 1787.19  6300.0 1791.26
  6404.3 1792.48  6425.1 1795.34  6461.0 1794.44  6493.8 1796.95  6512.2 1797.40
#Mann=13,-1,0
  3296.0    0.07       0  3360.2   0.035       0  3411.3    0.07       0
  3549.6   0.045       0  4515.2    0.05       0  4518.0   0.045       0
  4533.0    0.07       0  4619.8    0.05       0  5005.1    0.05       0
  5015.1    0.05       0  5054.5   0.045       0  6300.0   0.035       0
  6493.8    0.07       0
Bank Sta=5005.1,5015.1
Exp/Cntr=0.3,0.1

Type RM Length L Ch R = 1,22022,524,524,524
BEGIN DESCRIPTION:
Mapping XS 4a67c34c
END DESCRIPTION:
XS GIS Cut Line= 4
      1493392.42      6943364.05      1492459.21      6943698.27
      1491283.00      6943980.38      1490067.70      6944813.73
#Sta/Elev= 30
  3267.7 1802.37  3286.2 1802.91  3379.9 1802.06  3626.1 1798.16  3753.6 1795.00
  3881.0 1794.06  3934.1 1792.45  3987.3 1794.25  4040.7 1790.47  4080.4 1789.87
  4245.4 1787.42  4541.3 1785.25  4875.9 1784.03  4931.7 1783.68  4952.3 1784.80
  4972.9 1783.53  4977.5 1782.47  4978.0 1781.97  4988.7 1782.47  5008.5 1783.67
  5339.1 1783.32  5396.8 1784.51  5441.6 1782.97  5876.1 1784.76  6745.9 1790.30
  6838.5 1791.40  6847.3 1792.92  6889.3 1792.47  6904.2 1794.87  6942.1 1795.13
#Mann=8,-1,0
  3267.7    0.07       0  4080.4   0.045       0  4875.9    0.05       0
  4977.5    0.05       0  4988.7    0.05       0  5339.1    0.07       0
  5441.6   0.045       0  6745.9   0.035       0
Bank Sta=4977.5,4988.7
Exp/Cntr=0.3,0.1

Type RM Length L Ch R = 1,21498,475,475,475
BEGIN DESCRIPTION:
NC Unknown Stream 05 25.0
END DESCRIPTION:
XS GIS Cut Line= 3
      1493240.48      6943155.73      1491505.00      6943438.00
      1490315.75      6943763.20
#Sta/Elev= 30
  3246.5 1809.54  3273.5 1809.86  3302.7 1808.06  3323.0 1808.81  3415.6 1807.03
  3545.9 1804.76  3637.0 1805.38  3778.9 1803.85  3819.4 1800.80  3848.6 1802.69
  3853.6 1800.77  3910.1 1799.93  3920.7 1797.88  3976.7 1797.80  4305.3 1788.43
  4528.6 1784.27  4886.2 1783.44  4964.3 1782.91  4978.4 1781.11  4978.9 1780.61
  4990.6 1781.11  5013.6 1782.11  5844.5 1783.69  6107.9 1785.67  6145.2 1786.34
  6155.5 1786.98  6160.9 1788.57  6186.6 1787.43  6217.7 1789.55  6237.7 1789.04
#Mann=9,-1,0
  3246.5    0.07       0  3273.5   0.035       0  3415.6    0.07       0
  4305.3    0.05       0  4886.2    0.07       0  4978.4    0.07       0
  4990.6    0.07       0  5013.6   0.045       0  6107.9   0.035       0
Bank Sta=4978.4,4990.6
Exp/Cntr=0.3,0.1

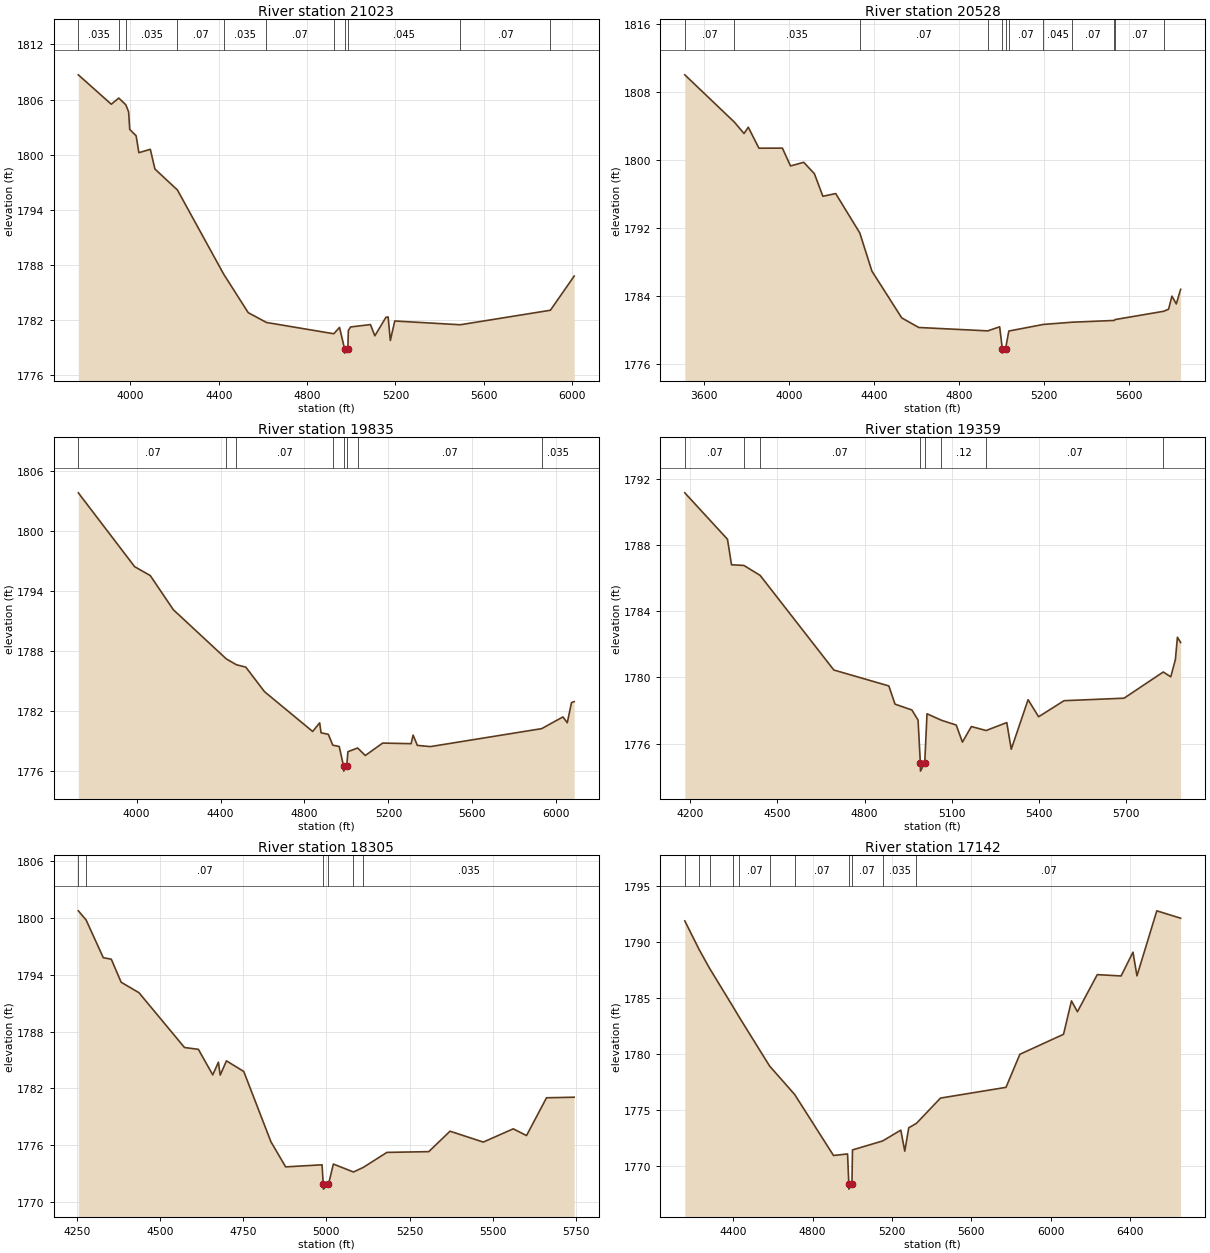
Type RM Length L Ch R = 1,21023,495,495,495
BEGIN DESCRIPTION:
Mapping XS 7dec6e13
END DESCRIPTION:
XS GIS Cut Line= 4
      1492658.87      6942921.35      1491916.68      6943129.69
      1490753.48      6943160.07      1490451.63      6943233.38
#Sta/Elev= 30
  3764.1 1808.69  3913.3 1805.49  3947.3 1806.16  3979.1 1805.43  3991.8 1804.66
  3997.0 1802.74  4025.9 1802.05  4038.2 1800.21  4090.1 1800.58  4110.9 1798.43
  4212.8 1796.15  4422.1 1786.99  4533.3 1782.79  4616.0 1781.72  4920.7 1780.49
  4946.8 1781.18  4969.4 1778.88  4969.9 1778.38  4984.3 1778.88  4986.8 1780.85
  4996.8 1781.23  5086.8 1781.49  5106.8 1780.27  5156.9 1782.28  5166.9 1782.32
  5176.9 1779.76  5196.9 1781.88  5493.5 1781.47  5901.6 1783.05  6009.2 1786.77
#Mann=11,-1,0
  3764.1   0.035       0  3947.3    0.07       0  3979.1   0.035       0
  4212.8    0.07       0  4422.1   0.035       0  4616.0    0.07       0
  4920.7   0.045       0  4969.4   0.045       0  4984.3   0.045       0
  5493.5    0.07       0  5901.6   0.035       0
Bank Sta=4969.4,4984.3
Exp/Cntr=0.3,0.1

Type RM Length L Ch R = 1,20528,693,693,693
BEGIN DESCRIPTION:
Mapping XS 55401f10
END DESCRIPTION:
XS GIS Cut Line= 4
      1492862.83      6942791.15      1492046.88      6942843.23
      1490979.18      6942799.83      1490545.15      6942895.31
#Sta/Elev= 30
  3511.2 1810.06  3744.8 1804.48  3789.6 1803.15  3809.6 1803.89  3859.7 1801.42
  3970.0 1801.43  4008.1 1799.33  4070.2 1799.76  4120.3 1798.42  4160.3 1795.76
  4220.5 1796.08  4333.8 1791.44  4390.7 1786.95  4530.9 1781.44  4610.9 1780.31
  4935.2 1779.91  4991.2 1780.39  5003.8 1777.79  5004.3 1777.29  5018.8 1777.79
  5034.2 1779.89  5196.8 1780.67  5331.2 1780.93  5530.2 1781.14  5533.2 1781.24
  5762.6 1782.22  5785.1 1782.46  5801.0 1784.00  5821.5 1783.08  5841.8 1784.80
#Mann=12,-1,0
  3511.2    0.07       0  3744.8   0.035       0  4333.8    0.07       0
  4935.2   0.045       0  5003.8   0.045       0  5018.8   0.045       0
  5034.2    0.07       0  5196.8   0.045       0  5331.2    0.07       0
  5530.2   0.045       0  5533.2    0.07       0  5762.6   0.035       0
Bank Sta=5003.8,5018.8
Exp/Cntr=0.3,0.1

Type RM Length L Ch R = 1,19835,476,476,476
BEGIN DESCRIPTION:
Mapping XS 32f95ce0
END DESCRIPTION:
XS GIS Cut Line= 4
      1492927.93      6942079.34      1492289.94      6942088.02
      1491126.75      6942400.52      1490623.30      6942535.06
#Sta/Elev= 30
  3721.9 1803.81  3990.3 1796.44  4064.9 1795.55  4174.9 1792.14  4427.4 1787.23
  4475.6 1786.65  4520.4 1786.41  4609.4 1783.96  4838.9 1779.99  4872.4 1780.85
  4878.9 1779.86  4913.7 1779.70  4934.9 1778.62  4965.6 1778.49  4986.2 1776.53
  4986.7 1776.03  5001.2 1776.53  5007.0 1777.97  5053.4 1778.34  5089.9 1777.59
  5172.7 1778.83  5308.3 1778.77  5317.7 1779.63  5338.0 1778.60  5400.5 1778.48
  5930.5 1780.27  6032.0 1781.44  6052.7 1780.86  6072.9 1782.87  6085.5 1782.97
#Mann=8,-1,0
  3721.9    0.07       0  4427.4   0.035       0  4475.6    0.07       0
  4934.9    0.12       0  4986.2    0.07       0  5001.2    0.12       0
  5053.4    0.07       0  5930.5   0.035       0
Bank Sta=4986.2,5001.2
Exp/Cntr=0.3,0.1

Type RM Length L Ch R = 1,19359,1054,1054,1054
BEGIN DESCRIPTION:
Mapping XS 0d0a85b3
END DESCRIPTION:
XS GIS Cut Line= 4
      1492164.05      6941502.09      1491894.98      6941593.23
      1491100.70      6942083.68      1490675.39      6942322.38
#Sta/Elev= 30
  4181.8 1791.14  4328.6 1788.34  4342.5 1786.80  4384.9 1786.76  4440.9 1786.16
  4694.4 1780.45  4883.6 1779.49  4904.9 1778.39  4962.8 1778.04  4984.1 1777.43
  4991.9 1774.85  4992.4 1774.35  5007.0 1774.85  5014.9 1777.81  5064.4 1777.42
  5115.4 1777.13  5136.6 1776.10  5167.4 1777.04  5218.2 1776.80  5289.2 1777.28
  5304.6 1775.67  5362.5 1778.66  5398.7 1777.63  5486.2 1778.60  5692.6 1778.75
  5827.3 1780.33  5853.2 1780.04  5869.1 1781.08  5876.1 1782.43  5887.1 1782.11
#Mann=8,-1,0
  4181.8    0.07       0  4384.9   0.035       0  4440.9    0.07       0
  4991.9    0.07       0  5007.0    0.07       0  5064.4    0.12       0
  5218.2    0.07       0  5827.3   0.035       0
Bank Sta=4991.9,5007
Exp/Cntr=0.3,0.1

Type RM Length L Ch R = 1,18305,1163,1163,1163
BEGIN DESCRIPTION:
Mapping XS eb286c25
END DESCRIPTION:
XS GIS Cut Line= 4
      1491118.07      6940473.44      1490944.45      6940903.13
      1490675.36      6941489.06      1490675.36      6941871.05
#Sta/Elev= 30
  4254.6 1800.75  4277.9 1799.79  4329.6 1795.80  4353.7 1795.64  4383.2 1793.21
  4436.9 1792.10  4573.7 1786.31  4615.4 1786.12  4658.6 1783.42  4675.6 1784.76
  4681.0 1783.40  4699.8 1784.90  4751.8 1783.78  4833.4 1776.36  4877.7 1773.70
  4987.1 1773.92  4990.7 1771.85  4991.2 1771.35  5006.4 1771.85  5021.1 1774.00
  5081.5 1773.16  5111.2 1773.65  5182.0 1775.23  5307.9 1775.31  5371.7 1777.47
  5471.7 1776.32  5561.7 1777.72  5601.7 1777.01  5661.7 1781.00  5744.8 1781.06
#Mann=6,-1,0
  4254.6   0.035       0  4277.9    0.07       0  4990.7    0.07       0
  5006.4    0.07       0  5081.5    0.07       0  5111.2   0.035       0
Bank Sta=4990.7,5006.4
Exp/Cntr=0.3,0.1

Type RM Length L Ch R = 1,17142,920,920,920
BEGIN DESCRIPTION:
NC Unknown Stream 05 21.0
END DESCRIPTION:
XS GIS Cut Line= 3
      1490754.99      6940288.01      1490155.00      6940888.00
      1490155.00      6942537.99
#Sta/Elev= 30
  4156.2 1791.92  4228.4 1789.36  4281.2 1787.67  4400.1 1784.21  4431.7 1783.27
  4583.5 1778.93  4709.9 1776.38  4905.7 1770.92  4976.4 1771.06  4982.7 1768.41
  4983.2 1767.91  4998.5 1768.41  5001.2 1771.42  5152.8 1772.22  5244.7 1773.19
  5264.7 1771.31  5284.7 1773.40  5323.6 1773.80  5444.7 1776.06  5774.7 1777.02
  5844.7 1779.98  6064.7 1781.77  6104.7 1784.76  6134.7 1783.79  6234.7 1787.11
  6354.7 1786.99  6414.7 1789.12  6434.7 1787.00  6534.7 1792.82  6654.7 1792.16
#Mann=11,-1,0
  4156.2    0.07       0  4228.4    0.16       0  4281.2    0.07       0
  4400.1    0.16       0  4431.7    0.07       0  4583.5    0.16       0
  4709.9    0.07       0  4982.7    0.07       0  4998.5    0.07       0
  5152.8   0.035       0  5323.6    0.07       0
Bank Sta=4982.7,4998.5
Exp/Cntr=0.3,0.1