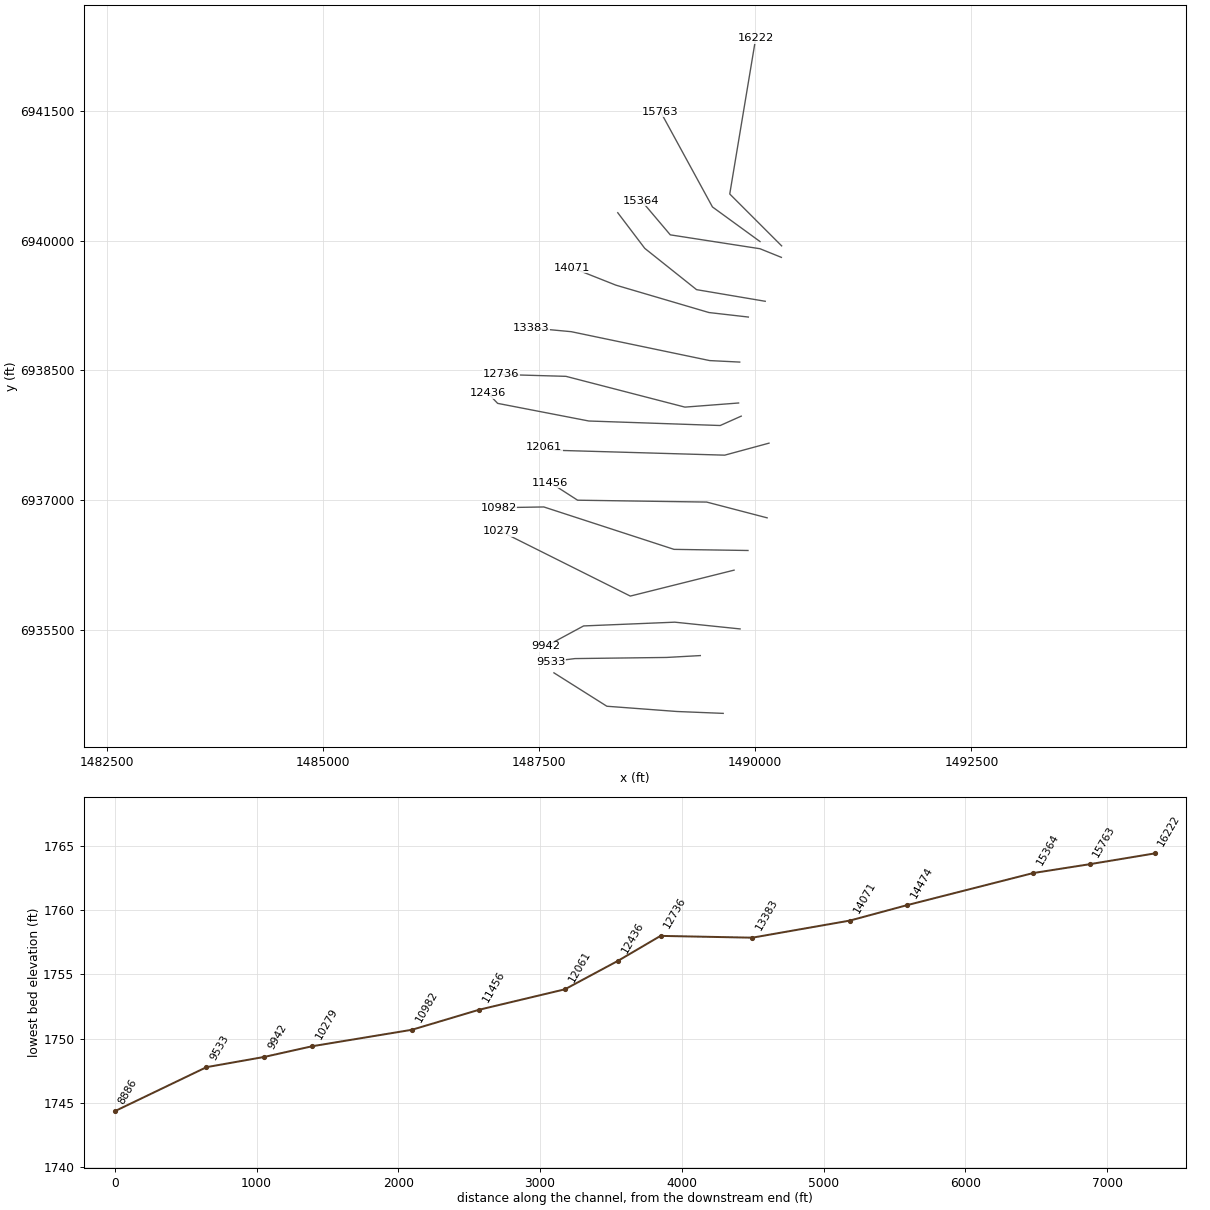
HEC-RAS study NC Unknown Stream 05.prj: NC Unknown Stream 05 Base Level Engineering

--- NC Unknown Stream 05.g01 (geometry) --- (continued)

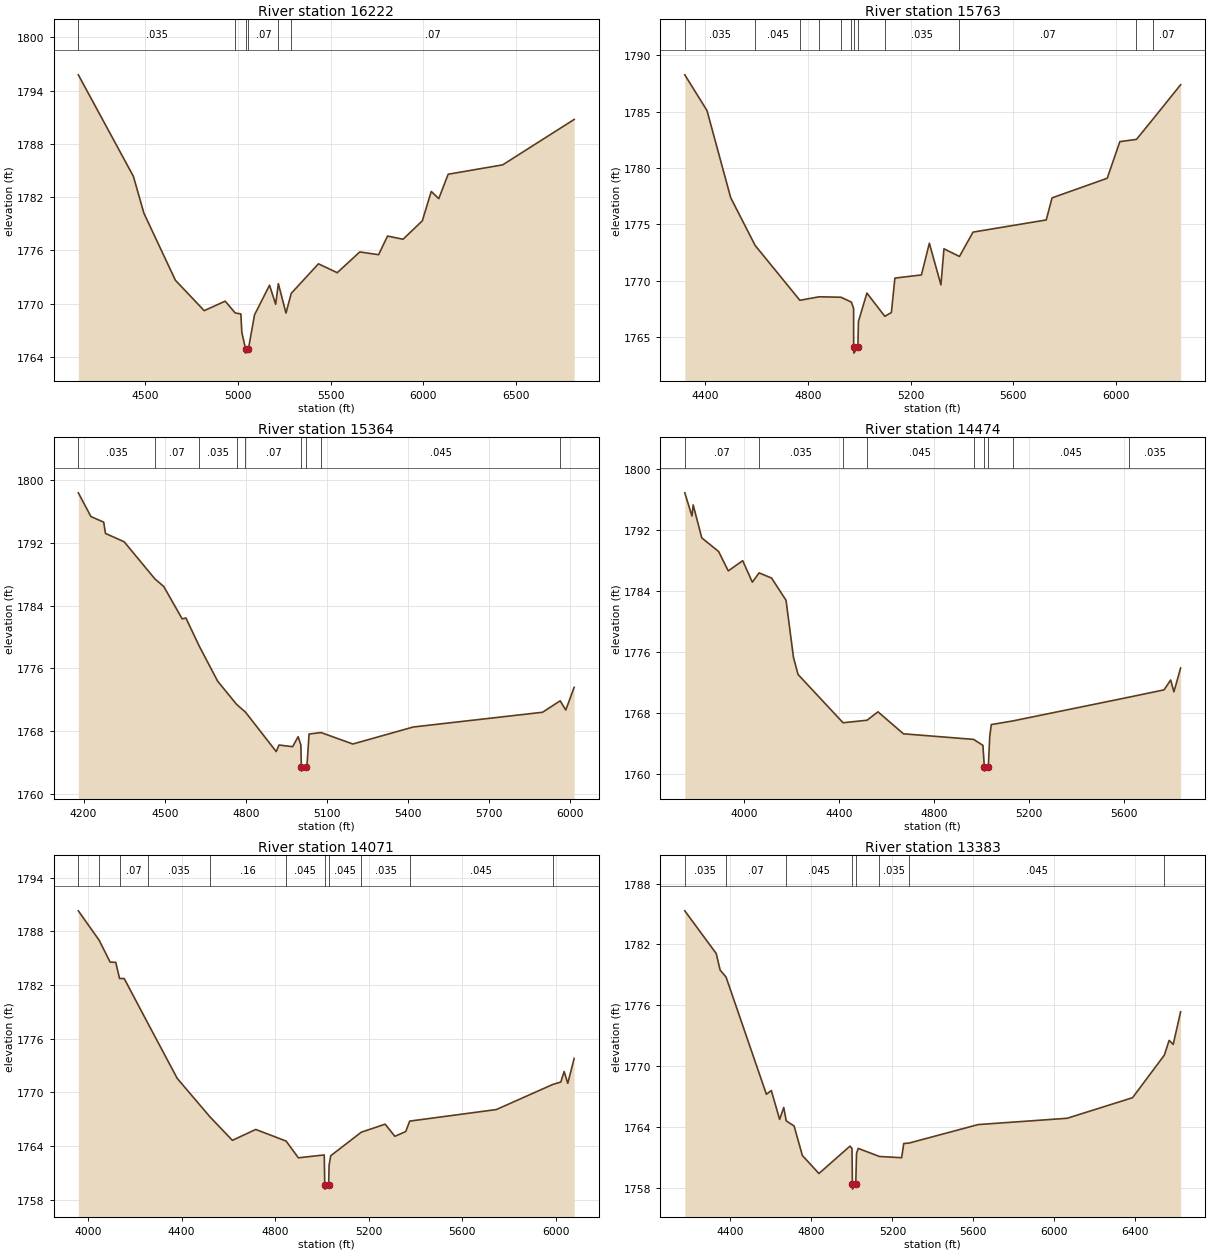
Type RM Length L Ch R = 1,16222,459,459,459
BEGIN DESCRIPTION:
NC Unknown Stream 05 20.0
END DESCRIPTION:
XS GIS Cut Line= 3
      1490305.00      6939938.00      1489705.00      6940538.00
      1490005.01      6942338.05
#Sta/Elev= 30
  4139.4 1795.79  4436.4 1784.34  4492.9 1780.19  4662.7 1772.63  4818.2 1769.20
  4931.4 1770.27  4985.1 1768.94  5015.8 1768.83  5020.9 1766.76  5040.8 1764.91
  5041.3 1764.41  5056.7 1764.91  5089.3 1768.72  5170.4 1772.07  5203.4 1769.92
  5217.9 1772.24  5259.1 1768.93  5287.4 1771.15  5434.0 1774.48  5535.4 1773.48
  5657.0 1775.82  5758.4 1775.51  5806.6 1777.61  5890.2 1777.25  5994.1 1779.33
  6042.3 1782.64  6082.8 1781.83  6133.5 1784.58  6427.5 1785.64  6812.8 1790.76
#Mann=6,-1,0
  4139.4   0.035       0  4985.1    0.07       0  5040.8    0.07       0
  5056.7    0.07       0  5217.9   0.035       0  5287.4    0.07       0
Bank Sta=5040.8,5056.7
Exp/Cntr=0.3,0.1

Type RM Length L Ch R = 1,15763,399,399,399
BEGIN DESCRIPTION:
NC Unknown Stream 05 19.0
END DESCRIPTION:
XS GIS Cut Line= 3
      1490055.01      6939988.00      1489505.00      6940388.00
      1488904.99      6941488.02
#Sta/Elev= 30
  4319.9 1788.27  4406.5 1785.10  4498.8 1777.37  4594.1 1773.13  4768.5 1768.26
  4844.2 1768.57  4928.8 1768.53  4969.2 1768.10  4978.0 1767.54  4978.3 1764.07
  4978.8 1763.57  4994.6 1764.07  4996.9 1766.38  5029.9 1768.90  5099.7 1766.84
  5125.3 1767.17  5139.0 1770.23  5242.5 1770.51  5273.4 1773.32  5318.5 1769.63
  5330.3 1772.83  5390.7 1772.15  5443.7 1774.31  5729.0 1775.39  5751.8 1777.35
  5966.8 1779.09  6016.1 1782.34  6080.9 1782.54  6144.5 1784.32  6253.0 1787.39
#Mann=12,-1,0
  4319.9   0.035       0  4594.1   0.045       0  4768.5   0.035       0
  4844.2   0.045       0  4928.8   0.035       0  4969.2   0.045       0
  4978.3   0.045       0  4994.6   0.045       0  5099.7   0.035       0
  5390.7    0.07       0  6080.9   0.035       0  6144.5    0.07       0
Bank Sta=4978.3,4994.6
Exp/Cntr=0.3,0.1

Type RM Length L Ch R = 1,15364,890,890,890
BEGIN DESCRIPTION:
Mapping XS 83e7ce6d
END DESCRIPTION:
XS GIS Cut Line= 4
      1490302.10      6939805.03      1490054.70      6939904.86
      1489017.37      6940065.45      1488683.14      6940460.45
#Sta/Elev= 30
  4180.6 1798.38  4227.3 1795.35  4274.5 1794.64  4281.0 1793.20  4350.0 1792.14
  4464.1 1787.39  4496.6 1786.43  4564.7 1782.30  4578.6 1782.41  4627.5 1778.85
  4695.8 1774.36  4766.1 1771.39  4798.7 1770.41  4912.6 1765.37  4922.7 1766.21
  4973.3 1766.00  4993.5 1767.27  5003.6 1766.24  5005.6 1763.38  5006.1 1762.88
  5021.9 1763.38  5026.2 1763.57  5034.0 1767.61  5078.3 1767.80  5195.9 1766.34
  5419.6 1768.51  5897.7 1770.39  5962.7 1771.85  5983.5 1770.68  6014.5 1773.57
#Mann=9,-1,0
  4180.6   0.035       0  4464.1    0.07       0  4627.5   0.035       0
  4766.1   0.045       0  4798.7    0.07       0  5005.6    0.07       0
  5021.9    0.07       0  5078.3   0.045       0  5962.7   0.035       0
Bank Sta=5005.6,5021.9
Exp/Cntr=0.3,0.1

Type RM Length L Ch R = 1,14474,403,403,403
BEGIN DESCRIPTION:
Mapping XS 824f03f9
END DESCRIPTION:
XS GIS Cut Line= 4
      1490115.50      6939297.22      1489321.19      6939431.77
      1488722.23      6939909.20      1488409.88      6940321.33
#Sta/Elev= 30
  3750.9 1796.85  3781.1 1793.81  3786.2 1795.26  3822.4 1790.95  3893.4 1789.16
  3934.0 1786.62  3994.8 1787.96  4035.4 1785.14  4064.0 1786.36  4116.5 1785.68
  4177.4 1782.77  4208.8 1775.27  4228.1 1773.04  4417.6 1766.72  4518.5 1767.05
  4564.7 1768.15  4672.0 1765.27  4967.4 1764.54  5006.7 1763.76  5012.9 1760.88
  5013.4 1760.38  5029.3 1760.88  5035.5 1764.88  5041.9 1766.48  5133.2 1766.96
  5622.0 1770.07  5769.8 1771.03  5797.8 1772.32  5811.4 1770.77  5839.6 1773.90
#Mann=9,-1,0
  3750.9    0.07       0  4064.0   0.035       0  4417.6    0.07       0
  4518.5   0.045       0  4967.4    0.07       0  5012.9    0.07       0
  5029.3    0.07       0  5133.2   0.045       0  5622.0   0.035       0
Bank Sta=5012.9,5029.3
Exp/Cntr=0.3,0.1

Type RM Length L Ch R = 1,14071,688,688,688
BEGIN DESCRIPTION:
Mapping XS 61f9b6db
END DESCRIPTION:
XS GIS Cut Line= 4
      1489920.17      6939114.93      1489464.42      6939167.02
      1488388.03      6939483.86      1487885.19      6939683.26
#Sta/Elev= 30
  3958.1 1790.28  4047.3 1786.99  4094.1 1784.55  4118.3 1784.52  4134.5 1782.72
  4154.5 1782.71  4257.4 1777.63  4381.2 1771.56  4520.3 1767.29  4617.3 1764.63
  4717.3 1765.85  4847.2 1764.55  4899.7 1762.68  5010.4 1763.00  5012.6 1759.68
  5013.1 1759.18  5029.1 1759.68  5031.2 1761.86  5038.2 1762.91  5168.8 1765.54
  5271.0 1766.44  5312.7 1765.08  5359.2 1765.62  5375.9 1766.78  5746.5 1768.07
  5988.6 1770.88  6022.8 1771.15  6037.0 1772.32  6052.5 1771.00  6079.8 1773.78
#Mann=11,-1,0
  3958.1    0.07       0  4047.3   0.035       0  4134.5    0.07       0
  4257.4   0.035       0  4520.3    0.16       0  4847.2   0.045       0
  5012.6   0.045       0  5029.1   0.045       0  5168.8   0.035       0
  5375.9   0.045       0  5988.6   0.035       0
Bank Sta=5012.6,5029.1
Exp/Cntr=0.3,0.1

Type RM Length L Ch R = 1,13383,647,647,647
BEGIN DESCRIPTION:
Mapping XS e3345011
END DESCRIPTION:
XS GIS Cut Line= 4
      1489820.33      6938594.10      1489473.10      6938611.46
      1487871.54      6938945.66      1487408.57      6938988.93
#Sta/Elev= 30
  4174.6 1785.31  4330.1 1781.09  4349.0 1779.47  4378.3 1778.78  4577.6 1767.21
  4602.0 1767.58  4642.9 1764.73  4663.3 1765.91  4675.6 1764.58  4714.4 1764.08
  4755.3 1761.17  4837.0 1759.39  4990.2 1762.09  5000.4 1761.86  5002.4 1758.35
  5002.9 1757.85  5018.9 1758.35  5022.7 1761.37  5031.1 1761.87  5136.0 1761.07
  5245.6 1760.95  5255.8 1762.35  5283.2 1762.40  5623.6 1764.22  6062.8 1764.84
  6385.8 1766.87  6542.8 1771.07  6566.6 1772.53  6586.7 1772.13  6623.3 1775.35
#Mann=8,-1,0
  4174.6   0.035       0  4378.3    0.07       0  4675.6   0.045       0
  5002.4   0.045       0  5018.9   0.045       0  5136.0   0.035       0
  5283.2   0.045       0  6542.8   0.035       0
Bank Sta=5002.4,5018.9
Exp/Cntr=0.3,0.1

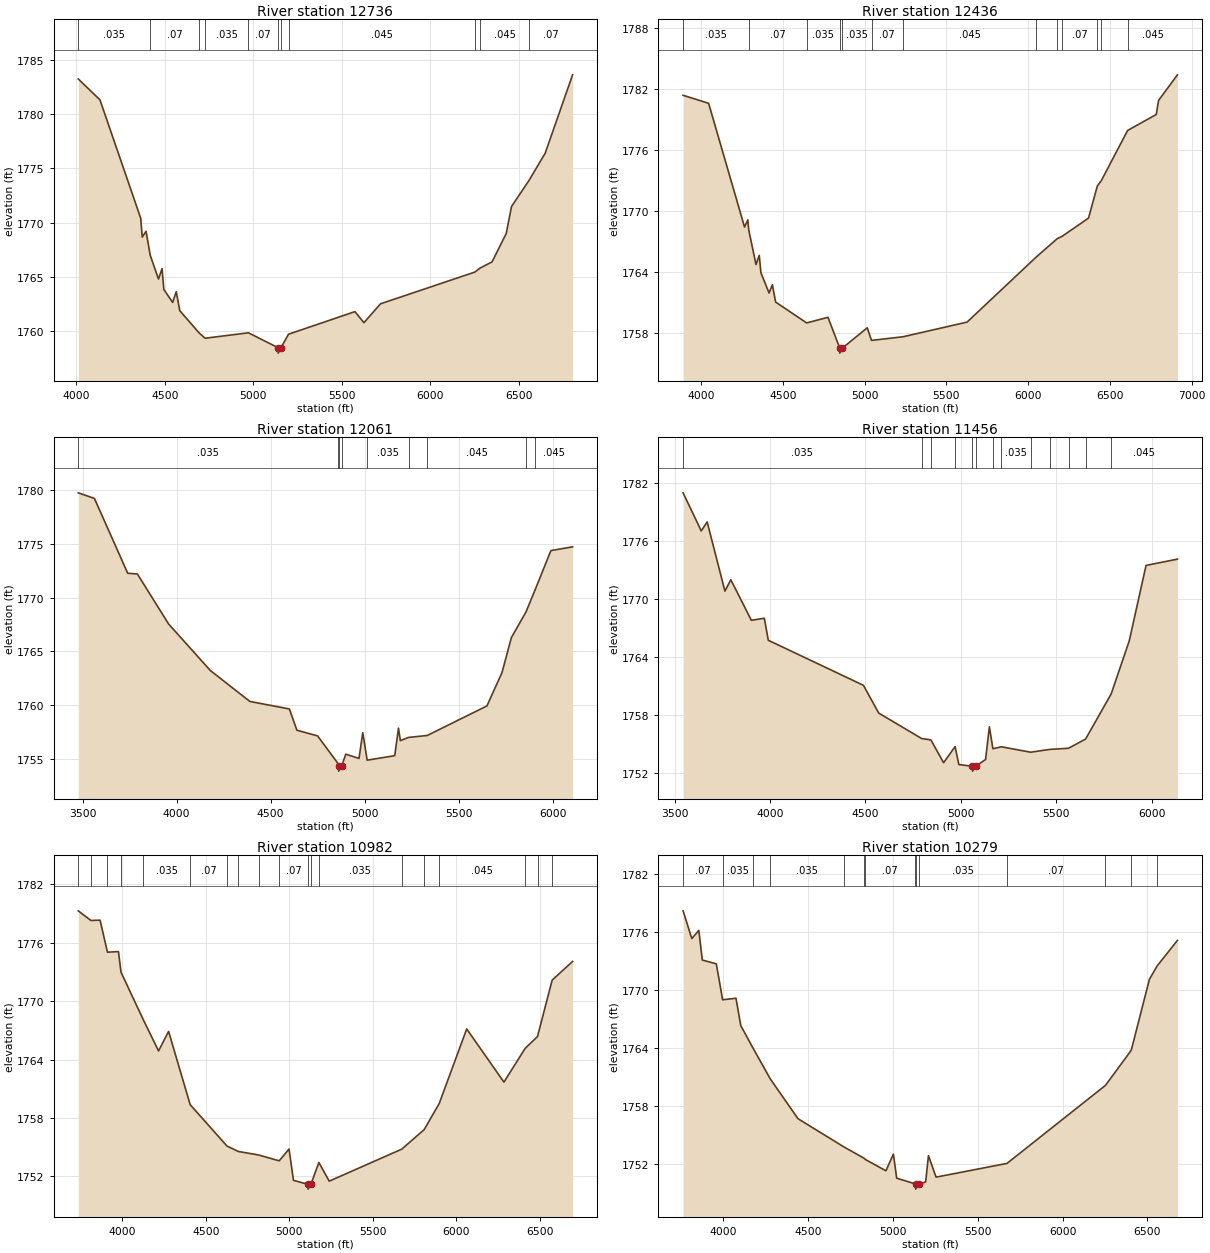
Type RM Length L Ch R = 1,12736,300,300,300
BEGIN DESCRIPTION:
Mapping XS 0add67b7
END DESCRIPTION:
XS GIS Cut Line= 4
      1489807.26      6938121.01      1489186.64      6938073.27
      1487810.77      6938429.17      1487059.99      6938450.87
#Sta/Elev= 30
  4010.9 1783.23  4133.5 1781.31  4364.2 1770.40  4372.6 1768.67  4394.3 1769.21
  4417.5 1767.01  4464.5 1764.81  4484.6 1765.77  4494.6 1763.85  4544.7 1762.66
  4564.8 1763.65  4584.9 1761.90  4693.7 1759.86  4727.9 1759.36  4972.9 1759.86
  5140.6 1758.49  5141.1 1757.99  5157.2 1758.49  5199.5 1759.73  5575.0 1761.81
  5626.0 1760.79  5719.6 1762.53  6252.8 1765.45  6283.4 1765.83  6350.4 1766.39
  6430.4 1769.00  6460.4 1771.49  6558.6 1773.87  6650.5 1776.39  6805.6 1783.61
#Mann=11,-1,0
  4010.9   0.035       0  4417.5    0.07       0  4693.7   0.045       0
  4727.9   0.035       0  4972.9    0.07       0  5140.6    0.07       0
  5157.2    0.07       0  5199.5   0.045       0  6252.8    0.07       0
  6283.4   0.045       0  6558.6    0.07       0
Bank Sta=5140.6,5157.2
Exp/Cntr=0.3,0.1

Type RM Length L Ch R = 1,12436,375,375,375
BEGIN DESCRIPTION:
Mapping XS d2482891
END DESCRIPTION:
XS GIS Cut Line= 5
      1489837.67      6937969.09      1489594.63      6937860.59
      1488075.53      6937912.68      1487020.84      6938116.67
      1486907.98      6938233.88
#Sta/Elev= 30
  3889.9 1781.40  4046.1 1780.61  4265.8 1768.44  4285.8 1769.15  4291.3 1768.17
  4335.8 1764.76  4355.8 1765.66  4365.8 1763.96  4415.8 1761.96  4435.9 1762.78
  4455.9 1761.07  4645.5 1759.02  4776.1 1759.57  4847.8 1756.55  4848.3 1756.05
  4864.4 1756.55  5016.2 1758.54  5042.2 1757.30  5235.1 1757.66  5626.6 1759.10
  6049.2 1765.49  6177.9 1767.30  6208.5 1767.54  6369.2 1769.32  6423.2 1772.48
  6447.8 1773.01  6608.5 1777.94  6783.6 1779.51  6797.7 1780.89  6913.0 1783.41
#Mann=13,-1,0
  3889.9   0.035       0  4291.3    0.07       0  4645.5   0.035       0
  4847.8   0.035       0  4864.4   0.035       0  5042.2    0.07       0
  5235.1   0.045       0  6049.2    0.07       0  6177.9   0.045       0
  6208.5    0.07       0  6423.2   0.045       0  6447.8    0.07       0
  6608.5   0.045       0
Bank Sta=4847.8,4864.4
Exp/Cntr=0.3,0.1

Type RM Length L Ch R = 1,12061,605,605,605
BEGIN DESCRIPTION:
Mapping XS a9a5e4bd
END DESCRIPTION:
XS GIS Cut Line= 4
      1490158.86      6937656.60      1489646.71      6937517.71
      1487693.59      6937574.13      1487555.05      6937613.10
#Sta/Elev= 30
  3477.2 1779.75  3563.1 1779.23  3740.2 1772.26  3791.7 1772.19  3957.8 1767.53
  4179.6 1763.20  4389.7 1760.32  4599.8 1759.62  4639.8 1757.64  4749.9 1757.11
  4856.7 1754.58  4861.6 1754.33  4862.1 1753.83  4878.3 1754.33  4899.9 1755.41
  4970.0 1755.01  4990.0 1757.41  5013.5 1754.85  5160.0 1755.27  5180.0 1757.83
  5190.0 1756.67  5233.6 1756.97  5332.7 1757.15  5650.2 1759.90  5730.3 1763.01
  5780.3 1766.27  5857.8 1768.65  5904.5 1770.63  5990.4 1774.37  6105.7 1774.72
#Mann=9,-1,0
  3477.2   0.035       0  4856.7    0.07       0  4861.6    0.07       0
  4878.3    0.07       0  5013.5   0.035       0  5233.6    0.07       0
  5332.7   0.045       0  5857.8    0.07       0  5904.5   0.045       0
Bank Sta=4861.6,4878.3
Exp/Cntr=0.3,0.1

Type RM Length L Ch R = 1,11456,474,474,474
BEGIN DESCRIPTION:
Mapping XS 31f55343
END DESCRIPTION:
XS GIS Cut Line= 4
      1490137.20      6936792.87      1489438.38      6936975.18
      1487945.32      6936996.88      1487629.20      6937200.41
#Sta/Elev= 30
  3543.9 1780.95  3639.2 1777.02  3670.2 1777.95  3763.2 1770.81  3794.2 1771.98
  3901.8 1767.80  3969.9 1768.01  3990.6 1765.74  4489.5 1761.09  4569.5 1758.23
  4794.6 1755.60  4843.0 1755.46  4909.6 1753.11  4969.9 1754.77  4989.6 1752.92
  5060.6 1752.74  5061.1 1752.24  5078.6 1752.74  5129.6 1753.44  5149.6 1756.81
  5168.0 1754.55  5212.5 1754.75  5366.2 1754.19  5465.3 1754.48  5564.4 1754.60
  5654.0 1755.55  5788.2 1760.21  5883.0 1765.69  5970.8 1773.46  6135.3 1774.11
#Mann=13,-1,0
  3543.9   0.035       0  4794.6    0.07       0  4843.0   0.035       0
  4969.9    0.07       0  5060.6    0.07       0  5078.6    0.07       0
  5168.0    0.07       0  5212.5   0.035       0  5366.2    0.07       0
  5465.3   0.035       0  5564.4    0.07       0  5654.0   0.035       0
  5788.2   0.045       0
Bank Sta=5060.6,5078.6
Exp/Cntr=0.3,0.1

Type RM Length L Ch R = 1,10982,703,703,703
BEGIN DESCRIPTION:
Mapping XS ab8dd28a
END DESCRIPTION:
XS GIS Cut Line= 4
      1489915.80      6936415.28      1489060.77      6936428.30
      1487554.70      6936918.75      1487033.91      6936910.07
#Sta/Elev= 30
  3736.4 1779.28  3812.1 1778.29  3867.2 1778.32  3911.2 1775.03  3977.2 1775.09
  3992.4 1772.97  4125.6 1768.10  4217.3 1764.88  4277.3 1766.89  4406.6 1759.36
  4626.9 1755.11  4694.9 1754.55  4815.8 1754.19  4939.6 1753.59  4998.4 1754.80
  5025.0 1751.58  5111.7 1751.18  5112.2 1750.68  5129.8 1751.18  5177.0 1753.42
  5239.1 1751.50  5673.6 1754.79  5807.8 1756.80  5898.0 1759.49  6062.3 1767.14
  6285.2 1761.68  6412.6 1765.15  6486.2 1766.36  6574.0 1772.16  6696.3 1774.08
#Mann=19,-1,0
  3736.4   0.035       0  3812.1    0.07       0  3911.2   0.035       0
  3992.4    0.07       0  4125.6   0.035       0  4406.6    0.07       0
  4626.9   0.035       0  4694.9    0.07       0  4815.8   0.035       0
  4939.6    0.07       0  5111.7    0.07       0  5129.8    0.07       0
  5177.0   0.035       0  5673.6    0.07       0  5807.8   0.035       0
  5898.0   0.045       0  6412.6    0.07       0  6486.2   0.045       0
  6574.0    0.07       0
Bank Sta=5111.7,5129.8
Exp/Cntr=0.3,0.1

Type RM Length L Ch R = 1,10279,337,337,337
BEGIN DESCRIPTION:
NC Unknown Stream 05 7.0
END DESCRIPTION:
XS GIS Cut Line= 3
      1489754.97      6936187.99      1488555.00      6935888.00
      1487054.96      6936638.02
#Sta/Elev= 30
  3763.0 1778.18  3814.5 1775.31  3855.7 1776.16  3876.4 1773.09  3958.8 1772.70
  3996.1 1768.98  4074.8 1769.14  4103.1 1766.31  4176.0 1763.96  4277.3 1760.79
  4440.7 1756.68  4711.6 1753.76  4832.3 1752.57  4836.9 1752.47  4958.7 1751.30
  5002.7 1753.02  5022.3 1750.53  5130.2 1749.95  5133.4 1749.90  5133.9 1749.40
  5151.5 1749.90  5192.8 1750.14  5209.5 1752.86  5254.3 1750.64  5672.3 1752.06
  6252.9 1760.13  6404.9 1763.76  6512.0 1771.10  6557.8 1772.49  6677.0 1775.12
#Mann=14,-1,0
  3763.0    0.07       0  3996.1   0.035       0  4176.0    0.07       0
  4277.3   0.035       0  4711.6    0.07       0  4832.3   0.035       0
  4836.9    0.07       0  5130.2   0.035       0  5133.4    0.07       0
  5151.5   0.035       0  5672.3    0.07       0  6252.9   0.045       0
  6404.9    0.07       0  6557.8   0.035       0
Bank Sta=5133.4,5151.5
Exp/Cntr=0.3,0.1

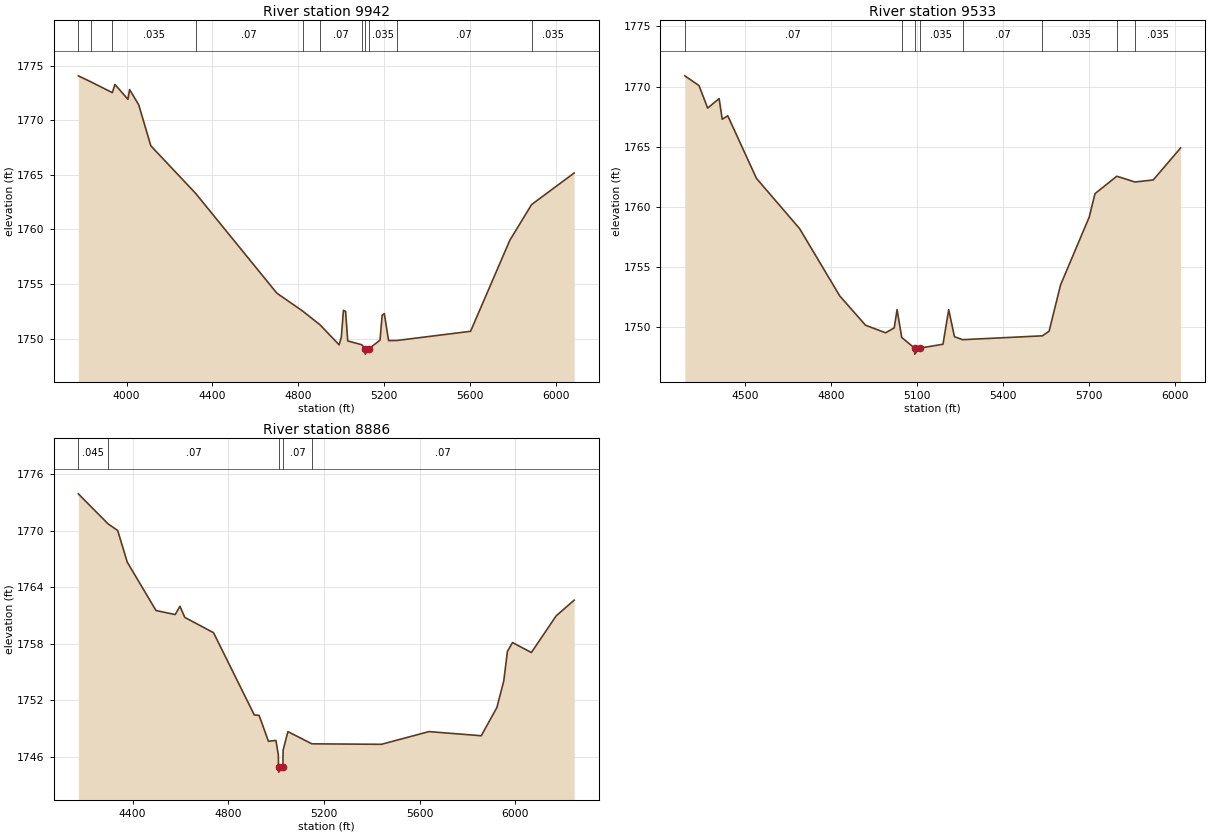
Type RM Length L Ch R = 1,9942,409,409,409
BEGIN DESCRIPTION:
Mapping XS 8f834557
END DESCRIPTION:
XS GIS Cut Line= 4
      1489824.68      6935508.16      1489069.45      6935586.29
      1488014.77      6935542.88      1487580.74      6935308.51
#Sta/Elev= 30
  3775.6 1774.06  3833.9 1773.51  3933.7 1772.52  3946.2 1773.27  4006.5 1771.91
  4014.3 1772.80  4056.8 1771.40  4113.1 1767.65  4321.4 1763.30  4699.4 1754.16
  4820.2 1752.51  4900.5 1751.26  4989.7 1749.42  4999.7 1750.11  5009.7 1752.58
  5019.7 1752.49  5029.7 1749.78  5095.0 1749.43  5110.7 1749.07  5111.2 1748.57
  5128.9 1749.07  5179.9 1749.85  5189.9 1752.13  5199.9 1752.28  5219.9 1749.81
  5258.4 1749.82  5601.5 1750.66  5784.3 1759.00  5885.6 1762.27  6083.7 1765.16
#Mann=11,-1,0
  3775.6   0.035       0  3833.9    0.07       0  3933.7   0.035       0
  4321.4    0.07       0  4820.2   0.035       0  4900.5    0.07       0
  5095.0   0.035       0  5110.7    0.07       0  5128.9   0.035       0
  5258.4    0.07       0  5885.6   0.035       0
Bank Sta=5110.7,5128.9
Exp/Cntr=0.3,0.1

Type RM Length L Ch R = 1,9533,647,647,647
BEGIN DESCRIPTION:
Mapping XS cc763dc2
END DESCRIPTION:
XS GIS Cut Line= 4
      1489364.56      6935200.00      1488973.97      6935178.30
      1487914.94      6935165.28      1487638.60      6935130.74
#Sta/Elev= 30
  4289.8 1770.89  4339.4 1770.08  4369.5 1768.21  4409.5 1769.00  4420.3 1767.28
  4439.6 1767.57  4539.7 1762.37  4690.0 1758.20  4830.0 1752.61  4920.0 1750.17
  4990.0 1749.54  5020.0 1749.95  5030.0 1751.47  5046.1 1749.16  5090.9 1748.27
  5091.4 1747.77  5109.1 1748.27  5190.0 1748.59  5210.0 1751.46  5230.0 1749.22
  5258.4 1748.97  5536.6 1749.29  5560.0 1749.67  5600.0 1753.52  5700.0 1759.16
  5720.0 1761.10  5796.1 1762.55  5859.5 1762.07  5923.1 1762.24  6018.6 1764.90
#Mann=8,-1,0
  4289.8    0.07       0  5046.1   0.035       0  5090.9    0.07       0
  5109.1   0.035       0  5258.4    0.07       0  5536.6   0.035       0
  5796.1    0.07       0  5859.5   0.035       0
Bank Sta=5090.9,5109.1
Exp/Cntr=0.3,0.1

Type RM Length L Ch R = 1,8886,432,432,432
BEGIN DESCRIPTION:
Mapping XS 6d59ae22
END DESCRIPTION:
XS GIS Cut Line= 4
      1489629.38      6934531.60      1489095.50      6934553.30
      1488283.86      6934614.06      1487671.90      6935000.34
#Sta/Elev= 30
  4173.5 1773.94  4298.0 1770.74  4338.0 1770.04  4378.0 1766.67  4498.1 1761.53
  4578.2 1761.10  4598.2 1761.98  4618.2 1760.80  4738.4 1759.17  4908.9 1750.42
  4928.9 1750.38  4967.9 1747.62  4999.1 1747.71  5009.2 1746.19  5010.1 1744.84
  5010.6 1744.34  5028.3 1744.84  5029.2 1746.68  5049.3 1748.65  5149.4 1747.35
  5440.4 1747.30  5638.6 1748.65  5857.2 1748.21  5922.5 1751.21  5951.3 1754.04
  5966.6 1757.19  5987.8 1758.12  6066.7 1757.06  6170.2 1760.96  6245.4 1762.63
#Mann=5,-1,0
  4173.5   0.045       0  4298.0    0.07       0  5010.1    0.07       0
  5028.3    0.07       0  5149.4    0.07       0
Bank Sta=5010.1,5028.3
Exp/Cntr=0.3,0.1