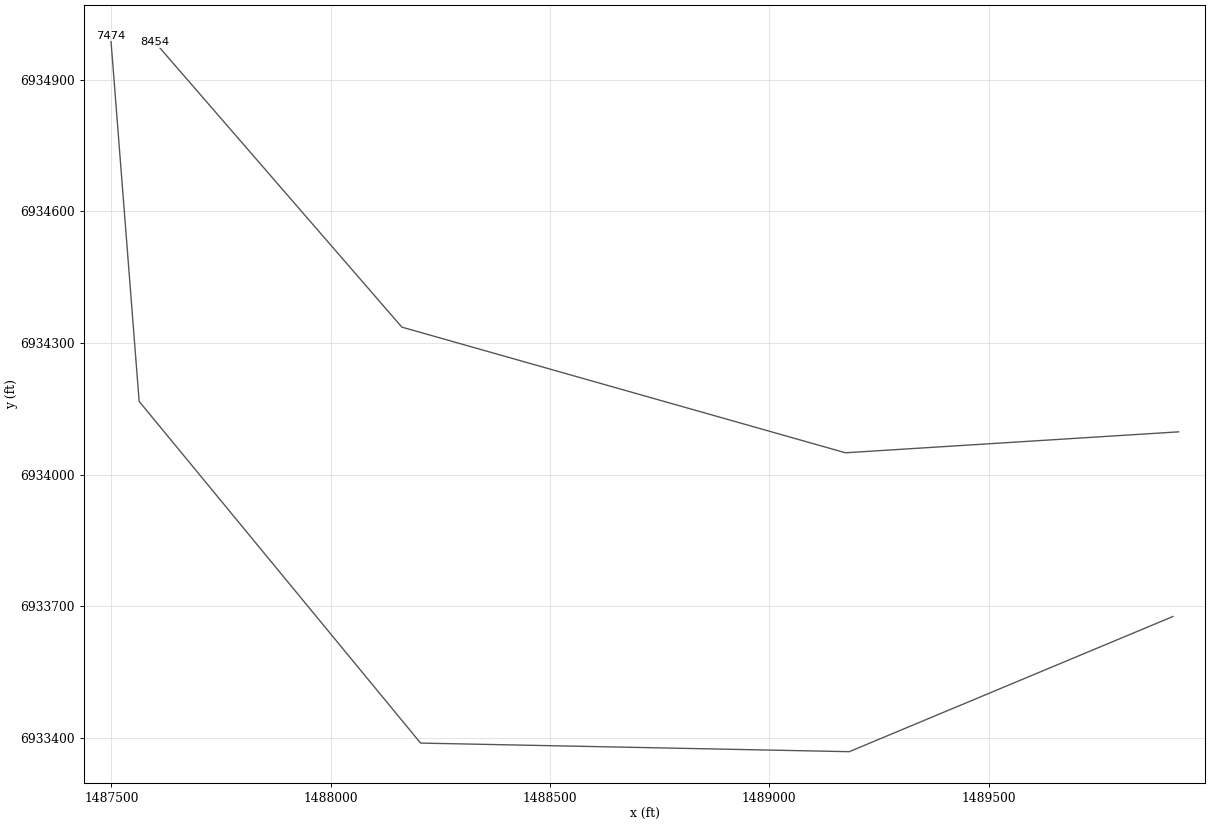
HEC-RAS study NC Unknown Stream 05.prj: NC Unknown Stream 05 Base Level Engineering

--- NC Unknown Stream 05.g01 (geometry) --- (continued)

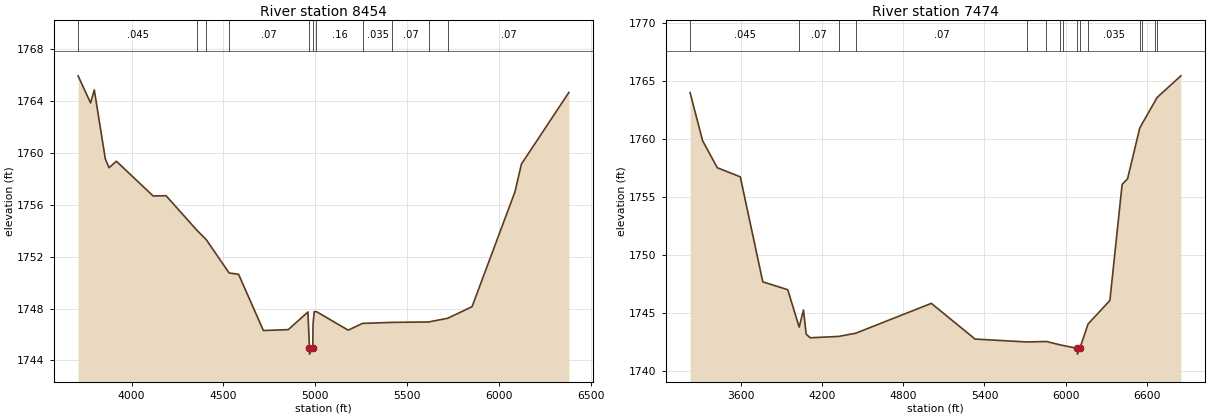
Type RM Length L Ch R = 1,8454,980,980,980
BEGIN DESCRIPTION:
Mapping XS 5762f7ab
END DESCRIPTION:
XS GIS Cut Line= 4
      1489933.13      6934097.57      1489173.62      6934049.83
      1488162.34      6934336.29      1487599.02      6934986.27
#Sta/Elev= 30
  3708.7 1765.95  3776.7 1763.86  3797.0 1764.86  3857.1 1759.54  3877.2 1758.86
  3917.2 1759.36  4117.6 1756.68  4187.8 1756.70  4356.1 1754.03  4406.8 1753.31
  4531.1 1750.74  4582.6 1750.64  4717.7 1746.30  4853.1 1746.37  4960.2 1747.73
  4968.5 1744.98  4969.0 1744.48  4986.7 1744.98  4987.9 1746.75  4994.1 1747.75
  5006.4 1747.76  5179.4 1746.33  5257.4 1746.85  5419.9 1746.93  5617.4 1746.96
  5722.0 1747.25  5853.8 1748.14  6087.4 1757.00  6122.5 1759.14  6380.9 1764.67
#Mann=11,-1,0
  3708.7   0.045       0  4356.1    0.07       0  4406.8   0.045       0
  4531.1    0.07       0  4968.5    0.07       0  4986.7    0.07       0
  5006.4    0.16       0  5257.4   0.035       0  5419.9    0.07       0
  5617.4   0.035       0  5722.0    0.07       0
Bank Sta=4968.5,4986.7
Exp/Cntr=0.3,0.1

Type RM Length L Ch R = 1,7474,0,0,0
BEGIN DESCRIPTION:
NC Unknown Stream 05 3.0
END DESCRIPTION:
XS GIS Cut Line= 5
      1489920.16      6933676.57      1489182.30      6933368.41
      1488205.00      6933388.00      1487563.38      6934167.02
      1487498.28      6935000.33
#Sta/Elev= 30
  3227.6 1764.00  3320.0 1759.85  3428.3 1757.52  3598.2 1756.73  3764.2 1747.67
  3948.4 1746.99  4032.8 1743.76  4064.5 1745.24  4084.5 1743.15  4114.5 1742.84
  4325.0 1742.96  4451.5 1743.24  5008.0 1745.81  5331.1 1742.73  5712.6 1742.48
  5857.3 1742.52  5954.4 1742.24  5978.6 1742.18  6086.1 1741.93  6086.6 1741.43
  6104.3 1741.93  6164.8 1744.03  6325.9 1746.06  6416.2 1756.08  6456.3 1756.56
  6545.8 1760.92  6563.1 1761.30  6656.0 1763.20  6674.0 1763.58  6849.8 1765.45
#Mann=15,-1,0
  3227.6   0.045       0  4032.8    0.07       0  4325.0   0.045       0
  4451.5    0.07       0  5712.6    0.16       0  5857.3    0.07       0
  5954.4    0.16       0  5978.6    0.07       0  6086.1    0.07       0
  6104.3    0.07       0  6164.8   0.035       0  6545.8    0.07       0
  6563.1   0.035       0  6656.0    0.07       0  6674.0   0.035       0
Bank Sta=6086.1,6104.3
Exp/Cntr=0.3,0.1

Chan Stop Cuts=-1