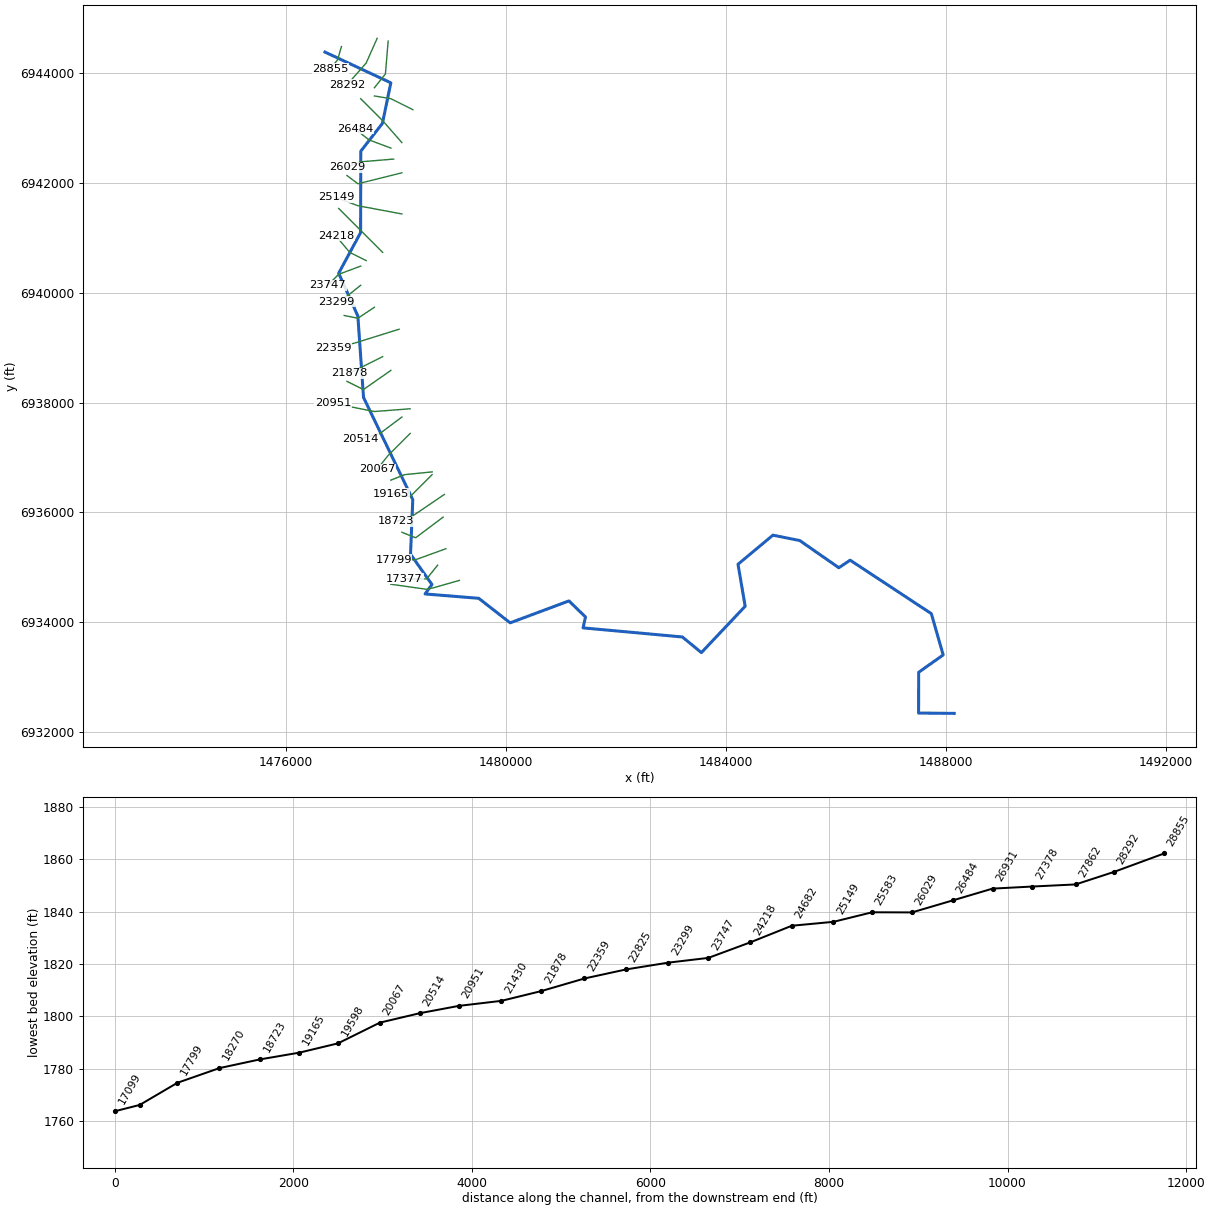
--- NC Unknown Stream 07.prj (project) ---

Proj Title=NC Unknown Stream 07 Base Level Engineering
Current Plan=p01
Default Exp/Contr=0.3,0.1
English Units
Geom File=g01
Flow File=f01
Plan File=p01
BEGIN DESCRIPTION:
NC Unknown Stream 07
END DESCRIPTION:

--- NC Unknown Stream 07.p01 (plan) ---

Plan Title=Multiple Run
Short Identifier=Multiple
Geom File=g01
Flow File=f01
Subcritical Flow
K Sum by GR= 0
Std Step Tol= 0.01
Critical Tol= 0.01
Num of Std Step Trials= 20
Max Error Tol= 0.3
Flow Tol Ratio= 0.001
Split Flow NTrial= 30
Split Flow Tol= 0.02
Split Flow Ratio= 0.02
Log Output Level= 0
Friction Slope Method= 1
Unsteady Friction Slope Method= 2
Unsteady Bridges Friction Slope Method= 1
Parabolic Critical Depth
Global Vel Dist=  1 , 1 , 1
Global Log Level= 0
CheckData=True
Encroach Param= -1, 0, 0, 0
BEGIN DESCRIPTION:
Multiple Run
END DESCRIPTION:

--- NC Unknown Stream 07.f01 (steady flow) ---

Flow Title=Multiple
Number of Profiles=7
Profile Names=10-year,25-year,50-year,1pct_min,100-year,1pct_plu,500-year
River Rch & RM= NC Unknown Strea,Reach-1,28855
     333     472     588     365     728    1452    1127
River Rch & RM= NC Unknown Strea,Reach-1,27862
     510     739     936     589    1175    2344    1873
River Rch & RM= NC Unknown Strea,Reach-1,26029
     658     966    1233     781    1559    3111    2524
River Rch & RM= NC Unknown Strea,Reach-1,17799
     767    1131    1450     921    1838    3668    2994
Boundary for River Rch & Prof#=NC Unknown Strea,Reach-1,1
Up Type=0
Dn Type=3
Dn Slope=0.001
Boundary for River Rch & Prof#=NC Unknown Strea,Reach-1,2
Up Type=0
Dn Type=3
Dn Slope=0.001
Boundary for River Rch & Prof#=NC Unknown Strea,Reach-1,3
Up Type=0
Dn Type=3
Dn Slope=0.001
Boundary for River Rch & Prof#=NC Unknown Strea,Reach-1,4
Up Type=0
Dn Type=3
Dn Slope=0.001
Boundary for River Rch & Prof#=NC Unknown Strea,Reach-1,5
Up Type=0
Dn Type=3
Dn Slope=0.001
Boundary for River Rch & Prof#=NC Unknown Strea,Reach-1,6
Up Type=0
Dn Type=3
Dn Slope=0.001
Boundary for River Rch & Prof#=NC Unknown Strea,Reach-1,7
Up Type=0
Dn Type=3
Dn Slope=0.001

--- NC Unknown Stream 07.g01 (geometry) ---

Geom Title=Existing Conditions

River Reach=NC Unknown Strea,Reach-1
Reach XY= 30
      1476705.00      6944388.00      1477903.80      6943827.50
      1477751.38      6943089.50      1477357.24      6942582.07
      1477353.80      6941098.50      1476954.90      6940358.10
      1477303.78      6939577.50      1477407.05      6938093.86
      1478303.03      6936232.10      1478262.32      6935237.90
      1478652.04      6934685.99      1478527.17      6934514.17
      1479503.53      6934434.47      1480075.12      6933987.66
      1481144.52      6934387.07      1481446.11      6934094.51
      1481401.55      6933895.80      1483208.66      6933730.33
      1483554.92      6933445.30      1484351.39      6934289.50
      1484221.27      6935055.31      1484856.46      6935585.00
      1485344.66      6935487.19      1486056.03      6934991.46
      1486261.80      6935129.23      1487738.99      6934155.13
      1487954.80      6933403.09      1487508.75      6933086.45
      1487506.88      6932343.68      1488155.00      6932338.00

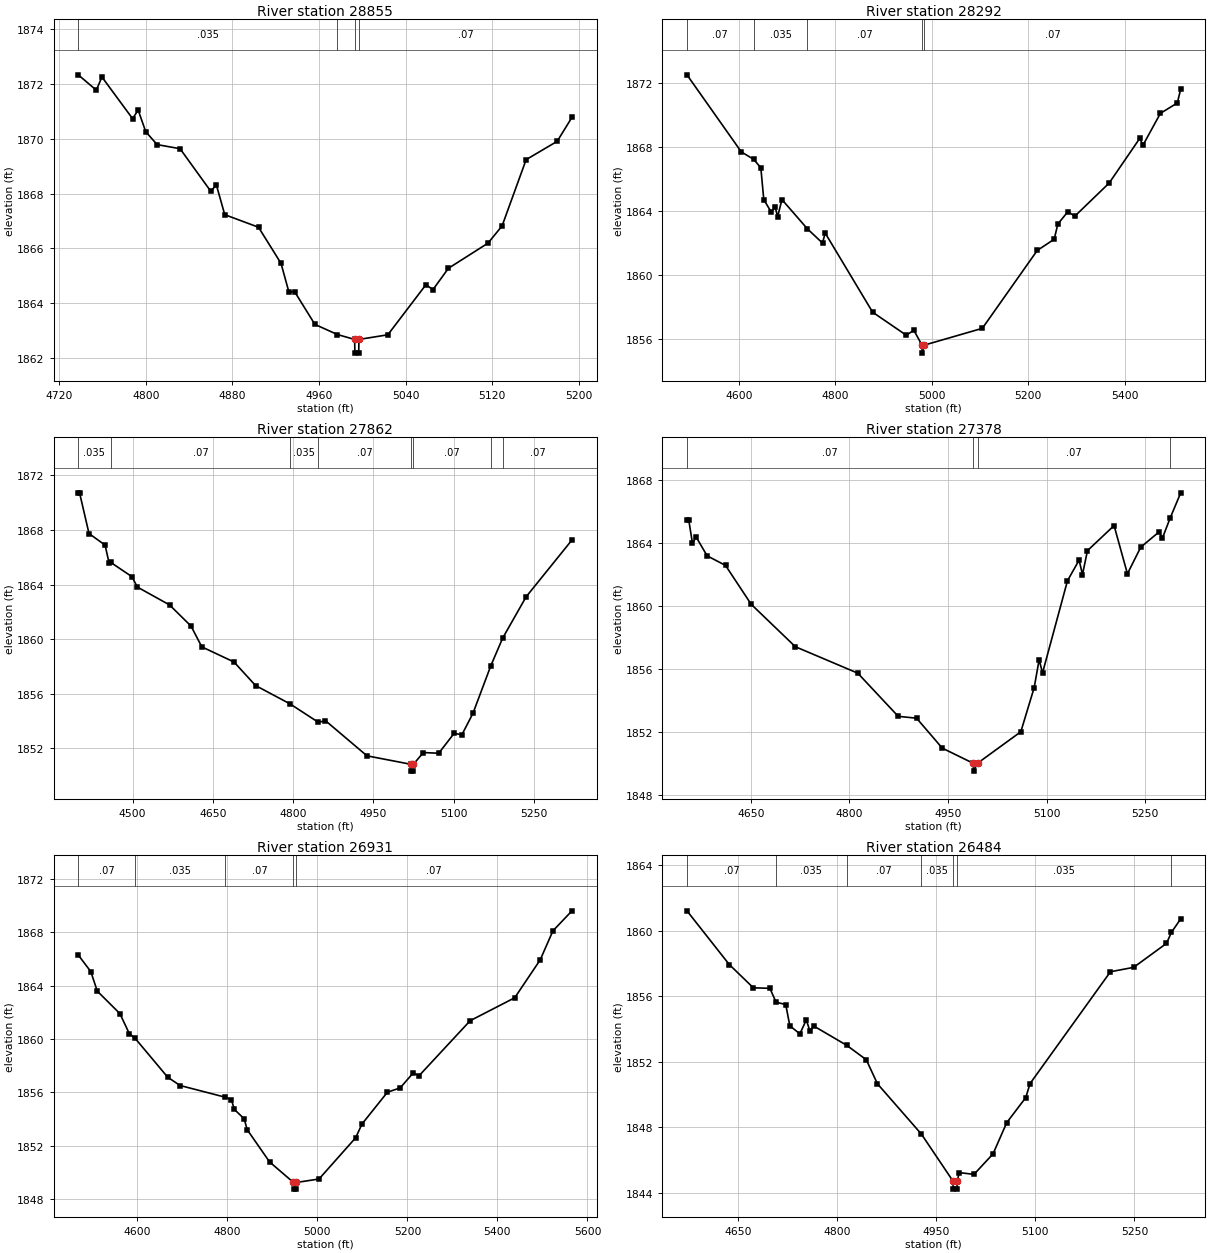
Type RM Length L Ch R = 1,28855,563,563,563
BEGIN DESCRIPTION:
NC Unknown Stream 07 42.0
END DESCRIPTION:
XS GIS Cut Line= 3
      1477004.99      6944487.96      1476934.76      6944246.73
      1476804.97      6944087.97
#Sta/Elev= 30
  4737.5 1872.34  4754.2 1871.78  4759.4 1872.26  4787.7 1870.74  4792.9 1871.05
  4799.9 1870.26  4810.4 1869.79  4831.6 1869.64  4859.9 1868.09  4865.2 1868.31
  4872.9 1867.23  4904.1 1866.77  4924.9 1865.45  4932.2 1864.40  4937.4 1864.42
  4956.2 1863.22  4977.0 1862.85  4992.9 1862.67  4993.2 1862.17  4996.7 1862.17
  4996.9 1862.67  5023.6 1862.84  5058.8 1864.67  5065.3 1864.49  5079.6 1865.27
  5116.2 1866.19  5129.2 1866.82  5151.4 1869.24  5180.1 1869.91  5193.8 1870.79
#Mann=4,-1,0
  4737.5   0.035       0  4977.0    0.07       0  4992.9    0.07       0
  4996.9    0.07       0
Bank Sta=4992.9,4996.9
Exp/Cntr=0.3,0.1

Type RM Length L Ch R = 1,28292,430,430,430
BEGIN DESCRIPTION:
NC Unknown Stream 07 41.0
END DESCRIPTION:
XS GIS Cut Line= 3
      1477654.99      6944637.98      1477455.00      6944188.00
      1477105.02      6943788.03
#Sta/Elev= 30
  4492.3 1872.51  4605.1 1867.69  4630.5 1867.23  4645.5 1866.70  4651.6 1864.71
  4667.4 1863.91  4674.9 1864.26  4680.4 1863.65  4689.3 1864.71  4742.1 1862.88
  4773.4 1861.99  4778.9 1862.62  4877.3 1857.67  4947.1 1856.23  4962.8 1856.54
  4979.7 1855.61  4980.0 1855.11  4984.3 1855.61  5104.8 1856.66  5218.7 1861.53
  5253.8 1862.23  5261.4 1863.18  5282.3 1863.96  5296.5 1863.67  5367.7 1865.74
  5431.3 1868.54  5437.9 1868.11  5474.0 1870.10  5509.1 1870.75  5516.2 1871.62
#Mann=5,-1,0
  4492.3    0.07       0  4630.5   0.035       0  4742.1    0.07       0
  4979.7    0.07       0  4984.3    0.07       0
Bank Sta=4979.7,4984.3
Exp/Cntr=0.3,0.1

Type RM Length L Ch R = 1,27862,484,484,484
BEGIN DESCRIPTION:
NC Unknown Stream 07 40.0
END DESCRIPTION:
XS GIS Cut Line= 3
      1477855.00      6944587.98      1477805.00      6943988.00
      1477605.01      6943738.01
#Sta/Elev= 30
  4398.6 1870.72  4401.1 1870.72  4418.7 1867.74  4448.8 1866.89  4456.3 1865.56
  4459.1 1865.63  4498.9 1864.58  4509.0 1863.82  4569.2 1862.51  4609.3 1860.96
  4629.4 1859.44  4689.6 1858.33  4729.7 1856.61  4794.4 1855.26  4847.3 1853.91
  4860.2 1854.04  4937.9 1851.46  5020.0 1850.84  5020.3 1850.34  5024.3 1850.34
  5024.6 1850.84  5043.1 1851.70  5071.9 1851.65  5100.7 1853.11  5115.1 1853.00
  5135.9 1854.58  5169.3 1858.07  5191.3 1860.08  5235.2 1863.11  5320.8 1867.27
#Mann=8,-1,0
  4398.6   0.035       0  4459.1    0.07       0  4794.4   0.035       0
  4847.3    0.07       0  5020.0    0.07       0  5024.6    0.07       0
  5169.3   0.035       0  5191.3    0.07       0
Bank Sta=5020,5024.6
Exp/Cntr=0.3,0.1

Type RM Length L Ch R = 1,27378,447,447,447
BEGIN DESCRIPTION:
NC Unknown Stream 07 39.0
END DESCRIPTION:
XS GIS Cut Line= 3
      1478304.97      6943338.01      1477905.00      6943538.00
      1477605.02      6943588.00
#Sta/Elev= 30
  4552.9 1865.47  4555.7 1865.47  4561.3 1864.00  4566.8 1864.41  4583.6 1863.21
  4611.6 1862.60  4650.7 1860.13  4717.8 1857.44  4812.8 1855.76  4874.3 1853.02
  4902.3 1852.90  4941.4 1851.00  4988.4 1850.04  4988.9 1849.54  4995.0 1850.04
  5060.9 1852.04  5081.2 1854.84  5088.8 1856.62  5093.9 1855.77  5131.9 1861.63
  5149.6 1862.94  5154.7 1862.02  5162.3 1863.54  5202.8 1865.13  5223.1 1862.07
  5243.4 1863.76  5271.3 1864.73  5276.3 1864.33  5288.3 1865.63  5304.2 1867.21
#Mann=4,-1,0
  4552.9    0.07       0  4988.4    0.07       0  4995.0    0.07       0
  5288.3   0.035       0
Bank Sta=4988.4,4995
Exp/Cntr=0.3,0.1

Type RM Length L Ch R = 1,26931,447,447,447
BEGIN DESCRIPTION:
NC Unknown Stream 07 38.0
END DESCRIPTION:
XS GIS Cut Line= 3
      1478105.01      6942737.99      1477755.00      6943138.00
      1477355.01      6943537.99
#Sta/Elev= 30
  4468.5 1866.30  4496.5 1865.05  4510.8 1863.59  4561.1 1861.90  4581.9 1860.41
  4595.1 1860.04  4667.4 1857.13  4694.9 1856.51  4795.6 1855.63  4808.8 1855.45
  4815.4 1854.72  4837.3 1854.01  4843.9 1853.20  4893.7 1850.78  4946.8 1849.24
  4947.3 1848.74  4953.0 1848.74  4953.5 1849.24  5003.6 1849.50  5084.9 1852.59
  5099.0 1853.62  5155.6 1856.01  5183.9 1856.33  5212.2 1857.43  5226.3 1857.26
  5339.4 1861.37  5438.4 1863.09  5495.0 1865.93  5523.3 1868.11  5565.7 1869.61
#Mann=5,-1,0
  4468.5    0.07       0  4595.1   0.035       0  4795.6    0.07       0
  4946.8    0.07       0  4953.5    0.07       0
Bank Sta=4946.8,4953.5
Exp/Cntr=0.3,0.1

Type RM Length L Ch R = 1,26484,455,455,455
BEGIN DESCRIPTION:
NC Unknown Stream 07 37.0
END DESCRIPTION:
XS GIS Cut Line= 3
      1477904.98      6942638.01      1477505.00      6942788.00
      1477255.03      6942987.98
#Sta/Elev= 30
  4572.8 1861.22  4636.9 1857.94  4673.3 1856.52  4698.3 1856.49  4707.7 1855.64
  4722.3 1855.50  4728.5 1854.20  4743.7 1853.71  4753.4 1854.56  4758.8 1853.90
  4765.0 1854.18  4814.6 1853.01  4844.2 1852.13  4861.1 1850.66  4927.6 1847.59
  4975.3 1844.73  4975.8 1844.23  4981.5 1844.23  4982.0 1844.73  4984.8 1845.24
  5007.2 1845.13  5036.0 1846.38  5056.8 1848.29  5085.6 1849.82  5092.0 1850.67
  5213.7 1857.50  5248.9 1857.77  5298.5 1859.23  5306.1 1859.91  5320.1 1860.73
#Mann=7,-1,0
  4572.8    0.07       0  4707.7   0.035       0  4814.6    0.07       0
  4927.6   0.035       0  4975.3   0.035       0  4982.0   0.035       0
  5306.1    0.07       0
Bank Sta=4975.3,4982
Exp/Cntr=0.3,0.1

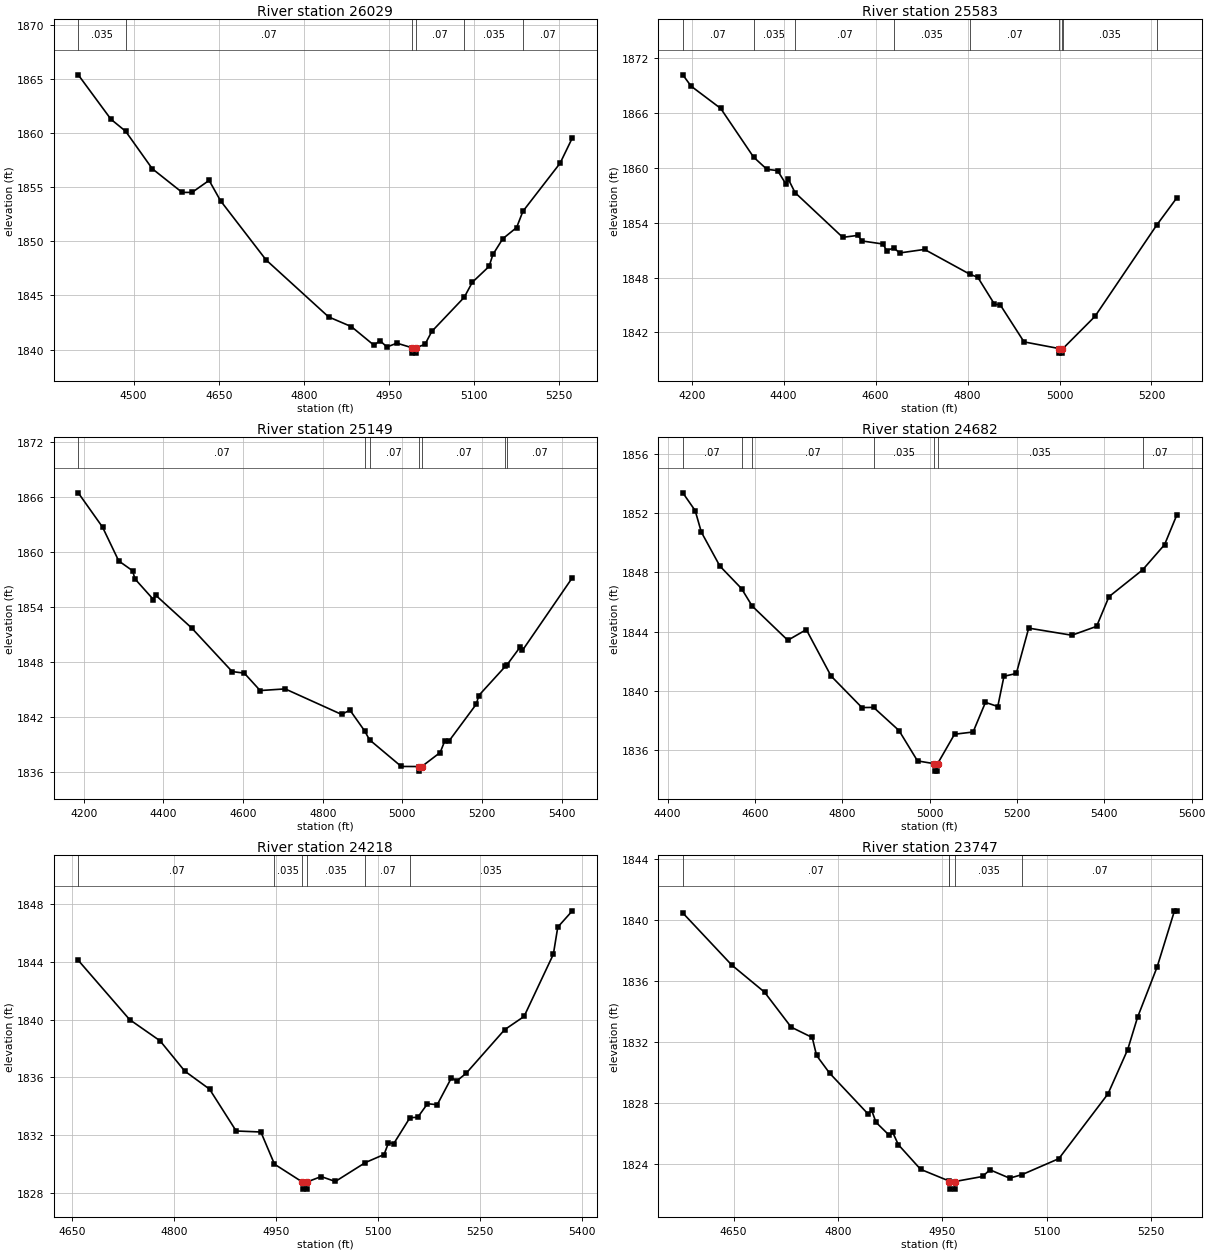
Type RM Length L Ch R = 1,26029,446,446,446
BEGIN DESCRIPTION:
NC Unknown Stream 07 36.0
END DESCRIPTION:
XS GIS Cut Line= 3
      1477955.02      6942438.00      1477355.00      6942388.00
      1477104.96      6942287.98
#Sta/Elev= 30
  4402.3 1865.40  4460.0 1861.29  4485.9 1860.18  4532.8 1856.72  4585.5 1854.53
  4603.0 1854.53  4633.1 1855.64  4653.2 1853.76  4733.5 1848.29  4843.8 1843.02
  4884.0 1842.12  4924.1 1840.39  4934.2 1840.83  4946.7 1840.24  4964.3 1840.59
  4990.9 1840.17  4991.4 1839.67  4997.3 1839.67  4997.8 1840.17  5013.8 1840.48
  5025.9 1841.68  5083.0 1844.83  5097.3 1846.22  5126.9 1847.69  5133.6 1848.79
  5151.1 1850.25  5175.4 1851.28  5186.5 1852.78  5252.1 1857.23  5273.7 1859.57
#Mann=6,-1,0
  4402.3   0.035       0  4485.9    0.07       0  4990.9    0.07       0
  4997.8    0.07       0  5083.0   0.035       0  5186.5    0.07       0
Bank Sta=4990.9,4997.8
Exp/Cntr=0.3,0.1

Type RM Length L Ch R = 1,25583,434,434,434
BEGIN DESCRIPTION:
NC Unknown Stream 07 35.0
END DESCRIPTION:
XS GIS Cut Line= 3
      1478104.96      6942187.99      1477305.00      6941988.00
      1477104.98      6942138.01
#Sta/Elev= 30
  4180.7 1870.20  4198.7 1868.96  4263.1 1866.52  4334.6 1861.19  4363.6 1859.85
  4386.8 1859.71  4404.9 1858.24  4410.0 1858.79  4424.8 1857.30  4528.5 1852.40
  4562.0 1852.62  4569.8 1852.01  4616.2 1851.67  4623.9 1850.95  4639.8 1851.24
  4652.2 1850.69  4706.4 1851.08  4804.3 1848.38  4822.3 1848.02  4858.4 1845.09
  4871.3 1844.99  4922.8 1840.95  4999.2 1840.22  4999.7 1839.72  5005.7 1839.72
  5006.2 1840.22  5007.4 1840.22  5077.2 1843.75  5211.2 1853.73  5255.3 1856.74
#Mann=9,-1,0
  4180.7    0.07       0  4334.6   0.035       0  4424.8    0.07       0
  4639.8   0.035       0  4804.3    0.07       0  4999.2    0.07       0
  5006.2    0.07       0  5007.4   0.035       0  5211.2    0.07       0
Bank Sta=4999.2,5006.2
Exp/Cntr=0.3,0.1

Type RM Length L Ch R = 1,25149,467,467,467
BEGIN DESCRIPTION:
NC Unknown Stream 07 34.0
END DESCRIPTION:
XS GIS Cut Line= 3
      1478104.95      6941438.01      1477305.00      6941588.00
      1476904.99      6941738.00
#Sta/Elev= 30
  4186.0 1866.44  4247.0 1862.70  4287.7 1859.01  4322.5 1857.94  4328.4 1857.05
  4375.0 1854.79  4380.1 1855.29  4470.8 1851.70  4572.6 1846.94  4603.1 1846.77
  4642.9 1844.87  4705.7 1845.05  4847.3 1842.27  4868.5 1842.73  4905.5 1840.46
  4917.6 1839.50  4997.4 1836.59  5041.7 1836.58  5042.2 1836.08  5048.8 1836.58
  5095.1 1838.11  5106.7 1839.38  5117.4 1839.37  5185.9 1843.39  5192.1 1844.33
  5258.8 1847.51  5263.2 1847.69  5296.3 1849.63  5301.6 1849.24  5427.1 1857.18
#Mann=7,-1,0
  4186.0    0.07       0  4905.5   0.035       0  4917.6    0.07       0
  5041.7    0.07       0  5048.8    0.07       0  5258.8   0.035       0
  5263.2    0.07       0
Bank Sta=5041.7,5048.8
Exp/Cntr=0.3,0.1

Type RM Length L Ch R = 1,24682,464,464,464
BEGIN DESCRIPTION:
NC Unknown Stream 07 33.0
END DESCRIPTION:
XS GIS Cut Line= 3
      1477755.00      6940738.00      1477355.00      6941138.00
      1476954.97      6941538.03
#Sta/Elev= 30
  4434.9 1853.36  4463.2 1852.16  4477.3 1850.71  4519.7 1848.42  4569.3 1846.90
  4593.7 1845.72  4675.3 1843.41  4717.7 1844.13  4774.3 1841.00  4845.0 1838.87
  4871.8 1838.88  4929.9 1837.32  4972.3 1835.27  5011.1 1835.08  5011.6 1834.58
  5017.8 1834.58  5018.3 1835.08  5057.1 1837.07  5099.6 1837.22  5127.9 1839.22
  5156.1 1838.94  5170.3 1840.98  5198.6 1841.17  5226.9 1844.23  5325.8 1843.75
  5382.4 1844.35  5410.7 1846.35  5487.7 1848.16  5538.0 1849.86  5566.3 1851.88
#Mann=7,-1,0
  4434.9    0.07       0  4569.3   0.035       0  4593.7    0.07       0
  4871.8   0.035       0  5011.1   0.035       0  5018.3   0.035       0
  5487.7    0.07       0
Bank Sta=5011.1,5018.3
Exp/Cntr=0.3,0.1

Type RM Length L Ch R = 1,24218,471,471,471
BEGIN DESCRIPTION:
NC Unknown Stream 07 32.0
END DESCRIPTION:
XS GIS Cut Line= 3
      1477455.01      6940587.99      1477155.00      6940738.00
      1476905.02      6941037.97
#Sta/Elev= 30
  4659.5 1844.12  4735.0 1840.01  4779.7 1838.54  4816.0 1836.44  4852.4 1835.19
  4891.5 1832.29  4927.8 1832.22  4947.8 1829.99  4988.5 1828.76  4989.0 1828.26
  4995.2 1828.26  4995.7 1828.76  5016.4 1829.13  5037.2 1828.79  5081.3 1830.10
  5108.8 1830.66  5115.3 1831.47  5123.1 1831.42  5146.8 1833.21  5158.3 1833.24
  5172.6 1834.18  5186.9 1834.11  5207.8 1835.98  5215.6 1835.76  5229.2 1836.28
  5285.9 1839.31  5314.5 1840.23  5357.5 1844.54  5364.0 1846.42  5385.4 1847.55
#Mann=6,-1,0
  4659.5    0.07       0  4947.8   0.035       0  4988.5   0.035       0
  4995.7   0.035       0  5081.3    0.07       0  5146.8   0.035       0
Bank Sta=4988.5,4995.7
Exp/Cntr=0.3,0.1

Type RM Length L Ch R = 1,23747,448,448,448
BEGIN DESCRIPTION:
NC Unknown Stream 07 31.0
END DESCRIPTION:
XS GIS Cut Line= 3
      1477354.95      6940487.98      1476955.00      6940338.00
      1476755.00      6940138.00
#Sta/Elev= 30
  4576.9 1840.46  4647.2 1837.04  4694.3 1835.26  4732.6 1832.96  4762.9 1832.28
  4769.1 1831.10  4787.8 1829.94  4843.0 1827.26  4848.3 1827.49  4854.5 1826.71
  4873.2 1825.87  4878.6 1826.04  4886.6 1825.24  4918.6 1823.62  4959.2 1822.86
  4960.1 1822.82  4960.6 1822.32  4967.5 1822.32  4968.0 1822.82  5007.6 1823.15
  5018.2 1823.59  5046.5 1823.04  5064.2 1823.27  5117.2 1824.32  5187.9 1828.58
  5216.2 1831.49  5230.3 1833.60  5258.6 1836.93  5283.4 1840.60  5286.9 1840.60
#Mann=5,-1,0
  4576.9    0.07       0  4959.2   0.035       0  4960.1   0.035       0
  4968.0   0.035       0  5064.2    0.07       0
Bank Sta=4960.1,4968
Exp/Cntr=0.3,0.1

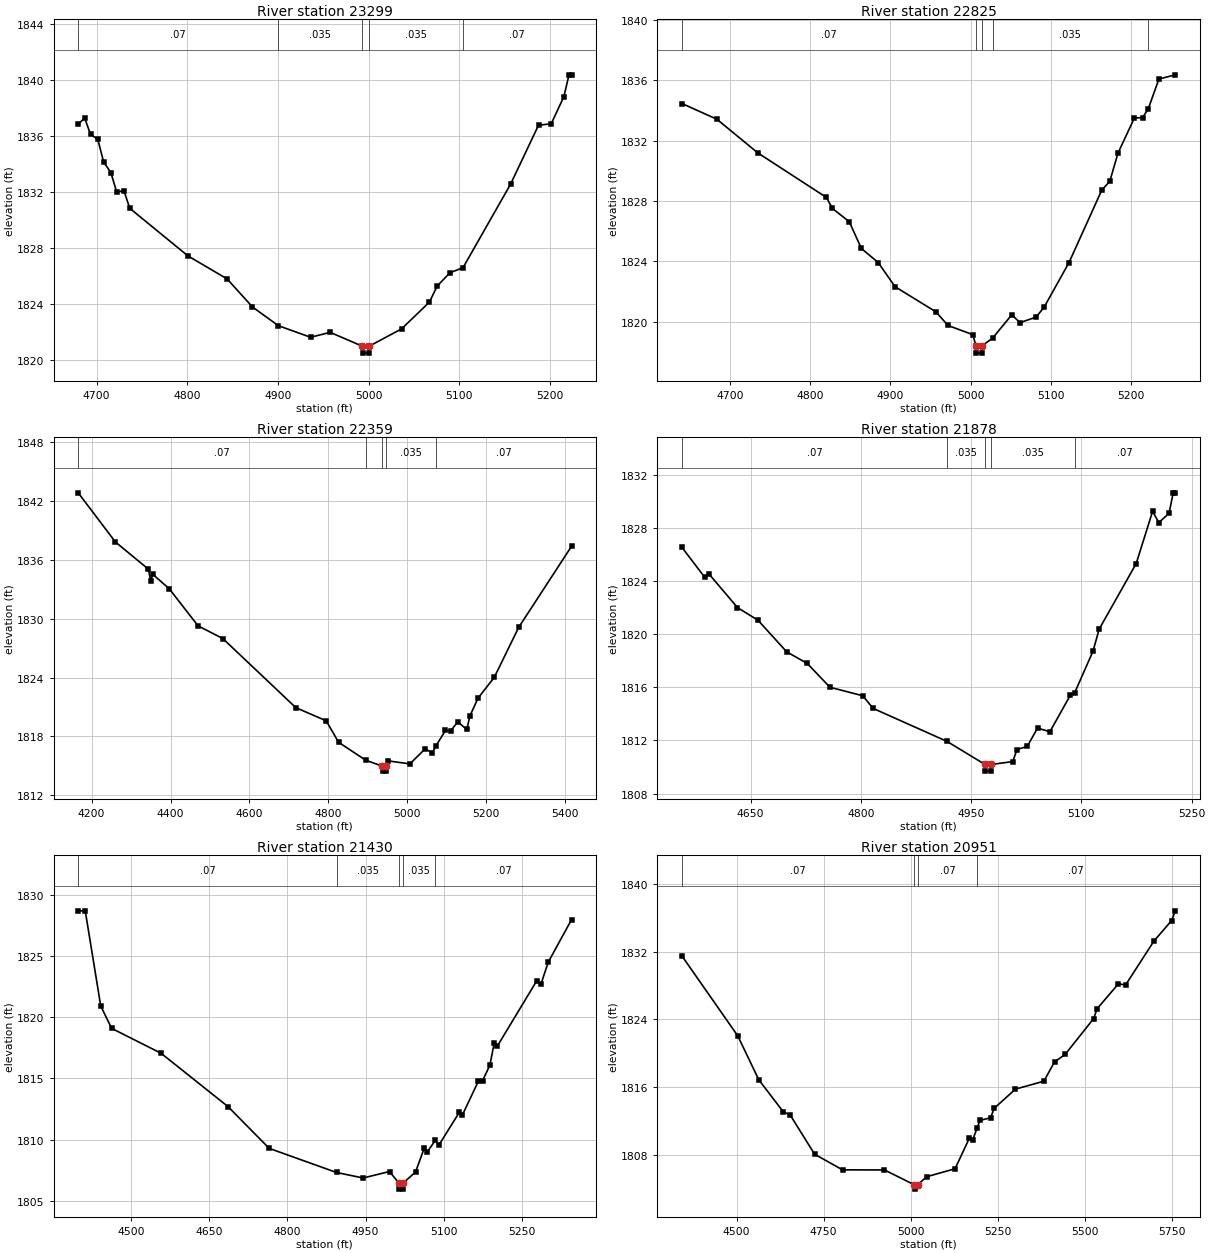
Type RM Length L Ch R = 1,23299,474,474,474
BEGIN DESCRIPTION:
NC Unknown Stream 07 30.0
END DESCRIPTION:
XS GIS Cut Line= 3
      1477355.00      6940138.00      1477105.00      6939938.00
      1476904.97      6939837.99
#Sta/Elev= 30
  4679.8 1836.85  4687.0 1837.26  4693.4 1836.10  4701.4 1835.76  4707.8 1834.14
  4715.8 1833.39  4722.2 1832.00  4730.2 1832.10  4736.6 1830.84  4800.7 1827.45
  4843.9 1825.81  4871.9 1823.81  4900.3 1822.48  4935.9 1821.65  4957.5 1822.00
  4992.8 1821.02  4993.3 1820.52  5000.2 1820.52  5000.7 1821.02  5036.3 1822.25
  5067.0 1824.16  5075.4 1825.29  5089.4 1826.24  5104.0 1826.61  5156.5 1832.57
  5187.2 1836.76  5201.2 1836.86  5215.2 1838.80  5220.8 1840.35  5223.6 1840.35
#Mann=5,-1,0
  4679.8    0.07       0  4900.3   0.035       0  4992.8   0.035       0
  5000.7   0.035       0  5104.0    0.07       0
Bank Sta=4992.8,5000.7
Exp/Cntr=0.3,0.1

Type RM Length L Ch R = 1,22825,466,466,466
BEGIN DESCRIPTION:
NC Unknown Stream 07 29.0
END DESCRIPTION:
XS GIS Cut Line= 3
      1477605.01      6939738.01      1477305.00      6939538.00
      1477055.02      6939588.00
#Sta/Elev= 30
  4639.9 1834.45  4683.5 1833.41  4734.6 1831.18  4820.2 1828.23  4827.7 1827.50
  4848.7 1826.62  4863.8 1824.85  4884.8 1823.92  4905.8 1822.32  4956.9 1820.65
  4971.9 1819.75  5003.0 1819.14  5006.6 1818.42  5007.1 1817.92  5014.2 1817.92
  5014.7 1818.42  5027.6 1818.92  5051.5 1820.46  5061.7 1819.94  5082.0 1820.31
  5092.2 1821.00  5122.8 1823.91  5163.6 1828.70  5173.8 1829.31  5184.0 1831.17
  5204.4 1833.49  5214.6 1833.52  5221.6 1834.08  5235.0 1836.07  5255.4 1836.35
#Mann=5,-1,0
  4639.9    0.07       0  5006.6    0.07       0  5014.7    0.07       0
  5027.6   0.035       0  5221.6    0.07       0
Bank Sta=5006.6,5014.7
Exp/Cntr=0.3,0.1

Type RM Length L Ch R = 1,22359,481,481,481
BEGIN DESCRIPTION:
NC Unknown Stream 07 28.0
END DESCRIPTION:
XS GIS Cut Line= 3
      1478054.98      6939337.99      1477255.00      6939088.00
      1476855.04      6938988.01
#Sta/Elev= 30
  4166.0 1842.84  4260.3 1837.83  4344.1 1835.05  4349.8 1833.86  4355.1 1834.53
  4396.5 1833.07  4469.8 1829.28  4532.7 1827.98  4717.6 1820.94  4794.6 1819.60
  4826.0 1817.41  4894.4 1815.59  4937.1 1814.97  4937.6 1814.47  4944.9 1814.47
  4945.4 1814.97  4950.2 1815.52  5006.7 1815.21  5045.4 1816.74  5063.4 1816.34
  5072.1 1817.00  5096.9 1818.62  5109.8 1818.55  5127.8 1819.49  5151.0 1818.72
  5158.7 1820.08  5179.4 1821.91  5220.6 1824.03  5282.4 1829.12  5416.4 1837.39
#Mann=5,-1,0
  4166.0    0.07       0  4894.4   0.035       0  4937.1   0.035       0
  4945.4   0.035       0  5072.1    0.07       0
Bank Sta=4937.1,4945.4
Exp/Cntr=0.3,0.1

Type RM Length L Ch R = 1,21878,448,448,448
BEGIN DESCRIPTION:
NC Unknown Stream 07 27.0
END DESCRIPTION:
XS GIS Cut Line= 3
      1477755.03      6938838.02      1477355.00      6938638.00
      1477154.96      6938537.98
#Sta/Elev= 30
  4556.7 1826.53  4587.5 1824.29  4593.1 1824.55  4632.2 1822.00  4660.2 1821.04
  4699.3 1818.66  4727.2 1817.79  4758.0 1816.00  4802.7 1815.36  4816.7 1814.41
  4917.1 1811.93  4969.0 1810.19  4969.5 1809.69  4976.9 1809.69  4977.4 1810.19
  5006.7 1810.41  5012.3 1811.31  5026.3 1811.55  5040.3 1812.93  5057.1 1812.65
  5085.0 1815.41  5090.8 1815.58  5115.8 1818.72  5124.1 1820.37  5174.5 1825.31
  5196.8 1829.24  5205.2 1828.39  5219.2 1829.09  5224.8 1830.63  5227.6 1830.63
#Mann=5,-1,0
  4556.7    0.07       0  4917.1   0.035       0  4969.0   0.035       0
  4977.4   0.035       0  5090.8    0.07       0
Bank Sta=4969,4977.4
Exp/Cntr=0.3,0.1

Type RM Length L Ch R = 1,21430,479,479,479
BEGIN DESCRIPTION:
NC Unknown Stream 07 26.0
END DESCRIPTION:
XS GIS Cut Line= 3
      1477904.99      6938588.00      1477405.00      6938238.00
      1477105.03      6938387.99
#Sta/Elev= 30
  4399.1 1828.70  4412.6 1828.69  4442.3 1820.92  4463.2 1819.09  4557.8 1817.06
  4686.4 1812.69  4765.3 1809.28  4894.3 1807.31  4945.3 1806.86  4995.9 1807.39
  5013.6 1806.45  5014.1 1805.95  5021.6 1805.95  5022.1 1806.45  5045.8 1807.35
  5062.5 1809.31  5068.1 1808.98  5083.6 1809.93  5090.5 1809.55  5129.6 1812.22
  5135.2 1811.97  5165.9 1814.75  5174.3 1814.82  5188.3 1816.08  5196.7 1817.92
  5202.3 1817.62  5277.7 1822.95  5286.1 1822.69  5300.1 1824.50  5344.8 1827.98
#Mann=5,-1,0
  4399.1    0.07       0  4894.3   0.035       0  5013.6   0.035       0
  5022.1   0.035       0  5083.6    0.07       0
Bank Sta=5013.6,5022.1
Exp/Cntr=0.3,0.1

Type RM Length L Ch R = 1,20951,437,437,437
BEGIN DESCRIPTION:
NC Unknown Stream 07 25.0
END DESCRIPTION:
XS GIS Cut Line= 3
      1478254.96      6937888.00      1477605.00      6937838.00
      1476855.03      6937987.99
#Sta/Elev= 30
  4343.2 1831.49  4503.6 1822.07  4563.8 1816.91  4634.0 1813.14  4654.1 1812.75
  4724.3 1808.13  4804.5 1806.29  4924.9 1806.28  5011.1 1804.52  5011.6 1804.02
  5019.8 1804.52  5046.1 1805.48  5127.6 1806.42  5168.4 1810.00  5178.6 1809.86
  5191.5 1811.27  5199.0 1812.12  5229.6 1812.42  5239.8 1813.53  5301.0 1815.80
  5382.6 1816.73  5413.2 1819.00  5443.8 1819.89  5525.4 1824.10  5535.6 1825.27
  5596.8 1828.21  5617.2 1828.06  5698.7 1833.24  5749.7 1835.66  5759.9 1836.80
#Mann=4,-1,0
  4343.2    0.07       0  5011.1    0.07       0  5019.8    0.07       0
  5191.5    0.07       0
Bank Sta=5011.1,5019.8
Exp/Cntr=0.3,0.1

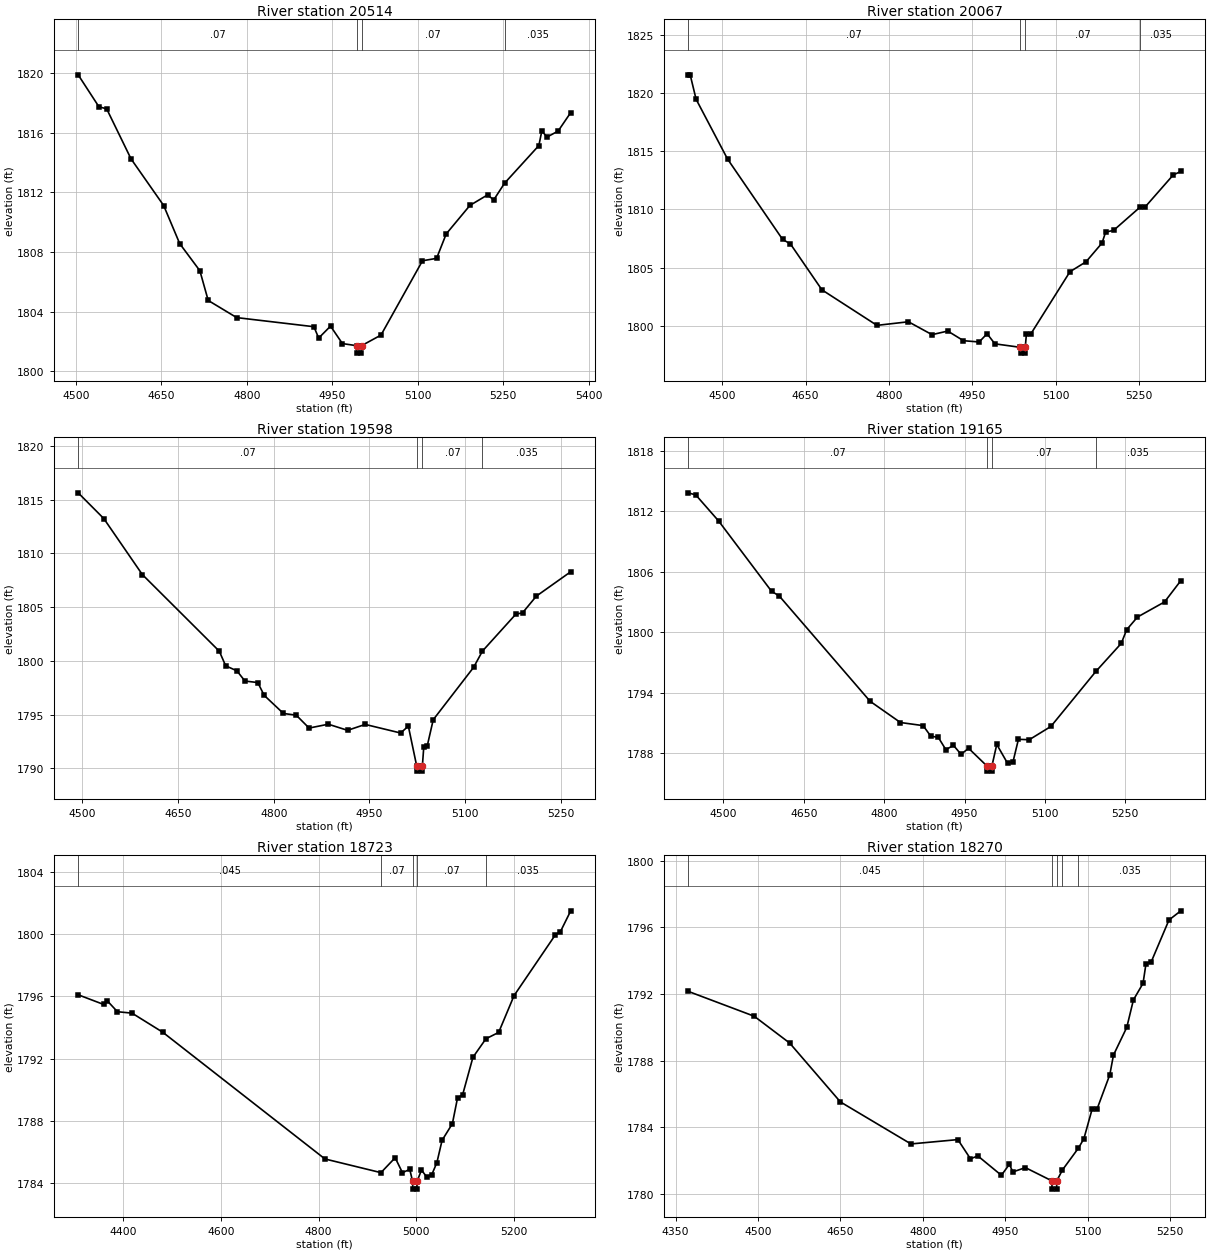
Type RM Length L Ch R = 1,20514,447,447,447
BEGIN DESCRIPTION:
NC Unknown Stream 07 24.0
END DESCRIPTION:
XS GIS Cut Line= 3
      1478104.99      6937737.99      1477705.00      6937438.00
      1477354.99      6937338.00
#Sta/Elev= 30
  4504.3 1819.88  4540.7 1817.74  4554.3 1817.60  4597.0 1814.25  4654.3 1811.12
  4682.4 1808.57  4717.8 1806.75  4732.4 1804.76  4782.4 1803.61  4917.8 1803.00
  4926.2 1802.24  4947.0 1803.04  4967.8 1801.87  4992.6 1801.73  4993.1 1801.23
  5000.9 1801.23  5001.4 1801.73  5035.5 1802.44  5108.3 1807.42  5133.0 1807.58
  5149.9 1809.22  5191.5 1811.13  5222.7 1811.84  5233.1 1811.49  5252.3 1812.62
  5312.4 1815.14  5317.6 1816.12  5326.7 1815.71  5346.2 1816.11  5368.3 1817.35
#Mann=4,-1,0
  4504.3    0.07       0  4992.6    0.07       0  5001.4    0.07       0
  5252.3   0.035       0
Bank Sta=4992.6,5001.4
Exp/Cntr=0.3,0.1

Type RM Length L Ch R = 1,20067,469,469,469
BEGIN DESCRIPTION:
NC Unknown Stream 07 23.0
END DESCRIPTION:
XS GIS Cut Line= 3
      1478254.99      6937437.99      1477855.00      6937038.00
      1477655.02      6936788.02
#Sta/Elev= 30
  4439.1 1821.59  4442.6 1821.59  4453.2 1819.49  4509.8 1814.34  4608.8 1807.42
  4622.9 1807.03  4679.5 1803.08  4778.5 1800.02  4835.1 1800.33  4877.5 1799.22
  4905.8 1799.53  4934.1 1798.70  4962.3 1798.59  4976.5 1799.30  4990.6 1798.43
  5036.3 1798.13  5036.8 1797.63  5044.7 1797.63  5045.2 1798.13  5047.2 1799.24
  5055.2 1799.28  5125.6 1804.64  5154.4 1805.49  5183.3 1807.11  5189.7 1808.05
  5204.1 1808.20  5252.2 1810.22  5260.9 1810.22  5311.3 1812.97  5324.9 1813.27
#Mann=4,-1,0
  4439.1    0.07       0  5036.3    0.07       0  5045.2    0.07       0
  5252.2   0.035       0
Bank Sta=5036.3,5045.2
Exp/Cntr=0.3,0.1

Type RM Length L Ch R = 1,19598,433,433,433
BEGIN DESCRIPTION:
NC Unknown Stream 07 22.0
END DESCRIPTION:
XS GIS Cut Line= 3
      1478654.98      6936738.00      1478155.00      6936688.00
      1477905.03      6936588.01
#Sta/Elev= 30
  4493.6 1815.65  4533.8 1813.25  4594.1 1808.04  4714.7 1800.90  4724.7 1799.54
  4742.3 1799.07  4754.9 1798.12  4775.0 1797.98  4785.0 1796.79  4815.2 1795.10
  4835.3 1794.94  4855.4 1793.74  4885.5 1794.10  4915.7 1793.53  4943.3 1794.08
  4998.8 1793.28  5010.9 1793.92  5023.9 1790.23  5024.4 1789.73  5032.4 1789.73
  5032.9 1790.23  5035.1 1792.00  5040.5 1792.08  5049.9 1794.52  5113.2 1799.40
  5127.0 1800.91  5179.2 1804.34  5189.9 1804.48  5211.5 1806.03  5265.3 1808.30
#Mann=4,-1,0
  4493.6    0.07       0  5023.9    0.07       0  5032.9    0.07       0
  5127.0   0.035       0
Bank Sta=5023.9,5032.9
Exp/Cntr=0.3,0.1

Type RM Length L Ch R = 1,19165,442,442,442
BEGIN DESCRIPTION:
NC Unknown Stream 07 21.0
END DESCRIPTION:
XS GIS Cut Line= 3
      1478654.99      6936687.99      1478255.00      6936288.00
      1477905.03      6936338.00
#Sta/Elev= 30
  4434.3 1813.84  4448.4 1813.63  4490.9 1811.05  4589.9 1804.05  4604.0 1803.60
  4773.7 1793.13  4830.3 1791.02  4872.7 1790.71  4886.8 1789.67  4901.0 1789.54
  4915.1 1788.32  4929.3 1788.75  4943.4 1787.86  4957.5 1788.46  4991.9 1786.69
  4992.4 1786.19  5000.5 1786.19  5001.0 1786.69  5010.1 1788.84  5030.3 1786.96
  5040.4 1787.12  5050.5 1789.35  5070.7 1789.31  5111.1 1790.63  5195.1 1796.10
  5242.4 1798.88  5252.5 1800.24  5272.7 1801.50  5323.2 1803.00  5353.5 1805.11
#Mann=4,-1,0
  4434.3    0.07       0  4991.9    0.07       0  5001.0    0.07       0
  5195.1   0.035       0
Bank Sta=4991.9,5001
Exp/Cntr=0.3,0.1

Type RM Length L Ch R = 1,18723,453,453,453
BEGIN DESCRIPTION:
NC Unknown Stream 07 20.0
END DESCRIPTION:
XS GIS Cut Line= 3
      1478878.02      6936327.15      1478305.00      6935938.00
      1478005.00      6935838.00
#Sta/Elev= 30
  4307.6 1796.11  4359.6 1795.49  4367.0 1795.73  4388.0 1795.02  4417.9 1794.93
  4480.9 1793.70  4813.1 1785.55  4927.8 1784.67  4956.9 1785.63  4971.8 1784.67
  4986.8 1784.88  4992.6 1784.11  4993.1 1783.61  5001.3 1783.61  5001.8 1784.11
  5010.8 1784.84  5021.3 1784.40  5031.9 1784.54  5042.4 1785.32  5053.0 1786.75
  5074.1 1787.82  5084.6 1789.47  5095.1 1789.68  5116.2 1792.09  5142.8 1793.28
  5168.9 1793.69  5200.5 1796.06  5284.9 1799.96  5295.4 1800.17  5316.5 1801.51
#Mann=5,-1,0
  4307.6   0.045       0  4927.8    0.07       0  4992.6    0.07       0
  5001.8    0.07       0  5142.8   0.035       0
Bank Sta=4992.6,5001.8
Exp/Cntr=0.3,0.1

Type RM Length L Ch R = 1,18270,471,471,471
BEGIN DESCRIPTION:
NC Unknown Stream 07 19.0
END DESCRIPTION:
XS GIS Cut Line= 3
      1478856.32      6935914.83      1478355.00      6935538.00
      1478105.01      6935638.00
#Sta/Elev= 30
  4372.9 1792.16  4492.9 1790.67  4557.5 1789.06  4649.8 1785.53  4778.2 1783.01
  4863.6 1783.27  4886.5 1782.12  4900.0 1782.29  4942.8 1781.13  4957.4 1781.79
  4963.6 1781.33  4986.5 1781.59  5034.5 1780.80  5035.0 1780.30  5043.2 1780.30
  5043.7 1780.80  5053.9 1781.45  5083.0 1782.76  5092.9 1783.32  5107.8 1785.08
  5117.2 1785.13  5140.1 1787.16  5146.8 1788.34  5171.0 1790.00  5183.1 1791.65
  5200.6 1792.64  5206.0 1793.83  5215.5 1793.93  5247.8 1796.44  5269.3 1796.99
#Mann=5,-1,0
  4372.9   0.045       0  5034.5   0.045       0  5043.7   0.045       0
  5053.9    0.07       0  5083.0   0.035       0
Bank Sta=5034.5,5043.7
Exp/Cntr=0.3,0.1

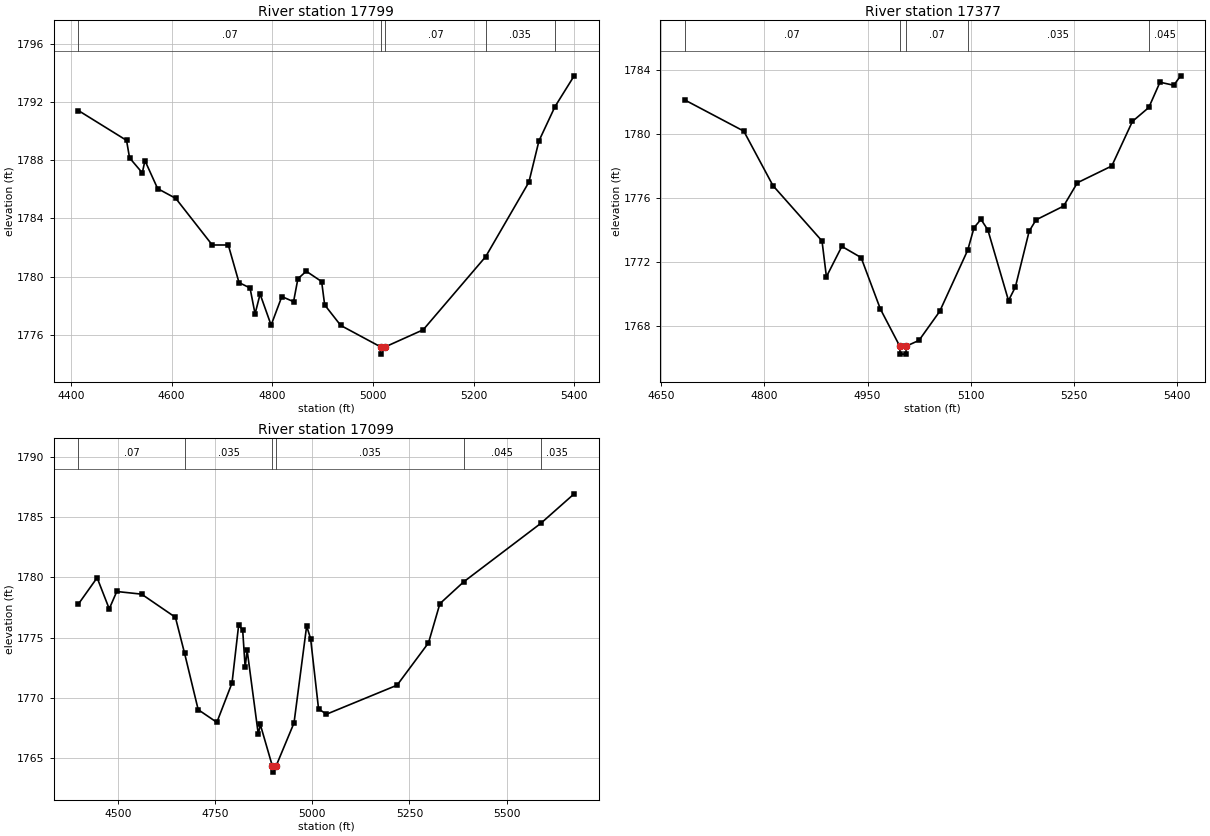
Type RM Length L Ch R = 1,17799,422,422,422
BEGIN DESCRIPTION:
NC Unknown Stream 07 18.0
END DESCRIPTION:
XS GIS Cut Line= 3
      1478905.03      6935338.01      1478355.00      6935138.00
      1477954.97      6935138.00
#Sta/Elev= 30
  4414.7 1791.41  4510.5 1789.36  4516.5 1788.16  4541.8 1787.13  4547.1 1787.97
  4572.3 1786.05  4608.3 1785.38  4680.8 1782.18  4712.7 1782.18  4734.0 1779.60
  4755.9 1779.23  4765.9 1777.45  4775.9 1778.81  4797.8 1776.68  4819.1 1778.64
  4842.4 1778.29  4851.0 1779.86  4867.6 1780.38  4898.2 1779.67  4904.2 1778.07
  4936.1 1776.66  5015.3 1775.19  5015.8 1774.69  5024.7 1775.19  5100.0 1776.36
  5224.2 1781.38  5310.0 1786.49  5330.0 1789.32  5361.8 1791.67  5400.0 1793.79
#Mann=5,-1,0
  4414.7    0.07       0  5015.3    0.07       0  5024.7    0.07       0
  5224.2   0.035       0  5361.8   0.045       0
Bank Sta=5015.3,5024.7
Exp/Cntr=0.3,0.1

Type RM Length L Ch R = 1,17377,278,278,278
BEGIN DESCRIPTION:
NC Unknown Stream 07 17.0
END DESCRIPTION:
XS GIS Cut Line= 3
      1478755.01      6935038.01      1478555.00      6934788.00
      1478154.97      6934788.00
#Sta/Elev= 30
  4684.5 1782.15  4770.2 1780.20  4812.6 1776.79  4883.8 1773.33  4890.2 1771.09
  4912.6 1772.99  4940.6 1772.29  4968.6 1769.07  4996.7 1766.75  4997.2 1766.25
  5005.7 1766.25  5006.2 1766.75  5024.7 1767.11  5054.7 1768.92  5095.4 1772.75
  5104.7 1774.17  5114.7 1774.68  5124.7 1774.02  5154.7 1769.60  5164.7 1770.45
  5184.7 1773.94  5194.7 1774.65  5234.7 1775.51  5254.7 1776.97  5304.7 1778.02
  5334.7 1780.81  5358.5 1781.68  5374.7 1783.26  5394.7 1783.07  5404.7 1783.66
#Mann=5,-1,0
  4684.5    0.07       0  4996.7    0.07       0  5006.2    0.07       0
  5095.4   0.035       0  5358.5   0.045       0
Bank Sta=4996.7,5006.2
Exp/Cntr=0.3,0.1

Type RM Length L Ch R = 1,17099,0,0,0
BEGIN DESCRIPTION:
NC Unknown Stream 07 16.0
END DESCRIPTION:
XS GIS Cut Line= 4
      1479151.48      6934761.20      1478677.53      6934625.78
      1478547.32      6934599.74      1477904.05      6934690.89
#Sta/Elev= 30
  4398.3 1777.78  4446.6 1779.97  4477.8 1777.39  4497.2 1778.83  4561.0 1778.61
  4648.0 1776.69  4671.7 1773.69  4706.6 1769.03  4754.6 1767.98  4793.6 1771.24
  4810.6 1776.02  4821.0 1775.65  4827.4 1772.56  4832.6 1773.94  4861.2 1766.99
  4866.4 1767.80  4897.4 1764.35  4897.9 1763.85  4906.9 1764.35  4953.1 1767.93
  4985.6 1775.97  4995.8 1774.91  5016.2 1769.10  5036.4 1768.65  5218.2 1771.06
  5299.0 1774.57  5328.3 1777.82  5389.5 1779.63  5587.5 1784.47  5673.7 1786.93
#Mann=6,-1,0
  4398.3    0.07       0  4671.7   0.035       0  4897.4   0.035       0
  4906.9   0.035       0  5389.5   0.045       0  5587.5   0.035       0
Bank Sta=4897.4,4906.9
Exp/Cntr=0.3,0.1

Chan Stop Cuts=-1