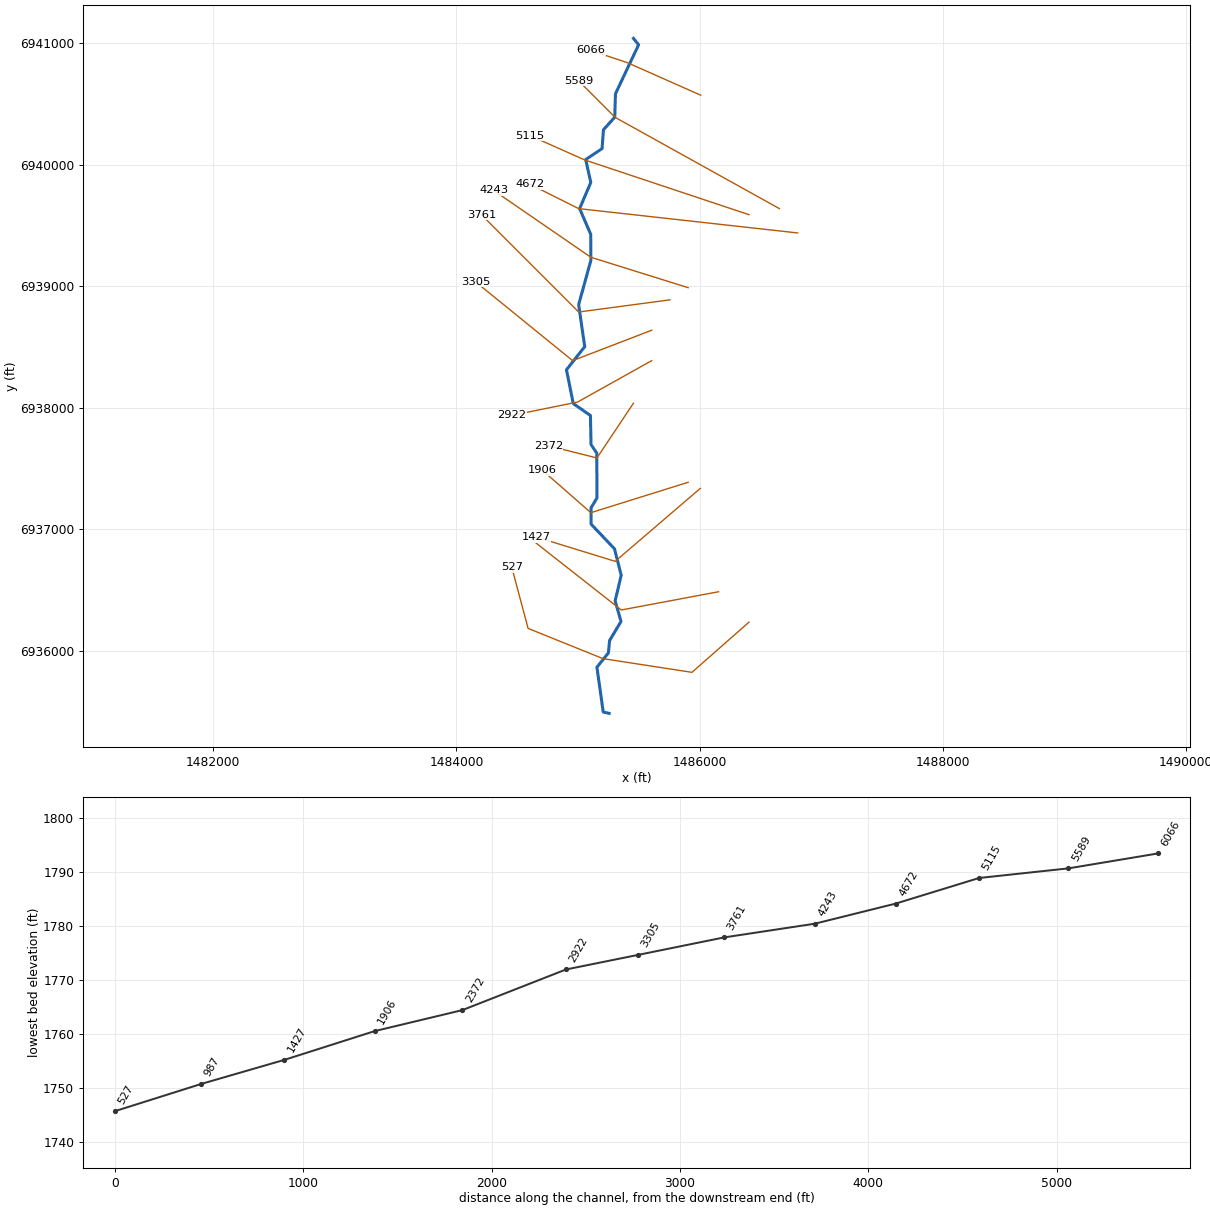
--- NC Unknown Stream 09.prj (project) ---

Proj Title=NC Unknown Stream 09 Base Level Engineering
Current Plan=p01
Default Exp/Contr=0.3,0.1
English Units
Geom File=g01
Flow File=f01
Plan File=p01
BEGIN DESCRIPTION:
NC Unknown Stream 09
END DESCRIPTION:

--- NC Unknown Stream 09.p01 (plan) ---

Plan Title=Multiple Run
Short Identifier=Multiple
Geom File=g01
Flow File=f01
Subcritical Flow
K Sum by GR= 0
Std Step Tol= 0.01
Critical Tol= 0.01
Num of Std Step Trials= 20
Max Error Tol= 0.3
Flow Tol Ratio= 0.001
Split Flow NTrial= 30
Split Flow Tol= 0.02
Split Flow Ratio= 0.02
Log Output Level= 0
Friction Slope Method= 1
Unsteady Friction Slope Method= 2
Unsteady Bridges Friction Slope Method= 1
Parabolic Critical Depth
Global Vel Dist=  1 , 1 , 1
Global Log Level= 0
CheckData=True
Encroach Param= -1, 0, 0, 0
BEGIN DESCRIPTION:
Multiple Run
END DESCRIPTION:

--- NC Unknown Stream 09.f01 (steady flow) ---

Flow Title=Multiple
Number of Profiles=7
Profile Names=10-year,25-year,50-year,1pct_min,100-year,1pct_plu,500-year
River Rch & RM= NC Unknown Strea,Reach-1,6066
     311     440     549     341     680    1356    1054
River Rch & RM= NC Unknown Strea,Reach-1,4672
     402     577     725     453     905    1805    1425
Boundary for River Rch & Prof#=NC Unknown Strea,Reach-1,1
Up Type=0
Dn Type=3
Dn Slope=0.001
Boundary for River Rch & Prof#=NC Unknown Strea,Reach-1,2
Up Type=0
Dn Type=3
Dn Slope=0.001
Boundary for River Rch & Prof#=NC Unknown Strea,Reach-1,3
Up Type=0
Dn Type=3
Dn Slope=0.001
Boundary for River Rch & Prof#=NC Unknown Strea,Reach-1,4
Up Type=0
Dn Type=3
Dn Slope=0.001
Boundary for River Rch & Prof#=NC Unknown Strea,Reach-1,5
Up Type=0
Dn Type=3
Dn Slope=0.001
Boundary for River Rch & Prof#=NC Unknown Strea,Reach-1,6
Up Type=0
Dn Type=3
Dn Slope=0.001
Boundary for River Rch & Prof#=NC Unknown Strea,Reach-1,7
Up Type=0
Dn Type=3
Dn Slope=0.001

--- NC Unknown Stream 09.g01 (geometry) ---

Geom Title=Existing Conditions

River Reach=NC Unknown Strea,Reach-1
Reach XY= 30
      1485455.00      6941038.00      1485497.42      6940984.80
      1485307.24      6940582.07      1485301.45      6940389.47
      1485208.56      6940286.53      1485197.30      6940131.53
      1485062.69      6940041.67      1485104.49      6939853.22
      1485012.56      6939638.00      1485103.78      6939427.50
      1485105.20      6939212.92      1485004.50      6938848.17
      1485054.62      6938503.16      1484904.50      6938313.04
      1484960.36      6938035.30      1485101.55      6937936.75
      1485106.22      6937698.50      1485153.78      6937627.50
      1485154.93      6937258.03      1485106.21      6937177.49
      1485107.05      6937043.86      1485299.53      6936840.45
      1485354.49      6936622.78      1485304.60      6936413.00
      1485352.86      6936243.97      1485258.83      6936086.41
      1485249.46      6935985.58      1485154.96      6935868.01
      1485206.45      6935499.44      1485255.00      6935488.00

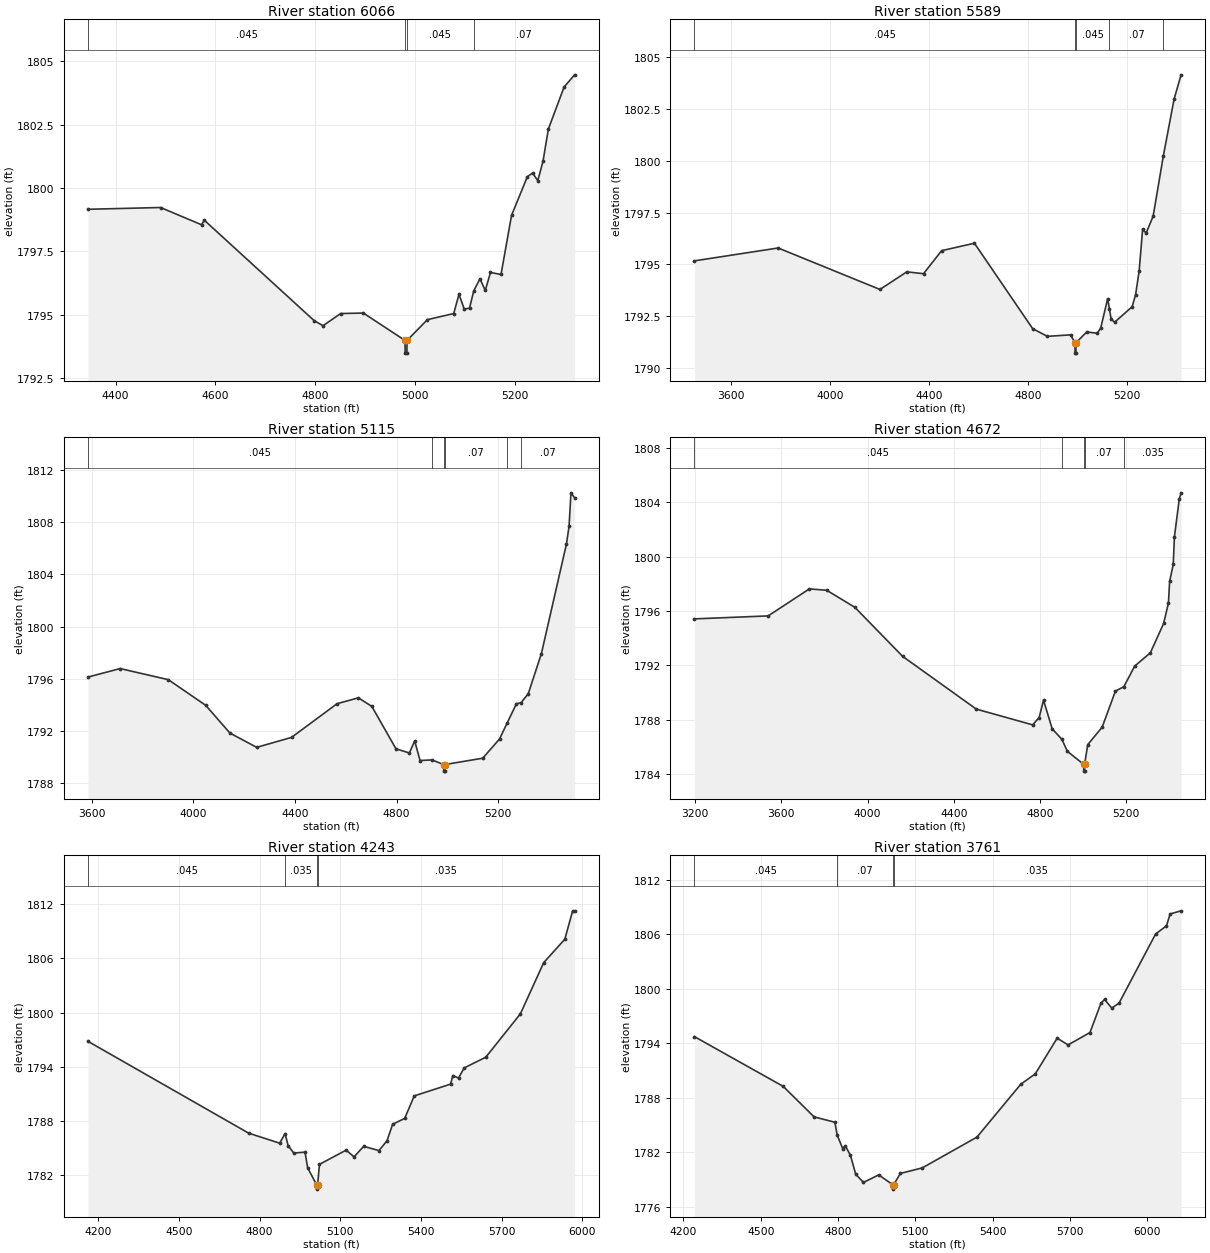
Type RM Length L Ch R = 1,6066,477,477,477
BEGIN DESCRIPTION:
NC Unknown Stream 09 13.0
END DESCRIPTION:
XS GIS Cut Line= 3
      1486008.02      6940570.61      1485405.00      6940838.00
      1485104.98      6940938.01
#Sta/Elev= 30
  4344.5 1799.16  4490.0 1799.23  4572.2 1798.55  4577.7 1798.73  4798.1 1794.77
  4815.9 1794.57  4851.0 1795.05  4896.7 1795.07  4980.3 1793.99  4980.5 1793.49
  4984.0 1793.49  4984.3 1793.99  5025.2 1794.81  5077.9 1795.05  5088.5 1795.81
  5099.0 1795.23  5109.6 1795.26  5118.2 1795.95  5130.6 1796.42  5141.2 1795.96
  5151.7 1796.67  5172.8 1796.59  5193.9 1798.92  5225.5 1800.44  5236.0 1800.59
  5246.6 1800.29  5257.1 1801.06  5267.7 1802.32  5299.3 1803.98  5320.4 1804.46
#Mann=4,-1,0
  4344.5   0.045       0  4980.3   0.045       0  4984.3   0.045       0
  5118.2    0.07       0
Bank Sta=4980.3,4984.3
Exp/Cntr=0.3,0.1

Type RM Length L Ch R = 1,5589,474,474,474
BEGIN DESCRIPTION:
NC Unknown Stream 09 12.0
END DESCRIPTION:
XS GIS Cut Line= 3
      1486654.98      6939638.01      1485305.00      6940388.00
      1485004.99      6940688.01
#Sta/Elev= 30
  3451.4 1795.17  3790.0 1795.79  4201.8 1793.79  4310.5 1794.64  4378.0 1794.55
  4451.2 1795.66  4583.9 1796.02  4819.6 1791.90  4879.0 1791.53  4972.8 1791.60
  4990.9 1791.22  4991.1 1790.72  4994.6 1790.72  4994.9 1791.22  5038.2 1791.74
  5080.6 1791.68  5094.7 1791.92  5123.0 1793.35  5130.0 1792.86  5137.1 1792.36
  5151.3 1792.21  5222.0 1792.96  5236.1 1793.54  5250.3 1794.68  5264.4 1796.69
  5278.6 1796.51  5306.9 1797.32  5348.4 1800.24  5391.7 1802.97  5420.0 1804.14
#Mann=5,-1,0
  3451.4   0.045       0  4990.9   0.045       0  4994.9   0.045       0
  5130.0    0.07       0  5348.4   0.035       0
Bank Sta=4990.9,4994.9
Exp/Cntr=0.3,0.1

Type RM Length L Ch R = 1,5115,443,443,443
BEGIN DESCRIPTION:
NC Unknown Stream 09 11.0
END DESCRIPTION:
XS GIS Cut Line= 3
      1486405.01      6939588.00      1485055.00      6940038.00
      1484604.98      6940238.01
#Sta/Elev= 30
  3585.1 1796.14  3711.6 1796.79  3901.3 1795.94  4048.9 1793.97  4143.8 1791.85
  4249.2 1790.76  4386.2 1791.52  4565.4 1794.10  4649.7 1794.55  4702.5 1793.89
  4797.3 1790.65  4850.0 1790.33  4871.1 1791.25  4892.2 1789.75  4939.4 1789.80
  4985.1 1789.44  4985.3 1788.94  4988.8 1788.94  4989.1 1789.44  5138.8 1789.93
  5205.1 1791.40  5235.4 1792.64  5271.5 1794.09  5289.8 1794.18  5318.0 1794.86
  5369.9 1797.94  5468.4 1806.32  5478.7 1807.67  5486.2 1810.24  5500.6 1809.86
#Mann=6,-1,0
  3585.1   0.045       0  4939.4    0.07       0  4985.1    0.07       0
  4989.1    0.07       0  5235.4   0.035       0  5289.8    0.07       0
Bank Sta=4985.1,4989.1
Exp/Cntr=0.3,0.1

Type RM Length L Ch R = 1,4672,429,429,429
BEGIN DESCRIPTION:
NC Unknown Stream 09 10.0
END DESCRIPTION:
XS GIS Cut Line= 3
      1486804.96      6939438.00      1485005.00      6939638.00
      1484604.96      6939838.02
#Sta/Elev= 30
  3196.7 1795.42  3538.8 1795.64  3729.9 1797.63  3810.4 1797.53  3941.2 1796.27
  4162.6 1792.66  4504.7 1788.77  4766.3 1787.61  4796.4 1788.15  4816.6 1789.43
  4856.8 1787.32  4902.0 1786.54  4927.2 1785.66  5003.1 1784.70  5003.4 1784.20
  5007.0 1784.20  5007.3 1784.70  5021.7 1786.15  5088.8 1787.44  5150.3 1790.10
  5189.3 1790.42  5239.7 1791.94  5312.4 1792.92  5373.9 1795.08  5396.3 1796.58
  5401.8 1798.18  5418.6 1799.43  5424.2 1801.48  5446.6 1804.25  5455.0 1804.71
#Mann=5,-1,0
  3196.7   0.045       0  4902.0    0.07       0  5003.1    0.07       0
  5007.3    0.07       0  5189.3   0.035       0
Bank Sta=5003.1,5007.3
Exp/Cntr=0.3,0.1

Type RM Length L Ch R = 1,4243,482,482,482
BEGIN DESCRIPTION:
NC Unknown Stream 09 9.0
END DESCRIPTION:
XS GIS Cut Line= 3
      1485904.95      6938988.01      1485105.00      6939238.00
      1484305.02      6939787.98
#Sta/Elev= 30
  4162.3 1796.82  4759.4 1786.67  4874.7 1785.56  4895.0 1786.62  4906.1 1785.30
  4927.1 1784.47  4969.0 1784.57  4978.9 1782.83  5011.8 1780.98  5012.1 1780.48
  5016.0 1780.98  5022.7 1783.22  5121.8 1784.79  5151.3 1784.05  5187.1 1785.21
  5243.9 1784.74  5273.7 1785.82  5294.7 1787.65  5339.4 1788.30  5375.2 1790.79
  5510.1 1792.09  5518.6 1793.04  5539.6 1792.76  5560.6 1793.88  5641.1 1795.07
  5769.6 1799.86  5856.2 1805.52  5934.8 1808.11  5963.8 1811.25  5971.2 1811.18
#Mann=4,-1,0
  4162.3   0.045       0  4895.0   0.035       0  5011.8   0.035       0
  5016.0   0.035       0
Bank Sta=5011.8,5016
Exp/Cntr=0.3,0.1

Type RM Length L Ch R = 1,3761,456,456,456
BEGIN DESCRIPTION:
NC Unknown Stream 09 8.0
END DESCRIPTION:
XS GIS Cut Line= 3
      1485755.00      6938888.00      1485005.00      6938788.00
      1484205.00      6939588.00
#Sta/Elev= 30
  4242.7 1794.74  4587.0 1789.26  4706.8 1785.90  4787.5 1785.31  4796.2 1783.92
  4817.7 1782.41  4827.8 1782.72  4848.0 1781.66  4868.2 1779.59  4898.4 1778.68
  4957.7 1779.51  5011.3 1778.44  5011.6 1777.94  5015.6 1778.44  5041.8 1779.67
  5126.6 1780.28  5338.7 1783.67  5508.5 1789.49  5565.0 1790.64  5649.9 1794.57
  5692.3 1793.83  5777.2 1795.19  5819.6 1798.41  5833.7 1798.84  5862.0 1797.88
  5890.3 1798.45  6031.7 1806.04  6074.1 1806.95  6088.3 1808.26  6130.7 1808.60
#Mann=4,-1,0
  4242.7   0.045       0  4796.2    0.07       0  5011.3    0.07       0
  5015.6   0.035       0
Bank Sta=5011.3,5015.6
Exp/Cntr=0.3,0.1

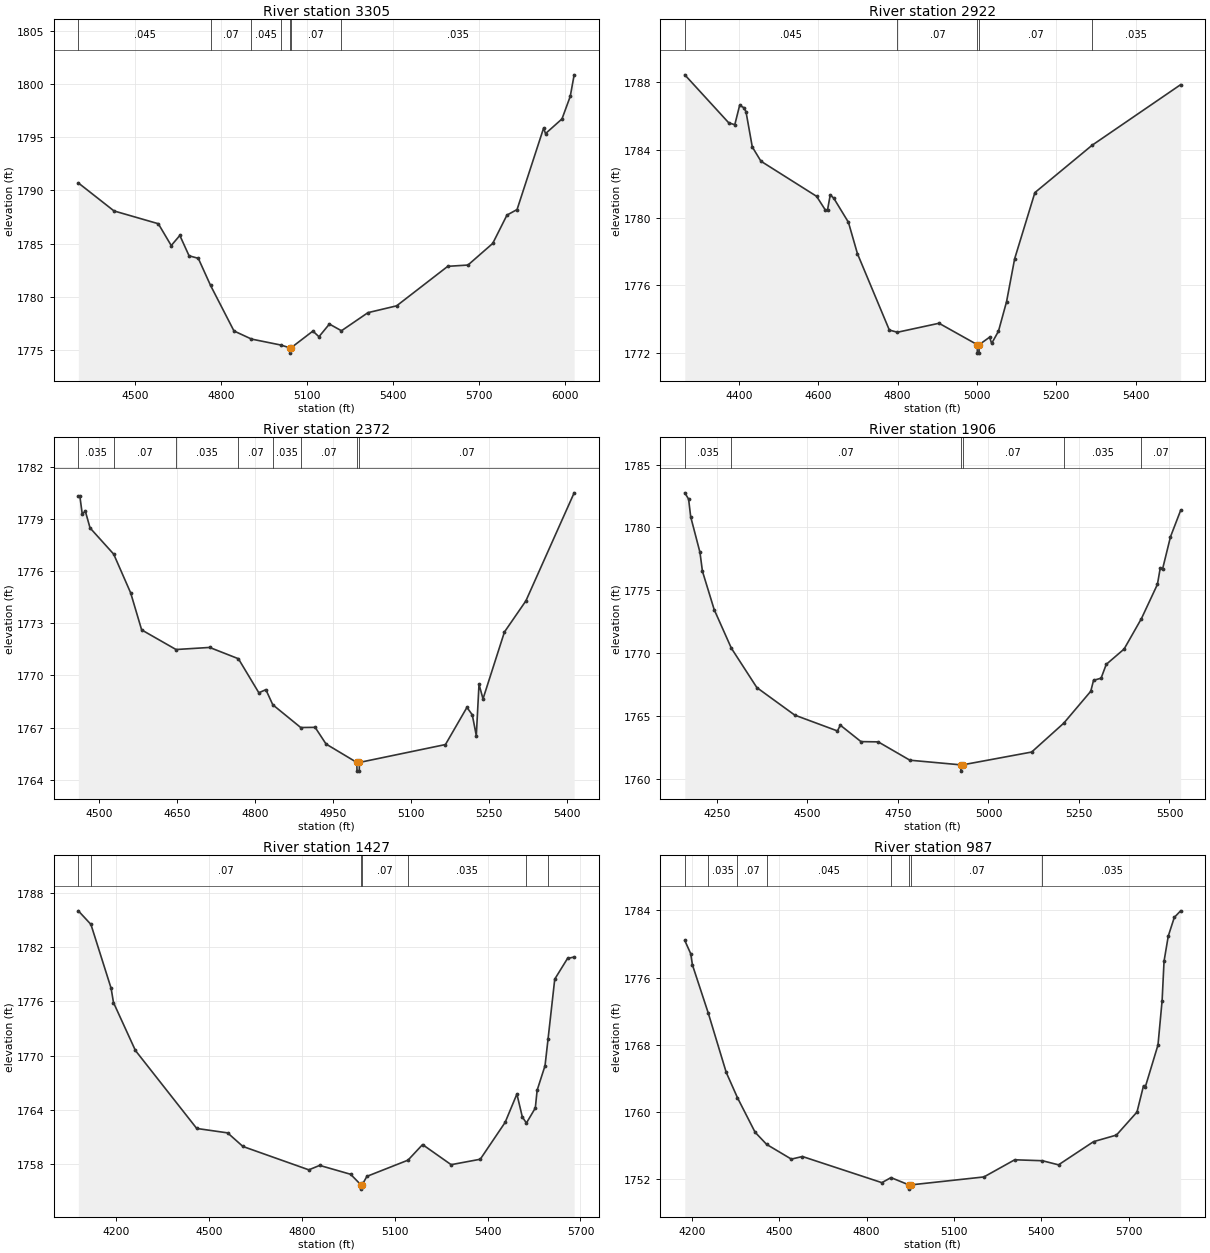
Type RM Length L Ch R = 1,3305,383,383,383
BEGIN DESCRIPTION:
NC Unknown Stream 09 7.0
END DESCRIPTION:
XS GIS Cut Line= 3
      1485605.02      6938638.01      1484955.00      6938388.00
      1484155.02      6939037.99
#Sta/Elev= 30
  4303.3 1790.69  4427.6 1788.06  4581.9 1786.86  4626.9 1784.81  4656.9 1785.76
  4689.0 1783.85  4721.2 1783.61  4764.0 1781.06  4845.5 1776.79  4906.5 1776.03
  5008.7 1775.47  5039.9 1775.21  5040.2 1774.71  5044.3 1775.21  5120.4 1776.78
  5141.5 1776.25  5177.9 1777.44  5219.9 1776.81  5312.2 1778.51  5412.1 1779.15
  5590.2 1782.86  5660.6 1782.98  5746.8 1785.01  5796.4 1787.67  5831.6 1788.19
  5924.2 1795.85  5930.7 1795.32  5988.1 1796.70  6016.9 1798.82  6030.5 1800.84
#Mann=7,-1,0
  4303.3   0.045       0  4764.0    0.07       0  4906.5   0.045       0
  5008.7    0.07       0  5039.9   0.045       0  5044.3    0.07       0
  5219.9   0.035       0
Bank Sta=5039.9,5044.3
Exp/Cntr=0.3,0.1

Type RM Length L Ch R = 1,2922,550,550,550
BEGIN DESCRIPTION:
NC Unknown Stream 09 6.0
END DESCRIPTION:
XS GIS Cut Line= 3
      1485604.99      6938387.99      1484996.10      6938047.66
      1484455.04      6937938.01
#Sta/Elev= 30
  4263.8 1788.41  4374.6 1785.58  4389.8 1785.47  4402.0 1786.61  4412.2 1786.48
  4418.0 1786.24  4433.9 1784.16  4455.7 1783.32  4596.0 1781.25  4617.8 1780.45
  4623.6 1780.46  4630.4 1781.34  4639.5 1781.13  4676.2 1779.72  4698.9 1777.87
  4779.3 1773.37  4799.6 1773.24  4904.5 1773.77  5000.8 1772.51  5001.2 1772.01
  5005.4 1772.01  5005.8 1772.51  5032.0 1772.95  5037.1 1772.58  5054.3 1773.30
  5074.7 1775.04  5095.1 1777.57  5146.1 1781.47  5290.3 1784.26  5513.4 1787.83
#Mann=5,-1,0
  4263.8   0.045       0  4799.6    0.07       0  5000.8    0.07       0
  5005.8    0.07       0  5290.3   0.035       0
Bank Sta=5000.8,5005.8
Exp/Cntr=0.3,0.1

Type RM Length L Ch R = 1,2372,466,466,466
BEGIN DESCRIPTION:
NC Unknown Stream 09 5.0
END DESCRIPTION:
XS GIS Cut Line= 3
      1485454.99      6938037.98      1485155.00      6937588.00
      1484755.02      6937688.00
#Sta/Elev= 30
  4459.9 1780.30  4462.9 1780.30  4467.4 1779.30  4473.4 1779.45  4482.4 1778.49
  4527.9 1776.98  4560.5 1774.75  4581.6 1772.62  4647.7 1771.49  4712.3 1771.61
  4767.6 1770.96  4806.9 1769.00  4820.4 1769.18  4833.7 1768.31  4887.4 1767.00
  4915.1 1767.01  4936.1 1766.05  4995.2 1764.99  4995.6 1764.49  4999.9 1764.49
  5000.2 1764.99  5165.6 1766.02  5206.9 1768.16  5217.2 1767.73  5224.9 1766.53
  5230.1 1769.49  5237.8 1768.65  5279.0 1772.50  5320.2 1774.29  5413.0 1780.51
#Mann=8,-1,0
  4459.9   0.035       0  4527.9    0.07       0  4647.7   0.035       0
  4767.6    0.07       0  4833.7   0.035       0  4887.4    0.07       0
  4995.2    0.07       0  5000.2    0.07       0
Bank Sta=4995.2,5000.2
Exp/Cntr=0.3,0.1

Type RM Length L Ch R = 1,1906,479,479,479
BEGIN DESCRIPTION:
NC Unknown Stream 09 4.0
END DESCRIPTION:
XS GIS Cut Line= 3
      1485905.01      6937388.00      1485105.00      6937138.00
      1484704.98      6937488.02
#Sta/Elev= 30
  4161.2 1782.76  4171.7 1782.26  4177.5 1780.85  4203.1 1778.02  4209.9 1776.52
  4242.4 1773.46  4289.8 1770.39  4360.3 1767.25  4465.0 1765.06  4582.9 1763.80
  4590.8 1764.26  4647.9 1762.95  4695.5 1762.93  4783.0 1761.47  4923.5 1761.10
  4923.9 1760.60  4928.6 1761.10  5119.4 1762.12  5208.1 1764.42  5282.7 1766.96
  5290.3 1767.83  5311.2 1768.00  5325.4 1769.10  5374.7 1770.32  5422.7 1772.75
  5466.8 1775.47  5474.4 1776.74  5481.0 1776.69  5502.9 1779.26  5530.9 1781.36
#Mann=6,-1,0
  4161.2   0.035       0  4289.8    0.07       0  4923.5    0.07       0
  4928.6    0.07       0  5208.1   0.035       0  5422.7    0.07       0
Bank Sta=4923.5,4928.6
Exp/Cntr=0.3,0.1

Type RM Length L Ch R = 1,1427,440,440,440
BEGIN DESCRIPTION:
NC Unknown Stream 09 3.0
END DESCRIPTION:
XS GIS Cut Line= 3
      1486005.00      6937338.00      1485305.00      6936738.00
      1484655.03      6936937.99
#Sta/Elev= 30
  4077.7 1786.01  4118.4 1784.51  4183.6 1777.46  4191.3 1775.88  4262.1 1770.59
  4460.2 1761.98  4560.1 1761.49  4609.5 1759.99  4822.4 1757.41  4857.5 1757.90
  4957.4 1756.92  4990.0 1755.78  4990.4 1755.28  4995.1 1755.78  5010.1 1756.69
  5142.9 1758.48  5189.9 1760.20  5282.2 1757.98  5376.3 1758.58  5456.7 1762.65
  5494.7 1765.78  5512.3 1763.24  5525.5 1762.58  5554.2 1764.24  5560.1 1766.20
  5585.6 1768.91  5595.4 1771.87  5617.0 1778.47  5658.2 1780.75  5679.7 1780.91
#Mann=7,-1,0
  4077.7   0.045       0  4118.4    0.07       0  4990.0    0.07       0
  4995.1    0.07       0  5142.9   0.035       0  5525.5    0.07       0
  5595.4   0.035       0
Bank Sta=4990,4995.1
Exp/Cntr=0.3,0.1

Type RM Length L Ch R = 1,987,460,460,460
BEGIN DESCRIPTION:
NC Unknown Stream 09 2.0
END DESCRIPTION:
XS GIS Cut Line= 3
      1486155.00      6936488.00      1485355.00      6936338.00
      1484654.97      6936888.02
#Sta/Elev= 30
  4174.9 1780.42  4195.2 1778.85  4201.2 1777.51  4255.8 1771.76  4317.3 1764.73
  4356.0 1761.71  4416.5 1757.61  4456.3 1756.16  4541.2 1754.41  4579.3 1754.72
  4852.3 1751.61  4883.5 1752.21  4945.5 1751.34  4945.9 1750.84  4950.7 1751.34
  5203.0 1752.29  5308.8 1754.33  5403.9 1754.22  5459.4 1753.73  5579.9 1756.49
  5658.5 1757.27  5729.1 1760.01  5751.6 1763.15  5758.0 1763.03  5801.3 1767.99
  5815.5 1773.28  5822.1 1777.95  5836.6 1780.94  5857.4 1783.17  5879.1 1783.95
#Mann=8,-1,0
  4174.9    0.07       0  4255.8   0.035       0  4356.0    0.07       0
  4456.3   0.045       0  4883.5    0.07       0  4945.5    0.07       0
  4950.7    0.07       0  5403.9   0.035       0
Bank Sta=4945.5,4950.7
Exp/Cntr=0.3,0.1

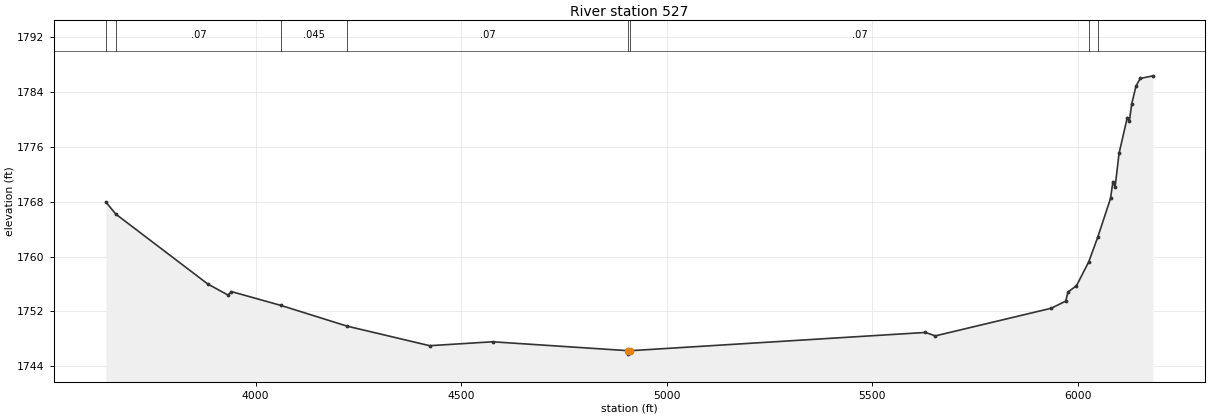
Type RM Length L Ch R = 1,527,0,0,0
BEGIN DESCRIPTION:
NC Unknown Stream 09 1.0
END DESCRIPTION:
XS GIS Cut Line= 5
      1486404.99      6936237.99      1485936.21      6935825.44
      1485205.00      6935938.00      1484588.99      6936186.55
      1484455.00      6936688.00
#Sta/Elev= 30
  3635.7 1767.94  3659.8 1766.19  3883.8 1755.99  3933.1 1754.38  3940.7 1754.90
  4061.5 1752.88  4222.5 1749.86  4423.3 1747.01  4576.4 1747.58  4906.3 1746.28
  4906.7 1745.78  4911.5 1746.28  5629.4 1748.94  5653.6 1748.44  5935.8 1752.47
  5970.7 1753.50  5976.3 1754.83  5997.0 1755.75  6026.9 1759.24  6048.6 1762.80
  6079.8 1768.47  6085.7 1770.93  6090.9 1770.10  6100.5 1775.02  6120.6 1780.26
  6125.8 1779.78  6131.5 1782.28  6141.9 1784.87  6152.2 1785.96  6183.3 1786.34
#Mann=8,-1,0
  3635.7   0.045       0  3659.8    0.07       0  4061.5   0.045       0
  4222.5    0.07       0  4906.3    0.07       0  4911.5    0.07       0
  6026.9   0.035       0  6048.6    0.07       0
Bank Sta=4906.3,4911.5
Exp/Cntr=0.3,0.1

Chan Stop Cuts=-1