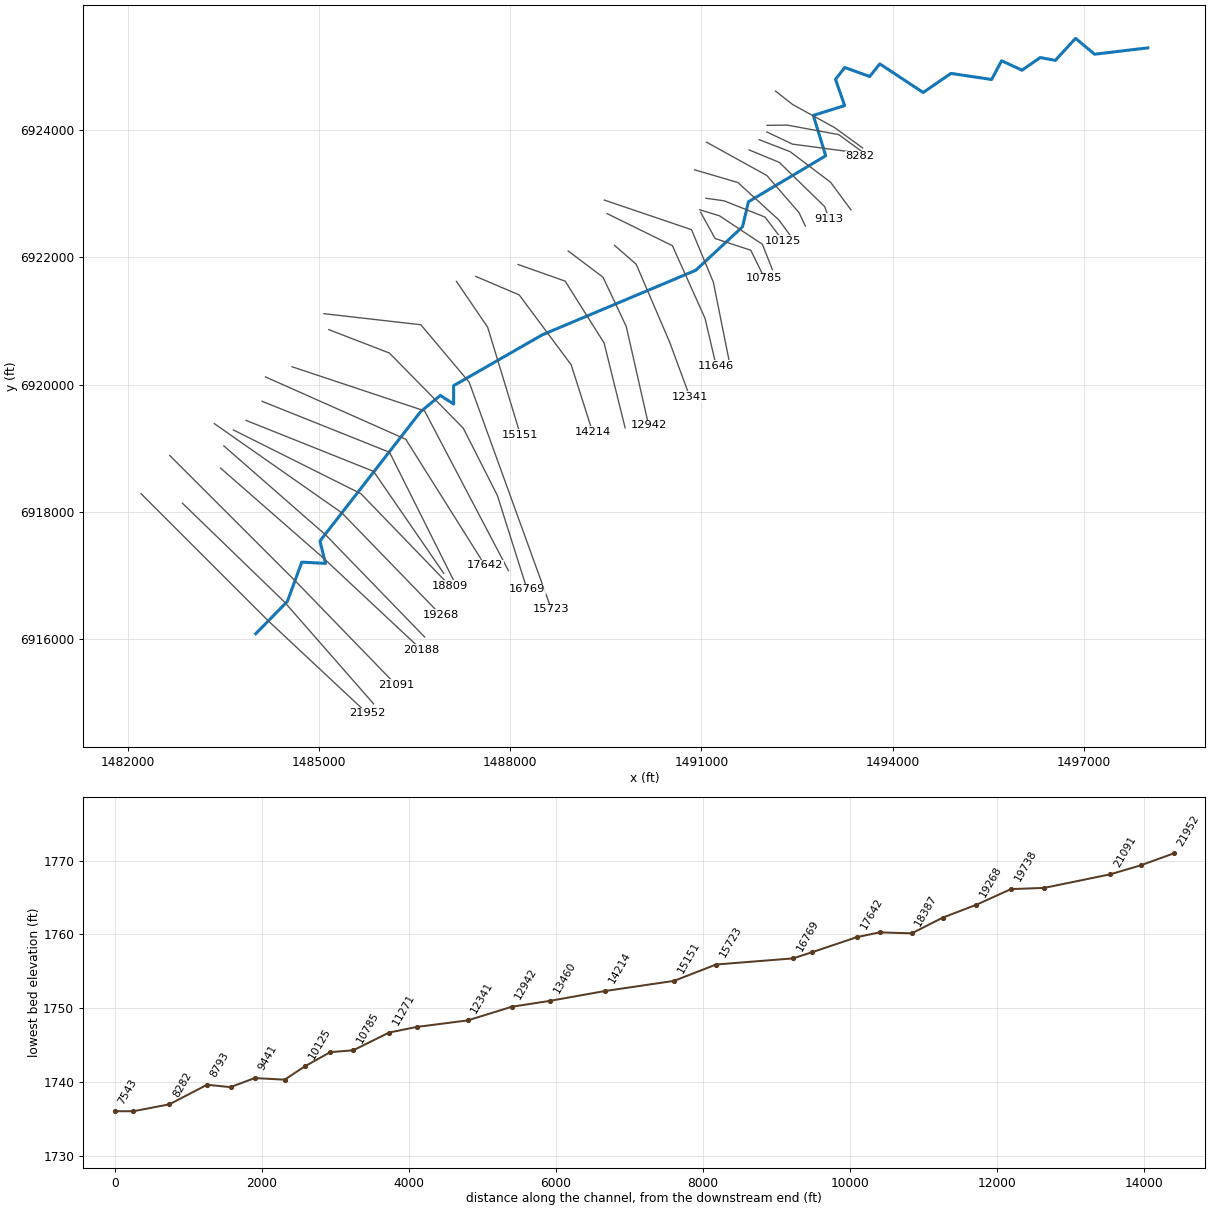
--- NC Unknown Stream 12.prj (project) ---

Proj Title=NC Unknown Stream 12 Base Level Engineering
Current Plan=p01
Default Exp/Contr=0.3,0.1
English Units
Geom File=g01
Flow File=f01
Plan File=p01
BEGIN DESCRIPTION:
NC Unknown Stream 12
END DESCRIPTION:

--- NC Unknown Stream 12.p01 (plan) ---

Plan Title=Multiple Run
Short Identifier=Multiple
Geom File=g01
Flow File=f01
Subcritical Flow
K Sum by GR= 0
Std Step Tol= 0.01
Critical Tol= 0.01
Num of Std Step Trials= 20
Max Error Tol= 0.3
Flow Tol Ratio= 0.001
Split Flow NTrial= 30
Split Flow Tol= 0.02
Split Flow Ratio= 0.02
Log Output Level= 0
Friction Slope Method= 1
Unsteady Friction Slope Method= 2
Unsteady Bridges Friction Slope Method= 1
Parabolic Critical Depth
Global Vel Dist=  1 , 1 , 1
Global Log Level= 0
CheckData=True
Encroach Param= -1, 0, 0, 0
BEGIN DESCRIPTION:
Multiple Run
END DESCRIPTION:

--- NC Unknown Stream 12.f01 (steady flow) ---

Flow Title=Multiple
Number of Profiles=7
Profile Names=10-year,25-year,50-year,1pct_min,100-year,1pct_plu,500-year
River Rch & RM= NC Unknown Strea,Reach-1,21952
     316     437     536     327     651    1300     973
River Rch & RM= NC Unknown Strea,Reach-1,13460
     419     587     727     446     890    1775    1351
River Rch & RM= NC Unknown Strea,Reach-1,11646
     510     717     889     546    1090    2174    1656
Boundary for River Rch & Prof#=NC Unknown Strea,Reach-1,1
Up Type=0
Dn Type=3
Dn Slope=0.001
Boundary for River Rch & Prof#=NC Unknown Strea,Reach-1,2
Up Type=0
Dn Type=3
Dn Slope=0.001
Boundary for River Rch & Prof#=NC Unknown Strea,Reach-1,3
Up Type=0
Dn Type=3
Dn Slope=0.001
Boundary for River Rch & Prof#=NC Unknown Strea,Reach-1,4
Up Type=0
Dn Type=3
Dn Slope=0.001
Boundary for River Rch & Prof#=NC Unknown Strea,Reach-1,5
Up Type=0
Dn Type=3
Dn Slope=0.001
Boundary for River Rch & Prof#=NC Unknown Strea,Reach-1,6
Up Type=0
Dn Type=3
Dn Slope=0.001
Boundary for River Rch & Prof#=NC Unknown Strea,Reach-1,7
Up Type=0
Dn Type=3
Dn Slope=0.001

--- NC Unknown Stream 12.g01 (geometry) ---

Geom Title=Existing Conditions

River Reach=NC Unknown Strea,Reach-1
Reach XY= 30
      1484005.00      6916088.00      1484501.89      6916596.32
      1484727.91      6917212.55      1485100.44      6917193.18
      1485012.86      6917544.17      1486591.67      6919574.61
      1486901.86      6919830.50      1487111.56      6919695.69
      1487110.16      6919983.40      1488502.70      6920782.17
      1490911.05      6921796.16      1491644.52      6922478.20
      1491737.78      6922871.74      1492949.83      6923593.41
      1492755.87      6924227.69      1493247.24      6924381.79
      1493104.13      6924793.04      1493248.81      6924980.19
      1493640.05      6924838.24      1493798.94      6925036.41
      1494479.94      6924587.38      1494915.51      6924886.79
      1495554.01      6924791.54      1495710.86      6925085.95
      1496030.00      6924937.41      1496316.95      6925136.09
      1496553.28      6925091.34      1496871.00      6925437.78
      1497170.15      6925188.38      1498005.00      6925288.00

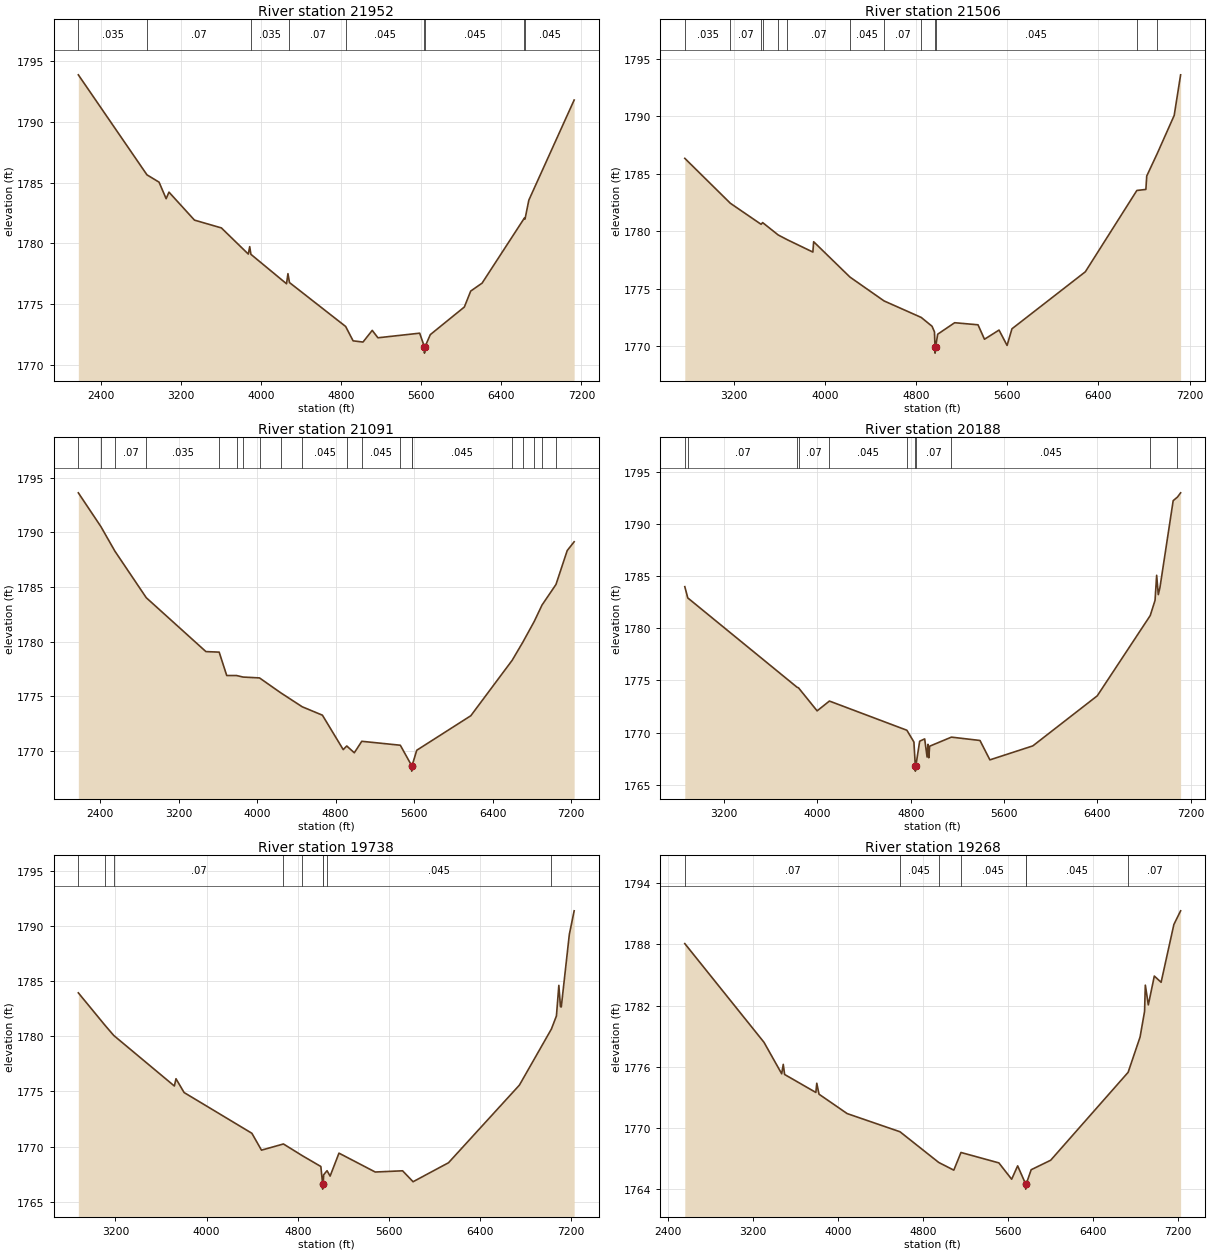
Type RM Length L Ch R = 1,21952,446,446,446
BEGIN DESCRIPTION:
NC Unknown Stream 12 29.0
END DESCRIPTION:
XS GIS Cut Line= 3
      1482204.99      6918288.01      1484205.00      6916288.00
      1485754.97      6914838.03
#Sta/Elev= 30
  2176.5 1793.85  2862.0 1785.63  2982.6 1785.03  3053.3 1783.67  3081.6 1784.21
  3336.2 1781.91  3604.9 1781.27  3873.6 1779.12  3887.7 1779.73  3899.7 1779.10
  4255.4 1776.68  4269.6 1777.51  4284.8 1776.78  4845.7 1773.17  4920.1 1771.99
  5018.9 1771.89  5111.2 1772.85  5167.9 1772.24  5585.0 1772.62  5632.8 1771.48
  5633.0 1770.98  5636.9 1771.48  5691.0 1772.50  6031.0 1774.77  6094.5 1776.08
  6207.9 1776.73  6631.3 1782.09  6636.9 1782.00  6674.8 1783.55  7127.4 1791.78
#Mann=9,-1,0
  2176.5   0.035       0  2862.0    0.07       0  3899.7   0.035       0
  4284.8    0.07       0  4845.7   0.045       0  5632.8   0.045       0
  5636.9   0.045       0  6631.3   0.035       0  6636.9   0.045       0
Bank Sta=5632.8,5636.9
Exp/Cntr=0.3,0.1

Type RM Length L Ch R = 1,21506,415,415,415
BEGIN DESCRIPTION:
NC Unknown Stream 12 28.0
END DESCRIPTION:
XS GIS Cut Line= 3
      1482855.00      6918138.00      1484455.00      6916588.00
      1485855.00      6914988.00
#Sta/Elev= 30
  2767.5 1786.35  3168.0 1782.43  3437.4 1780.60  3450.9 1780.75  3587.7 1779.67
  3668.5 1779.25  3892.0 1778.18  3899.0 1779.08  4217.7 1776.00  4517.1 1773.92
  4843.7 1772.48  4938.7 1771.71  4959.8 1771.22  4964.9 1769.87  4965.2 1769.37
  4969.1 1769.87  4988.1 1771.02  5137.1 1772.02  5342.1 1771.84  5399.0 1770.58
  5526.7 1771.38  5597.4 1770.04  5640.1 1771.49  6284.5 1776.46  6737.0 1783.55
  6816.1 1783.64  6823.6 1784.81  6916.4 1786.78  7064.7 1790.09  7121.2 1793.63
#Mann=13,-1,0
  2767.5   0.035       0  3168.0    0.07       0  3437.4   0.035       0
  3450.9    0.07       0  3587.7   0.035       0  3668.5    0.07       0
  4217.7   0.045       0  4517.1    0.07       0  4843.7   0.045       0
  4964.9   0.045       0  4969.1   0.045       0  6737.0   0.035       0
  6916.4   0.045       0
Bank Sta=4964.9,4969.1
Exp/Cntr=0.3,0.1

Type RM Length L Ch R = 1,21091,903,903,903
BEGIN DESCRIPTION:
NC Unknown Stream 12 27.0
END DESCRIPTION:
XS GIS Cut Line= 3
      1482655.03      6918887.97      1484655.00      6916888.00
      1486204.97      6915288.04
#Sta/Elev= 30
  2176.2 1793.62  2406.9 1790.52  2548.5 1788.29  2869.0 1784.02  3477.2 1779.09
  3612.4 1779.04  3689.4 1776.90  3789.4 1776.90  3855.2 1776.76  4023.8 1776.68
  4238.3 1775.33  4459.0 1774.04  4665.2 1773.27  4877.3 1770.12  4913.4 1770.45
  4990.4 1769.83  5066.5 1770.88  5459.6 1770.52  5575.2 1768.65  5575.5 1768.15
  5579.4 1768.65  5627.0 1770.06  6178.5 1773.22  6600.7 1778.30  6711.3 1779.99
  6826.3 1781.87  6904.5 1783.35  7046.7 1785.23  7161.6 1788.34  7232.2 1789.14
#Mann=20,-1,0
  2176.2    0.07       0  2406.9    0.07       0  2548.5    0.07       0
  2869.0   0.035       0  3612.4    0.07       0  3789.4   0.045       0
  3855.2    0.07       0  4023.8   0.045       0  4238.3    0.07       0
  4459.0   0.045       0  4913.4    0.07       0  5066.5   0.045       0
  5459.6   0.045       0  5575.2    0.07       0  5579.4   0.045       0
  6600.7    0.07       0  6711.3   0.045       0  6826.3    0.07       0
  6904.5   0.045       0  7046.7   0.035       0
Bank Sta=5575.2,5579.4
Exp/Cntr=0.3,0.1

Type RM Length L Ch R = 1,20188,450,450,450
BEGIN DESCRIPTION:
NC Unknown Stream 12 26.0
END DESCRIPTION:
XS GIS Cut Line= 3
      1483454.98      6918688.02      1485055.00      6917288.00
      1486605.03      6915837.97
#Sta/Elev= 30
  2864.4 1783.99  2890.0 1782.91  3825.9 1774.35  3838.8 1774.29  3998.2 1772.08
  4103.6 1773.02  4767.4 1770.22  4827.7 1769.09  4839.6 1766.80  4839.9 1766.30
  4844.2 1766.80  4877.0 1769.17  4919.8 1769.39  4940.6 1767.65  4948.2 1768.87
  4954.9 1767.58  4962.5 1768.69  5148.9 1769.56  5393.7 1769.24  5478.7 1767.38
  5846.5 1768.72  6398.5 1773.52  6852.6 1781.22  6893.9 1782.68  6907.6 1785.08
  6921.7 1783.23  6935.9 1783.91  7049.2 1792.24  7085.7 1792.58  7113.0 1792.99
#Mann=11,-1,0
  2864.4   0.035       0  2890.0    0.07       0  3825.9   0.045       0
  3838.8    0.07       0  4103.6   0.045       0  4767.4    0.07       0
  4839.6    0.07       0  4844.2    0.07       0  5148.9   0.045       0
  6852.6    0.07       0  7085.7   0.045       0
Bank Sta=4839.6,4844.2
Exp/Cntr=0.3,0.1

Type RM Length L Ch R = 1,19738,470,470,470
BEGIN DESCRIPTION:
NC Unknown Stream 12 25.0
END DESCRIPTION:
XS GIS Cut Line= 3
      1483505.03      6919037.97      1485105.00      6917638.00
      1486655.03      6916037.97
#Sta/Elev= 30
  2873.8 1783.92  3110.5 1780.95  3184.8 1780.06  3717.1 1775.48  3731.3 1776.14
  3802.5 1774.89  4397.6 1771.20  4482.0 1769.67  4674.7 1770.23  4842.1 1769.16
  5003.3 1768.19  5018.7 1766.64  5019.0 1766.14  5023.4 1766.64  5028.0 1767.44
  5057.8 1767.81  5084.6 1767.32  5162.5 1769.40  5480.7 1767.69  5721.2 1767.80
  5813.0 1766.81  6124.3 1768.53  6746.6 1775.56  7027.6 1780.64  7071.9 1781.83
  7093.1 1784.60  7107.2 1782.67  7114.4 1782.64  7185.1 1789.21  7227.5 1791.35
#Mann=9,-1,0
  2873.8    0.07       0  3110.5   0.035       0  3184.8    0.07       0
  4674.7   0.045       0  4842.1    0.07       0  5018.7    0.07       0
  5023.4    0.07       0  5057.8   0.045       0  7027.6    0.07       0
Bank Sta=5018.7,5023.4
Exp/Cntr=0.3,0.1

Type RM Length L Ch R = 1,19268,459,459,459
BEGIN DESCRIPTION:
NC Unknown Stream 12 24.0
END DESCRIPTION:
XS GIS Cut Line= 3
      1483355.04      6919387.97      1485355.00      6917988.00
      1486904.98      6916388.02
#Sta/Elev= 30
  2559.2 1788.07  3305.1 1778.40  3471.6 1775.32  3486.4 1776.24  3499.1 1775.25
  3793.3 1773.49  3802.0 1774.39  3823.0 1773.32  4088.0 1771.42  4585.4 1769.64
  4950.7 1766.63  5092.4 1765.88  5159.8 1767.61  5516.6 1766.59  5637.0 1764.99
  5693.6 1766.30  5768.8 1764.52  5769.1 1764.02  5773.8 1764.52  5820.9 1765.92
  6004.6 1766.85  6733.7 1775.46  6846.3 1778.92  6888.7 1781.43  6895.7 1784.00
  6924.0 1782.07  6980.5 1784.89  7044.3 1784.28  7164.5 1789.94  7228.1 1791.28
#Mann=7,-1,0
  2559.2    0.07       0  4585.4   0.045       0  4950.7    0.07       0
  5159.8   0.045       0  5768.8    0.07       0  5773.8   0.045       0
  6733.7    0.07       0
Bank Sta=5768.8,5773.8
Exp/Cntr=0.3,0.1

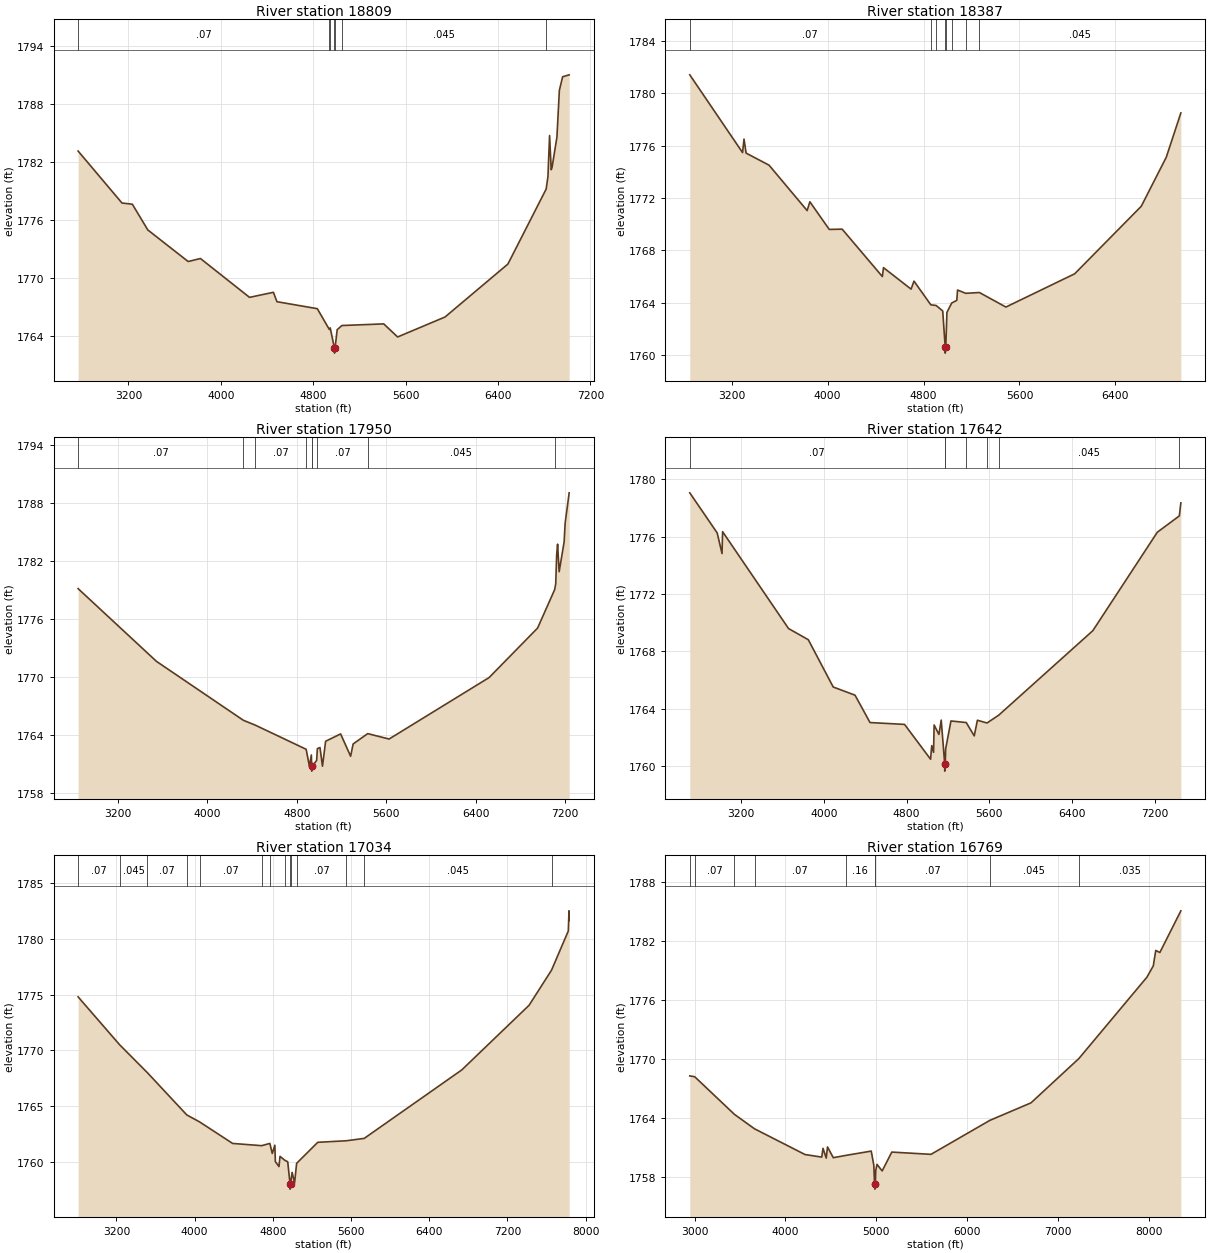
Type RM Length L Ch R = 1,18809,422,422,422
BEGIN DESCRIPTION:
NC Unknown Stream 12 23.0
END DESCRIPTION:
XS GIS Cut Line= 3
      1483655.01      6919287.99      1485655.00      6918288.00
      1487054.99      6916838.01
#Sta/Elev= 30
  2763.9 1783.14  3144.0 1777.77  3233.5 1777.65  3367.6 1774.99  3717.0 1771.73
  3823.2 1772.04  4248.1 1768.03  4454.9 1768.55  4485.7 1767.58  4835.0 1766.86
  4939.2 1764.71  4946.7 1764.88  4983.5 1762.77  4983.8 1762.27  4988.5 1762.77
  5007.0 1764.69  5047.6 1765.12  5410.1 1765.29  5530.3 1763.94  5940.6 1766.00
  6485.2 1771.47  6816.2 1779.21  6831.7 1780.50  6845.9 1784.74  6860.0 1781.21
  6867.0 1781.43  6909.4 1784.57  6930.7 1789.42  6959.0 1790.81  7015.5 1791.01
#Mann=7,-1,0
  2763.9    0.07       0  4939.2   0.045       0  4946.7    0.07       0
  4983.5    0.07       0  4988.5    0.07       0  5047.6   0.045       0
  6816.2    0.07       0
Bank Sta=4983.5,4988.5
Exp/Cntr=0.3,0.1

Type RM Length L Ch R = 1,18387,437,437,437
BEGIN DESCRIPTION:
NC Unknown Stream 12 22.0
END DESCRIPTION:
XS GIS Cut Line= 3
      1483855.02      6919437.99      1485855.00      6918638.00
      1486955.01      6917037.99
#Sta/Elev= 30
  2850.3 1781.40  3290.5 1775.46  3302.6 1776.49  3320.1 1775.42  3511.3 1774.50
  3829.0 1771.03  3851.9 1771.70  4013.5 1769.59  4121.2 1769.61  4456.4 1765.99
  4465.8 1766.67  4696.0 1765.03  4720.3 1765.64  4860.7 1763.83  4905.0 1763.78
  4959.9 1763.36  4980.2 1760.64  4980.6 1760.14  4985.4 1760.64  4994.9 1763.25
  5035.0 1763.97  5077.2 1764.17  5083.5 1764.96  5151.6 1764.71  5265.9 1764.77
  5486.7 1763.66  6060.4 1766.20  6615.9 1771.36  6824.6 1775.11  6946.0 1778.49
#Mann=8,-1,0
  2850.3    0.07       0  4860.7    0.16       0  4905.0    0.07       0
  4980.2    0.07       0  4985.4    0.07       0  5035.0    0.16       0
  5151.6    0.07       0  5265.9   0.045       0
Bank Sta=4980.2,4985.4
Exp/Cntr=0.3,0.1

Type RM Length L Ch R = 1,17950,308,308,308
BEGIN DESCRIPTION:
NC Unknown Stream 12 21.0
END DESCRIPTION:
XS GIS Cut Line= 3
      1484104.97      6919738.01      1486105.00      6918938.00
      1487105.02      6916937.97
#Sta/Elev= 30
  2845.6 1779.15  3545.7 1771.63  4323.1 1765.53  4431.0 1765.02  4884.5 1762.53
  4913.5 1760.78  4931.0 1761.94  4933.8 1760.77  4934.2 1760.27  4939.0 1760.77
  4978.2 1761.38  4984.8 1762.60  5008.1 1762.71  5030.4 1760.78  5058.4 1763.36
  5192.6 1764.12  5282.0 1761.81  5304.4 1763.08  5434.8 1764.15  5625.8 1763.59
  6520.2 1769.95  6953.5 1775.07  7106.3 1779.05  7115.6 1779.65  7124.0 1782.65
  7132.3 1783.75  7146.3 1780.90  7191.0 1784.00  7199.4 1785.89  7235.8 1789.06
#Mann=9,-1,0
  2845.6    0.07       0  4323.1    0.16       0  4431.0    0.07       0
  4884.5    0.16       0  4933.8    0.07       0  4939.0    0.16       0
  4984.8    0.07       0  5434.8   0.045       0  7106.3    0.07       0
Bank Sta=4933.8,4939
Exp/Cntr=0.3,0.1

Type RM Length L Ch R = 1,17642,608,608,608
BEGIN DESCRIPTION:
NC Unknown Stream 12 20.0
END DESCRIPTION:
XS GIS Cut Line= 3
      1484158.39      6920121.03      1486359.82      6919141.84
      1487602.75      6917162.87
#Sta/Elev= 30
  2705.0 1779.05  2970.1 1776.25  3016.6 1774.81  3022.1 1776.34  3659.4 1769.58
  3850.5 1768.80  4091.3 1765.50  4302.1 1764.93  4447.1 1763.02  4780.8 1762.89
  5032.4 1760.46  5043.4 1761.41  5061.1 1760.94  5066.6 1762.85  5113.0 1762.19
  5135.1 1763.19  5168.9 1760.13  5169.3 1759.63  5174.2 1760.13  5178.0 1761.19
  5229.3 1763.13  5377.0 1763.02  5454.3 1762.09  5484.9 1763.18  5578.1 1762.99
  5691.8 1763.54  6600.5 1769.43  7223.6 1776.30  7436.6 1777.44  7451.3 1778.35
#Mann=7,-1,0
  2705.0    0.07       0  5168.9    0.07       0  5174.2    0.07       0
  5377.0   0.045       0  5578.1    0.07       0  5691.8   0.045       0
  7436.6    0.07       0
Bank Sta=5168.9,5174.2
Exp/Cntr=0.3,0.1

Type RM Length L Ch R = 1,17034,265,265,265
BEGIN DESCRIPTION:
NC Unknown Stream 12 19.0
END DESCRIPTION:
XS GIS Cut Line= 3
      1484575.14      6920280.72      1486655.00      6919588.00
      1487970.45      6917080.26
#Sta/Elev= 30
  2807.8 1774.80  3233.0 1770.51  3516.0 1768.02  3920.0 1764.23  4050.4 1763.61
  4388.7 1761.68  4685.3 1761.48  4769.6 1761.68  4794.4 1760.78  4820.7 1761.52
  4826.0 1760.05  4863.0 1759.61  4873.5 1760.52  4923.1 1760.17  4952.5 1760.04
  4975.9 1758.09  4976.4 1757.59  4981.8 1758.09  4997.3 1759.09  5022.6 1758.15
  5043.6 1759.90  5259.7 1761.78  5553.0 1761.92  5734.9 1762.13  6733.1 1768.26
  7422.0 1774.05  7651.4 1777.19  7823.1 1780.70  7829.8 1782.50  7831.8 1781.64
#Mann=14,-1,0
  2807.8    0.07       0  3233.0   0.045       0  3516.0    0.07       0
  3920.0    0.16       0  4050.4    0.07       0  4685.3    0.16       0
  4769.6    0.07       0  4923.1    0.16       0  4975.9    0.07       0
  4981.8    0.16       0  5043.6    0.07       0  5553.0    0.16       0
  5734.9   0.045       0  7651.4    0.07       0
Bank Sta=4975.9,4981.8
Exp/Cntr=0.3,0.1

Type RM Length L Ch R = 1,16769,1046,1046,1046
BEGIN DESCRIPTION:
Mapping XS a78e5815
END DESCRIPTION:
XS GIS Cut Line= 5
      1485151.50      6920864.06      1486102.87      6920496.01
      1487262.60      6919315.45      1487797.32      6918259.90
      1488262.58      6916787.72
#Sta/Elev= 30
  2947.7 1768.26  3001.5 1768.18  3438.8 1764.35  3659.7 1762.88  4215.4 1760.26
  4399.3 1760.00  4413.4 1760.89  4448.7 1759.90  4462.9 1761.03  4526.5 1759.94
  4663.2 1760.17  4943.8 1760.61  4972.1 1759.18  4980.1 1757.35  4983.2 1757.24
  4983.7 1756.74  4989.2 1757.24  4993.2 1758.63  5007.4 1759.26  5063.9 1758.59
  5170.1 1760.51  5601.4 1760.28  6249.3 1763.74  6701.4 1765.52  7228.2 1770.03
  7976.8 1778.31  8046.7 1779.46  8073.8 1781.03  8118.9 1780.82  8349.9 1785.06
#Mann=10,-1,0
  2947.7   0.045       0  3001.5    0.07       0  3438.8   0.035       0
  3659.7    0.07       0  4663.2    0.16       0  4980.1    0.07       0
  4983.2    0.07       0  4989.2    0.07       0  6249.3   0.045       0
  7228.2   0.035       0
Bank Sta=4983.2,4989.2
Exp/Cntr=0.3,0.1

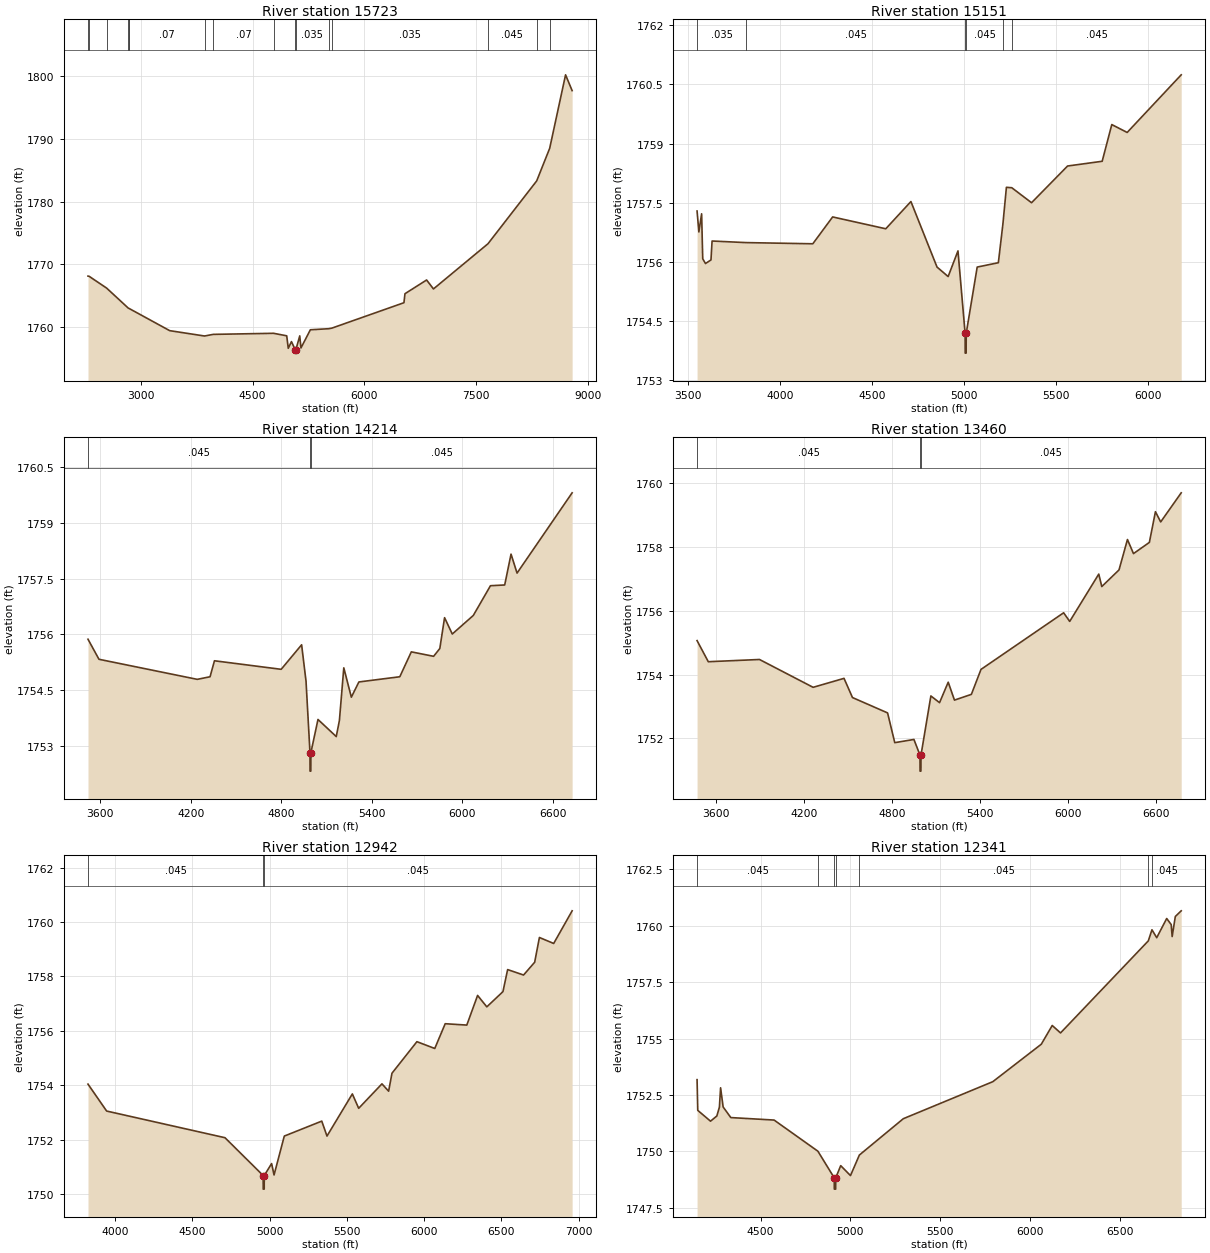
Type RM Length L Ch R = 1,15723,572,572,572
BEGIN DESCRIPTION:
NC Unknown Stream 12 18.0
END DESCRIPTION:
XS GIS Cut Line= 4
      1485075.09      6921114.07      1486595.93      6920940.45
      1487355.00      6920038.00      1488644.55      6916475.15
#Sta/Elev= 30
  2290.0 1768.15  2306.0 1768.11  2540.5 1766.24  2830.1 1763.07  2840.5 1763.01
  2844.2 1762.99  3387.0 1759.48  3854.6 1758.63  3971.7 1758.89  4781.3 1759.06
  4957.7 1758.66  4978.5 1756.68  5021.2 1757.74  5073.6 1756.41  5074.1 1755.91
  5079.6 1756.41  5132.5 1758.65  5148.8 1756.73  5275.1 1759.62  5522.8 1759.79
  5563.5 1759.88  6531.4 1763.92  6544.9 1765.35  6835.4 1767.53  6927.4 1766.11
  7659.4 1773.29  8313.5 1783.28  8487.8 1788.46  8700.9 1800.13  8789.0 1797.62
#Mann=16,-1,0
  2290.0   0.045       0  2306.0    0.07       0  2540.5   0.045       0
  2830.1    0.07       0  2840.5   0.045       0  2844.2    0.07       0
  3854.6   0.035       0  3971.7    0.07       0  4781.3   0.035       0
  5073.6   0.035       0  5079.6   0.035       0  5522.8    0.07       0
  5563.5   0.035       0  7659.4   0.045       0  8313.5    0.07       0
  8487.8   0.035       0
Bank Sta=5073.6,5079.6
Exp/Cntr=0.3,0.1

Type RM Length L Ch R = 1,15151,937,937,937
BEGIN DESCRIPTION:
Mapping XS df3ab163
END DESCRIPTION:
XS GIS Cut Line= 3
      1487154.82      6921621.55      1487645.27      6920901.07
      1488157.44      6919217.00
#Sta/Elev= 30
  3550.6 1757.29  3560.4 1756.76  3575.3 1757.22  3581.4 1756.08  3596.3 1755.96
  3626.2 1756.05  3632.2 1756.53  3815.9 1756.49  4179.8 1756.46  4287.6 1757.14
  4576.4 1756.84  4713.1 1757.53  4855.0 1755.87  4915.5 1755.63  4968.9 1756.28
  5007.7 1754.19  5008.2 1753.69  5013.2 1753.69  5013.7 1754.19  5073.4 1755.87
  5188.4 1755.98  5212.9 1756.95  5232.2 1757.89  5261.4 1757.88  5368.8 1757.50
  5564.7 1758.43  5752.8 1758.55  5805.1 1759.48  5888.7 1759.28  6182.4 1760.74
#Mann=6,-1,0
  3550.6   0.035       0  3815.9   0.045       0  5007.7   0.045       0
  5013.7   0.045       0  5212.9   0.035       0  5261.4   0.045       0
Bank Sta=5007.7,5013.7
Exp/Cntr=0.3,0.1

Type RM Length L Ch R = 1,14214,754,754,754
BEGIN DESCRIPTION:
Mapping XS 549ee18a
END DESCRIPTION:
XS GIS Cut Line= 4
      1487458.61      6921699.69      1488140.06      6921408.88
      1488956.04      6920310.79      1489289.72      6919262.08
#Sta/Elev= 30
  3518.8 1755.87  3591.6 1755.33  4243.3 1754.79  4328.0 1754.86  4357.2 1755.29
  4799.4 1755.06  4935.0 1755.72  4964.2 1754.74  4990.4 1752.82  4990.9 1752.32
  4996.0 1752.32  4996.5 1752.82  5043.5 1753.71  5164.5 1753.25  5185.4 1753.68
  5214.6 1755.10  5264.6 1754.31  5314.7 1754.72  5585.9 1754.86  5662.2 1755.53
  5810.1 1755.41  5851.1 1755.62  5882.6 1756.45  5933.7 1756.01  6073.2 1756.51
  6186.9 1757.31  6281.3 1757.33  6323.3 1758.16  6363.2 1757.65  6728.3 1759.81
#Mann=3,-1,0
  3518.8   0.045       0  4990.4   0.045       0  4996.5   0.045       0
Bank Sta=4990.4,4996.5
Exp/Cntr=0.3,0.1

Type RM Length L Ch R = 1,13460,518,518,518
BEGIN DESCRIPTION:
Mapping XS 52ad8cb7
END DESCRIPTION:
XS GIS Cut Line= 4
      1488122.75      6921886.30      1488860.55      6921625.90
      1489472.53      6920653.67      1489802.18      6919322.08
#Sta/Elev= 30
  3471.2 1755.06  3547.8 1754.40  3897.1 1754.47  4262.9 1753.60  4473.8 1753.88
  4531.5 1753.28  4771.0 1752.80  4820.0 1751.87  4950.7 1751.97  4992.1 1751.48
  4992.6 1750.98  4998.4 1750.98  4998.9 1751.48  5066.4 1753.33  5125.5 1753.12
  5184.6 1753.76  5227.3 1753.20  5342.7 1753.38  5408.3 1754.16  5972.1 1755.93
  6013.5 1755.66  6211.8 1757.14  6232.4 1756.75  6349.9 1757.27  6407.5 1758.22
  6448.7 1757.78  6557.0 1758.13  6598.4 1759.09  6634.2 1758.77  6774.2 1759.68
#Mann=3,-1,0
  3471.2   0.045       0  4992.1   0.045       0  4998.9   0.045       0
Bank Sta=4992.1,4998.9
Exp/Cntr=0.3,0.1

Type RM Length L Ch R = 1,12942,601,601,601
BEGIN DESCRIPTION:
Mapping XS 389b568d
END DESCRIPTION:
XS GIS Cut Line= 4
      1488908.27      6922099.00      1489455.17      6921686.66
      1489819.75      6920914.09      1490171.01      6919361.63
#Sta/Elev= 30
  3826.1 1754.04  3946.7 1753.05  4712.0 1752.07  4958.9 1750.68  4959.4 1750.18
  4965.6 1750.18  4966.1 1750.68  5013.5 1751.12  5029.3 1750.70  5095.6 1752.13
  5337.9 1752.68  5371.6 1752.13  5535.6 1753.68  5576.6 1753.15  5727.1 1754.05
  5770.3 1753.78  5791.9 1754.44  5953.2 1755.60  6068.7 1755.35  6136.1 1756.26
  6275.8 1756.21  6345.6 1757.30  6405.3 1756.88  6509.6 1757.44  6539.9 1758.25
  6642.9 1758.05  6714.7 1758.52  6745.4 1759.43  6837.7 1759.21  6957.0 1760.41
#Mann=3,-1,0
  3826.1   0.045       0  4958.9   0.045       0  4966.1   0.045       0
Bank Sta=4958.9,4966.1
Exp/Cntr=0.3,0.1

Type RM Length L Ch R = 1,12341,695,695,695
BEGIN DESCRIPTION:
Mapping XS d281f9cb
END DESCRIPTION:
XS GIS Cut Line= 4
      1489637.48      6922185.78      1489976.00      6921890.65
      1490501.17      6920666.69      1490818.01      6919807.32
#Sta/Elev= 30
  4145.9 1753.18  4149.7 1751.82  4220.9 1751.34  4256.0 1751.57  4270.3 1751.96
  4276.9 1752.82  4291.1 1751.97  4333.9 1751.50  4575.0 1751.39  4819.0 1750.01
  4910.0 1748.83  4910.5 1748.33  4917.9 1748.33  4918.4 1748.83  4946.1 1749.37
  5000.5 1748.93  5050.0 1749.84  5294.8 1751.45  5793.3 1753.09  6063.4 1754.75
  6124.3 1755.58  6170.6 1755.25  6659.7 1759.33  6679.8 1759.82  6706.4 1759.47
  6762.0 1760.32  6787.1 1760.05  6792.4 1759.52  6810.1 1760.41  6842.8 1760.66
#Mann=7,-1,0
  4145.9   0.045       0  4819.0    0.07       0  4910.0    0.07       0
  4918.4    0.07       0  5050.0   0.045       0  6659.7    0.16       0
  6679.8   0.045       0
Bank Sta=4910,4918.4
Exp/Cntr=0.3,0.1

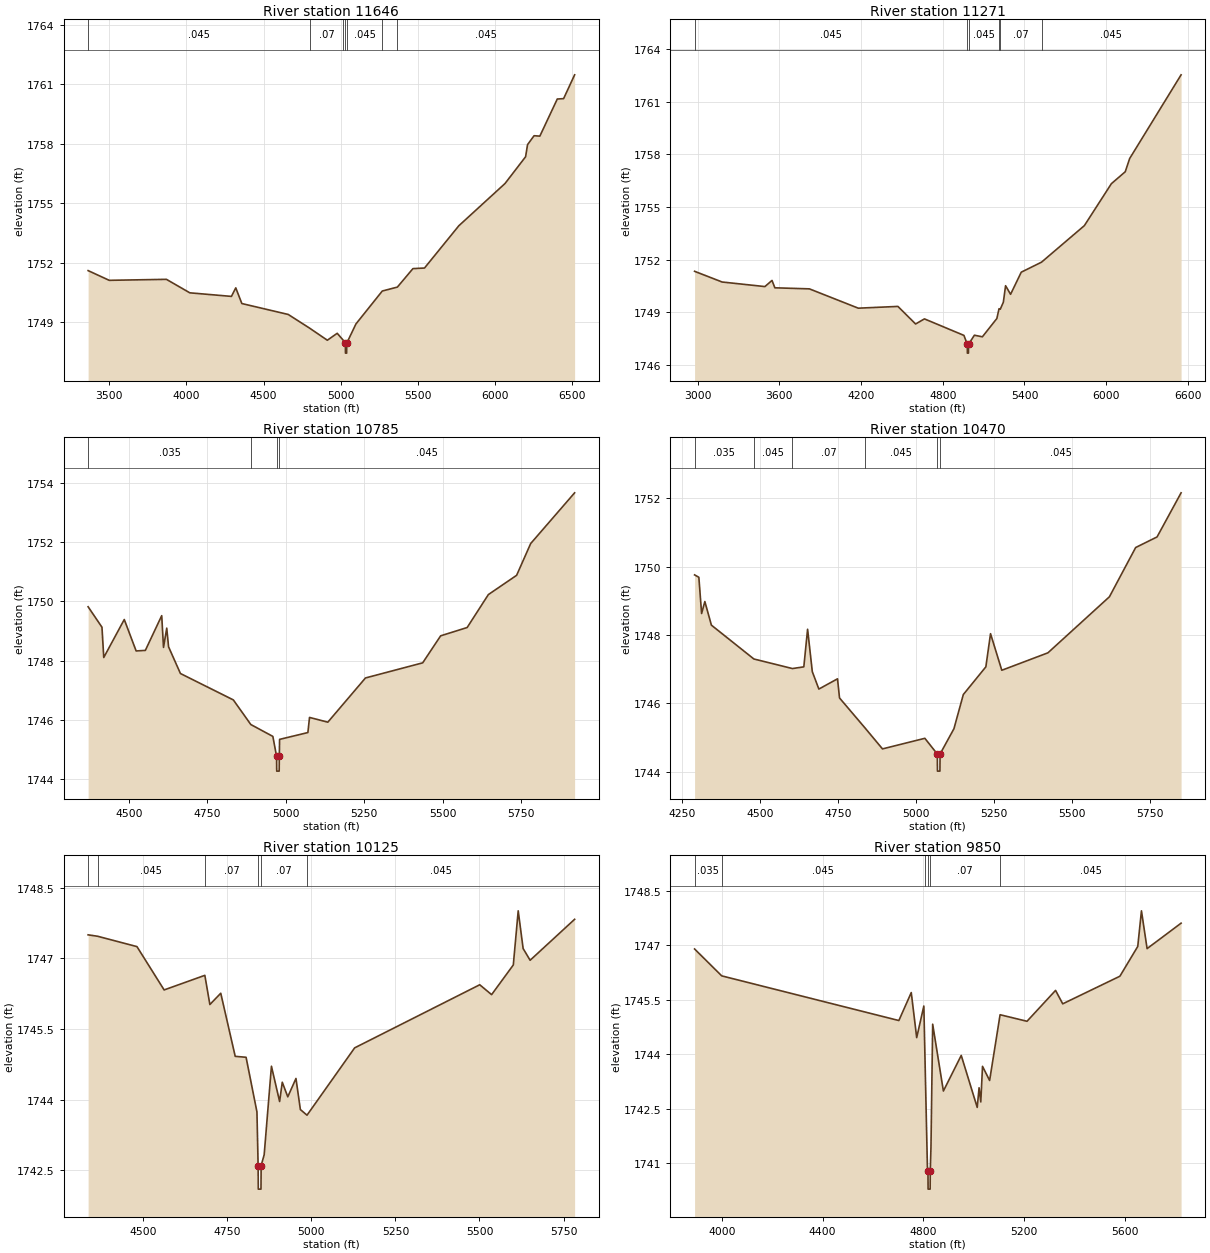
Type RM Length L Ch R = 1,11646,375,375,375
BEGIN DESCRIPTION:
Mapping XS ca77811c
END DESCRIPTION:
XS GIS Cut Line= 4
      1489520.30      6922684.91      1490544.58      6922181.45
      1491056.73      6921039.96      1491230.17      6920298.52
#Sta/Elev= 30
  3362.3 1751.60  3499.2 1751.11  3869.9 1751.16  4021.7 1750.48  4291.4 1750.30
  4319.5 1750.73  4358.9 1749.94  4659.4 1749.39  4798.1 1748.70  4913.1 1748.09
  4977.1 1748.44  5016.2 1748.09  5030.1 1747.94  5030.6 1747.44  5038.3 1747.44
  5038.8 1747.94  5098.5 1748.91  5269.2 1750.57  5367.4 1750.77  5468.0 1751.70
  5543.0 1751.73  5765.5 1753.86  6064.9 1755.99  6198.4 1757.34  6211.0 1757.95
  6253.4 1758.40  6290.8 1758.38  6403.8 1760.25  6444.8 1760.27  6516.2 1761.47
#Mann=7,-1,0
  3362.3   0.045       0  4798.1    0.07       0  5016.2   0.045       0
  5030.1    0.07       0  5038.8   0.045       0  5269.2    0.07       0
  5367.4   0.045       0
Bank Sta=5030.1,5038.8
Exp/Cntr=0.3,0.1

Type RM Length L Ch R = 1,11271,486,486,486
BEGIN DESCRIPTION:
Mapping XS af8a1669
END DESCRIPTION:
XS GIS Cut Line= 4
      1489476.83      6922897.61      1490844.06      6922433.19
      1491186.94      6921608.53      1491429.99      6920397.63
#Sta/Elev= 30
  2978.0 1751.34  3180.4 1750.73  3494.3 1750.47  3546.4 1750.82  3567.5 1750.40
  3821.0 1750.34  4180.0 1749.24  4470.9 1749.34  4600.8 1748.34  4665.8 1748.63
  4955.6 1747.69  4980.5 1747.18  4981.0 1746.68  4988.7 1746.68  4989.2 1747.18
  5032.6 1747.70  5091.1 1747.61  5197.3 1748.65  5213.4 1749.21  5222.5 1749.18
  5245.1 1749.58  5261.5 1750.52  5298.2 1750.03  5376.6 1751.29  5525.3 1751.86
  5839.8 1753.94  6038.3 1756.33  6140.1 1757.01  6172.3 1757.76  6550.1 1762.53
#Mann=6,-1,0
  2978.0   0.045       0  4980.5   0.045       0  4989.2   0.045       0
  5213.4   0.035       0  5222.5    0.07       0  5525.3   0.045       0
Bank Sta=4980.5,4989.2
Exp/Cntr=0.3,0.1

Type RM Length L Ch R = 1,10785,315,315,315
BEGIN DESCRIPTION:
Mapping XS 8d4b25c7
END DESCRIPTION:
XS GIS Cut Line= 4
      1490986.42      6922707.50      1491214.42      6922294.62
      1491774.32      6922110.16      1491988.88      6921672.36
#Sta/Elev= 30
  4370.8 1749.82  4414.9 1749.13  4420.6 1748.11  4485.9 1749.39  4523.7 1748.33
  4553.0 1748.35  4605.1 1749.52  4610.8 1748.45  4621.1 1749.10  4626.9 1748.47
  4664.7 1747.57  4833.1 1746.68  4888.8 1745.85  4958.9 1745.45  4970.7 1744.78
  4971.2 1744.28  4979.0 1744.28  4979.5 1744.78  4980.3 1745.35  5070.4 1745.58
  5075.6 1746.09  5133.9 1745.93  5253.7 1747.42  5435.9 1747.93  5493.0 1748.84
  5577.4 1749.12  5644.9 1750.23  5734.9 1750.88  5779.6 1751.95  5919.5 1753.66
#Mann=4,-1,0
  4370.8   0.035       0  4888.8   0.045       0  4970.7   0.045       0
  4979.5   0.045       0
Bank Sta=4970.7,4979.5
Exp/Cntr=0.3,0.1

Type RM Length L Ch R = 1,10470,345,345,345
BEGIN DESCRIPTION:
Mapping XS fb553a09
END DESCRIPTION:
XS GIS Cut Line= 4
      1490973.52      6922746.01      1491283.86      6922650.52
      1491956.61      6922203.47      1492112.86      6921806.34
#Sta/Elev= 30
  4290.1 1749.76  4303.8 1749.69  4312.6 1748.63  4323.0 1748.98  4344.0 1748.29
  4480.1 1747.30  4603.8 1747.02  4640.2 1747.07  4652.3 1748.17  4667.4 1746.93
  4688.4 1746.42  4748.2 1746.72  4754.6 1746.16  4836.6 1745.28  4892.3 1744.67
  5028.1 1744.98  5068.0 1744.52  5068.5 1744.02  5076.4 1744.02  5076.9 1744.52
  5121.3 1745.26  5151.4 1746.26  5223.6 1747.07  5238.6 1748.04  5274.7 1746.97
  5422.5 1747.48  5619.7 1749.12  5703.7 1750.56  5772.3 1750.87  5849.3 1752.16
#Mann=6,-1,0
  4290.1   0.035       0  4480.1   0.045       0  4603.8    0.07       0
  4836.6   0.045       0  5068.0   0.045       0  5076.9   0.045       0
Bank Sta=5068,5076.9
Exp/Cntr=0.3,0.1

Type RM Length L Ch R = 1,10125,275,275,275
BEGIN DESCRIPTION:
Mapping XS acbc77eb
END DESCRIPTION:
XS GIS Cut Line= 4
      1491071.14      6922926.14      1491353.31      6922887.07
      1491997.84      6922630.99      1492279.97      6922257.71
#Sta/Elev= 30
  4336.5 1747.50  4364.7 1747.47  4481.7 1747.25  4562.5 1746.33  4683.5 1746.64
  4698.5 1746.02  4730.8 1746.26  4773.8 1744.92  4806.1 1744.90  4838.4 1743.74
  4841.9 1742.60  4842.4 1742.10  4850.4 1742.10  4850.9 1742.60  4859.9 1742.83
  4881.5 1744.71  4905.8 1743.96  4913.7 1744.37  4930.1 1744.06  4954.4 1744.45
  4967.5 1743.79  4987.2 1743.67  5128.9 1745.10  5500.7 1746.44  5536.0 1746.23
  5600.5 1746.86  5615.1 1748.01  5629.7 1747.21  5650.5 1746.96  5782.8 1747.83
#Mann=6,-1,0
  4336.5   0.035       0  4364.7   0.045       0  4683.5    0.07       0
  4841.9   0.045       0  4850.9    0.07       0  4987.2   0.045       0
Bank Sta=4841.9,4850.9
Exp/Cntr=0.3,0.1

Type RM Length L Ch R = 1,9850,409,409,409
BEGIN DESCRIPTION:
Mapping XS 3fdc025c
END DESCRIPTION:
XS GIS Cut Line= 4
      1490894.15      6923372.80      1491572.49      6923173.53
      1492217.02      6922583.25      1492425.33      6922299.00
#Sta/Elev= 30
  3891.4 1746.90  3999.2 1746.16  4703.2 1744.93  4752.5 1745.70  4774.1 1744.46
  4802.5 1745.33  4805.6 1744.34  4816.6 1740.91  4818.9 1740.79  4819.4 1740.29
  4827.5 1740.29  4828.0 1740.79  4830.8 1741.44  4837.6 1744.83  4880.2 1742.99
  4951.1 1743.97  5014.6 1742.54  5022.0 1743.08  5028.8 1742.69  5035.7 1743.67
  5063.9 1743.28  5105.5 1745.09  5212.5 1744.91  5326.0 1745.76  5354.4 1745.39
  5581.6 1746.15  5652.6 1746.97  5667.3 1747.95  5689.7 1746.91  5824.8 1747.61
#Mann=6,-1,0
  3891.4   0.035       0  3999.2   0.045       0  4805.6    0.07       0
  4818.9    0.07       0  4828.0    0.07       0  5105.5   0.045       0
Bank Sta=4818.9,4828
Exp/Cntr=0.3,0.1

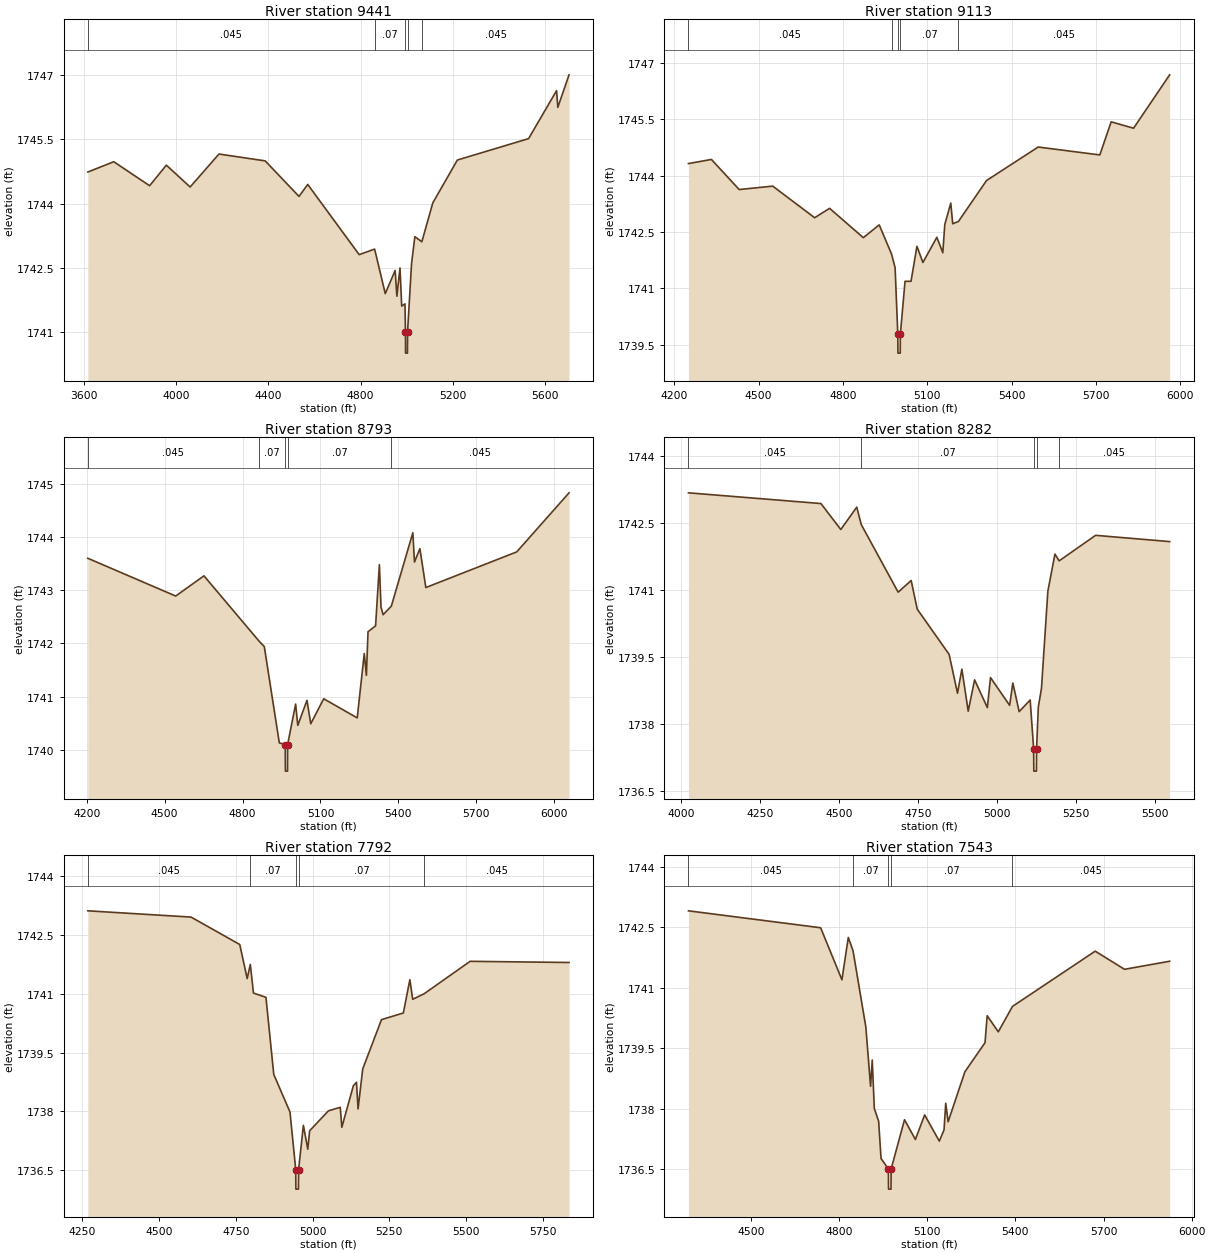
Type RM Length L Ch R = 1,9441,328,328,328
BEGIN DESCRIPTION:
Mapping XS 88969cfc
END DESCRIPTION:
XS GIS Cut Line= 4
      1491080.71      6923806.86      1492026.05      6923284.20
      1492531.69      6922700.44      1492630.78      6922489.35
#Sta/Elev= 30
  3617.9 1744.74  3730.3 1744.98  3885.6 1744.42  3958.2 1744.90  4061.3 1744.39
  4186.2 1745.16  4386.6 1745.00  4533.2 1744.17  4571.0 1744.45  4794.0 1742.81
  4860.9 1742.94  4907.0 1741.90  4949.8 1742.44  4957.4 1741.84  4970.9 1742.50
  4978.3 1741.61  4992.5 1741.66  4994.6 1741.01  4995.1 1740.51  5003.2 1740.51
  5003.7 1741.01  5021.0 1742.60  5035.3 1743.23  5065.6 1743.11  5113.2 1744.02
  5219.6 1745.02  5528.3 1745.52  5649.5 1746.64  5655.0 1746.25  5703.6 1747.01
#Mann=5,-1,0
  3617.9   0.045       0  4860.9    0.07       0  4994.6    0.07       0
  5003.7    0.07       0  5065.6   0.045       0
Bank Sta=4994.6,5003.7
Exp/Cntr=0.3,0.1

Type RM Length L Ch R = 1,9113,320,320,320
BEGIN DESCRIPTION:
Mapping XS 6fc41acc
END DESCRIPTION:
XS GIS Cut Line= 4
      1491748.26      6923685.69      1492221.36      6923490.37
      1492933.17      6922795.92      1493004.76      6922602.85
#Sta/Elev= 30
  4250.5 1744.32  4332.1 1744.43  4430.9 1743.63  4550.6 1743.72  4699.5 1742.88
  4752.7 1743.13  4872.7 1742.35  4929.2 1742.69  4973.4 1741.91  4985.8 1741.55
  4995.4 1739.78  4995.9 1739.28  5004.0 1739.28  5004.5 1739.78  5021.1 1741.19
  5042.4 1741.19  5063.5 1742.12  5084.8 1741.69  5134.3 1742.36  5155.6 1741.95
  5162.6 1742.70  5183.9 1743.27  5190.8 1742.72  5211.0 1742.78  5311.2 1743.87
  5494.9 1744.76  5714.2 1744.55  5754.6 1745.43  5834.3 1745.26  5962.7 1746.68
#Mann=5,-1,0
  4250.5   0.045       0  4973.4    0.07       0  4995.4    0.07       0
  5004.5    0.07       0  5211.0   0.045       0
Bank Sta=4995.4,5004.5
Exp/Cntr=0.3,0.1

Type RM Length L Ch R = 1,8793,511,511,511
BEGIN DESCRIPTION:
Mapping XS ad449e24
END DESCRIPTION:
XS GIS Cut Line= 4
      1491906.69      6923846.27      1492392.80      6923657.47
      1493026.49      6923177.87      1493345.49      6922746.02
#Sta/Elev= 30
  4204.2 1743.60  4542.5 1742.89  4651.4 1743.27  4862.3 1742.05  4883.7 1741.94
  4941.6 1740.13  4964.4 1740.10  4964.9 1739.60  4973.1 1739.60  4973.6 1740.10
  5004.4 1740.86  5012.7 1740.46  5048.1 1740.93  5062.6 1740.49  5112.6 1740.96
  5241.6 1740.60  5268.7 1741.81  5276.9 1741.40  5283.2 1742.22  5312.3 1742.33
  5326.9 1743.48  5333.2 1742.68  5341.4 1742.54  5372.9 1742.70  5455.8 1744.08
  5462.1 1743.53  5483.0 1743.78  5505.8 1743.05  5855.9 1743.72  6057.3 1744.83
#Mann=5,-1,0
  4204.2   0.045       0  4862.3    0.07       0  4964.4    0.07       0
  4973.6    0.07       0  5372.9   0.045       0
Bank Sta=4964.4,4973.6
Exp/Cntr=0.3,0.1

Type RM Length L Ch R = 1,8282,490,490,490
BEGIN DESCRIPTION:
Mapping XS 5f339102
END DESCRIPTION:
XS GIS Cut Line= 4
      1492025.86      6923967.53      1492428.68      6923776.54
      1493293.27      6923661.95      1493483.18      6923582.53
#Sta/Elev= 30
  4023.2 1743.17  4442.8 1742.93  4505.6 1742.35  4556.1 1742.85  4570.4 1742.46
  4687.2 1740.95  4728.4 1741.21  4747.7 1740.57  4848.6 1739.56  4875.2 1738.69
  4889.0 1739.23  4909.1 1738.29  4929.3 1738.99  4969.7 1738.37  4979.7 1739.04
  5040.3 1738.42  5050.4 1738.92  5070.5 1738.28  5105.3 1738.54  5116.3 1737.45
  5116.8 1736.95  5125.1 1736.95  5125.6 1737.45  5131.1 1738.38  5141.1 1738.80
  5161.3 1740.97  5183.7 1741.80  5197.1 1741.65  5312.6 1742.22  5547.0 1742.08
#Mann=5,-1,0
  4023.2   0.045       0  4570.4    0.07       0  5116.3    0.07       0
  5125.6    0.07       0  5197.1   0.045       0
Bank Sta=5116.3,5125.6
Exp/Cntr=0.3,0.1

Type RM Length L Ch R = 1,7792,249,249,249
BEGIN DESCRIPTION:
Mapping XS 4dbc1ad9
END DESCRIPTION:
XS GIS Cut Line= 4
      1492029.42      6924071.68      1492348.82      6924075.15
      1493154.38      6923925.84      1493500.39      6923673.25
#Sta/Elev= 30
  4268.2 1743.12  4604.3 1742.96  4762.9 1742.26  4787.1 1741.39  4797.3 1741.75
  4807.5 1741.02  4848.2 1740.91  4873.7 1738.94  4926.5 1737.98  4945.2 1736.51
  4945.7 1736.01  4954.0 1736.01  4954.5 1736.51  4970.2 1737.64  4984.5 1737.03
  4990.5 1737.50  5051.6 1738.01  5090.2 1738.10  5095.3 1737.59  5132.9 1738.65
  5143.1 1738.74  5148.2 1738.06  5163.4 1739.08  5224.5 1740.34  5295.7 1740.51
  5316.9 1741.36  5326.2 1740.86  5363.2 1741.00  5513.2 1741.83  5835.3 1741.80
#Mann=5,-1,0
  4268.2   0.045       0  4797.3    0.07       0  4945.2    0.07       0
  4954.5    0.07       0  5363.2   0.045       0
Bank Sta=4945.2,4954.5
Exp/Cntr=0.3,0.1

Type RM Length L Ch R = 1,7543,589,589,589
BEGIN DESCRIPTION:
Mapping XS 822b8d69
END DESCRIPTION:
XS GIS Cut Line= 4
      1492161.30      6924609.89      1492432.16      6924398.06
      1493088.41      6924036.95      1493529.37      6923717.51
#Sta/Elev= 30
  4287.7 1742.91  4737.5 1742.49  4809.9 1741.20  4831.6 1742.25  4847.7 1741.92
  4891.3 1740.03  4907.4 1738.56  4913.1 1739.21  4920.1 1738.01  4934.9 1737.69
  4943.0 1736.77  4968.0 1736.51  4968.5 1736.01  4976.9 1736.01  4977.4 1736.51
  5022.9 1737.73  5059.9 1737.24  5091.4 1737.85  5141.3 1737.20  5157.4 1737.48
  5163.1 1738.14  5171.3 1737.68  5228.4 1738.92  5296.8 1739.64  5304.2 1740.31
  5342.0 1739.91  5390.3 1740.54  5671.8 1741.91  5771.5 1741.46  5925.1 1741.66
#Mann=5,-1,0
  4287.7   0.045       0  4847.7    0.07       0  4968.0    0.07       0
  4977.4    0.07       0  5390.3   0.045       0
Bank Sta=4968,4977.4
Exp/Cntr=0.3,0.1