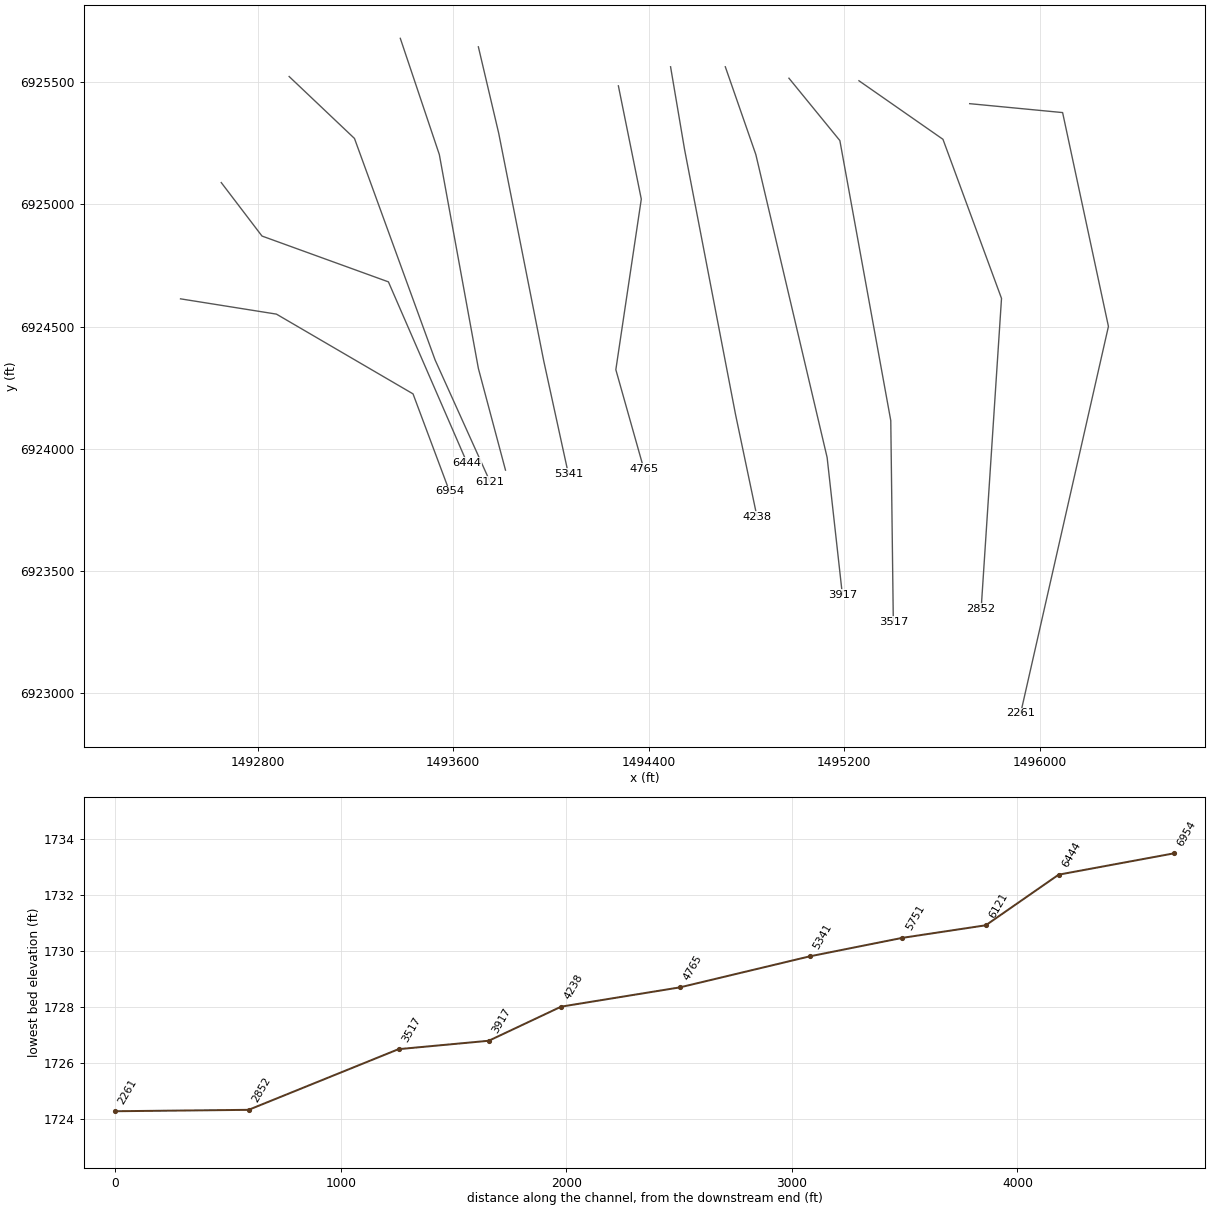
HEC-RAS study NC Unknown Stream 12.prj: NC Unknown Stream 12 Base Level Engineering

--- NC Unknown Stream 12.g01 (geometry) --- (continued)

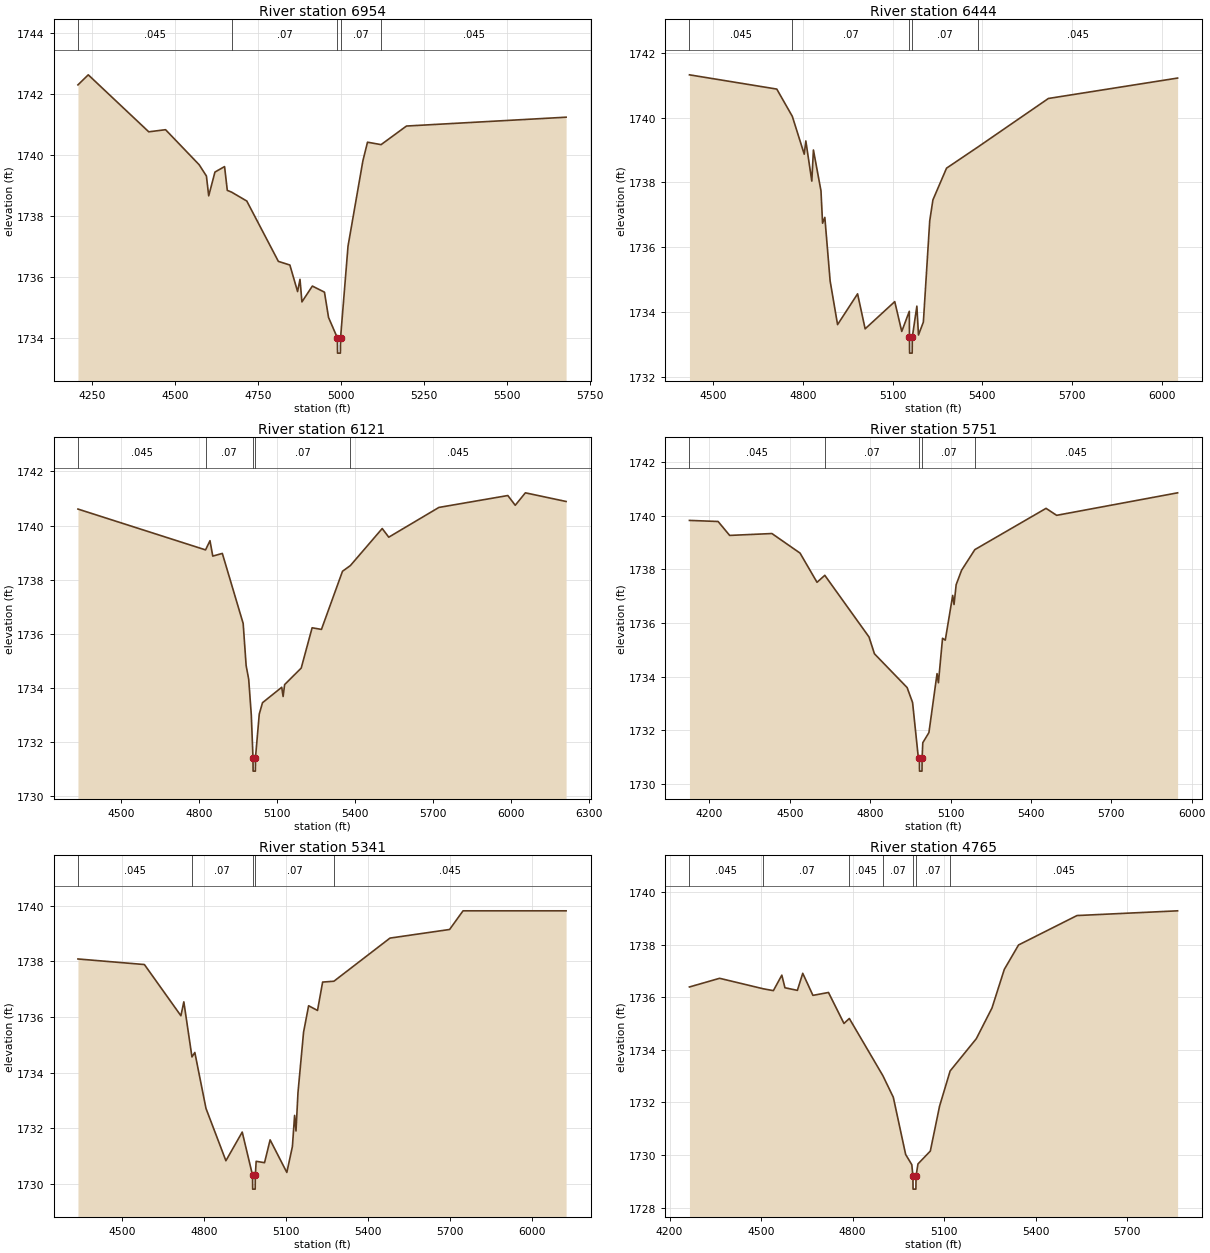
Type RM Length L Ch R = 1,6954,510,510,510
BEGIN DESCRIPTION:
Mapping XS 73d9362c
END DESCRIPTION:
XS GIS Cut Line= 4
      1492484.25      6924613.34      1492876.60      6924550.84
      1493435.63      6924224.45      1493584.92      6923825.18
#Sta/Elev= 30
  4206.4 1742.29  4237.5 1742.62  4419.8 1740.75  4470.4 1740.82  4571.7 1739.67
  4593.5 1739.30  4600.4 1738.65  4619.2 1739.43  4648.2 1739.61  4656.4 1738.83
  4669.6 1738.77  4715.1 1738.48  4810.3 1736.50  4845.0 1736.38  4868.2 1735.51
  4875.5 1735.91  4881.3 1735.17  4912.7 1735.69  4949.2 1735.49  4961.5 1734.66
  4988.1 1733.99  4988.6 1733.49  4997.2 1733.49  4997.7 1733.99  5020.2 1737.00
  5065.0 1739.80  5078.9 1740.41  5119.8 1740.33  5196.3 1740.94  5677.3 1741.23
#Mann=5,-1,0
  4206.4   0.045       0  4669.6    0.07       0  4988.1    0.07       0
  4997.7    0.07       0  5119.8   0.045       0
Bank Sta=4988.1,4997.7
Exp/Cntr=0.3,0.1

Type RM Length L Ch R = 1,6444,323,323,323
BEGIN DESCRIPTION:
Mapping XS 83170cf2
END DESCRIPTION:
XS GIS Cut Line= 4
      1492650.89      6925089.06      1492817.57      6924870.29
      1493334.93      6924682.79      1493657.13      6923941.40
#Sta/Elev= 30
  4419.9 1741.32  4712.2 1740.88  4764.1 1740.04  4804.1 1738.87  4809.4 1739.28
  4829.4 1738.04  4834.8 1739.00  4860.1 1737.74  4865.4 1736.74  4873.0 1736.92
  4890.7 1734.96  4915.6 1733.61  4982.6 1734.56  5007.9 1733.48  5107.0 1734.32
  5130.4 1733.40  5155.7 1734.02  5156.2 1733.23  5156.7 1732.73  5165.3 1732.73
  5165.8 1733.23  5181.0 1734.18  5186.4 1733.29  5202.8 1733.69  5224.0 1736.81
  5234.7 1737.46  5280.4 1738.44  5385.0 1739.09  5621.2 1740.59  6053.6 1741.22
#Mann=5,-1,0
  4419.9   0.045       0  4764.1    0.07       0  5156.2    0.07       0
  5165.8    0.07       0  5385.0   0.045       0
Bank Sta=5156.2,5165.8
Exp/Cntr=0.3,0.1

Type RM Length L Ch R = 1,6121,370,370,370
BEGIN DESCRIPTION:
Mapping XS 9a164fe1
END DESCRIPTION:
XS GIS Cut Line= 4
      1492928.69      6925523.06      1493196.05      6925269.59
      1493525.91      6924363.34      1493750.82      6923865.08
#Sta/Elev= 30
  4332.5 1740.61  4823.8 1739.10  4840.9 1739.44  4851.6 1738.87  4888.4 1738.97
  4968.6 1736.38  4980.1 1734.82  4989.9 1734.32  5000.0 1732.99  5006.4 1731.42
  5006.9 1730.92  5015.6 1730.92  5016.1 1731.42  5030.6 1733.03  5043.1 1733.45
  5117.1 1734.02  5122.4 1733.68  5128.3 1734.12  5192.1 1734.73  5234.1 1736.22
  5270.0 1736.16  5351.1 1738.31  5381.4 1738.52  5504.0 1739.89  5529.2 1739.57
  5722.2 1740.67  5987.6 1741.11  6016.2 1740.75  6055.2 1741.21  6212.0 1740.89
#Mann=5,-1,0
  4332.5   0.045       0  4823.8    0.07       0  5006.4    0.07       0
  5016.1    0.07       0  5381.4   0.045       0
Bank Sta=5006.4,5016.1
Exp/Cntr=0.3,0.1

Type RM Length L Ch R = 1,5751,410,410,410
BEGIN DESCRIPTION:
Mapping XS f61b5857
END DESCRIPTION:
XS GIS Cut Line= 4
      1493383.55      6925679.29      1493543.27      6925203.62
      1493702.99      6924328.62      1493813.96      6923912.49
#Sta/Elev= 30
  4125.7 1739.83  4232.6 1739.79  4275.8 1739.27  4433.5 1739.34  4538.5 1738.61
  4601.8 1737.52  4630.9 1737.78  4795.8 1735.48  4816.2 1734.85  4938.1 1733.59
  4958.5 1733.03  4978.8 1731.08  4983.9 1730.97  4984.4 1730.47  4993.6 1730.47
  4994.1 1730.97  4996.6 1731.53  5019.5 1731.91  5049.8 1734.11  5054.9 1733.77
  5070.3 1735.43  5080.5 1735.36  5108.2 1737.03  5113.2 1736.69  5121.1 1737.43
  5141.4 1737.97  5190.9 1738.74  5456.6 1740.28  5496.2 1740.02  5947.6 1740.86
#Mann=5,-1,0
  4125.7   0.045       0  4630.9    0.07       0  4983.9    0.07       0
  4994.1    0.07       0  5190.9   0.045       0
Bank Sta=4983.9,4994.1
Exp/Cntr=0.3,0.1

Type RM Length L Ch R = 1,5341,576,576,576
BEGIN DESCRIPTION:
Mapping XS e7603176
END DESCRIPTION:
XS GIS Cut Line= 4
      1493703.00      6925644.55      1493786.32      6925290.42
      1493970.35      6924359.87      1494071.04      6923898.09
#Sta/Elev= 30
  4339.7 1738.08  4582.7 1737.88  4716.2 1736.04  4726.9 1736.54  4756.6 1734.56
  4767.1 1734.72  4807.9 1732.71  4880.7 1730.83  4940.4 1731.86  4978.1 1730.31
  4978.6 1729.81  4987.8 1729.81  4988.3 1730.31  4991.4 1730.81  5022.0 1730.76
  5042.4 1731.58  5103.5 1730.41  5123.9 1731.34  5131.9 1732.46  5137.0 1731.90
  5144.3 1733.28  5164.7 1735.45  5183.2 1736.40  5215.7 1736.23  5234.4 1737.25
  5275.6 1737.28  5480.7 1738.83  5698.7 1739.14  5747.8 1739.81  6124.7 1739.81
#Mann=5,-1,0
  4339.7   0.045       0  4756.6    0.07       0  4978.1    0.07       0
  4988.3    0.07       0  5275.6   0.045       0
Bank Sta=4978.1,4988.3
Exp/Cntr=0.3,0.1

Type RM Length L Ch R = 1,4765,527,527,527
BEGIN DESCRIPTION:
Mapping XS 4079a840
END DESCRIPTION:
XS GIS Cut Line= 4
      1494275.90      6925484.90      1494369.66      6925021.33
      1494265.49      6924323.41      1494380.04      6923917.26
#Sta/Elev= 30
  4265.3 1736.40  4364.2 1736.73  4507.6 1736.33  4540.5 1736.26  4568.2 1736.85
  4578.4 1736.37  4619.2 1736.27  4636.8 1736.92  4670.2 1736.08  4721.2 1736.19
  4772.0 1735.01  4789.5 1735.20  4899.6 1733.02  4933.7 1732.20  4974.2 1730.02
  4994.4 1729.63  4998.0 1729.20  4998.5 1728.70  5007.8 1728.70  5008.3 1729.20
  5014.6 1729.66  5055.1 1730.15  5085.4 1731.86  5120.0 1733.20  5205.9 1734.43
  5257.3 1735.60  5297.7 1737.07  5344.4 1738.00  5536.0 1739.12  5865.9 1739.30
#Mann=7,-1,0
  4265.3   0.045       0  4507.6    0.07       0  4789.5   0.045       0
  4899.6    0.07       0  4998.0    0.07       0  5008.3    0.07       0
  5120.0   0.045       0
Bank Sta=4998,5008.3
Exp/Cntr=0.3,0.1

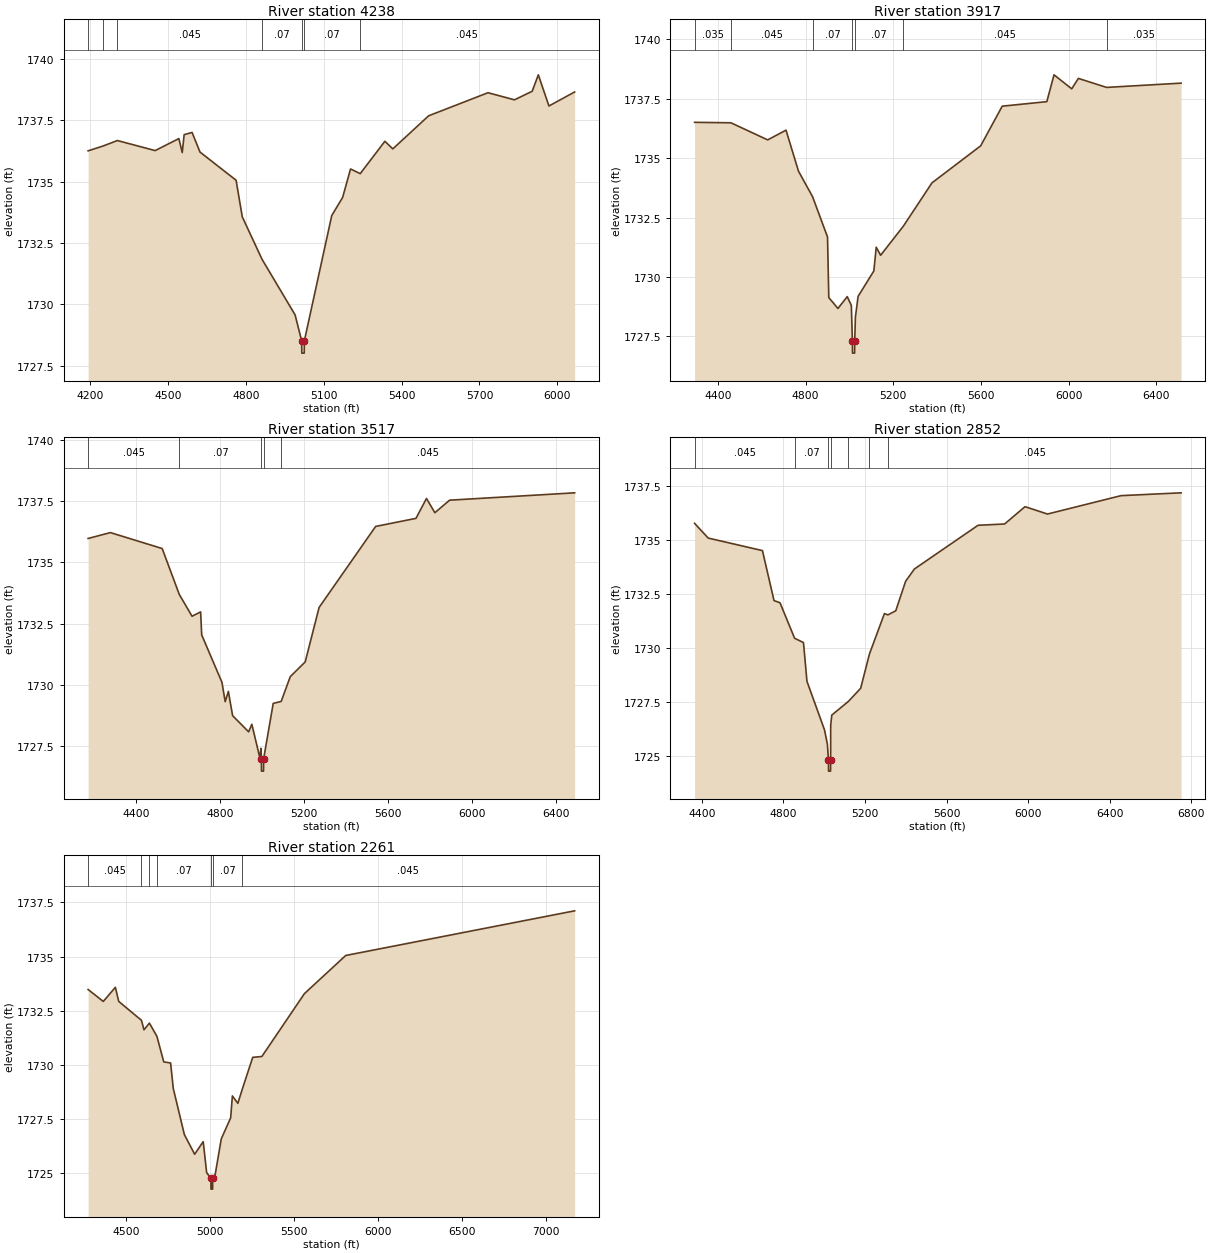
Type RM Length L Ch R = 1,4238,321,321,321
BEGIN DESCRIPTION:
Mapping XS 8ac151c4
END DESCRIPTION:
XS GIS Cut Line= 4
      1494489.45      6925562.97      1494546.74      6925224.45
      1494755.07      6924141.12      1494843.23      6923721.08
#Sta/Elev= 30
  4191.2 1736.26  4249.7 1736.46  4304.0 1736.68  4449.8 1736.27  4541.1 1736.76
  4554.1 1736.19  4561.5 1736.92  4592.0 1737.01  4622.6 1736.21  4761.8 1735.06
  4785.5 1733.57  4861.6 1731.84  4989.2 1729.57  5014.6 1728.51  5015.1 1728.01
  5024.4 1728.01  5024.9 1728.51  5130.5 1733.62  5172.5 1734.36  5203.0 1735.52
  5240.3 1735.33  5335.4 1736.65  5365.9 1736.34  5504.2 1737.69  5732.9 1738.63
  5835.0 1738.34  5903.3 1738.69  5927.0 1739.36  5967.9 1738.09  6066.9 1738.66
#Mann=7,-1,0
  4191.2   0.045       0  4249.7    0.07       0  4304.0   0.045       0
  4861.6    0.07       0  5014.6    0.07       0  5024.9    0.07       0
  5240.3   0.045       0
Bank Sta=5014.6,5024.9
Exp/Cntr=0.3,0.1

Type RM Length L Ch R = 1,3917,400,400,400
BEGIN DESCRIPTION:
Mapping XS fb323b22
END DESCRIPTION:
XS GIS Cut Line= 4
      1494713.42      6925562.96      1494838.41      6925203.62
      1495130.07      6923964.04      1495192.49      6923402.28
#Sta/Elev= 30
  4293.5 1736.51  4459.2 1736.49  4627.0 1735.77  4710.5 1736.18  4767.6 1734.45
  4831.6 1733.38  4899.9 1731.68  4905.7 1729.13  4947.4 1728.67  4989.8 1729.17
  5008.5 1728.80  5013.4 1727.29  5013.9 1726.79  5023.5 1726.79  5024.0 1727.29
  5027.0 1728.30  5039.3 1729.18  5111.2 1730.25  5122.1 1731.25  5142.0 1730.91
  5245.3 1732.13  5376.3 1733.96  5598.5 1735.52  5696.8 1737.19  5900.2 1737.38
  5933.0 1738.51  6013.8 1737.92  6044.0 1738.36  6172.7 1737.98  6512.6 1738.16
#Mann=7,-1,0
  4293.5   0.035       0  4459.2   0.045       0  4831.6    0.07       0
  5013.4    0.07       0  5024.0    0.07       0  5245.3   0.045       0
  6172.7   0.035       0
Bank Sta=5013.4,5024
Exp/Cntr=0.3,0.1

Type RM Length L Ch R = 1,3517,665,665,665
BEGIN DESCRIPTION:
Mapping XS 4bbc5610
END DESCRIPTION:
XS GIS Cut Line= 4
      1494973.82      6925516.12      1495182.16      6925260.91
      1495390.49      6924115.08      1495400.90      6923292.61
#Sta/Elev= 30
  4173.0 1735.97  4279.0 1736.21  4525.7 1735.56  4607.1 1733.69  4668.0 1732.80
  4708.7 1732.98  4713.9 1732.04  4810.3 1730.11  4825.7 1729.32  4840.8 1729.74
  4861.1 1728.75  4937.5 1728.09  4952.6 1728.40  4990.9 1727.03  4995.9 1727.42
  4998.1 1726.99  4998.6 1726.49  5008.3 1726.49  5008.8 1726.99  5054.4 1729.25
  5092.3 1729.33  5135.6 1730.34  5206.7 1730.94  5272.9 1733.16  5542.1 1736.46
  5734.2 1736.79  5784.2 1737.60  5824.2 1737.02  5894.2 1737.53  6489.6 1737.83
#Mann=5,-1,0
  4173.0   0.045       0  4607.1    0.07       0  4998.1    0.07       0
  5008.8    0.07       0  5092.3   0.045       0
Bank Sta=4998.1,5008.8
Exp/Cntr=0.3,0.1

Type RM Length L Ch R = 1,2852,591,591,591
BEGIN DESCRIPTION:
Mapping XS eac966ed
END DESCRIPTION:
XS GIS Cut Line= 4
      1495260.27      6925505.71      1495604.03      6925266.12
      1495843.62      6924615.08      1495760.28      6923344.25
#Sta/Elev= 30
  4364.1 1735.77  4430.8 1735.09  4697.0 1734.51  4753.7 1732.20  4783.1 1732.10
  4854.7 1730.46  4898.3 1730.26  4915.3 1728.47  5001.3 1726.23  5015.5 1725.57
  5020.8 1724.82  5021.3 1724.32  5031.0 1724.32  5031.5 1724.82  5031.8 1726.45
  5037.1 1726.91  5118.5 1727.54  5178.8 1728.15  5221.7 1729.73  5295.3 1731.60
  5312.4 1731.54  5350.9 1731.73  5399.1 1733.09  5442.3 1733.66  5754.5 1735.68
  5884.8 1735.74  5985.0 1736.54  6095.2 1736.20  6456.0 1737.05  6750.4 1737.18
#Mann=7,-1,0
  4364.1   0.045       0  4854.7    0.07       0  5020.8    0.07       0
  5031.5    0.07       0  5118.5   0.035       0  5221.7    0.07       0
  5312.4   0.045       0
Bank Sta=5020.8,5031.5
Exp/Cntr=0.3,0.1

Type RM Length L Ch R = 1,2261,0,0,0
BEGIN DESCRIPTION:
NC Unknown Stream 12 1.0
END DESCRIPTION:
XS GIS Cut Line= 4
      1495713.37      6925411.96      1496093.62      6925375.49
      1496281.12      6924500.49      1495921.73      6922917.12
#Sta/Elev= 30
  4271.4 1733.48  4361.8 1732.93  4433.8 1733.58  4453.9 1732.93  4589.3 1732.06
  4604.6 1731.62  4636.8 1731.93  4681.6 1731.32  4722.4 1730.14  4763.3 1730.09
  4779.0 1728.92  4845.1 1726.79  4906.5 1725.88  4957.6 1726.46  4978.1 1725.03
  5003.4 1724.77  5003.9 1724.27  5013.6 1724.27  5014.1 1724.77  5029.2 1724.95
  5065.3 1726.59  5121.3 1727.56  5131.5 1728.57  5164.2 1728.23  5189.2 1728.85
  5252.8 1730.35  5307.4 1730.39  5561.1 1733.29  5807.2 1735.05  7171.9 1737.11
#Mann=7,-1,0
  4271.4   0.045       0  4589.3    0.07       0  4636.8   0.045       0
  4681.6    0.07       0  5003.4    0.07       0  5014.1    0.07       0
  5189.2   0.045       0
Bank Sta=5003.4,5014.1
Exp/Cntr=0.3,0.1

Chan Stop Cuts=-1