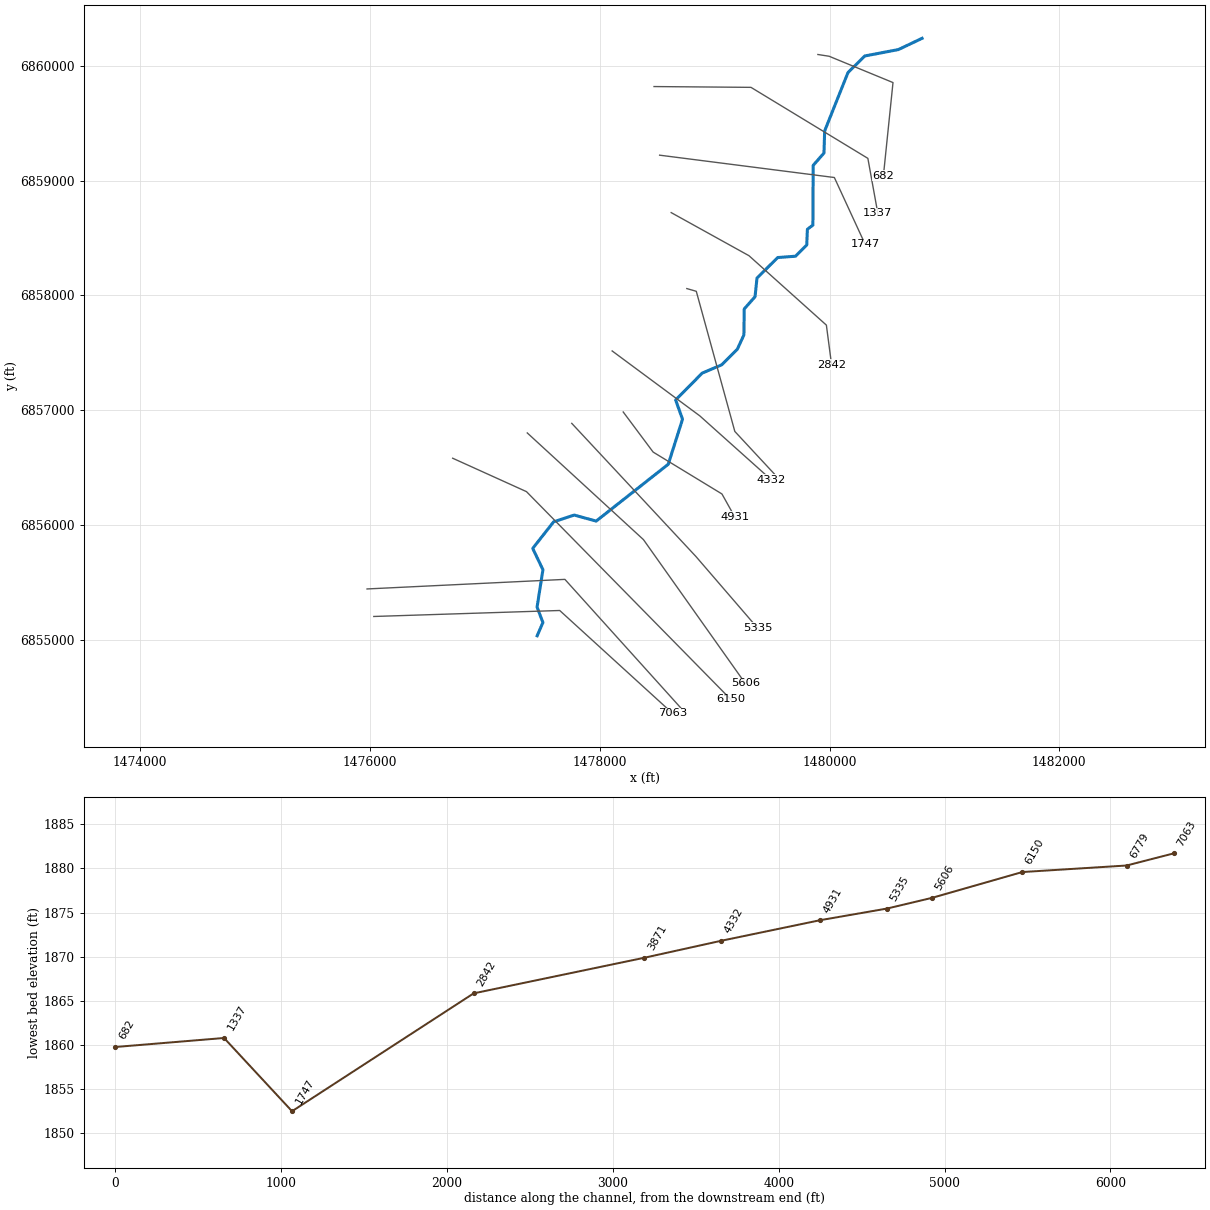
--- NC Unknown Stream 13.prj (project) ---

Proj Title=NC Unknown Stream 13 Base Level Engineering
Current Plan=p01
Default Exp/Contr=0.3,0.1
English Units
Geom File=g01
Flow File=f01
Plan File=p01
BEGIN DESCRIPTION:
NC Unknown Stream 13
END DESCRIPTION:

--- NC Unknown Stream 13.p01 (plan) ---

Plan Title=Multiple Run
Short Identifier=Multiple
Geom File=g01
Flow File=f01
Subcritical Flow
K Sum by GR= 0
Std Step Tol= 0.01
Critical Tol= 0.01
Num of Std Step Trials= 20
Max Error Tol= 0.3
Flow Tol Ratio= 0.001
Split Flow NTrial= 30
Split Flow Tol= 0.02
Split Flow Ratio= 0.02
Log Output Level= 0
Friction Slope Method= 1
Unsteady Friction Slope Method= 2
Unsteady Bridges Friction Slope Method= 1
Parabolic Critical Depth
Global Vel Dist=  1 , 1 , 1
Global Log Level= 0
CheckData=True
Encroach Param= -1, 0, 0, 0
BEGIN DESCRIPTION:
Multiple Run
END DESCRIPTION:

--- NC Unknown Stream 13.f01 (steady flow) ---

Flow Title=Multiple
Number of Profiles=7
Profile Names=10-year,25-year,50-year,1pct_min,100-year,1pct_plu,500-year
River Rch & RM= NC Unknown Strea,Reach-1,7063
     199     269     325     196     390     779     568
River Rch & RM= NC Unknown Strea,Reach-1,2842
     305     425     523     320     639    1275     964
Boundary for River Rch & Prof#=NC Unknown Strea,Reach-1,1
Up Type=0
Dn Type=3
Dn Slope=0.001
Boundary for River Rch & Prof#=NC Unknown Strea,Reach-1,2
Up Type=0
Dn Type=3
Dn Slope=0.001
Boundary for River Rch & Prof#=NC Unknown Strea,Reach-1,3
Up Type=0
Dn Type=3
Dn Slope=0.001
Boundary for River Rch & Prof#=NC Unknown Strea,Reach-1,4
Up Type=0
Dn Type=3
Dn Slope=0.001
Boundary for River Rch & Prof#=NC Unknown Strea,Reach-1,5
Up Type=0
Dn Type=3
Dn Slope=0.001
Boundary for River Rch & Prof#=NC Unknown Strea,Reach-1,6
Up Type=0
Dn Type=3
Dn Slope=0.001
Boundary for River Rch & Prof#=NC Unknown Strea,Reach-1,7
Up Type=0
Dn Type=3
Dn Slope=0.001

--- NC Unknown Stream 13.g01 (geometry) ---

Geom Title=Existing Conditions

River Reach=NC Unknown Strea,Reach-1
Reach XY= 30
      1477455.00      6855038.00      1477505.02      6855153.38
      1477454.19      6855288.00      1477505.21      6855613.09
      1477416.31      6855798.40      1477598.64      6856030.01
      1477777.37      6856088.57      1477968.65      6856036.23
      1478595.98      6856530.82      1478720.27      6856922.86
      1478660.08      6857090.30      1478891.79      6857324.38
      1479061.06      6857396.14      1479197.12      6857531.87
      1479254.50      6857656.68      1479257.07      6857882.14
      1479351.44      6857989.47      1479368.37      6858151.32
      1479548.81      6858330.18      1479703.54      6858341.54
      1479801.46      6858439.46      1479806.98      6858576.03
      1479855.12      6858612.88      1479857.07      6859132.14
      1479951.45      6859239.47      1479957.24      6859432.07
      1480160.52      6859940.43      1480306.50      6860084.39
      1480599.06      6860140.27      1480805.00      6860238.00

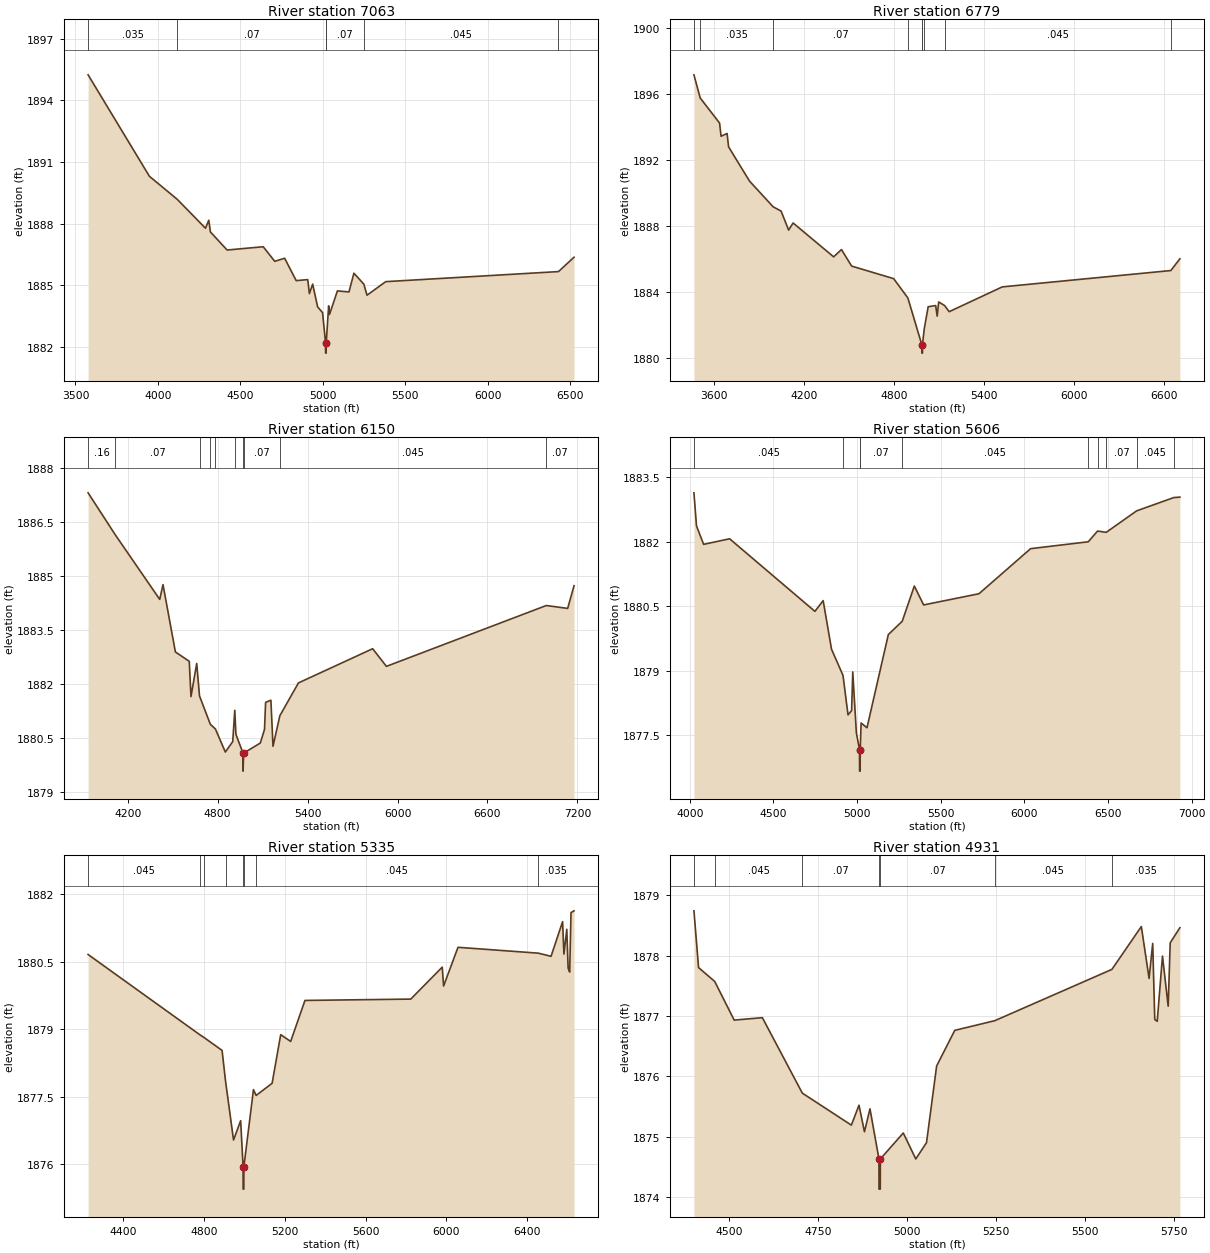
Type RM Length L Ch R = 1,7063,284,284,284
BEGIN DESCRIPTION:
NC Unknown Stream 13 5.0
END DESCRIPTION:
XS GIS Cut Line= 3
      1476033.16      6855205.99      1477651.26      6855258.08
      1478633.51      6854362.60
#Sta/Elev= 30
  3576.8 1895.24  3948.8 1890.30  4117.5 1889.18  4289.0 1887.77  4309.0 1888.16
  4319.0 1887.59  4420.2 1886.71  4639.2 1886.87  4709.2 1886.16  4769.3 1886.31
  4839.3 1885.22  4909.3 1885.27  4919.3 1884.59  4939.3 1885.05  4969.4 1883.94
  4999.4 1883.66  5017.4 1882.19  5017.6 1881.69  5021.1 1881.69  5021.4 1882.19
  5036.2 1883.99  5041.2 1883.57  5089.4 1884.72  5159.5 1884.67  5189.5 1885.58
  5249.6 1885.05  5268.9 1884.51  5382.4 1885.17  6430.6 1885.66  6524.9 1886.36
#Mann=6,-1,0
  3576.8   0.035       0  4117.5    0.07       0  5017.4    0.07       0
  5021.4    0.07       0  5249.6   0.045       0  6430.6    0.07       0
Bank Sta=5017.4,5021.4
Exp/Cntr=0.3,0.1

Type RM Length L Ch R = 1,6779,629,629,629
BEGIN DESCRIPTION:
NC Unknown Stream 13 4.0
END DESCRIPTION:
XS GIS Cut Line= 3
      1475974.17      6855445.57      1477696.40      6855528.91
      1478712.62      6854401.71
#Sta/Elev= 30
  3467.3 1897.17  3509.0 1895.77  3638.3 1894.25  3648.3 1893.45  3688.4 1893.62
  3698.4 1892.81  3838.6 1890.73  3995.5 1889.18  4048.8 1888.92  4098.9 1887.77
  4128.9 1888.20  4399.2 1886.15  4451.4 1886.59  4519.4 1885.59  4799.7 1884.83
  4894.5 1883.66  4987.9 1880.82  4988.2 1880.32  4991.7 1880.32  4991.9 1880.82
  5003.4 1881.77  5030.0 1883.13  5080.0 1883.20  5090.0 1882.56  5100.0 1883.42
  5139.7 1883.20  5170.1 1882.83  5524.1 1884.33  6648.5 1885.32  6709.2 1886.03
#Mann=9,-1,0
  3467.3    0.07       0  3509.0   0.035       0  3995.5    0.07       0
  4894.5    0.16       0  4987.9    0.07       0  4991.9    0.16       0
  5003.4    0.07       0  5139.7   0.045       0  6648.5    0.07       0
Bank Sta=4987.9,4991.9
Exp/Cntr=0.3,0.1

Type RM Length L Ch R = 1,6150,544,544,544
BEGIN DESCRIPTION:
NC Unknown Stream 13 3.0
END DESCRIPTION:
XS GIS Cut Line= 3
      1476719.61      6856583.35      1477362.00      6856292.54
      1479140.58      6854483.59
#Sta/Elev= 30
  3935.5 1887.31  4117.6 1886.14  4413.4 1884.35  4435.4 1884.76  4518.0 1882.89
  4610.4 1882.63  4622.0 1881.65  4660.2 1882.57  4678.8 1881.67  4751.2 1880.88
  4785.0 1880.75  4851.1 1880.11  4900.5 1880.40  4914.1 1881.27  4921.8 1880.60
  4969.2 1880.08  4969.5 1879.58  4973.2 1880.08  5084.4 1880.36  5112.6 1880.74
  5119.8 1881.49  5155.1 1881.55  5169.2 1880.27  5214.9 1881.12  5338.9 1882.03
  5834.0 1882.98  5925.8 1882.49  6992.6 1884.18  7135.1 1884.10  7177.5 1884.73
#Mann=10,-1,0
  3935.5    0.16       0  4117.6    0.07       0  4678.8   0.045       0
  4751.2    0.07       0  4785.0   0.045       0  4914.1    0.07       0
  4969.2    0.07       0  4973.2    0.07       0  5214.9   0.045       0
  6992.6    0.07       0
Bank Sta=4969.2,4973.2
Exp/Cntr=0.3,0.1

Type RM Length L Ch R = 1,5606,271,271,271
BEGIN DESCRIPTION:
NC Unknown Stream 13 2.0
END DESCRIPTION:
XS GIS Cut Line= 3
      1477368.91      6856803.56      1478380.23      6855874.71
      1479265.67      6854624.68
#Sta/Elev= 30
  4024.8 1883.14  4040.1 1882.37  4082.7 1881.94  4238.1 1882.07  4748.0 1880.38
  4797.3 1880.63  4847.2 1879.50  4915.8 1878.89  4945.9 1877.97  4967.4 1878.07
  4974.2 1878.97  4995.8 1877.55  5014.8 1877.16  5015.0 1876.66  5018.5 1876.66
  5018.8 1877.16  5024.2 1877.78  5059.3 1877.67  5186.9 1879.84  5270.0 1880.15
  5342.3 1880.97  5397.8 1880.53  5728.6 1880.79  6037.5 1881.84  6382.1 1882.00
  6437.7 1882.25  6489.6 1882.22  6671.2 1882.72  6893.6 1883.03  6929.8 1883.04
#Mann=10,-1,0
  4024.8   0.045       0  4915.8    0.07       0  5014.8    0.07       0
  5018.8    0.07       0  5270.0   0.045       0  6382.1    0.07       0
  6437.7   0.045       0  6489.6    0.07       0  6671.2   0.045       0
  6893.6    0.07       0
Bank Sta=5014.8,5018.8
Exp/Cntr=0.3,0.1

Type RM Length L Ch R = 1,5335,404,404,404
BEGIN DESCRIPTION:
Mapping XS 857c6b5e
END DESCRIPTION:
XS GIS Cut Line= 3
      1477756.12      6856886.84      1478836.83      6855728.01
      1479373.26      6855105.64
#Sta/Elev= 30
  4226.3 1880.66  4779.1 1878.88  4799.5 1878.82  4889.8 1878.53  4906.9 1877.85
  4946.5 1876.54  4981.7 1876.97  4993.8 1875.95  4994.1 1875.45  4997.6 1875.45
  4997.8 1875.95  5045.2 1877.66  5058.3 1877.53  5137.5 1877.80  5180.0 1878.88
  5229.4 1878.73  5300.2 1879.64  5824.1 1879.67  5980.0 1880.38  5986.6 1879.96
  6057.9 1880.82  6455.2 1880.69  6518.7 1880.62  6575.8 1881.39  6582.4 1880.67
  6596.6 1881.22  6603.2 1880.36  6610.9 1880.27  6617.5 1881.59  6632.5 1881.63
#Mann=8,-1,0
  4226.3   0.045       0  4779.1    0.07       0  4799.5   0.045       0
  4906.9    0.07       0  4993.8    0.07       0  4997.8    0.07       0
  5058.3   0.045       0  6455.2   0.035       0
Bank Sta=4993.8,4997.8
Exp/Cntr=0.3,0.1

Type RM Length L Ch R = 1,4931,599,599,599
BEGIN DESCRIPTION:
Mapping XS 092f2fbe
END DESCRIPTION:
XS GIS Cut Line= 4
      1478203.99      6856985.85      1478464.43      6856636.87
      1479063.39      6856272.28      1479175.02      6856072.39
#Sta/Elev= 30
  4400.7 1878.74  4413.7 1877.80  4459.1 1877.57  4513.8 1876.93  4593.0 1876.97
  4705.3 1875.72  4843.1 1875.19  4864.5 1875.52  4879.9 1875.08  4895.4 1875.46
  4920.6 1874.63  4920.8 1874.13  4924.3 1874.13  4924.6 1874.63  4989.0 1875.06
  5024.1 1874.63  5054.3 1874.90  5082.7 1876.17  5133.7 1876.76  5246.1 1876.92
  5575.3 1877.77  5658.0 1878.48  5679.7 1877.62  5689.9 1878.20  5695.7 1876.94
  5702.6 1876.91  5717.4 1877.99  5733.4 1877.16  5739.1 1878.21  5766.3 1878.46
#Mann=7,-1,0
  4400.7    0.07       0  4459.1   0.045       0  4705.3    0.07       0
  4920.6    0.07       0  4924.6    0.07       0  5246.1   0.045       0
  5575.3   0.035       0
Bank Sta=4920.6,4924.6
Exp/Cntr=0.3,0.1

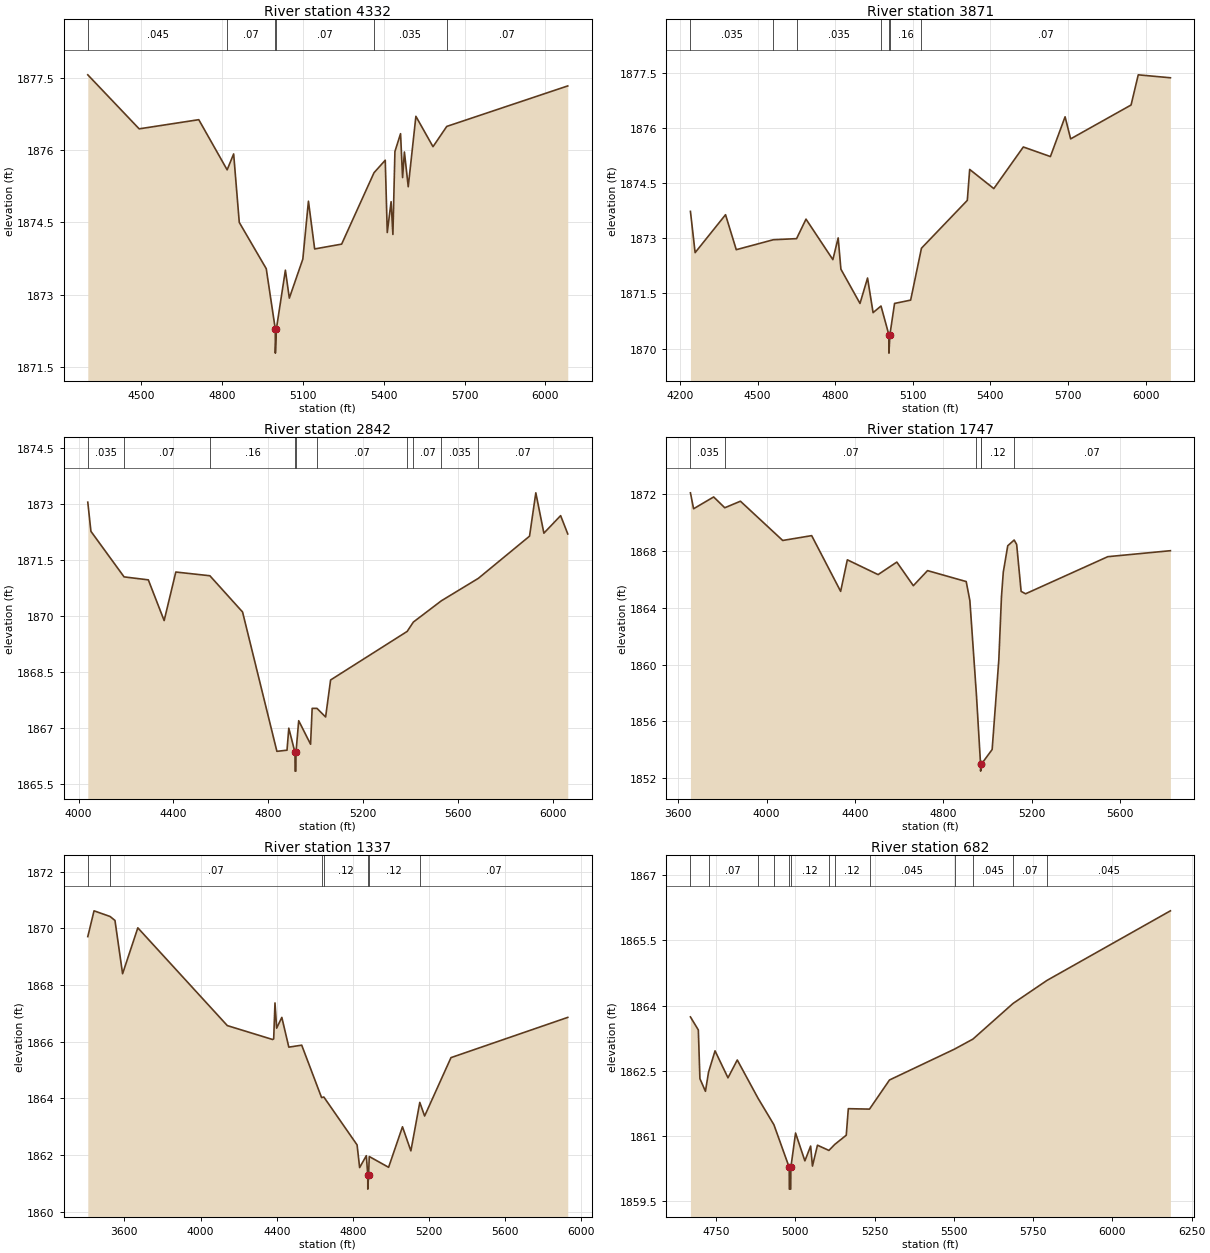
Type RM Length L Ch R = 1,4332,461,461,461
BEGIN DESCRIPTION:
Mapping XS 29de8428
END DESCRIPTION:
XS GIS Cut Line= 3
      1478107.70      6857517.05      1478870.68      6856951.97
      1479490.24      6856397.49
#Sta/Elev= 30
  4302.1 1877.56  4492.7 1876.44  4713.9 1876.63  4819.2 1875.59  4843.3 1875.92
  4864.2 1874.50  4964.3 1873.54  4997.8 1872.29  4998.1 1871.79  5001.8 1872.29
  5035.3 1873.51  5049.9 1872.93  5100.0 1873.74  5120.8 1874.94  5143.9 1873.95
  5244.0 1874.05  5364.1 1875.53  5405.8 1875.79  5413.3 1874.29  5427.5 1874.93
  5434.2 1874.25  5441.7 1875.97  5462.6 1876.34  5470.1 1875.43  5476.9 1875.96
  5491.1 1875.24  5519.5 1876.70  5583.0 1876.07  5634.0 1876.49  6083.0 1877.33
#Mann=6,-1,0
  4302.1   0.045       0  4819.2    0.07       0  4997.8    0.07       0
  5001.8    0.07       0  5364.1   0.035       0  5634.0    0.07       0
Bank Sta=4997.8,5001.8
Exp/Cntr=0.3,0.1

Type RM Length L Ch R = 1,3871,1029,1029,1029
BEGIN DESCRIPTION:
Mapping XS 497395cc
END DESCRIPTION:
XS GIS Cut Line= 4
      1478757.64      6858059.98      1478839.95      6858036.25
      1479175.37      6856816.55      1479519.10      6856446.78
#Sta/Elev= 30
  4240.7 1873.73  4258.8 1872.61  4376.4 1873.64  4417.9 1872.69  4561.1 1872.96
  4651.0 1872.99  4687.5 1873.52  4791.3 1872.42  4811.8 1873.01  4822.4 1872.16
  4896.2 1871.23  4925.4 1871.92  4946.8 1870.98  4977.4 1871.16  5007.8 1870.38
  5008.1 1869.88  5011.8 1870.38  5029.8 1871.23  5092.0 1871.32  5133.8 1872.73
  5311.1 1874.03  5320.2 1874.87  5413.5 1874.35  5527.6 1875.48  5632.3 1875.22
  5689.0 1876.30  5710.5 1875.70  5944.1 1876.62  5971.9 1877.44  6096.2 1877.36
#Mann=7,-1,0
  4240.7   0.035       0  4561.1    0.16       0  4651.0   0.035       0
  4977.4    0.16       0  5007.8    0.07       0  5011.8    0.16       0
  5133.8    0.07       0
Bank Sta=5007.8,5011.8
Exp/Cntr=0.3,0.1

Type RM Length L Ch R = 1,2842,1095,1095,1095
BEGIN DESCRIPTION:
Mapping XS 378496f4
END DESCRIPTION:
XS GIS Cut Line= 4
      1478621.53      6858721.07      1479298.63      6858346.07
      1479972.24      6857741.90      1480017.39      6857398.12
#Sta/Elev= 30
  4038.8 1873.05  4052.0 1872.27  4191.9 1871.05  4294.3 1870.97  4361.1 1869.88
  4410.3 1871.18  4554.1 1871.08  4692.0 1870.11  4836.9 1866.38  4879.6 1866.41
  4887.1 1867.00  4913.3 1866.35  4913.6 1865.85  4917.1 1865.85  4917.4 1866.35
  4928.9 1867.20  4979.0 1866.57  4985.7 1867.53  5006.0 1867.53  5042.5 1867.30
  5063.5 1868.29  5386.7 1869.59  5412.7 1869.84  5531.0 1870.41  5686.9 1871.01
  5903.1 1872.14  5929.6 1873.30  5963.7 1872.22  6034.3 1872.69  6064.4 1872.20
#Mann=10,-1,0
  4038.8   0.035       0  4191.9    0.07       0  4554.1    0.16       0
  4913.3    0.07       0  4917.4    0.16       0  5006.0    0.07       0
  5386.7   0.035       0  5412.7    0.07       0  5531.0   0.035       0
  5686.9    0.07       0
Bank Sta=4913.3,4917.4
Exp/Cntr=0.3,0.1

Type RM Length L Ch R = 1,1747,410,410,410
BEGIN DESCRIPTION:
Mapping XS 0c30f773
END DESCRIPTION:
XS GIS Cut Line= 3
      1478520.82      6859221.07      1480041.69      6859026.62
      1480309.06      6858446.74
#Sta/Elev= 30
  3655.1 1872.08  3669.4 1870.96  3760.1 1871.79  3810.5 1871.03  3881.3 1871.49
  4072.6 1868.73  4203.7 1869.07  4334.8 1865.15  4365.0 1867.37  4504.2 1866.33
  4589.0 1867.21  4663.7 1865.55  4727.9 1866.61  4902.9 1865.84  4919.5 1864.50
  4949.2 1857.87  4967.8 1853.01  4968.1 1852.51  4971.9 1853.01  5020.3 1854.03
  5050.5 1860.34  5062.4 1864.76  5070.7 1866.50  5090.9 1868.36  5119.9 1868.76
  5131.2 1868.45  5151.4 1865.15  5171.5 1864.98  5543.6 1867.59  5826.9 1868.01
#Mann=6,-1,0
  3655.1   0.035       0  3810.5    0.07       0  4949.2    0.12       0
  4967.8    0.07       0  4971.9    0.12       0  5119.9    0.07       0
Bank Sta=4967.8,4971.9
Exp/Cntr=0.3,0.1

Type RM Length L Ch R = 1,1337,655,655,655
BEGIN DESCRIPTION:
Mapping XS a7bacf3c
END DESCRIPTION:
XS GIS Cut Line= 4
      1478472.21      6859818.29      1479315.99      6859811.34
      1480333.35      6859193.29      1480420.08      6858714.58
#Sta/Elev= 30
  3407.9 1869.71  3440.7 1870.62  3525.0 1870.42  3550.7 1870.28  3590.7 1868.40
  3670.7 1870.02  4140.7 1866.57  4378.4 1866.08  4384.2 1866.10  4391.0 1867.37
  4399.7 1866.48  4426.9 1866.86  4463.7 1865.81  4531.4 1865.88  4635.7 1864.03
  4647.6 1864.05  4822.2 1862.36  4835.6 1861.56  4870.7 1861.98  4878.3 1861.30
  4878.5 1860.80  4882.4 1861.30  4886.2 1861.95  4987.7 1861.57  5060.6 1863.00
  5104.7 1862.15  5151.5 1863.86  5176.9 1863.38  5315.3 1865.44  5928.6 1866.86
#Mann=7,-1,0
  3407.9   0.035       0  3525.0    0.07       0  4635.7    0.16       0
  4647.6    0.12       0  4878.3    0.07       0  4882.4    0.12       0
  5151.5    0.07       0
Bank Sta=4878.3,4882.4
Exp/Cntr=0.3,0.1

Type RM Length L Ch R = 1,682,0,0,0
BEGIN DESCRIPTION:
NC Unknown Stream 13 1.0
END DESCRIPTION:
XS GIS Cut Line= 4
      1479898.31      6860097.28      1479996.16      6860082.02
      1480552.10      6859853.01      1480468.77      6859043.99
#Sta/Elev= 30
  4669.2 1863.74  4694.1 1863.44  4699.1 1862.32  4716.5 1862.03  4726.3 1862.47
  4746.8 1862.96  4787.6 1862.34  4816.9 1862.75  4882.4 1861.87  4932.5 1861.26
  4980.7 1860.28  4981.1 1859.78  4985.5 1859.78  4985.9 1860.28  5000.7 1861.07
  5030.1 1860.43  5048.2 1860.77  5054.0 1860.31  5069.8 1860.79  5105.9 1860.67
  5124.6 1860.81  5160.6 1861.02  5167.1 1861.63  5233.9 1861.62  5296.9 1862.29
  5502.1 1863.00  5560.0 1863.23  5686.5 1864.05  5793.6 1864.58  6182.8 1866.18
#Mann=13,-1,0
  4669.2   0.035       0  4726.3    0.07       0  4882.4   0.035       0
  4932.5    0.12       0  4980.7    0.07       0  4985.9    0.12       0
  5105.9    0.07       0  5124.6    0.12       0  5233.9   0.045       0
  5502.1    0.07       0  5560.0   0.045       0  5686.5    0.07       0
  5793.6   0.045       0
Bank Sta=4980.7,4985.9
Exp/Cntr=0.3,0.1

Chan Stop Cuts=-1