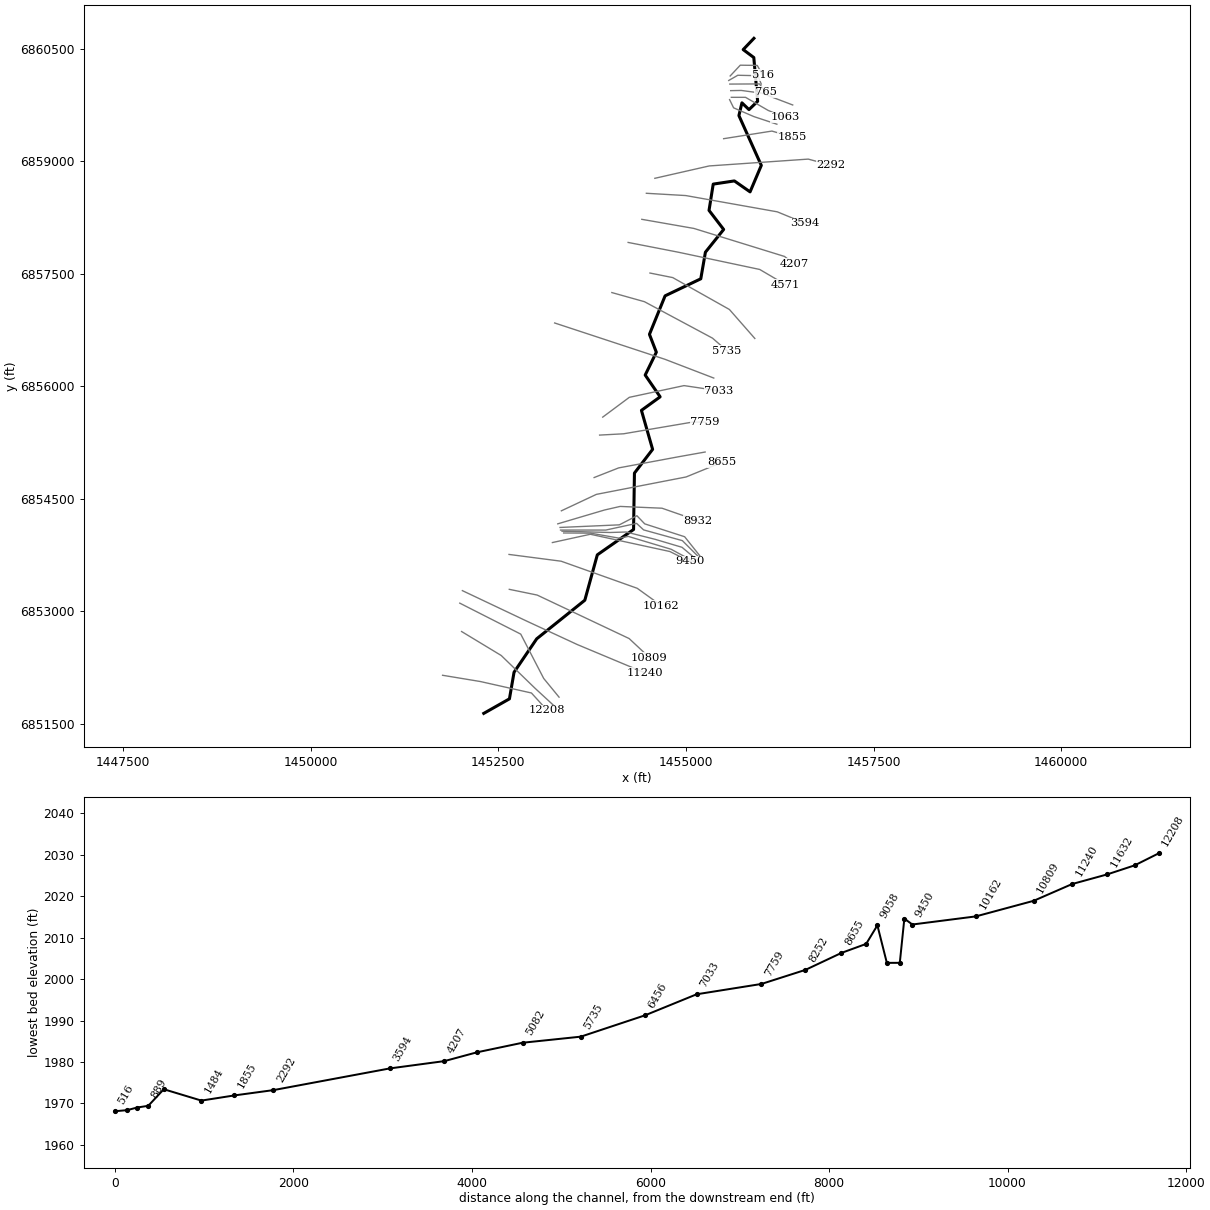
--- NC Unknown Stream 14.prj (project) ---

Proj Title=NC Unknown Stream 14 Base Level Engineering
Current Plan=p01
Default Exp/Contr=0.3,0.1
English Units
Geom File=g01
Flow File=f01
Plan File=p01
Y Axis Title=Elevation
X Axis Title(PF)=Main Channel Distance
X Axis Title(XS)=Station
BEGIN DESCRIPTION:
NC Unknown Stream 14
END DESCRIPTION:
DSS Export Rating Curves= 0
DSS Export Rating Curve Sorted= 0
DSS Export Volume Flow Curves= 0
DXF OffsetX= 0
DXF OffsetY= 0
DXF ScaleX= 1
DXF ScaleY= 10

--- NC Unknown Stream 14.p01 (plan) ---

Plan Title=Multiple Run
Short Identifier=Multiple
Geom File=g01
Flow File=f01
Subcritical Flow
K Sum by GR= 0
Std Step Tol= 0.01
Critical Tol= 0.01
Num of Std Step Trials= 20
Max Error Tol= 0.3
Flow Tol Ratio= 0.001
Split Flow NTrial= 30
Split Flow Tol= 0.02
Split Flow Ratio= 0.02
Log Output Level= 0
Friction Slope Method= 1
Unsteady Friction Slope Method= 2
Unsteady Bridges Friction Slope Method= 1
Parabolic Critical Depth
Global Vel Dist=  1 , 1 , 1
Global Log Level= 0
CheckData=True
Encroach Param= -1, 0, 0, 0
BEGIN DESCRIPTION:
Multiple Run
END DESCRIPTION:

--- NC Unknown Stream 14.f01 (steady flow) ---

Flow Title=Multiple
Number of Profiles=7
Profile Names=10-year,25-year,50-year,1pct_min,100-year,1pct_plu,500-year
River Rch & RM= NC Unknown Strea,Reach-1,12208
     373     540     685     432     862    1720    1382
River Rch & RM= NC Unknown Strea,Reach-1,10162
     369     531     670     420     839    1673    1330
River Rch & RM= NC Unknown Strea,Reach-1,5735
     614     902    1153     732    1461    2915    2374
Boundary for River Rch & Prof#=NC Unknown Strea,Reach-1,1
Up Type=0
Dn Type=3
Dn Slope=0.005
Boundary for River Rch & Prof#=NC Unknown Strea,Reach-1,2
Up Type=0
Dn Type=3
Dn Slope=0.005
Boundary for River Rch & Prof#=NC Unknown Strea,Reach-1,3
Up Type=0
Dn Type=3
Dn Slope=0.005
Boundary for River Rch & Prof#=NC Unknown Strea,Reach-1,4
Up Type=0
Dn Type=3
Dn Slope=0.005
Boundary for River Rch & Prof#=NC Unknown Strea,Reach-1,5
Up Type=0
Dn Type=3
Dn Slope=0.005
Boundary for River Rch & Prof#=NC Unknown Strea,Reach-1,6
Up Type=0
Dn Type=3
Dn Slope=0.005
Boundary for River Rch & Prof#=NC Unknown Strea,Reach-1,7
Up Type=0
Dn Type=3
Dn Slope=0.005

--- NC Unknown Stream 14.g01 (geometry) ---

Geom Title=Existing Conditions
Program Version=4.10

River Reach=NC Unknown Strea,Reach-1
Reach XY= 30
        1452305.        6851638.      1452647.14      6851831.83
      1452708.54      6852186.54      1453010.59      6852632.39
      1453651.45       6853146.5      1453818.21      6853751.73
      1454301.25      6854089.55      1454312.79      6854841.43
      1454554.94      6855158.03      1454405.97      6855677.73
      1454655.38      6855858.37      1454456.08      6856148.55
      1454604.63      6856453.27      1454512.74      6856691.34
       1454721.4      6857204.82      1455196.87      6857431.92
      1455258.54      6857786.54       1455501.7      6858089.76
      1455306.79      6858344.11      1455362.62       6858694.5
      1455644.57      6858736.95      1455853.63      6858591.01
      1456003.39      6858944.04      1455704.94      6859607.99
      1455745.24       6859778.1      1455839.18      6859687.71
      1455954.41      6859798.61      1455903.46      6860382.15
      1455761.98      6860487.79        1455905.        6860638.

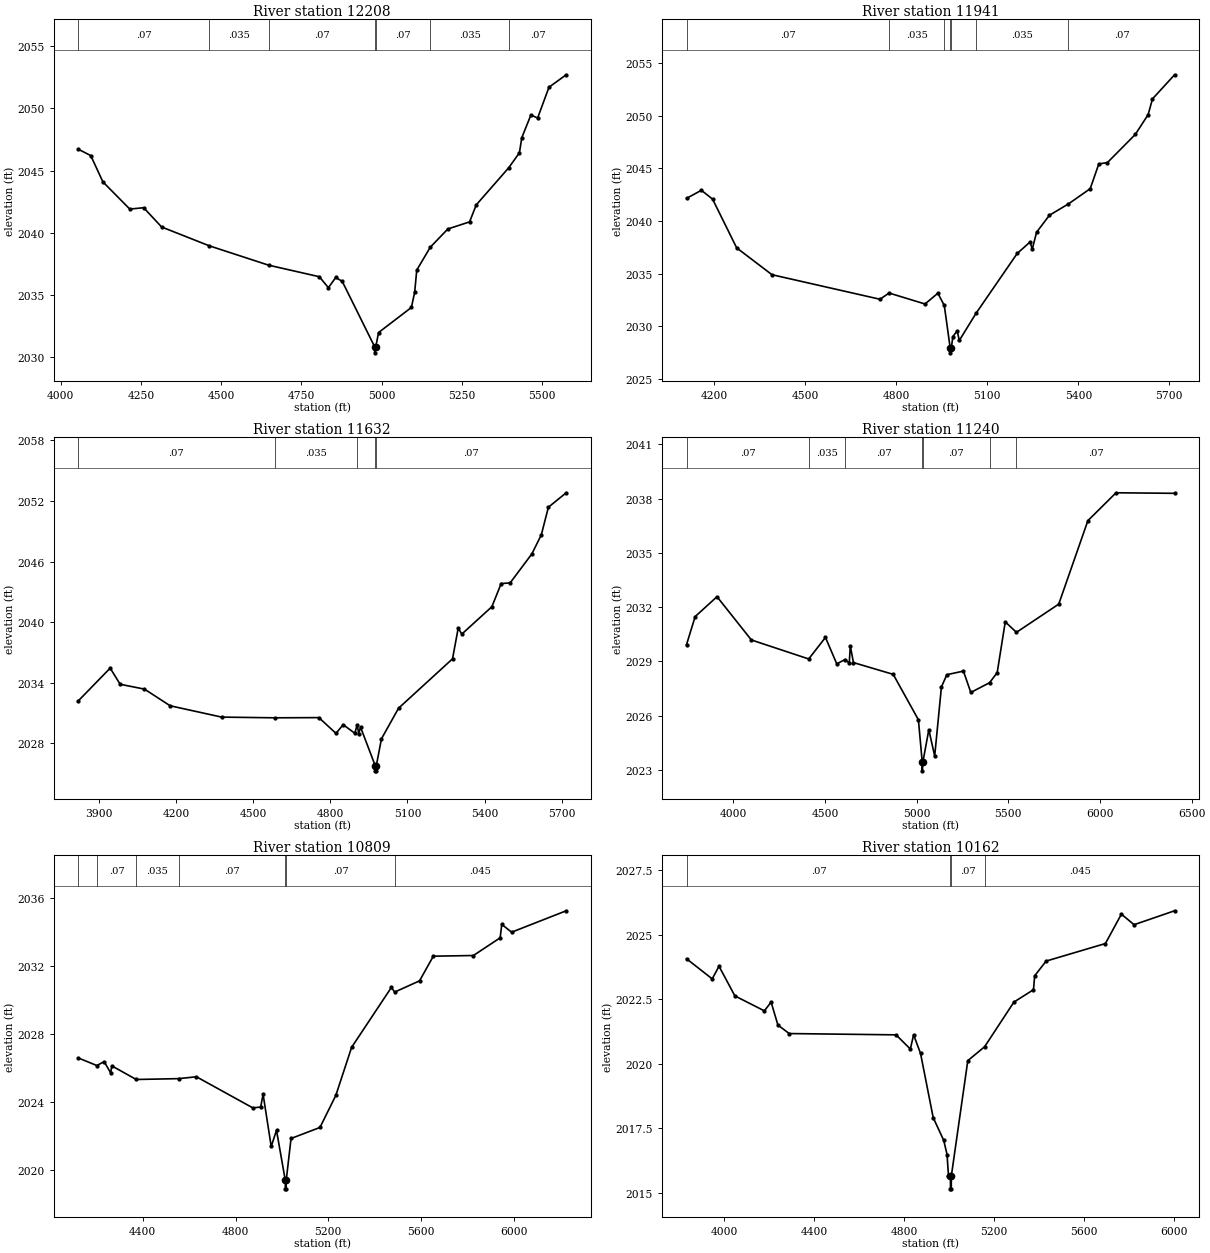
Type RM Length L Ch R = 1 ,12208   ,267,267,267
BEGIN DESCRIPTION:
Mapping XS 54761f6e
END DESCRIPTION:
XS GIS Cut Line= 4
      1451756.12      6852145.95      1452259.59      6852062.62
      1452940.15      6851909.84      1453150.99      6851678.26
#Sta/Elev= 30
  4054.5 2046.73  4093.9 2046.21  4131.6  2044.1  4215.5 2041.91  4258.7 2042.02
  4314.7 2040.47  4462.8 2038.96    4648  2037.4  4806.1 2036.47  4834.4 2035.59
  4857.3 2036.41  4877.7 2036.09  4978.3 2030.85  4978.6 2030.35  4982.3 2030.85
  4990.6 2031.98  5093.1    2034  5103.3 2035.23  5109.7    2037  5151.8 2038.84
  5206.6 2040.31  5274.3 2040.88  5295.2 2042.25  5396.6 2045.24  5429.7 2046.44
  5437.1 2047.65  5465.5 2049.48  5486.4 2049.23  5521.8 2051.71  5575.5 2052.71
#Mann= 7 ,-1 , 0
  4054.5     .07       0  4462.8    .035       0    4648     .07       0
  4978.3     .07       0  4982.3     .07       0  5151.8    .035       0
  5396.6     .07       0
Bank Sta=4978.3,4982.3
XS Rating Curve= 0 ,0
Exp/Cntr=0.3,0.1

Type RM Length L Ch R = 1 ,11941   ,309,309,309
BEGIN DESCRIPTION:
Mapping XS 7a9ef477
END DESCRIPTION:
XS GIS Cut Line= 4
      1452009.57       6852729.3      1452537.37      6852409.84
      1452988.76      6851972.34      1453256.09      6851725.84
#Sta/Elev= 30
  4108.1 2042.14  4157.1 2042.91    4194 2042.07  4273.5 2037.44  4389.9 2034.89
  4745.9 2032.56    4776 2033.15  4894.4 2032.11  4936.8 2033.13    4958 2031.97
  4977.3 2027.97  4977.5 2027.47  4981.3 2027.97  4986.4 2029.02  5000.4 2029.55
  5007.6 2028.65  5062.8 2031.23  5198.4 2036.91  5240.9    2038  5248.1 2037.32
  5262.2 2038.92  5304.7 2040.54  5367.1 2041.61  5439.1 2043.06  5467.4 2045.41
  5495.8 2045.54  5587.7 2048.21  5630.2  2050.1  5644.4 2051.59  5717.3 2053.88
#Mann= 7 ,-1 , 0
  4108.1     .07       0    4776    .035       0    4958     .07       0
  4977.3     .07       0  4981.3     .07       0  5062.8    .035       0
  5367.1     .07       0
Bank Sta=4977.3,4981.3
XS Rating Curve= 0 ,0
Exp/Cntr=0.3,0.1

Type RM Length L Ch R = 1 ,11632   ,392,392,392
BEGIN DESCRIPTION:
Mapping XS 290c57cf
END DESCRIPTION:
XS GIS Cut Line= 4
       1451985.3      6853107.75      1452797.79      6852694.56
      1453103.34      6852104.28       1453308.2      6851854.29
#Sta/Elev= 30
  3818.3 2032.19    3943 2035.45  3981.9 2033.85  4076.5 2033.37  4176.6 2031.72
  4376.8  2030.6    4583 2030.53  4755.2 2030.55  4821.7 2028.99  4849.8 2029.85
  4894.9    2029  4904.4 2029.85  4910.2 2028.96  4917.4  2029.6  4974.6 2025.78
  4974.9 2025.28  4978.4 2025.28  4978.6 2025.78  4998.7 2028.45  5065.2 2031.48
  5275.3 2036.37  5297.4 2039.41  5311.5 2038.82  5428.5 2041.53  5464.5 2043.82
  5499.6 2043.89  5584.3 2046.77  5620.9 2048.65  5648.3 2051.38  5717.7 2052.81
#Mann= 5 ,-1 , 0
  3818.3     .07       0    4583    .035       0  4904.4     .07       0
  4974.6     .07       0  4978.6     .07       0
Bank Sta=4974.6,4978.6
XS Rating Curve= 0 ,0
Exp/Cntr=0.3,0.1

Type RM Length L Ch R = 1 ,11240   ,431,431,431
BEGIN DESCRIPTION:
Mapping XS 62299bb7
END DESCRIPTION:
XS GIS Cut Line= 4
      1452020.05       6853274.4      1452884.59       6852864.7
      1453551.26      6852555.67      1454447.12      6852180.66
#Sta/Elev= 30
  3744.2 2029.93  3791.3 2031.48  3910.5 2032.58    4098 2030.19  4410.8 2029.14
  4502.2 2030.33  4563.9 2028.87  4609.3 2029.11  4632.1 2028.91  4637.7 2029.86
  4654.9 2028.94  4871.8 2028.29  5009.3 2025.78    5030 2023.46  5030.3 2022.96
    5034 2023.46  5066.1 2025.23  5098.1 2023.78  5134.8 2027.59  5164.3 2028.27
  5254.9 2028.47  5295.2 2027.29  5397.9 2027.83  5439.2 2028.39  5483.1 2031.19
  5544.1 2030.61  5774.9 2032.17  5933.9 2036.78  6087.4 2038.32  6406.9 2038.29
#Mann= 7 ,-1 , 0
  3744.2     .07       0  4410.8    .035       0  4609.3     .07       0
    5030     .07       0    5034     .07       0  5397.9    .035       0
  5544.1     .07       0
Bank Sta=5030,5034
XS Rating Curve= 0 ,0
Exp/Cntr=0.3,0.1

Type RM Length L Ch R = 1 ,10809   ,647,647,647
BEGIN DESCRIPTION:
Mapping XS e0b1d9bb
END DESCRIPTION:
XS GIS Cut Line= 4
      1452645.06      6853291.78      1453016.54       6853215.4
      1454242.23      6852635.53      1454512.53      6852382.56
#Sta/Elev= 30
    4121 2026.61  4201.7 2026.16  4233.2 2026.39  4261.3 2025.73  4266.4 2026.14
  4371.6 2025.34  4554.8 2025.39  4631.3  2025.5  4874.6 2023.67  4908.4 2023.72
  4918.9 2024.47  4953.9  2021.4  4976.7 2022.35  5014.6 2019.41  5014.9 2018.91
  5018.4 2018.91  5018.6 2019.41  5039.4 2021.87  5164.2 2022.52  5232.5  2024.4
  5300.7 2027.23  5472.1 2030.75  5486.5 2030.48  5593.7 2031.14  5653.1 2032.59
  5826.1 2032.63  5941.5 2033.67  5948.4 2034.46  5990.9    2034  6226.4 2035.26
#Mann= 7 ,-1 , 0
    4121    .035       0  4201.7     .07       0  4371.6    .035       0
  4554.8     .07       0  5014.6     .07       0  5018.6     .07       0
  5486.5    .045       0
Bank Sta=5014.6,5018.6
XS Rating Curve= 0 ,0
Exp/Cntr=0.3,0.1

Type RM Length L Ch R = 1 ,10162   ,712,712,712
BEGIN DESCRIPTION:
Mapping XS ef9b44a3
END DESCRIPTION:
XS GIS Cut Line= 4
      1452641.51      6853757.07      1453335.98      6853666.78
      1454349.87      6853305.67      1454671.43      6853074.02
#Sta/Elev= 30
  3831.7 2024.07  3946.1 2023.29  3976.4 2023.78    4047 2022.63  4178.3 2022.05
  4208.3 2022.39  4238.6  2021.5    4289 2021.17  4764.5 2021.12  4828.2 2020.57
  4842.7 2021.12  4873.6  2020.4  4929.9 2017.91  4976.8 2017.03  4991.6 2016.48
    4998 2015.65  5006.7 2015.65  5006.9 2015.15  5010.4 2015.15  5010.7 2015.65
    5084 2020.12  5158.9 2020.66  5289.2 2022.39  5376.4 2022.87  5381.7 2023.41
  5432.7 2023.98  5696.6 2024.66  5767.8  2025.8  5824.2 2025.39  6004.6 2025.93
#Mann= 4 ,-1 , 0
  3831.7     .07       0  5006.7     .07       0  5010.7     .07       0
  5158.9    .045       0
Bank Sta=5006.7,5010.7
XS Rating Curve= 0 ,0
Exp/Cntr=0.3,0.1

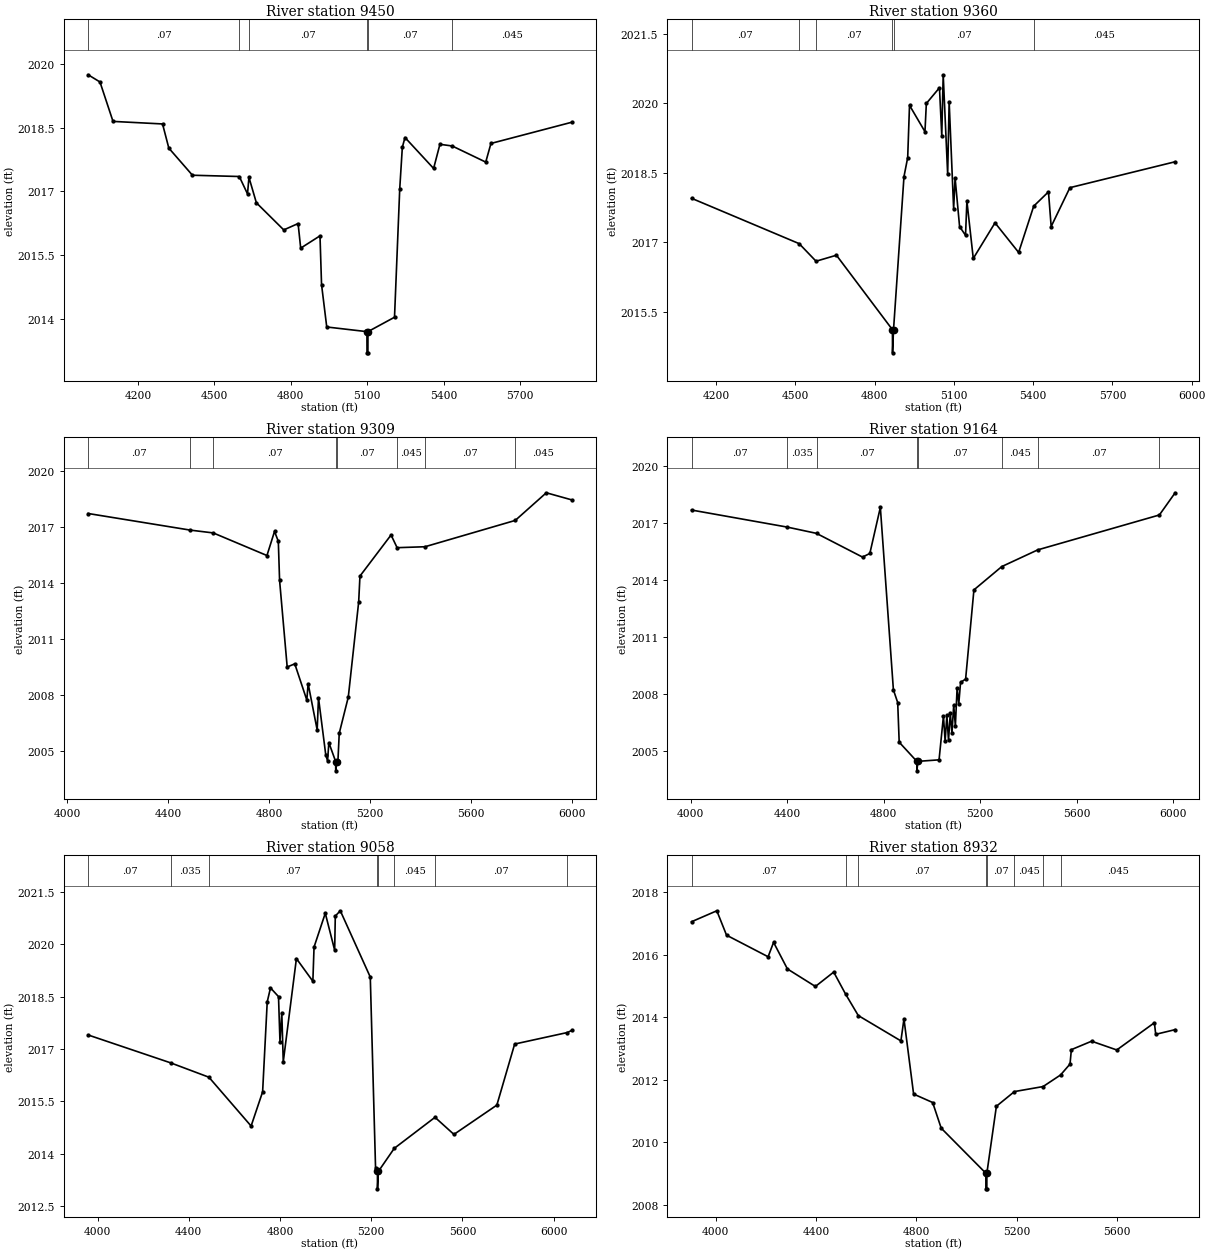
Type RM Length L Ch R = 1 ,9450    ,90,90,90
BEGIN DESCRIPTION:
Mapping XS 249cc91f
END DESCRIPTION:
XS GIS Cut Line= 4
      1453219.69      6853915.49      1453725.31      6854026.16
      1454784.33      6853796.12      1455050.33      6853663.13
#Sta/Elev= 30
  4004.4 2019.75  4050.8 2019.58    4102 2018.65  4296.5 2018.59  4321.1 2018.02
  4413.9 2017.38  4597.8 2017.35  4630.1 2016.94  4635.7 2017.33  4664.9 2016.73
  4772.4 2016.09  4828.7 2016.24  4838.9 2015.66  4914.7 2015.95  4920.8  2014.8
  4941.2  2013.8    5099 2013.69  5099.3 2013.19  5102.8 2013.19    5103 2013.69
  5207.3 2014.03  5227.8 2017.06    5238 2018.04  5248.4 2018.27  5360.8 2017.54
  5385.6 2018.11  5433.8 2018.07  5565.5 2017.69  5585.9 2018.13  5903.1 2018.63
#Mann= 6 ,-1 , 0
  4004.4     .07       0  4597.8    .035       0  4635.7     .07       0
    5099     .07       0    5103     .07       0  5433.8    .045       0
Bank Sta=5099,5103
XS Rating Curve= 0 ,0
Exp/Cntr=0.3,0.1

Type RM Length L Ch R = 1 ,9360    ,51,51,51
BEGIN DESCRIPTION:
Mapping XS bfa97b72
END DESCRIPTION:
XS GIS Cut Line= 6
      1453369.31      6854043.06      1453727.38      6854040.89
       1454111.5      6853973.61      1454230.85      6853997.49
       1454801.6      6853826.05      1455118.41      6853654.62
#Sta/Elev= 30
  4107.4 2017.95  4514.6 2016.97  4578.5 2016.59  4655.6 2016.72  4867.6 2015.11
  4867.9 2014.61  4871.7 2015.11  4911.3 2018.42  4925.3 2018.83  4932.2 2019.96
  4990.7 2019.39  4995.9    2020  5045.6 2020.34  5054.3  2019.3  5059.7 2020.62
  5076.6 2018.47  5082.2 2020.04  5099.2 2017.72  5104.7 2018.39  5121.7 2017.34
  5144.2 2017.15  5149.4 2017.89  5173.5 2016.65  5255.8 2017.42  5345.2 2016.78
  5402.2 2017.78  5458.1 2018.09  5468.3 2017.34  5539.2 2018.18  5937.5 2018.74
#Mann= 6 ,-1 , 0
  4107.4     .07       0  4514.6    .035       0  4578.5     .07       0
  4867.6     .07       0  4871.7     .07       0  5402.2    .045       0
Bank Sta=4867.6,4871.7
XS Rating Curve= 0 ,0
Exp/Cntr=0.3,0.1

Type RM Length L Ch R = 1 ,9309    ,145,145,145
BEGIN DESCRIPTION:
Mapping XS 90600a31
END DESCRIPTION:
XS GIS Cut Line= 6
      1453347.64      6854066.93      1453985.63      6854049.57
      1454202.64      6854056.08      1454588.93      6853958.42
        1454947.      6853852.09       1455166.2      6853667.61
#Sta/Elev= 30
  4083.7 2017.72  4488.2 2016.83  4578.8 2016.68  4791.3 2015.47  4821.3 2016.76
  4836.3 2016.23  4841.3 2014.14  4871.4  2009.5  4901.4 2009.67  4949.1 2007.73
  4954.3 2008.61  4990.1 2006.13  4995.3 2007.85    5024  2004.8  5031.2 2004.47
  5036.3 2005.45  5063.2 2004.44  5063.5 2003.94  5067.3 2004.44  5072.2 2004.46
  5077.4 2005.95  5113.2 2007.89  5154.3 2012.98  5159.4 2014.37  5282.5 2016.57
  5306.4 2015.89  5416.7 2015.94    5774 2017.35  5896.9 2018.83  5997.5 2018.45
#Mann= 8 ,-1 , 0
  4083.7     .07       0  4488.2    .035       0  4578.8     .07       0
  5063.2     .07       0  5067.3     .07       0  5306.4    .045       0
  5416.7     .07       0    5774    .045       0
Bank Sta=5063.2,5067.3
XS Rating Curve= 0 ,0
Exp/Cntr=0.3,0.1

Type RM Length L Ch R = 1 ,9164    ,106,106,106
BEGIN DESCRIPTION:
Mapping XS 92d90707
END DESCRIPTION:
XS GIS Cut Line= 6
      1453328.03      6854082.12      1453931.37      6854082.12
      1454341.53       6854171.1      1454434.85      6854084.29
      1454951.34      6853941.06      1455169.67      6853722.73
#Sta/Elev= 30
  4003.9 2017.68  4400.8 2016.78  4521.8 2016.45  4712.5  2015.2  4742.9 2015.39
  4786.5 2017.82  4840.6  2008.2  4858.4 2007.53  4864.6 2005.44  4937.8 2004.43
  4938.1 2003.93  4941.9 2004.43  5029.9 2004.51  5048.1 2006.82    5055  2005.5
  5062.3 2006.85  5069.1 2005.54  5076.5 2006.98  5083.3 2005.91  5090.6 2007.39
  5097.5  2006.3  5104.8 2008.31  5111.6 2007.46    5119 2008.59    5140 2008.77
  5174.4 2013.47    5290  2014.7    5439 2015.58  5943.3 2017.42  6008.6 2018.59
#Mann= 8 ,-1 , 0
  4003.9     .07       0  4400.8    .035       0  4521.8     .07       0
  4937.8     .07       0  4941.9     .07       0    5290    .045       0
    5439     .07       0  5943.3    .045       0
Bank Sta=4937.8,4941.9
XS Rating Curve= 0 ,0
Exp/Cntr=0.3,0.1

Type RM Length L Ch R = 1 ,9058    ,126,126,126
BEGIN DESCRIPTION:
Mapping XS d6b6f863
END DESCRIPTION:
XS GIS Cut Line= 6
      1453321.59      6854116.84       1454111.5      6854151.57
      1454345.87      6854273.09      1454450.04      6854164.59
      1454981.72      6853993.15      1455185.71      6853737.08
#Sta/Elev= 30
    3959  2017.4  4321.2  2016.6  4488.4 2016.19  4673.5 2014.79    4724 2015.77
  4744.2 2018.35  4758.5 2018.75  4793.7  2018.5  4800.1 2017.21  4808.1 2018.04
  4814.5 2016.63  4872.2 2019.59  4944.3 2018.94  4949.5 2019.92  4998.8 2020.89
  5039.9 2019.83  5042.7 2020.81  5064.7 2020.96  5196.1 2019.06  5219.2 2013.59
  5227.5 2013.49  5227.7 2012.99  5231.6 2013.49  5301.2 2014.15  5479.9 2015.04
  5562.9 2014.55  5751.1 2015.39  5829.2 2017.14    6060 2017.47  6079.4 2017.53
#Mann= 8 ,-1 , 0
    3959     .07       0  4321.2    .035       0  4488.4     .07       0
  5227.5     .07       0  5231.6     .07       0  5301.2    .045       0
  5479.9     .07       0    6060    .045       0
Bank Sta=5227.5,5231.6
XS Rating Curve= 0 ,0
Exp/Cntr=0.3,0.1

Type RM Length L Ch R = 1 ,8932    ,277,277,277
BEGIN DESCRIPTION:
Mapping XS 68664e9c
END DESCRIPTION:
XS GIS Cut Line= 5
      1453291.26      6854165.04      1453914.11      6854349.51
      1454122.44      6854397.25      1454680.17      6854373.38
      1455159.73      6854206.29
#Sta/Elev= 30
  3903.5 2017.05  4004.2  2017.4    4043 2016.62  4208.9 2015.93  4230.7 2016.39
  4285.9 2015.54  4397.6 2014.98  4470.6 2015.44  4518.4 2014.73  4568.7 2014.05
  4738.7 2013.24  4750.9 2013.94  4789.4 2011.54  4865.4 2011.27  4899.5 2010.45
  5077.6 2009.01  5077.9 2008.51  5081.5 2008.51  5081.7 2009.01  5119.7 2011.15
  5191.8 2011.62    5306 2011.78  5375.6 2012.15  5413.5  2012.5  5418.8 2012.96
  5499.6 2013.23    5600 2012.95  5750.1 2013.82  5755.4 2013.45  5832.9  2013.6
#Mann= 8 ,-1 , 0
  3903.5     .07       0  4518.4    .035       0  4568.7     .07       0
  5077.6     .07       0  5081.7     .07       0  5191.8    .045       0
    5306     .07       0  5375.6    .045       0
Bank Sta=5077.6,5081.7
XS Rating Curve= 0 ,0
Exp/Cntr=0.3,0.1

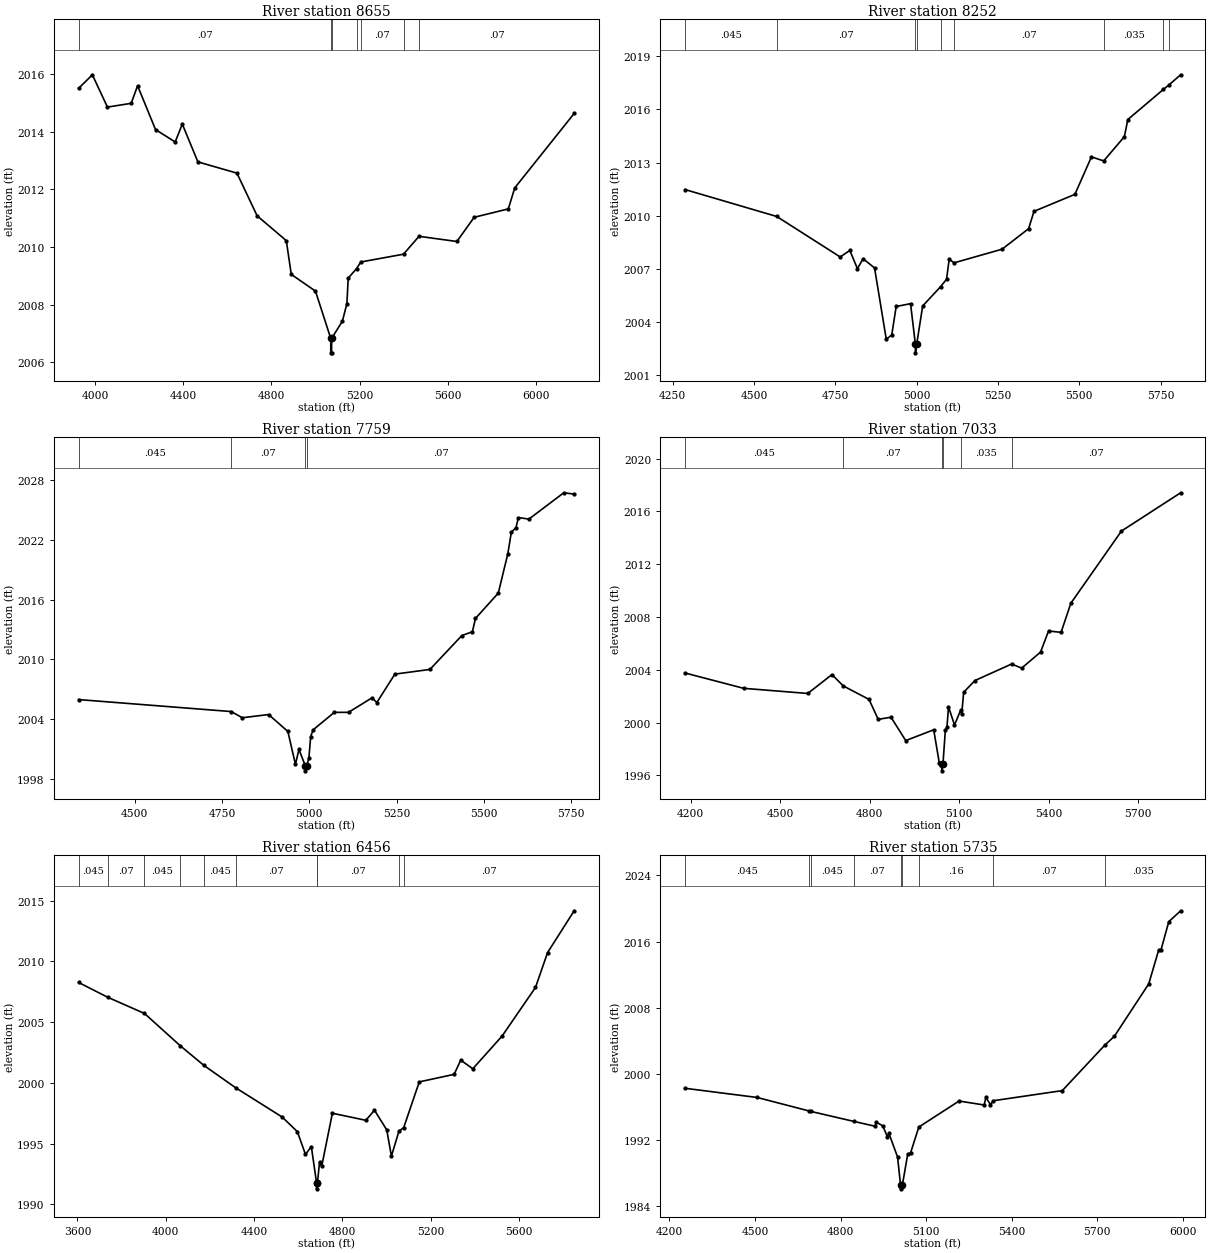
Type RM Length L Ch R = 1 ,8655    ,403,403,403
BEGIN DESCRIPTION:
Mapping XS 8596ec10
END DESCRIPTION:
XS GIS Cut Line= 4
      1453339.03      6854338.66       1453805.6      6854557.84
      1455001.35      6854790.05      1455478.77      6854985.36
#Sta/Elev= 30
  3924.8  2015.5  3987.1 2015.97  4055.5 2014.85  4163.4 2014.98  4192.4 2015.59
  4273.9 2014.07  4363.1 2013.64  4395.4 2014.26  4466.2 2012.95  4643.4 2012.56
  4735.1 2011.08  4867.5 2010.22    4890 2009.05  4999.9 2008.47  5069.2 2006.83
  5069.5 2006.33  5073.1 2006.33  5073.3 2006.83  5122.2 2007.43  5142.6 2008.04
  5148.5 2008.92  5186.3 2009.25  5205.7 2009.48  5399.5 2009.75  5469.9 2010.37
  5641.7 2010.19  5720.4 2011.03  5875.2 2011.32  5904.6 2012.05  6174.2 2014.63
#Mann= 7 ,-1 , 0
  3924.8     .07       0  5069.2     .07       0  5073.3     .07       0
  5186.3    .045       0  5205.7     .07       0  5399.5    .045       0
  5469.9     .07       0
Bank Sta=5069.2,5073.3
XS Rating Curve= 0 ,0
Exp/Cntr=0.3,0.1

Type RM Length L Ch R = 1 ,8252    ,493,493,493
BEGIN DESCRIPTION:
Mapping XS 18270e63
END DESCRIPTION:
XS GIS Cut Line= 4
       1453775.7      6854782.25      1454102.04      6854910.71
      1454904.13      6855060.01      1455254.82      6855122.51
#Sta/Elev= 30
  4288.4 2011.47  4569.9 2009.95  4765.1 2007.66  4794.7 2008.03  4817.9    2007
  4835.4 2007.56  4870.6 2007.04  4906.6 2003.01  4923.4 2003.25  4937.1 2004.86
  4981.2 2005.02    4996 2002.74  4996.3 2002.24  5000.2 2002.74  5018.5 2004.89
    5074 2005.99  5091.8  2006.4  5099.9 2007.52  5115.4 2007.33  5262.6  2008.1
    5344 2009.26  5360.6 2010.24  5486.3  2011.2  5537.1 2013.32  5574.7 2013.09
  5638.3 2014.46  5648.9 2015.43    5758 2017.13  5774.8 2017.38  5811.2 2017.96
#Mann= 9 ,-1 , 0
  4288.4    .045       0  4569.9     .07       0    4996     .07       0
  5000.2     .07       0    5074    .035       0  5115.4     .07       0
  5574.7    .035       0    5758     .07       0  5774.8     .05       0
Bank Sta=4996,5000.2
XS Rating Curve= 0 ,0
Exp/Cntr=0.3,0.1

Type RM Length L Ch R = 1 ,7759    ,726,726,726
BEGIN DESCRIPTION:
Mapping XS 5233da02
END DESCRIPTION:
XS GIS Cut Line= 4
      1453848.57      6855348.21      1454168.01      6855365.57
      1455088.15      6855521.82      1455254.82      6855521.82
#Sta/Elev= 30
  4339.1 2005.98  4776.3 2004.78  4808.1 2004.16  4883.4 2004.48  4938.6 2002.79
  4960.3 1999.49  4970.4 2000.99  4988.6 1999.34  4988.8 1998.84  4992.8 1999.34
  4998.9 2000.12    5004 2002.28    5011 2002.95  5071.8  2004.7  5112.4  2004.7
  5179.8 2006.16  5193.5 2005.68  5245.2 2008.53  5345.7    2009    5437 2012.39
  5467.4 2012.78  5476.2 2014.11  5541.6 2016.65  5568.8 2020.58    5579 2022.75
  5592.3 2023.21  5599.2 2024.22  5629.2 2024.06  5729.2  2026.7    5759 2026.57
#Mann= 4 ,-1 , 0
  4339.1    .045       0  4776.3     .07       0  4988.6     .07       0
  4992.8     .07       0
Bank Sta=4988.6,4992.8
XS Rating Curve= 0 ,0
Exp/Cntr=0.3,0.1

Type RM Length L Ch R = 1 ,7033    ,577,577,577
BEGIN DESCRIPTION:
Mapping XS 516a01fe
END DESCRIPTION:
XS GIS Cut Line= 4
       1453890.2      6855587.77       1454244.4      6855851.68
      1454973.57      6856007.93      1455441.14      6855938.66
#Sta/Elev= 30
  4181.5 2003.76  4377.6  2002.6  4592.4 2002.21  4673.5 2003.64  4711.4 2002.78
  4797.7 2001.76  4828.4 2000.25  4871.3 2000.41  4920.7 1998.64  5014.4 1999.46
  5032.9 1996.97    5041 1996.85  5041.3 1996.35  5045.3 1996.85  5053.4 1999.44
  5058.8 1999.65  5063.9  2001.2    5084 1999.82  5104.9 2000.96  5108.2 2000.63
  5114.7  2002.3  5152.5 2003.19  5275.4 2004.44    5309 2004.13  5372.2 2005.34
  5399.1 2006.94  5441.1 2006.84  5473.7 2009.04  5643.3 2014.51  5841.6 2017.41
#Mann= 6 ,-1 , 0
  4181.5    .045       0  4711.4     .07       0    5041     .07       0
  5045.3     .07       0  5104.9    .035       0  5275.4     .07       0
Bank Sta=5041,5045.3
XS Rating Curve= 0 ,0
Exp/Cntr=0.3,0.1

Type RM Length L Ch R = 1 ,6456    ,721,721,721
BEGIN DESCRIPTION:
NC Unknown Stream 14 2.0
END DESCRIPTION:
XS GIS Cut Line= 3
      1453249.66      6856842.99      1454719.76      6856358.66
      1455369.71      6856108.68
#Sta/Elev= 30
  3605.5 2008.26  3736.5 2007.05  3903.8 2005.71    4066 2003.05  4173.3 2001.43
  4317.2 1999.59  4527.1 1997.19  4595.9 1995.99  4632.9 1994.11  4659.4 1994.76
  4682.9 1991.78  4683.2 1991.28  4687.2 1991.78  4696.4 1993.47  4706.1 1993.12
  4754.7  1997.5  4906.2 1996.92  4945.4 1997.75  5000.9 1996.13    5022 1993.97
    5056 1996.02  5077.7 1996.32  5148.2 2000.08    5306  2000.7    5336 2001.87
  5390.6 2001.16  5523.2 2003.85  5674.5 2007.85  5729.2 2010.72  5849.7 2014.16
#Mann= 10 ,-1 , 0
  3605.5    .045       0  3736.5     .07       0  3903.8    .045       0
    4066     .07       0  4173.3    .045       0  4317.2     .07       0
  4682.9     .07       0  4687.2     .07       0    5056     .16       0
  5077.7     .07       0
Bank Sta=4682.9,4687.2
XS Rating Curve= 0 ,0
Exp/Cntr=0.3,0.1

Type RM Length L Ch R = 1 ,5735    ,653,653,653
BEGIN DESCRIPTION:
Mapping XS fddb91a7
END DESCRIPTION:
XS GIS Cut Line= 4
      1454011.74      6857248.39      1454445.79      6857126.85
      1455352.91      6856640.74      1455547.35      6856472.23
#Sta/Elev= 30
  4255.1 1998.27  4507.7 1997.16  4689.7 1995.53  4695.3 1995.48  4846.4 1994.27
  4920.3 1993.69  4925.9 1994.16  4947.9 1993.74  4964.1 1992.43  4969.8 1992.81
  4999.9 1989.97  5010.3 1986.62  5010.8 1986.12    5017 1986.62  5035.6 1990.32
  5045.3 1990.44  5074.5 1993.59  5215.5 1996.73  5303.7 1996.25  5309.4 1997.16
  5325.6 1996.31  5336.2 1996.77  5577.4 1997.99  5726.1 2003.47  5759.9 2004.55
  5880.5 2010.89  5915.6 2015.01    5923 2014.93  5950.7  2018.4  5992.3 2019.72
#Mann= 9 ,-1 , 0
  4255.1    .045       0  4689.7     .07       0  4695.3    .045       0
  4846.4     .07       0  5010.3     .07       0    5017     .07       0
  5074.5     .16       0  5336.2     .07       0  5726.1    .035       0
Bank Sta=5010.3,5017
XS Rating Curve= 0 ,0
Exp/Cntr=0.3,0.1

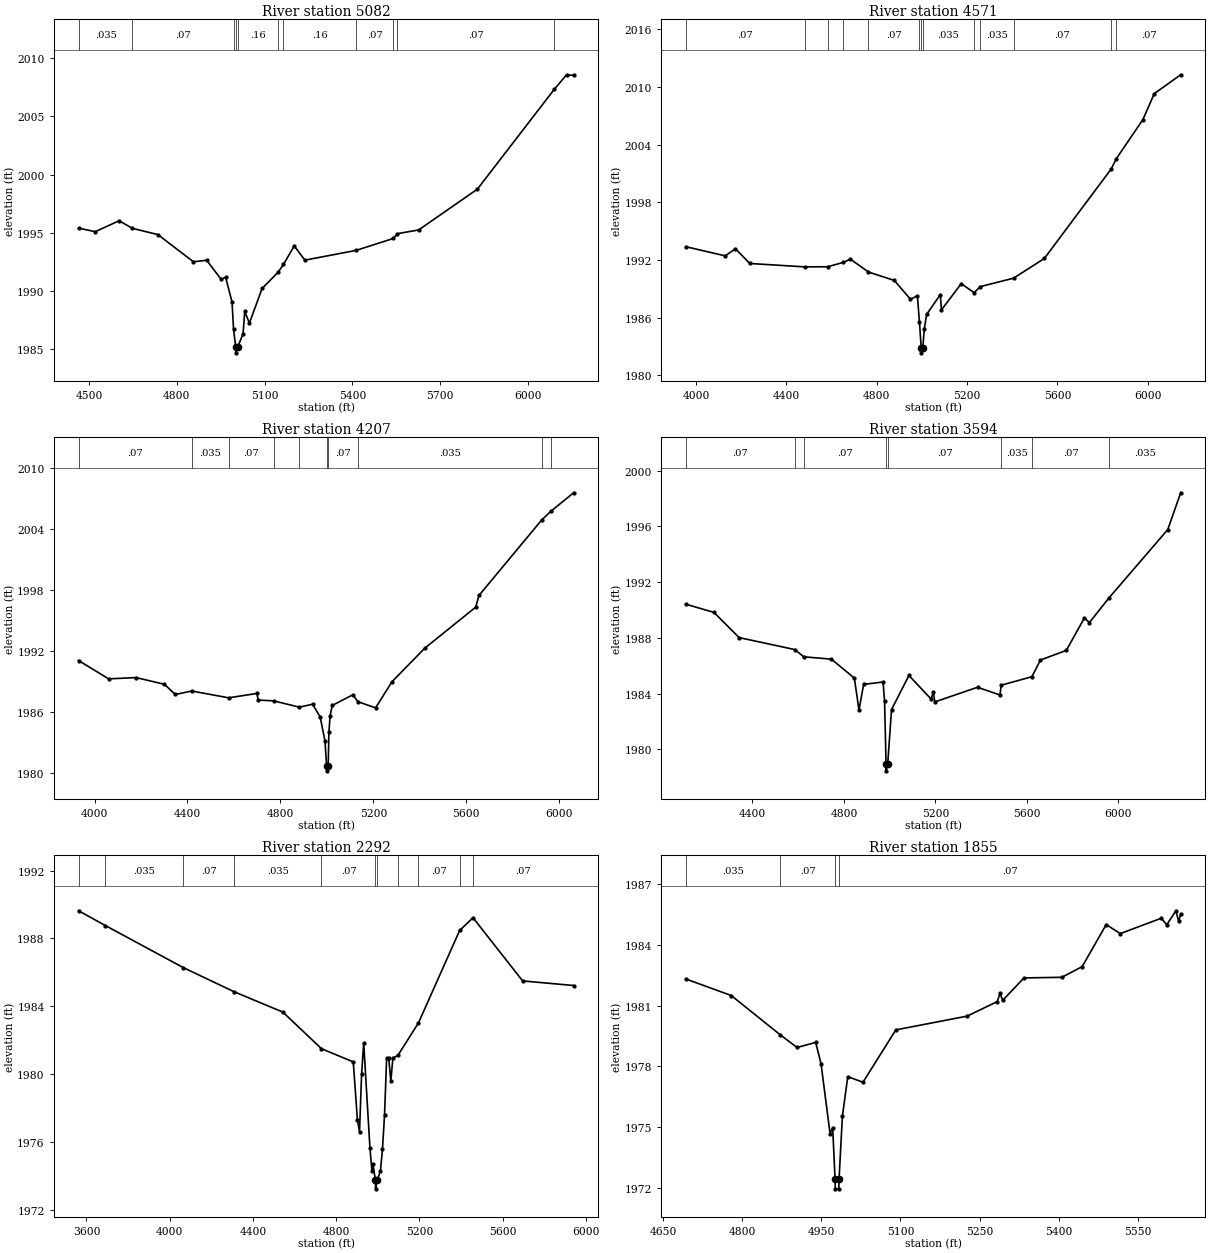
Type RM Length L Ch R = 1 ,5082    ,511,511,511
BEGIN DESCRIPTION:
Mapping XS 9f0bed6d
END DESCRIPTION:
XS GIS Cut Line= 4
      1454519.54      6857508.81       1454823.4      6857448.03
      1455578.61      6857022.69      1455917.17      6856636.38
#Sta/Elev= 30
  4464.8 1995.39  4521.4 1995.08  4602.9 1996.02  4648.7 1995.37  4735.5 1994.83
  4856.9 1992.49  4902.1 1992.62  4951.2 1990.99  4967.1 1991.14  4988.8 1989.01
  4993.9 1986.67  5001.3 1985.15  5001.8 1984.65  5008.1 1985.15  5026.4 1986.29
  5032.1 1988.21    5048 1987.21  5091.4 1990.19    5146 1991.59  5164.3 1992.26
  5201.2 1993.86  5237.3 1992.63  5412.3 1993.47  5539.8  1994.5  5553.5 1994.91
    5626 1995.23  5826.4 1998.74  6089.2 2007.34    6131 2008.59  6155.1 2008.54
#Mann= 11 ,-1 , 0
  4464.8    .035       0  4648.7     .07       0  4993.9     .16       0
  5001.3     .07       0  5008.1     .16       0    5146     .07       0
  5164.3     .16       0  5412.3     .07       0  5539.8     .16       0
  5553.5     .07       0  6089.2    .035       0
Bank Sta=5001.3,5008.1
XS Rating Curve= 0 ,0
Exp/Cntr=0.3,0.1

Type RM Length L Ch R = 1 ,4571    ,364,364,364
BEGIN DESCRIPTION:
Mapping XS d7b2662e
END DESCRIPTION:
XS GIS Cut Line= 4
      1454228.81      6857916.78      1454897.18      6857786.58
      1455982.25      6857556.54       1456329.1      6857352.77
#Sta/Elev= 30
  3953.5 1993.38    4129 1992.42  4173.8 1993.17  4237.4 1991.63  4480.6 1991.28
    4582 1991.29  4652.5 1991.75  4683.3 1992.08  4763.2 1990.74  4877.5 1989.87
  4949.1 1987.91  4979.8 1988.27  4989.1  1985.5  4996.8 1982.84  4997.3 1982.34
  5003.7 1982.84  5010.4 1984.83  5020.7 1986.34  5081.3 1988.39  5086.4 1986.81
    5174 1989.53  5230.9  1988.6    5259 1989.23  5405.7  1990.1    5542 1992.15
    5838 2001.45  5861.4 2002.54  5978.8  2006.6    6029 2009.29  6145.9 2011.25
#Mann= 13 ,-1 , 0
  3953.5     .07       0  4480.6    .035       0    4582     .07       0
  4652.5    .035       0  4763.2     .07       0  4989.1    .035       0
  4996.8     .07       0  5003.7    .035       0  5230.9     .16       0
    5259    .035       0  5405.7     .07       0    5838    .035       0
  5861.4     .07       0
Bank Sta=4996.8,5003.7
XS Rating Curve= 0 ,0
Exp/Cntr=0.3,0.1

Type RM Length L Ch R = 1 ,4207    ,613,613,613
BEGIN DESCRIPTION:
Mapping XS 5d7033e3
END DESCRIPTION:
XS GIS Cut Line= 4
      1454411.02      6858224.95      1455105.51      6858103.42
      1456312.11      6857730.15      1456441.18       6857631.2
#Sta/Elev= 30
  3931.3 1991.08  4060.4 1989.28  4179.4  1989.4  4300.8 1988.74  4347.6 1987.74
  4418.3 1988.08  4577.3 1987.41  4698.6 1987.84  4704.6 1987.19    4771 1987.11
  4881.7 1986.49  4938.2 1986.78  4970.8 1985.55  4991.7 1983.19  4998.7 1980.72
  4999.2 1980.22  5005.6 1980.72  5008.7    1984  5013.9 1985.63  5023.1 1986.66
  5111.8 1987.71  5133.4 1987.03  5209.6 1986.42  5280.1 1988.99  5421.1 1992.29
  5640.7 1996.34  5654.6 1997.49  5925.8 2004.95  5963.8 2005.77    6062  2007.6
#Mann= 10 ,-1 , 0
  3931.3     .07       0  4418.3    .035       0  4577.3     .07       0
    4771    .035       0  4881.7     .07       0  4998.7     .07       0
  5005.6     .07       0  5133.4    .035       0  5925.8     .07       0
  5963.8    .035       0
Bank Sta=4998.7,5005.6
XS Rating Curve= 0 ,0
Exp/Cntr=0.3,0.1

Type RM Length L Ch R = 1 ,3594    ,1302,1302,1302
BEGIN DESCRIPTION:
Mapping XS 310318aa
END DESCRIPTION:
XS GIS Cut Line= 4
      1454471.85      6858572.17      1454997.01      6858541.78
      1456216.63      6858324.77      1456585.37      6858172.93
#Sta/Elev= 30
  4108.4 1990.42  4231.8 1989.83  4341.9 1988.02  4585.3 1987.16  4624.6 1986.64
  4745.4 1986.47  4845.7 1985.11    4866 1982.81  4886.3 1984.66  4971.3 1984.83
  4977.7 1983.47  4984.3 1978.95  4984.8 1978.45  4991.5 1978.95  5008.2 1982.85
  5084.3  1985.3  5180.9 1983.61    5191 1984.11  5197.2  1983.4    5384 1984.45
  5482.1  1983.9  5487.6  1984.6  5621.8 1985.21  5659.2 1986.41  5772.1  1987.1
  5851.2 1989.43  5873.2  1989.1  5958.7 1990.87  6215.7 1995.78    6272 1998.42
#Mann= 8 ,-1 , 0
  4108.4     .07       0  4585.3    .035       0  4624.6     .07       0
  4984.3     .07       0  4991.5     .07       0  5487.6    .035       0
  5621.8     .07       0  5958.7    .035       0
Bank Sta=4984.3,4991.5
XS Rating Curve= 0 ,0
Exp/Cntr=0.3,0.1

Type RM Length L Ch R = 1 ,2292    ,437,437,437
BEGIN DESCRIPTION:
Mapping XS cda7e80a
END DESCRIPTION:
XS GIS Cut Line= 4
      1454584.66      6858771.81      1455309.51      6858936.75
      1456628.95       6859027.9      1456931.34      6858945.82
#Sta/Elev= 30
  3562.2 1989.63  3690.7 1988.76  4064.9 1986.28  4309.9 1984.85    4544 1983.65
  4729.7 1981.49  4882.4 1980.71  4902.5 1977.27  4912.5  1976.6  4922.5    1980
  4932.6 1981.82  4962.6 1975.63  4972.2 1974.28  4977.2 1974.67    4989 1973.72
  4989.5 1973.22  4996.5 1973.72  5012.8 1974.25  5022.8 1975.55  5032.8 1977.59
  5042.8 1980.92  5052.8 1980.96  5062.9 1979.58  5072.9 1980.94  5096.7 1981.09
  5195.7 1983.01  5393.8 1988.47  5458.1 1989.22  5696.6 1985.49  5941.5 1985.22
#Mann= 11 ,-1 , 0
  3562.2     .07       0  3690.7    .035       0  4064.9     .07       0
  4309.9    .035       0  4729.7     .07       0    4989     .07       0
  4996.5     .07       0  5096.7    .035       0  5195.7     .07       0
  5393.8    .035       0  5458.1     .07       0
Bank Sta=4989,4996.5
XS Rating Curve= 0 ,0
Exp/Cntr=0.3,0.1

Type RM Length L Ch R = 1 ,1855    ,371,371,371
BEGIN DESCRIPTION:
Mapping XS 9d70b591
END DESCRIPTION:
XS GIS Cut Line= 3
       1455501.5      6859300.03       1456144.7      6859401.59
      1456420.39      6859320.97
#Sta/Elev= 30
  4692.8 1982.32  4779.2  1981.5  4871.4 1979.57    4904 1978.93  4939.3 1979.18
  4949.4 1978.13  4966.5 1974.67  4971.5 1974.96    4976 1972.44  4976.5 1971.94
  4983.1 1971.94  4983.6 1972.44  4989.9 1975.52  5000.1 1977.49  5028.9 1977.21
  5091.2  1979.8  5226.3 1980.48  5283.5  1981.2  5288.7 1981.61  5293.8 1981.26
  5334.1 1982.37  5405.9  1982.4  5444.5 1982.93  5490.1 1985.01  5516.6 1984.56
  5594.3 1985.32  5604.8    1985  5622.2 1985.69  5627.4 1985.16  5631.2 1985.53
#Mann= 4 ,-1 , 0
  4692.8    .035       0  4871.4     .07       0    4976     .07       0
  4983.6     .07       0
Bank Sta=4976,4983.6
XS Rating Curve= 0 ,0
Exp/Cntr=0.3,0.1

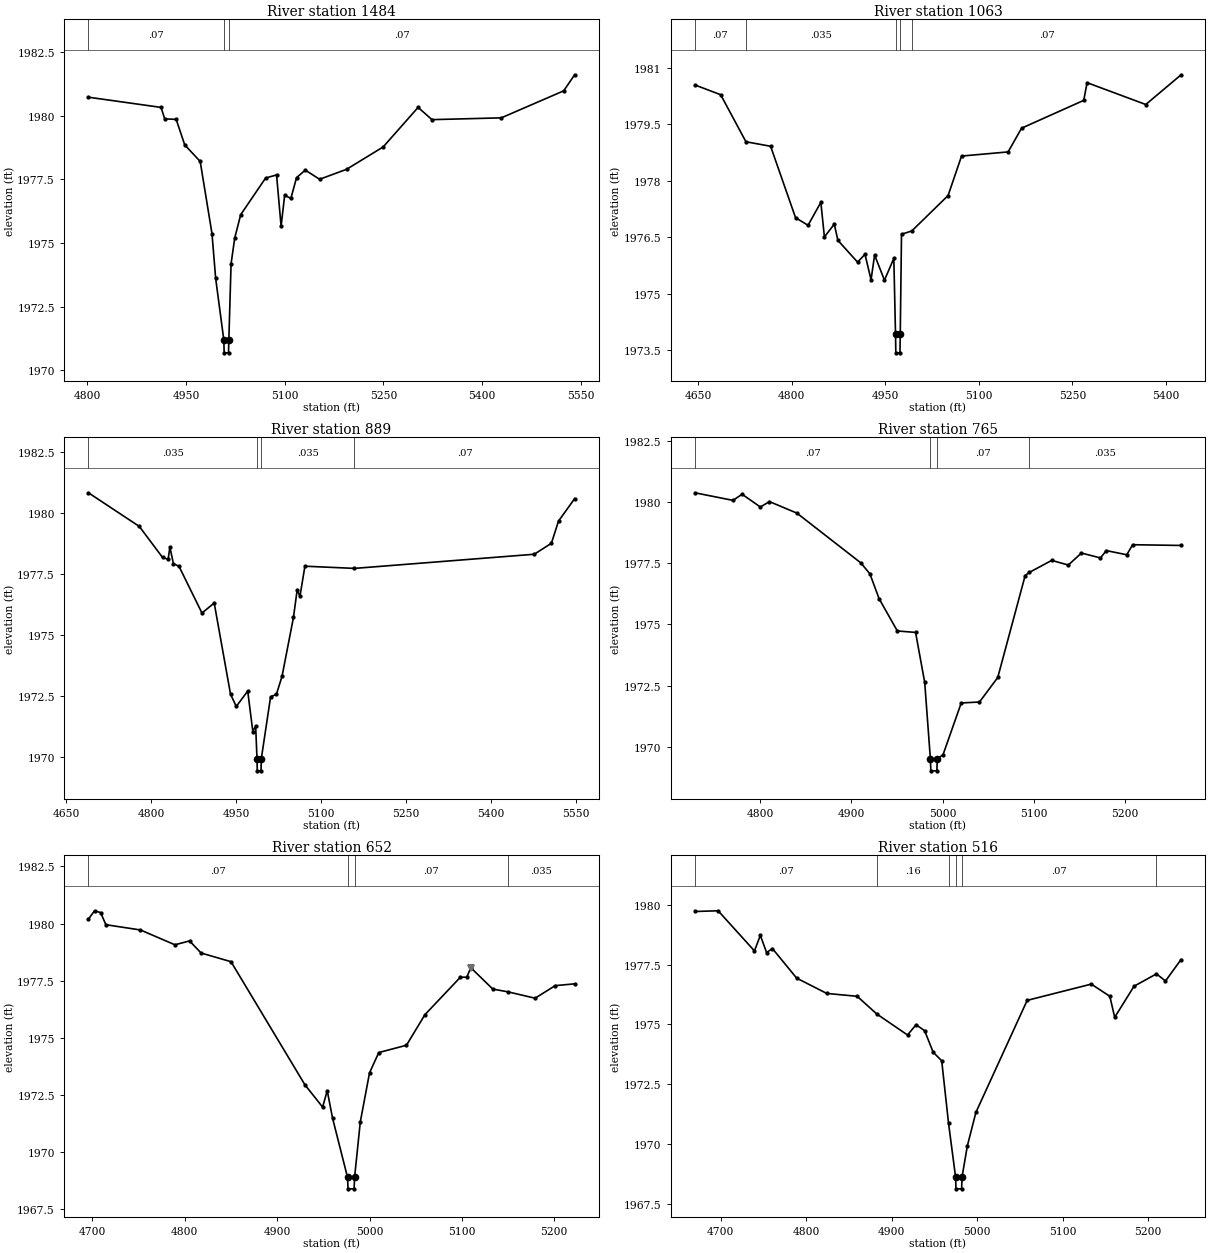
Type RM Length L Ch R = 1 ,1484    ,421,421,421
BEGIN DESCRIPTION:
Mapping XS 977e67cd
END DESCRIPTION:
XS GIS Cut Line= 4
      1455580.79      6859820.68      1455634.28      6859711.49
      1455905.12       6859594.3      1456210.77      6859493.28
#Sta/Elev= 30
  4801.9 1980.72  4912.2 1980.32  4917.8 1979.87  4935.2 1979.85  4948.2 1978.85
  4971.7  1978.2  4989.6 1975.37  4995.2 1973.61  5007.6 1971.19  5008.1 1970.69
  5014.7 1970.69  5015.2 1971.19  5018.6 1974.18  5024.1 1975.19  5033.2 1976.11
  5071.1 1977.55  5087.7 1977.67  5094.6 1975.66    5100 1976.87  5109.5 1976.75
    5118 1977.56  5131.3 1977.86  5153.1  1977.5    5194 1977.89  5249.7 1978.77
  5302.7 1980.32  5323.8 1979.84  5429.1 1979.91  5523.9 1980.97  5540.5  1981.6
#Mann= 3 ,-1 , 0
  4801.9     .07       0  5007.6     .07       0  5015.2     .07       0
Bank Sta=5007.6,5015.2
XS Rating Curve= 0 ,0
Exp/Cntr=0.3,0.1

Type RM Length L Ch R = 1 ,1063    ,174,174,174
BEGIN DESCRIPTION:
Mapping XS 1c7cce8a
END DESCRIPTION:
XS GIS Cut Line= 4
      1455603.72      6859851.48      1455792.92      6859851.48
      1456093.27      6859677.87      1456317.22      6859584.12
#Sta/Elev= 30
  4645.2 1980.55  4686.5 1980.29    4727 1979.04  4766.5 1978.92  4806.5 1977.02
  4826.5 1976.82    4847 1977.43  4852.7 1976.51  4868.5 1976.85  4874.3 1976.42
  4905.8 1975.84  4917.7 1976.05  4927.4 1975.37  4933.1 1976.03  4948.9 1975.36
  4963.9 1975.94  4966.6 1973.93  4967.1 1973.43  4973.7 1973.43  4974.2 1973.93
  4976.2 1976.58  4992.7 1976.67  5050.8 1977.61  5072.4 1978.66    5147 1978.77
  5168.5  1979.4  5268.1 1980.14  5273.5 1980.61  5367.5 1980.03  5424.1 1980.82
#Mann= 5 ,-1 , 0
  4645.2     .07       0    4727    .035       0  4966.6     .07       0
  4974.2    .035       0  4992.7     .07       0
Bank Sta=4966.6,4974.2
XS Rating Curve= 0 ,0
Exp/Cntr=0.3,0.1

Type RM Length L Ch R = 1 ,889     ,124,124,124
BEGIN DESCRIPTION:
Mapping XS 945ffb9f
END DESCRIPTION:
XS GIS Cut Line= 4
      1455595.25      6859940.65      1455735.85      6859943.26
      1456009.28       6859906.8      1456421.57      6859749.64
#Sta/Elev= 30
  4689.5 1980.83  4779.3 1979.45  4820.2 1978.18  4830.1  1978.1  4833.2  1978.6
  4839.4 1977.93  4849.4 1977.81  4889.8  1975.9  4911.4 1976.31  4940.2 1972.57
  4950.3 1972.07  4970.5  1972.7  4979.5 1971.04  4984.5 1971.27  4986.9 1969.93
  4987.4 1969.43    4994 1969.43  4994.5 1969.93  5010.9 1972.47    5021 1972.56
    5031  1973.3  5051.2 1975.72  5057.7 1976.84  5062.7 1976.59  5071.4 1977.82
  5158.8 1977.73    5476 1978.31  5506.2 1978.76  5518.8 1979.67  5547.2 1980.59
#Mann= 4 ,-1 , 0
  4689.5    .035       0  4986.9     .07       0  4994.5    .035       0
  5158.8     .07       0
Bank Sta=4986.9,4994.5
XS Rating Curve= 0 ,0
Exp/Cntr=0.3,0.1

Type RM Length L Ch R = 1 ,765     ,113,113,113
BEGIN DESCRIPTION:
Mapping XS 5a7dad11
END DESCRIPTION:
XS GIS Cut Line= 3
      1455583.26      6860028.13       1455978.1      6860030.23
       1456064.2      6859922.83
#Sta/Elev= 30
  4728.7 1980.37  4770.4 1980.06  4780.4 1980.31  4800.4 1979.79  4810.4 1980.01
  4840.4 1979.54  4910.4 1977.51  4920.4 1977.06  4930.4 1976.05  4950.4 1974.73
  4970.4 1974.67  4980.4 1972.63  4986.6 1969.52  4987.1 1969.02  4993.7 1969.02
  4994.2 1969.52  5000.4 1969.67  5020.4 1971.79  5040.4 1971.83  5060.4 1972.83
  5090.4 1976.99    5095 1977.12  5119.5 1977.61  5137.7 1977.42    5152 1977.91
  5172.9 1977.71  5179.3 1978.01  5201.7 1977.84  5208.1 1978.25  5261.2 1978.22
#Mann= 4 ,-1 , 0
  4728.7     .07       0  4986.6     .07       0  4994.2     .07       0
    5095    .035       0
Bank Sta=4986.6,4994.2
XS Rating Curve= 0 ,0
Exp/Cntr=0.3,0.1

Type RM Length L Ch R = 1 ,652     ,136,136,136
BEGIN DESCRIPTION:
Mapping XS 52a55819
END DESCRIPTION:
XS GIS Cut Line= 4
      1455569.21      6860076.09      1455690.25      6860145.69
      1455956.75      6860139.62      1456002.77      6860028.46
#Sta/Elev= 30
  4695.6  1980.2  4702.3 1980.56  4708.8 1980.48  4714.5 1979.95  4751.9 1979.72
  4789.3 1979.07  4805.1 1979.24  4817.6 1978.71    4850 1978.33    4930 1972.94
  4949.2 1971.96  4954.2 1972.68    4960 1971.47  4976.2 1968.88  4976.7 1968.38
  4983.3 1968.38  4983.8 1968.88    4990 1971.31    5000 1973.46    5010 1974.35
    5040 1974.67    5060 1976.01  5098.4 1977.65  5105.4 1977.65  5109.6 1978.07
  5133.5 1977.13  5149.8 1977.01  5179.3 1976.73    5201 1977.28  5222.1 1977.36
#Mann= 4 ,-1 , 0
  4695.6     .07       0  4976.2     .07       0  4983.8     .07       0
  5149.8    .035       0
Levee=0,,,-1,5109.6,1978.07,,
Bank Sta=4976.2,4983.8
XS Rating Curve= 0 ,0
Exp/Cntr=0.3,0.1

Type RM Length L Ch R = 1 ,516     ,254,254,254
BEGIN DESCRIPTION:
Mapping XS 8718a69f
END DESCRIPTION:
XS GIS Cut Line= 4
      1455588.49       6860136.2      1455723.04      6860279.86
      1455949.44      6860277.05      1456020.58      6860149.95
#Sta/Elev= 30
  4669.8 1979.73    4697 1979.76  4739.5 1978.08  4746.4 1978.73  4753.7 1978.01
  4760.5 1978.18  4788.9 1976.94  4824.1  1976.3  4859.7 1976.18  4882.6 1975.44
  4918.6 1974.56  4928.6 1974.99  4938.6 1974.74  4948.6 1973.84  4958.6 1973.48
  4966.6 1970.86  4974.8 1968.62  4975.3 1968.12  4981.9 1968.12  4982.4 1968.62
  4988.6 1969.92  4998.6 1971.32  5058.6 1976.01  5133.6 1976.69  5155.3 1976.18
    5161  1975.3  5183.6  1976.6  5209.9 1977.12  5220.4 1976.82  5238.7 1977.72
#Mann= 6 ,-1 , 0
  4669.8     .07       0  4882.6     .16       0  4966.6     .07       0
  4974.8     .07       0  4982.4     .07       0  5209.9    .035       0
Bank Sta=4974.8,4982.4
XS Rating Curve= 0 ,0
Exp/Cntr=0.3,0.1