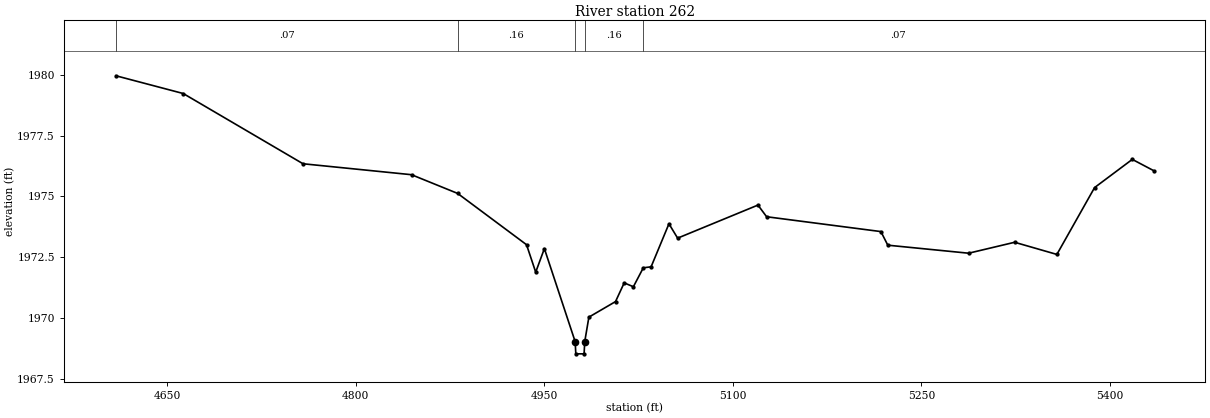
HEC-RAS study NC Unknown Stream 14.prj: NC Unknown Stream 14 Base Level Engineering

--- NC Unknown Stream 14.g01 (geometry) --- (continued)

Type RM Length L Ch R = 1 ,262     ,0,0,0
BEGIN DESCRIPTION:
NC Unknown Stream 14 1.0
END DESCRIPTION:
XS GIS Cut Line= 6
      1455553.57       6860143.8      1455697.87      6860355.39
      1455897.72        6860545.       1455968.9      6860531.98
      1455980.18      6860418.26      1455980.27       6860311.1
#Sta/Elev= 30
  4609.2 1979.96  4662.7 1979.23    4758 1976.34  4844.3 1975.89    4881 1975.12
  4935.8 1973.01  4943.1 1971.88    4950 1972.85  4974.5 1969.02    4975 1968.52
  4981.6 1968.52  4982.1 1969.02  4985.4 1970.03  5006.6 1970.67  5013.5 1971.44
  5020.8 1971.28  5028.7 1972.06  5034.9  1972.1  5049.1 1973.87    5056 1973.28
  5119.9 1974.64  5126.8 1974.16  5217.7 1973.55  5223.2 1972.99  5287.5 1972.66
  5324.1 1973.11  5357.7 1972.61  5387.7 1975.36  5417.7 1976.52  5434.6 1976.06
#Mann= 5 ,-1 , 0
  4609.2     .07       0    4881     .16       0  4974.5     .07       0
  4982.1     .16       0  5028.7     .07       0
Bank Sta=4974.5,4982.1
XS Rating Curve= 0 ,0
Exp/Cntr=0.3,0.1

Chan Stop Cuts=-1
Use User Specified Reach Order=0
Composite Channel Slope=5