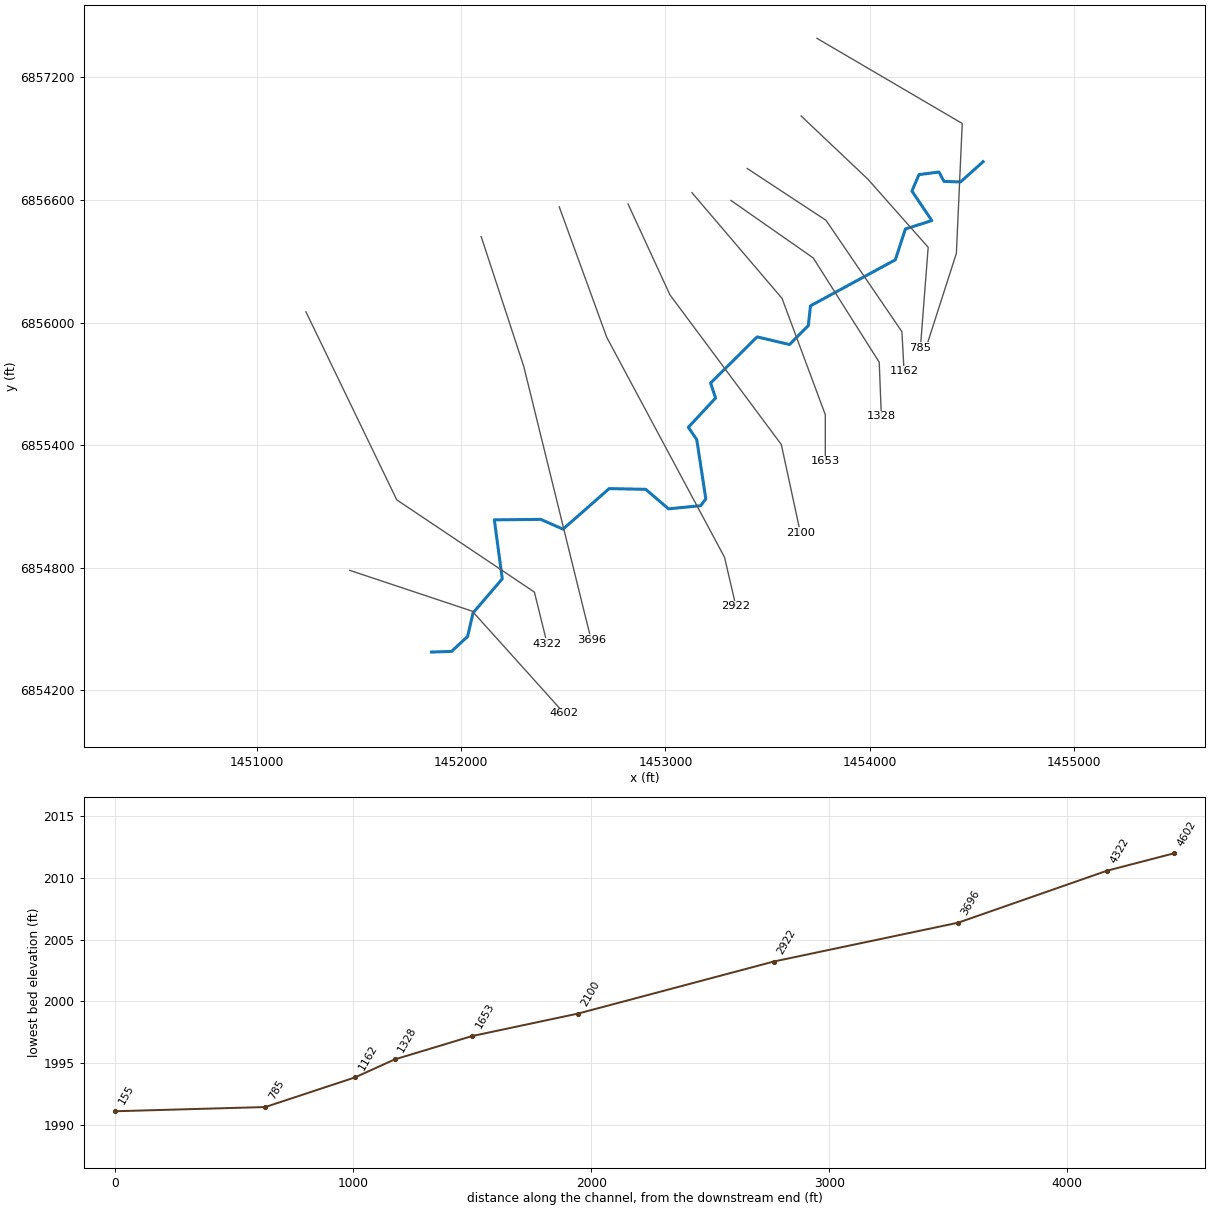
--- NC Unknown Stream 15.prj (project) ---

Proj Title=NC Unknown Stream 15 Base Level Engineering
Current Plan=p01
Default Exp/Contr=0.3,0.1
English Units
Geom File=g01
Flow File=f01
Plan File=p01
BEGIN DESCRIPTION:
NC Unknown Stream 15
END DESCRIPTION:

--- NC Unknown Stream 15.p01 (plan) ---

Plan Title=Multiple Run
Short Identifier=Multiple
Geom File=g01
Flow File=f01
Subcritical Flow
K Sum by GR= 0
Std Step Tol= 0.01
Critical Tol= 0.01
Num of Std Step Trials= 20
Max Error Tol= 0.3
Flow Tol Ratio= 0.001
Split Flow NTrial= 30
Split Flow Tol= 0.02
Split Flow Ratio= 0.02
Log Output Level= 0
Friction Slope Method= 1
Unsteady Friction Slope Method= 2
Unsteady Bridges Friction Slope Method= 1
Parabolic Critical Depth
Global Vel Dist=  1 , 1 , 1
Global Log Level= 0
CheckData=True
Encroach Param= -1, 0, 0, 0
BEGIN DESCRIPTION:
Multiple Run
END DESCRIPTION:

--- NC Unknown Stream 15.f01 (steady flow) ---

Flow Title=Multiple
Number of Profiles=7
Profile Names=10-year,25-year,50-year,1pct_min,100-year,1pct_plu,500-year
River Rch & RM= NC Unknown Strea,Reach-1,4602
     319     454     568     354     705    1407    1101
River Rch & RM= NC Unknown Strea,Reach-1,1328
     321     456     569     354     706    1409    1099
Boundary for River Rch & Prof#=NC Unknown Strea,Reach-1,1
Up Type=0
Dn Type=3
Dn Slope=0.001
Boundary for River Rch & Prof#=NC Unknown Strea,Reach-1,2
Up Type=0
Dn Type=3
Dn Slope=0.001
Boundary for River Rch & Prof#=NC Unknown Strea,Reach-1,3
Up Type=0
Dn Type=3
Dn Slope=0.001
Boundary for River Rch & Prof#=NC Unknown Strea,Reach-1,4
Up Type=0
Dn Type=3
Dn Slope=0.001
Boundary for River Rch & Prof#=NC Unknown Strea,Reach-1,5
Up Type=0
Dn Type=3
Dn Slope=0.001
Boundary for River Rch & Prof#=NC Unknown Strea,Reach-1,6
Up Type=0
Dn Type=3
Dn Slope=0.001
Boundary for River Rch & Prof#=NC Unknown Strea,Reach-1,7
Up Type=0
Dn Type=3
Dn Slope=0.001

--- NC Unknown Stream 15.g01 (geometry) ---

Geom Title=Existing Conditions

River Reach=NC Unknown Strea,Reach-1
Reach XY= 30
      1451855.00      6854388.00      1451953.61      6854391.37
      1452032.14      6854464.44      1452058.50      6854579.52
      1452201.69      6854746.48      1452162.90      6855035.09
      1452389.79      6855037.46      1452498.97      6854989.62
      1452724.98      6855188.04      1452903.53      6855184.45
      1453015.44      6855089.04      1453172.66      6855104.41
      1453197.79      6855137.65      1453153.61      6855427.57
      1453112.32      6855488.10      1453245.70      6855631.33
      1453221.39      6855704.67      1453448.94      6855930.52
      1453607.31      6855893.09      1453699.46      6855985.62
      1453710.25      6856082.56      1454125.51      6856307.72
      1454174.44      6856458.63      1454303.99      6856499.74
      1454206.57      6856644.09      1454241.23      6856724.82
      1454338.98      6856737.19      1454363.50      6856691.37
      1454444.42      6856688.87      1454555.00      6856788.00

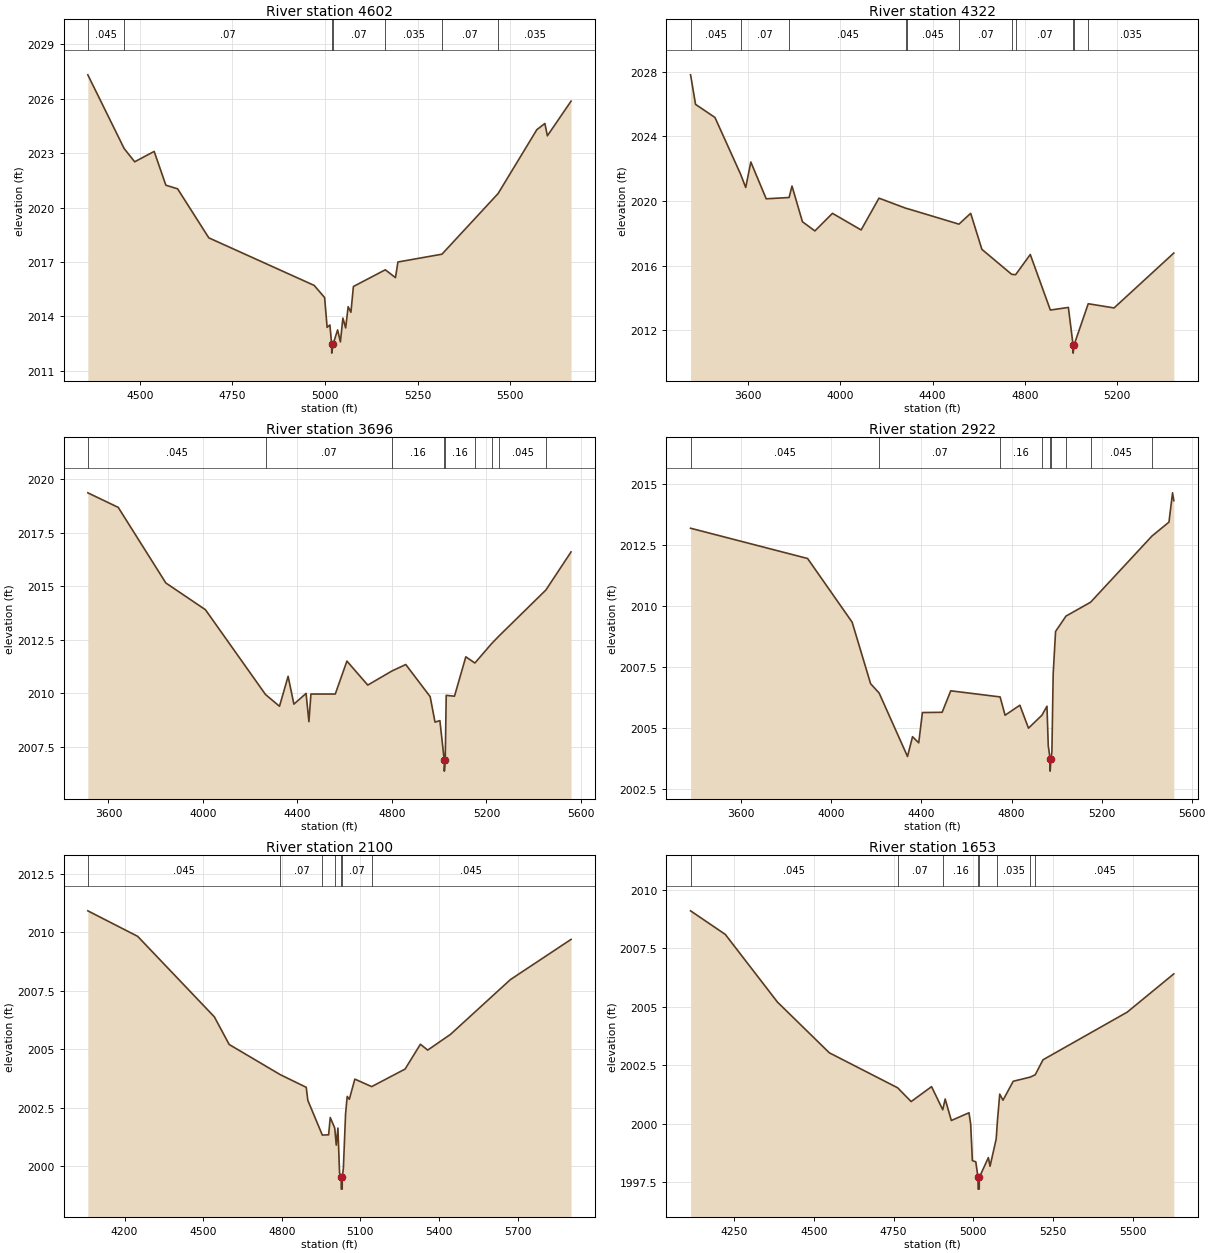
Type RM Length L Ch R = 1,4602,280,280,280
BEGIN DESCRIPTION:
NC Unknown Stream 15 5.0
END DESCRIPTION:
XS GIS Cut Line= 3
      1451454.98      6854788.01      1452055.00      6854588.00
      1452505.03      6854087.97
#Sta/Elev= 30
  4359.5 2027.31  4457.6 2023.25  4486.0 2022.52  4538.7 2023.09  4570.3 2021.23
  4602.0 2021.03  4686.3 2018.33  4970.9 2015.71  4999.1 2015.04  5005.8 2013.40
  5013.3 2013.53  5018.0 2012.48  5018.3 2011.98  5022.0 2012.48  5034.2 2013.26
  5041.7 2012.60  5048.4 2013.91  5055.9 2013.37  5062.6 2014.54  5070.1 2014.23
  5076.8 2015.65  5163.0 2016.57  5190.4 2016.14  5197.1 2017.00  5316.0 2017.43
  5467.6 2020.77  5572.3 2024.29  5594.0 2024.63  5600.7 2023.95  5664.7 2025.86
#Mann=7,-1,0
  4359.5   0.045       0  4457.6    0.07       0  5018.0    0.07       0
  5022.0    0.07       0  5163.0   0.035       0  5316.0    0.07       0
  5467.6   0.035       0
Bank Sta=5018,5022
Exp/Cntr=0.3,0.1

Type RM Length L Ch R = 1,4322,626,626,626
BEGIN DESCRIPTION:
Mapping XS 73935840
END DESCRIPTION:
XS GIS Cut Line= 4
      1451240.91      6856053.11      1451685.38      6855132.93
      1452358.99      6854681.54      1452421.48      6854428.10
#Sta/Elev= 30
  3351.5 2027.82  3373.1 2025.99  3457.1 2025.18  3569.0 2021.64  3590.4 2020.84
  3612.6 2022.42  3679.2 2020.14  3778.4 2020.22  3791.0 2020.93  3836.2 2018.72
  3890.2 2018.15  3966.3 2019.24  4090.4 2018.21  4167.9 2020.18  4285.0 2019.55
  4291.4 2019.53  4514.4 2018.57  4565.2 2019.24  4613.7 2017.01  4742.9 2015.46
  4759.9 2015.44  4823.4 2016.69  4910.4 2013.25  4988.5 2013.41  5008.9 2011.08
  5009.2 2010.58  5012.9 2011.08  5074.5 2013.64  5186.4 2013.38  5445.3 2016.78
#Mann=11,-1,0
  3351.5   0.045       0  3569.0    0.07       0  3778.4   0.045       0
  4285.0    0.07       0  4291.4   0.045       0  4514.4    0.07       0
  4742.9   0.045       0  4759.9    0.07       0  5008.9    0.07       0
  5012.9    0.07       0  5074.5   0.035       0
Bank Sta=5008.9,5012.9
Exp/Cntr=0.3,0.1

Type RM Length L Ch R = 1,3696,774,774,774
BEGIN DESCRIPTION:
Mapping XS 3d12a506
END DESCRIPTION:
XS GIS Cut Line= 4
      1452098.56      6856421.15      1452306.90      6855785.71
      1452591.63      6854629.46      1452636.76      6854448.93
#Sta/Elev= 30
  3512.7 2019.37  3641.4 2018.69  3842.9 2015.16  4010.6 2013.91  4264.8 2009.95
  4324.1 2009.40  4360.5 2010.80  4385.0 2009.50  4436.5 2010.00  4448.6 2008.68
  4457.1 2009.97  4560.1 2009.97  4609.5 2011.51  4697.7 2010.39  4800.4 2011.05
  4858.6 2011.35  4961.8 2009.85  4982.4 2008.66  5003.0 2008.73  5021.6 2006.87
  5021.8 2006.37  5025.6 2006.87  5029.8 2009.91  5064.8 2009.87  5112.8 2011.71
  5151.2 2011.42  5222.3 2012.33  5254.8 2012.70  5451.7 2014.83  5558.3 2016.61
#Mann=9,-1,0
  3512.7   0.045       0  4264.8    0.07       0  4800.4    0.16       0
  5021.6    0.07       0  5025.6    0.16       0  5151.2   0.045       0
  5222.3    0.07       0  5254.8   0.045       0  5451.7   0.035       0
Bank Sta=5021.6,5025.6
Exp/Cntr=0.3,0.1

Type RM Length L Ch R = 1,2922,822,822,822
BEGIN DESCRIPTION:
Mapping XS ced8549c
END DESCRIPTION:
XS GIS Cut Line= 4
      1452480.51      6856566.97      1452713.15      6855928.07
      1453289.54      6854851.68      1453344.99      6854612.56
#Sta/Elev= 30
  3374.4 2013.18  3894.2 2011.94  4092.1 2009.33  4174.1 2006.81  4211.9 2006.43
  4338.0 2003.83  4360.2 2004.64  4387.8 2004.39  4404.1 2005.63  4491.8 2005.64
  4530.0 2006.52  4749.3 2006.27  4771.3 2005.52  4837.1 2005.93  4875.3 2004.99
  4935.0 2005.52  4957.4 2005.89  4963.1 2004.28  4971.2 2003.73  4971.5 2003.23
  4975.2 2003.73  4979.3 2004.02  4985.0 2007.21  4995.6 2008.95  5041.8 2009.58
  5151.3 2010.15  5423.8 2012.86  5499.3 2013.43  5515.2 2014.63  5520.8 2014.31
#Mann=9,-1,0
  3374.4   0.045       0  4211.9    0.07       0  4749.3    0.16       0
  4935.0    0.07       0  4971.2    0.07       0  4975.2    0.07       0
  5041.8   0.035       0  5151.3   0.045       0  5423.8   0.035       0
Bank Sta=4971.2,4975.2
Exp/Cntr=0.3,0.1

Type RM Length L Ch R = 1,2100,447,447,447
BEGIN DESCRIPTION:
Mapping XS 080915bc
END DESCRIPTION:
XS GIS Cut Line= 4
      1452817.33      6856580.82      1453022.18      6856136.40
      1453567.32      6855403.76      1453660.71      6854971.39
#Sta/Elev= 30
  4059.6 2010.91  4249.9 2009.82  4542.7 2006.38  4599.3 2005.20  4794.4 2003.91
  4893.4 2003.37  4899.6 2002.81  4954.9 2001.33  4978.9 2001.34  4985.1 2002.08
  5002.2 2001.63  5008.1 2000.90  5014.4 2001.63  5020.6 1999.72  5027.0 1999.52
  5027.2 1999.02  5030.7 1999.02  5031.0 1999.52  5035.2 1999.91  5043.6 2002.23
  5049.8 2002.98  5058.0 2002.86  5079.0 2003.72  5143.3 2003.40  5270.9 2004.15
  5329.3 2005.21  5357.2 2004.96  5444.0 2005.63  5672.7 2007.97  5904.5 2009.69
#Mann=7,-1,0
  4059.6   0.045       0  4794.4    0.07       0  4954.9   0.045       0
  5002.2    0.07       0  5027.0   0.045       0  5031.0    0.07       0
  5143.3   0.045       0
Bank Sta=5027,5031
Exp/Cntr=0.3,0.1

Type RM Length L Ch R = 1,1653,325,325,325
BEGIN DESCRIPTION:
Mapping XS ea9168ec
END DESCRIPTION:
XS GIS Cut Line= 4
      1453129.81      6856636.41      1453570.79      6856119.04
      1453782.60      6855549.60      1453782.60      6855321.76
#Sta/Elev= 30
  4113.3 2009.11  4222.2 2008.10  4385.8 2005.20  4548.3 2003.03  4762.6 2001.53
  4804.9 2000.94  4868.9 2001.58  4904.0 2000.59  4911.6 2001.05  4930.9 2000.13
  4986.3 2000.46  4991.6 1999.98  4996.9 1998.41  5007.6 1998.36  5014.6 1997.69
  5014.9 1997.19  5018.4 1997.19  5018.6 1997.69  5047.0 1998.54  5052.3 1998.17
  5071.6 1999.34  5075.5 2000.12  5082.7 2001.26  5093.0 2001.00  5125.0 2001.81
  5178.9 2001.99  5194.0 2002.09  5218.4 2002.73  5482.3 2004.77  5628.5 2006.41
#Mann=8,-1,0
  4113.3   0.045       0  4762.6    0.07       0  4904.0    0.16       0
  5014.6    0.07       0  5018.6    0.16       0  5075.5   0.035       0
  5178.9    0.07       0  5194.0   0.045       0
Bank Sta=5014.6,5018.6
Exp/Cntr=0.3,0.1

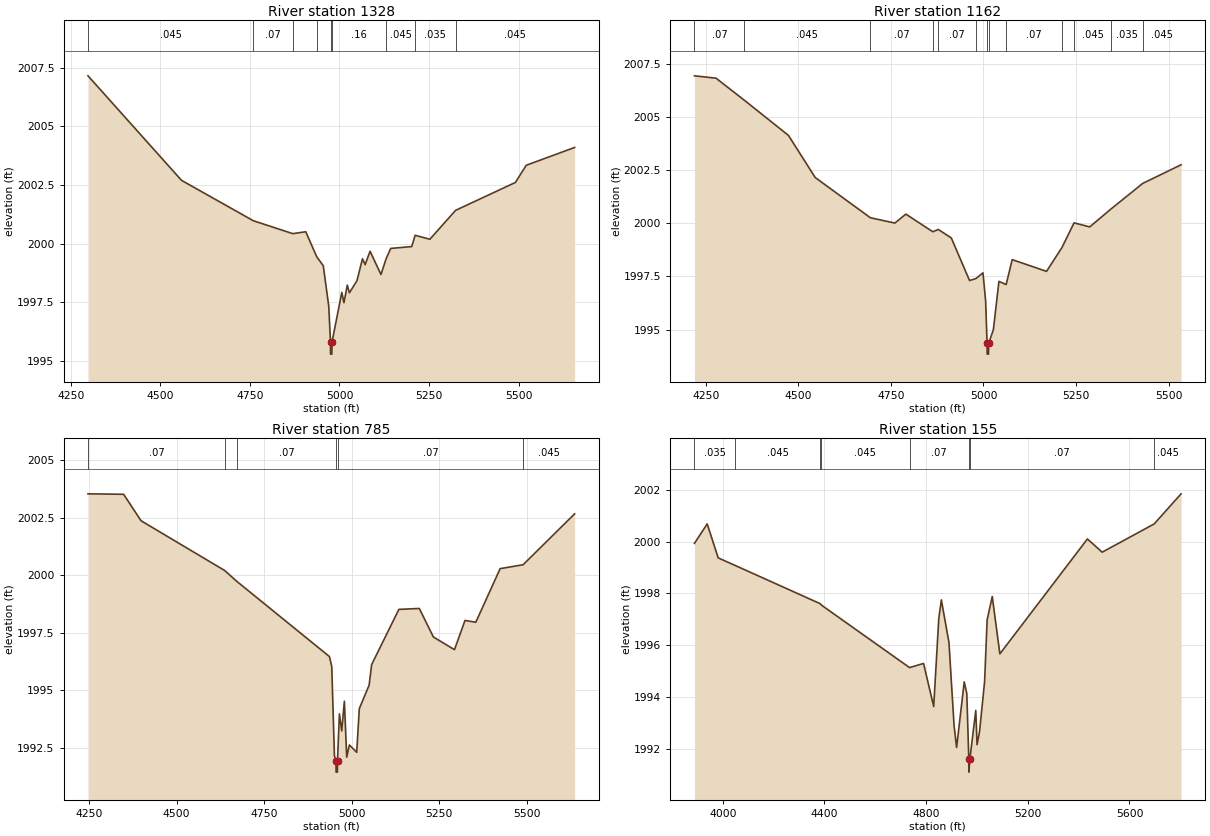
Type RM Length L Ch R = 1,1328,166,166,166
BEGIN DESCRIPTION:
Mapping XS c632e31e
END DESCRIPTION:
XS GIS Cut Line= 4
      1453320.82      6856598.19      1453723.57      6856316.96
      1454046.49      6855806.54      1454056.90      6855542.86
#Sta/Elev= 30
  4297.6 2007.15  4558.8 2002.70  4759.3 2000.98  4869.6 2000.43  4905.9 2000.51
  4936.3 1999.45  4954.8 1999.06  4970.1 1997.33  4974.9 1995.80  4975.1 1995.30
  4978.7 1995.30  4979.0 1995.80  5006.5 1997.93  5012.5 1997.49  5021.8 1998.24
  5027.7 1997.91  5048.9 1998.43  5064.2 1999.36  5071.6 1999.11  5085.4 1999.68
  5115.9 1998.69  5130.2 1999.36  5143.0 1999.80  5201.8 1999.88  5211.3 2000.36
  5252.4 2000.19  5324.1 2001.42  5491.4 2002.61  5521.5 2003.34  5656.7 2004.10
#Mann=9,-1,0
  4297.6   0.045       0  4759.3    0.07       0  4869.6   0.045       0
  4936.3    0.16       0  4974.9    0.07       0  4979.0    0.16       0
  5130.2   0.045       0  5211.3   0.035       0  5324.1   0.045       0
Bank Sta=4974.9,4979
Exp/Cntr=0.3,0.1

Type RM Length L Ch R = 1,1162,377,377,377
BEGIN DESCRIPTION:
Mapping XS 4befd914
END DESCRIPTION:
XS GIS Cut Line= 4
      1453400.64      6856754.47      1453786.07      6856500.99
      1454157.60      6855955.85      1454167.97      6855762.25
#Sta/Elev= 30
  4219.1 2006.93  4277.3 2006.82  4354.1 2005.78  4473.1 2004.13  4545.4 2002.15
  4694.4 2000.26  4760.6 2000.01  4790.4 2000.43  4863.2 1999.60  4877.9 1999.71
  4913.1 1999.31  4962.4 1997.31  4979.5 1997.40  4998.7 1997.67  5005.9 1996.34
  5009.8 1994.35  5010.1 1993.85  5013.7 1993.85  5014.0 1994.35  5026.8 1995.00
  5041.8 1997.27  5061.3 1997.12  5077.7 1998.29  5170.5 1997.74  5212.1 1998.86
  5244.8 2000.02  5287.1 1999.83  5344.6 2000.67  5430.1 2001.87  5534.0 2002.75
#Mann=13,-1,0
  4219.1    0.07       0  4354.1   0.045       0  4694.4    0.07       0
  4863.2   0.045       0  4877.9    0.07       0  4979.5    0.16       0
  5009.8    0.07       0  5014.0    0.16       0  5061.3    0.07       0
  5212.1   0.035       0  5244.8   0.045       0  5344.6   0.035       0
  5430.1   0.045       0
Bank Sta=5009.8,5014
Exp/Cntr=0.3,0.1

Type RM Length L Ch R = 1,785,630,630,630
BEGIN DESCRIPTION:
Mapping XS 582ddff6
END DESCRIPTION:
XS GIS Cut Line= 4
      1453664.52      6857011.42      1453990.93      6856702.37
      1454286.07      6856369.04      1454247.88      6855876.04
#Sta/Elev= 30
  4247.2 2003.54  4348.9 2003.52  4398.7 2002.37  4637.3 2000.21  4671.8 1999.74
  4936.5 1996.47  4943.1 1996.04  4950.7 1992.16  4955.3 1991.95  4955.5 1991.45
  4959.2 1991.45  4959.5 1991.95  4964.9 1993.98  4971.6 1993.24  4979.1 1994.53
  4985.8 1992.10  4993.4 1992.63  5014.3 1992.31  5021.8 1994.21  5049.8 1995.23
  5056.9 1996.12  5134.7 1998.52  5193.1 1998.56  5233.2 1997.32  5293.4 1996.77
  5323.5 1998.04  5354.3 1997.96  5423.8 2000.29  5489.4 2000.46  5636.4 2002.67
#Mann=6,-1,0
  4247.2    0.07       0  4637.3   0.045       0  4671.8    0.07       0
  4955.3    0.07       0  4959.5    0.07       0  5489.4   0.045       0
Bank Sta=4955.3,4959.5
Exp/Cntr=0.3,0.1

Type RM Length L Ch R = 1,155,0,0,0
BEGIN DESCRIPTION:
NC Unknown Stream 15 1.0
END DESCRIPTION:
XS GIS Cut Line= 4
      1453741.78      6857391.62      1454452.74      6856974.94
      1454424.09      6856339.53      1454285.20      6855907.22
#Sta/Elev= 30
  3888.9 1999.93  3939.0 2000.68  3982.3 1999.37  4048.6 1999.08  4384.5 1997.60
  4386.9 1997.56  4735.0 1995.14  4790.0 1995.30  4830.0 1993.64  4850.0 1997.03
  4860.1 1997.75  4890.1 1996.10  4910.1 1992.91  4920.1 1992.06  4950.1 1994.59
  4960.2 1994.14  4968.1 1991.61  4968.3 1991.11  4972.3 1991.61  4995.5 1993.49
  5000.5 1992.17  5010.2 1992.66  5030.2 1994.60  5040.2 1996.98  5060.3 1997.88
  5090.3 1995.67  5434.7 2000.10  5492.8 1999.59  5697.4 2000.68  5803.1 2001.84
#Mann=8,-1,0
  3888.9   0.035       0  4048.6   0.045       0  4384.5    0.07       0
  4386.9   0.045       0  4735.0    0.07       0  4968.1    0.07       0
  4972.3    0.07       0  5697.4   0.045       0
Bank Sta=4968.1,4972.3
Exp/Cntr=0.3,0.1

Chan Stop Cuts=-1