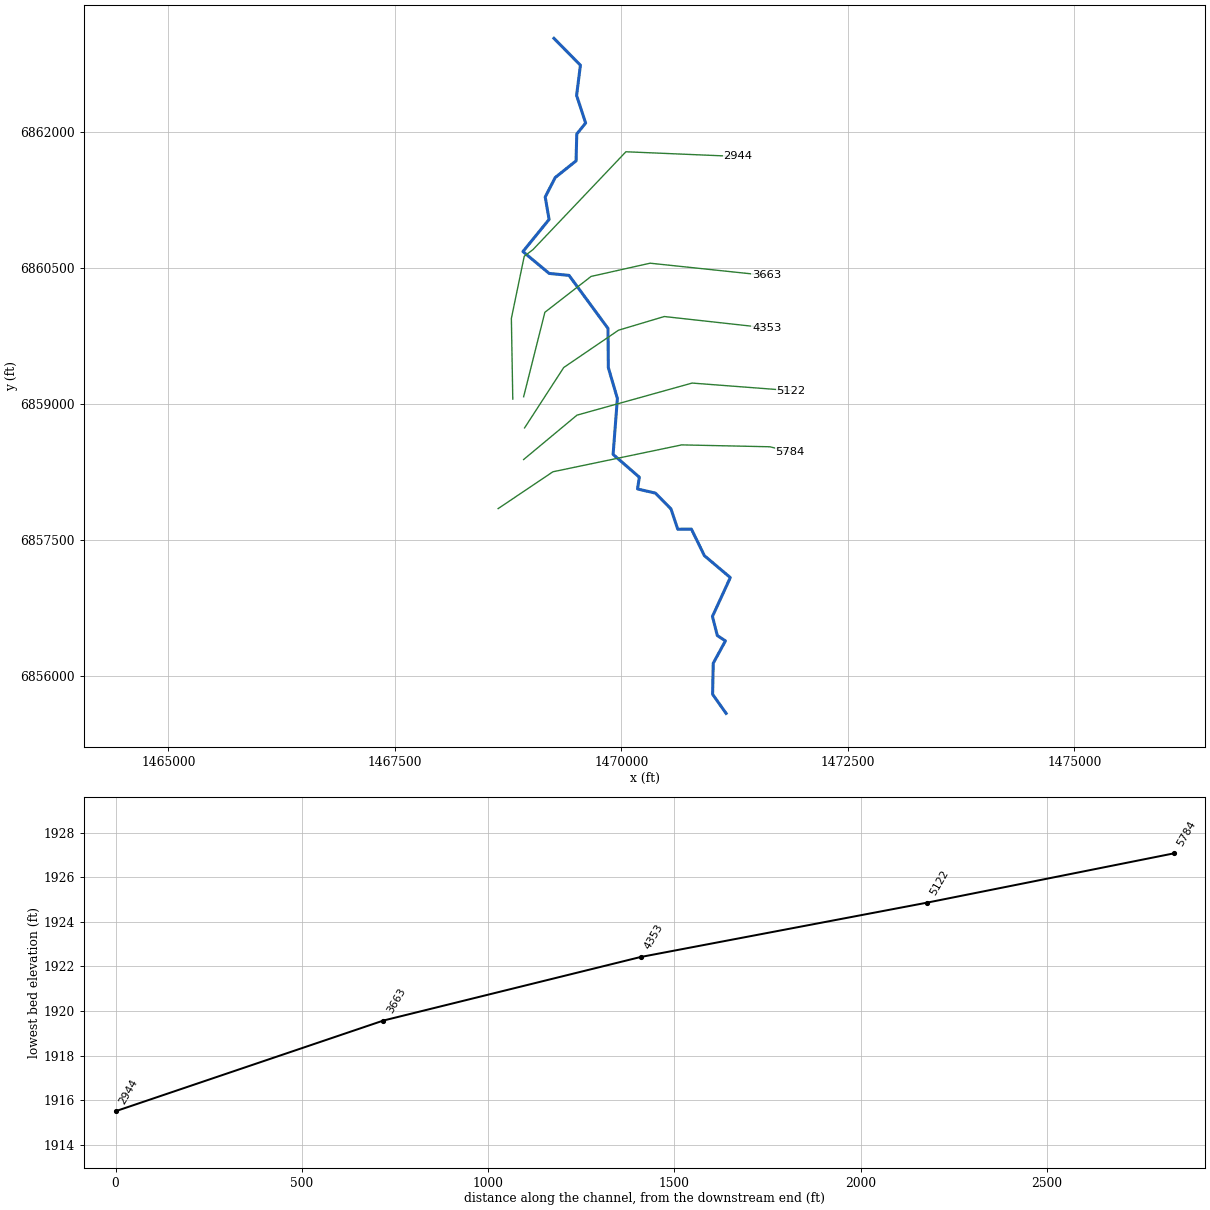
--- NC Unknown Stream 17.prj (project) ---

Proj Title=NC Unknown Stream 17 Base Level Engineering
Current Plan=p01
Default Exp/Contr=0.3,0.1
English Units
Geom File=g01
Flow File=f01
Plan File=p01
BEGIN DESCRIPTION:
NC Unknown Stream 17
END DESCRIPTION:

--- NC Unknown Stream 17.p01 (plan) ---

Plan Title=Multiple Run
Short Identifier=Multiple
Geom File=g01
Flow File=f01
Subcritical Flow
K Sum by GR= 0
Std Step Tol= 0.01
Critical Tol= 0.01
Num of Std Step Trials= 20
Max Error Tol= 0.3
Flow Tol Ratio= 0.001
Split Flow NTrial= 30
Split Flow Tol= 0.02
Split Flow Ratio= 0.02
Log Output Level= 0
Friction Slope Method= 1
Unsteady Friction Slope Method= 2
Unsteady Bridges Friction Slope Method= 1
Parabolic Critical Depth
Global Vel Dist=  1 , 1 , 1
Global Log Level= 0
CheckData=True
Encroach Param= -1, 0, 0, 0
BEGIN DESCRIPTION:
Multiple Run
END DESCRIPTION:

--- NC Unknown Stream 17.f01 (steady flow) ---

Flow Title=Multiple
Number of Profiles=7
Profile Names=10-year,25-year,50-year,1pct_min,100-year,1pct_plu,500-year
River Rch & RM= NC Unknown Strea,Reach-1,5784
     334     463     568     346     690    1377    1031
River Rch & RM= NC Unknown Strea,Reach-1,5122
     458     645     801     493     983    1961    1500
River Rch & RM= NC Unknown Strea,Reach-1,3663
     558     794     993     615    1227    2448    1897
Boundary for River Rch & Prof#=NC Unknown Strea,Reach-1,1
Up Type=0
Dn Type=3
Dn Slope=0.001
Boundary for River Rch & Prof#=NC Unknown Strea,Reach-1,2
Up Type=0
Dn Type=3
Dn Slope=0.001
Boundary for River Rch & Prof#=NC Unknown Strea,Reach-1,3
Up Type=0
Dn Type=3
Dn Slope=0.001
Boundary for River Rch & Prof#=NC Unknown Strea,Reach-1,4
Up Type=0
Dn Type=3
Dn Slope=0.001
Boundary for River Rch & Prof#=NC Unknown Strea,Reach-1,5
Up Type=0
Dn Type=3
Dn Slope=0.001
Boundary for River Rch & Prof#=NC Unknown Strea,Reach-1,6
Up Type=0
Dn Type=3
Dn Slope=0.001
Boundary for River Rch & Prof#=NC Unknown Strea,Reach-1,7
Up Type=0
Dn Type=3
Dn Slope=0.001

--- NC Unknown Stream 17.g01 (geometry) ---

Geom Title=Existing Conditions

River Reach=NC Unknown Strea,Reach-1
Reach XY= 30
      1471155.00      6855588.00      1471006.05      6855798.44
      1471013.01      6856141.33      1471147.74      6856388.30
      1471058.21      6856446.34      1471004.40      6856658.05
      1471201.63      6857086.72      1470915.78      6857328.32
      1470772.13      6857621.96      1470621.44      6857620.36
      1470546.87      6857844.07      1470375.43      6858018.63
      1470177.46      6858064.53      1470197.50      6858194.05
      1469908.07      6858446.30      1469955.20      6859063.08
      1469855.52      6859403.22      1469851.46      6859836.54
      1469421.76      6860421.57      1469202.55      6860443.46
      1468912.76      6860684.58      1469201.54      6861039.50
      1469158.67      6861286.42      1469268.61      6861501.24
      1469499.20      6861685.70      1469507.06      6861982.14
      1469604.75      6862103.22      1469505.07      6862408.03
      1469547.31      6862741.67      1469255.00      6863038.00

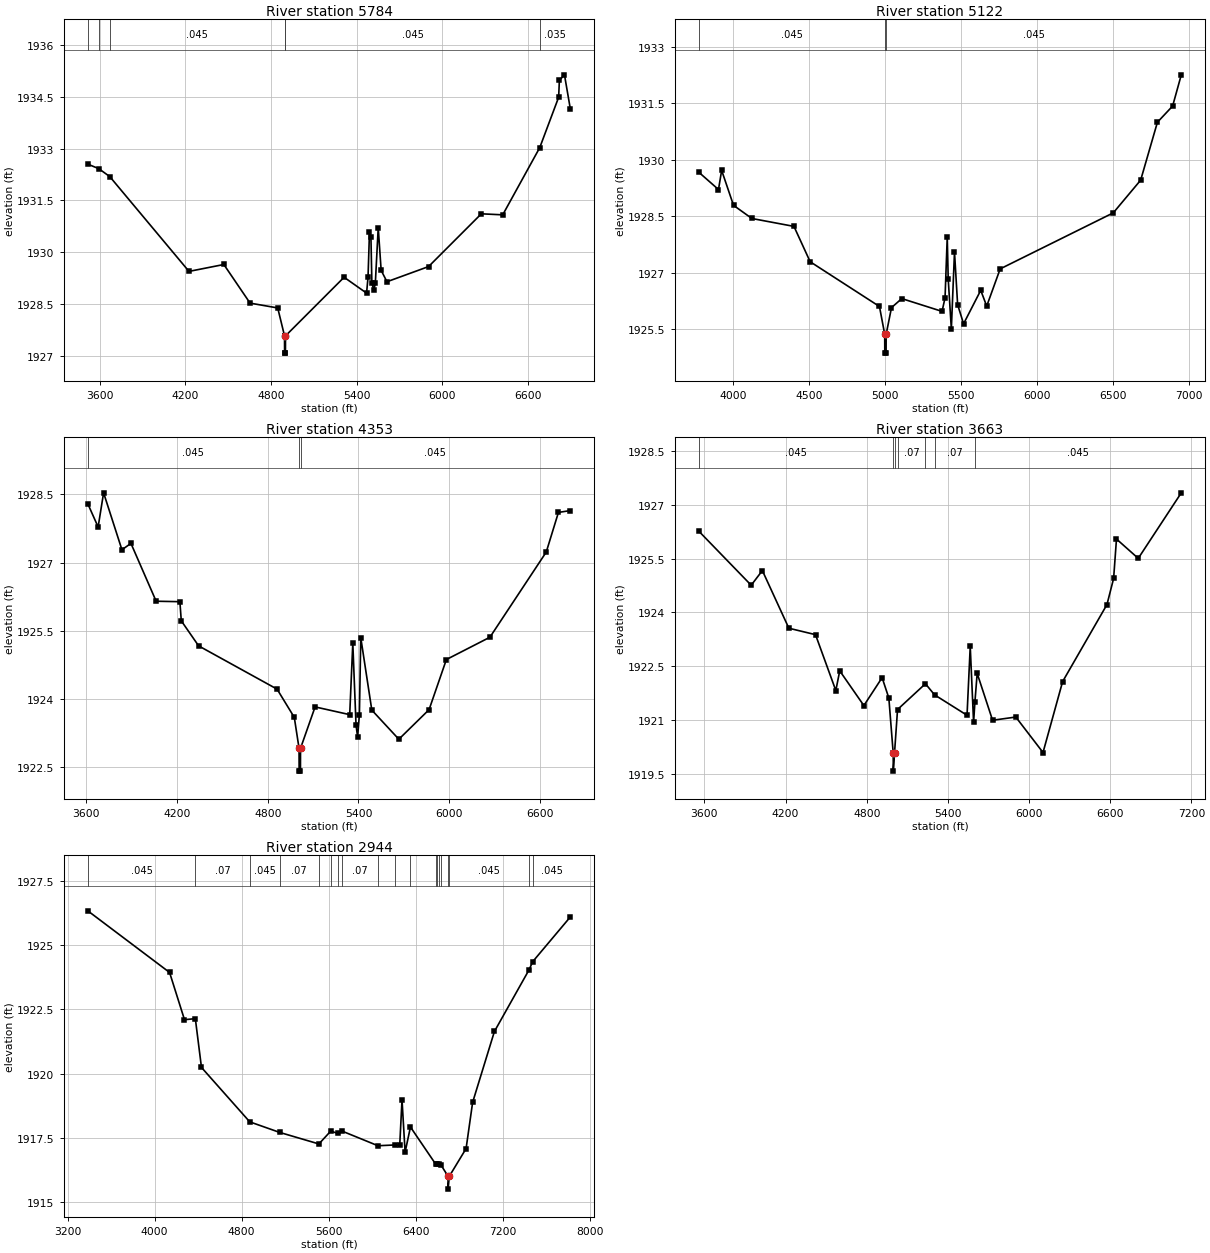
Type RM Length L Ch R = 1,5784,662,662,662
BEGIN DESCRIPTION:
Mapping XS 7ce44b7d
END DESCRIPTION:
XS GIS Cut Line= 5
      1468639.39      6857848.02      1469243.54      6858254.26
      1470665.41      6858551.13      1471639.37      6858530.30
      1471861.66      6858473.43
#Sta/Elev= 30
  3515.1 1932.55  3591.7 1932.42  3669.0 1932.19  4224.9 1929.44  4469.4 1929.64
  4653.3 1928.52  4847.3 1928.38  4895.0 1927.57  4895.5 1927.07  4901.3 1927.07
  4901.8 1927.57  5312.8 1929.27  5470.5 1928.81  5480.7 1929.27  5490.9 1930.59
  5501.1 1930.43  5507.7 1929.09  5521.6 1928.91  5531.8 1929.09  5552.2 1930.71
  5572.7 1929.47  5613.5 1929.14  5905.3 1929.58  6275.4 1931.11  6425.4 1931.08
  6685.2 1933.03  6817.7 1934.49  6822.8 1934.98  6858.5 1935.14  6899.3 1934.16
#Mann=6,-1,0
  3515.1   0.045       0  3591.7   0.035       0  3669.0   0.045       0
  4895.0   0.045       0  4901.8   0.045       0  6685.2   0.035       0
Bank Sta=4895,4901.8
Exp/Cntr=0.3,0.1

Type RM Length L Ch R = 1,5122,769,769,769
BEGIN DESCRIPTION:
Mapping XS 01d2a365
END DESCRIPTION:
XS GIS Cut Line= 4
      1468920.60      6858389.66      1469509.16      6858879.26
      1470779.99      6859233.42      1471871.89      6859150.23
#Sta/Elev= 30
  3771.4 1929.67  3901.2 1929.21  3922.0 1929.72  4000.2 1928.79  4121.2 1928.44
  4398.5 1928.23  4505.3 1927.29  4962.1 1926.10  4996.7 1925.36  4997.2 1924.86
  5005.7 1924.86  5006.2 1925.36  5041.3 1926.07  5109.2 1926.31  5374.6 1925.97
  5394.3 1926.33  5408.8 1927.95  5415.1 1926.84  5435.8 1925.50  5456.6 1927.55
  5477.2 1926.15  5516.5 1925.64  5629.5 1926.53  5668.9 1926.11  5757.6 1927.10
  6503.1 1928.59  6683.6 1929.46  6794.0 1931.00  6894.2 1931.43  6951.3 1932.26
#Mann=3,-1,0
  3771.4   0.045       0  4996.7   0.045       0  5006.2   0.045       0
Bank Sta=4996.7,5006.2
Exp/Cntr=0.3,0.1

Type RM Length L Ch R = 1,4353,690,690,690
BEGIN DESCRIPTION:
Mapping XS 88505f6f
END DESCRIPTION:
XS GIS Cut Line= 5
      1468931.01      6858738.59      1469363.33      6859405.30
      1469967.49      6859816.76      1470472.70      6859967.80
      1471602.93      6859842.79
#Sta/Elev= 30
  3610.4 1928.29  3678.7 1927.78  3714.9 1928.53  3836.1 1927.28  3895.7 1927.42
  4062.3 1926.15  4219.3 1926.14  4228.5 1925.72  4343.2 1925.17  4861.8 1924.22
  4975.7 1923.60  5007.2 1922.92  5007.7 1922.42  5016.3 1922.42  5016.8 1922.92
  5113.2 1923.83  5342.1 1923.66  5362.5 1925.23  5383.9 1923.43  5394.3 1923.17
  5406.1 1923.66  5415.2 1925.35  5488.2 1923.76  5666.9 1923.12  5866.8 1923.77
  5981.2 1924.87  6269.2 1925.36  6641.5 1927.23  6722.0 1928.10  6800.4 1928.14
#Mann=3,-1,0
  3610.4   0.045       0  5007.2   0.045       0  5016.8   0.045       0
Bank Sta=5007.2,5016.8
Exp/Cntr=0.3,0.1

Type RM Length L Ch R = 1,3663,719,719,719
BEGIN DESCRIPTION:
Mapping XS 4c82b9dd
END DESCRIPTION:
XS GIS Cut Line= 5
      1468920.63      6859082.42      1469154.99      6860014.67
      1469665.41      6860410.51      1470316.45      6860556.34
      1471601.50      6860421.07
#Sta/Elev= 30
  3558.8 1926.27  3946.1 1924.76  4028.6 1925.17  4224.5 1923.56  4421.5 1923.38
  4571.6 1921.82  4600.6 1922.37  4779.0 1921.40  4913.8 1922.18  4963.6 1921.61
  4995.9 1920.07  4996.4 1919.57  5005.5 1920.07  5027.9 1921.29  5234.1 1922.01
  5301.4 1921.70  5541.5 1921.13  5565.2 1923.05  5590.0 1920.93  5599.8 1921.50
  5616.5 1922.30  5730.3 1920.99  5902.1 1921.08  6103.2 1920.09  6248.1 1922.07
  6575.8 1924.22  6625.1 1924.95  6646.2 1926.05  6807.1 1925.51  7125.3 1927.34
#Mann=7,-1,0
  3558.8   0.045       0  4995.9   0.045       0  5005.5   0.045       0
  5027.9    0.07       0  5234.1   0.045       0  5301.4    0.07       0
  5599.8   0.045       0
Bank Sta=4995.9,5005.5
Exp/Cntr=0.3,0.1

Type RM Length L Ch R = 1,2944,0,0,0
BEGIN DESCRIPTION:
NC Unknown Stream 17 1.0
END DESCRIPTION:
XS GIS Cut Line= 6
      1468800.83      6859056.29      1468785.20      6859946.96
      1468927.07      6860632.26      1469024.79      6860707.38
      1470049.49      6861786.16      1471281.93      6861734.16
#Sta/Elev= 30
  3386.0 1926.34  4137.8 1923.94  4274.8 1922.10  4374.6 1922.14  4431.0 1920.24
  4874.9 1918.12  5149.2 1917.71  5510.3 1917.26  5619.4 1917.76  5684.3 1917.67
  5723.7 1917.76  6053.4 1917.19  6208.2 1917.22  6253.5 1917.21  6274.5 1918.98
  6302.8 1916.94  6352.0 1917.92  6582.9 1916.48  6600.2 1916.48  6616.6 1916.49
  6632.8 1916.44  6697.6 1916.00  6698.1 1915.50  6709.2 1916.00  6863.5 1917.08
  6923.6 1918.88  7123.8 1921.64  7441.9 1924.04  7475.9 1924.36  7821.3 1926.10
#Mann=19,-1,0
  3386.0   0.045       0  4374.6    0.07       0  4874.9   0.045       0
  5149.2    0.07       0  5510.3   0.045       0  5619.4    0.07       0
  5684.3   0.045       0  5723.7    0.07       0  6053.4   0.045       0
  6208.2   0.035       0  6352.0   0.045       0  6582.9   0.035       0
  6600.2   0.045       0  6616.6   0.035       0  6632.8   0.045       0
  6697.6   0.045       0  6709.2   0.045       0  7441.9   0.035       0
  7475.9   0.045       0
Bank Sta=6697.6,6709.2
Exp/Cntr=0.3,0.1

Chan Stop Cuts=-1