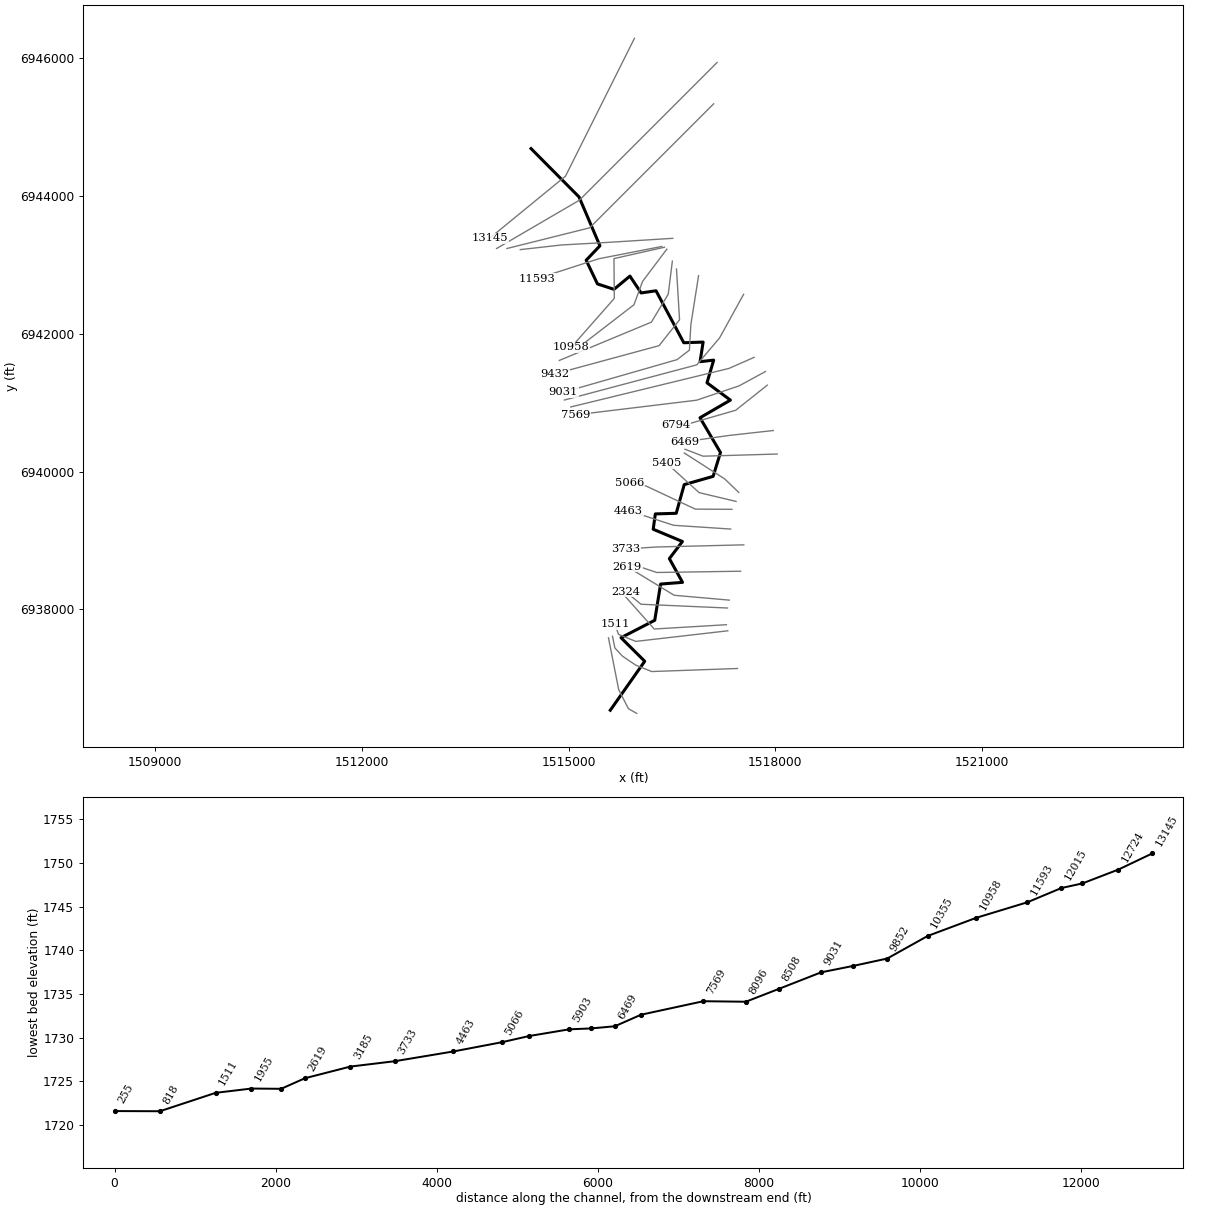
--- NC Unknown Stream 18.prj (project) ---

Proj Title=NC Unknown Stream 18 Base Level Engineering
Current Plan=p01
Default Exp/Contr=0.3,0.1
English Units
Geom File=g01
Flow File=f01
Plan File=p01
BEGIN DESCRIPTION:
NC Unknown Stream 18
END DESCRIPTION:

--- NC Unknown Stream 18.p01 (plan) ---

Plan Title=Multiple Run
Short Identifier=Multiple
Geom File=g01
Flow File=f01
Subcritical Flow
K Sum by GR= 0
Std Step Tol= 0.01
Critical Tol= 0.01
Num of Std Step Trials= 20
Max Error Tol= 0.3
Flow Tol Ratio= 0.001
Split Flow NTrial= 30
Split Flow Tol= 0.02
Split Flow Ratio= 0.02
Log Output Level= 0
Friction Slope Method= 1
Unsteady Friction Slope Method= 2
Unsteady Bridges Friction Slope Method= 1
Parabolic Critical Depth
Global Vel Dist=  1 , 1 , 1
Global Log Level= 0
CheckData=True
Encroach Param= -1, 0, 0, 0
BEGIN DESCRIPTION:
Multiple Run
END DESCRIPTION:

--- NC Unknown Stream 18.f01 (steady flow) ---

Flow Title=Multiple
Number of Profiles=7
Profile Names=10-year,25-year,50-year,1pct_min,100-year,1pct_plu,500-year
River Rch & RM= NC Unknown Strea,Reach-1,13145
     388     551     688     428     854    1704    1333
River Rch & RM= NC Unknown Strea,Reach-1,12015
     501     720     907     568    1134    2262    1795
River Rch & RM= NC Unknown Strea,Reach-1,7569
     533     763     958     597    1191    2377    1870
Boundary for River Rch & Prof#=NC Unknown Strea,Reach-1,1
Up Type=0
Dn Type=3
Dn Slope=0.001
Boundary for River Rch & Prof#=NC Unknown Strea,Reach-1,2
Up Type=0
Dn Type=3
Dn Slope=0.001
Boundary for River Rch & Prof#=NC Unknown Strea,Reach-1,3
Up Type=0
Dn Type=3
Dn Slope=0.001
Boundary for River Rch & Prof#=NC Unknown Strea,Reach-1,4
Up Type=0
Dn Type=3
Dn Slope=0.001
Boundary for River Rch & Prof#=NC Unknown Strea,Reach-1,5
Up Type=0
Dn Type=3
Dn Slope=0.001
Boundary for River Rch & Prof#=NC Unknown Strea,Reach-1,6
Up Type=0
Dn Type=3
Dn Slope=0.001
Boundary for River Rch & Prof#=NC Unknown Strea,Reach-1,7
Up Type=0
Dn Type=3
Dn Slope=0.001

--- NC Unknown Stream 18.g01 (geometry) ---

Geom Title=Existing Conditions

River Reach=NC Unknown Strea,Reach-1
Reach XY= 30
      1514455.00      6944688.00      1515151.24      6943986.44
      1515454.32      6943277.25      1515254.63      6943067.81
      1515418.44      6942724.36      1515658.43      6942645.79
      1515889.78      6942837.77      1516052.29      6942593.28
      1516268.24      6942624.89      1516671.28      6941870.77
      1516952.09      6941880.10      1516907.84      6941595.89
      1517104.96      6941618.30      1517008.01      6941289.37
      1517347.99      6941038.19      1516906.88      6940782.29
      1517203.92      6940277.45      1517097.19      6939931.79
      1516677.70      6939811.91      1516561.52      6939395.67
      1516258.52      6939386.78      1516227.55      6939164.16
      1516651.48      6938986.54      1516461.99      6938738.22
      1516653.13      6938393.69      1516334.92      6938368.73
      1516249.93      6937843.03      1515760.37      6937590.37
      1516104.45      6937248.64      1515605.00      6936538.00

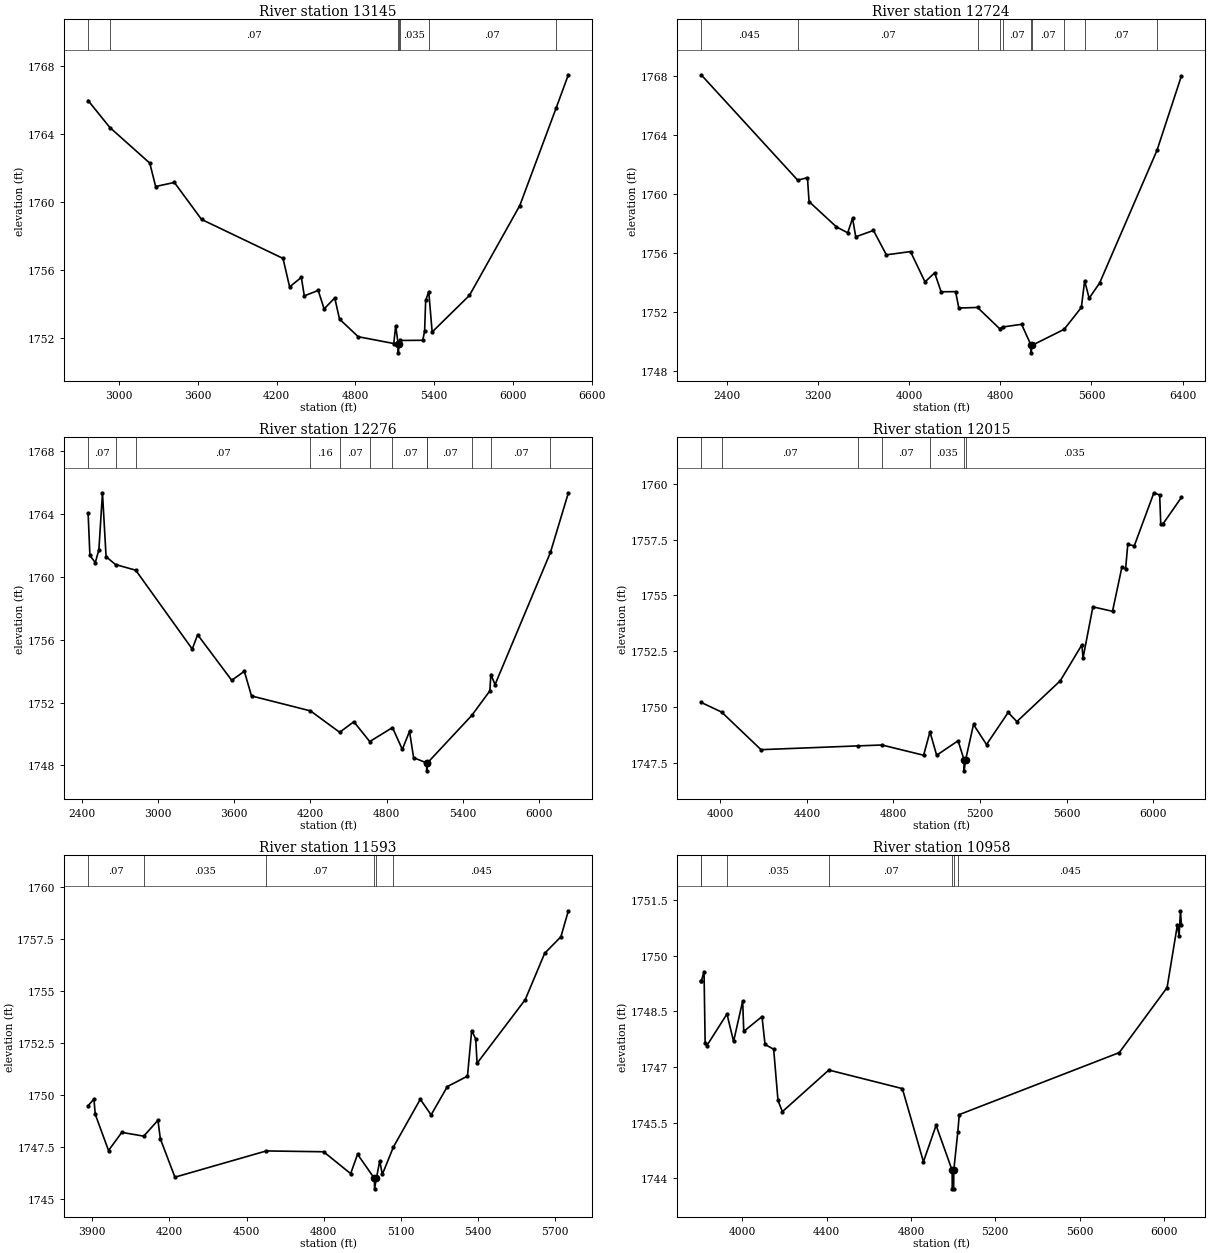
Type RM Length L Ch R = 1,13145,421,421,421
BEGIN DESCRIPTION:
NC Unknown Stream 18 7.0
END DESCRIPTION:
XS GIS Cut Line= 3
      1515955.00      6946288.00      1514955.00      6944288.00
      1513855.02      6943388.02
#Sta/Elev= 30
  2764.2 1765.98  2929.8 1764.39  3233.8 1762.29  3278.5 1760.91  3421.0 1761.15
  3627.9 1758.97  4248.4 1756.67  4298.7 1754.99  4388.1 1755.55  4410.5 1754.46
  4516.7 1754.78  4561.4 1753.69  4642.5 1754.34  4678.8 1753.09  4821.4 1752.05
  5092.1 1751.65  5106.5 1752.70  5125.9 1751.60  5126.3 1751.10  5131.7 1751.60
  5139.9 1751.83  5312.5 1751.84  5326.9 1752.38  5334.8 1754.19  5358.3 1754.71
  5384.3 1752.33  5668.5 1754.49  6051.9 1759.79  6327.6 1765.52  6421.5 1767.50
#Mann=7,-1,0
  2764.2   0.035       0  2929.8    0.07       0  5125.9    0.07       0
  5131.7    0.07       0  5139.9   0.035       0  5358.3    0.07       0
  6327.6   0.045       0
Bank Sta=5125.9,5131.7
Exp/Cntr=0.3,0.1

Type RM Length L Ch R = 1,12724,448,448,448
BEGIN DESCRIPTION:
NC Unknown Stream 18 6.0
END DESCRIPTION:
XS GIS Cut Line= 3
      1517155.02      6945938.02      1515155.00      6943938.00
      1513955.00      6943238.00
#Sta/Elev= 30
  2172.0 1768.06  3019.9 1760.93  3105.4 1761.10  3119.5 1759.48  3360.0 1757.77
  3459.0 1757.37  3501.4 1758.35  3529.7 1757.10  3685.2 1757.53  3798.4 1755.88
  4010.5 1756.10  4137.8 1754.05  4222.6 1754.66  4279.2 1753.38  4406.5 1753.39
  4434.8 1752.28  4598.9 1752.32  4793.7 1750.88  4821.5 1751.00  4986.3 1751.18
  5069.9 1749.75  5070.4 1749.25  5075.7 1749.75  5359.7 1750.84  5511.1 1752.32
  5539.9 1754.13  5579.3 1752.94  5671.9 1753.98  6175.4 1762.95  6389.7 1767.98
#Mann=10,-1,0
  2172.0   0.045       0  3019.9    0.07       0  4598.9   0.035       0
  4793.7    0.16       0  4821.5    0.07       0  5069.9    0.07       0
  5075.7    0.07       0  5359.7   0.035       0  5539.9    0.07       0
  6175.4   0.045       0
Bank Sta=5069.9,5075.7
Exp/Cntr=0.3,0.1

Type RM Length L Ch R = 1,12276,261,261,261
BEGIN DESCRIPTION:
NC Unknown Stream 18 5.0
END DESCRIPTION:
XS GIS Cut Line= 3
      1517104.97      6945337.97      1515305.00      6943538.00
      1514104.97      6943237.99
#Sta/Elev= 30
  2449.8 1764.03  2463.9 1761.35  2506.3 1760.89  2534.6 1761.71  2562.9 1765.33
  2591.2 1761.27  2665.5 1760.77  2824.8 1760.41  3270.0 1755.40  3312.4 1756.31
  3581.1 1753.41  3680.1 1753.99  3736.7 1752.42  4201.1 1751.47  4431.1 1750.11
  4542.8 1750.78  4668.1 1749.52  4847.1 1750.41  4924.6 1749.02  4981.2 1750.17
  5013.4 1748.50  5116.1 1748.16  5116.6 1747.66  5122.0 1748.16  5471.5 1751.18
  5613.8 1752.74  5622.1 1753.78  5655.0 1753.14  6091.2 1761.54  6232.3 1765.32
#Mann=12,-1,0
  2449.8    0.07       0  2665.5   0.045       0  2824.8    0.07       0
  4201.1    0.16       0  4431.1    0.07       0  4668.1    0.16       0
  4847.1    0.07       0  5116.1    0.07       0  5122.0    0.07       0
  5471.5   0.035       0  5622.1    0.07       0  6091.2   0.035       0
Bank Sta=5116.1,5122
Exp/Cntr=0.3,0.1

Type RM Length L Ch R = 1,12015,422,422,422
BEGIN DESCRIPTION:
Mapping XS 0fd8811f
END DESCRIPTION:
XS GIS Cut Line= 4
      1516510.94      6943385.80      1515555.20      6943325.91
      1514896.34      6943289.45      1514298.73      6943221.89
#Sta/Elev= 30
  3911.8 1750.20  4005.9 1749.77  4188.3 1748.08  4636.5 1748.25  4746.9 1748.29
  4939.7 1747.83  4968.9 1748.88  4999.8 1747.83  5099.0 1748.48  5126.2 1747.63
  5126.7 1747.13  5133.8 1747.63  5170.1 1749.21  5230.2 1748.31  5330.3 1749.75
  5370.4 1749.34  5570.9 1751.17  5671.1 1752.79  5676.1 1752.19  5721.8 1754.49
  5812.4 1754.29  5855.7 1756.27  5872.8 1756.19  5882.9 1757.29  5913.0 1757.23
  6003.6 1759.61  6030.3 1759.51  6035.3 1758.22  6043.9 1758.19  6130.7 1759.40
#Mann=7,-1,0
  3911.8   0.045       0  4005.9    0.07       0  4636.5    0.16       0
  4746.9    0.07       0  4968.9   0.035       0  5126.2   0.035       0
  5133.8   0.035       0
Bank Sta=5126.2,5133.8
Exp/Cntr=0.3,0.1

Type RM Length L Ch R = 1,11593,635,635,635
BEGIN DESCRIPTION:
Mapping XS 1309c481
END DESCRIPTION:
XS GIS Cut Line= 3
      1516351.42      6943267.49      1515435.40      6943088.93
      1514547.42      6942802.48
#Sta/Elev= 30
  3884.4 1749.49  3907.0 1749.81  3912.1 1749.08  3963.7 1747.34  4015.3 1748.21
  4100.5 1748.03  4155.8 1748.79  4165.1 1747.90  4221.8 1746.06  4576.9 1747.32
  4799.6 1747.28  4904.7 1746.23  4931.5 1747.16  4997.0 1746.00  4997.5 1745.50
  5004.8 1746.00  5017.7 1746.85  5027.7 1746.19  5070.9 1747.51  5175.3 1749.80
  5217.4 1749.05  5280.4 1750.41  5358.7 1750.91  5375.0 1753.10  5390.7 1752.70
  5396.0 1751.53  5583.0 1754.58  5658.7 1756.81  5721.7 1757.60  5750.7 1758.85
#Mann=6,-1,0
  3884.4    0.07       0  4100.5   0.035       0  4576.9    0.07       0
  4997.0    0.07       0  5004.8    0.07       0  5070.9   0.045       0
Bank Sta=4997,5004.8
Exp/Cntr=0.3,0.1

Type RM Length L Ch R = 1,10958,603,603,603
BEGIN DESCRIPTION:
Mapping XS 5d56d48f
END DESCRIPTION:
XS GIS Cut Line= 4
      1516390.47      6943256.64      1515658.22      6943091.70
      1515663.44      6942514.45      1515035.24      6941801.76
#Sta/Elev= 30
  3805.1 1749.32  3805.6 1749.31  3818.7 1749.57  3823.9 1747.66  3831.2 1747.57
  3927.5 1748.43  3958.8 1747.69  4002.0 1748.78  4007.1 1747.96  4093.6 1748.36
  4108.0 1747.61  4149.0 1747.48  4169.5 1746.10  4190.4 1745.80  4410.7 1746.92
  4759.4 1746.42  4859.4 1744.45  4919.4 1745.43  4995.5 1744.22  4996.0 1743.72
  5002.8 1743.72  5003.3 1744.22  5022.2 1745.24  5029.4 1745.72  5788.3 1747.39
  6015.0 1749.14  6064.3 1750.84  6071.9 1750.53  6078.6 1751.21  6083.0 1750.83
#Mann=7,-1,0
  3805.1   0.045       0  3805.6    0.07       0  3927.5   0.035       0
  4410.7    0.07       0  4995.5    0.07       0  5003.3    0.07       0
  5022.2   0.045       0
Bank Sta=4995.5,5003.3
Exp/Cntr=0.3,0.1

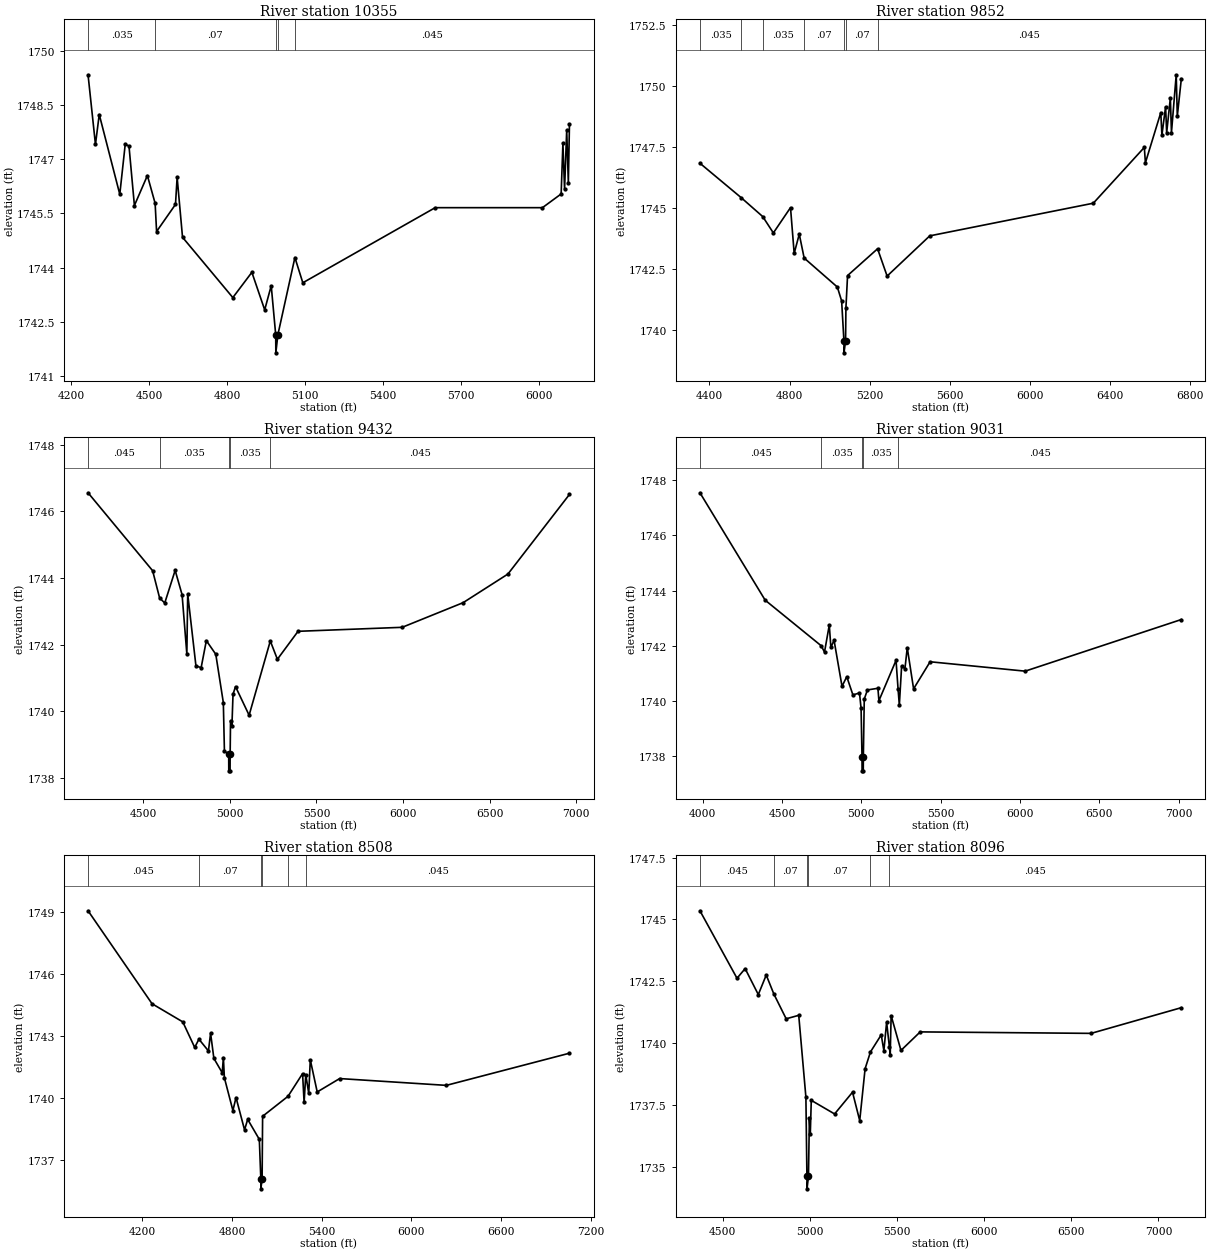
Type RM Length L Ch R = 1,10355,503,503,503
BEGIN DESCRIPTION:
Mapping XS a63e8eb5
END DESCRIPTION:
XS GIS Cut Line= 4
      1516425.17      6943228.44      1516073.43      6942760.80
      1515948.43      6942422.26      1515229.68      6941867.95
#Sta/Elev= 30
  4265.2 1749.34  4293.7 1747.41  4308.3 1748.24  4387.4 1746.03  4408.3 1747.41
  4422.8 1747.37  4443.7 1745.72  4493.7 1746.55  4523.5 1745.78  4529.1 1745.00
  4601.9 1745.75  4608.2 1746.50  4629.0 1744.84  4822.7 1743.17  4896.0 1743.87
  4945.4 1742.83  4970.5 1743.50  4987.8 1742.14  4988.3 1741.64  4996.1 1742.14
  5061.7 1744.28  5092.2 1743.58  5601.9 1745.66  6014.9 1745.66  6086.9 1746.04
  6093.7 1747.44  6100.1 1746.17  6108.3 1747.81  6114.6 1746.34  6118.9 1747.97
#Mann=5,-1,0
  4265.2   0.035       0  4523.5    0.07       0  4987.8    0.07       0
  4996.1    0.07       0  5061.7   0.045       0
Bank Sta=4987.8,4996.1
Exp/Cntr=0.3,0.1

Type RM Length L Ch R = 1,9852,420,420,420
BEGIN DESCRIPTION:
Mapping XS 2b4080f9
END DESCRIPTION:
XS GIS Cut Line= 4
      1516505.71      6943055.05      1516445.82      6942575.91
      1516201.03      6942169.66      1514864.80      6941613.83
#Sta/Elev= 30
  4352.3 1746.83  4558.0 1745.42  4666.1 1744.64  4719.0 1743.97  4804.7 1745.01
  4823.0 1743.13  4848.4 1743.92  4872.8 1742.94  5038.6 1741.75  5060.0 1741.18
  5071.4 1739.55  5071.9 1739.05  5079.7 1739.55  5081.4 1740.89  5089.6 1742.22
  5239.5 1743.32  5287.2 1742.20  5500.1 1743.85  6317.0 1745.19  6571.8 1747.48
  6577.2 1746.85  6654.1 1748.91  6659.6 1747.98  6678.0 1749.15  6683.4 1748.08
  6701.8 1749.51  6707.3 1748.09  6731.1 1750.46  6736.5 1748.76  6756.7 1750.30
#Mann=7,-1,0
  4352.3   0.035       0  4558.0   0.045       0  4666.1   0.035       0
  4872.8    0.07       0  5071.4    0.07       0  5079.7    0.07       0
  5239.5   0.045       0
Bank Sta=5071.4,5079.7
Exp/Cntr=0.3,0.1

Type RM Length L Ch R = 1,9432,401,401,401
BEGIN DESCRIPTION:
Mapping XS 2f7e57e0
END DESCRIPTION:
XS GIS Cut Line= 4
      1516565.61      6942940.50      1516609.88      6942203.51
      1516313.01      6941828.51      1514801.85      6941418.51
#Sta/Elev= 30
  4179.7 1746.56  4552.9 1744.22  4593.4 1743.40  4623.0 1743.25  4683.1 1744.23
  4723.2 1743.50  4750.7 1741.72  4755.7 1743.52  4803.3 1741.36  4833.4 1741.31
  4863.4 1742.12  4918.0 1741.71  4961.6 1740.26  4967.9 1738.80  4992.6 1738.71
  4993.1 1738.21  5000.5 1738.21  5001.0 1738.71  5003.2 1739.72  5011.2 1739.55
  5017.6 1740.51  5032.0 1740.74  5110.6 1739.88  5233.1 1742.11  5274.0 1741.56
  5393.4 1742.40  5995.3 1742.52  6347.5 1743.26  6606.5 1744.12  6962.1 1746.51
#Mann=5,-1,0
  4179.7   0.045       0  4593.4   0.035       0  4992.6   0.035       0
  5001.0   0.035       0  5233.1   0.045       0
Bank Sta=4992.6,5001
Exp/Cntr=0.3,0.1

Type RM Length L Ch R = 1,9031,523,523,523
BEGIN DESCRIPTION:
Mapping XS 6c8046a9
END DESCRIPTION:
XS GIS Cut Line= 5
      1516885.92      6942844.12      1516773.95      6942133.20
      1516753.11      6941763.41      1516573.43      6941625.39
      1514923.45      6941151.61
#Sta/Elev= 30
  3983.7 1747.54  4394.8 1743.65  4747.7 1742.00  4768.6 1741.77  4798.7 1742.75
  4808.8 1741.94  4828.8 1742.20  4878.9 1740.53  4908.9 1740.88  4947.6 1740.22
  4989.0 1740.29  4999.1 1739.73  5004.9 1737.97  5005.4 1737.47  5012.8 1737.47
  5013.3 1737.97  5019.1 1740.07  5039.1 1740.40  5105.1 1740.46  5111.4 1740.01
  5219.3 1741.47  5232.0 1740.44  5240.1 1739.85  5254.6 1741.27  5275.4 1741.17
  5290.0 1741.93  5329.9 1740.44  5434.0 1741.42  6032.9 1741.08  7017.0 1742.95
#Mann=5,-1,0
  3983.7   0.045       0  4747.7   0.035       0  5004.9   0.035       0
  5013.3   0.035       0  5232.0   0.045       0
Bank Sta=5004.9,5013.3
Exp/Cntr=0.3,0.1

Type RM Length L Ch R = 1,8508,412,412,412
BEGIN DESCRIPTION:
Mapping XS bf7d9bf1
END DESCRIPTION:
XS GIS Cut Line= 4
      1517539.56      6942573.27      1517190.61      6941940.49
      1516859.88      6941549.86      1514938.22      6941039.22
#Sta/Elev= 30
  3836.0 1749.07  4264.4 1744.56  4470.1 1743.68  4550.0 1742.44  4578.3 1742.84
  4642.0 1742.27  4656.3 1743.13  4678.3 1741.91  4734.3 1741.21  4742.0 1741.95
  4748.6 1740.97  4805.7 1739.38  4826.6 1740.01  4883.7 1738.44  4904.6 1738.95
  4982.6 1737.98  4992.5 1736.08  4993.0 1735.58  5001.3 1736.08  5004.6 1739.10
  5174.8 1740.07  5272.1 1741.17  5282.4 1739.77  5293.5 1741.12  5313.5 1740.21
  5323.8 1741.84  5370.1 1740.28  5520.4 1740.93  6234.4 1740.60  7058.8 1742.16
#Mann=6,-1,0
  3836.0   0.045       0  4578.3    0.07       0  4992.5    0.07       0
  5001.3    0.07       0  5174.8   0.035       0  5293.5   0.045       0
Bank Sta=4992.5,5001.3
Exp/Cntr=0.3,0.1

Type RM Length L Ch R = 1,8096,527,527,527
BEGIN DESCRIPTION:
Mapping XS fdb5e64e
END DESCRIPTION:
XS GIS Cut Line= 3
      1517693.22      6941659.24      1517326.03      6941497.78
      1515031.94      6940938.93
#Sta/Elev= 30
  4369.1 1745.35  4581.8 1742.62  4628.5 1743.01  4704.0 1741.96  4749.5 1742.75
  4793.4 1741.98  4863.9 1740.98  4936.0 1741.12  4977.1 1737.81  4983.0 1734.60
  4983.5 1734.10  4991.8 1734.60  4997.1 1736.95  5002.3 1736.31  5008.0 1737.68
  5141.8 1737.13  5244.7 1738.01  5285.9 1736.86  5316.8 1738.96  5347.6 1739.64
  5409.4 1740.33  5424.5 1739.69  5440.3 1740.84  5456.4 1739.83  5460.9 1739.50
  5466.2 1741.11  5522.6 1739.70  5633.1 1740.45  6613.6 1740.39  7131.4 1741.43
#Mann=6,-1,0
  4369.1   0.045       0  4793.4    0.07       0  4983.0    0.07       0
  4991.8    0.07       0  5347.6   0.035       0  5456.4   0.045       0
Bank Sta=4983,4991.8
Exp/Cntr=0.3,0.1

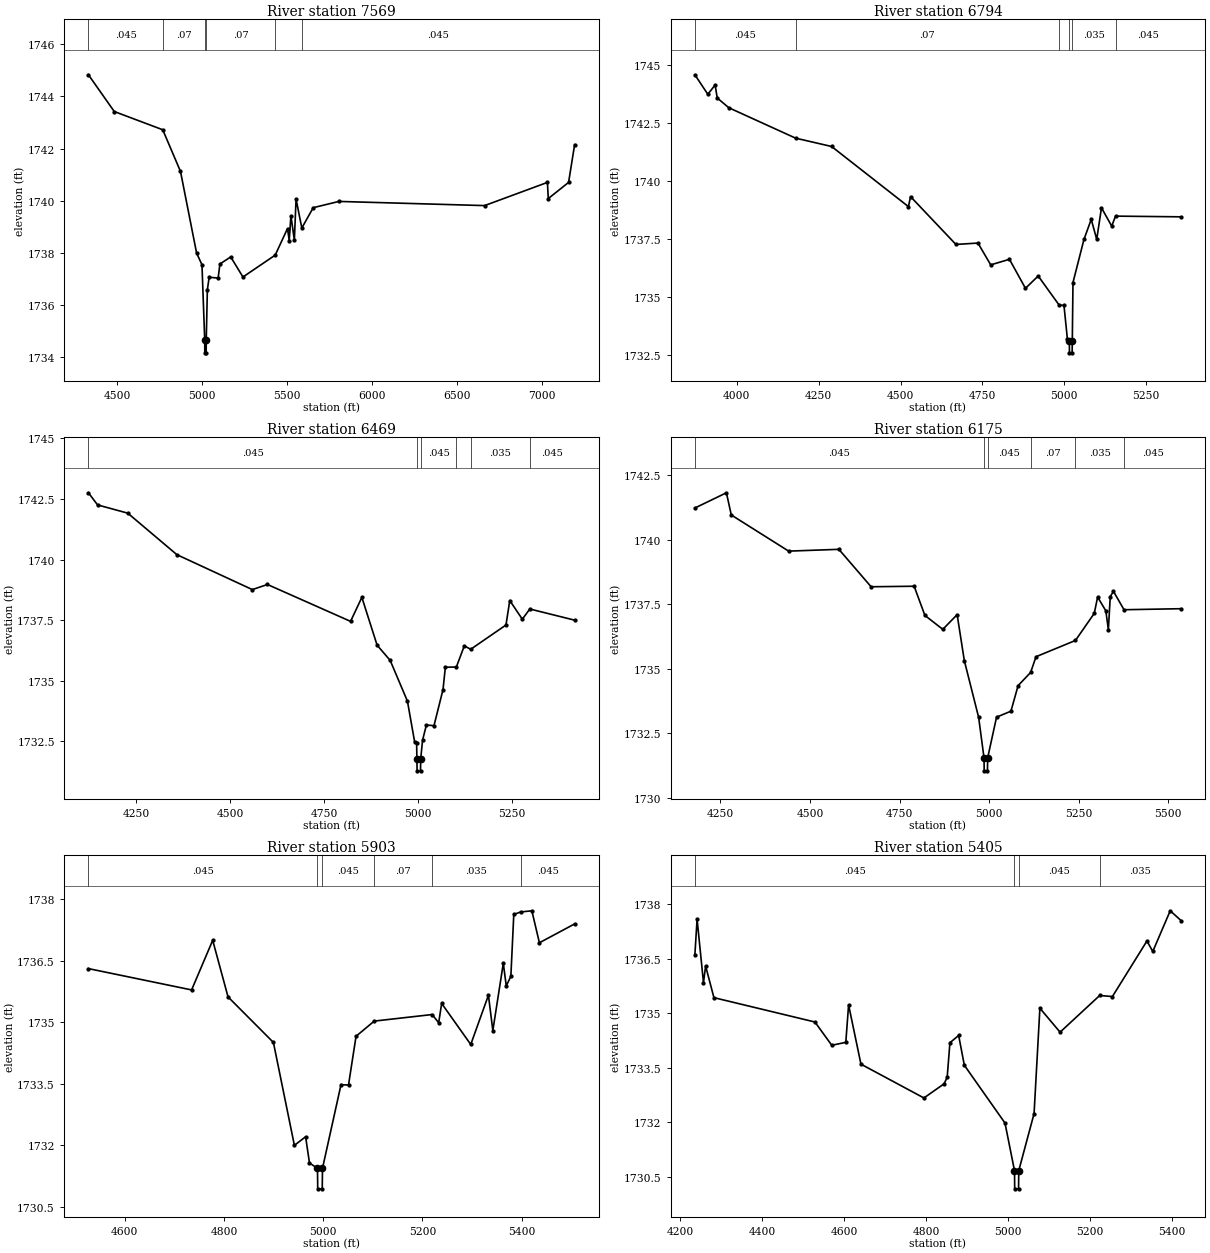
Type RM Length L Ch R = 1,7569,775,775,775
BEGIN DESCRIPTION:
Mapping XS 3a06a990
END DESCRIPTION:
XS GIS Cut Line= 4
      1517857.25      6941453.50      1517474.47      6941245.18
      1516857.28      6941036.84      1515099.62      6940823.96
#Sta/Elev= 30
  4332.1 1744.83  4484.0 1743.42  4769.0 1742.72  4873.3 1741.12  4967.9 1737.99
  4999.5 1737.54  5015.6 1734.66  5016.1 1734.16  5024.2 1734.16  5024.7 1734.66
  5031.2 1736.58  5041.7 1737.06  5094.5 1737.03  5105.1 1737.57  5168.4 1737.84
  5240.4 1737.07  5430.0 1737.91  5502.2 1738.93  5512.3 1738.47  5522.3 1739.42
  5542.5 1738.49  5552.5 1740.06  5586.4 1738.95  5653.3 1739.73  5804.4 1739.97
  6660.6 1739.81  7029.8 1740.70  7034.9 1740.08  7154.2 1740.70  7189.8 1742.15
#Mann=6,-1,0
  4332.1   0.045       0  4769.0    0.07       0  5015.6    0.07       0
  5024.7    0.07       0  5430.0   0.035       0  5586.4   0.045       0
Bank Sta=5015.6,5024.7
Exp/Cntr=0.3,0.1

Type RM Length L Ch R = 1,6794,325,325,325
BEGIN DESCRIPTION:
Mapping XS ae1fcf4c
END DESCRIPTION:
XS GIS Cut Line= 4
      1517883.36      6941255.62      1517424.99      6940891.01
      1516747.90      6940695.70      1516555.21      6940672.26
#Sta/Elev= 30
  3872.2 1744.59  3911.7 1743.75  3934.0 1744.15  3940.5 1743.59  3975.8 1743.17
  4179.7 1741.86  4289.7 1741.50  4524.2 1738.91  4530.7 1739.34  4669.2 1737.28
  4736.5 1737.34  4775.4 1736.40  4832.6 1736.64  4881.5 1735.39  4920.4 1735.92
  4984.2 1734.67  4999.1 1734.65  5009.5 1733.21  5015.4 1733.11  5015.9 1732.61
  5024.0 1732.61  5024.5 1733.11  5026.6 1735.64  5060.2 1737.50  5082.3 1738.36
  5099.1 1737.50  5113.6 1738.86  5144.8 1738.07  5156.5 1738.50  5356.7 1738.47
#Mann=6,-1,0
  3872.2   0.045       0  4179.7    0.07       0  4984.2   0.035       0
  5015.4   0.035       0  5024.5   0.035       0  5156.5   0.045       0
Bank Sta=5015.4,5024.5
Exp/Cntr=0.3,0.1

Type RM Length L Ch R = 1,6469,294,294,294
BEGIN DESCRIPTION:
Mapping XS 458c7eaa
END DESCRIPTION:
XS GIS Cut Line= 3
      1517969.24      6940596.74      1517315.61      6940523.82
      1516683.91      6940432.84
#Sta/Elev= 30
  4122.3 1742.75  4146.7 1742.25  4227.2 1741.91  4358.0 1740.20  4559.2 1738.76
  4599.5 1738.97  4821.0 1737.45  4851.1 1738.44  4891.7 1736.47  4926.6 1735.84
  4972.6 1734.16  4992.0 1732.46  4997.0 1732.44  4997.8 1731.79  4998.3 1731.29
  5007.4 1731.29  5007.9 1731.79  5013.0 1732.56  5023.1 1733.18  5043.3 1733.15
  5067.4 1734.64  5073.6 1735.56  5103.0 1735.57  5124.1 1736.44  5141.2 1736.30
  5235.2 1737.30  5245.3 1738.31  5278.7 1737.54  5298.8 1737.96  5418.2 1737.50
#Mann=6,-1,0
  4122.3   0.045       0  4997.8   0.045       0  5007.9   0.045       0
  5103.0    0.07       0  5141.2   0.035       0  5298.8   0.045       0
Bank Sta=4997.8,5007.9
Exp/Cntr=0.3,0.1

Type RM Length L Ch R = 1,6175,272,272,272
BEGIN DESCRIPTION:
Mapping XS 9bee73cb
END DESCRIPTION:
XS GIS Cut Line= 3
      1518026.59      6940255.60      1516951.03      6940224.34
      1516689.00      6940325.52
#Sta/Elev= 30
  4178.9 1741.22  4266.9 1741.81  4280.5 1740.95  4440.6 1739.55  4580.7 1739.62
  4670.7 1738.17  4790.8 1738.19  4820.8 1737.06  4870.8 1736.52  4910.8 1737.09
  4930.8 1735.31  4970.8 1733.11  4985.8 1731.54  4986.3 1731.04  4995.4 1731.04
  4995.9 1731.54  5020.8 1733.12  5060.9 1733.35  5080.9 1734.34  5115.8 1734.85
  5130.9 1735.46  5240.9 1736.09  5293.5 1737.14  5302.8 1737.77  5325.7 1737.24
  5332.8 1736.51  5338.1 1737.79  5347.1 1737.99  5376.5 1737.28  5535.8 1737.32
#Mann=6,-1,0
  4178.9   0.045       0  4985.8   0.045       0  4995.9   0.045       0
  5115.8    0.07       0  5240.9   0.035       0  5376.5   0.045       0
Bank Sta=4985.8,4995.9
Exp/Cntr=0.3,0.1

Type RM Length L Ch R = 1,5903,498,498,498
BEGIN DESCRIPTION:
Mapping XS d1381720
END DESCRIPTION:
XS GIS Cut Line= 3
      1517469.26      6939698.31      1517266.13      6939893.61
      1516678.81      6940270.44
#Sta/Elev= 30
  4527.0 1736.31  4734.9 1735.79  4777.4 1737.00  4808.3 1735.62  4899.7 1734.51
  4942.0 1732.00  4964.6 1732.21  4972.4 1731.57  4988.5 1731.44  4989.0 1730.94
  4998.1 1730.94  4998.6 1731.44  5035.9 1733.48  5051.0 1733.47  5066.2 1734.66
  5102.8 1735.03  5219.4 1735.19  5232.7 1734.99  5238.7 1735.46  5297.3 1734.46
  5332.9 1735.66  5341.8 1734.80  5362.9 1736.44  5368.8 1735.89  5378.1 1736.12
  5384.0 1737.63  5397.6 1737.69  5420.4 1737.72  5435.6 1736.94  5506.6 1737.40
#Mann=6,-1,0
  4527.0   0.045       0  4988.5   0.045       0  4998.6   0.045       0
  5102.8    0.07       0  5219.4   0.035       0  5397.6   0.045       0
Bank Sta=4988.5,4998.6
Exp/Cntr=0.3,0.1

Type RM Length L Ch R = 1,5405,339,339,339
BEGIN DESCRIPTION:
Mapping XS da7150fa
END DESCRIPTION:
XS GIS Cut Line= 3
      1517430.23      6939568.09      1516893.74      6939695.70
      1516422.40      6940122.77
#Sta/Elev= 30
  4235.6 1736.61  4241.0 1737.59  4256.6 1735.84  4261.8 1736.30  4282.1 1735.43
  4528.8 1734.76  4569.9 1734.12  4604.2 1734.20  4611.0 1735.23  4641.2 1733.60
  4795.0 1732.67  4844.3 1733.06  4851.8 1733.24  4858.5 1734.19  4879.8 1734.39
  4893.7 1733.57  4993.0 1731.98  5016.2 1730.67  5016.7 1730.17  5026.1 1730.17
  5026.6 1730.67  5064.0 1732.24  5078.2 1735.14  5127.5 1734.48  5224.3 1735.49
  5255.3 1735.46  5339.7 1736.99  5353.9 1736.70  5396.5 1737.82  5423.1 1737.55
#Mann=4,-1,0
  4235.6   0.045       0  5016.2   0.045       0  5026.6   0.045       0
  5224.3   0.035       0
Bank Sta=5016.2,5026.6
Exp/Cntr=0.3,0.1

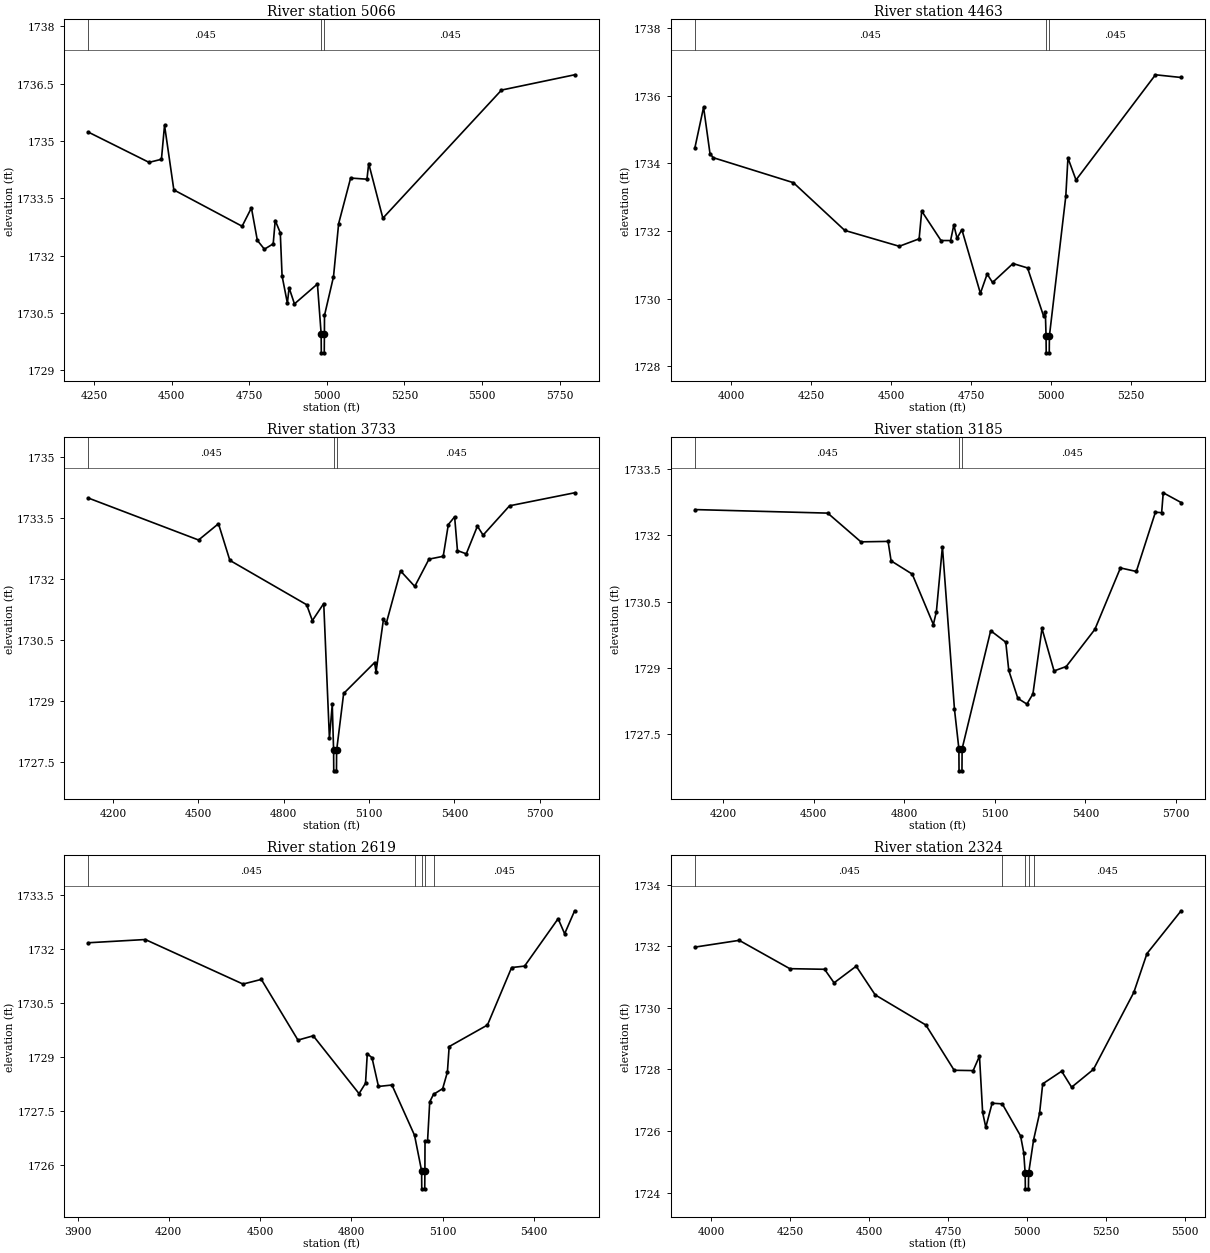
Type RM Length L Ch R = 1,5066,603,603,603
BEGIN DESCRIPTION:
Mapping XS 16d0c3d8
END DESCRIPTION:
XS GIS Cut Line= 4
      1517370.30      6939453.51      1516839.05      6939456.11
      1516122.90      6939792.05      1515883.34      6939841.53
#Sta/Elev= 30
  4231.4 1735.23  4426.7 1734.44  4466.7 1734.52  4476.7 1735.41  4506.7 1733.72
  4726.7 1732.77  4756.7 1733.25  4775.8 1732.40  4798.6 1732.17  4826.9 1732.31
  4833.4 1732.92  4849.7 1732.60  4855.5 1731.47  4872.6 1730.76  4878.1 1731.16
  4895.4 1730.74  4969.4 1731.26  4981.4 1729.96  4981.9 1729.46  4991.4 1729.46
  4991.9 1729.96  4992.2 1730.44  5021.2 1731.45  5037.8 1732.84  5076.4 1734.03
  5129.1 1734.00  5134.6 1734.41  5180.3 1732.98  5562.6 1736.33  5798.3 1736.73
#Mann=3,-1,0
  4231.4   0.045       0  4981.4   0.045       0  4991.9   0.045       0
Bank Sta=4981.4,4991.9
Exp/Cntr=0.3,0.1

Type RM Length L Ch R = 1,4463,730,730,730
BEGIN DESCRIPTION:
Mapping XS 694f7689
END DESCRIPTION:
XS GIS Cut Line= 3
      1517352.10      6939167.05      1516523.95      6939221.74
      1515868.82      6939434.92
#Sta/Elev= 30
  3887.0 1734.46  3914.2 1735.66  3934.2 1734.29  3944.2 1734.17  4194.8 1733.43
  4355.1 1732.02  4525.5 1731.55  4587.5 1731.77  4595.6 1732.59  4655.8 1731.72
  4685.8 1731.72  4695.9 1732.18  4705.9 1731.79  4721.1 1732.04  4778.9 1730.16
  4800.0 1730.73  4816.9 1730.48  4880.7 1731.04  4926.2 1730.91  4976.5 1729.48
  4981.8 1729.61  4984.0 1728.90  4984.5 1728.40  4994.0 1728.40  4994.5 1728.90
  5045.7 1733.03  5052.4 1734.16  5077.6 1733.51  5325.8 1736.62  5405.9 1736.54
#Mann=3,-1,0
  3887.0   0.045       0  4984.0   0.045       0  4994.5   0.045       0
Bank Sta=4984,4994.5
Exp/Cntr=0.3,0.1

Type RM Length L Ch R = 1,3733,548,548,548
BEGIN DESCRIPTION:
Mapping XS 159bc280
END DESCRIPTION:
XS GIS Cut Line= 3
      1517542.13      6938937.88      1516273.95      6938906.64
      1515833.85      6938877.99
#Sta/Elev= 30
  4113.1 1733.98  4500.4 1732.95  4570.4 1733.35  4610.4 1732.45  4880.5 1731.36
  4900.5 1730.97  4940.5 1731.39  4960.5 1728.08  4970.5 1728.91  4975.2 1727.78
  4975.7 1727.28  4985.3 1727.28  4985.8 1727.78  5010.5 1729.18  5119.4 1729.94
  5124.4 1729.71  5150.5 1731.00  5160.6 1730.91  5210.6 1732.19  5260.6 1731.81
  5310.6 1732.48  5360.6 1732.55  5378.6 1733.33  5400.7 1733.52  5410.7 1732.69
  5441.7 1732.61  5480.8 1733.29  5500.9 1733.07  5593.8 1733.79  5822.7 1734.11
#Mann=3,-1,0
  4113.1   0.045       0  4975.2   0.045       0  4985.8   0.045       0
Bank Sta=4975.2,4985.8
Exp/Cntr=0.3,0.1

Type RM Length L Ch R = 1,3185,566,566,566
BEGIN DESCRIPTION:
Mapping XS 57726bf6
END DESCRIPTION:
XS GIS Cut Line= 3
      1517495.27      6938555.07      1516279.15      6938536.84
      1515904.19      6938661.83
#Sta/Elev= 30
  4105.9 1732.58  4546.2 1732.50  4656.2 1731.85  4746.2 1731.86  4756.2 1731.42
  4826.3 1731.12  4896.3 1729.98  4906.3 1730.27  4926.3 1731.74  4966.3 1728.06
  4980.9 1727.17  4981.4 1726.67  4991.1 1726.67  4991.6 1727.17  5086.3 1729.84
  5136.3 1729.58  5146.3 1728.94  5176.3 1728.31  5206.3 1728.18  5226.3 1728.41
  5256.3 1729.89  5296.3 1728.93  5336.7 1729.03  5431.6 1729.87  5516.3 1731.26
  5569.0 1731.18  5632.2 1732.52  5652.9 1732.51  5658.2 1732.96  5717.4 1732.74
#Mann=3,-1,0
  4105.9   0.045       0  4980.9   0.045       0  4991.6   0.045       0
Bank Sta=4980.9,4991.6
Exp/Cntr=0.3,0.1

Type RM Length L Ch R = 1,2619,295,295,295
BEGIN DESCRIPTION:
Mapping XS 151cd55f
END DESCRIPTION:
XS GIS Cut Line= 3
      1517331.27      6938135.80      1516531.76      6938206.11
      1515852.05      6938620.19
#Sta/Elev= 30
  3935.8 1732.18  4122.8 1732.27  4444.0 1731.03  4504.3 1731.16  4624.7 1729.47
  4674.9 1729.59  4825.5 1727.98  4846.8 1728.27  4852.6 1729.09  4868.1 1728.98
  4889.4 1728.18  4933.7 1728.22  5008.0 1726.82  5031.2 1725.83  5031.7 1725.33
  5041.5 1725.33  5042.0 1725.83  5042.4 1726.65  5050.8 1726.67  5057.9 1727.75
  5070.3 1727.96  5100.5 1728.12  5116.0 1728.58  5121.8 1729.29  5247.7 1729.89
  5327.1 1731.49  5369.7 1731.53  5480.1 1732.85  5501.4 1732.43  5534.3 1733.07
#Mann=5,-1,0
  3935.8   0.045       0  5008.0    0.07       0  5031.2   0.045       0
  5042.0    0.07       0  5070.3   0.045       0
Bank Sta=5031.2,5042
Exp/Cntr=0.3,0.1

Type RM Length L Ch R = 1,2324,369,369,369
BEGIN DESCRIPTION:
Mapping XS 53575678
END DESCRIPTION:
XS GIS Cut Line= 4
      1517305.25      6938021.22      1516651.55      6938049.86
      1516049.99      6938075.91      1515831.27      6938255.57
#Sta/Elev= 30
  3948.5 1731.97  4088.9 1732.19  4249.0 1731.27  4359.1 1731.25  4389.2 1730.81
  4459.2 1731.35  4519.3 1730.42  4679.9 1729.44  4769.5 1727.97  4829.6 1727.96
  4849.6 1728.43  4859.6 1726.60  4869.6 1726.12  4889.6 1726.90  4921.7 1726.88
  4979.7 1725.84  4989.7 1725.30  4994.3 1724.62  4994.8 1724.12  5004.6 1724.12
  5005.1 1724.62  5020.9 1725.71  5039.8 1726.57  5049.8 1727.53  5109.8 1727.94
  5141.3 1727.42  5210.5 1728.00  5338.3 1730.50  5379.9 1731.76  5488.0 1733.15
#Mann=5,-1,0
  3948.5   0.045       0  4921.7    0.07       0  4994.3    0.07       0
  5005.1    0.07       0  5020.9   0.045       0
Bank Sta=4994.3,5005.1
Exp/Cntr=0.3,0.1

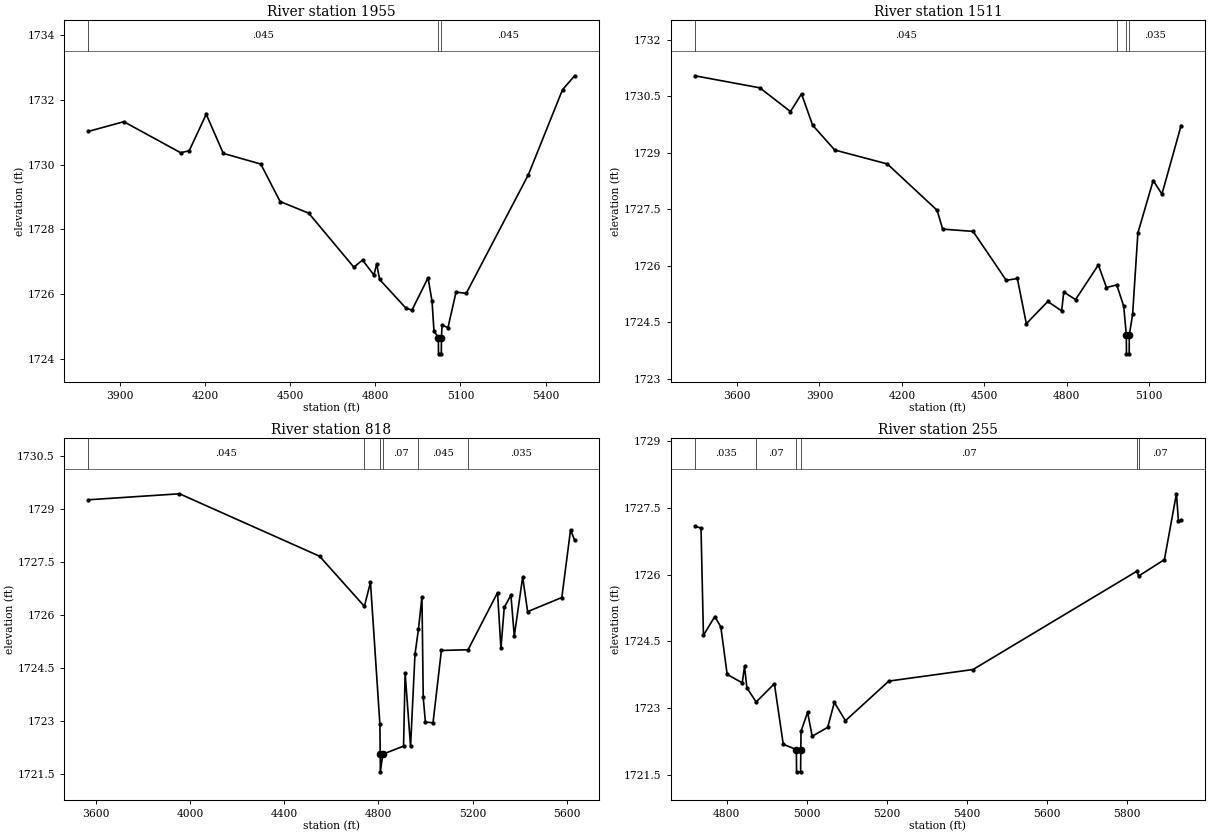
Type RM Length L Ch R = 1,1955,444,444,444
BEGIN DESCRIPTION:
Mapping XS 3766dc9c
END DESCRIPTION:
XS GIS Cut Line= 3
      1517289.56      6937779.03      1516242.70      6937716.53
      1515800.39      6938213.47
#Sta/Elev= 30
  3788.7 1731.03  3913.5 1731.33  4113.8 1730.37  4143.9 1730.43  4204.0 1731.56
  4264.1 1730.35  4396.3 1730.02  4464.5 1728.86  4565.4 1728.50  4724.4 1726.83
  4755.0 1727.05  4795.1 1726.59  4805.1 1726.93  4815.1 1726.45  4907.3 1725.57
  4929.1 1725.50  4985.9 1726.50  5000.0 1725.78  5006.8 1724.86  5022.3 1724.65
  5022.8 1724.15  5032.7 1724.15  5033.2 1724.65  5035.3 1725.04  5056.2 1724.96
  5084.6 1726.06  5120.5 1726.02  5339.6 1729.69  5460.0 1732.32  5502.7 1732.75
#Mann=3,-1,0
  3788.7   0.045       0  5022.3   0.045       0  5033.2   0.045       0
Bank Sta=5022.3,5033.2
Exp/Cntr=0.3,0.1

Type RM Length L Ch R = 1,1511,693,693,693
BEGIN DESCRIPTION:
Mapping XS d7db0e69
END DESCRIPTION:
XS GIS Cut Line= 4
      1517310.42      6937690.49      1515974.47      6937536.84
      1515724.47      6937638.41      1515672.60      6937783.62
#Sta/Elev= 30
  3447.0 1731.04  3683.3 1730.72  3794.7 1730.09  3835.0 1730.56  3875.2 1729.73
  3955.7 1729.07  4147.0 1728.70  4328.2 1727.47  4348.3 1726.97  4459.0 1726.91
  4579.8 1725.61  4620.1 1725.66  4652.8 1724.46  4730.8 1725.05  4781.2 1724.80
  4789.0 1725.30  4831.8 1725.10  4914.8 1726.02  4944.3 1725.42  4981.7 1725.49
  5007.1 1724.92  5016.5 1724.16  5017.0 1723.66  5026.9 1723.66  5027.4 1724.16
  5039.4 1724.71  5058.6 1726.87  5114.3 1728.26  5146.1 1727.90  5215.8 1729.72
#Mann=4,-1,0
  3447.0   0.045       0  4981.7   0.035       0  5016.5   0.035       0
  5027.4   0.035       0
Bank Sta=5016.5,5027.4
Exp/Cntr=0.3,0.1

Type RM Length L Ch R = 1,818,563,563,563
BEGIN DESCRIPTION:
Mapping XS f3a5f726
END DESCRIPTION:
XS GIS Cut Line= 6
      1517451.06      6937143.62      1516206.24      6937099.34
      1515971.86      6937193.09      1515780.90      6937323.13
      1515671.52      6937441.18      1515636.81      6937611.28
#Sta/Elev= 30
  3569.2 1729.26  3955.8 1729.43  4550.7 1727.66  4740.8 1726.24  4766.7 1726.92
  4806.7 1722.90  4808.1 1722.05  4808.6 1721.55  4819.2 1722.05  4907.2 1722.28
  4913.8 1724.35  4936.9 1722.27  4955.7 1724.88  4970.4 1725.59  4985.3 1726.51
  4990.7 1723.66  4999.9 1722.96  5032.2 1722.94  5067.8 1724.99  5181.1 1725.01
  5306.3 1726.63  5320.5 1725.05  5334.7 1726.21  5363.0 1726.56  5377.2 1725.40
  5412.9 1727.07  5433.9 1726.09  5579.1 1726.49  5616.2 1728.41  5633.5 1728.11
#Mann=6,-1,0
  3569.2   0.045       0  4740.8    0.07       0  4808.1   0.045       0
  4819.2    0.07       0  4970.4   0.045       0  5181.1   0.035       0
Bank Sta=4808.1,4819.2
Exp/Cntr=0.3,0.1

Type RM Length L Ch R = 1,255,0,0,0
BEGIN DESCRIPTION:
NC Unknown Stream 18 1.0
END DESCRIPTION:
XS GIS Cut Line= 4
      1515988.36      6936492.30      1515868.29      6936559.79
      1515726.81      6936836.58      1515578.63      6937588.94
#Sta/Elev= 30
  4720.2 1727.09  4735.5 1727.05  4741.6 1724.64  4769.9 1725.06  4785.0 1724.83
  4800.9 1723.76  4838.6 1723.57  4844.3 1723.94  4850.2 1723.46  4873.3 1723.14
  4918.9 1723.55  4941.1 1722.19  4973.9 1722.07  4974.4 1721.57  4984.5 1721.57
  4985.0 1722.07  4985.5 1722.48  5001.9 1722.91  5013.4 1722.37  5052.2 1722.57
  5068.8 1723.13  5096.6 1722.72  5205.0 1723.61  5415.5 1723.87  5825.1 1726.08
  5829.3 1725.97  5893.9 1726.34  5923.9 1727.82  5929.0 1727.20  5935.6 1727.23
#Mann=6,-1,0
  4720.2   0.035       0  4873.3    0.07       0  4973.9    0.07       0
  4985.0    0.07       0  5825.1   0.035       0  5829.3    0.07       0
Bank Sta=4973.9,4985
Exp/Cntr=0.3,0.1

Chan Stop Cuts=-1