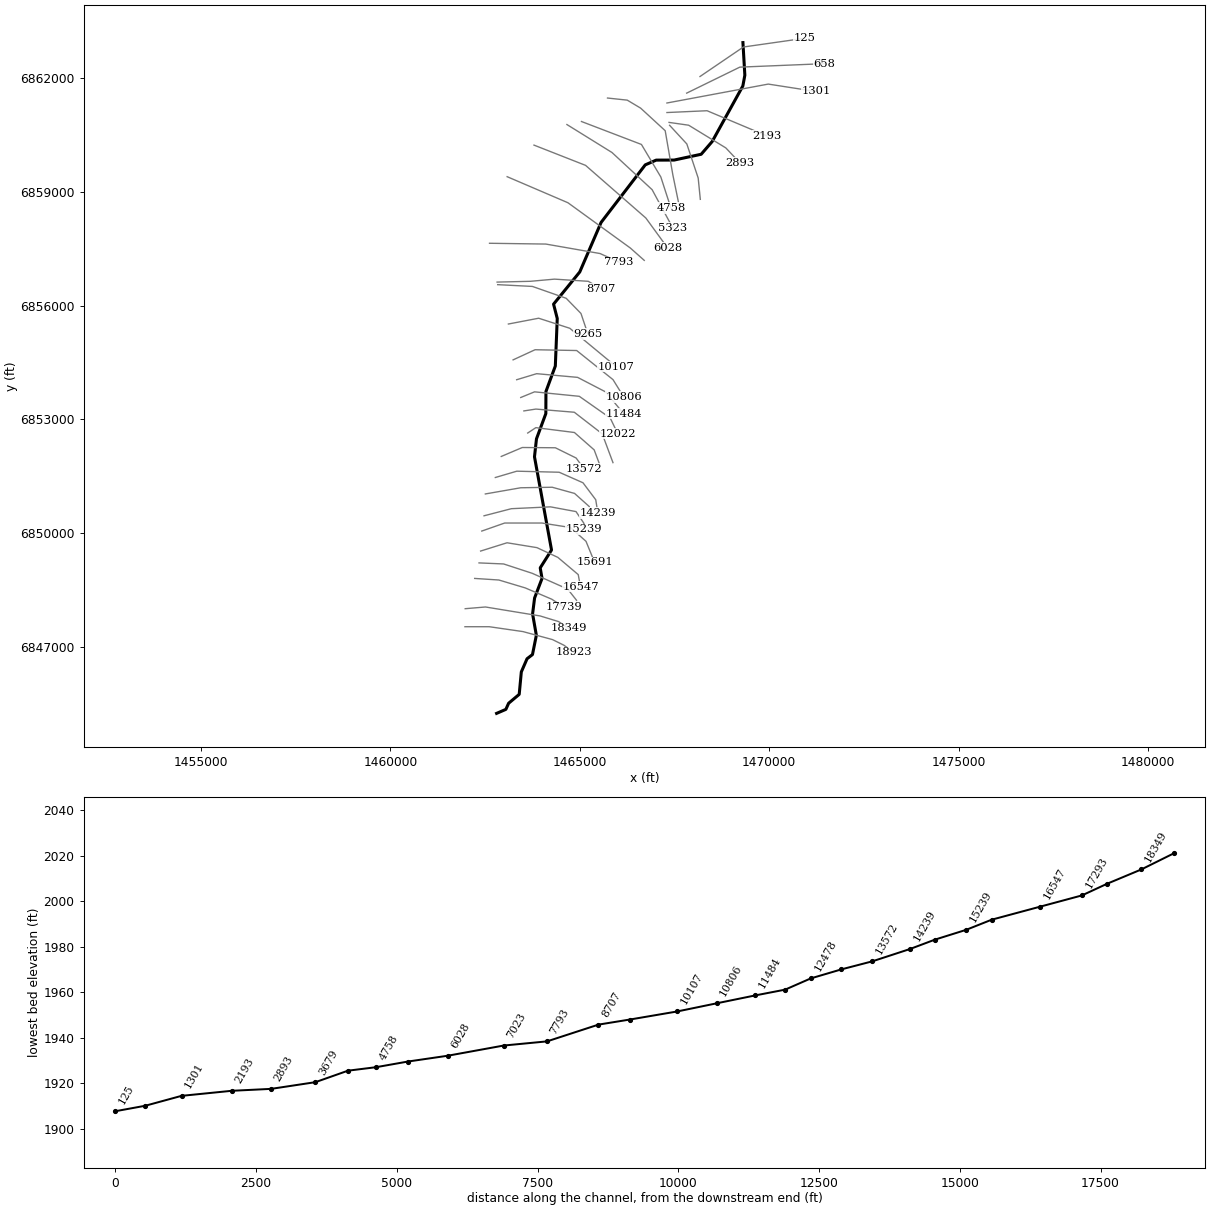
--- NC Unknown Stream 20.prj (project) ---

Proj Title=NC Unknown Stream 20 Base Level Engineering
Current Plan=p01
Default Exp/Contr=0.3,0.1
English Units
Geom File=g01
Flow File=f01
Plan File=p01
BEGIN DESCRIPTION:
NC Unknown Stream 20
END DESCRIPTION:

--- NC Unknown Stream 20.p01 (plan) ---

Plan Title=Multiple Run
Short Identifier=Multiple
Geom File=g01
Flow File=f01
Subcritical Flow
K Sum by GR= 0
Std Step Tol= 0.01
Critical Tol= 0.01
Num of Std Step Trials= 20
Max Error Tol= 0.3
Flow Tol Ratio= 0.001
Split Flow NTrial= 30
Split Flow Tol= 0.02
Split Flow Ratio= 0.02
Log Output Level= 0
Friction Slope Method= 1
Unsteady Friction Slope Method= 2
Unsteady Bridges Friction Slope Method= 1
Parabolic Critical Depth
Global Vel Dist=  1 , 1 , 1
Global Log Level= 0
CheckData=True
Encroach Param= -1, 0, 0, 0
BEGIN DESCRIPTION:
Multiple Run
END DESCRIPTION:

--- NC Unknown Stream 20.f01 (steady flow) ---

Flow Title=Multiple
Number of Profiles=7
Profile Names=10-year,25-year,50-year,1pct_min,100-year,1pct_plu,500-year
River Rch & RM= NC Unknown Strea,Reach-1,18923
     394     574     729     462     921    1838    1487
River Rch & RM= NC Unknown Strea,Reach-1,14239
     597     885    1138     728    1453    2898    2395
River Rch & RM= NC Unknown Strea,Reach-1,10107
     590     872    1120     715    1427    2847    2344
River Rch & RM= NC Unknown Strea,Reach-1,9265
     730    1071    1368     866    1729    3449    2795
Boundary for River Rch & Prof#=NC Unknown Strea,Reach-1,1
Up Type=0
Dn Type=3
Dn Slope=0.001
Boundary for River Rch & Prof#=NC Unknown Strea,Reach-1,2
Up Type=0
Dn Type=3
Dn Slope=0.001
Boundary for River Rch & Prof#=NC Unknown Strea,Reach-1,3
Up Type=0
Dn Type=3
Dn Slope=0.001
Boundary for River Rch & Prof#=NC Unknown Strea,Reach-1,4
Up Type=0
Dn Type=3
Dn Slope=0.001
Boundary for River Rch & Prof#=NC Unknown Strea,Reach-1,5
Up Type=0
Dn Type=3
Dn Slope=0.001
Boundary for River Rch & Prof#=NC Unknown Strea,Reach-1,6
Up Type=0
Dn Type=3
Dn Slope=0.001
Boundary for River Rch & Prof#=NC Unknown Strea,Reach-1,7
Up Type=0
Dn Type=3
Dn Slope=0.001

--- NC Unknown Stream 20.g01 (geometry) ---

Geom Title=Existing Conditions

River Reach=NC Unknown Strea,Reach-1
Reach XY= 30
      1462805.00      6845238.00      1463049.42      6845343.58
      1463121.63      6845504.71      1463401.39      6845739.50
      1463457.26      6846332.06      1463608.51      6846679.52
      1463751.46      6846789.46      1463853.78      6847298.50
      1463754.60      6847863.00      1463807.24      6848282.07
      1464003.79      6848798.51      1463955.94      6849077.52
      1464254.40      6849548.62      1463804.64      6852008.15
      1463857.24      6852482.07      1464104.20      6853148.70
      1464107.07      6853732.14      1464354.48      6854403.22
      1464405.36      6855658.15      1464308.15      6856036.32
      1464999.17      6856885.70      1465563.16      6858194.05
      1466727.86      6859711.84      1467015.50      6859836.78
      1467489.78      6859838.52      1468203.53      6859991.54
      1468494.24      6860328.32      1469302.93      6861793.86
      1469355.45      6862077.81      1469305.00      6862938.00

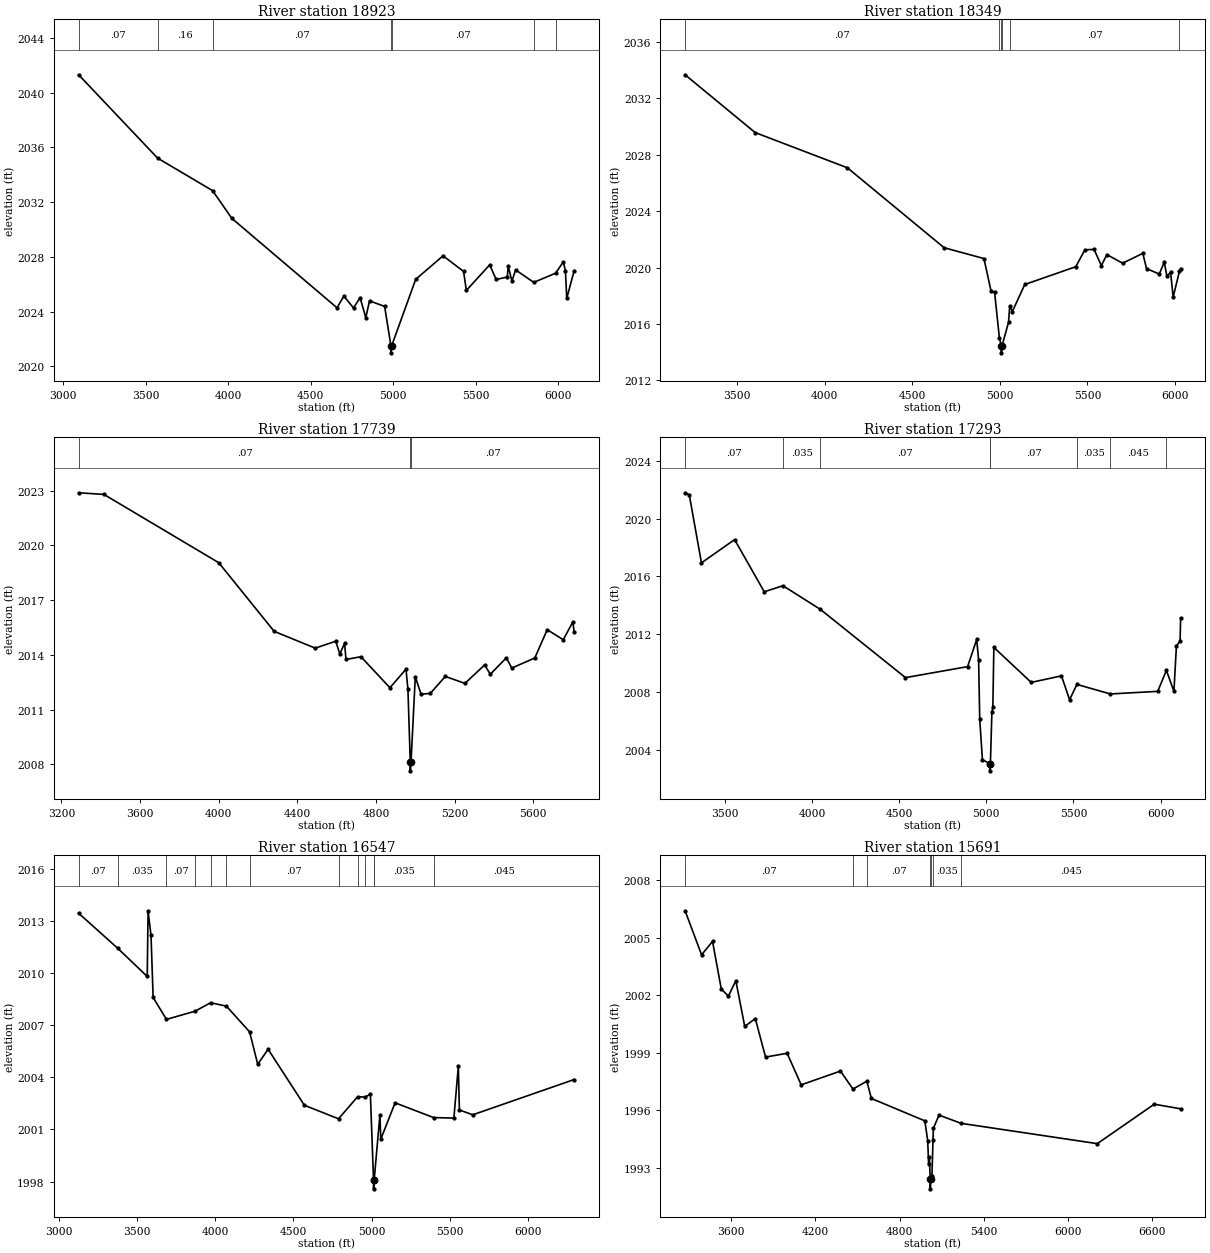
Type RM Length L Ch R = 1,18923,574,574,574
BEGIN DESCRIPTION:
Mapping XS 3084f4a2
END DESCRIPTION:
XS GIS Cut Line= 6
      1461969.63      6847524.51      1462612.03      6847524.51
      1463500.91      6847396.04      1464282.16      6847184.23
      1464584.25      6847034.93      1464837.70      6846847.44
#Sta/Elev= 30
  3093.6 2041.31  3572.0 2035.22  3905.5 2032.84  4021.5 2030.82  4659.1 2024.28
  4700.5 2025.14  4758.9 2024.27  4798.8 2025.02  4833.4 2023.56  4855.9 2024.79
  4947.7 2024.38  4985.6 2021.49  4985.8 2020.99  4989.6 2021.49  5135.7 2026.36
  5301.5 2028.08  5425.8 2026.94  5442.5 2025.55  5584.0 2027.42  5623.3 2026.35
  5690.6 2026.53  5696.2 2027.33  5718.6 2026.23  5741.0 2027.05  5851.0 2026.14
  5983.4 2026.81  6030.0 2027.64  6042.7 2027.00  6050.9 2024.97  6095.8 2027.00
#Mann=7,-1,0
  3093.6    0.07       0  3572.0    0.16       0  3905.5    0.07       0
  4985.6    0.07       0  4989.6    0.07       0  5851.0   0.035       0
  5983.4    0.07       0
Bank Sta=4985.6,4989.6
Exp/Cntr=0.3,0.1

Type RM Length L Ch R = 1,18349,610,610,610
BEGIN DESCRIPTION:
Mapping XS a9c8821a
END DESCRIPTION:
XS GIS Cut Line= 5
      1461976.59      6848000.20      1462511.33      6848045.34
      1463952.30      6847809.23      1464441.89      6847659.93
      1464705.75      6847479.39
#Sta/Elev= 30
  3203.9 2033.68  3603.7 2029.58  4130.3 2027.08  4682.1 2021.41  4909.6 2020.64
  4950.1 2018.34  4970.4 2018.24  4997.9 2014.99  5008.9 2014.45  5009.2 2013.95
  5012.9 2014.45  5050.1 2016.12  5056.8 2017.28  5071.7 2016.88  5142.7 2018.80
  5433.6 2020.06  5485.8 2021.26  5538.1 2021.29  5579.9 2020.14  5611.3 2020.92
  5701.1 2020.31  5816.4 2021.01  5837.5 2019.93  5910.2 2019.54  5938.9 2020.38
  5953.8 2019.40  5974.8 2019.66  5989.7 2017.91  6025.6 2019.75  6032.3 2019.92
#Mann=6,-1,0
  3203.9    0.07       0  4997.9   0.035       0  5008.9   0.035       0
  5012.9   0.035       0  5056.8    0.07       0  6025.6   0.035       0
Bank Sta=5008.9,5012.9
Exp/Cntr=0.3,0.1

Type RM Length L Ch R = 1,17739,446,446,446
BEGIN DESCRIPTION:
Mapping XS ccd9d385
END DESCRIPTION:
XS GIS Cut Line= 5
      1462226.58      6848798.82      1462865.50      6848757.15
      1463559.94      6848548.82      1464261.33      6848250.20
      1464590.61      6848035.31
#Sta/Elev= 30
  3287.2 2022.88  3415.9 2022.79  4000.0 2019.05  4281.9 2015.29  4490.7 2014.37
  4595.1 2014.75  4616.0 2014.05  4640.0 2014.63  4647.3 2013.75  4723.5 2013.90
  4870.8 2012.20  4952.5 2013.22  4962.3 2012.12  4974.2 2008.15  4974.4 2007.65
  4978.2 2008.15  4999.8 2012.80  5028.9 2011.85  5076.1 2011.89  5152.4 2012.82
  5252.4 2012.44  5352.4 2013.45  5381.4 2012.94  5462.8 2013.84  5490.8 2013.28
  5607.6 2013.83  5670.9 2015.38  5752.5 2014.83  5801.3 2015.81  5808.0 2015.23
#Mann=3,-1,0
  3287.2    0.07       0  4974.2    0.07       0  4978.2    0.07       0
Bank Sta=4974.2,4978.2
Exp/Cntr=0.3,0.1

Type RM Length L Ch R = 1,17293,746,746,746
BEGIN DESCRIPTION:
Mapping XS a2571355
END DESCRIPTION:
XS GIS Cut Line= 5
      1462341.15      6849208.54      1462990.50      6849180.76
      1463743.97      6848934.23      1464681.47      6848517.57
      1464913.89      6848222.70
#Sta/Elev= 30
  3271.2 2021.78  3295.1 2021.64  3365.1 2016.93  3555.3 2018.54  3725.5 2014.93
  3832.7 2015.35  4047.8 2013.71  4536.1 2008.99  4892.5 2009.75  4944.9 2011.63
  4955.8 2010.19  4962.2 2006.11  4977.7 2003.31  5019.5 2003.04  5019.7 2002.54
  5023.5 2003.04  5032.0 2006.60  5037.5 2006.94  5043.3 2011.08  5257.7 2008.66
  5431.4 2009.11  5477.9 2007.46  5519.9 2008.52  5711.9 2007.86  5983.7 2008.04
  6033.7 2009.49  6076.7 2008.04  6091.2 2011.20  6112.0 2011.50  6115.3 2013.11
#Mann=8,-1,0
  3271.2    0.07       0  3832.7   0.035       0  4047.8    0.07       0
  5019.5    0.07       0  5023.5    0.07       0  5519.9   0.035       0
  5711.9   0.045       0  6033.7    0.07       0
Bank Sta=5019.5,5023.5
Exp/Cntr=0.3,0.1

Type RM Length L Ch R = 1,16547,856,856,856
BEGIN DESCRIPTION:
Mapping XS 962e4117
END DESCRIPTION:
XS GIS Cut Line= 6
      1462382.86      6849521.04      1463080.78      6849739.79
      1463868.97      6849611.32      1464421.05      6849354.37
      1464959.25      6848899.51      1465018.28      6848576.56
#Sta/Elev= 30
  3124.7 2013.44  3373.9 2011.43  3563.9 2009.80  3569.1 2013.58  3588.0 2012.16
  3601.6 2008.59  3686.9 2007.33  3869.4 2007.80  3970.1 2008.29  4070.9 2008.09
  4219.1 2006.61  4271.0 2004.75  4337.5 2005.61  4569.6 2002.39  4788.2 2001.61
  4910.6 2002.88  4956.7 2002.86  4992.2 2003.02  5012.3 1998.08  5012.6 1997.58
  5016.3 1998.08  5053.2 2001.83  5058.8 2000.44  5150.3 2002.53  5397.0 2001.68
  5526.6 2001.65  5555.2 2004.64  5561.8 2002.12  5647.5 2001.84  6296.6 2003.87
#Mann=13,-1,0
  3124.7    0.07       0  3373.9   0.035       0  3686.9    0.07       0
  3869.4   0.035       0  3970.1    0.07       0  4070.9   0.035       0
  4219.1    0.07       0  4788.2   0.035       0  4910.6    0.07       0
  4956.7   0.035       0  5012.3   0.035       0  5016.3   0.035       0
  5397.0   0.045       0
Bank Sta=5012.3,5016.3
Exp/Cntr=0.3,0.1

Type RM Length L Ch R = 1,15691,452,452,452
BEGIN DESCRIPTION:
Mapping XS a67c29cf
END DESCRIPTION:
XS GIS Cut Line= 6
      1462414.07      6850048.80      1463018.28      6850260.62
      1464000.91      6850260.62      1464754.39      6850142.57
      1465164.11      6849777.98      1465389.79      6849225.94
#Sta/Elev= 30
  3272.1 2006.41  3389.6 2004.11  3467.6 2004.81  3529.7 2002.33  3580.4 2001.95
  3633.4 2002.76  3697.0 2000.37  3772.4 2000.78  3845.3 1998.77  3999.1 1998.97
  4099.1 1997.32  4379.1 1998.04  4468.1 1997.10  4567.1 1997.51  4599.1 1996.61
  4980.1 1995.44  5000.4 1994.41  5007.1 1993.18  5012.2 1993.56  5018.6 1992.39
  5018.8 1991.89  5022.6 1992.39  5030.7 1992.57  5038.3 1994.44  5040.8 1995.05
  5081.3 1995.74  5238.5 1995.31  6208.8 1994.25  6614.6 1996.31  6802.5 1996.07
#Mann=7,-1,0
  3272.1    0.07       0  4468.1   0.035       0  4567.1    0.07       0
  5018.6    0.07       0  5022.6    0.07       0  5038.3   0.035       0
  5238.5   0.045       0
Bank Sta=5018.6,5022.6
Exp/Cntr=0.3,0.1

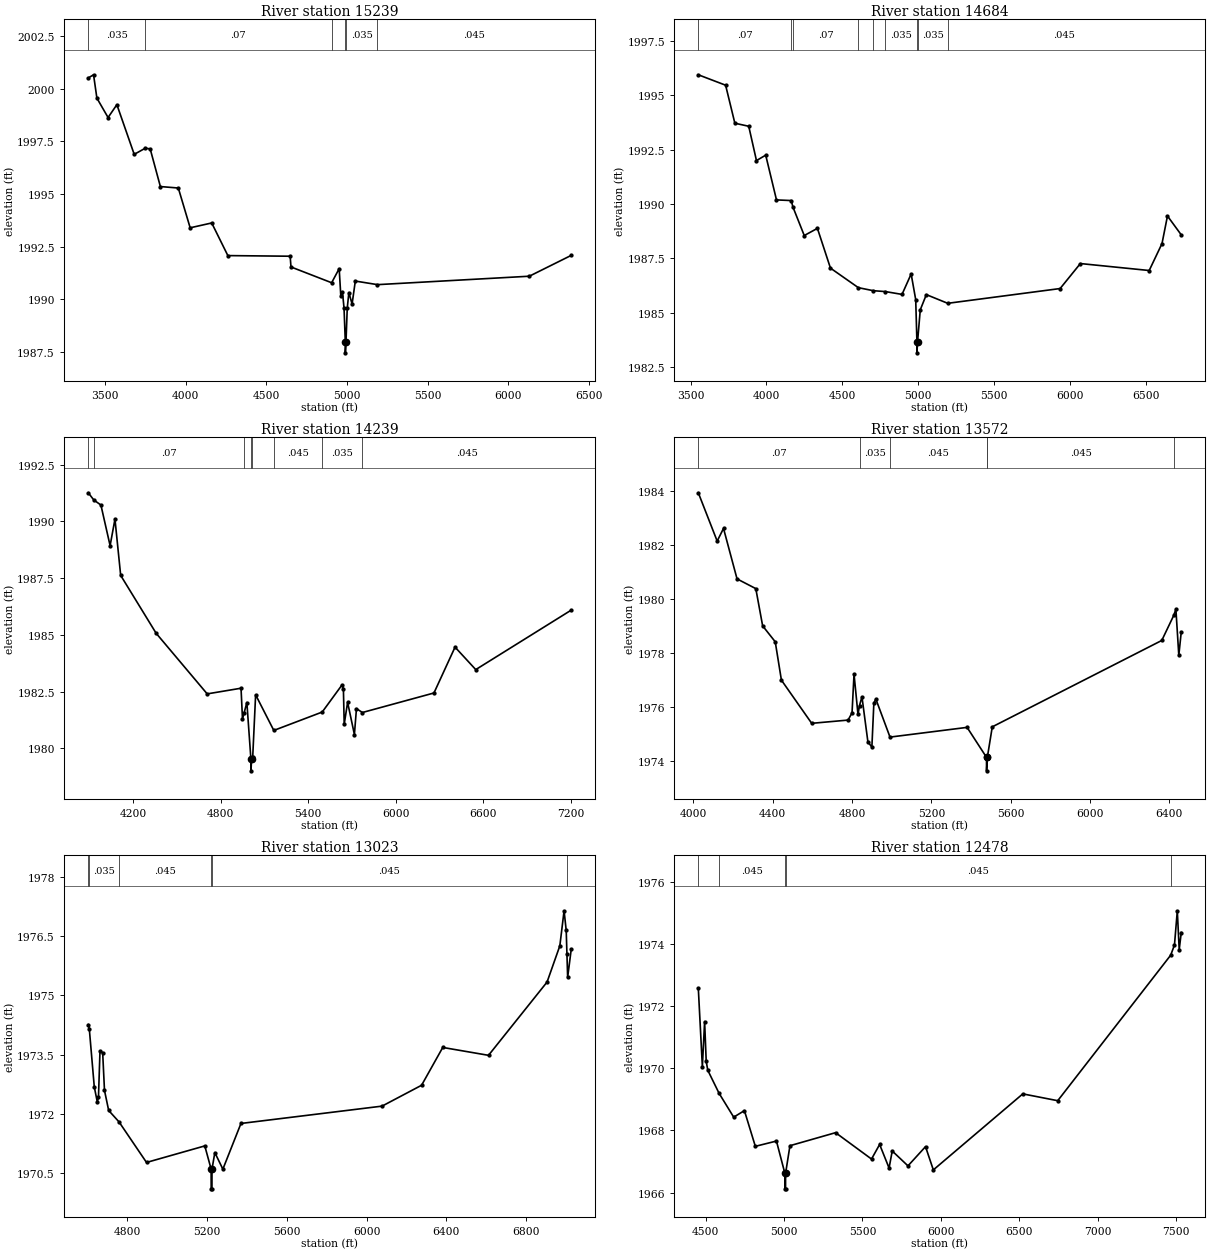
Type RM Length L Ch R = 1,15239,555,555,555
BEGIN DESCRIPTION:
Mapping XS 70344f5c
END DESCRIPTION:
XS GIS Cut Line= 6
      1462473.11      6850451.59      1463195.36      6850639.09
      1464226.61      6850687.70      1464900.22      6850562.70
      1465108.55      6850253.68      1465112.03      6850093.91
#Sta/Elev= 30
  3394.9 2000.51  3427.8 2000.66  3448.5 1999.55  3517.8 1998.63  3572.5 1999.24
  3680.0 1996.88  3748.4 1997.17  3779.1 1997.14  3842.3 1995.35  3953.6 1995.28
  4027.1 1993.39  4160.8 1993.62  4260.9 1992.07  4647.5 1992.04  4652.6 1991.53
  4904.8 1990.78  4951.6 1991.45  4961.6 1990.17  4971.7 1990.35  4981.7 1989.58
  4989.7 1987.95  4989.9 1987.45  4993.7 1987.95  5001.7 1989.58  5011.7 1990.31
  5031.7 1989.77  5051.7 1990.86  5189.3 1990.69  6131.1 1991.09  6391.1 1992.08
#Mann=6,-1,0
  3394.9   0.035       0  3748.4    0.07       0  4904.8   0.035       0
  4989.7   0.035       0  4993.7   0.035       0  5189.3   0.045       0
Bank Sta=4989.7,4993.7
Exp/Cntr=0.3,0.1

Type RM Length L Ch R = 1,14684,445,445,445
BEGIN DESCRIPTION:
Mapping XS 4d82d649
END DESCRIPTION:
XS GIS Cut Line= 6
      1462507.86      6851027.98      1463441.89      6851191.18
      1464271.75      6851205.07      1464862.03      6851041.87
      1465250.91      6850694.65      1465268.27      6850427.33
#Sta/Elev= 30
  3551.1 1995.95  3730.9 1995.47  3791.8 1993.72  3883.2 1993.58  3934.0 1992.00
  3994.9 1992.25  4065.9 1990.19  4163.3 1990.16  4173.7 1989.87  4248.7 1988.55
  4335.3 1988.88  4421.2 1987.05  4604.9 1986.15  4703.8 1986.01  4782.8 1985.97
  4892.4 1985.84  4952.5 1986.78  4982.5 1985.60  4990.5 1983.65  4990.7 1983.15
  4994.5 1983.65  5012.5 1985.13  5052.5 1985.83  5193.3 1985.43  5933.3 1986.11
  6066.6 1987.26  6519.8 1986.94  6604.1 1988.18  6640.0 1989.45  6730.9 1988.58
#Mann=9,-1,0
  3551.1    0.07       0  4163.3   0.035       0  4173.7    0.07       0
  4604.9   0.035       0  4703.8    0.07       0  4782.8   0.035       0
  4990.5   0.035       0  4994.5   0.035       0  5193.3   0.045       0
Bank Sta=4990.5,4994.5
Exp/Cntr=0.3,0.1

Type RM Length L Ch R = 1,14239,667,667,667
BEGIN DESCRIPTION:
Mapping XS dcb652df
END DESCRIPTION:
XS GIS Cut Line= 6
      1462771.78      6851462.02      1463337.72      6851628.68
      1464455.78      6851600.90      1465084.25      6851323.12
      1465421.05      6850875.20      1465476.61      6850524.49
#Sta/Elev= 30
  3892.8 1991.26  3931.2 1990.94  3979.6 1990.72  4042.6 1988.93  4075.9 1990.10
  4115.1 1987.62  4358.3 1985.07  4708.2 1982.40  4940.2 1982.65  4950.2 1981.29
  4962.0 1981.58  4980.2 1982.02  5008.1 1979.51  5008.4 1979.01  5012.3 1979.51
  5020.2 1979.61  5040.2 1982.36  5164.9 1980.79  5496.6 1981.60  5633.1 1982.80
  5642.0 1982.62  5647.5 1981.06  5670.8 1982.03  5717.4 1980.61  5731.5 1981.75
  5772.4 1981.58  6262.8 1982.44  6407.3 1984.46  6549.3 1983.47  7203.8 1986.09
#Mann=8,-1,0
  3892.8   0.045       0  3931.2    0.07       0  4962.0   0.035       0
  5008.1   0.035       0  5012.3   0.035       0  5164.9   0.045       0
  5496.6   0.035       0  5772.4   0.045       0
Bank Sta=5008.1,5012.3
Exp/Cntr=0.3,0.1

Type RM Length L Ch R = 1,13572,549,549,549
BEGIN DESCRIPTION:
Mapping XS 3a3efc59
END DESCRIPTION:
XS GIS Cut Line= 5
      1462928.03      6852017.58      1463483.55      6852253.68
      1464355.08      6852246.73      1464903.69      6851975.90
      1465108.53      6851694.68
#Sta/Elev= 30
  4024.9 1983.92  4120.1 1982.13  4152.0 1982.60  4220.2 1980.73  4314.8 1980.37
  4349.3 1978.99  4412.8 1978.40  4443.9 1976.98  4596.6 1975.38  4780.0 1975.50
  4800.0 1975.77  4810.0 1977.20  4830.0 1975.71  4837.6 1976.04  4850.0 1976.36
  4880.0 1974.69  4900.0 1974.50  4910.0 1976.13  4920.0 1976.28  4991.4 1974.87
  5380.0 1975.23  5477.9 1974.12  5478.1 1973.62  5482.1 1974.12  5507.0 1975.25
  6361.6 1978.45  6422.0 1979.38  6432.7 1979.61  6447.4 1977.90  6459.8 1978.77
#Mann=6,-1,0
  4024.9    0.07       0  4837.6   0.035       0  4991.4   0.045       0
  5477.9   0.045       0  5482.1   0.045       0  6422.0   0.035       0
Bank Sta=5477.9,5482.1
Exp/Cntr=0.3,0.1

Type RM Length L Ch R = 1,13023,545,545,545
BEGIN DESCRIPTION:
Mapping XS 4000b6c3
END DESCRIPTION:
XS GIS Cut Line= 5
      1463625.92      6852635.62      1463841.19      6852777.98
      1464858.55      6852649.51      1465379.39      6852191.18
      1465535.63      6851774.52
#Sta/Elev= 30
  4604.2 1974.26  4609.5 1974.15  4634.4 1972.68  4649.4 1972.30  4655.4 1972.41
  4663.0 1973.58  4676.5 1973.55  4685.6 1972.59  4706.6 1972.08  4758.5 1971.79
  4896.4 1970.76  5188.7 1971.18  5220.5 1970.59  5220.8 1970.09  5224.5 1970.09
  5224.8 1970.59  5239.1 1971.01  5279.4 1970.59  5370.1 1971.75  6077.7 1972.19
  6276.0 1972.72  6382.2 1973.68  6611.7 1973.48  6905.3 1975.34  6969.4 1976.26
  6990.7 1977.15  7001.4 1976.65  7005.1 1976.04  7008.6 1975.46  7026.5 1976.17
#Mann=6,-1,0
  4604.2    0.07       0  4609.5   0.035       0  4758.5   0.045       0
  5220.5   0.045       0  5224.8   0.045       0  7005.1   0.035       0
Bank Sta=5220.5,5224.8
Exp/Cntr=0.3,0.1

Type RM Length L Ch R = 1,12478,456,456,456
BEGIN DESCRIPTION:
Mapping XS 5761c023
END DESCRIPTION:
XS GIS Cut Line= 5
      1463525.18      6853218.95      1463841.19      6853267.57
      1464855.08      6853184.23      1465591.19      6852614.79
      1465875.93      6851854.34
#Sta/Elev= 30
  4453.4 1972.59  4479.3 1970.06  4493.7 1971.51  4503.8 1970.23  4513.9 1969.94
  4585.7 1969.20  4679.1 1968.43  4747.4 1968.64  4817.1 1967.49  4951.7 1967.66
  5005.4 1966.62  5005.8 1966.12  5009.7 1966.12  5010.0 1966.62  5037.8 1967.51
  5328.8 1967.93  5557.9 1967.08  5609.7 1967.55  5669.9 1966.79  5690.0 1967.34
  5790.4 1966.86  5902.3 1967.48  5952.1 1966.73  6522.6 1969.18  6745.3 1968.96
  7465.8 1973.65  7489.8 1973.98  7507.8 1975.08  7520.0 1973.83  7533.1 1974.38
#Mann=5,-1,0
  4453.4   0.035       0  4585.7   0.045       0  5005.4   0.045       0
  5010.0   0.045       0  7465.8   0.035       0
Bank Sta=5005.4,5010
Exp/Cntr=0.3,0.1

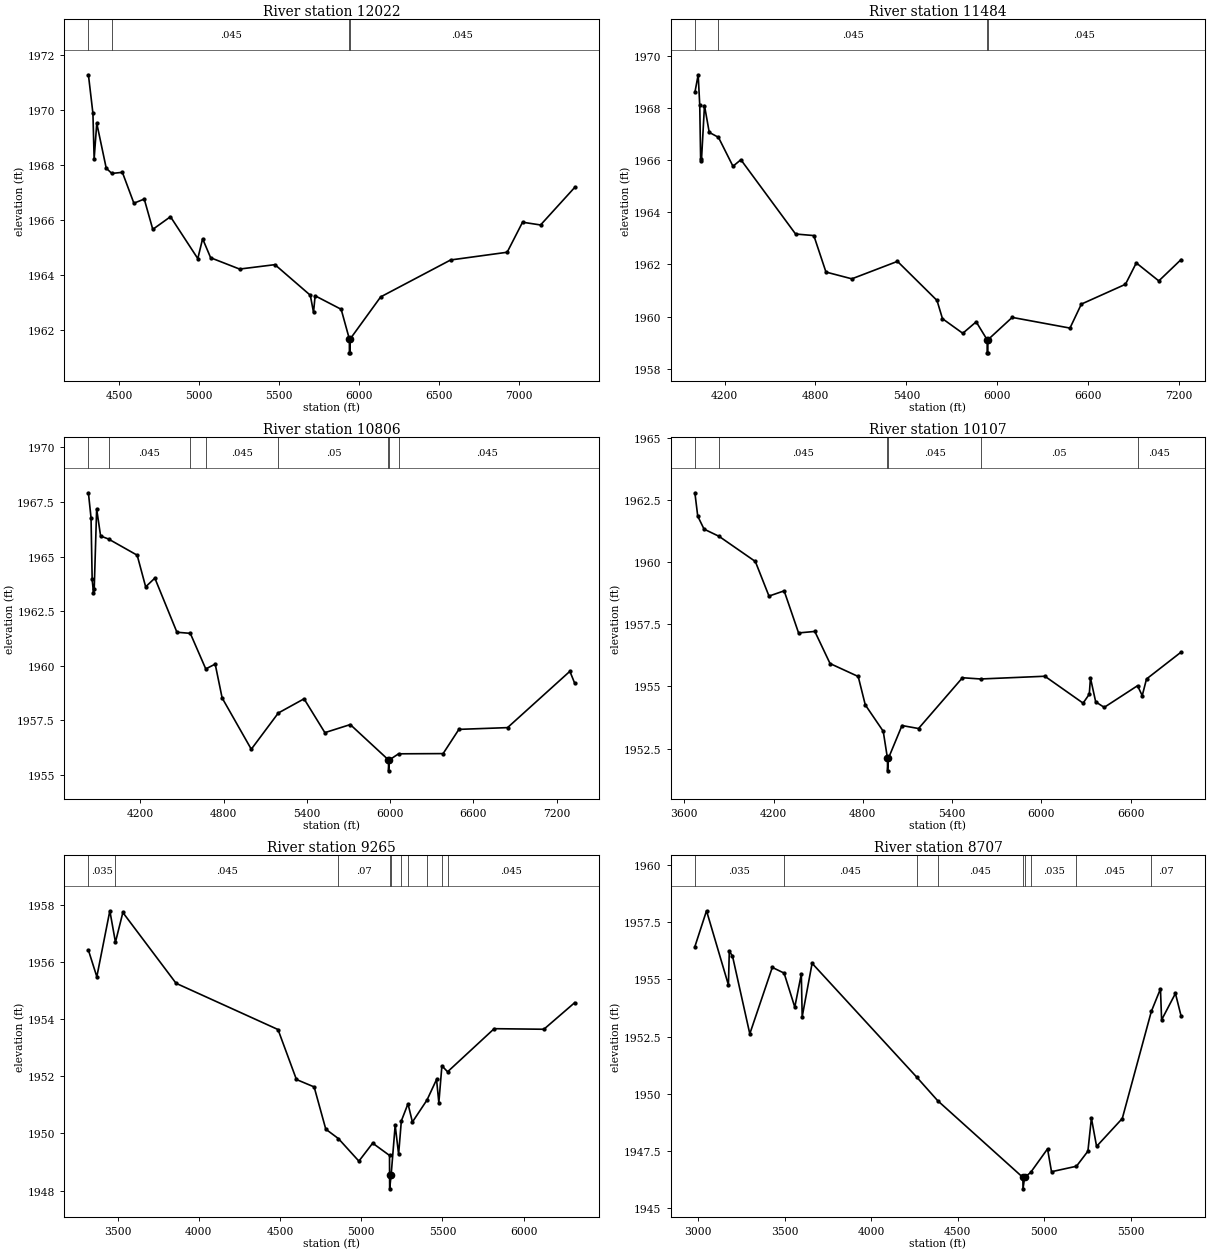
Type RM Length L Ch R = 1,12022,538,538,538
BEGIN DESCRIPTION:
Mapping XS b0b1eb79
END DESCRIPTION:
XS GIS Cut Line= 5
      1463441.90      6853573.13      1463806.47      6853722.43
      1464987.03      6853604.37      1465803.00      6853031.45
      1466004.39      6852614.79
#Sta/Elev= 30
  4306.5 1971.27  4334.7 1969.87  4342.3 1968.22  4358.7 1969.51  4417.9 1967.88
  4452.9 1967.69  4518.9 1967.73  4590.8 1966.61  4655.6 1966.76  4709.0 1965.66
  4819.6 1966.12  4990.4 1964.60  5020.6 1965.32  5070.8 1964.63  5251.7 1964.22
  5472.8 1964.38  5693.9 1963.27  5714.0 1962.65  5724.1 1963.25  5886.9 1962.76
  5938.2 1961.68  5938.5 1961.18  5942.4 1961.18  5942.8 1961.68  6133.9 1963.21
  6571.4 1964.55  6924.8 1964.83  7021.0 1965.92  7133.7 1965.82  7346.7 1967.18
#Mann=4,-1,0
  4306.5   0.035       0  4452.9   0.045       0  5938.2   0.045       0
  5942.8   0.045       0
Bank Sta=5938.2,5942.8
Exp/Cntr=0.3,0.1

Type RM Length L Ch R = 1,11484,678,678,678
BEGIN DESCRIPTION:
Mapping XS a6be705c
END DESCRIPTION:
XS GIS Cut Line= 5
      1463334.27      6854041.88      1463862.03      6854201.59
      1464941.89      6854104.37      1465684.94      6853718.95
      1466153.66      6853149.54
#Sta/Elev= 30
  4003.7 1968.60  4025.4 1969.28  4035.8 1968.12  4041.6 1966.05  4046.8 1965.96
  4067.1 1968.10  4098.5 1967.07  4159.3 1966.88  4255.2 1965.77  4307.5 1966.02
  4668.5 1963.17  4789.0 1963.11  4869.1 1961.71  5040.0 1961.45  5341.2 1962.12
  5602.3 1960.62  5638.4 1959.92  5772.5 1959.36  5861.0 1959.80  5933.4 1959.11
  5933.7 1958.61  5937.7 1958.61  5938.1 1959.11  6098.7 1959.97  6480.2 1959.56
  6555.3 1960.48  6846.5 1961.24  6918.0 1962.06  7066.7 1961.37  7213.9 1962.19
#Mann=4,-1,0
  4003.7   0.035       0  4159.3   0.045       0  5933.4   0.045       0
  5938.1   0.045       0
Bank Sta=5933.4,5938.1
Exp/Cntr=0.3,0.1

Type RM Length L Ch R = 1,10806,699,699,699
BEGIN DESCRIPTION:
Mapping XS 9c047036
END DESCRIPTION:
XS GIS Cut Line= 5
      1463240.46      6854566.16      1463820.36      6854833.54
      1464917.58      6854812.70      1465875.91      6854045.34
      1466160.34      6853587.49
#Sta/Elev= 30
  3826.7 1967.92  3845.6 1966.77  3853.7 1963.95  3863.1 1963.35  3868.6 1963.53
  3886.0 1967.18  3914.5 1965.94  3971.9 1965.80  4178.0 1965.06  4239.1 1963.61
  4305.2 1964.01  4464.4 1961.53  4560.6 1961.48  4672.1 1959.85  4740.0 1960.07
  4790.0 1958.52  5000.0 1956.17  5194.7 1957.83  5380.1 1958.48  5530.1 1956.93
  5713.1 1957.30  5988.4 1955.68  5988.9 1955.18  5994.4 1955.68  6061.1 1955.96
  6381.9 1955.97  6495.6 1957.08  6846.1 1957.16  7295.1 1959.74  7329.4 1959.20
#Mann=8,-1,0
  3826.7   0.035       0  3971.9   0.045       0  4560.6    0.07       0
  4672.1   0.045       0  5194.7    0.05       0  5988.4   0.045       0
  5994.4    0.05       0  6061.1   0.045       0
Bank Sta=5988.4,5994.4
Exp/Cntr=0.3,0.1

Type RM Length L Ch R = 1,10107,842,842,842
BEGIN DESCRIPTION:
NC Unknown Stream 19 1.0
END DESCRIPTION:
XS GIS Cut Line= 4
      1463116.11      6855512.09      1463914.74      6855664.87
      1464737.03      6855399.51      1465961.37      6854386.74
#Sta/Elev= 30
  3671.7 1962.78  3690.9 1961.84  3733.3 1961.32  3834.2 1961.03  4077.8 1960.02
  4169.5 1958.63  4271.3 1958.84  4368.2 1957.15  4477.4 1957.21  4579.7 1955.92
  4768.8 1955.40  4816.3 1954.26  4936.9 1953.20  4965.4 1952.11  4965.9 1951.61
  4971.5 1952.11  5063.0 1953.43  5174.0 1953.31  5469.2 1955.35  5591.4 1955.30
  6022.8 1955.41  6279.4 1954.33  6321.1 1954.69  6328.9 1955.34  6364.1 1954.38
  6421.4 1954.16  6645.2 1955.03  6676.7 1954.63  6705.4 1955.30  6937.8 1956.38
#Mann=6,-1,0
  3671.7   0.035       0  3834.2   0.045       0  4965.4   0.045       0
  4971.5   0.045       0  5591.4    0.05       0  6645.2   0.045       0
Bank Sta=4965.4,4971.5
Exp/Cntr=0.3,0.1

Type RM Length L Ch R = 1,9265,558,558,558
BEGIN DESCRIPTION:
Mapping XS 8b316f4d
END DESCRIPTION:
XS GIS Cut Line= 5
      1462833.30      6856550.67      1463749.99      6856503.79
      1464640.61      6856191.29      1465031.24      6855790.25
      1465213.53      6855248.59
#Sta/Elev= 30
  3320.5 1956.42  3372.3 1955.49  3452.4 1957.80  3486.9 1956.70  3532.5 1957.74
  3860.1 1955.26  4487.6 1953.64  4601.0 1951.89  4710.0 1951.63  4781.7 1950.15
  4859.4 1949.82  4985.5 1949.03  5070.3 1949.66  5174.0 1949.23  5174.4 1948.56
  5174.9 1948.06  5184.2 1948.56  5208.9 1950.29  5230.0 1949.27  5246.8 1950.44
  5287.8 1951.04  5314.9 1950.40  5404.7 1951.17  5463.5 1951.89  5477.7 1951.08
  5496.5 1952.37  5531.5 1952.16  5818.3 1953.67  6124.3 1953.65  6313.6 1954.58
#Mann=10,-1,0
  3320.5   0.035       0  3486.9   0.045       0  4859.4    0.07       0
  5174.4    0.07       0  5184.2    0.07       0  5246.8   0.045       0
  5287.8    0.07       0  5404.7   0.035       0  5496.5    0.07       0
  5531.5   0.045       0
Bank Sta=5174.4,5184.2
Exp/Cntr=0.3,0.1

Type RM Length L Ch R = 1,8707,914,914,914
BEGIN DESCRIPTION:
Mapping XS 6b4335ea
END DESCRIPTION:
XS GIS Cut Line= 5
      1462817.74      6856618.38      1463697.90      6856639.21
      1464333.32      6856696.50      1465223.95      6856639.21
      1465567.74      6856436.06
#Sta/Elev= 30
  2982.0 1956.44  3049.3 1958.01  3175.9 1954.76  3180.9 1956.24  3199.3 1956.03
  3299.4 1952.62  3429.4 1955.53  3497.6 1955.28  3559.4 1953.79  3597.2 1955.24
  3602.2 1953.37  3659.5 1955.71  4264.5 1950.72  4385.5 1949.69  4877.9 1946.33
  4878.4 1945.83  4887.8 1946.33  4922.8 1946.55  5020.2 1947.58  5043.2 1946.58
  5187.4 1946.82  5253.6 1947.48  5273.7 1948.93  5303.7 1947.69  5452.2 1948.91
  5620.1 1953.60  5672.9 1954.59  5679.5 1953.23  5759.4 1954.39  5792.2 1953.40
#Mann=9,-1,0
  2982.0   0.035       0  3497.6   0.045       0  4264.5    0.07       0
  4385.5   0.045       0  4877.9   0.035       0  4887.8   0.045       0
  4922.8   0.035       0  5187.4   0.045       0  5620.1    0.07       0
Bank Sta=4877.9,4887.8
Exp/Cntr=0.3,0.1

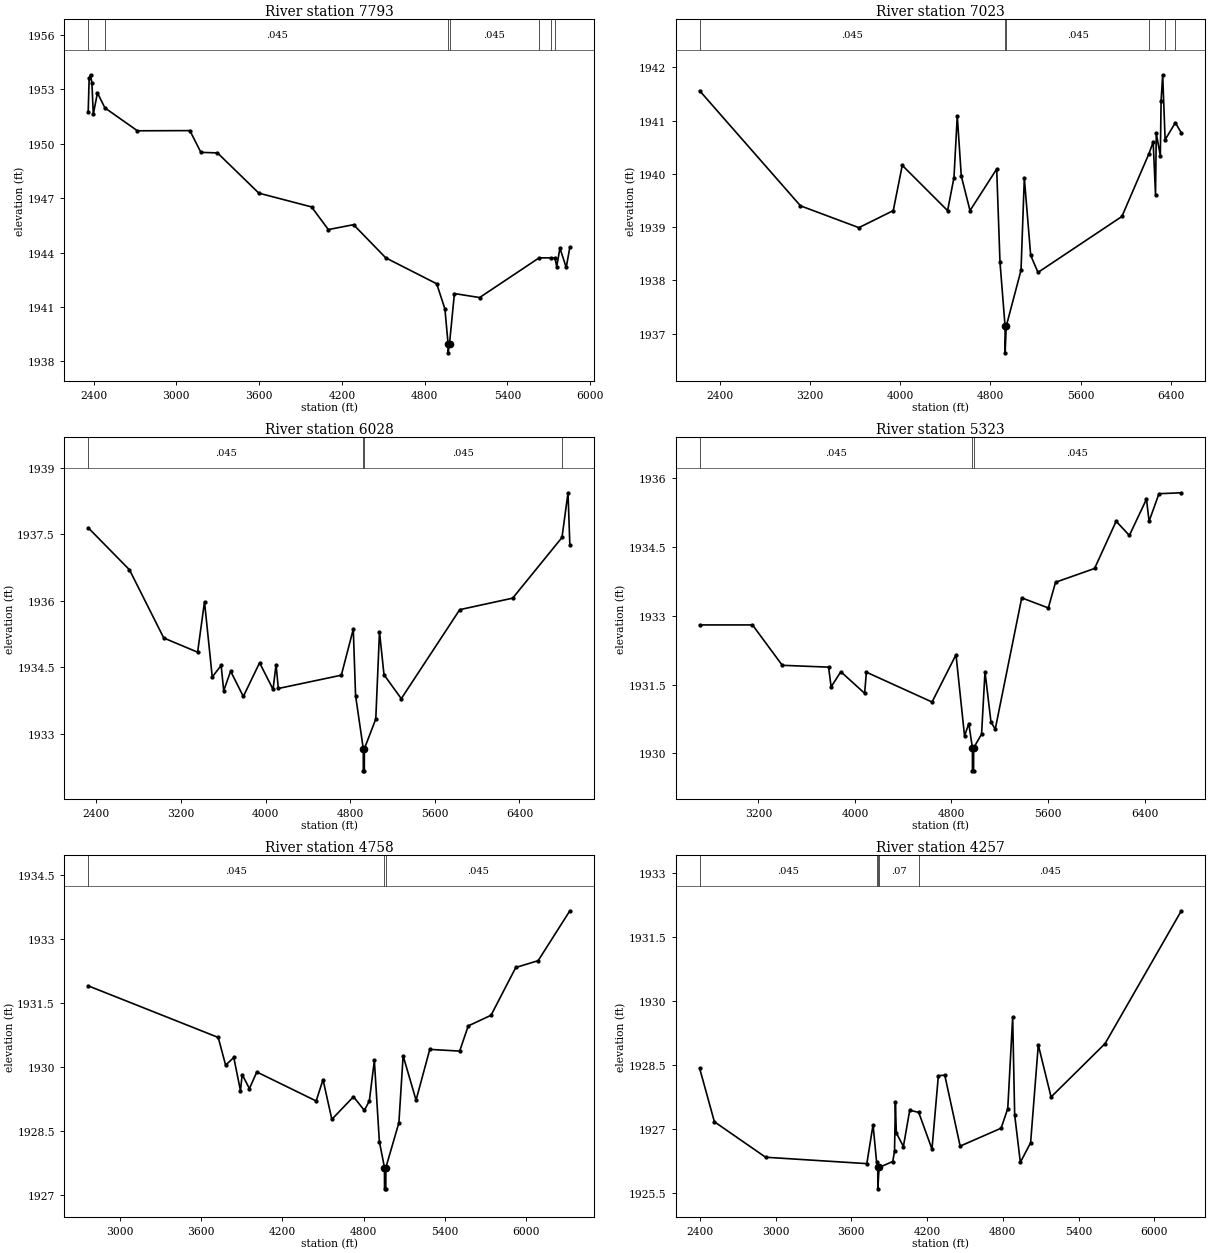
Type RM Length L Ch R = 1,7793,770,770,770
BEGIN DESCRIPTION:
Mapping XS 769dcb84
END DESCRIPTION:
XS GIS Cut Line= 4
      1462618.04      6857642.68      1464104.15      6857621.85
      1465534.71      6857371.85      1466039.19      6857145.09
#Sta/Elev= 30
  2361.0 1951.75  2368.0 1953.62  2378.0 1953.81  2388.0 1953.35  2398.0 1951.63
  2428.0 1952.81  2482.6 1951.98  2718.0 1950.72  3098.0 1950.73  3178.0 1949.53
  3298.1 1949.50  3598.1 1947.28  3980.1 1946.52  4101.9 1945.27  4284.6 1945.54
  4518.1 1943.71  4887.4 1942.28  4946.9 1940.89  4969.8 1938.97  4970.3 1938.47
  4980.1 1938.97  5015.6 1941.74  5198.3 1941.52  5629.7 1943.71  5713.5 1943.71
  5744.5 1943.70  5757.5 1943.23  5780.6 1944.25  5826.1 1943.18  5852.6 1944.30
#Mann=7,-1,0
  2361.0   0.035       0  2482.6   0.045       0  4969.8   0.045       0
  4980.1   0.045       0  5629.7   0.035       0  5713.5   0.045       0
  5744.5   0.035       0
Bank Sta=4969.8,4980.1
Exp/Cntr=0.3,0.1

Type RM Length L Ch R = 1,7023,995,995,995
BEGIN DESCRIPTION:
Mapping XS 7cab6fae
END DESCRIPTION:
XS GIS Cut Line= 4
      1463083.30      6859399.64      1464687.49      6858712.13
      1466333.32      6857517.68      1466701.36      6857191.31
#Sta/Elev= 30
  2222.2 1941.56  3116.2 1939.40  3634.1 1938.99  3938.8 1939.31  4018.6 1940.16
  4420.6 1939.31  4477.0 1939.93  4506.4 1941.09  4541.9 1939.96  4619.3 1939.31
  4855.8 1940.09  4885.2 1938.34  4930.2 1937.14  4930.7 1936.64  4940.6 1937.14
  5071.5 1938.19  5100.9 1939.92  5157.3 1938.47  5222.2 1938.15  5966.1 1939.20
  6206.1 1940.38  6243.3 1940.60  6264.2 1939.61  6270.8 1940.76  6306.8 1940.34
  6313.5 1941.37  6327.7 1941.86  6349.2 1940.64  6439.8 1940.96  6493.0 1940.77
#Mann=6,-1,0
  2222.2   0.045       0  4930.2   0.045       0  4940.6   0.045       0
  6206.1   0.035       0  6349.2   0.045       0  6439.8    0.07       0
Bank Sta=4930.2,4940.6
Exp/Cntr=0.3,0.1

Type RM Length L Ch R = 1,6028,705,705,705
BEGIN DESCRIPTION:
Mapping XS c53ef315
END DESCRIPTION:
XS GIS Cut Line= 4
      1463791.63      6860232.97      1465152.77      6859698.24
      1466743.04      6858309.35      1467319.45      6857517.66
#Sta/Elev= 30
  2323.4 1937.65  2713.8 1936.70  3037.9 1935.16  3357.8 1934.84  3422.9 1935.98
  3496.0 1934.28  3580.0 1934.54  3604.4 1933.97  3670.0 1934.41  3789.8 1933.84
  3943.6 1934.60  4070.8 1934.00  4099.3 1934.56  4120.7 1934.02  4716.3 1934.32
  4829.3 1935.36  4850.9 1933.86  4923.7 1932.66  4924.2 1932.16  4933.6 1932.16
  4934.1 1932.66  5041.9 1933.33  5077.0 1935.30  5119.7 1934.33  5283.0 1933.79
  5835.5 1935.80  6335.9 1936.06  6802.0 1937.43  6859.0 1938.44  6876.5 1937.25
#Mann=4,-1,0
  2323.4   0.045       0  4923.7   0.045       0  4934.1   0.045       0
  6802.0   0.035       0
Bank Sta=4923.7,4934.1
Exp/Cntr=0.3,0.1

Type RM Length L Ch R = 1,5323,565,565,565
BEGIN DESCRIPTION:
Mapping XS d6c90fc1
END DESCRIPTION:
XS GIS Cut Line= 4
      1464660.55      6860775.51      1465849.81      6860037.65
      1466908.84      6859056.74      1467455.74      6858045.42
#Sta/Elev= 30
  2712.5 1932.80  3150.4 1932.80  3397.3 1931.92  3781.1 1931.88  3802.4 1931.45
  3882.8 1931.78  4080.0 1931.31  4094.6 1931.77  4638.9 1931.12  4837.4 1932.15
  4908.2 1930.38  4943.4 1930.65  4973.4 1930.12  4973.9 1929.62  4983.3 1929.62
  4983.8 1930.12  5049.4 1930.42  5077.8 1931.78  5127.6 1930.68  5162.8 1930.53
  5382.2 1933.39  5602.7 1933.17  5662.6 1933.73  5986.1 1934.03  6165.0 1935.06
  6274.4 1934.75  6416.2 1935.54  6438.1 1935.06  6519.9 1935.66  6705.3 1935.68
#Mann=3,-1,0
  2712.5   0.045       0  4973.4   0.045       0  4983.8   0.045       0
Bank Sta=4973.4,4983.8
Exp/Cntr=0.3,0.1

Type RM Length L Ch R = 1,4758,501,501,501
BEGIN DESCRIPTION:
Mapping XS a01d35c8
END DESCRIPTION:
XS GIS Cut Line= 4
      1465044.31      6860855.59      1466626.72      6860250.32
      1467138.88      6859390.95      1467403.64      6858574.96
#Sta/Elev= 30
  2767.6 1931.90  3726.6 1930.69  3781.3 1930.04  3841.4 1930.22  3890.8 1929.44
  3903.2 1929.82  3956.8 1929.49  4011.1 1929.88  4449.1 1929.20  4499.5 1929.70
  4564.7 1928.77  4724.3 1929.30  4804.1 1928.98  4841.1 1929.20  4878.1 1930.15
  4915.1 1928.25  4952.7 1927.64  4953.2 1927.14  4962.6 1927.14  4963.1 1927.64
  5059.1 1928.69  5090.3 1930.26  5185.7 1929.22  5286.9 1930.41  5507.4 1930.37
  5570.5 1930.96  5738.7 1931.21  5921.1 1932.33  6086.2 1932.49  6320.1 1933.66
#Mann=3,-1,0
  2767.6   0.045       0  4952.7   0.045       0  4963.1   0.045       0
Bank Sta=4952.7,4963.1
Exp/Cntr=0.3,0.1

Type RM Length L Ch R = 1,4257,578,578,578
BEGIN DESCRIPTION:
Mapping XS f58f7de4
END DESCRIPTION:
XS GIS Cut Line= 6
      1465731.61      6861475.14      1466252.48      6861419.59
      1466606.65      6861207.78      1467253.72      6860612.74
      1467455.72      6859447.37      1467620.32      6858646.01
#Sta/Elev= 30
  2398.1 1928.42  2514.9 1927.17  2920.7 1926.34  3722.6 1926.19  3772.0 1927.10
  3799.6 1926.24  3809.3 1926.10  3809.8 1925.60  3819.8 1926.10  3928.0 1926.24
  3942.1 1926.48  3948.9 1927.63  3956.3 1926.91  4012.4 1926.59  4062.4 1927.44
  4133.7 1927.39  4238.8 1926.53  4289.5 1928.25  4340.3 1928.26  4462.1 1926.60
  4786.8 1927.02  4839.3 1927.48  4878.2 1929.62  4894.0 1927.33  4939.1 1926.22
  5020.3 1926.68  5081.2 1928.97  5182.4 1927.75  5610.2 1929.00  6214.5 1932.11
#Mann=5,-1,0
  2398.1   0.045       0  3799.6    0.07       0  3809.3   0.045       0
  3819.8    0.07       0  4133.7   0.045       0
Bank Sta=3809.3,3819.8
Exp/Cntr=0.3,0.1

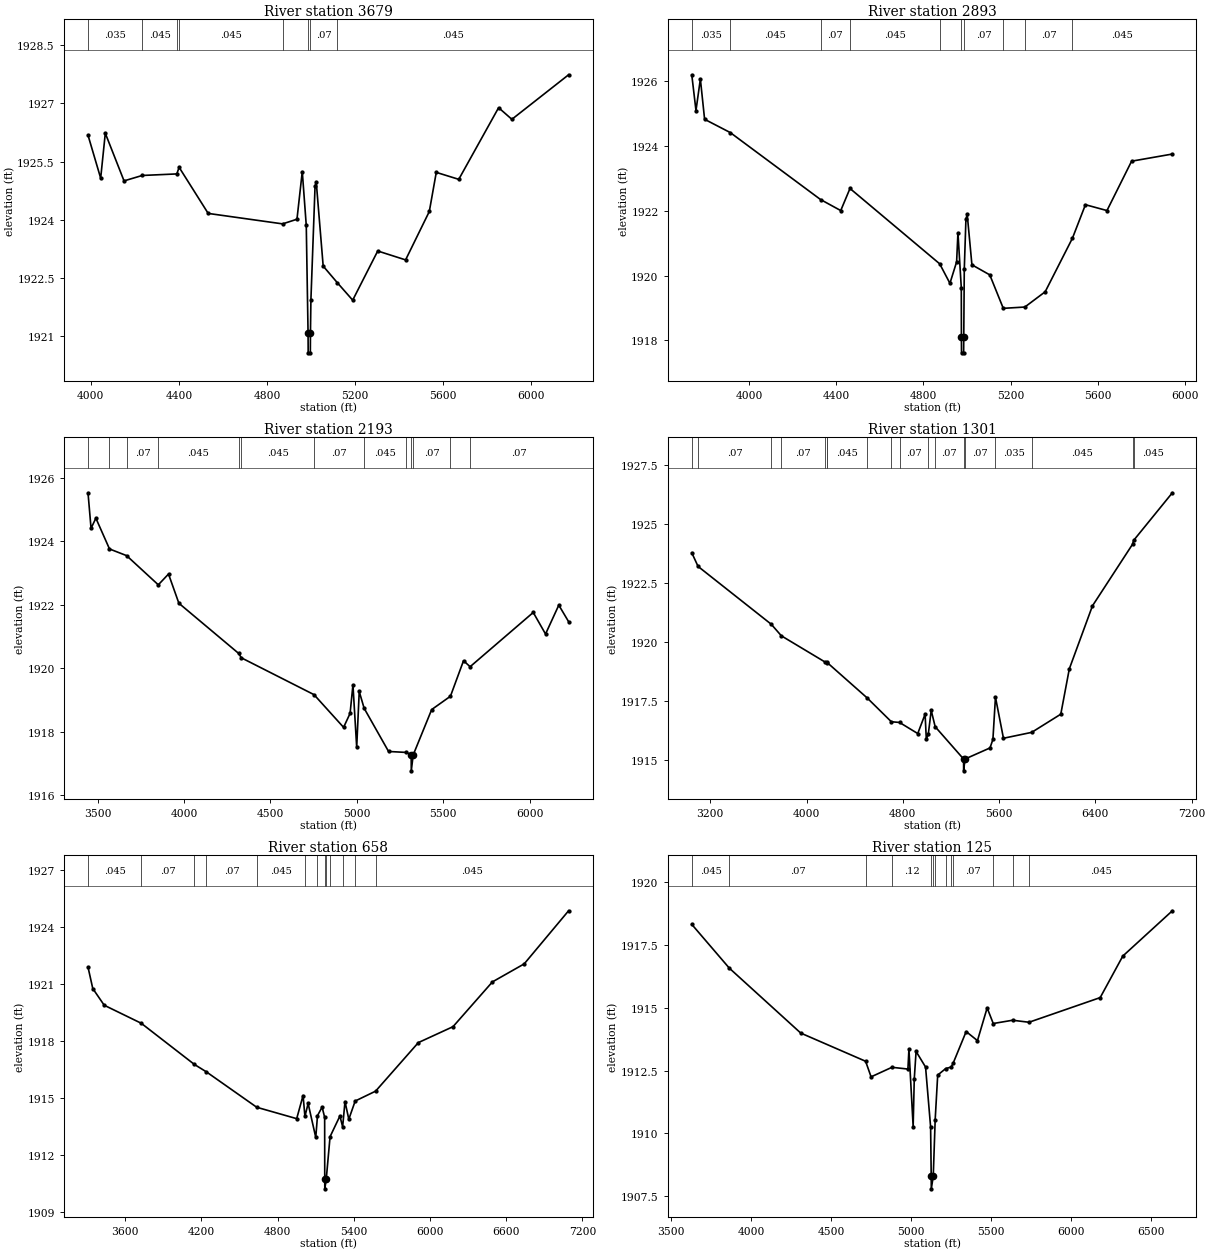
Type RM Length L Ch R = 1,3679,786,786,786
BEGIN DESCRIPTION:
Mapping XS 206e94d2
END DESCRIPTION:
XS GIS Cut Line= 4
      1467370.65      6860754.93      1467824.64      6860263.34
      1468124.12      6859364.90      1468180.43      6858801.80
#Sta/Elev= 30
  3987.7 1926.18  4045.2 1925.07  4066.2 1926.23  4151.3 1925.00  4233.9 1925.14
  4390.9 1925.18  4401.4 1925.35  4533.4 1924.16  4871.3 1923.89  4936.5 1924.01
  4960.6 1925.24  4978.7 1923.85  4986.9 1921.06  4987.4 1920.56  4997.2 1920.56
  4997.7 1921.06  4999.8 1921.93  5018.6 1924.86  5023.9 1924.98  5055.5 1922.80
  5119.8 1922.37  5189.5 1921.92  5303.2 1923.19  5429.7 1922.96  5537.4 1924.21
  5569.0 1925.22  5671.1 1925.04  5852.0 1926.89  5912.3 1926.59  6169.8 1927.74
#Mann=8,-1,0
  3987.7   0.035       0  4233.9   0.045       0  4390.9   0.035       0
  4401.4   0.045       0  4871.3    0.07       0  4986.9    0.07       0
  4997.7    0.07       0  5119.8   0.045       0
Bank Sta=4986.9,4997.7
Exp/Cntr=0.3,0.1

Type RM Length L Ch R = 1,2893,700,700,700
BEGIN DESCRIPTION:
Mapping XS 30d9d1f6
END DESCRIPTION:
XS GIS Cut Line= 4
      1467355.89      6860831.92      1467872.38      6860758.13
      1468853.29      6860159.17      1469221.07      6859769.75
#Sta/Elev= 30
  3736.0 1926.18  3755.3 1925.08  3775.5 1926.05  3794.9 1924.81  3913.0 1924.40
  4327.2 1922.34  4420.0 1922.00  4462.5 1922.68  4874.4 1920.36  4921.4 1919.76
  4952.1 1920.42  4958.2 1921.32  4973.6 1919.62  4974.1 1918.12  4974.6 1917.62
  4984.4 1917.62  4984.9 1918.12  4987.3 1920.19  4994.9 1921.74  5000.8 1921.88
  5022.4 1920.33  5104.4 1920.02  5166.4 1918.99  5265.4 1919.03  5358.8 1919.50
  5484.0 1921.15  5543.6 1922.18  5642.5 1922.00  5755.6 1923.52  5942.7 1923.74
#Mann=10,-1,0
  3736.0   0.035       0  3913.0   0.045       0  4327.2    0.07       0
  4462.5   0.045       0  4874.4    0.07       0  4974.1    0.07       0
  4984.9    0.07       0  5166.4   0.045       0  5265.4    0.07       0
  5484.0   0.045       0
Bank Sta=4974.1,4984.9
Exp/Cntr=0.3,0.1

Type RM Length L Ch R = 1,2193,892,892,892
BEGIN DESCRIPTION:
NC Unknown Stream 20 4.0
END DESCRIPTION:
XS GIS Cut Line= 3
      1467299.50      6861092.34      1468358.50      6861140.08
      1469945.47      6860472.33
#Sta/Elev= 30
  3443.8 1925.53  3461.4 1924.41  3489.3 1924.73  3568.2 1923.76  3667.2 1923.55
  3850.7 1922.63  3909.8 1922.97  3969.8 1922.05  4315.7 1920.47  4331.6 1920.33
  4752.1 1919.17  4923.2 1918.14  4960.8 1918.58  4977.4 1919.48  4999.1 1917.51
  5013.7 1919.27  5042.2 1918.74  5183.6 1917.38  5286.8 1917.35  5314.5 1917.27
  5315.0 1916.77  5326.1 1917.27  5433.1 1918.70  5541.7 1919.12  5617.5 1920.24
  5655.5 1920.05  6021.0 1921.76  6092.2 1921.08  6168.9 1921.99  6225.6 1921.47
#Mann=13,-1,0
  3443.8   0.035       0  3568.2   0.045       0  3667.2    0.07       0
  3850.7   0.045       0  4315.7    0.07       0  4331.6   0.045       0
  4752.1    0.07       0  5042.2   0.045       0  5286.8    0.07       0
  5314.5    0.07       0  5326.1    0.07       0  5541.7   0.045       0
  5655.5    0.07       0
Bank Sta=5314.5,5326.1
Exp/Cntr=0.3,0.1

Type RM Length L Ch R = 1,1301,643,643,643
BEGIN DESCRIPTION:
NC Unknown Stream 20 3.0
END DESCRIPTION:
XS GIS Cut Line= 3
      1467299.44      6861344.07      1469973.08      6861843.20
      1471230.89      6861648.02
#Sta/Elev= 30
  3046.4 1923.79  3098.7 1923.21  3706.8 1920.76  3790.7 1920.27  4156.9 1919.15
  4166.5 1919.16  4173.1 1919.13  4503.3 1917.64  4704.4 1916.63  4772.5 1916.60
  4923.8 1916.13  4984.9 1916.95  4995.1 1915.89  5011.4 1916.10  5035.7 1917.11
  5068.6 1916.42  5304.6 1915.05  5305.1 1914.55  5316.3 1915.05  5524.0 1915.52
  5548.3 1915.88  5569.5 1917.67  5635.9 1915.93  5870.5 1916.18  6112.2 1916.95
  6183.1 1918.87  6375.4 1921.54  6708.5 1924.15  6717.1 1924.31  7039.1 1926.33
#Mann=18,-1,0
  3046.4   0.035       0  3098.7    0.07       0  3706.8   0.045       0
  3790.7    0.07       0  4156.9   0.045       0  4166.5    0.07       0
  4173.1   0.045       0  4503.3    0.07       0  4704.4   0.045       0
  4772.5    0.07       0  5011.4   0.035       0  5068.6    0.07       0
  5304.6    0.07       0  5316.3    0.07       0  5569.5   0.035       0
  5870.5   0.045       0  6708.5   0.035       0  6717.1   0.045       0
Bank Sta=5304.6,5316.3
Exp/Cntr=0.3,0.1

Type RM Length L Ch R = 1,658,533,533,533
BEGIN DESCRIPTION:
NC Unknown Stream 20 2.0
END DESCRIPTION:
XS GIS Cut Line= 3
      1467820.26      6861604.47      1469222.21      6862290.25
      1471444.45      6862381.40
#Sta/Elev= 30
  3306.4 1921.90  3344.0 1920.77  3434.1 1919.89  3725.5 1918.94  4144.0 1916.77
  4238.1 1916.38  4635.4 1914.51  4949.9 1913.91  5000.0 1915.13  5014.8 1914.03
  5040.0 1914.71  5100.1 1912.92  5113.7 1914.07  5150.1 1914.52  5170.1 1913.98
  5170.8 1910.71  5171.3 1910.21  5182.5 1910.71  5212.7 1912.96  5290.2 1914.05
  5311.7 1913.48  5330.3 1914.81  5360.3 1913.88  5410.6 1914.84  5571.3 1915.36
  5908.0 1917.92  6181.0 1918.76  6491.2 1921.12  6741.5 1922.07  7091.2 1924.87
#Mann=13,-1,0
  3306.4   0.045       0  3725.5    0.07       0  4144.0   0.045       0
  4238.1    0.07       0  4635.4   0.045       0  5014.8    0.07       0
  5113.7    0.12       0  5170.8   0.045       0  5182.5    0.12       0
  5212.7    0.07       0  5311.7    0.12       0  5410.6    0.07       0
  5571.3   0.045       0
Bank Sta=5170.8,5182.5
Exp/Cntr=0.3,0.1

Type RM Length L Ch R = 1,125,0,0,0
BEGIN DESCRIPTION:
NC Unknown Stream 20 1.0
END DESCRIPTION:
XS GIS Cut Line= 3
      1468171.85      6862042.85      1469316.83      6862821.50
      1470921.83      6863050.41
#Sta/Elev= 30
  3629.7 1918.31  3864.6 1916.57  4311.3 1913.99  4717.0 1912.87  4751.2 1912.25
  4881.7 1912.63  4981.7 1912.56  4988.0 1913.35  5014.4 1910.27  5021.3 1912.16
  5032.7 1913.26  5092.0 1912.64  5123.6 1910.26  5127.4 1908.30  5127.9 1907.80
  5140.1 1908.30  5152.2 1910.55  5167.9 1912.32  5218.0 1912.58  5252.5 1912.64
  5264.4 1912.79  5345.9 1914.05  5416.6 1913.69  5477.2 1914.99  5515.4 1914.37
  5636.4 1914.50  5739.1 1914.42  6184.3 1915.40  6325.7 1917.05  6635.6 1918.85
#Mann=13,-1,0
  3629.7   0.045       0  3864.6    0.07       0  4717.0   0.045       0
  4881.7    0.12       0  5127.4    0.07       0  5140.1    0.12       0
  5152.2   0.045       0  5218.0    0.07       0  5252.5   0.045       0
  5264.4    0.07       0  5515.4   0.045       0  5636.4   0.035       0
  5739.1   0.045       0
Bank Sta=5127.4,5140.1
Exp/Cntr=0.3,0.1

Chan Stop Cuts=-1