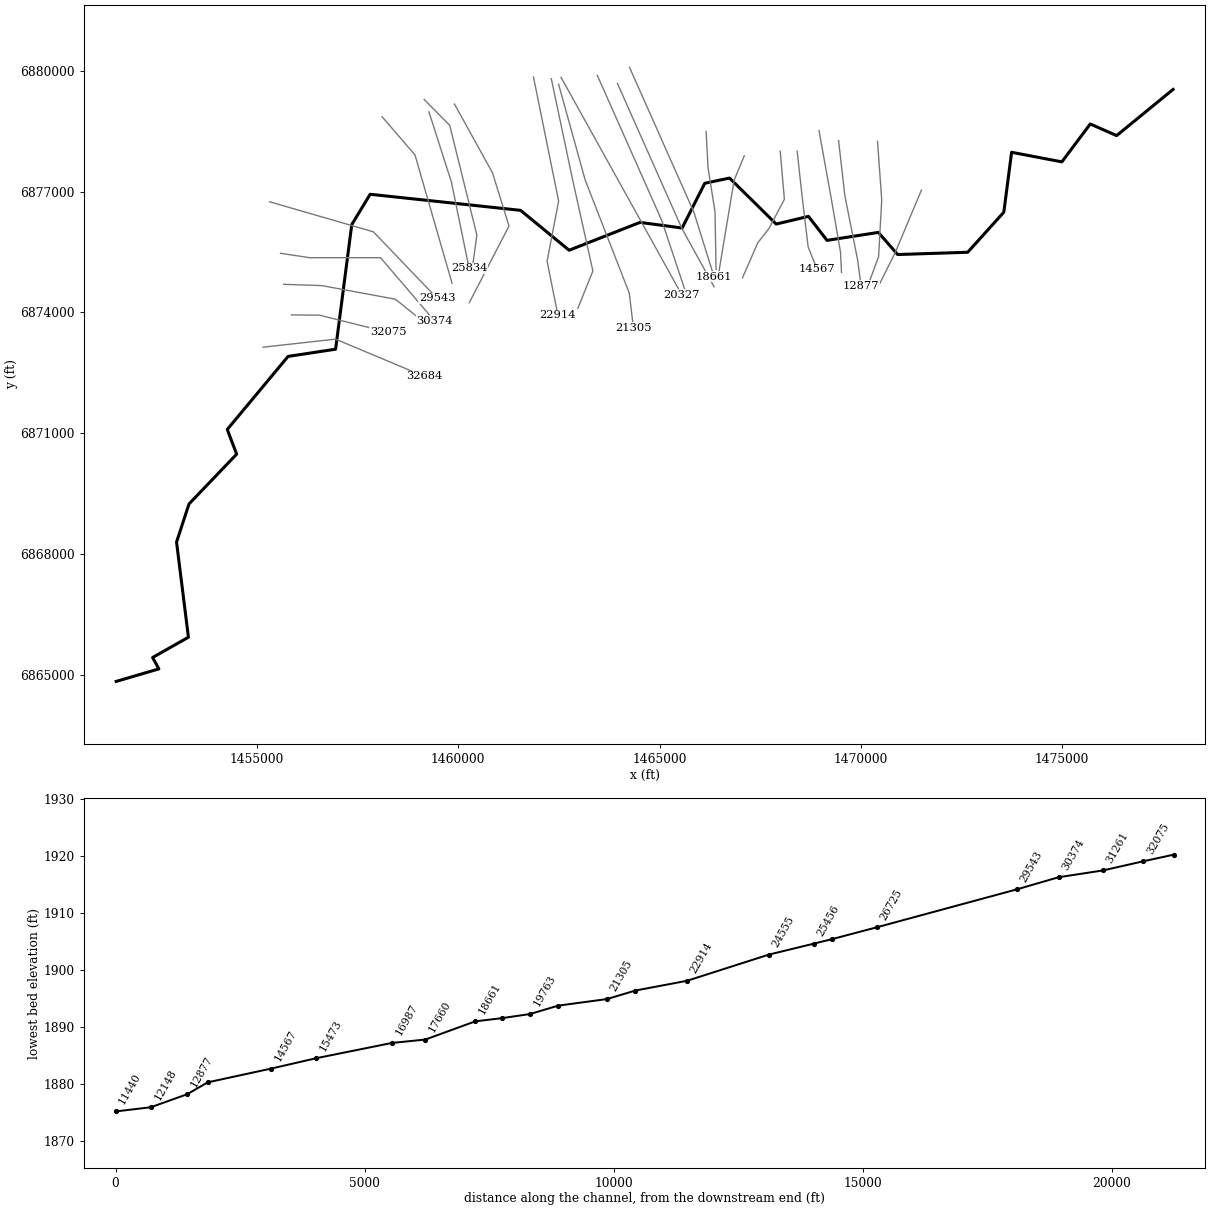
--- NC Unknown Stream 24.prj (project) ---

Proj Title=NC Unknown Stream 24 Base Level Engineering
Current Plan=p01
Default Exp/Contr=0.3,0.1
English Units
Geom File=g01
Flow File=f01
Plan File=p01
Y Axis Title=Elevation
X Axis Title(PF)=Main Channel Distance
X Axis Title(XS)=Station
BEGIN DESCRIPTION:
NC Unknown Stream 24
END DESCRIPTION:
DSS Export Rating Curves= 0
DSS Export Rating Curve Sorted= 0
DSS Export Volume Flow Curves= 0
DXF OffsetX= 0
DXF OffsetY= 0
DXF ScaleX= 1
DXF ScaleY= 10

--- NC Unknown Stream 24.p01 (plan) ---

Plan Title=Multiple Run
Short Identifier=Multiple
Geom File=g01
Flow File=f01
Subcritical Flow
K Sum by GR= 0
Std Step Tol= 0.01
Critical Tol= 0.01
Num of Std Step Trials= 20
Max Error Tol= 0.3
Flow Tol Ratio= 0.001
Split Flow NTrial= 30
Split Flow Tol= 0.02
Split Flow Ratio= 0.02
Log Output Level= 0
Friction Slope Method= 1
Unsteady Friction Slope Method= 2
Unsteady Bridges Friction Slope Method= 1
Parabolic Critical Depth
Global Vel Dist=  1 , 1 , 1
Global Log Level= 0
CheckData=True
Encroach Param= -1, 0, 0, 0
BEGIN DESCRIPTION:
Multiple Run
END DESCRIPTION:

--- NC Unknown Stream 24.f01 (steady flow) ---

Flow Title=Multiple
Program Version=4.10
Number of Profiles= 7
Profile Names=10-year,25-year,50-year,1pct_min,100-year,1pct_plu,500-year
River Rch & RM=NC Unknown Strea,Reach-1         ,32684
     638     921    1164     729    1454    2900    2297
River Rch & RM=NC Unknown Strea,Reach-1         ,31261
     647     931    1172     731    1458    2910    2288
River Rch & RM=NC Unknown Strea,Reach-1         ,26725
    1079    1578    2008    1263    2521    5030    4026
River Rch & RM=NC Unknown Strea,Reach-1         ,22914
    1079    1578    2008    1263    2521    5030    4026
River Rch & RM=NC Unknown Strea,Reach-1         ,20327
    1152    1689    2154    1358    2709    5405    4342
River Rch & RM=NC Unknown Strea,Reach-1         ,18661
    1219    1791    2287    1444    2881    5748    4629
River Rch & RM=NC Unknown Strea,Reach-1         ,15473
    1267    1862    2379    1502    2996    5978    4815
River Rch & RM=NC Unknown Strea,Reach-1         ,11440
    1283    1882    2400    1513    3018    6022    4836
River Rch & RM=NC Unknown Strea,Reach-1         ,5024
    1392    2047    2616    1652    3296    6577    5299
River Rch & RM=NC Unknown Strea,Reach-1         ,1161
    1392    2047    2616    1652    3296    6577    5299
River Rch & RM=NC Unknown Strea,Reach-1         ,689
    1392    2047    2616    1652    3296    6577    5299
Boundary for River Rch & Prof#=NC Unknown Strea,Reach-1         , 1
Up Type= 0
Dn Type= 3
Dn Slope=0.01
Boundary for River Rch & Prof#=NC Unknown Strea,Reach-1         , 2
Up Type= 0
Dn Type= 3
Dn Slope=0.01
Boundary for River Rch & Prof#=NC Unknown Strea,Reach-1         , 3
Up Type= 0
Dn Type= 3
Dn Slope=0.01
Boundary for River Rch & Prof#=NC Unknown Strea,Reach-1         , 4
Up Type= 0
Dn Type= 3
Dn Slope=0.01
Boundary for River Rch & Prof#=NC Unknown Strea,Reach-1         , 5
Up Type= 0
Dn Type= 3
Dn Slope=0.01
Boundary for River Rch & Prof#=NC Unknown Strea,Reach-1         , 6
Up Type= 0
Dn Type= 3
Dn Slope=0.01
Boundary for River Rch & Prof#=NC Unknown Strea,Reach-1         , 7
Up Type= 0
Dn Type= 3
Dn Slope=0.01
DSS Import GetInterval= 0
DSS Import GetPeak= 0
DSS Import FillOption= 0

--- NC Unknown Stream 24.g01 (geometry) ---

Geom Title=Existing Conditions

River Reach=NC Unknown Strea,Reach-1
Reach XY= 30
      1451505.00      6864838.00      1452565.44      6865149.11
      1452409.74      6865432.38      1453299.60      6865935.57
      1453004.50      6868298.17      1453314.01      6869245.02
      1454497.64      6870481.66      1454263.96      6871094.67
      1455774.59      6872908.57      1456955.00      6873088.00
      1457356.54      6876182.15      1457813.31      6876934.85
      1461549.15      6876535.94      1462755.01      6875545.53
      1464515.51      6876236.78      1465561.55      6876097.24
      1466124.60      6877208.17      1466739.78      6877337.51
      1467898.54      6876195.64      1468699.06      6876385.74
      1469160.93      6875790.23      1470434.90      6875988.10
      1470915.61      6875438.59      1472655.00      6875495.08
      1473551.90      6876489.65      1473745.30      6877977.81
      1474993.77      6877739.73      1475698.83      6878680.24
      1476353.42      6878391.83      1477755.00      6879538.00

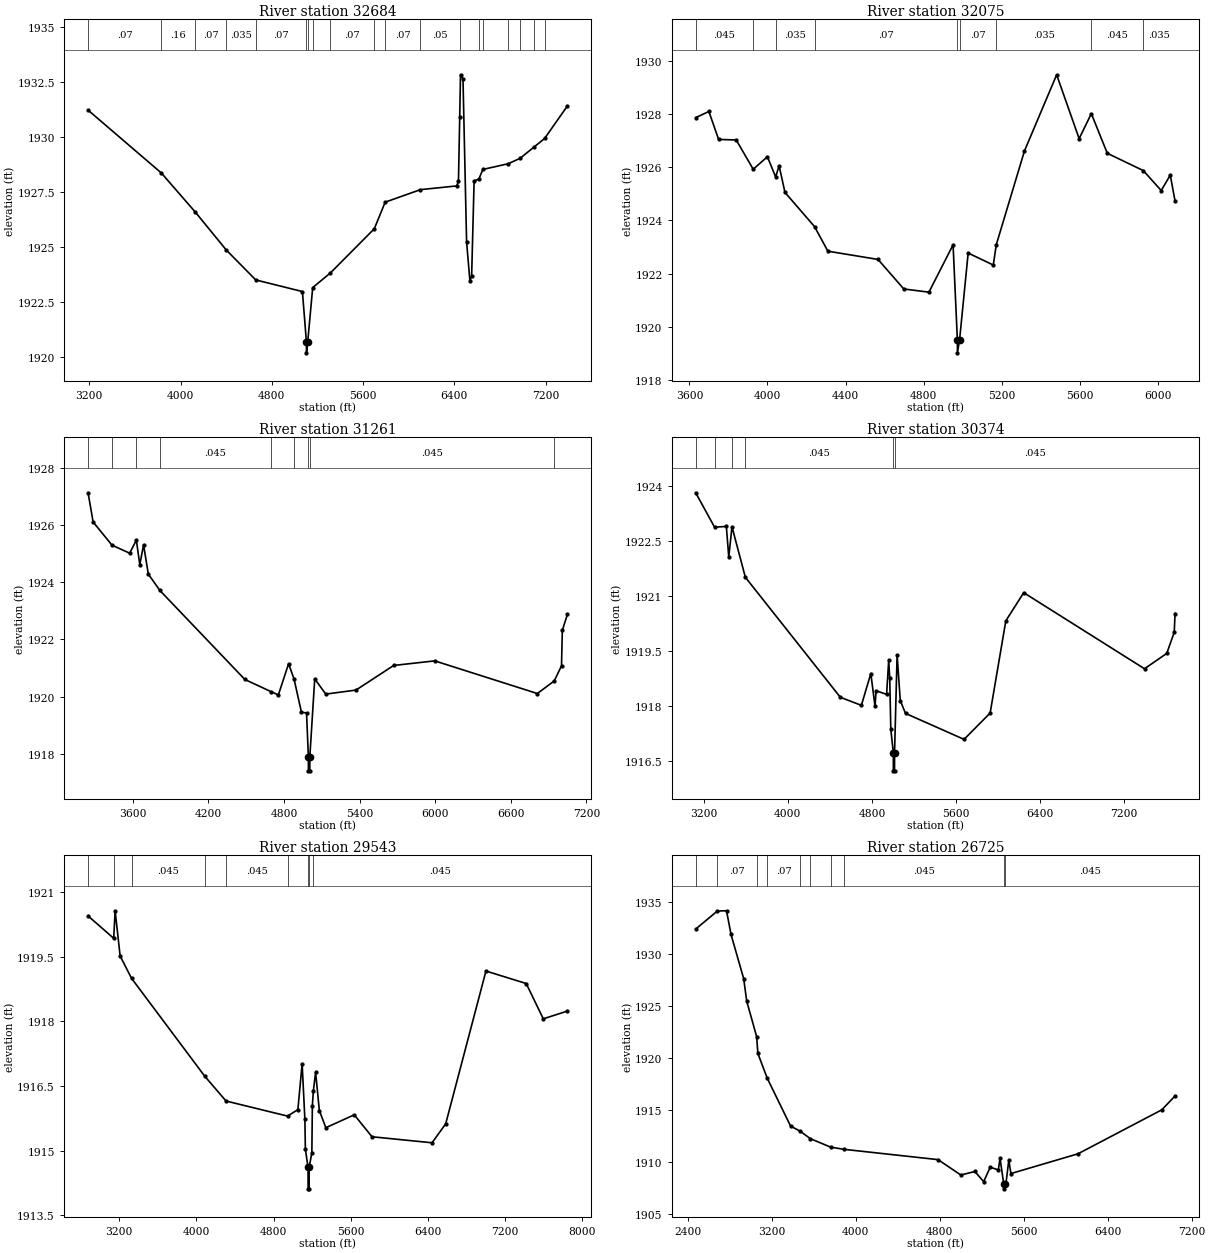
Type RM Length L Ch R = 1,32684,609,609,609
BEGIN DESCRIPTION:
NC Unknown Stream 25 5.0
END DESCRIPTION:
XS GIS Cut Line= 3
      1455154.95      6873137.99      1456955.00      6873338.00
      1459158.91      6872412.69
#Sta/Elev= 30
  3189.8 1931.23  3831.7 1928.37  4129.6 1926.59  4401.5 1924.86  4659.4 1923.50
  5068.5 1922.97  5103.6 1920.68  5104.1 1920.18  5115.1 1920.68  5158.6 1923.15
  5312.2 1923.81  5698.8 1925.83  5793.8 1927.04  6102.6 1927.61  6421.7 1927.78
  6436.3 1927.99  6447.3 1930.92  6454.2 1932.84  6475.9 1932.66  6507.6 1925.22
  6536.8 1923.45  6551.8 1923.69  6573.5 1928.01  6615.1 1928.09  6649.7 1928.53
  6872.9 1928.79  6977.4 1929.04  7096.2 1929.54  7191.4 1929.94  7391.2 1931.42
#Mann=19,-1,0
  3189.8    0.07       0  3831.7    0.16       0  4129.6    0.07       0
  4401.5   0.035       0  4659.4    0.07       0  5103.6    0.07       0
  5115.1    0.07       0  5158.6   0.035       0  5312.2    0.07       0
  5698.8    0.05       0  5793.8    0.07       0  6102.6    0.05       0
  6447.3    0.07       0  6615.1    0.05       0  6649.7    0.07       0
  6872.9    0.05       0  6977.4    0.07       0  7096.2    0.05       0
  7191.4    0.07       0
Bank Sta=5103.6,5115.1
Exp/Cntr=0.3,0.1

Type RM Length L Ch R = 1,32075,814,814,814
BEGIN DESCRIPTION:
Mapping XS 86a858e0
END DESCRIPTION:
XS GIS Cut Line= 4
      1455857.50      6873938.43      1456555.46      6873933.22
      1457992.96      6873573.84      1458261.87      6873506.62
#Sta/Elev= 30
  3632.1 1927.86  3699.6 1928.09  3749.6 1927.04  3839.6 1927.02  3926.9 1925.92
  3999.6 1926.39  4041.9 1925.63  4059.6 1926.05  4089.6 1925.05  4241.6 1923.76
  4309.6 1922.84  4566.7 1922.53  4698.8 1921.42  4827.6 1921.30  4951.3 1923.08
  4973.2 1919.52  4973.7 1919.02  4984.8 1919.52  5028.6 1922.77  5157.5 1922.32
  5172.6 1923.08  5317.3 1926.61  5482.2 1929.47  5597.5 1927.07  5659.9 1928.01
  5741.8 1926.52  5926.1 1925.87  6018.2 1925.12  6064.6 1925.70  6089.0 1924.73
#Mann=9,-1,0
  3632.1   0.045       0  3926.9    0.07       0  4041.9   0.035       0
  4241.6    0.07       0  4973.2    0.07       0  4984.8    0.07       0
  5172.6   0.035       0  5659.9   0.045       0  5926.1   0.035       0
Bank Sta=4973.2,4984.8
Exp/Cntr=0.3,0.1

Type RM Length L Ch R = 1,31261,887,887,887
BEGIN DESCRIPTION:
Mapping XS 3bdd2e1f
END DESCRIPTION:
XS GIS Cut Line= 4
      1455664.86      6874698.84      1456612.75      6874667.59
      1458440.87      6874329.05      1459216.88      6873704.08
#Sta/Elev= 30
  3245.1 1927.12  3285.3 1926.10  3435.0 1925.29  3575.4 1925.01  3628.3 1925.47
  3655.5 1924.61  3685.5 1925.30  3723.2 1924.28  3814.7 1923.71  4489.5 1920.60
  4694.9 1920.18  4755.1 1920.06  4836.5 1921.15  4880.1 1920.61  4938.2 1919.46
  4978.9 1919.43  4993.4 1917.91  4993.9 1917.41  5004.6 1917.41  5005.1 1917.91
  5043.8 1920.62  5131.4 1920.09  5371.2 1920.23  5670.4 1921.09  5995.9 1921.25
  6810.4 1920.11  6944.9 1920.55  7002.4 1921.08  7008.8 1922.32  7049.1 1922.87
#Mann=9,-1,0
  3245.1   0.045       0  3435.0    0.07       0  3628.3   0.035       0
  3814.7   0.045       0  4694.9    0.07       0  4880.1   0.045       0
  4993.4   0.045       0  5005.1   0.045       0  6944.9   0.035       0
Bank Sta=4993.4,5005.1
Exp/Cntr=0.3,0.1

Type RM Length L Ch R = 1,30374,831,831,831
BEGIN DESCRIPTION:
Mapping XS bff159e6
END DESCRIPTION:
XS GIS Cut Line= 4
      1455586.72      6875469.68      1456310.67      6875360.30
      1458071.08      6875360.30      1459414.81      6873787.41
#Sta/Elev= 30
  3123.5 1923.82  3303.0 1922.88  3415.1 1922.90  3438.1 1922.06  3468.7 1922.89
  3596.1 1921.51  4500.0 1918.23  4700.0 1918.01  4790.0 1918.88  4830.0 1917.98
  4840.0 1918.41  4940.0 1918.31  4960.0 1919.24  4970.0 1918.75  4980.0 1917.35
  5004.1 1916.72  5004.6 1916.22  5015.3 1916.22  5015.8 1916.72  5040.0 1919.39
  5070.0 1918.14  5120.0 1917.79  5677.1 1917.08  5925.3 1917.80  6074.6 1920.32
  6244.7 1921.09  7394.2 1919.01  7606.1 1919.43  7677.4 1920.01  7684.8 1920.52
#Mann=6,-1,0
  3123.5    0.05       0  3303.0    0.07       0  3468.7   0.035       0
  3596.1   0.045       0  5004.1   0.045       0  5015.8   0.045       0
Bank Sta=5004.1,5015.8
Exp/Cntr=0.3,0.1

Type RM Length L Ch R = 1,29543,2818,2818,2818
BEGIN DESCRIPTION:
NC Unknown Stream 25 4.0
END DESCRIPTION:
XS GIS Cut Line= 3
      1455315.85      6876749.20      1457894.00      6876002.66
      1459473.89      6874353.33
#Sta/Elev= 30
  2877.5 1920.45  3143.3 1919.93  3157.7 1920.57  3209.8 1919.52  3328.2 1919.00
  4085.5 1916.73  4307.6 1916.15  4945.0 1915.80  5052.1 1915.95  5096.1 1917.02
  5124.5 1915.73  5129.7 1915.03  5157.5 1914.61  5158.0 1914.11  5168.7 1914.11
  5169.2 1914.61  5196.9 1914.95  5202.1 1916.04  5212.3 1916.38  5235.7 1916.82
  5274.5 1915.93  5341.7 1915.53  5636.4 1915.83  5820.1 1915.32  6442.5 1915.18
  6584.0 1915.62  7001.3 1919.17  7418.7 1918.88  7595.4 1918.06  7845.5 1918.24
#Mann=9,-1,0
  2877.5   0.045       0  3143.3   0.035       0  3328.2   0.045       0
  4085.5    0.07       0  4307.6   0.045       0  4945.0   0.035       0
  5157.5   0.035       0  5169.2   0.035       0  5212.3   0.045       0
Bank Sta=5157.5,5169.2
Exp/Cntr=0.3,0.1

Type RM Length L Ch R = 1,26725,891,891,891
BEGIN DESCRIPTION:
NC Unknown Stream 25 3.0
END DESCRIPTION:
XS GIS Cut Line= 3
      1458111.03      6878858.54      1458926.98      6877912.39
      1459847.13      6874726.60
#Sta/Elev= 30
  2475.8 1932.43  2682.3 1934.17  2769.4 1934.19  2812.2 1931.91  2932.8 1927.66
  2961.4 1925.51  3056.4 1922.07  3067.8 1920.47  3156.3 1918.10  3379.3 1913.48
  3471.6 1912.98  3567.2 1912.27  3761.1 1911.45  3888.9 1911.24  4783.7 1910.25
  5001.1 1908.77  5134.9 1909.11  5218.5 1908.13  5280.6 1909.52  5358.2 1909.26
  5374.3 1910.37  5409.4 1907.94  5409.9 1907.44  5422.6 1907.94  5430.7 1907.95
  5457.6 1910.18  5478.4 1908.91  6116.6 1910.81  6914.8 1915.04  7041.2 1916.37
#Mann=10,-1,0
  2475.8   0.045       0  2682.3    0.07       0  3056.4   0.045       0
  3156.3    0.07       0  3471.6   0.035       0  3567.2   0.045       0
  3761.1    0.07       0  3888.9   0.045       0  5409.4   0.045       0
  5422.6   0.045       0
Bank Sta=5409.4,5422.6
Exp/Cntr=0.3,0.1

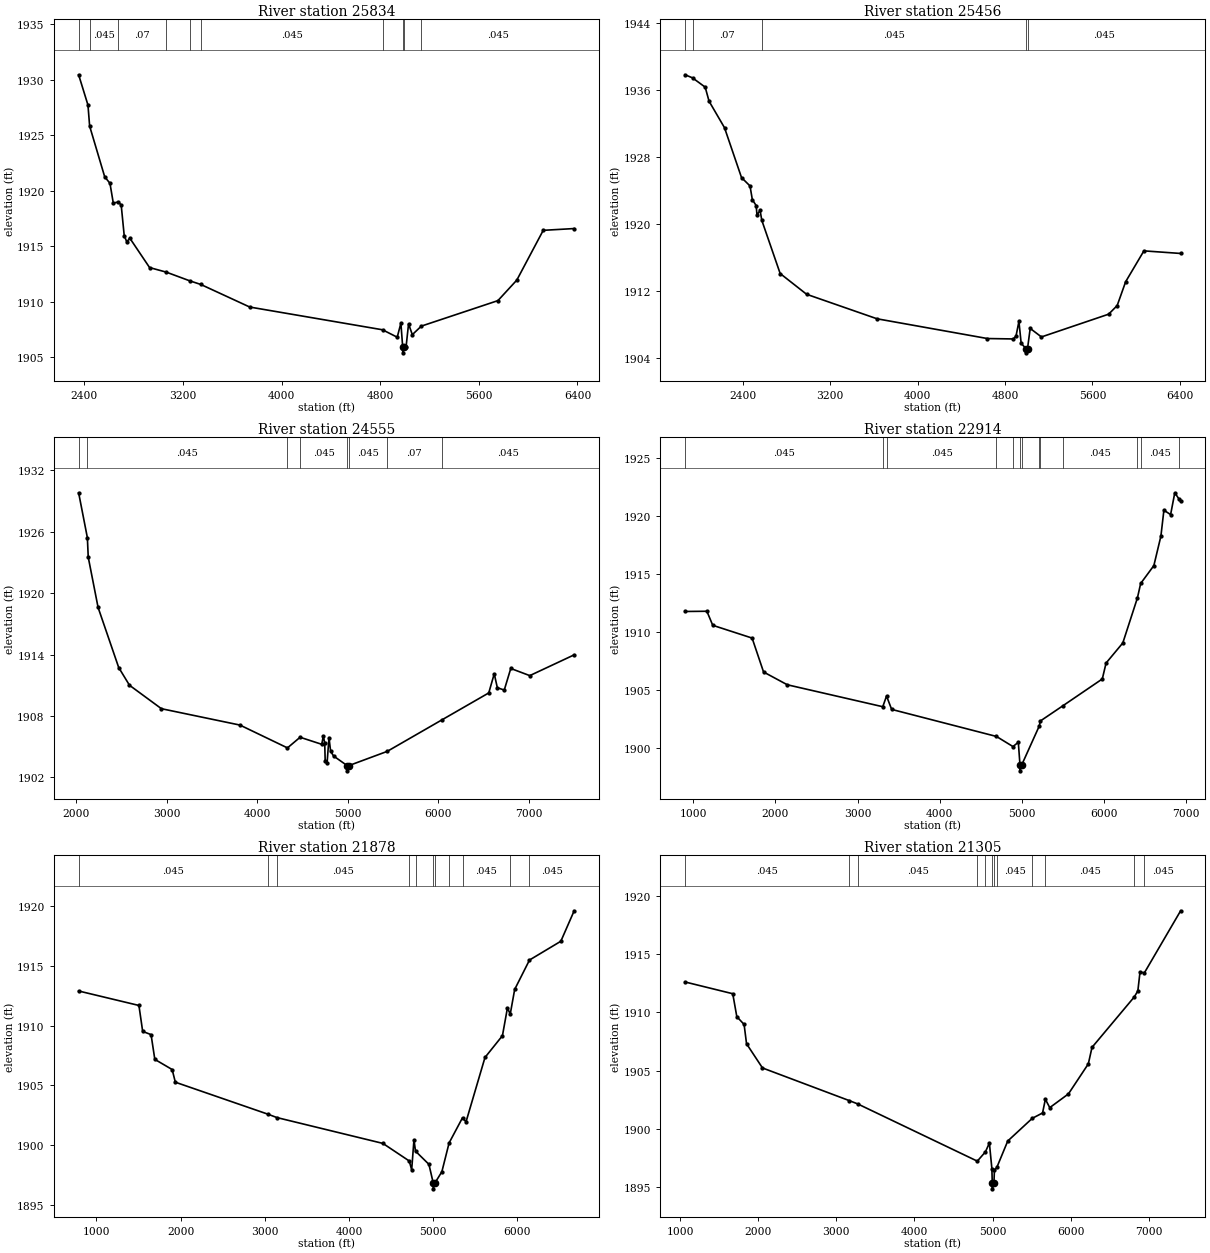
Type RM Length L Ch R = 1,25834,378,378,378
BEGIN DESCRIPTION:
NC Unknown Stream 25 2.0
END DESCRIPTION:
XS GIS Cut Line= 3
      1459274.21      6878980.09      1459829.76      6877243.98
      1460272.28      6875092.14
#Sta/Elev= 30
  2353.6 1930.46  2429.3 1927.73  2442.9 1925.83  2565.0 1921.26  2607.8 1920.67
  2634.6 1918.90  2676.9 1918.98  2698.9 1918.71  2723.3 1915.96  2744.3 1915.38
  2768.4 1915.73  2929.2 1913.07  3064.4 1912.66  3256.1 1911.87  3344.1 1911.55
  3741.7 1909.51  4818.5 1907.46  4938.0 1906.79  4967.7 1908.06  4982.4 1905.88
  4982.9 1905.38  4995.7 1905.88  5009.5 1905.90  5029.9 1907.99  5060.5 1907.02
  5133.5 1907.79  5754.8 1910.09  5907.9 1911.94  6122.3 1916.43  6373.3 1916.59
#Mann=10,-1,0
  2353.6    0.07       0  2442.9   0.045       0  2676.9    0.07       0
  3064.4   0.045       0  3256.1    0.07       0  3344.1   0.045       0
  4818.5    0.07       0  4982.4    0.07       0  4995.7    0.07       0
  5133.5   0.045       0
Bank Sta=4982.4,4995.7
Exp/Cntr=0.3,0.1

Type RM Length L Ch R = 1,25456,901,901,901
BEGIN DESCRIPTION:
NC Unknown Stream 24 18.0
END DESCRIPTION:
XS GIS Cut Line= 4
      1459155.02      6879287.98      1459789.83      6878646.76
      1460463.44      6875924.54      1460352.33      6875105.07
#Sta/Elev= 30
  1873.2 1937.80  1941.3 1937.43  2057.0 1936.32  2092.4 1934.64  2233.8 1931.47
  2389.4 1925.51  2467.1 1924.51  2488.4 1922.87  2523.7 1922.16  2530.8 1921.02
  2559.1 1921.60  2575.2 1920.39  2743.0 1914.04  2984.9 1911.56  3629.3 1908.63
  4638.8 1906.27  4875.8 1906.22  4900.5 1906.55  4927.3 1908.32  4947.9 1905.69
  4992.7 1905.06  4993.2 1904.56  5006.0 1905.06  5030.3 1907.48  5133.3 1906.46
  5747.9 1909.18  5826.2 1910.21  5903.7 1913.06  6070.8 1916.75  6406.8 1916.44
#Mann=5,-1,0
  1873.2   0.035       0  1941.3    0.07       0  2575.2   0.045       0
  4992.7   0.045       0  5006.0   0.045       0
Bank Sta=4992.7,5006
Exp/Cntr=0.3,0.1

Type RM Length L Ch R = 1,24555,1641,1641,1641
BEGIN DESCRIPTION:
NC Unknown Stream 24 17.0
END DESCRIPTION:
XS GIS Cut Line= 4
      1459907.88      6879174.54      1460852.33      6877466.21
      1461262.05      6876146.76      1460275.96      6874244.02
#Sta/Elev= 30
  2023.6 1929.80  2120.3 1925.41  2129.8 1923.51  2238.6 1918.60  2466.5 1912.73
  2585.6 1911.00  2938.4 1908.71  3806.7 1907.11  4331.6 1904.88  4471.2 1905.92
  4710.8 1905.23  4727.7 1906.04  4743.3 1905.37  4748.6 1903.58  4769.5 1903.41
  4790.5 1905.89  4808.5 1904.56  4841.0 1904.09  4993.2 1903.14  4993.7 1902.64
  5006.7 1903.14  5433.8 1904.54  6035.0 1907.60  6556.2 1910.25  6616.9 1912.12
  6651.1 1910.76  6727.6 1910.53  6799.6 1912.64  7009.6 1911.94  7500.3 1913.97
#Mann=8,-1,0
  2023.6    0.07       0  2120.3   0.045       0  4331.6    0.07       0
  4471.2   0.045       0  4993.2   0.045       0  5006.7   0.045       0
  5433.8    0.07       0  6035.0   0.045       0
Bank Sta=4993.2,5006.7
Exp/Cntr=0.3,0.1

Type RM Length L Ch R = 1,22914,1036,1036,1036
BEGIN DESCRIPTION:
Mapping XS 8b19749f
END DESCRIPTION:
XS GIS Cut Line= 4
      1461869.70      6879848.14      1462494.69      6876766.55
      1462208.23      6875273.50      1462477.32      6873928.05
#Sta/Elev= 30
   899.3 1911.77  1164.7 1911.79  1236.2 1910.58  1715.7 1909.48  1855.1 1906.56
  2144.3 1905.46  3307.4 1903.57  3353.2 1904.49  3415.5 1903.34  4692.4 1901.01
  4893.4 1900.14  4958.6 1900.51  4978.9 1898.55  4979.4 1898.05  4999.4 1898.55
  5215.7 1901.94  5224.8 1902.33  5497.1 1903.63  5981.7 1905.96  6027.6 1907.33
  6231.5 1909.06  6409.6 1912.94  6449.0 1914.18  6609.7 1915.72  6695.6 1918.26
  6732.1 1920.49  6813.7 1920.11  6864.7 1921.99  6915.2 1921.46  6936.0 1921.25
#Mann=13,-1,0
   899.3   0.045       0  3307.4   0.035       0  3353.2   0.045       0
  4692.4   0.035       0  4893.4    0.07       0  4978.9    0.07       0
  4999.4    0.07       0  5215.7   0.045       0  5224.8    0.07       0
  5497.1   0.045       0  6409.6    0.07       0  6449.0   0.045       0
  6915.2    0.07       0
Bank Sta=4978.9,4999.4
Exp/Cntr=0.3,0.1

Type RM Length L Ch R = 1,21878,573,573,573
BEGIN DESCRIPTION:
Mapping XS 0cc80c2f
END DESCRIPTION:
XS GIS Cut Line= 4
      1462312.40      6879804.78      1462841.92      6877296.07
      1463345.39      6875030.44      1462972.42      6874102.36
#Sta/Elev= 30
   789.1 1912.89  1505.1 1911.68  1549.7 1909.51  1649.3 1909.24  1693.9 1907.17
  1899.8 1906.32  1937.6 1905.26  3039.0 1902.58  3144.7 1902.30  4402.8 1900.14
  4715.6 1898.67  4744.3 1897.93  4771.6 1900.44  4790.1 1899.49  4949.2 1898.39
  5000.0 1896.84  5000.5 1896.34  5021.3 1896.84  5102.8 1897.77  5188.8 1900.18
  5348.4 1902.29  5389.6 1901.94  5615.0 1907.33  5822.3 1909.15  5881.5 1911.47
  5915.0 1910.96  5967.6 1913.02  6143.6 1915.48  6515.8 1917.05  6674.2 1919.60
#Mann=11,-1,0
   789.1   0.045       0  3039.0   0.035       0  3144.7   0.045       0
  4715.6   0.035       0  4790.1    0.07       0  5000.0    0.07       0
  5021.3    0.07       0  5188.8   0.035       0  5348.4   0.045       0
  5915.0    0.07       0  6143.6   0.045       0
Bank Sta=5000,5021.3
Exp/Cntr=0.3,0.1

Type RM Length L Ch R = 1,21305,978,978,978
BEGIN DESCRIPTION:
Mapping XS 35723b5f
END DESCRIPTION:
XS GIS Cut Line= 4
      1462494.69      6879665.88      1463154.42      6877287.39
      1464248.17      6874483.57      1464352.34      6873624.15
#Sta/Elev= 30
  1064.3 1912.62  1674.4 1911.61  1726.3 1909.64  1819.7 1908.97  1850.8 1907.31
  2055.0 1905.23  3167.3 1902.42  3273.7 1902.14  4805.1 1897.22  4909.1 1898.02
  4959.5 1898.78  4991.7 1896.57  4996.4 1895.34  4996.9 1894.84  5017.8 1895.34
  5023.9 1896.42  5056.1 1896.70  5194.6 1898.95  5508.5 1900.90  5640.2 1901.36
  5676.2 1902.54  5732.4 1901.82  5971.6 1903.00  6226.1 1905.58  6273.3 1907.00
  6813.9 1911.33  6860.1 1911.85  6887.6 1913.47  6944.1 1913.41  7407.9 1918.74
#Mann=12,-1,0
  1064.3   0.045       0  3167.3   0.035       0  3273.7   0.045       0
  4805.1   0.035       0  4909.1    0.07       0  4996.4    0.07       0
  5017.8    0.07       0  5056.1   0.045       0  5508.5   0.035       0
  5676.2   0.045       0  6813.9    0.07       0  6944.1   0.045       0
Bank Sta=4996.4,5017.8
Exp/Cntr=0.3,0.1

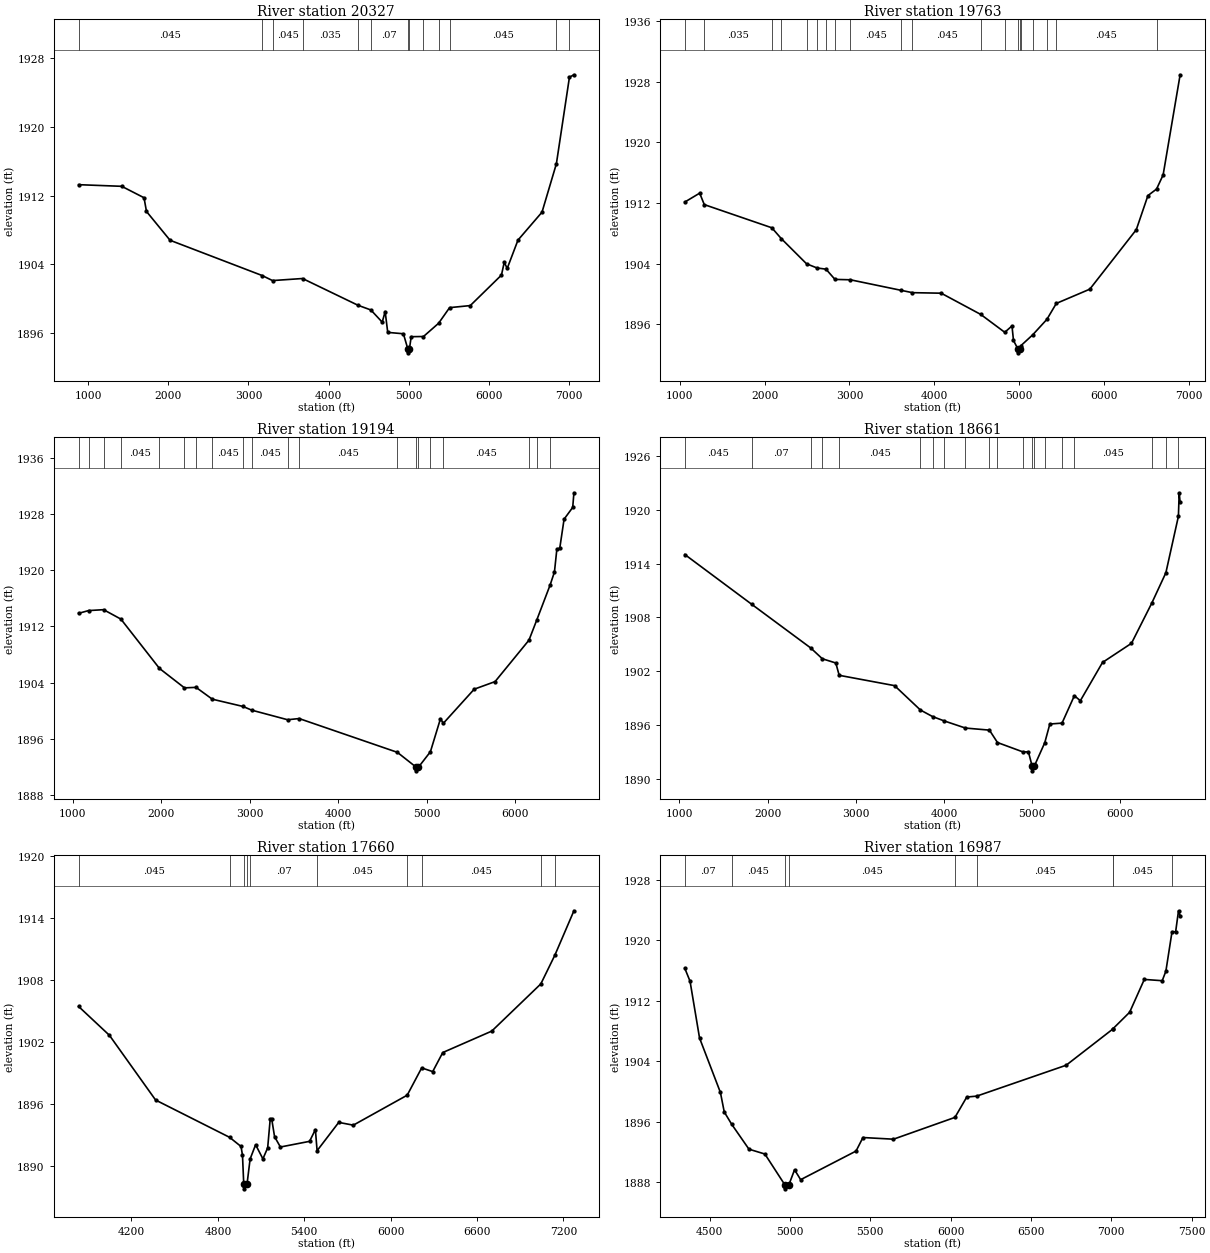
Type RM Length L Ch R = 1,20327,564,564,564
BEGIN DESCRIPTION:
NC Unknown Stream 24 15.0
END DESCRIPTION:
XS GIS Cut Line= 3
      1462554.99      6879838.02      1464555.00      6876238.00
      1465555.00      6874438.00
#Sta/Elev= 30
   882.2 1913.26  1419.9 1913.07  1697.9 1911.74  1728.7 1910.14  2022.7 1906.79
  3170.2 1902.69  3300.5 1902.10  3674.8 1902.34  4368.0 1899.22  4527.0 1898.68
  4668.7 1897.26  4705.3 1898.50  4737.4 1896.07  4933.0 1895.91  4986.5 1894.19
  4987.0 1893.69  5008.8 1894.19  5030.2 1895.57  5183.2 1895.59  5371.8 1897.13
  5508.9 1898.95  5766.9 1899.19  6155.9 1902.74  6190.2 1904.22  6227.9 1903.52
  6361.8 1906.81  6661.5 1910.06  6841.0 1915.70  7003.7 1925.77  7059.6 1926.05
#Mann=13,-1,0
   882.2   0.045       0  3170.2   0.035       0  3300.5   0.045       0
  3674.8   0.035       0  4368.0   0.045       0  4527.0    0.07       0
  4986.5    0.07       0  5008.8    0.07       0  5183.2   0.045       0
  5371.8   0.035       0  5508.9   0.045       0  6841.0   0.035       0
  7003.7    0.07       0
Bank Sta=4986.5,5008.8
Exp/Cntr=0.3,0.1

Type RM Length L Ch R = 1,19763,569,569,569
BEGIN DESCRIPTION:
NC Unknown Stream 24 14.0
END DESCRIPTION:
XS GIS Cut Line= 3
      1463455.01      6879887.98      1465055.00      6876288.00
      1465655.00      6874487.99
#Sta/Elev= 30
  1060.6 1912.12  1235.7 1913.29  1289.8 1911.78  2086.1 1908.72  2196.7 1907.30
  2495.0 1903.97  2618.3 1903.42  2724.1 1903.26  2830.0 1901.91  3011.3 1901.86
  3608.6 1900.47  3742.8 1900.16  4081.6 1900.09  4547.6 1897.29  4830.8 1894.93
  4916.0 1895.77  4933.8 1893.85  4986.2 1892.72  4986.7 1892.22  5008.5 1892.72
  5020.6 1893.16  5160.5 1894.60  5327.6 1896.64  5438.4 1898.74  5832.9 1900.62
  6381.0 1908.47  6518.0 1912.97  6619.8 1913.83  6697.2 1915.70  6897.5 1928.91
#Mann=20,-1,0
  1060.6   0.045       0  1289.8   0.035       0  2086.1   0.045       0
  2196.7   0.035       0  2495.0    0.07       0  2618.3   0.035       0
  2724.1    0.07       0  2830.0   0.045       0  3011.3   0.045       0
  3608.6   0.035       0  3742.8   0.045       0  4547.6   0.045       0
  4830.8    0.07       0  4986.2   0.045       0  5008.5   0.045       0
  5020.6    0.07       0  5160.5   0.045       0  5327.6   0.035       0
  5438.4   0.045       0  6619.8   0.035       0
Bank Sta=4986.2,5008.5
Exp/Cntr=0.3,0.1

Type RM Length L Ch R = 1,19194,533,533,533
BEGIN DESCRIPTION:
NC Unknown Stream 24 13.0
END DESCRIPTION:
XS GIS Cut Line= 3
      1463955.00      6879688.01      1465555.00      6876088.00
      1466355.00      6874638.00
#Sta/Elev= 30
  1069.0 1913.87  1181.1 1914.26  1350.7 1914.39  1546.7 1913.05  1982.4 1906.04
  2264.7 1903.28  2395.6 1903.35  2579.3 1901.67  2925.6 1900.64  3025.2 1900.11
  3430.3 1898.75  3560.0 1898.92  4669.9 1894.12  4884.4 1891.99  4884.9 1891.49
  4906.9 1891.99  5043.2 1894.20  5157.0 1898.90  5189.0 1898.24  5538.0 1903.09
  5773.8 1904.17  6156.8 1910.06  6246.6 1912.98  6396.1 1917.91  6444.6 1919.75
  6472.0 1923.01  6504.2 1923.09  6553.4 1927.25  6650.9 1928.92  6664.6 1931.00
#Mann=20,-1,0
  1069.0   0.045       0  1181.1   0.045       0  1350.7    0.07       0
  1546.7   0.045       0  1982.4    0.07       0  2264.7   0.035       0
  2395.6    0.07       0  2579.3   0.045       0  2925.6    0.07       0
  3025.2   0.045       0  3430.3    0.07       0  3560.0   0.045       0
  4669.9    0.07       0  4884.4    0.07       0  4906.9    0.07       0
  5043.2   0.035       0  5189.0   0.045       0  6156.8    0.07       0
  6246.6   0.045       0  6396.1    0.07       0
Bank Sta=4884.4,4906.9
Exp/Cntr=0.3,0.1

Type RM Length L Ch R = 1,18661,1001,1001,1001
BEGIN DESCRIPTION:
NC Unknown Stream 24 12.0
END DESCRIPTION:
XS GIS Cut Line= 3
      1464255.01      6880087.97      1465855.00      6876488.00
      1466354.99      6874888.02
#Sta/Elev= 30
  1060.5 1915.00  1817.8 1909.47  2488.2 1904.60  2619.6 1903.40  2772.4 1902.93
  2810.6 1901.56  3438.6 1900.41  3731.4 1897.70  3869.1 1896.97  4002.8 1896.48
  4242.2 1895.69  4514.1 1895.46  4605.3 1894.08  4893.0 1893.04  4956.2 1893.04
  4999.2 1891.43  4999.7 1890.93  5021.8 1891.43  5141.6 1894.06  5199.1 1896.14
  5337.3 1896.24  5477.2 1899.29  5544.8 1898.73  5796.3 1902.99  6124.7 1905.12
  6354.3 1909.58  6514.7 1912.97  6656.7 1919.25  6665.8 1921.87  6676.3 1920.81
#Mann=20,-1,0
  1060.5   0.045       0  1817.8    0.07       0  2488.2   0.045       0
  2619.6   0.035       0  2810.6   0.045       0  3731.4   0.045       0
  3869.1   0.035       0  4002.8   0.045       0  4242.2    0.07       0
  4514.1   0.045       0  4605.3    0.07       0  4893.0    0.07       0
  4999.2    0.07       0  5021.8    0.07       0  5141.6    0.07       0
  5337.3   0.035       0  5477.2   0.045       0  6354.3    0.07       0
  6514.7   0.045       0  6656.7    0.07       0
Bank Sta=4999.2,5021.8
Exp/Cntr=0.3,0.1

Type RM Length L Ch R = 1,17660,673,673,673
BEGIN DESCRIPTION:
Mapping XS b0ace7a9
END DESCRIPTION:
XS GIS Cut Line= 4
      1466157.60      6878491.80      1466205.34      6877593.38
      1466378.95      6876503.97      1466404.99      6875067.35
#Sta/Elev= 30
  3832.8 1905.44  4046.9 1902.64  4367.4 1896.36  4881.3 1892.74  4960.7 1891.85
  4970.8 1891.01  4979.4 1888.24  4979.9 1887.74  5002.7 1888.24  5023.8 1890.64
  5062.0 1892.02  5112.6 1890.65  5145.7 1891.72  5163.2 1894.49  5173.4 1894.55
  5193.6 1892.80  5234.1 1891.80  5436.6 1892.35  5477.1 1893.49  5488.9 1891.44
  5639.2 1894.19  5740.4 1893.92  6114.7 1896.83  6215.2 1899.48  6291.7 1899.12
  6361.7 1900.97  6701.8 1903.05  7042.6 1907.63  7140.5 1910.43  7272.5 1914.73
#Mann=10,-1,0
  3832.8   0.045       0  4881.3    0.07       0  4979.4    0.07       0
  5002.7    0.07       0  5023.8    0.07       0  5488.9   0.045       0
  6114.7   0.035       0  6215.2   0.045       0  7042.6    0.07       0
  7140.5   0.045       0
Bank Sta=4979.4,5002.7
Exp/Cntr=0.3,0.1

Type RM Length L Ch R = 1,16987,1514,1514,1514
BEGIN DESCRIPTION:
NC Unknown Stream 24 11.0
END DESCRIPTION:
XS GIS Cut Line= 3
      1467105.00      6877888.01      1466855.00      6877288.00
      1466455.00      6874888.02
#Sta/Elev= 30
  4345.3 1916.27  4377.8 1914.57  4436.9 1907.07  4566.9 1899.87  4590.7 1897.30
  4636.7 1895.68  4744.5 1892.38  4843.6 1891.74  4968.8 1887.64  4969.3 1887.14
  4992.5 1887.64  5028.3 1889.66  5066.3 1888.35  5411.0 1892.13  5454.1 1893.92
  5644.1 1893.70  6026.7 1896.58  6100.3 1899.27  6162.1 1899.39  6718.8 1903.47
  7008.1 1908.23  7010.2 1908.29  7114.1 1910.47  7205.4 1914.81  7316.9 1914.64
  7339.7 1915.90  7377.9 1921.11  7400.5 1921.11  7418.3 1923.88  7428.4 1923.24
#Mann=9,-1,0
  4345.3    0.07       0  4636.7   0.045       0  4968.8   0.045       0
  4992.5   0.045       0  6026.7   0.035       0  6162.1   0.045       0
  7008.1    0.07       0  7010.2   0.045       0  7377.9    0.07       0
Bank Sta=4968.8,4992.5
Exp/Cntr=0.3,0.1

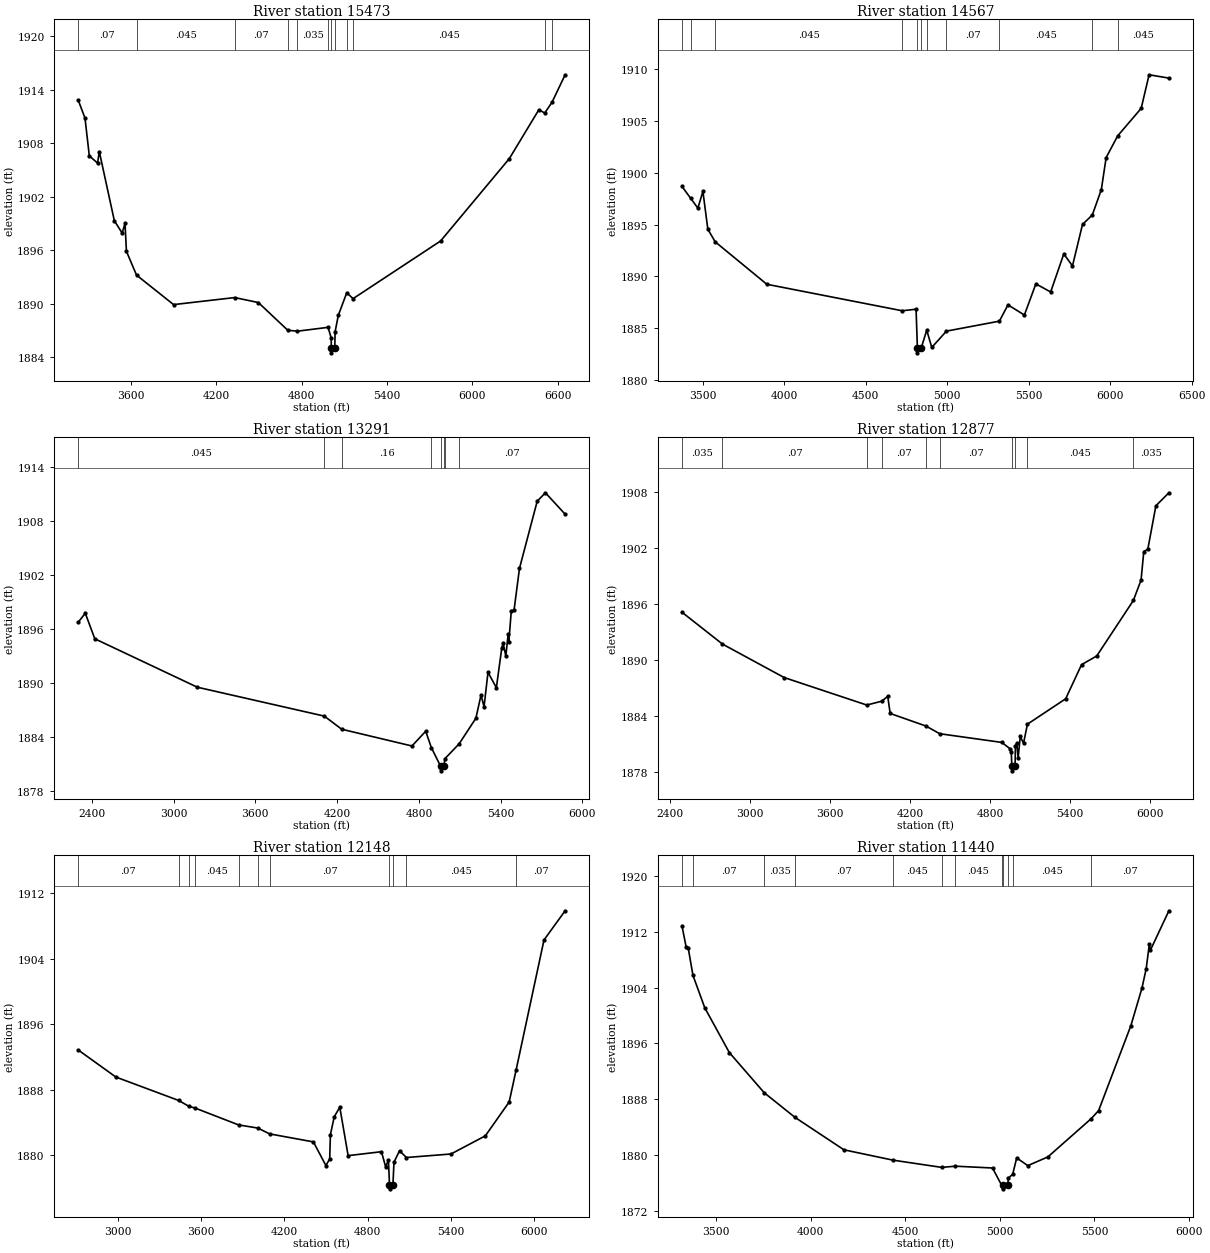
Type RM Length L Ch R = 1,15473,906,906,906
BEGIN DESCRIPTION:
Mapping XS f9a854d1
END DESCRIPTION:
XS GIS Cut Line= 5
      1467997.88      6878005.66      1468102.04      6876812.13
      1467720.10      6876087.30      1467442.32      6875731.40
      1467060.37      6874858.99
#Sta/Elev= 30
  3230.7 1912.82  3278.5 1910.80  3308.7 1906.57  3367.0 1905.75  3378.9 1907.05
  3484.7 1899.28  3539.5 1897.91  3559.6 1898.98  3569.6 1895.86  3640.4 1893.19
  3900.9 1889.88  4330.4 1890.67  4496.6 1890.11  4703.4 1887.00  4771.2 1886.90
  4986.4 1887.33  5008.3 1886.13  5009.3 1884.97  5009.8 1884.47  5033.1 1884.97
  5036.0 1886.85  5058.0 1888.66  5117.5 1891.21  5162.2 1890.55  5777.2 1897.02
  6260.0 1906.26  6467.4 1911.74  6508.7 1911.37  6559.9 1912.58  6651.9 1915.66
#Mann=12,-1,0
  3230.7    0.07       0  3640.4   0.045       0  4330.4    0.07       0
  4703.4   0.045       0  4771.2   0.035       0  4986.4   0.045       0
  5009.3   0.045       0  5033.1   0.045       0  5117.5    0.07       0
  5162.2   0.045       0  6508.7   0.035       0  6559.9   0.045       0
Bank Sta=5009.3,5033.1
Exp/Cntr=0.3,0.1

Type RM Length L Ch R = 1,14567,1276,1276,1276
BEGIN DESCRIPTION:
Mapping XS 84b2f7a7
END DESCRIPTION:
XS GIS Cut Line= 4
      1468418.88      6878005.73      1468544.75      6876859.87
      1468692.32      6875627.23      1468913.68      6875076.01
#Sta/Elev= 30
  3372.1 1898.67  3425.3 1897.53  3469.7 1896.58  3500.6 1898.19  3530.8 1894.55
  3575.8 1893.34  3892.9 1889.25  4723.7 1886.70  4808.7 1886.85  4816.8 1883.15
  4817.3 1882.65  4841.0 1883.15  4874.2 1884.83  4905.0 1883.17  4995.2 1884.74
  5320.1 1885.70  5372.7 1887.27  5473.4 1886.29  5543.9 1889.29  5634.6 1888.51
  5715.2 1892.17  5768.6 1891.02  5830.1 1895.01  5890.2 1895.92  5945.6 1898.36
  5975.2 1901.45  6046.1 1903.54  6190.3 1906.19  6238.7 1909.42  6360.3 1909.10
#Mann=11,-1,0
  3372.1   0.045       0  3425.3    0.07       0  3575.8   0.045       0
  4723.7   0.035       0  4816.8    0.07       0  4841.0   0.035       0
  4874.2   0.045       0  4995.2    0.07       0  5320.1   0.045       0
  5890.2    0.07       0  6046.1   0.045       0
Bank Sta=4816.8,4841
Exp/Cntr=0.3,0.1

Type RM Length L Ch R = 1,13291,414,414,414
BEGIN DESCRIPTION:
Mapping XS 2cc22936
END DESCRIPTION:
XS GIS Cut Line= 4
      1468961.43      6878517.81      1469278.26      6876760.04
      1469495.27      6875501.36      1469521.31      6874993.57
#Sta/Elev= 30
  2300.8 1896.74  2352.8 1897.74  2422.5 1894.90  3174.5 1889.52  4106.0 1886.31
  4233.8 1884.85  4749.1 1882.99  4850.0 1884.63  4891.2 1882.81  4959.6 1880.73
  4960.1 1880.23  4984.0 1880.73  4990.1 1881.57  5095.5 1883.24  5217.9 1886.07
  5255.9 1888.66  5277.8 1887.34  5306.7 1891.17  5368.3 1889.47  5407.6 1893.85
  5417.6 1894.43  5437.6 1892.98  5454.5 1895.39  5459.5 1894.52  5477.7 1898.00
  5497.7 1898.05  5537.7 1902.72  5667.9 1910.19  5728.0 1911.12  5872.6 1908.74
#Mann=8,-1,0
  2300.8   0.045       0  4106.0   0.035       0  4233.8    0.16       0
  4891.2    0.07       0  4959.6    0.07       0  4984.0    0.07       0
  4990.1    0.16       0  5095.5    0.07       0
Bank Sta=4959.6,4984
Exp/Cntr=0.3,0.1

Type RM Length L Ch R = 1,12877,729,729,729
BEGIN DESCRIPTION:
Mapping XS cc08c1f7
END DESCRIPTION:
XS GIS Cut Line= 4
      1469447.53      6878270.46      1469603.78      6876898.93
      1469920.62      6875306.05      1470007.17      6874661.22
#Sta/Elev= 30
  2486.9 1895.11  2791.1 1891.70  3254.3 1888.12  3874.1 1885.18  3986.4 1885.59
  4031.4 1886.11  4049.8 1884.28  4318.9 1882.93  4421.8 1882.11  4887.8 1881.18
  4949.0 1880.51  4959.2 1880.11  4962.7 1878.64  4963.2 1878.14  4987.4 1878.64
  4989.8 1880.80  5000.0 1881.10  5010.2 1879.52  5026.2 1881.82  5051.0 1881.09
  5079.9 1883.13  5367.1 1885.85  5486.3 1889.50  5600.4 1890.43  5875.3 1896.37
  5933.0 1898.55  5953.5 1901.60  5983.8 1901.86  6044.4 1906.50  6142.0 1907.89
#Mann=10,-1,0
  2486.9   0.035       0  2791.1    0.07       0  3874.1   0.035       0
  3986.4    0.07       0  4318.9   0.035       0  4421.8    0.07       0
  4962.7    0.07       0  4987.4    0.07       0  5079.9   0.045       0
  5875.3   0.035       0
Bank Sta=4962.7,4987.4
Exp/Cntr=0.3,0.1

Type RM Length L Ch R = 1,12148,708,708,708
BEGIN DESCRIPTION:
Mapping XS b330adbf
END DESCRIPTION:
XS GIS Cut Line= 4
      1470415.41      6878248.81      1470519.58      6876790.42
      1470441.45      6875384.17      1470220.09      6874785.18
#Sta/Elev= 30
  2715.1 1892.84  2986.6 1889.53  3438.6 1886.67  3511.6 1885.96  3560.2 1885.72
  3870.4 1883.68  4009.8 1883.29  4094.3 1882.58  4410.0 1881.60  4500.1 1878.71
  4527.6 1879.52  4532.6 1882.48  4560.2 1884.67  4600.3 1885.84  4660.4 1879.92
  4900.7 1880.40  4930.8 1878.54  4950.8 1879.40  4958.5 1876.36  4959.0 1875.86
  4983.2 1876.36  4990.9 1879.12  5030.9 1880.52  5080.2 1879.69  5401.5 1880.12
  5649.2 1882.34  5821.0 1886.48  5870.8 1890.38  6071.9 1906.29  6224.2 1909.86
#Mann=11,-1,0
  2715.1    0.07       0  3438.6   0.045       0  3511.6    0.07       0
  3560.2   0.045       0  3870.4    0.07       0  4009.8   0.035       0
  4094.3    0.07       0  4958.5    0.07       0  4983.2    0.07       0
  5080.2   0.045       0  5870.8    0.07       0
Bank Sta=4958.5,4983.2
Exp/Cntr=0.3,0.1

Type RM Length L Ch R = 1,11440,791,791,791
BEGIN DESCRIPTION:
NC Unknown Stream 24 5.0
END DESCRIPTION:
XS GIS Cut Line= 3
      1471505.01      6877038.03      1470855.00      6875488.00
      1470455.01      6874688.03
#Sta/Elev= 30
  3318.7 1912.87  3340.4 1909.87  3351.3 1909.74  3376.9 1905.74  3439.3 1901.10
  3569.0 1894.68  3753.7 1888.91  3916.1 1885.38  4175.4 1880.72  4435.9 1879.23
  4692.1 1878.20  4765.2 1878.37  4961.1 1878.11  5008.6 1875.67  5017.7 1875.62
  5018.2 1875.12  5042.7 1875.62  5044.2 1876.65  5067.8 1877.21  5088.9 1879.56
  5147.6 1878.45  5253.9 1879.70  5482.6 1885.18  5522.2 1886.35  5692.7 1898.53
  5751.4 1903.92  5773.7 1906.69  5790.5 1910.23  5796.1 1909.37  5893.9 1915.02
#Mann=12,-1,0
  3318.7   0.035       0  3376.9    0.07       0  3753.7   0.035       0
  3916.1    0.07       0  4435.9   0.045       0  4692.1    0.07       0
  4765.2   0.045       0  5008.6    0.07       0  5017.7   0.045       0
  5042.7    0.07       0  5067.8   0.045       0  5482.6    0.07       0
Bank Sta=5017.7,5042.7
Exp/Cntr=0.3,0.1