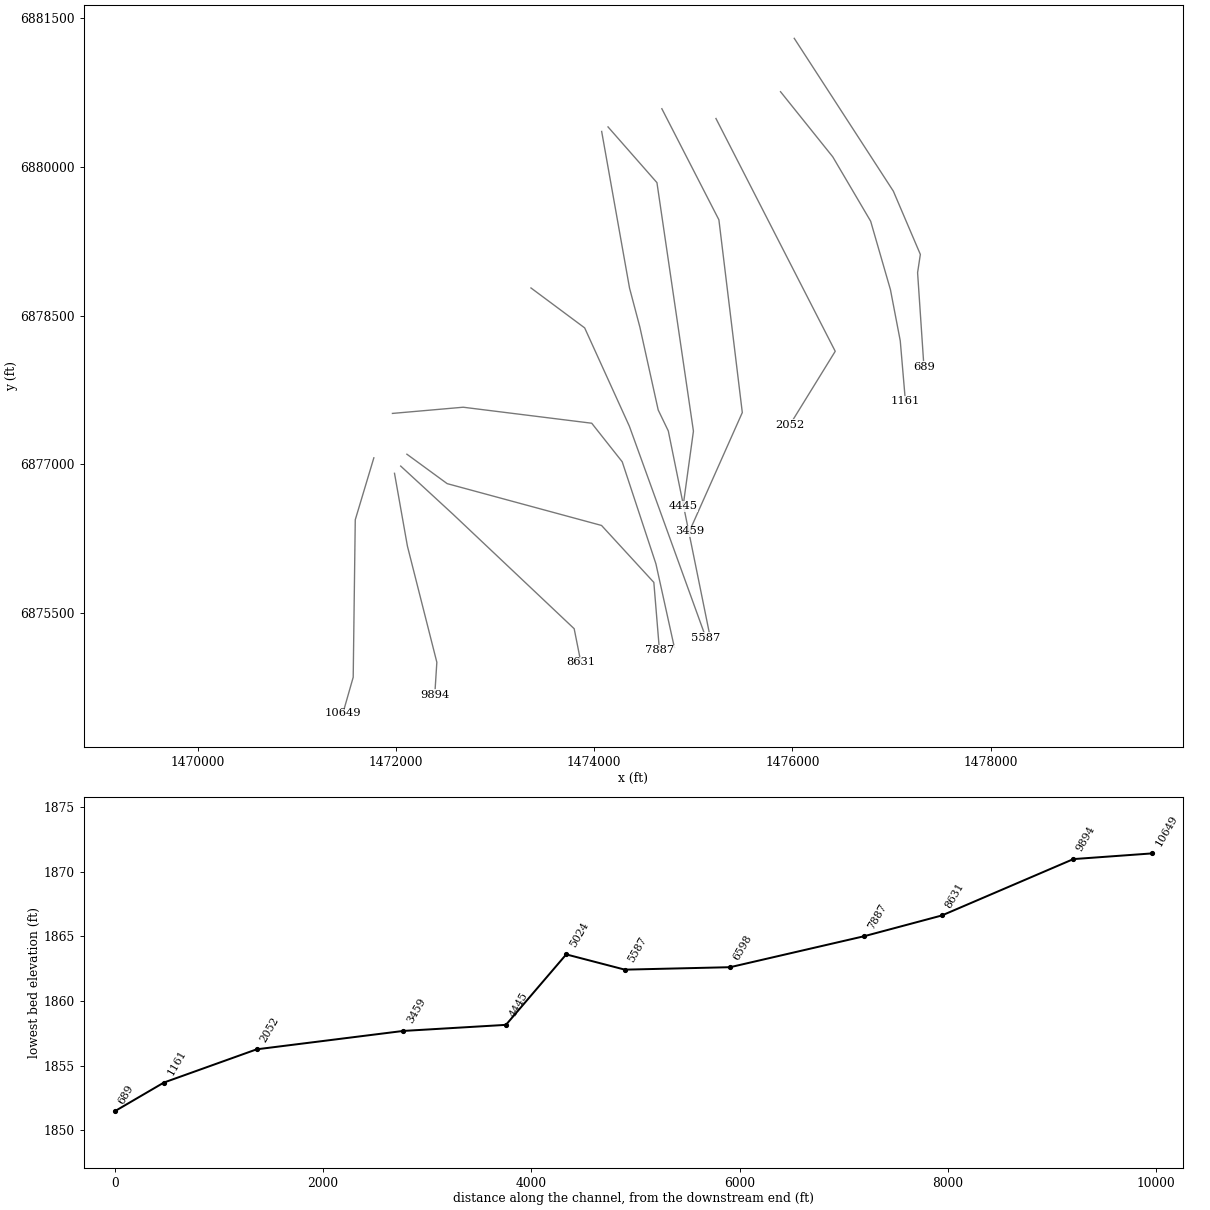
HEC-RAS study NC Unknown Stream 24.prj: NC Unknown Stream 24 Base Level Engineering

--- NC Unknown Stream 24.g01 (geometry) --- (continued)

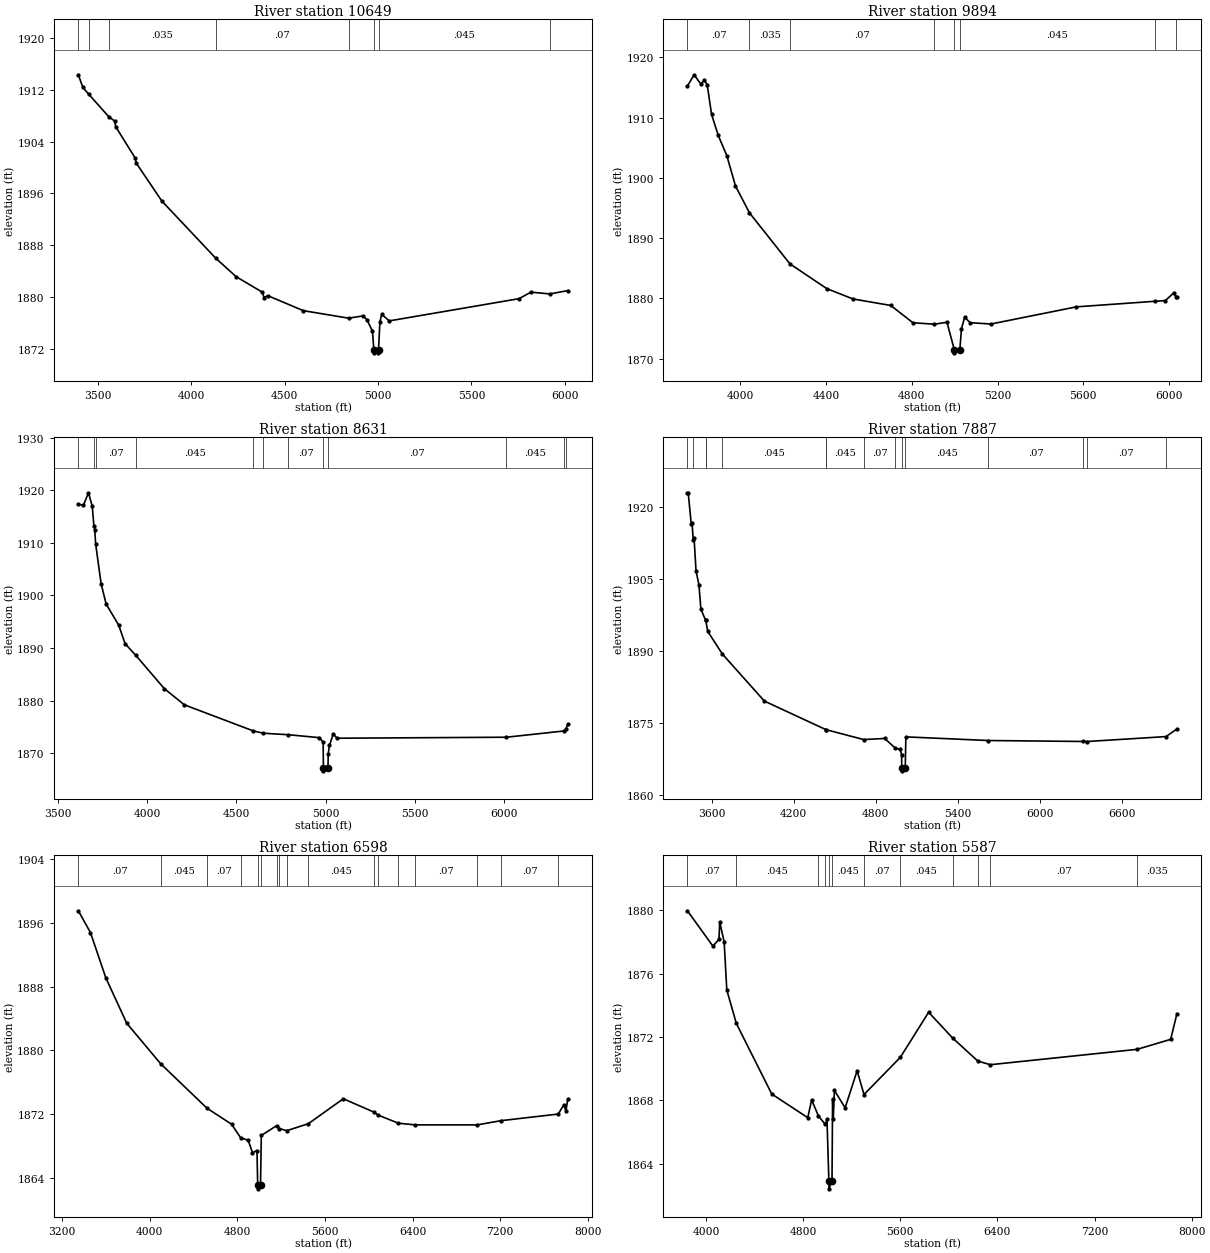
Type RM Length L Ch R = 1,10649,755,755,755
BEGIN DESCRIPTION:
Mapping XS 78ec7d9f
END DESCRIPTION:
XS GIS Cut Line= 4
      1471777.38      6877064.99      1471589.89      6876440.02
      1471569.06      6874851.48      1471464.90      6874486.93
#Sta/Elev= 30
  3395.2 1914.32  3419.5 1912.37  3451.7 1911.29  3557.7 1907.87  3590.0 1907.17
  3595.3 1906.31  3699.7 1901.46  3705.3 1900.70  3842.4 1894.83  4130.0 1886.04
  4239.7 1883.17  4379.7 1880.78  4389.7 1879.94  4409.7 1880.23  4599.8 1877.92
  4842.0 1876.76  4919.8 1877.11  4939.8 1876.55  4969.8 1874.77  4977.3 1871.91
  4977.8 1871.41  5001.8 1871.41  5002.3 1871.91  5009.8 1876.21  5019.8 1877.34
  5059.8 1876.34  5754.4 1879.77  5818.5 1880.78  5919.0 1880.50  6015.5 1881.01
#Mann=8,-1,0
  3395.2   0.035       0  3451.7    0.07       0  3557.7   0.035       0
  4130.0    0.07       0  4842.0   0.045       0  4977.3   0.045       0
  5002.3   0.045       0  5919.0   0.035       0
Bank Sta=4977.3,5002.3
Exp/Cntr=0.3,0.1

Type RM Length L Ch R = 1,9894,1263,1263,1263
BEGIN DESCRIPTION:
Mapping XS 326a3b19
END DESCRIPTION:
XS GIS Cut Line= 4
      1471985.73      6876908.76      1472115.93      6876174.39
      1472412.81      6875002.52      1472391.97      6874674.39
#Sta/Elev= 30
  3753.4 1915.23  3784.6 1917.09  3815.1 1915.59  3832.8 1916.16  3845.6 1915.44
  3865.9 1910.53  3896.9 1907.05  3937.0 1903.69  3977.6 1898.64  4042.9 1894.18
  4231.5 1885.73  4403.5 1881.62  4526.4 1879.90  4701.8 1878.83  4805.5 1875.96
  4905.5 1875.72  4964.3 1876.04  4998.5 1871.47  4999.0 1870.97  5024.1 1871.47
  5031.9 1874.95  5046.3 1876.85  5073.2 1875.97  5169.3 1875.75  5568.3 1878.60
  5934.6 1879.52  5983.2 1879.64  6023.3 1880.95  6032.2 1880.25  6036.9 1880.22
#Mann=8,-1,0
  3753.4    0.07       0  4042.9   0.035       0  4231.5    0.07       0
  4905.5   0.045       0  4998.5   0.045       0  5024.1   0.045       0
  5934.6   0.035       0  6032.2   0.045       0
Bank Sta=4998.5,5024.1
Exp/Cntr=0.3,0.1

Type RM Length L Ch R = 1,8631,744,744,744
BEGIN DESCRIPTION:
Mapping XS dcf83eb7
END DESCRIPTION:
XS GIS Cut Line= 4
      1472048.25      6876981.66      1472574.26      6876497.31
      1473798.22      6875341.06      1473865.87      6875001.72
#Sta/Elev= 30
  3613.0 1917.37  3641.6 1917.18  3669.9 1919.55  3690.9 1917.02  3700.2 1913.32
  3705.1 1912.53  3710.1 1909.82  3740.8 1902.23  3769.2 1898.35  3839.7 1894.33
  3875.2 1890.83  3935.2 1888.60  4094.7 1882.28  4207.5 1879.18  4594.2 1874.21
  4649.5 1873.77  4790.1 1873.49  4964.6 1872.93  4986.1 1872.06  4987.4 1867.11
  4987.9 1866.61  5013.1 1867.11  5014.4 1869.83  5021.2 1871.44  5042.7 1873.64
  5063.7 1872.82  6013.8 1873.01  6336.7 1874.20  6346.8 1874.50  6357.8 1875.52
#Mann=12,-1,0
  3613.0    0.07       0  3700.2   0.035       0  3710.1    0.07       0
  3935.2   0.045       0  4594.2    0.07       0  4649.5   0.045       0
  4790.1    0.07       0  4987.4    0.07       0  5013.1    0.07       0
  6013.8   0.045       0  6336.7    0.07       0  6346.8   0.035       0
Bank Sta=4987.4,5013.1
Exp/Cntr=0.3,0.1

Type RM Length L Ch R = 1,7887,1289,1289,1289
BEGIN DESCRIPTION:
Mapping XS 83537733
END DESCRIPTION:
XS GIS Cut Line= 5
      1472110.73      6877101.48      1472516.97      6876804.60
      1474074.26      6876382.73      1474601.96      6875808.18
      1474658.47      6875123.30
#Sta/Elev= 30
  3421.4 1922.97  3427.1 1922.97  3449.0 1916.51  3455.2 1916.58  3464.3 1913.10
  3469.9 1913.48  3484.5 1906.62  3505.4 1903.84  3520.0 1898.72  3553.7 1896.44
  3554.7 1896.49  3570.2 1894.06  3676.9 1889.37  3984.7 1879.55  4437.0 1873.58
  4438.9 1873.57  4712.2 1871.53  4865.3 1871.76  4943.9 1869.74  4979.3 1869.46
  4989.6 1868.40  4990.5 1865.51  4991.0 1865.01  5016.2 1865.51  5020.7 1872.09
  5624.6 1871.33  6317.2 1871.13  6345.8 1871.12  6925.1 1872.15  7005.3 1873.72
#Mann=15,-1,0
  3421.4   0.035       0  3464.3    0.07       0  3553.7   0.035       0
  3554.7    0.07       0  3676.9   0.045       0  4437.0    0.07       0
  4438.9   0.045       0  4712.2    0.07       0  4943.9   0.045       0
  4990.5   0.045       0  5016.2   0.045       0  5624.6    0.07       0
  6317.2   0.035       0  6345.8    0.07       0  6925.1   0.035       0
Bank Sta=4990.5,5016.2
Exp/Cntr=0.3,0.1

Type RM Length L Ch R = 1,6598,1011,1011,1011
BEGIN DESCRIPTION:
Mapping XS 8f74fe60
END DESCRIPTION:
XS GIS Cut Line= 6
      1471964.86      6877512.93      1472678.43      6877575.44
      1473975.31      6877413.98      1474283.13      6877024.68
      1474623.00      6875995.11      1474809.09      6875151.69
#Sta/Elev= 30
  3349.5 1897.52  3460.0 1894.79  3600.6 1889.10  3791.3 1883.40  4100.5 1878.32
  4524.0 1872.73  4747.6 1870.73  4831.3 1869.02  4899.4 1868.71  4939.1 1867.17
  4980.1 1867.41  4986.6 1863.11  4987.1 1862.61  5012.4 1863.11  5019.7 1869.31
  5159.3 1870.54  5184.8 1870.18  5251.9 1869.91  5449.2 1870.79  5768.2 1873.92
  6049.1 1872.23  6085.3 1871.87  6270.6 1870.85  6424.2 1870.64  6990.3 1870.64
  7208.1 1871.17  7729.9 1872.00  7779.8 1873.14  7800.2 1872.38  7816.9 1873.90
#Mann=17,-1,0
  3349.5    0.07       0  4100.5   0.045       0  4524.0    0.07       0
  4831.3   0.045       0  4986.6   0.045       0  5012.4   0.045       0
  5159.3    0.07       0  5184.8   0.045       0  5251.9    0.07       0
  5449.2   0.045       0  6049.1    0.07       0  6085.3   0.045       0
  6270.6   0.035       0  6424.2    0.07       0  6990.3   0.035       0
  7208.1    0.07       0  7729.9   0.035       0
Bank Sta=4986.6,5012.4
Exp/Cntr=0.3,0.1

Type RM Length L Ch R = 1,5587,563,563,563
BEGIN DESCRIPTION:
Mapping XS 1fe37072
END DESCRIPTION:
XS GIS Cut Line= 4
      1473362.45      6878778.57      1473904.13      6878375.78
      1474355.51      6877382.73      1475126.49      6875252.29
#Sta/Elev= 30
  3847.0 1879.96  4056.6 1877.73  4106.7 1878.16  4112.9 1879.26  4149.3 1878.00
  4171.3 1874.96  4249.9 1872.85  4541.6 1868.40  4838.1 1866.91  4870.1 1868.03
  4926.5 1867.01  4983.0 1866.48  4996.4 1866.81  5012.0 1862.92  5012.5 1862.42
  5037.8 1862.92  5042.5 1868.06  5048.0 1866.83  5057.8 1868.63  5145.8 1867.53
  5244.6 1869.87  5301.2 1868.37  5600.2 1870.71  5833.8 1873.56  6030.4 1871.94
  6238.7 1870.48  6341.8 1870.25  7551.5 1871.22  7827.3 1871.85  7878.5 1873.46
#Mann=12,-1,0
  3847.0    0.07       0  4249.9   0.045       0  4926.5    0.07       0
  4983.0   0.045       0  5012.0   0.045       0  5037.8   0.045       0
  5301.2    0.07       0  5600.2   0.045       0  6030.4    0.07       0
  6238.7   0.035       0  6341.8    0.07       0  7551.5   0.035       0
Bank Sta=5012,5037.8
Exp/Cntr=0.3,0.1

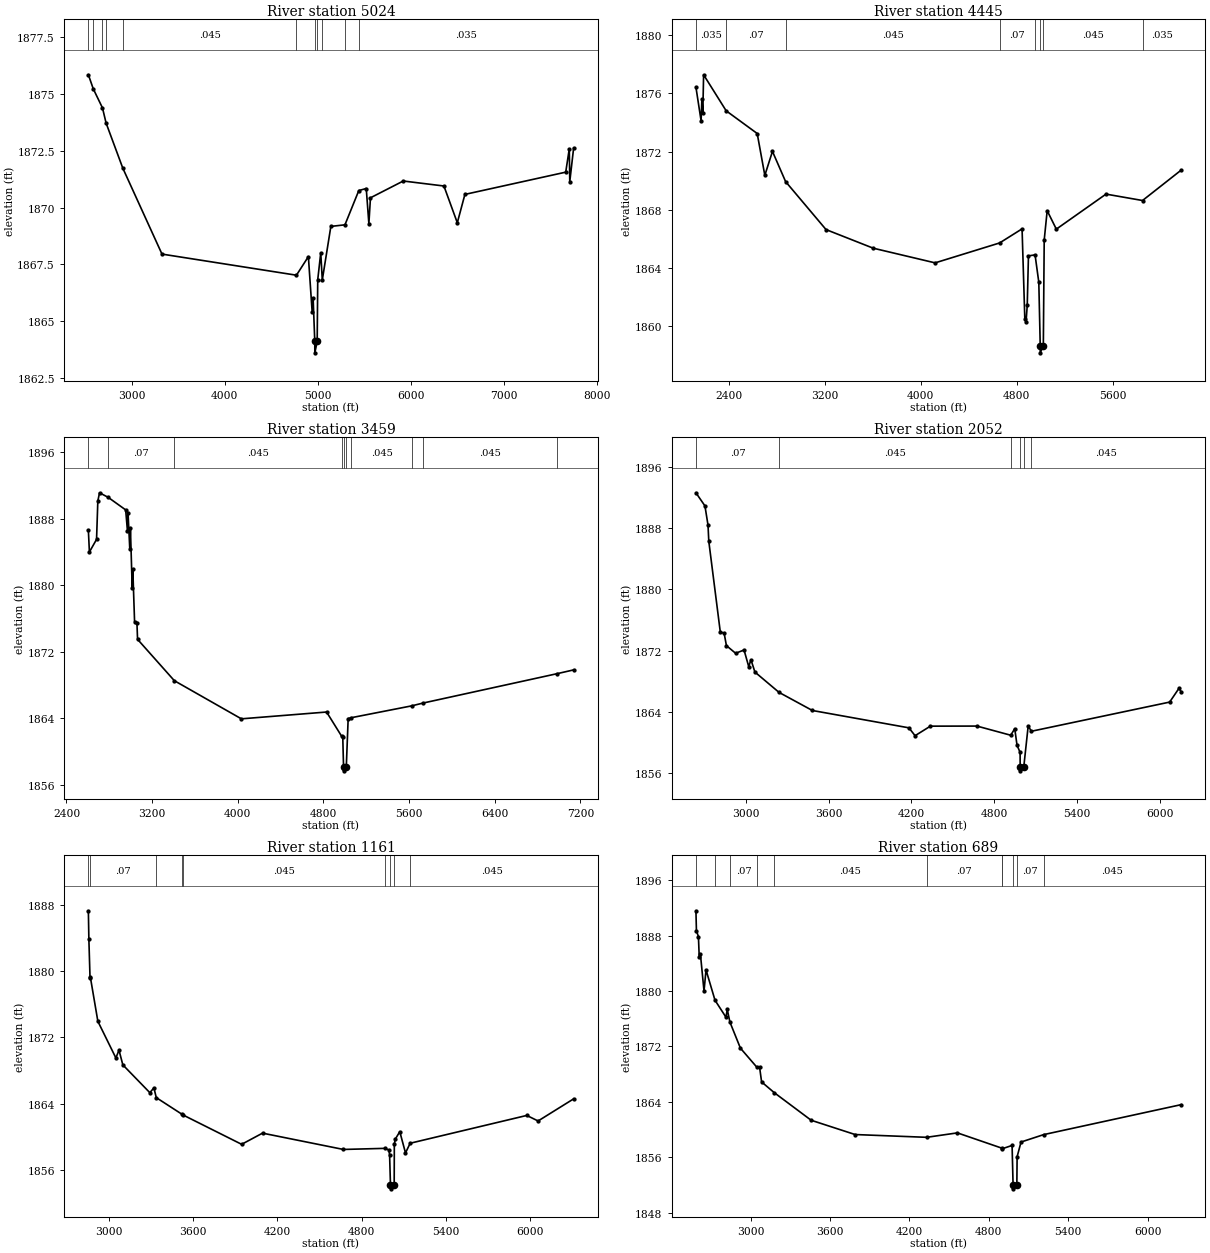
Type RM Length L Ch R = 1,5024,579,579,579
BEGIN DESCRIPTION:
Mapping XS 3106e556
END DESCRIPTION:
XS GIS Cut Line= 6
      1474075.65      6880357.52      1474356.90      6878776.80
      1474461.07      6878383.57      1474645.97      6877547.63
      1474747.96      6877335.72      1475168.95      6875262.98
#Sta/Elev= 30
  2534.3 1875.85  2587.1 1875.23  2686.1 1874.39  2725.2 1873.72  2904.3 1871.74
  3326.1 1867.95  4772.3 1867.02  4900.6 1867.84  4941.5 1865.39  4951.8 1866.00
  4969.5 1864.10  4970.0 1863.60  4995.4 1864.10  5001.3 1866.82  5033.7 1868.01
  5050.3 1866.81  5142.4 1869.17  5294.0 1869.24  5443.1 1870.75  5523.1 1870.84
  5551.3 1869.29  5568.4 1870.43  5921.2 1871.17  6358.4 1870.95  6502.5 1869.33
  6584.1 1870.58  7668.5 1871.56  7706.9 1872.59  7712.0 1871.14  7753.1 1872.61
#Mann=11,-1,0
  2534.3   0.035       0  2587.1    0.07       0  2686.1   0.045       0
  2725.2   0.035       0  2904.3   0.045       0  4772.3    0.07       0
  4969.5    0.07       0  4995.4    0.07       0  5050.3   0.035       0
  5294.0    0.07       0  5443.1   0.035       0
Bank Sta=4969.5,4995.4
Exp/Cntr=0.3,0.1

Type RM Length L Ch R = 1,4445,986,986,986
BEGIN DESCRIPTION:
NC Unknown Stream 24 4.0
END DESCRIPTION:
XS GIS Cut Line= 4
      1474139.72      6880403.28      1474633.29      6879841.06
      1475001.35      6877334.12      1474897.19      6876577.21
#Sta/Elev= 30
  2126.2 1876.43  2169.3 1874.11  2176.0 1875.63  2183.5 1874.63  2190.2 1877.28
  2378.5 1874.80  2637.1 1873.24  2700.7 1870.36  2764.3 1872.01  2874.0 1869.93
  3211.0 1866.63  3604.5 1865.35  4120.6 1864.34  4658.4 1865.71  4845.7 1866.68
  4868.5 1860.51  4878.7 1860.26  4888.8 1861.42  4898.9 1864.82  4954.1 1864.89
  4985.3 1863.00  4997.1 1858.65  4997.6 1858.15  5023.0 1858.65  5030.3 1865.91
  5055.1 1867.93  5131.3 1866.66  5545.6 1869.07  5850.1 1868.63  6172.2 1870.72
#Mann=8,-1,0
  2126.2   0.035       0  2378.5    0.07       0  2874.0   0.045       0
  4658.4    0.07       0  4954.1   0.045       0  4997.1   0.045       0
  5023.0   0.045       0  5850.1   0.035       0
Bank Sta=4997.1,5023
Exp/Cntr=0.3,0.1

Type RM Length L Ch R = 1,3459,1407,1407,1407
BEGIN DESCRIPTION:
NC Unknown Stream 24 3.0
END DESCRIPTION:
XS GIS Cut Line= 4
      1474682.76      6880586.65      1475258.29      6879466.06
      1475494.40      6877521.62      1474960.45      6876321.95
#Sta/Elev= 30
  2604.6 1886.64  2614.3 1884.02  2681.1 1885.54  2693.0 1890.16  2708.9 1891.15
  2789.5 1890.60  2953.0 1889.09  2969.5 1886.56  2975.2 1888.72  2991.7 1884.33
  2997.4 1886.86  3013.9 1879.74  3019.5 1881.98  3036.1 1875.65  3058.3 1875.45
  3064.0 1873.51  3407.6 1868.53  4033.6 1863.94  4829.4 1864.76  4970.7 1861.83
  4980.5 1861.75  4987.7 1858.18  4988.2 1857.68  5013.6 1858.18  5030.9 1863.97
  5061.6 1864.08  5623.7 1865.50  5730.6 1865.84  6983.9 1869.38  7136.2 1869.83
#Mann=10,-1,0
  2604.6   0.035       0  2789.5    0.07       0  3407.6   0.045       0
  4970.7    0.07       0  4987.7    0.07       0  5013.6    0.07       0
  5061.6   0.045       0  5623.7    0.07       0  5730.6   0.045       0
  6983.9   0.035       0
Bank Sta=4987.7,5013.6
Exp/Cntr=0.3,0.1

Type RM Length L Ch R = 1,2052,891,891,891
BEGIN DESCRIPTION:
NC Unknown Stream 24 2.0
END DESCRIPTION:
XS GIS Cut Line= 3
      1475228.62      6880487.99      1476431.90      6878139.67
      1475973.57      6877396.61
#Sta/Elev= 30
  2640.4 1892.66  2705.7 1890.94  2727.9 1888.42  2733.5 1886.31  2816.7 1874.44
  2844.5 1874.28  2861.1 1872.65  2927.7 1871.65  2988.7 1872.08  3022.4 1869.91
  3038.7 1870.80  3067.4 1869.19  3241.9 1866.53  3483.1 1864.16  4181.9 1861.89
  4226.3 1860.86  4337.3 1862.11  4674.2 1862.12  4918.8 1860.92  4947.7 1861.78
  4964.3 1859.61  4986.5 1858.67  4987.0 1856.76  4987.5 1856.26  5013.0 1856.76
  5045.0 1862.13  5068.3 1861.44  6068.9 1865.26  6136.3 1867.06  6152.1 1866.63
#Mann=6,-1,0
  2640.4    0.07       0  3241.9   0.045       0  4918.8    0.07       0
  4987.0    0.07       0  5013.0    0.07       0  5068.3   0.045       0
Bank Sta=4987,5013
Exp/Cntr=0.3,0.1

Type RM Length L Ch R = 1,1161,472,472,472
BEGIN DESCRIPTION:
Mapping XS 0ec56b62
END DESCRIPTION:
XS GIS Cut Line= 6
      1475879.90      6880758.47      1476407.25      6880100.91
      1476789.20      6879452.04      1476988.85      6878761.28
      1477087.81      6878245.66      1477139.89      6877636.29
#Sta/Elev= 30
  2855.3 1887.29  2858.9 1883.86  2866.9 1879.31  2870.4 1879.18  2922.9 1873.93
  3050.9 1869.51  3073.3 1870.44  3100.5 1868.67  3292.6 1865.31  3321.4 1865.89
  3338.5 1864.71  3523.2 1862.68  3531.6 1862.59  3945.6 1859.07  4094.1 1860.42
  4669.4 1858.45  4962.7 1858.58  4992.8 1858.39  4998.0 1857.80  5004.2 1854.19
  5004.7 1853.69  5030.7 1854.19  5031.7 1859.09  5038.3 1859.69  5070.5 1860.60
  5111.1 1858.03  5144.3 1859.20  5973.9 1862.56  6054.2 1861.89  6306.8 1864.56
#Mann=9,-1,0
  2855.3   0.035       0  2870.4    0.07       0  3338.5   0.045       0
  3523.2    0.07       0  3531.6   0.045       0  4962.7    0.07       0
  5004.2    0.07       0  5030.7    0.07       0  5144.3   0.045       0
Bank Sta=5004.2,5030.7
Exp/Cntr=0.3,0.1

Type RM Length L Ch R = 1,689,0,0,0
BEGIN DESCRIPTION:
NC Unknown Stream 24 1.0
END DESCRIPTION:
XS GIS Cut Line= 5
      1476018.38      6881296.84      1477018.36      6879754.77
      1477290.50      6879116.97      1477262.72      6878932.94
      1477326.52      6877986.15
#Sta/Elev= 30
  2587.4 1891.57  2591.2 1888.67  2606.3 1887.85  2612.3 1884.91  2621.5 1885.28
  2648.5 1880.00  2663.7 1883.04  2731.5 1878.67  2814.7 1876.21  2823.9 1877.36
  2844.2 1875.52  2923.5 1871.76  3048.7 1868.99  3068.5 1869.00  3083.6 1866.89
  3179.2 1865.34  3458.1 1861.36  3790.4 1859.30  4330.1 1858.90  4563.1 1859.54
  4898.4 1857.34  4903.3 1857.26  4976.3 1857.73  4983.9 1851.97  4984.4 1851.47
  5012.2 1851.97  5014.3 1856.10  5044.0 1858.22  5215.1 1859.29  6253.8 1863.61
#Mann=11,-1,0
  2587.4    0.07       0  2731.5   0.035       0  2844.2    0.07       0
  3048.7   0.035       0  3179.2   0.045       0  4330.1    0.07       0
  4898.4   0.045       0  4903.3    0.07       0  4983.9    0.07       0
  5012.2    0.07       0  5215.1   0.045       0
Bank Sta=4983.9,5012.2
Exp/Cntr=0.3,0.1

Chan Stop Cuts=-1