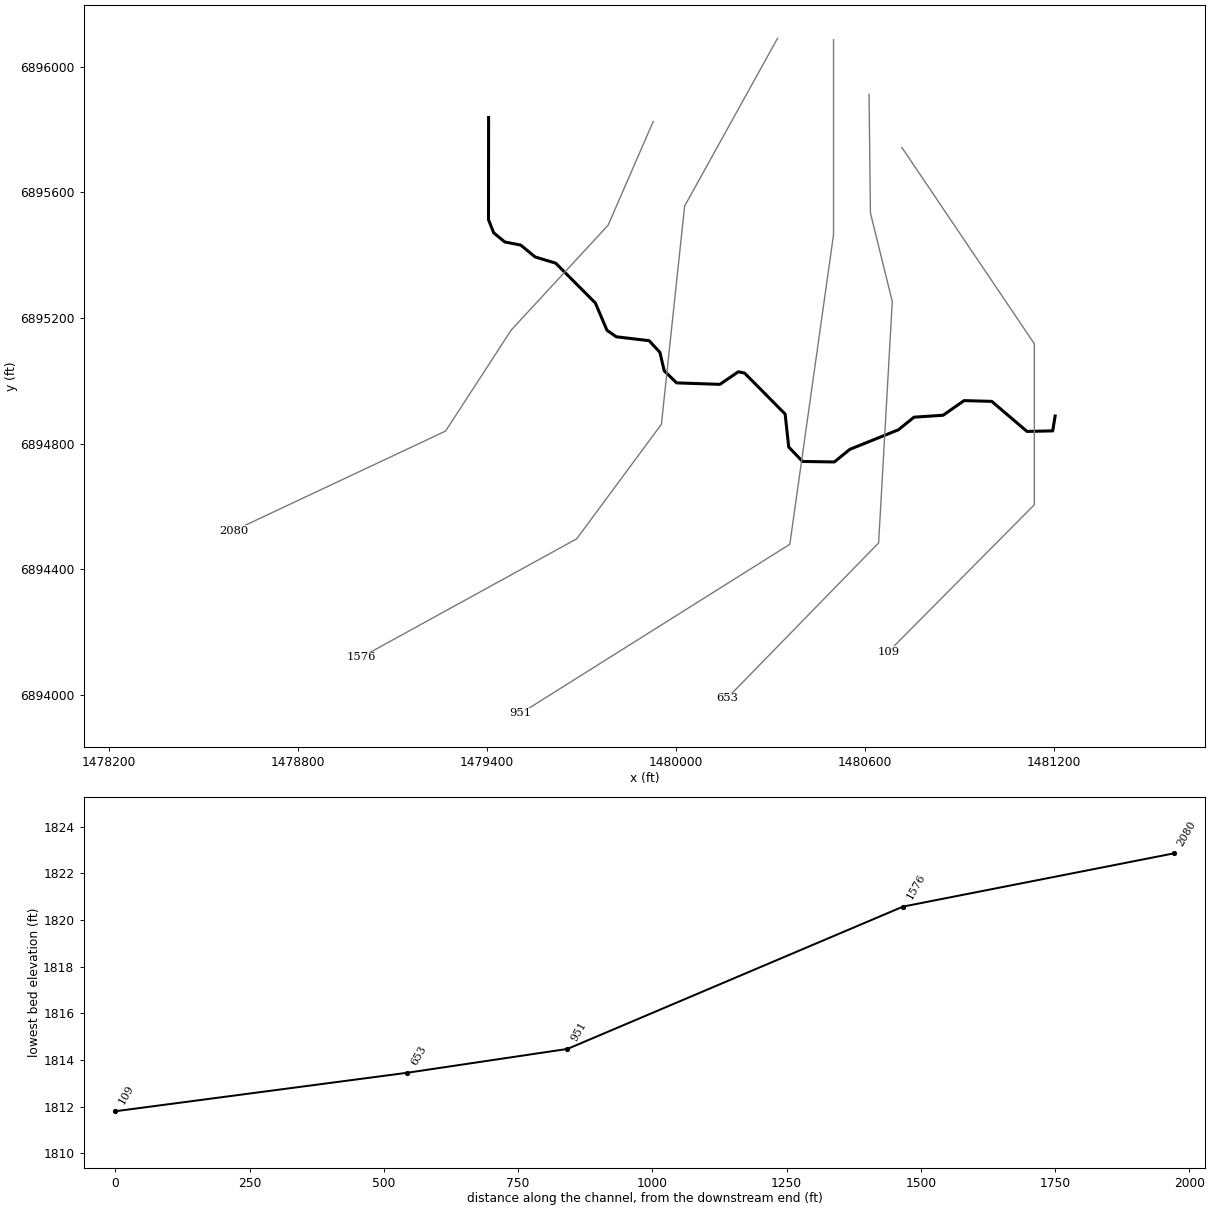
--- NC Unknown Stream 31.prj (project) ---

Proj Title=NC Unknown Stream 31 Base Level Engineering
Current Plan=p01
Default Exp/Contr=0.3,0.1
English Units
Geom File=g01
Flow File=f01
Plan File=p01
BEGIN DESCRIPTION:
NC Unknown Stream 31
END DESCRIPTION:

--- NC Unknown Stream 31.p01 (plan) ---

Plan Title=Multiple Run
Short Identifier=Multiple
Geom File=g01
Flow File=f01
Subcritical Flow
K Sum by GR= 0
Std Step Tol= 0.01
Critical Tol= 0.01
Num of Std Step Trials= 20
Max Error Tol= 0.3
Flow Tol Ratio= 0.001
Split Flow NTrial= 30
Split Flow Tol= 0.02
Split Flow Ratio= 0.02
Log Output Level= 0
Friction Slope Method= 1
Unsteady Friction Slope Method= 2
Unsteady Bridges Friction Slope Method= 1
Parabolic Critical Depth
Global Vel Dist=  1 , 1 , 1
Global Log Level= 0
CheckData=True
Encroach Param= -1, 0, 0, 0
BEGIN DESCRIPTION:
Multiple Run
END DESCRIPTION:

--- NC Unknown Stream 31.f01 (steady flow) ---

Flow Title=Multiple
Number of Profiles=7
Profile Names=10-year,25-year,50-year,1pct_min,100-year,1pct_plu,500-year
River Rch & RM= NC Unknown Strea,Reach-1,2080
     288     400     492     301     600    1197     903
River Rch & RM= NC Unknown Strea,Reach-1,1576
     349     489     606     372     743    1483    1132
Boundary for River Rch & Prof#=NC Unknown Strea,Reach-1,1
Up Type=0
Dn Type=3
Dn Slope=0.001
Boundary for River Rch & Prof#=NC Unknown Strea,Reach-1,2
Up Type=0
Dn Type=3
Dn Slope=0.001
Boundary for River Rch & Prof#=NC Unknown Strea,Reach-1,3
Up Type=0
Dn Type=3
Dn Slope=0.001
Boundary for River Rch & Prof#=NC Unknown Strea,Reach-1,4
Up Type=0
Dn Type=3
Dn Slope=0.001
Boundary for River Rch & Prof#=NC Unknown Strea,Reach-1,5
Up Type=0
Dn Type=3
Dn Slope=0.001
Boundary for River Rch & Prof#=NC Unknown Strea,Reach-1,6
Up Type=0
Dn Type=3
Dn Slope=0.001
Boundary for River Rch & Prof#=NC Unknown Strea,Reach-1,7
Up Type=0
Dn Type=3
Dn Slope=0.001

--- NC Unknown Stream 31.g01 (geometry) ---

Geom Title=Existing Conditions

River Reach=NC Unknown Strea,Reach-1
Reach XY= 30
      1479405.00      6895838.00      1479404.67      6895512.79
      1479421.27      6895470.86      1479456.39      6895441.85
      1479507.16      6895431.89      1479552.81      6895394.10
      1479618.22      6895374.38      1479744.21      6895247.66
      1479781.11      6895160.72      1479810.71      6895140.08
      1479915.10      6895127.61      1479949.25      6895090.55
      1479963.03      6895031.64      1480002.30      6894993.35
      1480139.83      6894988.65      1480198.47      6895028.71
      1480218.38      6895024.47      1480347.14      6894894.17
      1480358.51      6894789.25      1480402.29      6894743.28
      1480503.41      6894741.67      1480552.82      6894781.88
      1480707.18      6894844.12      1480756.58      6894884.17
      1480849.03      6894890.36      1480915.55      6894936.90
      1481003.50      6894934.53      1481115.53      6894838.88
      1481197.24      6894840.56      1481205.00      6894888.00

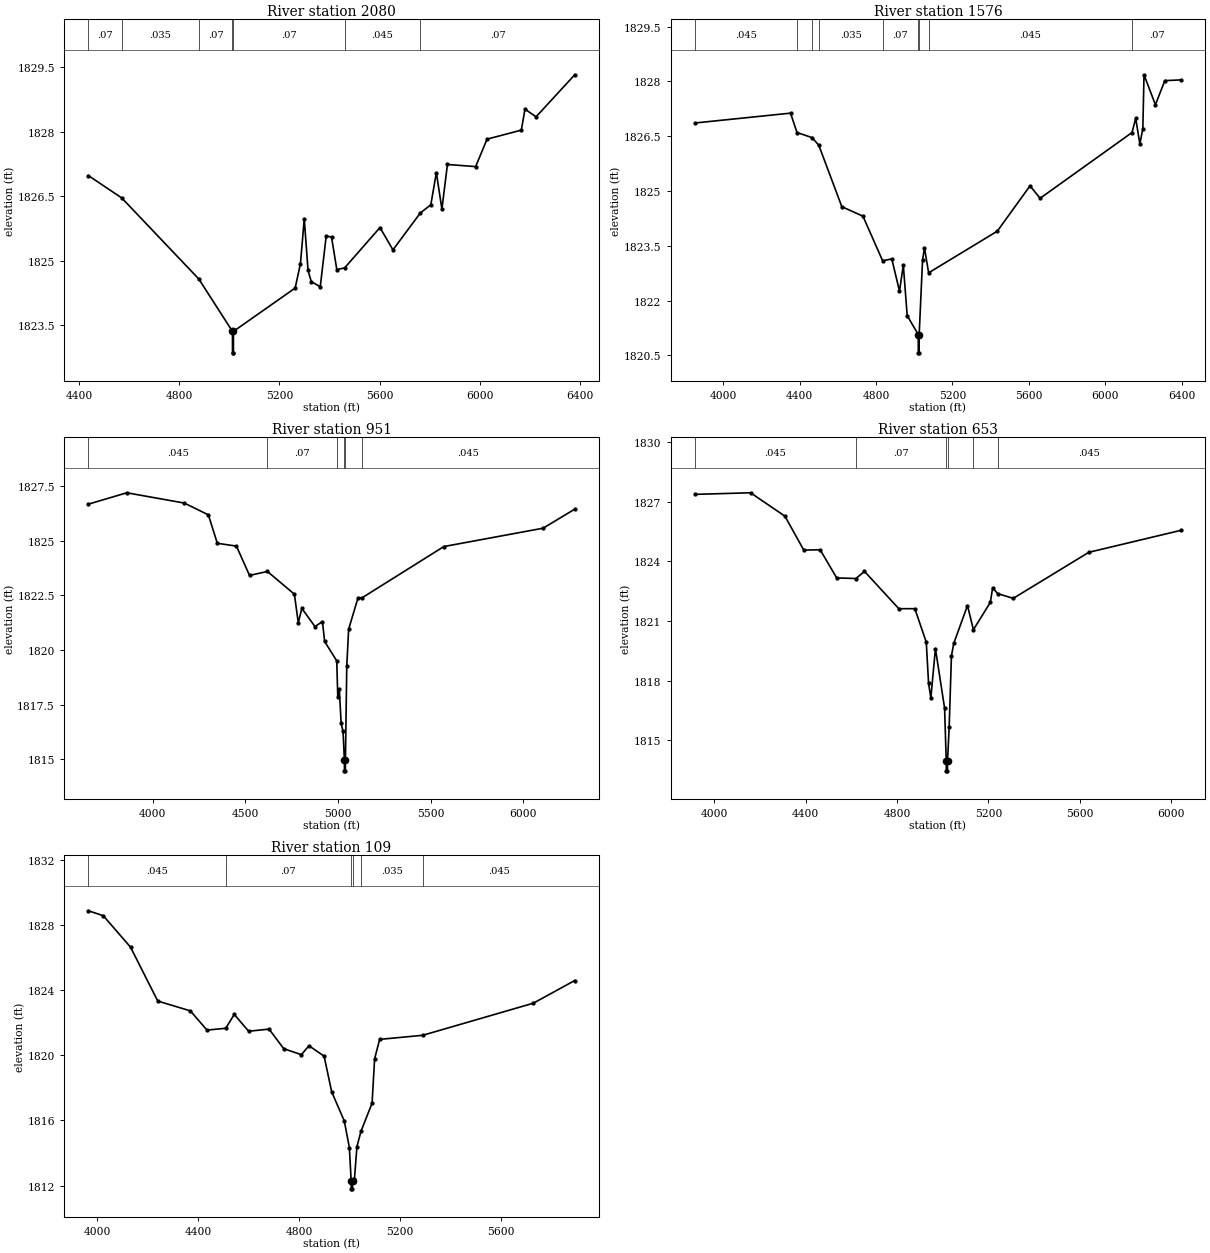
Type RM Length L Ch R = 1,2080,504,504,504
BEGIN DESCRIPTION:
Stream 31 2.0
END DESCRIPTION:
XS GIS Cut Line= 5
      1479928.01      6895825.18      1479784.77      6895495.29
      1479476.61      6895161.08      1479268.28      6894839.90
      1478595.53      6894523.06
#Sta/Elev= 30
  4437.5 1826.98  4570.4 1826.46  4878.2 1824.57  5012.3 1823.35  5012.6 1822.85
  5016.1 1822.85  5016.3 1823.35  5262.6 1824.36  5283.7 1824.93  5298.9 1825.97
  5314.0 1824.77  5326.9 1824.51  5362.7 1824.39  5386.5 1825.57  5407.7 1825.55
  5428.8 1824.79  5460.1 1824.83  5601.1 1825.77  5652.8 1825.25  5762.2 1826.11
  5804.0 1826.30  5826.1 1827.05  5848.2 1826.20  5870.3 1827.24  5982.9 1827.19
  6028.4 1827.83  6165.2 1828.04  6179.8 1828.53  6224.0 1828.35  6378.2 1829.33
#Mann=7,-1,0
  4437.5    0.07       0  4570.4   0.035       0  4878.2    0.07       0
  5012.3    0.07       0  5016.3    0.07       0  5460.1   0.045       0
  5762.2    0.07       0
Bank Sta=5012.3,5016.3
Exp/Cntr=0.3,0.1

Type RM Length L Ch R = 1,1576,625,625,625
BEGIN DESCRIPTION:
Mapping XS 9a157983
END DESCRIPTION:
XS GIS Cut Line= 5
      1480322.98      6896089.93      1480027.82      6895556.05
      1479954.04      6894861.61      1479684.94      6894497.02
      1478999.60      6894119.65
#Sta/Elev= 30
  3852.3 1826.86  4353.0 1827.13  4386.8 1826.60  4465.8 1826.46  4501.0 1826.25
  4621.3 1824.57  4731.9 1824.31  4834.7 1823.09  4882.7 1823.14  4923.0 1822.26
  4943.1 1822.97  4963.2 1821.59  5021.1 1821.07  5021.4 1820.57  5025.6 1820.57
  5026.0 1821.07  5043.6 1823.11  5053.7 1823.44  5075.4 1822.76  5434.7 1823.90
  5605.9 1825.14  5658.7 1824.80  6139.6 1826.60  6158.6 1826.99  6180.4 1826.29
  6196.0 1826.70  6202.2 1828.18  6261.8 1827.36  6311.1 1828.02  6396.2 1828.04
#Mann=9,-1,0
  3852.3   0.045       0  4386.8    0.07       0  4465.8   0.045       0
  4501.0   0.035       0  4834.7    0.07       0  5021.1    0.07       0
  5026.0    0.07       0  5075.4   0.045       0  6139.6    0.07       0
Bank Sta=5021.1,5026
Exp/Cntr=0.3,0.1

Type RM Length L Ch R = 1,951,298,298,298
BEGIN DESCRIPTION:
Mapping XS 6949bceb
END DESCRIPTION:
XS GIS Cut Line= 4
      1480500.91      6896085.53      1480500.91      6895464.90
      1480362.03      6894479.66      1479507.01      6893941.48
#Sta/Elev= 30
  3652.4 1826.67  3859.9 1827.19  4169.9 1826.72  4300.2 1826.18  4348.4 1824.88
  4451.7 1824.75  4522.4 1823.41  4619.0 1823.59  4764.7 1822.55  4785.5 1821.25
  4805.1 1821.90  4875.8 1821.07  4916.2 1821.30  4927.8 1820.39  4993.4 1819.50
  4999.0 1817.84  5007.1 1818.20  5017.2 1816.64  5027.3 1816.27  5034.6 1814.97
  5035.0 1814.47  5039.8 1814.47  5040.3 1814.97  5047.5 1819.27  5057.6 1820.95
  5108.1 1822.38  5131.0 1822.39  5571.7 1824.73  6107.9 1825.57  6278.3 1826.44
#Mann=6,-1,0
  3652.4   0.045       0  4619.0    0.07       0  4993.4   0.035       0
  5034.6   0.035       0  5040.3   0.035       0  5131.0   0.045       0
Bank Sta=5034.6,5040.3
Exp/Cntr=0.3,0.1

Type RM Length L Ch R = 1,653,544,544,544
BEGIN DESCRIPTION:
Mapping XS d8ec32eb
END DESCRIPTION:
XS GIS Cut Line= 5
      1480613.76      6895911.97      1480618.10      6895534.35
      1480687.55      6895252.23      1480644.14      6894484.00
      1480162.40      6893989.23
#Sta/Elev= 30
  3914.9 1827.38  4158.9 1827.46  4309.4 1826.28  4391.8 1824.57  4463.3 1824.59
  4535.9 1823.17  4619.8 1823.14  4657.4 1823.50  4807.7 1821.62  4877.8 1821.62
  4927.9 1819.93  4937.9 1817.86  4947.9 1817.12  4967.9 1819.61  5008.0 1816.61
  5015.2 1813.95  5015.6 1813.45  5020.4 1813.45  5020.9 1813.95  5028.0 1815.64
  5038.0 1819.24  5048.1 1819.87  5108.2 1821.78  5134.1 1820.56  5208.3 1821.94
  5218.3 1822.67  5240.2 1822.38  5308.5 1822.14  5639.1 1824.46  6043.1 1825.57
#Mann=6,-1,0
  3914.9   0.045       0  4619.8    0.07       0  5015.2    0.07       0
  5020.9    0.07       0  5134.1   0.035       0  5240.2   0.045       0
Bank Sta=5015.2,5020.9
Exp/Cntr=0.3,0.1

Type RM Length L Ch R = 1,109,0,0,0
BEGIN DESCRIPTION:
NC Unknown Stream 31 1.0
END DESCRIPTION:
XS GIS Cut Line= 4
      1480717.90      6895742.72      1481138.93      6895117.68
      1481138.93      6894605.53      1480674.54      6894136.80
#Sta/Elev= 30
  3965.9 1828.86  4024.6 1828.56  4132.6 1826.63  4240.5 1823.32  4369.5 1822.72
  4435.4 1821.54  4509.5 1821.65  4543.4 1822.50  4600.4 1821.47  4681.3 1821.60
  4739.2 1820.40  4809.2 1820.03  4839.2 1820.58  4899.2 1819.94  4929.2 1817.75
  4979.2 1815.96  4999.2 1814.33  5006.3 1812.30  5006.8 1811.80  5011.6 1811.80
  5012.1 1812.30  5019.2 1812.38  5029.2 1814.39  5045.2 1815.33  5089.2 1817.06
  5099.2 1819.78  5119.2 1820.97  5289.6 1821.22  5727.7 1823.19  5891.5 1824.58
#Mann=6,-1,0
  3965.9   0.045       0  4509.5    0.07       0  5006.3    0.07       0
  5012.1    0.07       0  5045.2   0.035       0  5289.6   0.045       0
Bank Sta=5006.3,5012.1
Exp/Cntr=0.3,0.1

Chan Stop Cuts=-1