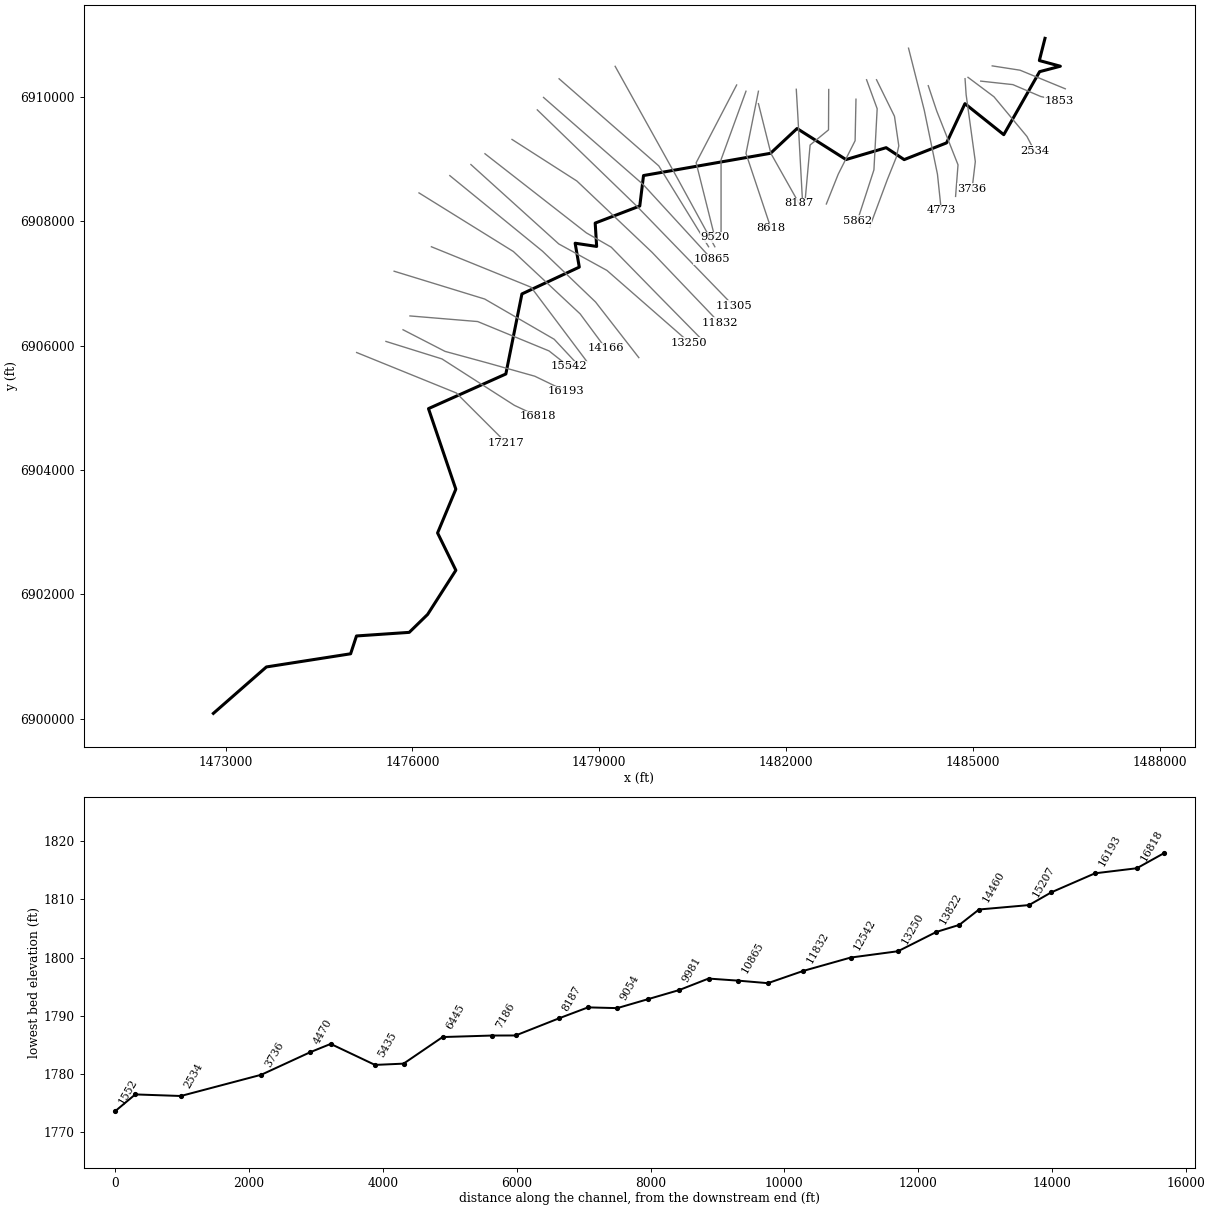
--- NC Unknown Stream 32.prj (project) ---

Proj Title=NC Unknown Stream 32 Base Level Engineering
Current Plan=p01
Default Exp/Contr=0.3,0.1
English Units
Geom File=g01
Flow File=f01
Plan File=p01
BEGIN DESCRIPTION:
NC Unknown Stream 32
END DESCRIPTION:

--- NC Unknown Stream 32.p01 (plan) ---

Plan Title=Multiple Run
Short Identifier=Multiple
Geom File=g01
Flow File=f01
Subcritical Flow
K Sum by GR= 0
Std Step Tol= 0.01
Critical Tol= 0.01
Num of Std Step Trials= 20
Max Error Tol= 0.3
Flow Tol Ratio= 0.001
Split Flow NTrial= 30
Split Flow Tol= 0.02
Split Flow Ratio= 0.02
Log Output Level= 0
Friction Slope Method= 1
Unsteady Friction Slope Method= 2
Unsteady Bridges Friction Slope Method= 1
Parabolic Critical Depth
Global Vel Dist=  1 , 1 , 1
Global Log Level= 0
CheckData=True
Encroach Param= -1, 0, 0, 0
BEGIN DESCRIPTION:
Multiple Run
END DESCRIPTION:

--- NC Unknown Stream 32.f01 (steady flow) ---

Flow Title=Multiple
Number of Profiles=7
Profile Names=10-year,25-year,50-year,1pct_min,100-year,1pct_plu,500-year
River Rch & RM= NC Unknown Strea,Reach-1,17217
     450     638     796     492     982    1959    1513
River Rch & RM= NC Unknown Strea,Reach-1,14460
     558     799    1004     625    1246    2487    1946
River Rch & RM= NC Unknown Strea,Reach-1,8187
     591     848    1066     664    1326    2645    2074
River Rch & RM= NC Unknown Strea,Reach-1,4773
     676     974    1229     767    1531    3055    2409
Boundary for River Rch & Prof#=NC Unknown Strea,Reach-1,1
Up Type=0
Dn Type=3
Dn Slope=0.001
Boundary for River Rch & Prof#=NC Unknown Strea,Reach-1,2
Up Type=0
Dn Type=3
Dn Slope=0.001
Boundary for River Rch & Prof#=NC Unknown Strea,Reach-1,3
Up Type=0
Dn Type=3
Dn Slope=0.001
Boundary for River Rch & Prof#=NC Unknown Strea,Reach-1,4
Up Type=0
Dn Type=3
Dn Slope=0.001
Boundary for River Rch & Prof#=NC Unknown Strea,Reach-1,5
Up Type=0
Dn Type=3
Dn Slope=0.001
Boundary for River Rch & Prof#=NC Unknown Strea,Reach-1,6
Up Type=0
Dn Type=3
Dn Slope=0.001
Boundary for River Rch & Prof#=NC Unknown Strea,Reach-1,7
Up Type=0
Dn Type=3
Dn Slope=0.001

--- NC Unknown Stream 32.g01 (geometry) ---

Geom Title=Existing Conditions

River Reach=NC Unknown Strea,Reach-1
Reach XY= 30
      1472805.00      6900088.00      1473656.50      6900834.39
      1475008.43      6901045.76      1475102.38      6901332.27
      1475949.15      6901390.06      1476244.24      6901678.32
      1476697.72      6902388.10      1476404.15      6902988.01
      1476697.21      6903691.42      1476258.12      6904986.38
      1477499.97      6905542.93      1477758.16      6906829.66
      1478679.10      6907260.85      1478612.48      6907644.70
      1478957.72      6907593.28      1478934.34      6907968.60
      1479650.00      6908243.00      1479710.17      6908732.59
      1481749.03      6909090.14      1482175.02      6909488.45
      1482960.68      6908989.56      1483605.00      6909180.44
      1483894.29      6908988.70      1484575.13      6909257.77
      1484870.08      6909887.82      1485493.17      6909389.61
      1486068.40      6910402.17      1486401.70      6910489.77
      1486064.17      6910581.00      1486155.00      6910938.00

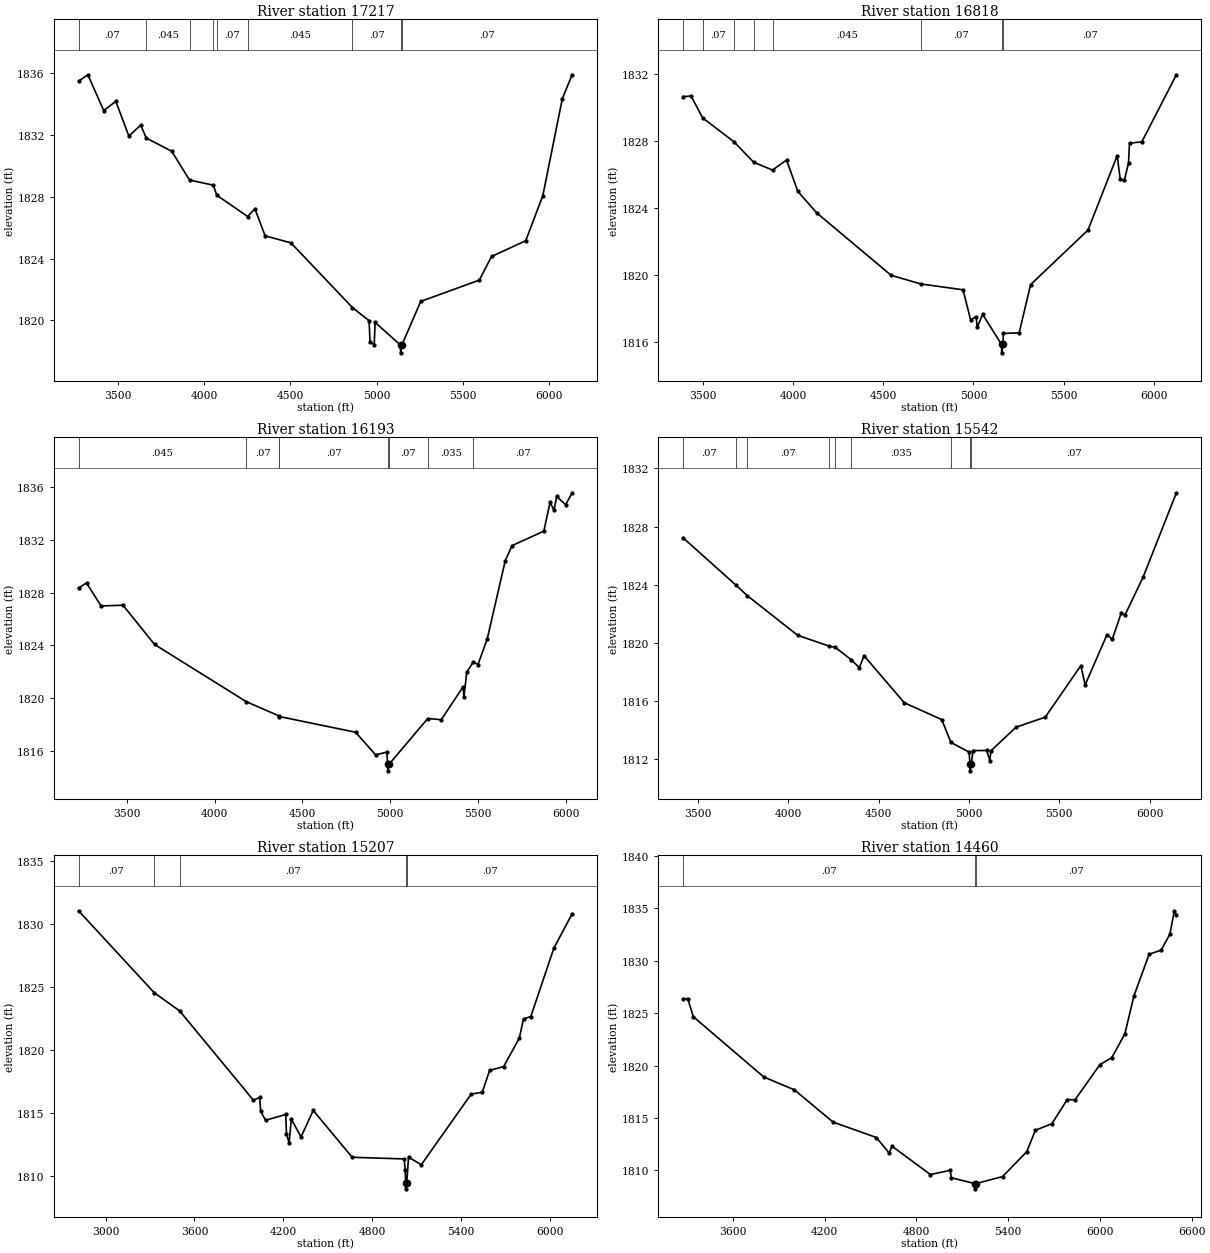
Type RM Length L Ch R = 1,17217,399,399,399
BEGIN DESCRIPTION:
NC Unknown Stream 32 20.0
END DESCRIPTION:
XS GIS Cut Line= 3
      1475104.96      6905888.02      1476705.00      6905238.00
      1477505.00      6904438.00
#Sta/Elev= 30
  3273.1 1835.48  3327.1 1835.90  3419.1 1833.58  3489.0 1834.18  3564.6 1831.93
  3633.3 1832.64  3665.5 1831.80  3812.6 1830.95  3916.2 1829.08  4053.8 1828.75
  4073.5 1828.10  4252.7 1826.72  4294.6 1827.22  4353.5 1825.47  4503.4 1825.01
  4859.6 1820.82  4955.9 1819.97  4961.3 1818.59  4985.4 1818.43  4990.8 1819.86
  5137.8 1818.39  5138.3 1817.89  5145.4 1818.39  5254.7 1821.22  5594.1 1822.60
  5664.8 1824.13  5862.8 1825.15  5961.8 1828.06  6074.9 1834.35  6131.5 1835.90
#Mann=9,-1,0
  3273.1    0.07       0  3665.5   0.045       0  3916.2    0.07       0
  4053.8   0.045       0  4073.5    0.07       0  4252.7   0.045       0
  4859.6    0.07       0  5137.8    0.07       0  5145.4    0.07       0
Bank Sta=5137.8,5145.4
Exp/Cntr=0.3,0.1

Type RM Length L Ch R = 1,16818,625,625,625
BEGIN DESCRIPTION:
Mapping XS a19d5170
END DESCRIPTION:
XS GIS Cut Line= 4
      1475575.54      6906066.40      1476474.87      6905785.14
      1477638.07      6905038.62      1478015.01      6904862.25
#Sta/Elev= 30
  3386.1 1830.66  3431.8 1830.70  3496.3 1829.39  3670.2 1827.96  3779.4 1826.74
  3884.1 1826.27  3961.8 1826.87  4024.7 1825.00  4129.4 1823.71  4542.4 1819.98
  4707.5 1819.46  4941.9 1819.11  4984.2 1817.31  5014.6 1817.51  5020.5 1816.86
  5050.9 1817.64  5156.0 1815.84  5156.5 1815.34  5163.8 1815.84  5165.9 1816.50
  5253.7 1816.54  5317.2 1819.42  5635.6 1822.68  5797.8 1827.13  5815.1 1825.71
  5837.9 1825.67  5860.8 1826.69  5866.3 1827.88  5934.8 1827.96  6126.7 1831.97
#Mann=8,-1,0
  3386.1   0.045       0  3496.3    0.07       0  3670.2   0.045       0
  3779.4    0.07       0  3884.1   0.045       0  4707.5    0.07       0
  5156.0    0.07       0  5163.8    0.07       0
Bank Sta=5156,5163.8
Exp/Cntr=0.3,0.1

Type RM Length L Ch R = 1,16193,651,651,651
BEGIN DESCRIPTION:
Mapping XS 77b53af5
END DESCRIPTION:
XS GIS Cut Line= 5
      1475849.87      6906253.89      1476523.48      6905906.67
      1477210.98      6905719.17      1477964.46      6905507.37
      1478467.94      6905264.31
#Sta/Elev= 30
  3224.0 1828.34  3269.4 1828.73  3352.4 1826.98  3477.3 1827.04  3657.1 1824.06
  4179.7 1819.72  4367.3 1818.63  4368.0 1818.59  4802.5 1817.40  4916.8 1815.68
  4980.1 1815.89  4985.5 1814.97  4986.0 1814.47  4993.4 1814.97  5213.6 1818.44
  5290.7 1818.35  5414.8 1820.84  5420.0 1820.08  5436.1 1821.96  5474.2 1822.75
  5499.9 1822.53  5553.0 1824.50  5655.4 1830.42  5694.2 1831.56  5875.1 1832.66
  5910.8 1834.86  5933.0 1834.24  5948.4 1835.29  5999.6 1834.66  6036.2 1835.57
#Mann=8,-1,0
  3224.0   0.045       0  4179.7    0.07       0  4367.3   0.045       0
  4368.0    0.07       0  4985.5    0.07       0  4993.4    0.07       0
  5213.6   0.035       0  5474.2    0.07       0
Bank Sta=4985.5,4993.4
Exp/Cntr=0.3,0.1

Type RM Length L Ch R = 1,15542,335,335,335
BEGIN DESCRIPTION:
Mapping XS 53e06ccb
END DESCRIPTION:
XS GIS Cut Line= 4
      1475960.98      6906476.12      1477047.79      6906385.84
      1478193.62      6905913.62      1478509.60      6905663.61
#Sta/Elev= 30
  3415.4 1827.24  3707.2 1824.00  3773.4 1823.24  4051.6 1820.52  4226.4 1819.78
  4260.3 1819.69  4348.0 1818.84  4392.8 1818.30  4418.7 1819.12  4641.4 1815.89
  4849.0 1814.73  4899.9 1813.16  5000.5 1812.50  5004.9 1811.71  5005.4 1811.21
  5013.1 1811.71  5022.1 1812.60  5097.8 1812.61  5115.5 1811.91  5120.9 1812.58
  5260.1 1814.21  5422.3 1814.90  5619.0 1818.44  5643.0 1817.12  5764.3 1820.58
  5793.1 1820.25  5842.8 1822.06  5863.6 1821.92  5963.8 1824.52  6148.2 1830.32
#Mann=9,-1,0
  3415.4    0.07       0  3707.2   0.045       0  3773.4    0.07       0
  4226.4   0.045       0  4260.3    0.07       0  4348.0   0.035       0
  4899.9    0.07       0  5004.9    0.07       0  5013.1    0.07       0
Bank Sta=5004.9,5013.1
Exp/Cntr=0.3,0.1

Type RM Length L Ch R = 1,15207,747,747,747
BEGIN DESCRIPTION:
Mapping XS bb5ac306
END DESCRIPTION:
XS GIS Cut Line= 4
      1475706.64      6907194.87      1477160.64      6906747.82
      1478276.09      6906101.12      1478630.97      6905720.27
#Sta/Elev= 30
  2817.5 1831.04  3328.3 1824.55  3499.7 1823.11  3998.0 1816.03  4039.8 1816.25
  4046.9 1815.16  4079.7 1814.44  4215.7 1814.90  4220.9 1813.38  4238.6 1812.65
  4253.7 1814.53  4319.1 1813.12  4401.5 1815.22  4664.4 1811.51  5014.1 1811.38
  5023.0 1810.53  5024.7 1809.51  5025.2 1809.01  5032.9 1809.51  5044.6 1811.52
  5130.7 1810.92  5467.8 1816.52  5542.3 1816.66  5592.1 1818.40  5686.3 1818.69
  5792.3 1820.95  5820.6 1822.47  5870.0 1822.66  6025.8 1828.09  6148.6 1830.79
#Mann=5,-1,0
  2817.5    0.07       0  3328.3   0.035       0  3499.7    0.07       0
  5024.7    0.07       0  5032.9    0.07       0
Bank Sta=5024.7,5032.9
Exp/Cntr=0.3,0.1

Type RM Length L Ch R = 1,14460,294,294,294
BEGIN DESCRIPTION:
NC Unknown Stream 32 16.0
END DESCRIPTION:
XS GIS Cut Line= 3
      1476305.02      6907587.99      1477905.00      6906938.00
      1478805.02      6905737.98
#Sta/Elev= 30
  3273.3 1826.36  3305.7 1826.36  3341.6 1824.65  3802.2 1818.91  4002.9 1817.68
  4255.5 1814.61  4538.4 1813.14  4622.5 1811.66  4640.1 1812.32  4892.3 1809.61
  5022.1 1810.02  5028.4 1809.31  5182.5 1808.75  5183.0 1808.25  5191.0 1808.75
  5363.8 1809.42  5522.1 1811.79  5578.4 1813.83  5686.7 1814.46  5786.7 1816.76
  5836.7 1816.72  6000.3 1820.08  6078.4 1820.76  6163.8 1823.03  6222.1 1826.61
  6322.1 1830.60  6400.3 1830.99  6457.6 1832.50  6486.7 1834.74  6500.3 1834.34
#Mann=3,-1,0
  3273.3    0.07       0  5182.5    0.07       0  5191.0    0.07       0
Bank Sta=5182.5,5191
Exp/Cntr=0.3,0.1

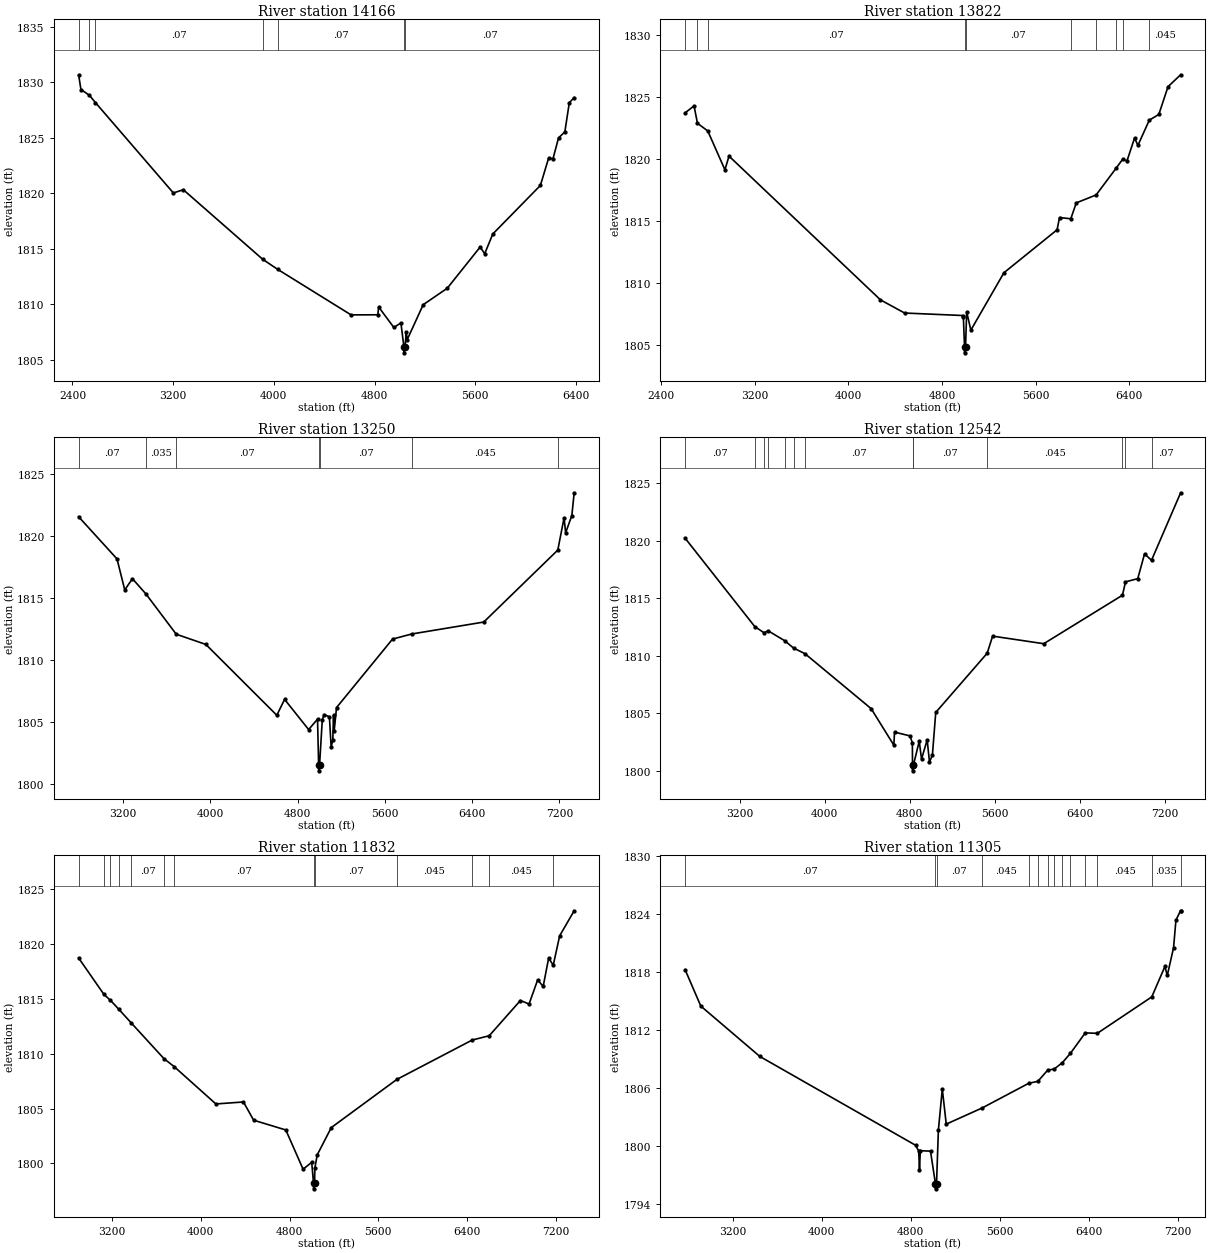
Type RM Length L Ch R = 1,14166,344,344,344
BEGIN DESCRIPTION:
Mapping XS fa8a5577
END DESCRIPTION:
XS GIS Cut Line= 4
      1476105.96      6908453.54      1477620.71      6907511.71
      1478692.75      6906509.10      1479100.40      6905958.35
#Sta/Elev= 30
  2449.2 1830.67  2467.4 1829.34  2534.2 1828.83  2582.2 1828.17  3201.7 1820.02
  3280.9 1820.31  3911.6 1814.04  4029.6 1813.14  4613.5 1809.03  4825.9 1809.04
  4832.8 1809.74  4953.0 1807.90  5009.6 1808.30  5033.7 1806.11  5034.2 1805.61
  5042.2 1806.11  5052.1 1807.47  5059.4 1806.80  5186.5 1809.95  5377.5 1811.43
  5639.3 1815.15  5674.9 1814.54  5739.4 1816.32  6117.6 1820.70  6182.3 1823.14
  6217.8 1823.11  6261.6 1824.98  6311.7 1825.52  6347.2 1828.15  6385.9 1828.62
#Mann=7,-1,0
  2449.2    0.07       0  2534.2   0.035       0  2582.2    0.07       0
  3911.6   0.035       0  4029.6    0.07       0  5033.7    0.07       0
  5042.2    0.07       0
Bank Sta=5033.7,5042.2
Exp/Cntr=0.3,0.1

Type RM Length L Ch R = 1,13822,572,572,572
BEGIN DESCRIPTION:
Mapping XS 2bf2156c
END DESCRIPTION:
XS GIS Cut Line= 4
      1476600.70      6908731.35      1478089.46      6907516.05
      1478940.15      6906700.07      1479634.61      6905805.96
#Sta/Elev= 30
  2604.7 1823.74  2681.2 1824.30  2710.3 1822.90  2798.4 1822.28  2944.7 1819.15
  2979.9 1820.25  4273.7 1808.66  4479.7 1807.60  4974.7 1807.40  4981.6 1807.25
  4991.5 1804.89  4992.0 1804.39  5000.1 1804.89  5009.9 1807.69  5045.5 1806.22
  5328.2 1810.85  5782.0 1814.31  5802.9 1815.30  5899.3 1815.20  5945.9 1816.48
  6115.5 1817.12  6288.8 1819.31  6342.2 1820.00  6379.4 1819.87  6443.6 1821.71
  6472.6 1821.12  6569.5 1823.15  6650.9 1823.61  6729.6 1825.85  6837.4 1826.81
#Mann=10,-1,0
  2604.7    0.07       0  2710.3   0.035       0  2798.4    0.07       0
  4991.5    0.07       0  5000.1    0.07       0  5899.3   0.045       0
  6115.5    0.07       0  6288.8   0.045       0  6342.2    0.07       0
  6569.5   0.045       0
Bank Sta=4991.5,5000.1
Exp/Cntr=0.3,0.1

Type RM Length L Ch R = 1,13250,708,708,708
BEGIN DESCRIPTION:
Mapping XS a4fffee8
END DESCRIPTION:
XS GIS Cut Line= 4
      1476939.27      6908909.28      1478349.87      6907633.23
      1479122.44      6907207.89      1480446.22      6906049.04
#Sta/Elev= 30
  2792.3 1821.52  3144.2 1818.13  3215.2 1815.63  3285.5 1816.54  3409.4 1815.31
  3687.3 1812.07  3958.7 1811.25  4609.5 1805.55  4680.5 1806.83  4901.2 1804.40
  4982.6 1805.24  4992.7 1801.58  4993.2 1801.08  5001.4 1801.58  5026.1 1805.16
  5042.2 1805.61  5091.5 1805.43  5107.6 1802.98  5122.7 1803.57  5129.3 1805.56
  5135.1 1804.28  5156.9 1806.17  5670.5 1811.68  5846.5 1812.09  6506.6 1813.05
  7185.6 1818.84  7243.1 1821.44  7257.4 1820.23  7314.3 1821.62  7335.7 1823.45
#Mann=7,-1,0
  2792.3    0.07       0  3409.4   0.035       0  3687.3    0.07       0
  4992.7    0.07       0  5001.4    0.07       0  5846.5   0.045       0
  7185.6    0.07       0
Bank Sta=4992.7,5001.4
Exp/Cntr=0.3,0.1

Type RM Length L Ch R = 1,12542,710,710,710
BEGIN DESCRIPTION:
Mapping XS 7aeb2f32
END DESCRIPTION:
XS GIS Cut Line= 5
      1477164.99      6909082.88      1478792.58      6907811.19
      1479191.89      6907581.15      1479916.71      6906838.96
      1480684.93      6906057.72
#Sta/Elev= 30
  2688.2 1820.23  3343.4 1812.54  3429.2 1812.01  3469.5 1812.17  3623.1 1811.32
  3708.3 1810.67  3815.7 1810.18  4437.7 1805.40  4651.1 1802.22  4657.4 1803.36
  4802.6 1803.03  4825.1 1802.43  4826.4 1800.49  4826.9 1799.99  4835.2 1800.49
  4889.7 1802.57  4911.3 1801.01  4964.2 1802.68  4986.0 1800.77  5013.3 1801.33
  5044.9 1805.07  5528.5 1810.22  5579.6 1811.71  6060.4 1811.05  6800.8 1815.27
  6828.9 1816.43  6944.4 1816.71  7008.1 1818.86  7073.8 1818.31  7347.6 1824.18
#Mann=13,-1,0
  2688.2    0.07       0  3343.4   0.035       0  3429.2    0.07       0
  3469.5   0.035       0  3623.1    0.07       0  3708.3   0.035       0
  3815.7    0.07       0  4826.4    0.07       0  4835.2    0.07       0
  5528.5   0.045       0  6800.8    0.07       0  6828.9   0.045       0
  7073.8    0.07       0
Bank Sta=4826.4,4835.2
Exp/Cntr=0.3,0.1

Type RM Length L Ch R = 1,11832,527,527,527
BEGIN DESCRIPTION:
Mapping XS 88cb1049
END DESCRIPTION:
XS GIS Cut Line= 4
      1477599.01      6909312.92      1478640.67      6908644.52
      1479847.27      6907498.69      1480928.01      6906365.86
#Sta/Elev= 30
  2898.9 1818.71  3127.4 1815.39  3185.4 1814.86  3259.3 1814.06  3373.9 1812.79
  3668.7 1809.54  3758.9 1808.83  4136.2 1805.42  4384.8 1805.60  4476.6 1803.94
  4766.6 1803.05  4922.3 1799.48  5000.0 1800.10  5016.8 1798.19  5017.3 1797.69
  5026.1 1798.19  5028.3 1799.58  5049.7 1800.78  5176.8 1803.27  5767.0 1807.65
  6446.9 1811.24  6600.3 1811.63  6881.5 1814.84  6959.5 1814.52  7037.2 1816.72
  7086.8 1816.12  7136.2 1818.71  7177.5 1818.05  7235.3 1820.73  7366.2 1823.01
#Mann=13,-1,0
  2898.9    0.07       0  3127.4   0.035       0  3185.4    0.07       0
  3259.3   0.035       0  3373.9    0.07       0  3668.7   0.035       0
  3758.9    0.07       0  5016.8    0.07       0  5026.1    0.07       0
  5767.0   0.045       0  6446.9    0.07       0  6600.3   0.045       0
  7177.5    0.07       0
Bank Sta=5016.8,5026.1
Exp/Cntr=0.3,0.1

Type RM Length L Ch R = 1,11305,440,440,440
BEGIN DESCRIPTION:
NC Unknown Stream 32 12.0
END DESCRIPTION:
XS GIS Cut Line= 3
      1478005.01      6909787.99      1479605.00      6908238.00
      1481154.99      6906638.01
#Sta/Elev= 30
  2771.4 1818.22  2912.7 1814.46  3443.2 1809.26  4843.5 1800.09  4871.8 1799.50
  4878.8 1797.54  4886.0 1799.53  4977.8 1799.48  5022.5 1796.09  5023.0 1795.59
  5031.9 1796.09  5048.6 1801.64  5083.8 1805.90  5119.3 1802.27  5443.9 1803.95
  5861.3 1806.49  5943.2 1806.69  6030.9 1807.84  6089.8 1807.96  6163.7 1808.62
  6236.4 1809.59  6369.1 1811.69  6478.1 1811.65  6967.3 1815.41  7085.4 1818.55
  7106.5 1817.62  7163.1 1820.49  7184.4 1823.34  7225.9 1824.30  7226.7 1824.30
#Mann=14,-1,0
  2771.4    0.07       0  5022.5    0.07       0  5031.9    0.07       0
  5443.9   0.045       0  5861.3    0.07       0  5943.2   0.045       0
  6030.9    0.07       0  6089.8   0.045       0  6163.7    0.07       0
  6236.4   0.045       0  6369.1    0.07       0  6478.1   0.045       0
  6967.3   0.035       0  7225.9    0.07       0
Bank Sta=5022.5,5031.9
Exp/Cntr=0.3,0.1

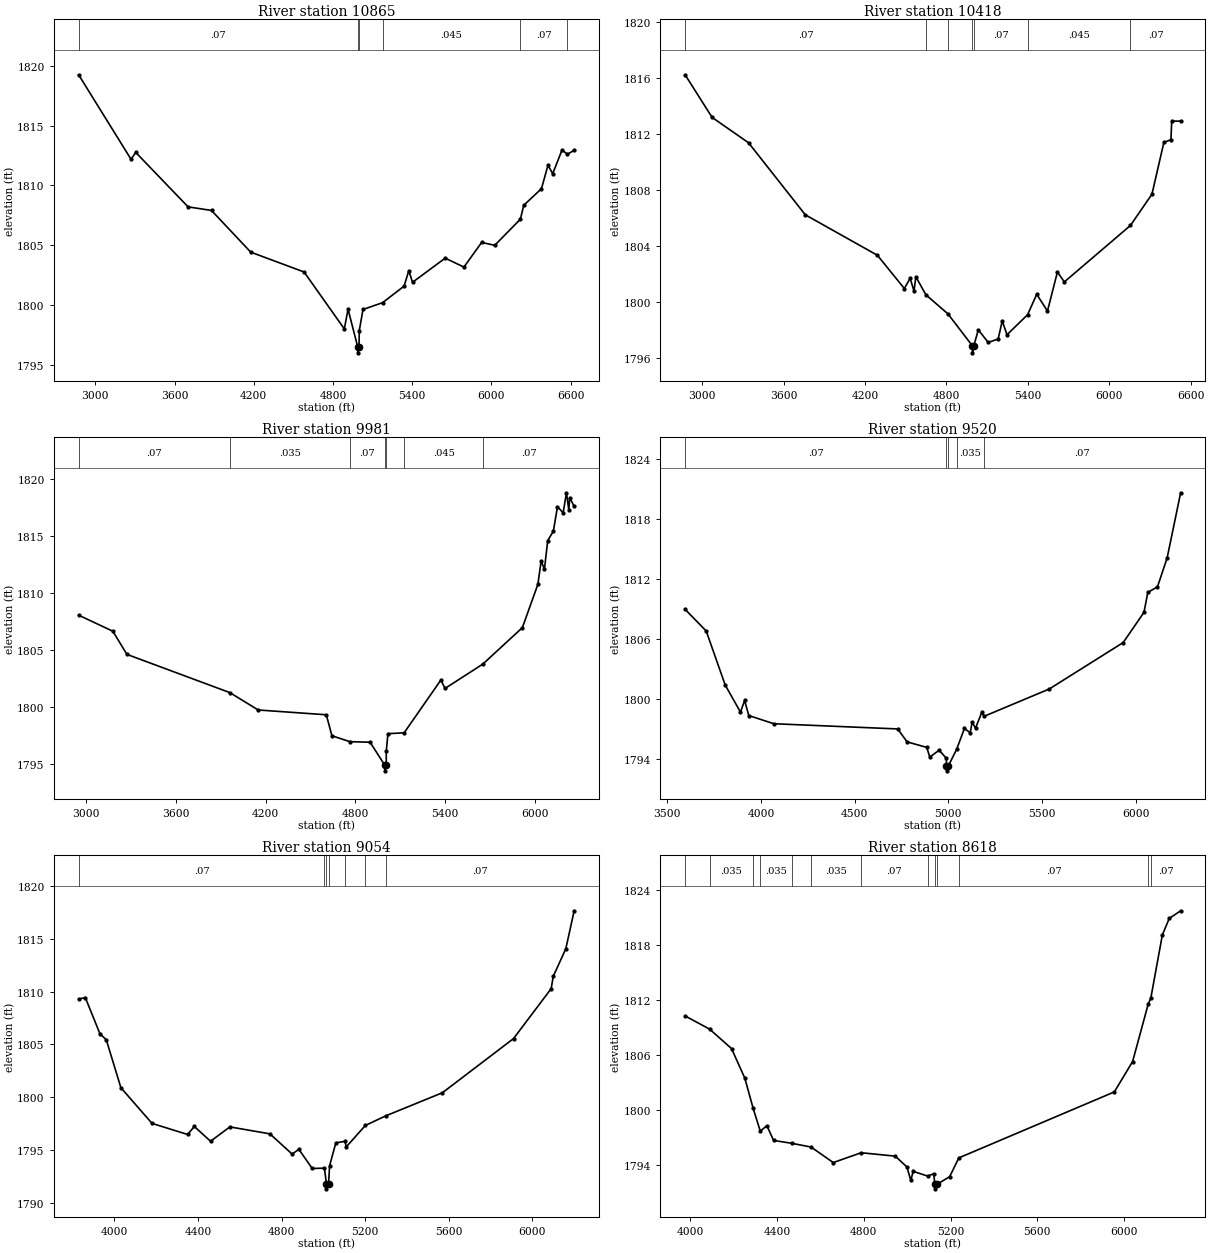
Type RM Length L Ch R = 1,10865,447,447,447
BEGIN DESCRIPTION:
NC Unknown Stream 32 11.0
END DESCRIPTION:
XS GIS Cut Line= 3
      1478104.97      6909988.03      1479705.00      6908588.00
      1480805.03      6907387.96
#Sta/Elev= 30
  2873.3 1819.24  3270.5 1812.18  3305.7 1812.76  3702.4 1808.21  3879.9 1807.91
  4177.0 1804.43  4581.3 1802.77  4886.0 1798.02  4914.4 1799.66  4987.3 1796.52
  4987.8 1796.02  4997.3 1796.52  4999.4 1797.87  5027.4 1799.64  5175.8 1800.21
  5338.8 1801.59  5374.6 1802.88  5402.9 1801.91  5650.5 1803.93  5792.0 1803.18
  5926.5 1805.24  6025.7 1805.00  6219.7 1807.18  6245.3 1808.34  6379.7 1809.73
  6429.0 1811.69  6464.5 1810.98  6535.1 1812.95  6576.5 1812.61  6627.3 1812.93
#Mann=6,-1,0
  2873.3    0.07       0  4987.3    0.07       0  4997.3    0.07       0
  5175.8   0.045       0  6219.7    0.07       0  6576.5   0.045       0
Bank Sta=4987.3,4997.3
Exp/Cntr=0.3,0.1

Type RM Length L Ch R = 1,10418,437,437,437
BEGIN DESCRIPTION:
NC Unknown Stream 32 10.0
END DESCRIPTION:
XS GIS Cut Line= 3
      1478354.97      6910288.02      1479955.00      6908888.00
      1480755.00      6907588.00
#Sta/Elev= 30
  2874.2 1816.22  3073.1 1813.18  3341.7 1811.37  3760.2 1806.23  4291.7 1803.34
  4490.1 1800.97  4532.8 1801.70  4561.3 1800.79  4575.1 1801.81  4649.0 1800.52
  4810.6 1799.17  4991.9 1796.88  4992.4 1796.38  5002.0 1796.88  5035.5 1798.02
  5108.5 1797.12  5181.9 1797.37  5211.6 1798.66  5246.8 1797.67  5398.6 1799.10
  5465.9 1800.56  5545.2 1799.36  5618.5 1802.15  5669.5 1801.44  6156.8 1805.47
  6315.3 1807.70  6403.0 1811.39  6455.1 1811.59  6461.0 1812.92  6526.7 1812.91
#Mann=7,-1,0
  2874.2    0.07       0  4649.0   0.035       0  4810.6    0.07       0
  4991.9    0.07       0  5002.0    0.07       0  5398.6   0.045       0
  6156.8    0.07       0
Bank Sta=4991.9,5002
Exp/Cntr=0.3,0.1

Type RM Length L Ch R = 1,9981,461,461,461
BEGIN DESCRIPTION:
NC Unknown Stream 32 9.0
END DESCRIPTION:
XS GIS Cut Line= 3
      1479255.01      6910487.99      1480255.00      6908688.00
      1480855.00      6907588.01
#Sta/Elev= 30
  2950.1 1808.07  3178.9 1806.66  3272.7 1804.63  3961.6 1801.27  4150.1 1799.75
  4605.4 1799.33  4643.1 1797.49  4762.8 1796.97  4898.2 1796.92  4996.1 1794.91
  4996.6 1794.41  5006.3 1794.91  5006.4 1796.12  5017.3 1797.67  5125.9 1797.75
  5371.3 1802.38  5398.9 1801.64  5652.1 1803.78  5916.2 1806.98  6019.7 1810.78
  6041.5 1812.84  6063.3 1812.08  6085.2 1814.61  6123.1 1815.44  6150.7 1817.59
  6188.6 1817.05  6210.5 1818.81  6226.6 1817.30  6232.3 1818.39  6262.2 1817.61
#Mann=7,-1,0
  2950.1    0.07       0  3961.6   0.035       0  4762.8    0.07       0
  4996.1    0.07       0  5006.3    0.07       0  5125.9   0.045       0
  5652.1    0.07       0
Bank Sta=4996.1,5006.3
Exp/Cntr=0.3,0.1

Type RM Length L Ch R = 1,9520,466,466,466
BEGIN DESCRIPTION:
NC Unknown Stream 32 8.0
END DESCRIPTION:
XS GIS Cut Line= 3
      1481205.00      6910187.99      1480555.00      6908938.00
      1480854.99      6907738.02
#Sta/Elev= 30
  3595.1 1808.97  3707.8 1806.81  3809.2 1801.42  3890.7 1798.72  3912.9 1799.88
  3935.0 1798.38  4068.5 1797.56  4730.4 1797.04  4780.3 1795.75  4885.2 1795.20
  4901.7 1794.23  4951.5 1794.92  4990.1 1794.11  4990.5 1793.36  4991.0 1792.86
  5001.0 1793.36  5045.3 1795.02  5086.5 1797.09  5117.4 1796.65  5127.7 1797.73
  5145.7 1797.11  5179.2 1798.70  5191.5 1798.30  5540.0 1801.03  5934.3 1805.66
  6045.1 1808.67  6065.7 1810.66  6117.2 1811.22  6168.8 1814.10  6240.9 1820.60
#Mann=5,-1,0
  3595.1    0.07       0  4990.5    0.07       0  5001.0    0.07       0
  5045.3   0.035       0  5191.5    0.07       0
Bank Sta=4990.5,5001
Exp/Cntr=0.3,0.1

Type RM Length L Ch R = 1,9054,436,436,436
BEGIN DESCRIPTION:
NC Unknown Stream 32 7.0
END DESCRIPTION:
XS GIS Cut Line= 3
      1481355.01      6910088.01      1480955.00      6908988.00
      1480955.00      6907787.99
#Sta/Elev= 30
  3829.5 1809.28  3861.4 1809.43  3931.3 1806.00  3961.9 1805.42  4031.7 1800.88
  4180.7 1797.50  4350.9 1796.45  4382.8 1797.21  4460.6 1795.81  4553.1 1797.17
  4744.6 1796.51  4851.0 1794.59  4882.9 1795.05  4946.8 1793.23  5005.4 1793.26
  5014.7 1791.80  5015.2 1791.30  5025.2 1791.80  5030.0 1793.49  5060.0 1795.66
  5103.3 1795.80  5110.0 1795.28  5201.2 1797.31  5299.1 1798.22  5570.0 1800.41
  5910.0 1805.54  6090.0 1810.27  6100.0 1811.44  6160.0 1814.05  6200.0 1817.65
#Mann=7,-1,0
  3829.5    0.07       0  5005.4   0.035       0  5014.7    0.07       0
  5025.2   0.035       0  5103.3    0.07       0  5201.2    0.16       0
  5299.1    0.07       0
Bank Sta=5014.7,5025.2
Exp/Cntr=0.3,0.1

Type RM Length L Ch R = 1,8618,431,431,431
BEGIN DESCRIPTION:
NC Unknown Stream 32 6.0
END DESCRIPTION:
XS GIS Cut Line= 3
      1481554.99      6910087.96      1481355.00      6909088.00
      1481755.01      6907887.98
#Sta/Elev= 30
  3976.1 1810.25  4088.9 1808.82  4190.2 1806.70  4251.4 1803.48  4289.7 1800.21
  4322.7 1797.71  4353.4 1798.31  4384.0 1796.70  4466.9 1796.39  4557.0 1795.98
  4659.3 1794.29  4787.8 1795.36  4944.9 1794.99  4998.5 1793.82  5016.9 1792.34
  5027.5 1793.33  5094.5 1792.82  5122.4 1793.07  5127.6 1791.93  5128.1 1791.43
  5138.1 1791.93  5196.1 1792.76  5238.2 1794.80  5955.1 1801.98  6039.4 1805.29
  6111.4 1811.55  6123.3 1812.19  6176.5 1819.07  6208.1 1820.86  6260.8 1821.70
#Mann=13,-1,0
  3976.1    0.07       0  4088.9   0.035       0  4289.7    0.07       0
  4322.7   0.035       0  4466.9    0.07       0  4557.0   0.035       0
  4787.8    0.07       0  5094.5   0.035       0  5127.6    0.07       0
  5138.1   0.035       0  5238.2    0.07       0  6111.4   0.035       0
  6123.3    0.07       0
Bank Sta=5127.6,5138.1
Exp/Cntr=0.3,0.1

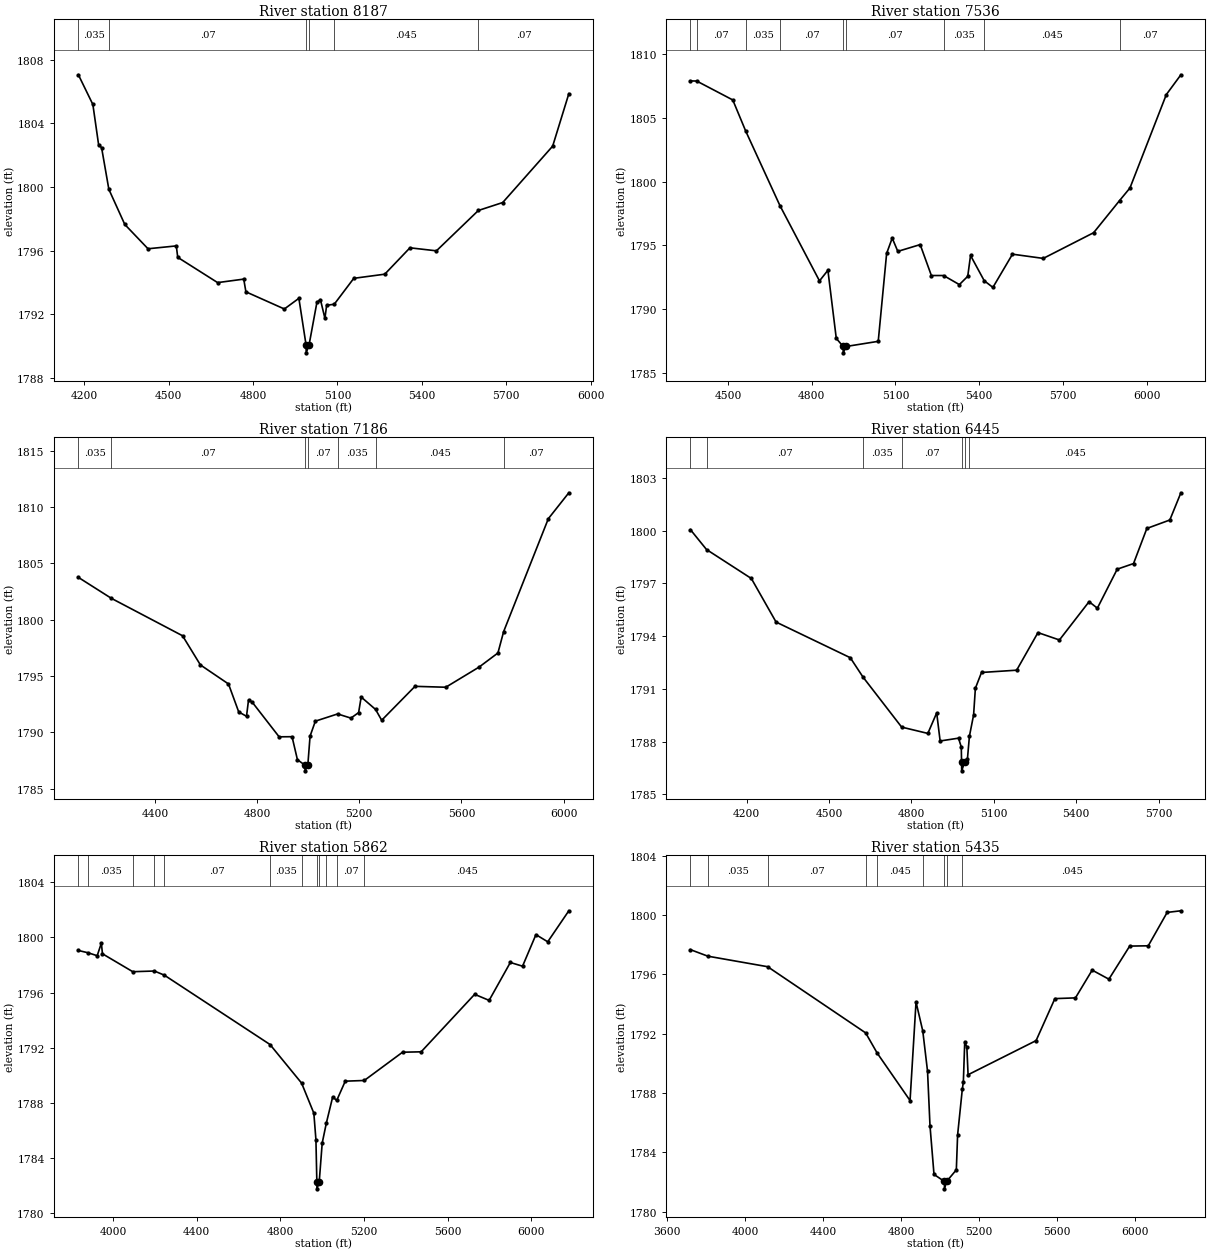
Type RM Length L Ch R = 1,8187,651,651,651
BEGIN DESCRIPTION:
NC Unknown Stream 32 5.0
END DESCRIPTION:
XS GIS Cut Line= 3
      1481555.01      6909887.97      1481755.00      6909088.00
      1482205.01      6908287.98
#Sta/Elev= 30
  4179.5 1807.06  4231.0 1805.19  4251.6 1802.63  4261.9 1802.48  4287.8 1799.85
  4344.4 1797.64  4426.9 1796.11  4527.4 1796.29  4532.5 1795.57  4674.2 1793.98
  4767.0 1794.20  4774.7 1793.40  4911.3 1792.32  4962.9 1792.99  4988.4 1790.06
  4988.9 1789.56  4999.1 1790.06  5027.0 1792.74  5039.5 1792.91  5055.4 1791.73
  5061.5 1792.55  5088.6 1792.62  5158.0 1794.25  5268.0 1794.51  5357.5 1796.17
  5451.6 1795.98  5600.6 1798.52  5687.1 1799.02  5864.6 1802.57  5922.0 1805.87
#Mann=6,-1,0
  4179.5   0.035       0  4287.8    0.07       0  4988.4   0.035       0
  4999.1    0.07       0  5088.6   0.045       0  5600.6    0.07       0
Bank Sta=4988.4,4999.1
Exp/Cntr=0.3,0.1

Type RM Length L Ch R = 1,7536,350,350,350
BEGIN DESCRIPTION:
NC Unknown Stream 32 4.0
END DESCRIPTION:
XS GIS Cut Line= 3
      1482162.37      6910119.32      1482186.68      6909709.62
      1482259.59      6908365.92
#Sta/Elev= 30
  4365.9 1807.88  4388.3 1807.87  4517.5 1806.39  4563.7 1803.96  4686.4 1798.12
  4828.0 1792.23  4858.1 1793.06  4888.1 1787.73  4912.6 1787.10  4913.1 1786.60
  4923.7 1787.10  5038.3 1787.50  5068.4 1794.38  5088.4 1795.58  5108.4 1794.54
  5188.5 1795.07  5228.6 1792.65  5272.3 1792.65  5328.8 1791.94  5358.8 1792.59
  5368.8 1794.22  5417.9 1792.24  5448.9 1791.72  5519.0 1794.32  5629.2 1793.99
  5809.5 1796.00  5902.2 1798.51  5939.6 1799.50  6069.8 1806.81  6122.0 1808.36
#Mann=9,-1,0
  4365.9   0.035       0  4388.3    0.07       0  4563.7   0.035       0
  4686.4    0.07       0  4912.6    0.07       0  4923.7    0.07       0
  5272.3   0.035       0  5417.9   0.045       0  5902.2    0.07       0
Bank Sta=4912.6,4923.7
Exp/Cntr=0.3,0.1

Type RM Length L Ch R = 1,7186,741,741,741
BEGIN DESCRIPTION:
NC Unknown Stream 32 3.0
END DESCRIPTION:
XS GIS Cut Line= 4
      1482683.21      6910115.86      1482679.73      6909466.57
      1482384.59      6909223.51      1482305.00      6908338.02
#Sta/Elev= 30
  4100.1 1803.76  4229.4 1801.90  4508.0 1798.58  4578.0 1795.99  4688.0 1794.30
  4728.0 1791.82  4758.5 1791.43  4766.4 1792.87  4780.7 1792.69  4886.2 1789.61
  4936.9 1789.62  4957.9 1787.58  4987.5 1787.09  4988.0 1786.59  4998.6 1787.09
  5007.4 1789.67  5028.2 1791.00  5115.3 1791.64  5167.4 1791.27  5197.5 1791.76
  5207.6 1793.14  5263.9 1792.04  5287.9 1791.08  5418.4 1794.09  5538.9 1794.01
  5669.4 1795.80  5743.1 1797.05  5765.5 1798.95  5940.5 1808.97  6020.8 1811.27
#Mann=7,-1,0
  4100.1   0.035       0  4229.4    0.07       0  4987.5    0.07       0
  4998.6    0.07       0  5115.3   0.035       0  5263.9   0.045       0
  5765.5    0.07       0
Bank Sta=4987.5,4998.6
Exp/Cntr=0.3,0.1

Type RM Length L Ch R = 1,6445,583,583,583
BEGIN DESCRIPTION:
Mapping XS 49069d0f
END DESCRIPTION:
XS GIS Cut Line= 4
      1483120.71      6909959.64      1483106.82      6909292.96
      1482835.98      6908754.76      1482645.03      6908275.64
#Sta/Elev= 30
  3995.8 1800.06  4054.3 1798.93  4217.5 1797.28  4307.5 1794.80  4577.6 1792.77
  4623.8 1791.67  4764.5 1788.82  4859.9 1788.46  4892.1 1789.63  4904.6 1788.03
  4971.5 1788.19  4981.6 1787.69  4982.6 1786.83  4983.1 1786.33  4993.8 1786.83
  5004.0 1787.01  5011.2 1788.30  5026.4 1789.51  5032.9 1791.03  5055.2 1791.93
  5183.1 1792.06  5260.7 1794.20  5338.8 1793.78  5446.7 1795.96  5476.9 1795.59
  5549.1 1797.81  5608.5 1798.13  5657.0 1800.13  5740.6 1800.61  5780.9 1802.16
#Mann=7,-1,0
  3995.8   0.035       0  4054.3    0.07       0  4623.8   0.035       0
  4764.5    0.07       0  4982.6    0.07       0  4993.8    0.07       0
  5011.2   0.045       0
Bank Sta=4982.6,4993.8
Exp/Cntr=0.3,0.1

Type RM Length L Ch R = 1,5862,427,427,427
BEGIN DESCRIPTION:
Mapping XS aaba1b68
END DESCRIPTION:
XS GIS Cut Line= 4
      1483290.83      6910272.16      1483460.98      6909806.85
      1483408.90      6908824.21      1483141.83      6908002.18
#Sta/Elev= 30
  3835.0 1799.05  3882.2 1798.88  3924.9 1798.67  3944.8 1799.58  3950.1 1798.81
  4095.0 1797.51  4198.2 1797.56  4245.8 1797.26  4750.7 1792.23  4901.7 1789.43
  4960.2 1787.25  4970.2 1785.33  4974.6 1782.26  4975.1 1781.76  4985.9 1782.26
  5000.2 1785.08  5020.0 1786.53  5050.3 1788.43  5069.5 1788.17  5110.4 1789.57
  5201.2 1789.62  5384.1 1791.67  5473.1 1791.70  5728.7 1795.87  5797.9 1795.43
  5899.3 1798.18  5957.6 1797.91  6021.6 1800.20  6078.0 1799.68  6178.8 1801.93
#Mann=12,-1,0
  3835.0    0.07       0  3882.2   0.035       0  4095.0    0.07       0
  4198.2   0.035       0  4245.8    0.07       0  4750.7   0.035       0
  4901.7    0.07       0  4974.6    0.07       0  4985.9    0.07       0
  5020.0   0.035       0  5069.5    0.07       0  5201.2   0.045       0
Bank Sta=4974.6,4985.9
Exp/Cntr=0.3,0.1

Type RM Length L Ch R = 1,5435,662,662,662
BEGIN DESCRIPTION:
Mapping XS 9264288b
END DESCRIPTION:
XS GIS Cut Line= 6
      1483450.55      6910272.16      1483738.76      6909685.32
      1483808.21      6909209.62      1483766.54      6909022.12
      1483624.18      6908667.96      1483343.28      6907911.97
#Sta/Elev= 30
  3718.8 1797.66  3808.0 1797.22  4114.8 1796.51  4617.2 1792.05  4676.3 1790.69
  4844.9 1787.49  4875.5 1794.13  4910.1 1792.18  4934.5 1789.47  4947.2 1785.78
  4967.7 1782.51  5021.0 1782.04  5021.5 1781.54  5032.4 1782.04  5082.2 1782.82
  5088.7 1785.17  5112.8 1788.25  5118.2 1788.75  5125.3 1791.46  5136.1 1791.09
  5142.4 1789.23  5491.1 1791.53  5587.5 1794.36  5693.0 1794.41  5778.7 1796.28
  5864.4 1795.67  5971.1 1797.90  6066.3 1797.92  6163.2 1800.17  6233.6 1800.28
#Mann=9,-1,0
  3718.8    0.07       0  3808.0   0.035       0  4114.8    0.07       0
  4617.2   0.035       0  4676.3   0.045       0  4910.1    0.07       0
  5021.0    0.07       0  5032.4    0.07       0  5112.8   0.045       0
Bank Sta=5021,5032.4
Exp/Cntr=0.3,0.1

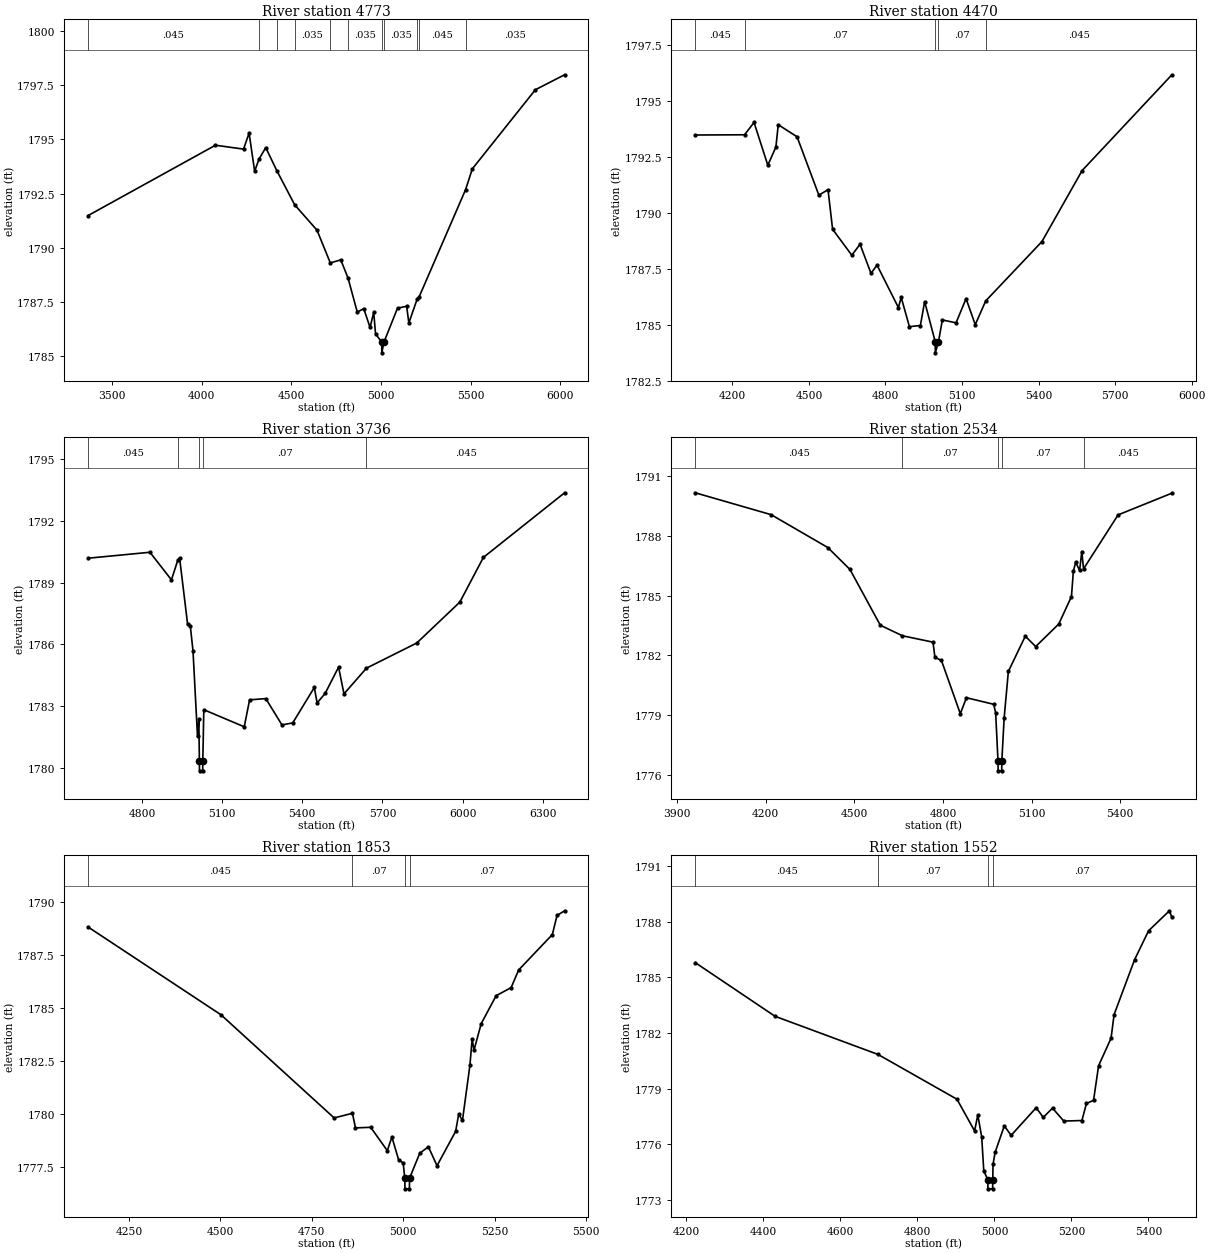
Type RM Length L Ch R = 1,4773,303,303,303
BEGIN DESCRIPTION:
Mapping XS ed2354a6
END DESCRIPTION:
XS GIS Cut Line= 4
      1483964.45      6910779.96      1484216.19      6909786.01
      1484428.87      6908753.03      1484489.63      6908175.80
#Sta/Elev= 30
  3364.5 1791.48  4076.3 1794.73  4233.0 1794.55  4264.0 1795.29  4294.9 1793.53
  4319.0 1794.08  4356.8 1794.62  4419.1 1793.55  4518.4 1791.98  4643.0 1790.81
  4717.2 1789.30  4775.8 1789.44  4816.6 1788.59  4867.7 1787.03  4904.0 1787.19
  4939.1 1786.32  4959.5 1787.02  4969.8 1786.02  5004.1 1785.65  5004.6 1785.15
  5017.0 1785.65  5092.3 1787.21  5143.3 1787.30  5155.6 1786.53  5202.5 1787.64
  5213.4 1787.74  5472.3 1792.68  5509.9 1793.64  5861.8 1797.29  6024.9 1797.98
#Mann=11,-1,0
  3364.5   0.045       0  4319.0   0.035       0  4419.1    0.07       0
  4518.4   0.035       0  4717.2    0.07       0  4816.6   0.035       0
  5004.1   0.035       0  5017.0   0.035       0  5202.5    0.07       0
  5213.4   0.045       0  5472.3   0.035       0
Bank Sta=5004.1,5017
Exp/Cntr=0.3,0.1

Type RM Length L Ch R = 1,4470,734,734,734
BEGIN DESCRIPTION:
Mapping XS fe32a299
END DESCRIPTION:
XS GIS Cut Line= 4
      1484281.29      6910176.66      1484415.84      6909772.99
      1484758.73      6908904.94      1484719.67      6908397.16
#Sta/Elev= 30
  4054.4 1793.47  4247.7 1793.48  4284.9 1794.03  4338.9 1792.12  4370.5 1792.93
  4379.8 1793.93  4453.5 1793.39  4539.0 1790.78  4574.8 1791.03  4592.8 1789.26
  4668.0 1788.10  4700.3 1788.59  4743.3 1787.29  4766.8 1787.66  4850.8 1785.76
  4861.6 1786.22  4893.8 1784.91  4936.8 1784.96  4953.5 1786.03  4994.9 1784.24
  4995.4 1783.74  5007.8 1784.24  5022.9 1785.21  5076.6 1785.08  5115.8 1786.16
  5151.9 1785.00  5192.9 1786.06  5413.2 1788.71  5570.6 1791.88  5922.5 1796.16
#Mann=5,-1,0
  4054.4   0.045       0  4247.7    0.07       0  4994.9    0.07       0
  5007.8    0.07       0  5192.9   0.045       0
Bank Sta=4994.9,5007.8
Exp/Cntr=0.3,0.1

Type RM Length L Ch R = 1,3736,1202,1202,1202
BEGIN DESCRIPTION:
Mapping XS e397ddbe
END DESCRIPTION:
XS GIS Cut Line= 4
      1484871.57      6910289.53      1484888.93      6910033.41
      1485036.50      6908957.02      1484984.42      6908518.67
#Sta/Elev= 30
  4597.4 1790.18  4829.5 1790.47  4910.0 1789.13  4933.7 1790.08  4940.5 1790.20
  4970.6 1786.97  4980.7 1786.89  4990.8 1785.67  5007.6 1781.53  5012.6 1782.35
  5014.6 1780.35  5015.1 1779.85  5027.0 1779.85  5027.5 1780.35  5031.2 1782.82
  5182.6 1781.99  5202.7 1783.30  5263.3 1783.36  5323.9 1782.08  5364.2 1782.18
  5445.0 1783.90  5455.5 1783.15  5485.4 1783.61  5535.8 1784.89  5556.0 1783.59
  5640.3 1784.84  5828.5 1786.06  5989.9 1788.05  6078.0 1790.22  6382.0 1793.36
#Mann=5,-1,0
  4597.4   0.045       0  4933.7    0.07       0  5014.6    0.07       0
  5027.5    0.07       0  5640.3   0.045       0
Bank Sta=5014.6,5027.5
Exp/Cntr=0.3,0.1

Type RM Length L Ch R = 1,2534,681,681,681
BEGIN DESCRIPTION:
Mapping XS 24d5e2b7
END DESCRIPTION:
XS GIS Cut Line= 4
      1484919.28      6910311.22      1485335.98      6909998.69
      1485865.50      6909360.66      1485987.02      6909126.31
#Sta/Elev= 30
  3961.3 1790.16  4218.5 1789.06  4410.3 1787.41  4485.3 1786.31  4588.0 1783.51
  4663.1 1782.98  4766.4 1782.66  4772.9 1781.90  4795.0 1781.74  4858.9 1779.07
  4879.7 1779.87  4972.1 1779.54  4978.6 1779.10  4986.5 1776.70  4987.0 1776.20
  4999.0 1776.20  4999.5 1776.70  5007.3 1778.85  5021.6 1781.19  5078.9 1782.96
  5114.1 1782.44  5192.2 1783.57  5235.2 1784.95  5241.7 1786.21  5249.5 1786.68
  5262.8 1786.26  5270.3 1787.21  5276.1 1786.34  5393.2 1789.05  5575.3 1790.14
#Mann=5,-1,0
  3961.3   0.045       0  4663.1    0.07       0  4986.5    0.07       0
  4999.5    0.07       0  5276.1   0.045       0
Bank Sta=4986.5,4999.5
Exp/Cntr=0.3,0.1

Type RM Length L Ch R = 1,1853,301,301,301
BEGIN DESCRIPTION:
Mapping XS 55528287
END DESCRIPTION:
XS GIS Cut Line= 4
      1485123.30      6910250.42      1485639.80      6910194.00
      1486086.85      6910003.03      1486377.65      6909937.92
#Sta/Elev= 30
  4137.7 1788.81  4501.6 1784.67  4811.1 1779.81  4861.1 1780.03  4869.5 1779.34
  4911.0 1779.37  4956.5 1778.27  4969.1 1778.91  4987.2 1777.85  5000.0 1777.68
  5004.3 1776.97  5004.8 1776.47  5016.9 1776.47  5017.4 1776.97  5045.3 1778.15
  5068.9 1778.45  5092.5 1777.56  5143.4 1779.18  5151.8 1779.99  5162.0 1779.69
  5182.5 1782.30  5188.5 1783.53  5193.6 1783.00  5213.2 1784.25  5254.2 1785.57
  5295.2 1785.95  5315.7 1786.78  5407.9 1788.45  5420.7 1789.35  5441.4 1789.57
#Mann=4,-1,0
  4137.7   0.045       0  4861.1    0.07       0  5004.3    0.07       0
  5017.4    0.07       0
Bank Sta=5004.3,5017.4
Exp/Cntr=0.3,0.1

Type RM Length L Ch R = 1,1552,488,488,488
BEGIN DESCRIPTION:
Mapping XS d2df4b85
END DESCRIPTION:
XS GIS Cut Line= 3
      1485307.91      6910495.25      1485755.00      6910425.80
      1486480.96      6910126.75
#Sta/Elev= 30
  4223.2 1785.80  4430.5 1782.90  4697.8 1780.84  4902.8 1778.42  4948.5 1776.71
  4956.9 1777.57  4967.0 1776.38  4972.4 1774.55  4982.7 1774.08  4983.2 1773.58
  4995.3 1773.58  4995.8 1774.08  4996.4 1774.90  5001.8 1775.55  5025.7 1776.98
  5043.4 1776.47  5108.4 1777.96  5126.9 1777.44  5150.9 1777.94  5180.2 1777.24
  5227.2 1777.27  5238.9 1778.19  5257.4 1778.36  5270.5 1780.23  5302.9 1781.72
  5310.7 1782.99  5364.0 1785.96  5400.3 1787.52  5454.4 1788.60  5460.8 1788.24
#Mann=4,-1,0
  4223.2   0.045       0  4697.8    0.07       0  4982.7    0.07       0
  4995.8    0.07       0
Bank Sta=4982.7,4995.8
Exp/Cntr=0.3,0.1