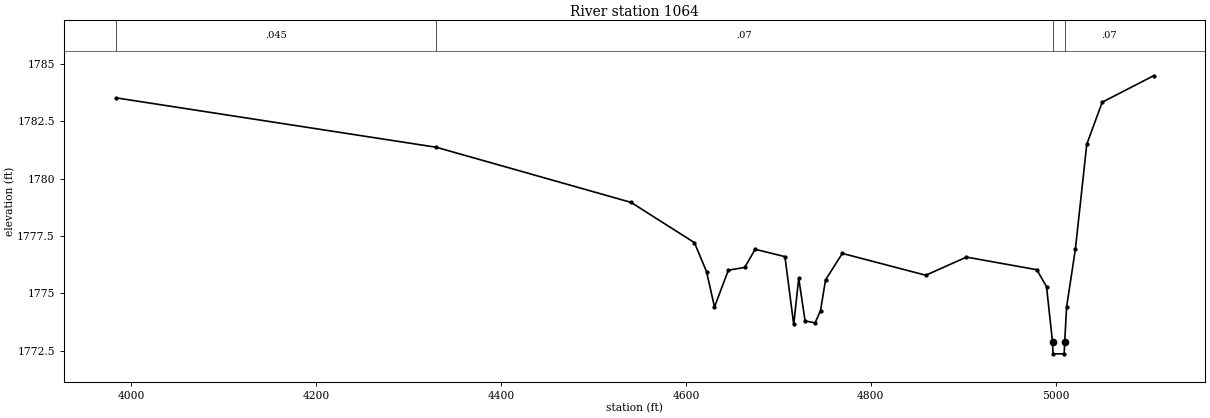
HEC-RAS study NC Unknown Stream 32.prj: NC Unknown Stream 32 Base Level Engineering

--- NC Unknown Stream 32.g01 (geometry) --- (continued)

Type RM Length L Ch R = 1,1064,0,0,0
BEGIN DESCRIPTION:
NC Unknown Stream 32 1.0
END DESCRIPTION:
XS GIS Cut Line= 3
      1485392.56      6910720.94      1485905.79      6910595.13
      1486451.37      6910361.31
#Sta/Elev= 30
  3983.7 1783.51  4330.0 1781.36  4540.7 1778.96  4609.2 1777.21  4622.3 1775.95
  4630.9 1774.41  4645.9 1776.01  4663.6 1776.13  4674.9 1776.92  4707.1 1776.60
  4716.6 1773.65  4722.0 1775.66  4728.9 1773.80  4739.7 1773.72  4745.6 1774.25
  4751.0 1775.59  4769.2 1776.74  4859.4 1775.79  4903.4 1776.58  4979.5 1776.03
  4990.0 1775.29  4996.5 1772.87  4997.0 1772.37  5009.1 1772.37  5009.6 1772.87
  5011.7 1774.41  5021.2 1776.93  5033.5 1781.49  5050.2 1783.32  5105.7 1784.47
#Mann=4,-1,0
  3983.7   0.045       0  4330.0    0.07       0  4996.5    0.07       0
  5009.6    0.07       0
Bank Sta=4996.5,5009.6
Exp/Cntr=0.3,0.1

Chan Stop Cuts=-1