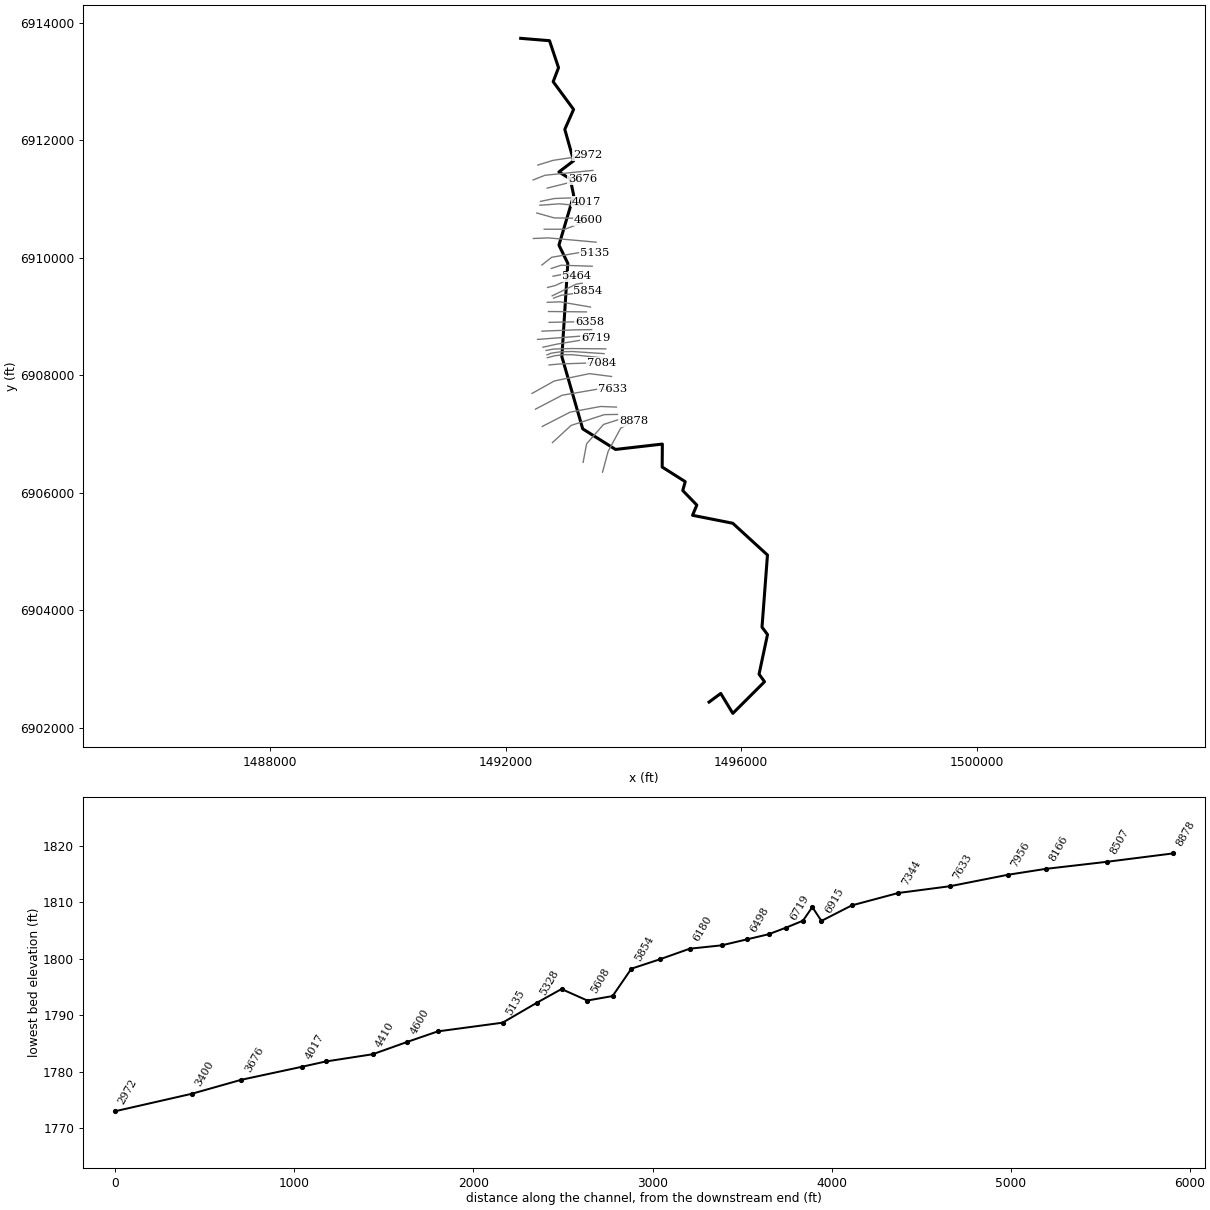
--- NC Unknown Stream 34.prj (project) ---

Proj Title=NC Unknown Stream 34 Base Level Engineering
Current Plan=p01
Default Exp/Contr=0.3,0.1
English Units
Geom File=g01
Flow File=f01
Plan File=p01
BEGIN DESCRIPTION:
NC Unknown Stream 34
END DESCRIPTION:

--- NC Unknown Stream 34.p01 (plan) ---

Plan Title=Multiple Run
Short Identifier=Multiple
Geom File=g01
Flow File=f01
Subcritical Flow
K Sum by GR= 0
Std Step Tol= 0.01
Critical Tol= 0.01
Num of Std Step Trials= 20
Max Error Tol= 0.3
Flow Tol Ratio= 0.001
Split Flow NTrial= 30
Split Flow Tol= 0.02
Split Flow Ratio= 0.02
Log Output Level= 0
Friction Slope Method= 1
Unsteady Friction Slope Method= 2
Unsteady Bridges Friction Slope Method= 1
Parabolic Critical Depth
Global Vel Dist=  1 , 1 , 1
Global Log Level= 0
CheckData=True
Encroach Param= -1, 0, 0, 0
BEGIN DESCRIPTION:
Multiple Run
END DESCRIPTION:

--- NC Unknown Stream 34.f01 (steady flow) ---

Flow Title=Multiple
Number of Profiles=7
Profile Names=10-year,25-year,50-year,1pct_min,100-year,1pct_plu,500-year
River Rch & RM= NC Unknown Strea,Reach-1,8878
     213     285     342     204     406     810     579
River Rch & RM= NC Unknown Strea,Reach-1,8166
     376     524     646     395     789    1574    1191
River Rch & RM= NC Unknown Strea,Reach-1,1442
     444     622     771     473     944    1883    1434
Boundary for River Rch & Prof#=NC Unknown Strea,Reach-1,1
Up Type=0
Dn Type=3
Dn Slope=0.001
Boundary for River Rch & Prof#=NC Unknown Strea,Reach-1,2
Up Type=0
Dn Type=3
Dn Slope=0.001
Boundary for River Rch & Prof#=NC Unknown Strea,Reach-1,3
Up Type=0
Dn Type=3
Dn Slope=0.001
Boundary for River Rch & Prof#=NC Unknown Strea,Reach-1,4
Up Type=0
Dn Type=3
Dn Slope=0.001
Boundary for River Rch & Prof#=NC Unknown Strea,Reach-1,5
Up Type=0
Dn Type=3
Dn Slope=0.001
Boundary for River Rch & Prof#=NC Unknown Strea,Reach-1,6
Up Type=0
Dn Type=3
Dn Slope=0.001
Boundary for River Rch & Prof#=NC Unknown Strea,Reach-1,7
Up Type=0
Dn Type=3
Dn Slope=0.001

--- NC Unknown Stream 34.g01 (geometry) ---

Geom Title=Existing Conditions

River Reach=NC Unknown Strea,Reach-1
Reach XY= 30
      1495455.00      6902438.00      1495653.37      6902584.91
      1495858.57      6902245.48      1496397.50      6902784.42
      1496304.42      6902913.00      1496447.89      6903588.00
      1496354.52      6903712.97      1496447.21      6904941.42
      1495857.42      6905482.46      1495174.26      6905617.92
      1495247.23      6905791.41      1495008.13      6906039.63
      1495050.01      6906190.55      1494658.46      6906439.47
      1494661.53      6906830.33      1493865.44      6906739.06
      1493308.54      6907089.47      1492954.64      6908317.85
      1493055.36      6909908.15      1492904.63      6910217.63
      1493155.51      6911063.12      1493097.33      6911344.52
      1492904.33      6911462.99      1493154.77      6911654.02
      1493004.18      6912188.00      1493153.82      6912527.49
      1492806.61      6912999.83      1492897.70      6913237.92
      1492744.53      6913697.83      1492255.00      6913738.00

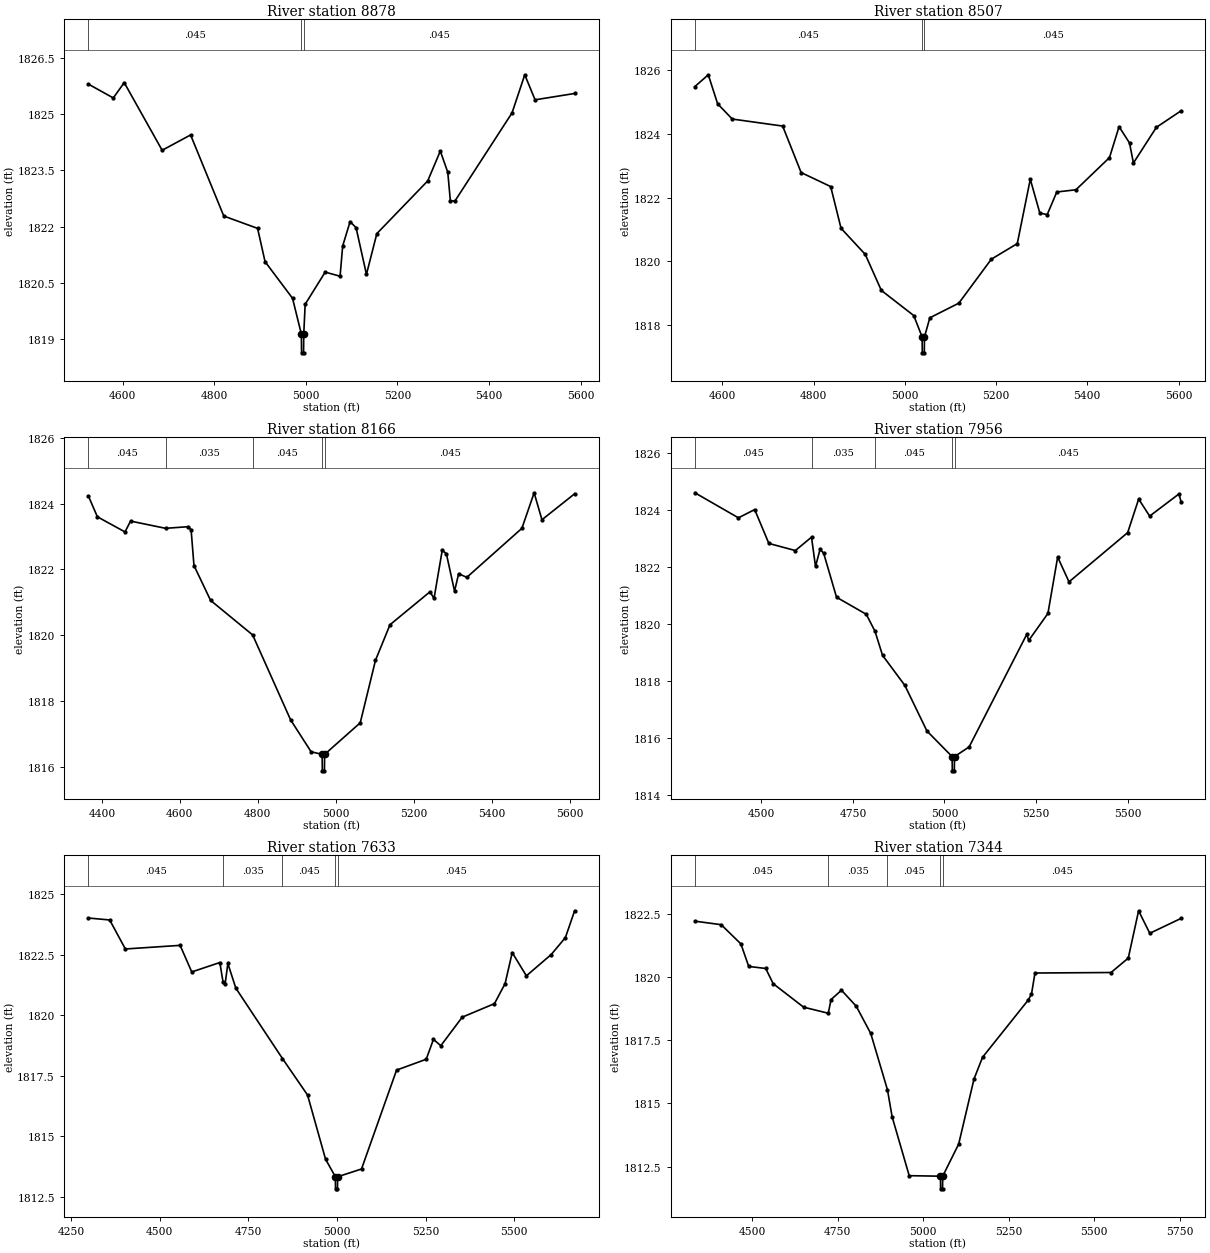
Type RM Length L Ch R = 1,8878,371,371,371
BEGIN DESCRIPTION:
Mapping XS 7144dc25
END DESCRIPTION:
XS GIS Cut Line= 4
      1493645.45      6906352.44      1493739.20      6906703.11
      1493954.47      6907102.42      1494171.57      6907216.14
#Sta/Elev= 30
  4525.5 1825.81  4579.8 1825.44  4603.7 1825.85  4686.5 1824.04  4748.6 1824.45
  4821.1 1822.28  4894.9 1821.95  4911.2 1821.06  4971.2 1820.08  4990.5 1819.12
  4990.9 1818.62  4995.3 1818.62  4995.7 1819.12  4998.8 1819.92  5042.5 1820.78
  5075.0 1820.67  5080.7 1821.48  5096.9 1822.13  5109.9 1821.97  5132.6 1820.72
  5155.3 1821.81  5266.4 1823.22  5293.9 1824.02  5310.2 1823.45  5315.8 1822.69
  5325.7 1822.68  5450.5 1825.04  5478.3 1826.06  5500.8 1825.39  5587.2 1825.56
#Mann=3,-1,0
  4525.5   0.045       0  4990.5   0.045       0  4995.7   0.045       0
Bank Sta=4990.5,4995.7
Exp/Cntr=0.3,0.1

Type RM Length L Ch R = 1,8507,341,341,341
BEGIN DESCRIPTION:
Mapping XS eb442906
END DESCRIPTION:
XS GIS Cut Line= 4
      1493315.58      6906519.08      1493374.61      6906835.06
      1493662.81      6907164.92      1493954.44      6907258.66
#Sta/Elev= 30
  4539.9 1825.49  4569.3 1825.86  4589.7 1824.95  4621.8 1824.47  4732.3 1824.25
  4772.8 1822.79  4837.6 1822.35  4860.3 1821.04  4913.4 1820.22  4948.6 1819.09
  5019.7 1818.30  5038.0 1817.63  5038.4 1817.13  5042.8 1817.13  5043.2 1817.63
  5054.9 1818.23  5118.5 1818.69  5189.7 1820.07  5246.6 1820.56  5275.1 1822.58
  5296.0 1821.52  5312.2 1821.47  5333.2 1822.18  5375.2 1822.25  5448.7 1823.26
  5469.7 1824.23  5492.6 1823.72  5501.2 1823.09  5551.5 1824.21  5605.7 1824.73
#Mann=3,-1,0
  4539.9   0.045       0  5038.0   0.045       0  5043.2   0.045       0
Bank Sta=5038,5043.2
Exp/Cntr=0.3,0.1

Type RM Length L Ch R = 1,8166,210,210,210
BEGIN DESCRIPTION:
Mapping XS 007a3bee
END DESCRIPTION:
XS GIS Cut Line= 4
      1492794.72      6906855.86      1493110.72      6907147.56
      1493676.70      6907331.58      1493898.87      6907335.06
#Sta/Elev= 30
  4365.4 1824.23  4388.4 1823.60  4459.3 1823.14  4473.5 1823.47  4563.3 1823.25
  4622.1 1823.30  4628.9 1823.20  4636.2 1822.12  4678.8 1821.06  4786.7 1820.01
  4884.1 1817.43  4936.7 1816.46  4965.0 1816.38  4965.5 1815.88  4970.9 1815.88
  4971.4 1816.38  5062.8 1817.34  5101.9 1819.24  5139.1 1820.32  5241.6 1821.32
  5252.1 1821.12  5273.1 1822.58  5283.7 1822.48  5304.7 1821.34  5315.2 1821.87
  5336.2 1821.76  5477.5 1823.25  5508.9 1824.33  5528.9 1823.51  5612.8 1824.30
#Mann=5,-1,0
  4365.4   0.045       0  4563.3   0.035       0  4786.7   0.045       0
  4965.0   0.045       0  4971.4   0.045       0
Bank Sta=4965,4971.4
Exp/Cntr=0.3,0.1

Type RM Length L Ch R = 1,7956,323,323,323
BEGIN DESCRIPTION:
Mapping XS 82c94dca
END DESCRIPTION:
XS GIS Cut Line= 4
      1492621.12      6907130.19      1493093.36      6907373.25
      1493610.72      6907470.47      1493880.79      6907460.09
#Sta/Elev= 30
  4318.4 1824.61  4437.3 1823.73  4481.7 1824.02  4520.4 1822.83  4592.7 1822.58
  4636.9 1823.05  4647.8 1822.02  4660.2 1822.62  4670.0 1822.49  4705.2 1820.94
  4786.5 1820.34  4810.4 1819.74  4830.8 1818.90  4891.9 1817.84  4952.1 1816.24
  5020.9 1815.34  5021.4 1814.84  5026.9 1814.84  5027.4 1815.34  5067.3 1815.68
  5224.9 1819.64  5230.0 1819.42  5282.5 1820.37  5309.1 1822.35  5340.1 1821.48
  5500.3 1823.21  5530.3 1824.39  5560.3 1823.79  5640.4 1824.57  5646.2 1824.29
#Mann=5,-1,0
  4318.4   0.045       0  4636.9   0.035       0  4810.4   0.045       0
  5020.9   0.045       0  5027.4   0.045       0
Bank Sta=5020.9,5027.4
Exp/Cntr=0.3,0.1

Type RM Length L Ch R = 1,7633,289,289,289
BEGIN DESCRIPTION:
Mapping XS 642b2f21
END DESCRIPTION:
XS GIS Cut Line= 4
      1492506.54      6907425.33      1492957.95      6907661.45
      1493562.11      6907765.61      1493811.08      6907762.15
#Sta/Elev= 30
  4298.9 1824.02  4358.9 1823.94  4403.1 1822.74  4557.6 1822.89  4590.4 1821.79
  4669.6 1822.18  4678.7 1821.37  4684.4 1821.28  4692.2 1822.14  4714.7 1821.12
  4846.2 1818.21  4917.0 1816.70  4967.7 1814.05  4995.4 1813.32  4995.9 1812.82
  5001.4 1812.82  5001.9 1813.32  5069.2 1813.64  5168.1 1817.73  5251.8 1818.18
  5272.1 1819.00  5292.9 1818.74  5353.3 1819.92  5444.3 1820.48  5474.3 1821.31
  5494.3 1822.59  5534.3 1821.63  5604.3 1822.51  5644.3 1823.21  5670.4 1824.32
#Mann=5,-1,0
  4298.9   0.045       0  4678.7   0.035       0  4846.2   0.045       0
  4995.4   0.045       0  5001.9   0.045       0
Bank Sta=4995.4,5001.9
Exp/Cntr=0.3,0.1

Type RM Length L Ch R = 1,7344,260,260,260
BEGIN DESCRIPTION:
Mapping XS 8160901a
END DESCRIPTION:
XS GIS Cut Line= 4
      1492447.54      6907692.70      1492826.00      6907904.50
      1493423.22      6908029.50      1493798.23      6907980.89
#Sta/Elev= 30
  4332.2 1822.20  4409.2 1822.06  4466.8 1821.30  4489.7 1820.41  4539.4 1820.33
  4561.1 1819.73  4650.2 1818.80  4722.3 1818.56  4730.4 1819.10  4760.9 1819.47
  4804.0 1818.84  4846.6 1817.76  4895.5 1815.53  4909.0 1814.47  4959.0 1812.14
  5050.4 1812.12  5050.9 1811.62  5056.5 1811.62  5057.0 1812.12  5103.7 1813.39
  5148.5 1815.96  5173.5 1816.82  5306.4 1819.07  5316.6 1819.31  5326.8 1820.15
  5549.3 1820.17  5599.7 1820.74  5629.9 1822.61  5662.6 1821.72  5754.2 1822.31
#Mann=5,-1,0
  4332.2   0.045       0  4722.3   0.035       0  4895.5   0.045       0
  5050.4   0.045       0  5057.0   0.045       0
Bank Sta=5050.4,5057
Exp/Cntr=0.3,0.1

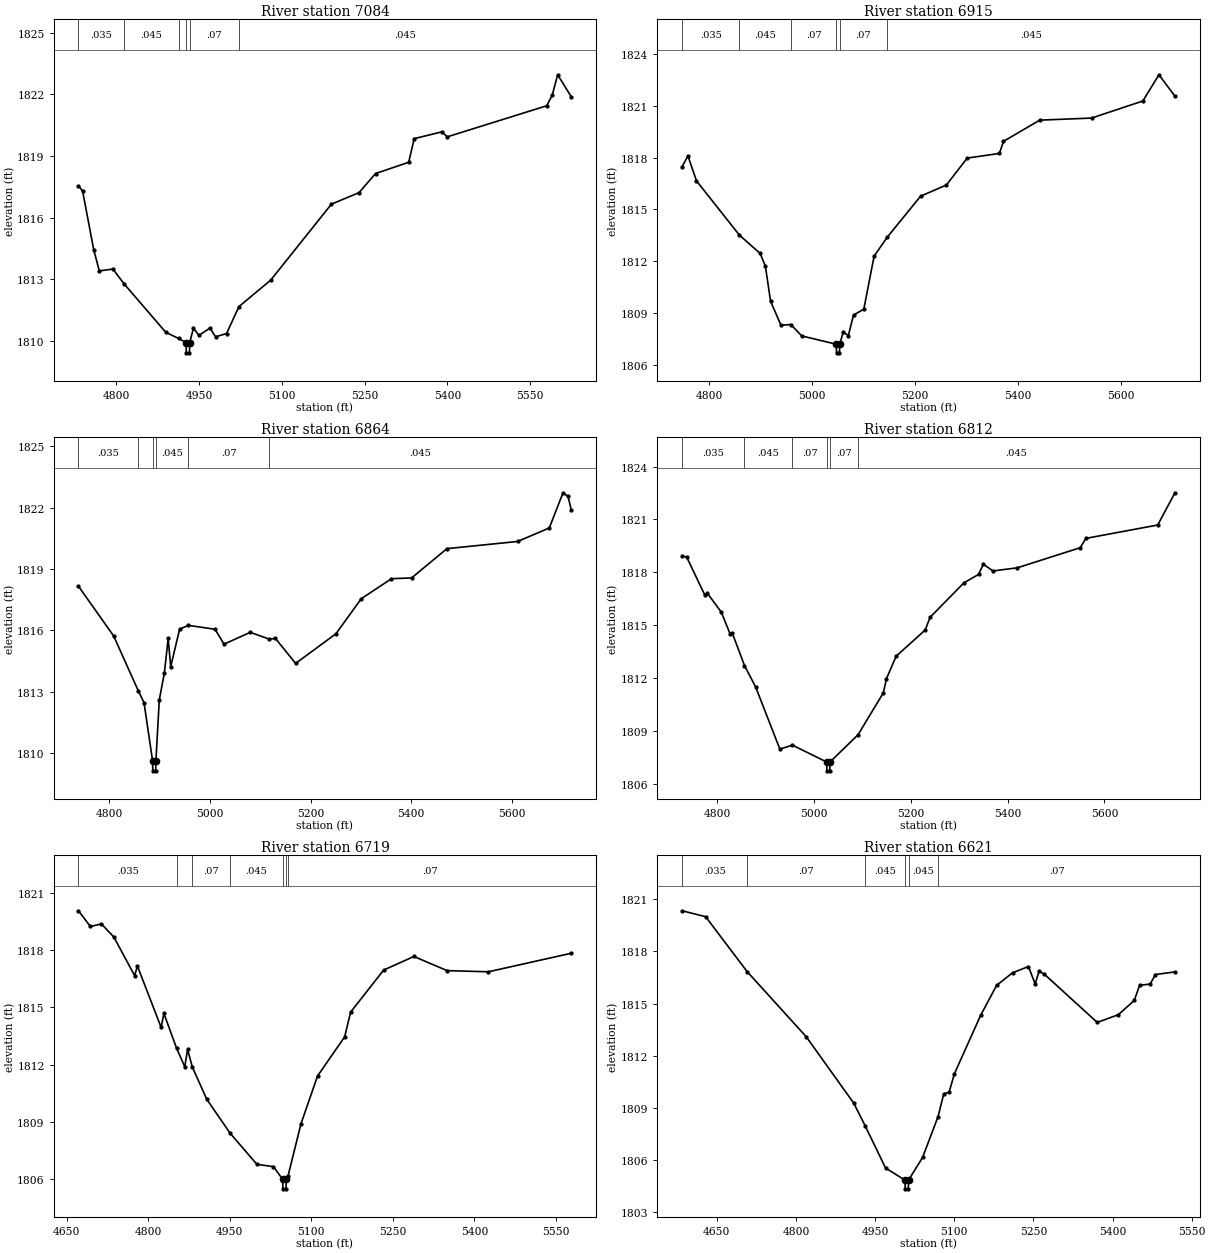
Type RM Length L Ch R = 1,7084,169,169,169
BEGIN DESCRIPTION:
Mapping XS c7f033c9
END DESCRIPTION:
XS GIS Cut Line= 3
      1492737.49      6908177.07      1492918.01      6908194.43
      1493629.80      6908217.00
#Sta/Elev= 30
  4731.2 1817.56  4738.7 1817.29  4758.8 1814.44  4768.9 1813.41  4793.6 1813.50
  4813.5 1812.79  4889.4 1810.42  4912.7 1810.12  4926.2 1809.92  4926.7 1809.42
  4932.3 1809.42  4932.8 1809.92  4939.6 1810.62  4949.6 1810.27  4969.6 1810.63
  4979.6 1810.20  4999.6 1810.36  5022.0 1811.67  5079.6 1812.96  5189.7 1816.66
  5239.7 1817.22  5269.7 1818.15  5329.8 1818.70  5339.8 1819.85  5389.8 1820.18
  5399.8 1819.94  5579.9 1821.45  5589.9 1821.96  5599.9 1822.96  5624.7 1821.88
#Mann=6,-1,0
  4731.2   0.035       0  4813.5   0.045       0  4912.7    0.07       0
  4926.2    0.07       0  4932.8    0.07       0  5022.0   0.045       0
Bank Sta=4926.2,4932.8
Exp/Cntr=0.3,0.1

Type RM Length L Ch R = 1,6915,51,51,51
BEGIN DESCRIPTION:
Mapping XS 821691c5
END DESCRIPTION:
XS GIS Cut Line= 5
      1492707.93      6908300.33      1492831.21      6908333.32
      1492973.57      6908352.42      1493147.18      6908350.68
      1493655.87      6908296.86
#Sta/Elev= 30
  4747.8 1817.46  4759.2 1818.10  4775.8 1816.65  4859.0 1813.51  4899.4 1812.44
  4909.5 1811.71  4919.6 1809.67  4939.8 1808.28  4958.9 1808.32  4980.1 1807.66
  5047.1 1807.18  5047.6 1806.68  5053.3 1806.68  5053.8 1807.18  5060.5 1807.88
  5070.5 1807.68  5080.5 1808.87  5100.5 1809.21  5120.5 1812.29  5145.6 1813.37
  5210.6 1815.76  5260.8 1816.41  5301.1 1817.97  5363.6 1818.24  5371.5 1818.94
  5441.9 1820.17  5542.4 1820.29  5641.9 1821.28  5673.2 1822.80  5704.2 1821.56
#Mann=6,-1,0
  4747.8   0.035       0  4859.0   0.045       0  4958.9    0.07       0
  5047.1    0.07       0  5053.8    0.07       0  5145.6   0.045       0
Bank Sta=5047.1,5053.8
Exp/Cntr=0.3,0.1

Type RM Length L Ch R = 1,6864,52,52,52
BEGIN DESCRIPTION:
Mapping XS 3dcb33cd
END DESCRIPTION:
XS GIS Cut Line= 6
      1492700.96      6908348.93      1492775.65      6908378.46
      1492905.86      6908397.56      1492985.72      6908402.77
      1493133.29      6908406.24      1493671.60      6908369.89
#Sta/Elev= 30
  4738.9 1818.15  4808.8 1815.72  4857.7 1813.04  4869.1 1812.46  4886.0 1809.63
  4886.5 1809.13  4892.2 1809.13  4892.7 1809.63  4899.4 1812.60  4909.5 1813.91
  4917.0 1815.60  4922.1 1814.22  4939.8 1816.06  4957.4 1816.24  5010.1 1816.05
  5028.0 1815.32  5080.1 1815.90  5117.5 1815.57  5130.2 1815.60  5170.2 1814.38
  5250.3 1815.83  5300.5 1817.54  5360.6 1818.52  5400.7 1818.56  5470.8 1819.99
  5611.2 1820.34  5674.1 1821.00  5701.4 1822.72  5711.4 1822.54  5718.0 1821.86
#Mann=6,-1,0
  4738.9   0.035       0  4857.7   0.045       0  4886.0    0.07       0
  4892.7   0.045       0  4957.4    0.07       0  5117.5   0.045       0
Bank Sta=4886,4892.7
Exp/Cntr=0.3,0.1

Type RM Length L Ch R = 1,6812,93,93,93
BEGIN DESCRIPTION:
Mapping XS 99086f1d
END DESCRIPTION:
XS GIS Cut Line= 4
      1492685.39      6908423.60      1492810.38      6908447.90
      1493098.57      6908456.58      1493700.50      6908451.38
#Sta/Elev= 30
  4728.0 1818.94  4737.8 1818.85  4775.3 1816.68  4780.4 1816.80  4809.1 1815.73
  4827.0 1814.51  4832.1 1814.52  4856.9 1812.70  4880.0 1811.48  4930.0 1807.95
  4955.9 1808.18  5026.7 1807.22  5027.2 1806.72  5032.9 1806.72  5033.4 1807.22
  5091.4 1808.77  5143.6 1811.15  5150.1 1811.96  5170.1 1813.23  5230.1 1814.72
  5240.1 1815.44  5310.1 1817.40  5340.1 1817.87  5350.1 1818.45  5370.1 1818.07
  5420.1 1818.25  5550.1 1819.39  5561.7 1819.92  5710.1 1820.68  5745.6 1822.51
#Mann=6,-1,0
  4728.0   0.035       0  4856.9   0.045       0  4955.9    0.07       0
  5026.7    0.07       0  5033.4    0.07       0  5091.4   0.045       0
Bank Sta=5026.7,5033.4
Exp/Cntr=0.3,0.1

Type RM Length L Ch R = 1,6719,98,98,98
BEGIN DESCRIPTION:
Mapping XS 3c1d4fbd
END DESCRIPTION:
XS GIS Cut Line= 3
      1492633.68      6908479.58      1492868.10      6908531.67
      1493525.67      6908640.18
#Sta/Elev= 30
  4671.8 1820.05  4693.6 1819.23  4714.1 1819.36  4736.7 1818.68  4775.1 1816.66
  4780.2 1817.16  4823.8 1813.95  4828.9 1814.68  4852.4 1812.85  4867.3 1811.89
  4872.4 1812.80  4881.3 1811.87  4907.8 1810.19  4950.9 1808.41  5000.0 1806.79
  5030.4 1806.67  5047.3 1806.01  5047.8 1805.51  5053.5 1805.51  5054.0 1806.01
  5057.0 1806.16  5081.1 1808.92  5111.5 1811.41  5161.4 1813.46  5172.3 1814.75
  5233.1 1816.95  5288.7 1817.66  5349.9 1816.92  5425.7 1816.86  5578.4 1817.83
#Mann=7,-1,0
  4671.8   0.035       0  4852.4   0.045       0  4881.3    0.07       0
  4950.9   0.045       0  5047.3   0.045       0  5054.0   0.045       0
  5057.0    0.07       0
Bank Sta=5047.3,5054
Exp/Cntr=0.3,0.1

Type RM Length L Ch R = 1,6621,123,123,123
BEGIN DESCRIPTION:
Mapping XS b37e9e35
END DESCRIPTION:
XS GIS Cut Line= 2
      1492540.41      6908611.97      1493471.77      6908683.44
#Sta/Elev= 30
  4584.2 1820.34  4628.9 1820.00  4707.5 1816.84  4819.5 1813.09  4909.7 1809.26
  4931.7 1807.93  4969.9 1805.53  5006.7 1804.83  5007.2 1804.33  5012.9 1804.33
  5013.4 1804.83  5040.1 1806.14  5069.3 1808.48  5080.2 1809.80  5090.3 1809.89
  5100.3 1810.95  5150.4 1814.34  5180.5 1816.05  5210.6 1816.77  5240.7 1817.13
  5253.4 1816.13  5260.8 1816.86  5270.8 1816.69  5371.1 1813.91  5411.2 1814.36
  5441.3 1815.18  5451.3 1816.05  5471.4 1816.12  5481.4 1816.67  5518.3 1816.82
#Mann=6,-1,0
  4584.2   0.035       0  4707.5    0.07       0  4931.7   0.045       0
  5006.7   0.045       0  5013.4   0.045       0  5069.3    0.07       0
Bank Sta=5006.7,5013.4
Exp/Cntr=0.3,0.1

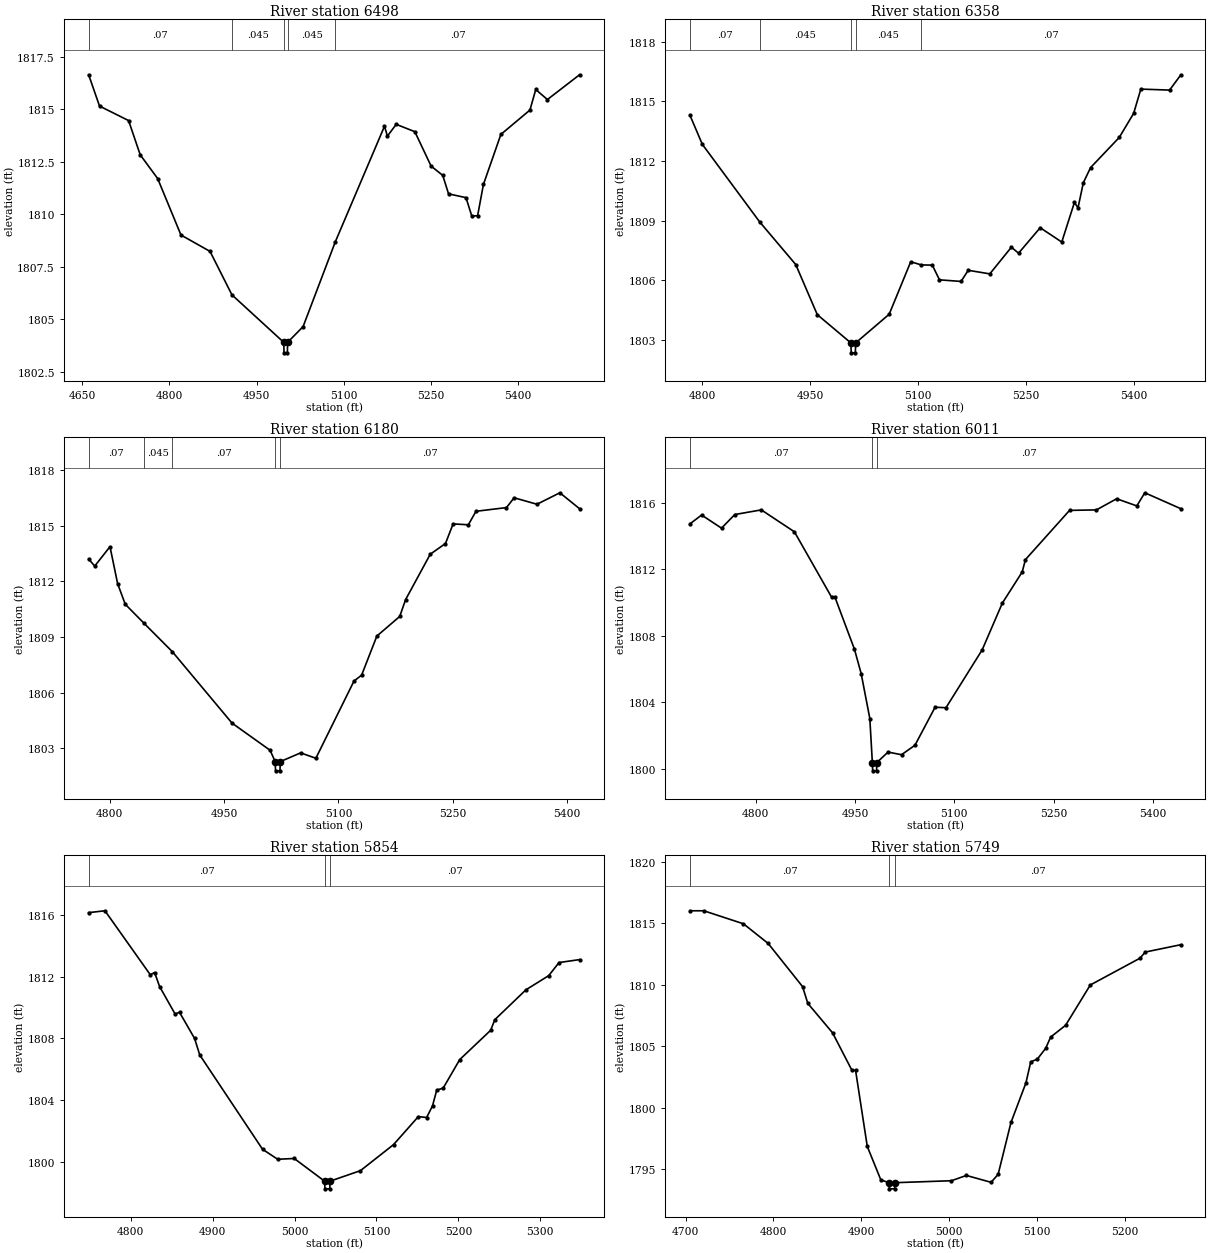
Type RM Length L Ch R = 1,6498,140,140,140
BEGIN DESCRIPTION:
Mapping XS 53862c5c
END DESCRIPTION:
XS GIS Cut Line= 3
      1492616.35      6908753.03      1493174.09      6908774.73
      1493460.30      6908779.06
#Sta/Elev= 30
  4661.1 1816.65  4679.8 1815.16  4729.8 1814.47  4749.8 1812.84  4779.8 1811.71
  4819.9 1809.02  4869.9 1808.24  4907.6 1806.17  4996.7 1803.91  4997.2 1803.41
  5002.9 1803.41  5003.4 1803.91  5030.0 1804.66  5085.6 1808.71  5170.0 1814.20
  5175.0 1813.73  5190.2 1814.29  5222.2 1813.94  5250.2 1812.30  5270.2 1811.86
  5280.2 1810.98  5310.2 1810.80  5320.2 1809.92  5330.2 1809.94  5340.2 1811.43
  5370.2 1813.81  5420.2 1814.97  5430.2 1815.95  5450.2 1815.47  5505.5 1816.65
#Mann=5,-1,0
  4661.1    0.07       0  4907.6   0.045       0  4996.7   0.045       0
  5003.4   0.045       0  5085.6    0.07       0
Bank Sta=4996.7,5003.4
Exp/Cntr=0.3,0.1

Type RM Length L Ch R = 1,6358,178,178,178
BEGIN DESCRIPTION:
Mapping XS 3ddb57eb
END DESCRIPTION:
XS GIS Cut Line= 2
      1492737.94      6908902.77      1493420.71      6908915.77
#Sta/Elev= 30
  4782.9 1814.30  4800.1 1812.84  4879.9 1808.94  4930.0 1806.80  4960.0 1804.28
  5006.7 1802.86  5007.2 1802.36  5012.9 1802.36  5013.4 1802.86  5060.0 1804.30
  5090.0 1806.94  5104.7 1806.78  5120.0 1806.77  5130.0 1806.03  5160.0 1805.95
  5170.0 1806.51  5200.0 1806.33  5230.0 1807.67  5240.0 1807.37  5270.1 1808.65
  5300.1 1807.93  5317.7 1809.92  5322.7 1809.65  5330.1 1810.91  5340.1 1811.67
  5380.1 1813.19  5400.1 1814.40  5410.1 1815.62  5450.1 1815.57  5465.8 1816.34
#Mann=5,-1,0
  4782.9    0.07       0  4879.9   0.045       0  5006.7   0.045       0
  5013.4   0.045       0  5104.7    0.07       0
Bank Sta=5006.7,5013.4
Exp/Cntr=0.3,0.1

Type RM Length L Ch R = 1,6180,169,169,169
BEGIN DESCRIPTION:
Mapping XS 8c2bdb79
END DESCRIPTION:
XS GIS Cut Line= 2
      1492727.04      6909087.23      1493370.81      6909080.72
#Sta/Elev= 30
  4772.4 1813.21  4780.4 1812.83  4800.4 1813.88  4810.4 1811.88  4820.4 1810.77
  4844.8 1809.75  4882.3 1808.20  4960.4 1804.35  5010.4 1802.88  5017.0 1802.27
  5017.5 1801.77  5023.3 1801.77  5023.8 1802.27  5050.4 1802.74  5070.4 1802.45
  5120.4 1806.62  5130.4 1806.94  5150.4 1809.05  5180.4 1810.11  5188.1 1811.02
  5220.4 1813.47  5240.4 1814.05  5250.4 1815.11  5270.4 1815.06  5280.4 1815.79
  5320.4 1815.99  5330.4 1816.52  5360.4 1816.17  5390.4 1816.79  5416.2 1815.93
#Mann=5,-1,0
  4772.4    0.07       0  4844.8   0.045       0  4882.3    0.07       0
  5017.0    0.07       0  5023.8    0.07       0
Bank Sta=5017,5023.8
Exp/Cntr=0.3,0.1

Type RM Length L Ch R = 1,6011,157,157,157
BEGIN DESCRIPTION:
Mapping XS 34fc380c
END DESCRIPTION:
XS GIS Cut Line= 3
      1492707.48      6909243.48      1492922.36      6909252.16
      1493440.54      6909163.26
#Sta/Elev= 30
  4701.1 1814.74  4718.6 1815.27  4748.7 1814.48  4768.7 1815.30  4808.7 1815.58
  4858.7 1814.26  4915.0 1810.31  4920.0 1810.31  4949.3 1807.19  4959.4 1805.73
  4972.5 1803.02  4976.3 1800.37  4976.8 1799.87  4982.6 1799.87  4983.1 1800.37
  5000.0 1801.00  5020.3 1800.84  5040.6 1801.41  5071.0 1803.70  5087.4 1803.67
  5142.0 1807.15  5172.5 1809.97  5202.4 1811.84  5207.4 1812.59  5273.9 1815.55
  5314.5 1815.58  5345.0 1816.25  5375.4 1815.82  5387.5 1816.61  5441.9 1815.65
#Mann=3,-1,0
  4701.1    0.07       0  4976.3    0.07       0  4983.1    0.07       0
Bank Sta=4976.3,4983.1
Exp/Cntr=0.3,0.1

Type RM Length L Ch R = 1,5854,105,105,105
BEGIN DESCRIPTION:
Mapping XS 729998de
END DESCRIPTION:
XS GIS Cut Line= 3
      1492813.89      6909315.11      1492941.89      6909362.83
      1493399.77      6909427.94
#Sta/Elev= 30
  4748.7 1816.16  4768.6 1816.28  4823.9 1812.13  4829.2 1812.27  4835.3 1811.36
  4854.2 1809.58  4859.6 1809.69  4878.0 1807.99  4884.3 1806.92  4960.9 1800.80
  4979.4 1800.15  4999.6 1800.20  5036.6 1798.73  5037.1 1798.23  5042.9 1798.23
  5043.4 1798.73  5080.4 1799.41  5120.8 1801.10  5151.1 1802.92  5161.2 1802.86
  5168.4 1803.62  5173.5 1804.64  5181.4 1804.77  5201.6 1806.62  5239.3 1808.52
  5244.4 1809.21  5282.4 1811.15  5310.2 1812.07  5322.8 1812.92  5347.8 1813.11
#Mann=3,-1,0
  4748.7    0.07       0  5036.6    0.07       0  5043.4    0.07       0
Bank Sta=5036.6,5043.4
Exp/Cntr=0.3,0.1

Type RM Length L Ch R = 1,5749,141,141,141
BEGIN DESCRIPTION:
Mapping XS 7940c65c
END DESCRIPTION:
XS GIS Cut Line= 4
      1492789.95      6909354.14      1492959.25      6909436.62
      1493200.13      6909553.81      1493301.02      6909568.83
#Sta/Elev= 30
  4705.1 1816.02  4720.8 1816.02  4765.9 1814.96  4794.0 1813.36  4833.1 1809.85
  4839.1 1808.48  4867.2 1806.09  4889.3 1803.03  4893.4 1803.03  4906.7 1796.84
  4922.1 1794.12  4931.4 1793.89  4931.9 1793.39  4937.7 1793.39  4938.2 1793.89
  5002.4 1794.05  5019.4 1794.48  5047.5 1793.92  5055.5 1794.57  5070.1 1798.79
  5087.1 1802.01  5092.6 1803.73  5100.0 1803.94  5109.6 1804.83  5115.2 1805.74
  5132.2 1806.70  5160.3 1809.98  5216.8 1812.16  5222.8 1812.66  5263.3 1813.26
#Mann=3,-1,0
  4705.1    0.07       0  4931.4    0.07       0  4938.2    0.07       0
Bank Sta=4931.4,4938.2
Exp/Cntr=0.3,0.1

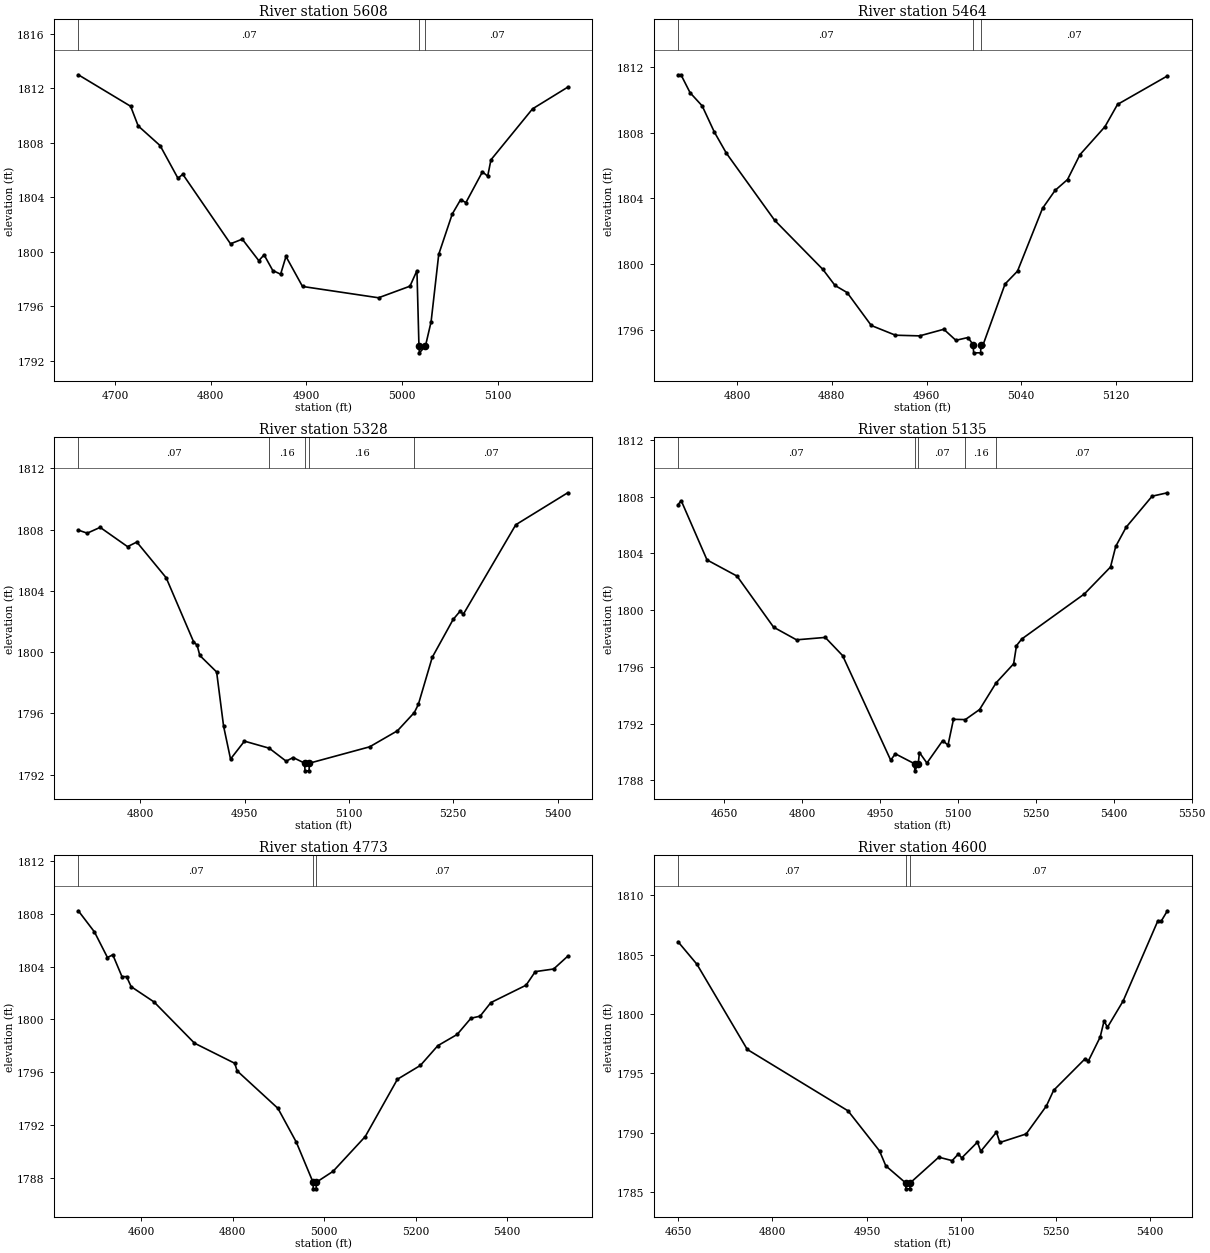
Type RM Length L Ch R = 1,5608,144,144,144
BEGIN DESCRIPTION:
Mapping XS 20b103dd
END DESCRIPTION:
XS GIS Cut Line= 4
      1492711.86      6909497.39      1492844.23      6909529.94
      1493113.33      6909655.80      1493191.84      6909655.80
#Sta/Elev= 30
  4661.5 1813.00  4716.2 1810.69  4724.1 1809.25  4747.1 1807.80  4765.7 1805.41
  4770.8 1805.70  4820.7 1800.60  4833.0 1800.94  4850.3 1799.36  4855.8 1799.79
  4864.9 1798.64  4873.1 1798.37  4878.7 1799.67  4896.0 1797.47  4975.5 1796.64
  5008.4 1797.49  5015.7 1798.63  5017.8 1793.10  5018.3 1792.60  5024.6 1793.10
  5030.5 1794.88  5038.5 1799.83  5052.6 1802.78  5061.4 1803.84  5066.9 1803.62
  5084.2 1805.88  5089.7 1805.56  5093.1 1806.76  5136.6 1810.50  5173.4 1812.09
#Mann=3,-1,0
  4661.5    0.07       0  5017.8    0.07       0  5024.6    0.07       0
Bank Sta=5017.8,5024.6
Exp/Cntr=0.3,0.1

Type RM Length L Ch R = 1,5464,136,136,136
BEGIN DESCRIPTION:
NC Unknown Stream 34 8.0
END DESCRIPTION:
XS GIS Cut Line= 3
      1492805.04      6909688.01      1493055.00      6909738.00
      1493204.97      6909688.01
#Sta/Elev= 30
  4750.3 1811.51  4752.8 1811.51  4760.5 1810.42  4770.7 1809.62  4780.9 1808.04
  4791.1 1806.75  4831.8 1802.68  4872.6 1799.69  4882.8 1798.72  4893.0 1798.29
  4913.4 1796.29  4933.8 1795.70  4954.2 1795.66  4974.6 1796.06  4984.8 1795.39
  4995.0 1795.56  4999.3 1795.13  4999.8 1794.63  5005.6 1794.63  5006.1 1795.13
  5007.8 1795.13  5026.3 1798.81  5036.8 1799.59  5057.9 1803.40  5068.5 1804.49
  5079.0 1805.15  5089.5 1806.66  5110.6 1808.36  5121.2 1809.71  5163.3 1811.44
#Mann=3,-1,0
  4750.3    0.07       0  4999.3    0.07       0  5006.1    0.07       0
Bank Sta=4999.3,5006.1
Exp/Cntr=0.3,0.1

Type RM Length L Ch R = 1,5328,193,193,193
BEGIN DESCRIPTION:
Mapping XS 08af6eab
END DESCRIPTION:
XS GIS Cut Line= 3
      1492775.17      6909819.85      1492941.89      6909875.42
      1493469.67      6909858.06
#Sta/Elev= 30
  4710.8 1807.97  4723.6 1807.77  4742.2 1808.15  4781.6 1806.89  4794.9 1807.19
  4837.1 1804.86  4876.4 1800.69  4881.7 1800.44  4885.5 1799.78  4909.7 1798.70
  4919.7 1795.16  4929.7 1793.01  4949.7 1794.18  4985.3 1793.72  5009.7 1792.87
  5019.7 1793.11  5036.3 1792.74  5036.8 1792.24  5042.6 1792.24  5043.1 1792.74
  5129.8 1793.81  5169.8 1794.86  5194.0 1796.05  5199.8 1796.58  5219.8 1799.66
  5249.8 1802.13  5259.6 1802.66  5264.6 1802.48  5339.9 1808.32  5414.6 1810.41
#Mann=5,-1,0
  4710.8    0.07       0  4985.3    0.16       0  5036.3    0.07       0
  5043.1    0.16       0  5194.0    0.07       0
Bank Sta=5036.3,5043.1
Exp/Cntr=0.3,0.1

Type RM Length L Ch R = 1,5135,362,362,362
BEGIN DESCRIPTION:
Mapping XS a3fbd3a2
END DESCRIPTION:
XS GIS Cut Line= 4
      1492615.52      6909878.91      1492782.16      6910010.84
      1493275.22      6910094.17      1493504.39      6910083.75
#Sta/Elev= 30
  4561.3 1807.44  4567.5 1807.71  4617.1 1803.54  4674.9 1802.40  4745.3 1798.80
  4789.4 1797.91  4844.7 1798.08  4878.1 1796.80  4970.7 1789.43  4979.6 1789.88
  5016.6 1789.18  5017.1 1788.68  5023.7 1789.18  5026.0 1789.97  5040.4 1789.23
  5070.8 1790.81  5081.0 1790.49  5091.5 1792.31  5114.3 1792.29  5141.8 1793.00
  5173.6 1794.88  5207.3 1796.22  5212.8 1797.50  5223.0 1797.97  5343.7 1801.15
  5393.8 1803.04  5403.8 1804.49  5423.8 1805.84  5473.9 1808.03  5503.3 1808.27
#Mann=5,-1,0
  4561.3    0.07       0  5016.6    0.07       0  5023.7    0.07       0
  5114.3    0.16       0  5173.6    0.07       0
Bank Sta=5016.6,5023.7
Exp/Cntr=0.3,0.1

Type RM Length L Ch R = 1,4773,173,173,173
BEGIN DESCRIPTION:
Mapping XS 767c1fc7
END DESCRIPTION:
XS GIS Cut Line= 3
      1492469.71      6910330.28      1492726.61      6910340.70
      1493535.62      6910267.78
#Sta/Elev= 30
  4463.0 1808.25  4498.3 1806.64  4526.7 1804.70  4538.3 1804.91  4558.4 1803.25
  4568.4 1803.25  4578.4 1802.49  4628.4 1801.33  4716.8 1798.20  4804.9 1796.67
  4809.9 1796.10  4899.2 1793.25  4939.4 1790.68  4975.9 1787.64  4976.4 1787.14
  4982.6 1787.14  4983.1 1787.64  5019.7 1788.47  5090.0 1791.11  5160.3 1795.46
  5210.5 1796.51  5248.6 1798.01  5290.8 1798.86  5320.9 1800.09  5341.0 1800.25
  5364.5 1801.28  5441.4 1802.60  5461.5 1803.63  5501.7 1803.83  5532.4 1804.80
#Mann=3,-1,0
  4463.0    0.07       0  4975.9    0.07       0  4983.1    0.07       0
Bank Sta=4975.9,4983.1
Exp/Cntr=0.3,0.1

Type RM Length L Ch R = 1,4600,190,190,190
BEGIN DESCRIPTION:
NC Unknown Stream 34 6.0
END DESCRIPTION:
XS GIS Cut Line= 3
      1492655.00      6910488.00      1493005.00      6910488.00
      1493405.00      6910638.00
#Sta/Elev= 30
  4650.0 1806.10  4680.0 1804.20  4760.0 1797.01  4920.0 1791.83  4970.0 1788.45
  4980.0 1787.19  5011.5 1785.75  5012.0 1785.25  5018.2 1785.25  5018.7 1785.75
  5064.1 1787.92  5085.4 1787.63  5095.2 1788.19  5100.6 1787.86  5125.5 1789.19
  5130.8 1788.42  5155.7 1790.03  5161.1 1789.16  5202.9 1789.88  5235.0 1792.24
  5246.5 1793.56  5296.4 1796.22  5301.7 1796.04  5320.4 1798.05  5326.6 1799.41
  5332.0 1798.88  5356.9 1801.10  5412.1 1807.87  5417.4 1807.84  5427.2 1808.71
#Mann=3,-1,0
  4650.0    0.07       0  5011.5    0.07       0  5018.7    0.07       0
Bank Sta=5011.5,5018.7
Exp/Cntr=0.3,0.1

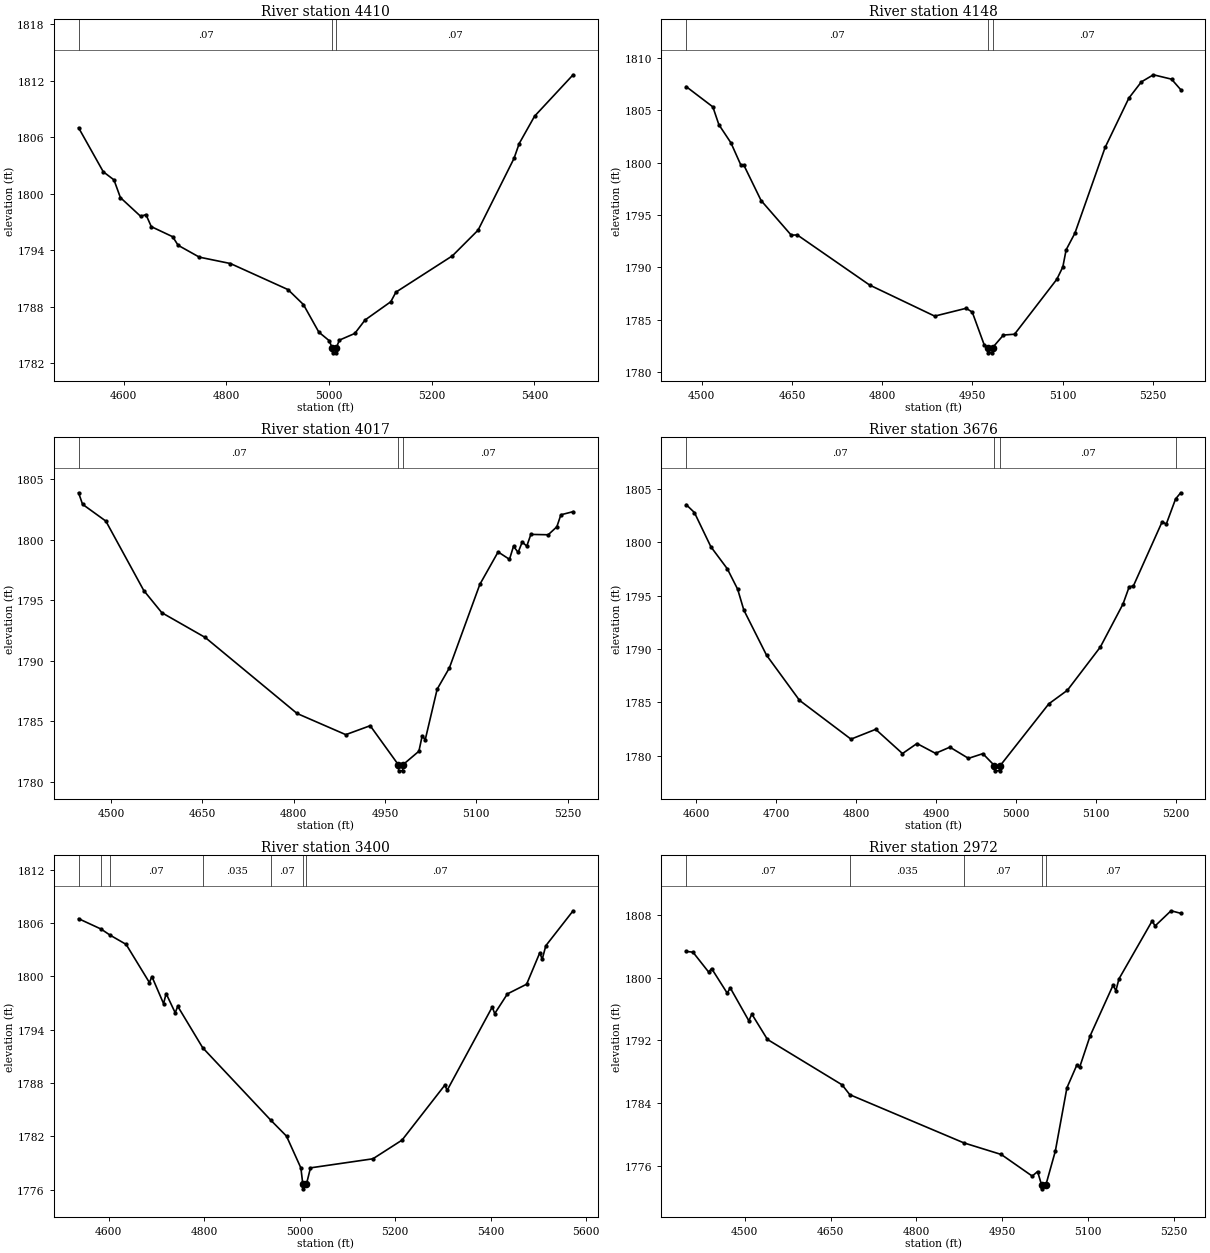
Type RM Length L Ch R = 1,4410,262,262,262
BEGIN DESCRIPTION:
Mapping XS 49efa101
END DESCRIPTION:
XS GIS Cut Line= 3
      1492528.72      6910764.30      1492823.83      6910680.98
      1493480.00      6910670.56
#Sta/Elev= 30
  4512.5 1807.02  4560.6 1802.34  4581.4 1801.48  4593.9 1799.60  4633.3 1797.61
  4643.7 1797.79  4654.1 1796.51  4695.7 1795.44  4706.3 1794.53  4747.6 1793.27
  4808.2 1792.59  4920.3 1789.82  4950.3 1788.23  4980.3 1785.30  5000.3 1784.40
  5006.7 1783.60  5007.2 1783.10  5013.5 1783.10  5014.0 1783.60  5020.3 1784.45
  5050.3 1785.16  5070.3 1786.59  5120.4 1788.53  5130.4 1789.55  5240.4 1793.41
  5290.4 1796.14  5360.4 1803.77  5370.4 1805.34  5400.4 1808.25  5475.4 1812.65
#Mann=3,-1,0
  4512.5    0.07       0  5006.7    0.07       0  5014.0    0.07       0
Bank Sta=5006.7,5014
Exp/Cntr=0.3,0.1

Type RM Length L Ch R = 1,4148,131,131,131
BEGIN DESCRIPTION:
Mapping XS 7054bbc7
END DESCRIPTION:
XS GIS Cut Line= 3
      1492580.73      6910896.25      1492914.11      6910920.56
      1493400.16      6910875.43
#Sta/Elev= 30
  4473.9 1807.27  4518.3 1805.33  4528.3 1803.63  4548.4 1801.89  4565.0 1799.75
  4570.1 1799.73  4598.5 1796.38  4648.6 1793.07  4658.7 1793.09  4779.0 1788.30
  4887.2 1785.33  4939.6 1786.08  4949.7 1785.71  4969.7 1782.56  4976.1 1782.32
  4976.6 1781.82  4983.0 1781.82  4983.5 1782.32  5001.5 1783.52  5020.0 1783.60
  5090.3 1788.85  5100.3 1790.03  5105.8 1791.67  5120.4 1793.26  5170.6 1801.45
  5210.1 1806.17  5230.9 1807.72  5250.9 1808.40  5281.1 1807.98  5296.3 1806.98
#Mann=3,-1,0
  4473.9    0.07       0  4976.1    0.07       0  4983.5    0.07       0
Bank Sta=4976.1,4983.5
Exp/Cntr=0.3,0.1

Type RM Length L Ch R = 1,4017,341,341,341
BEGIN DESCRIPTION:
Mapping XS 7c7d597d
END DESCRIPTION:
XS GIS Cut Line= 4
      1492591.15      6910962.22      1492827.30      6911010.84
      1493289.11      6911028.20      1493371.19      6910956.38
#Sta/Elev= 30
  4446.8 1803.88  4453.3 1802.93  4491.6 1801.54  4553.9 1795.80  4583.5 1793.97
  4654.9 1791.92  4805.7 1785.64  4885.7 1783.89  4925.8 1784.63  4972.1 1781.40
  4972.6 1780.90  4979.0 1780.90  4979.5 1781.40  5005.8 1782.52  5011.2 1783.79
  5016.2 1783.47  5035.8 1787.65  5055.9 1789.41  5105.9 1796.31  5135.9 1798.99
  5154.6 1798.38  5161.2 1799.46  5168.8 1798.95  5175.5 1799.81  5183.0 1799.47
  5189.7 1800.44  5218.2 1800.41  5232.4 1801.07  5239.0 1802.06  5259.1 1802.32
#Mann=3,-1,0
  4446.8    0.07       0  4972.1    0.07       0  4979.5    0.07       0
Bank Sta=4972.1,4979.5
Exp/Cntr=0.3,0.1

Type RM Length L Ch R = 1,3676,276,276,276
BEGIN DESCRIPTION:
NC Unknown Stream 34 4.0
END DESCRIPTION:
XS GIS Cut Line= 3
      1492705.04      6911188.01      1493105.00      6911288.00
      1493304.98      6911337.99
#Sta/Elev= 30
  4587.2 1803.53  4597.5 1802.79  4618.1 1799.58  4638.7 1797.51  4651.6 1795.60
  4659.3 1793.65  4687.7 1789.42  4728.9 1785.19  4793.3 1781.55  4824.2 1782.47
  4857.7 1780.20  4875.8 1781.14  4899.0 1780.22  4917.0 1780.80  4940.2 1779.75
  4958.2 1780.19  4972.6 1779.08  4973.1 1778.58  4979.5 1778.58  4980.0 1779.08
  5040.7 1784.86  5063.9 1786.13  5105.1 1790.18  5133.5 1794.22  5141.2 1795.83
  5146.4 1795.90  5182.4 1801.92  5187.6 1801.71  5199.2 1804.06  5205.6 1804.64
#Mann=4,-1,0
  4587.2    0.07       0  4972.6    0.07       0  4980.0    0.07       0
  5199.2   0.035       0
Bank Sta=4972.6,4980
Exp/Cntr=0.3,0.1

Type RM Length L Ch R = 1,3400,428,428,428
BEGIN DESCRIPTION:
Mapping XS adf6b1f2
END DESCRIPTION:
XS GIS Cut Line= 3
      1492466.21      6911326.82      1492667.58      6911406.67
      1493481.82      6911489.83
#Sta/Elev= 30
  4537.3 1806.50  4584.5 1805.33  4603.2 1804.65  4636.8 1803.61  4685.5 1799.32
  4690.8 1799.99  4715.2 1796.94  4720.5 1798.08  4739.5 1795.92  4744.9 1796.64
  4797.1 1791.98  4939.3 1783.85  4972.5 1782.04  5002.6 1778.46  5006.7 1776.61
  5007.2 1776.11  5014.1 1776.61  5022.7 1778.47  5153.4 1779.49  5214.3 1781.59
  5303.8 1787.77  5308.8 1787.20  5403.2 1796.57  5408.3 1795.82  5434.9 1798.04
  5475.1 1799.13  5502.7 1802.67  5507.7 1801.93  5515.3 1803.46  5572.4 1807.39
#Mann=7,-1,0
  4537.3    0.07       0  4584.5   0.035       0  4603.2    0.07       0
  4797.1   0.035       0  4939.3    0.07       0  5006.7    0.07       0
  5014.1    0.07       0
Bank Sta=5006.7,5014.1
Exp/Cntr=0.3,0.1

Type RM Length L Ch R = 1,2972,289,289,289
BEGIN DESCRIPTION:
Mapping XS 80d8fe7b
END DESCRIPTION:
XS GIS Cut Line= 3
      1492546.03      6911580.28      1492803.00      6911660.14
      1493391.66      6911750.18
#Sta/Elev= 30
  4397.5 1803.36  4409.4 1803.26  4436.7 1800.73  4442.0 1801.17  4469.3 1798.02
  4474.5 1798.71  4507.1 1794.49  4512.3 1795.35  4539.6 1792.11  4670.1 1786.31
  4683.6 1785.05  4883.1 1778.89  4948.4 1777.41  5002.5 1774.65  5011.9 1775.23
  5018.9 1773.52  5019.4 1773.02  5026.4 1773.52  5042.9 1777.83  5063.2 1785.93
  5080.3 1788.80  5085.4 1788.55  5103.6 1792.54  5143.8 1799.03  5148.8 1798.35
  5154.2 1799.85  5212.2 1807.25  5217.3 1806.61  5245.2 1808.55  5262.1 1808.23
#Mann=5,-1,0
  4397.5    0.07       0  4683.6   0.035       0  4883.1    0.07       0
  5018.9    0.07       0  5026.4    0.07       0
Bank Sta=5018.9,5026.4
Exp/Cntr=0.3,0.1