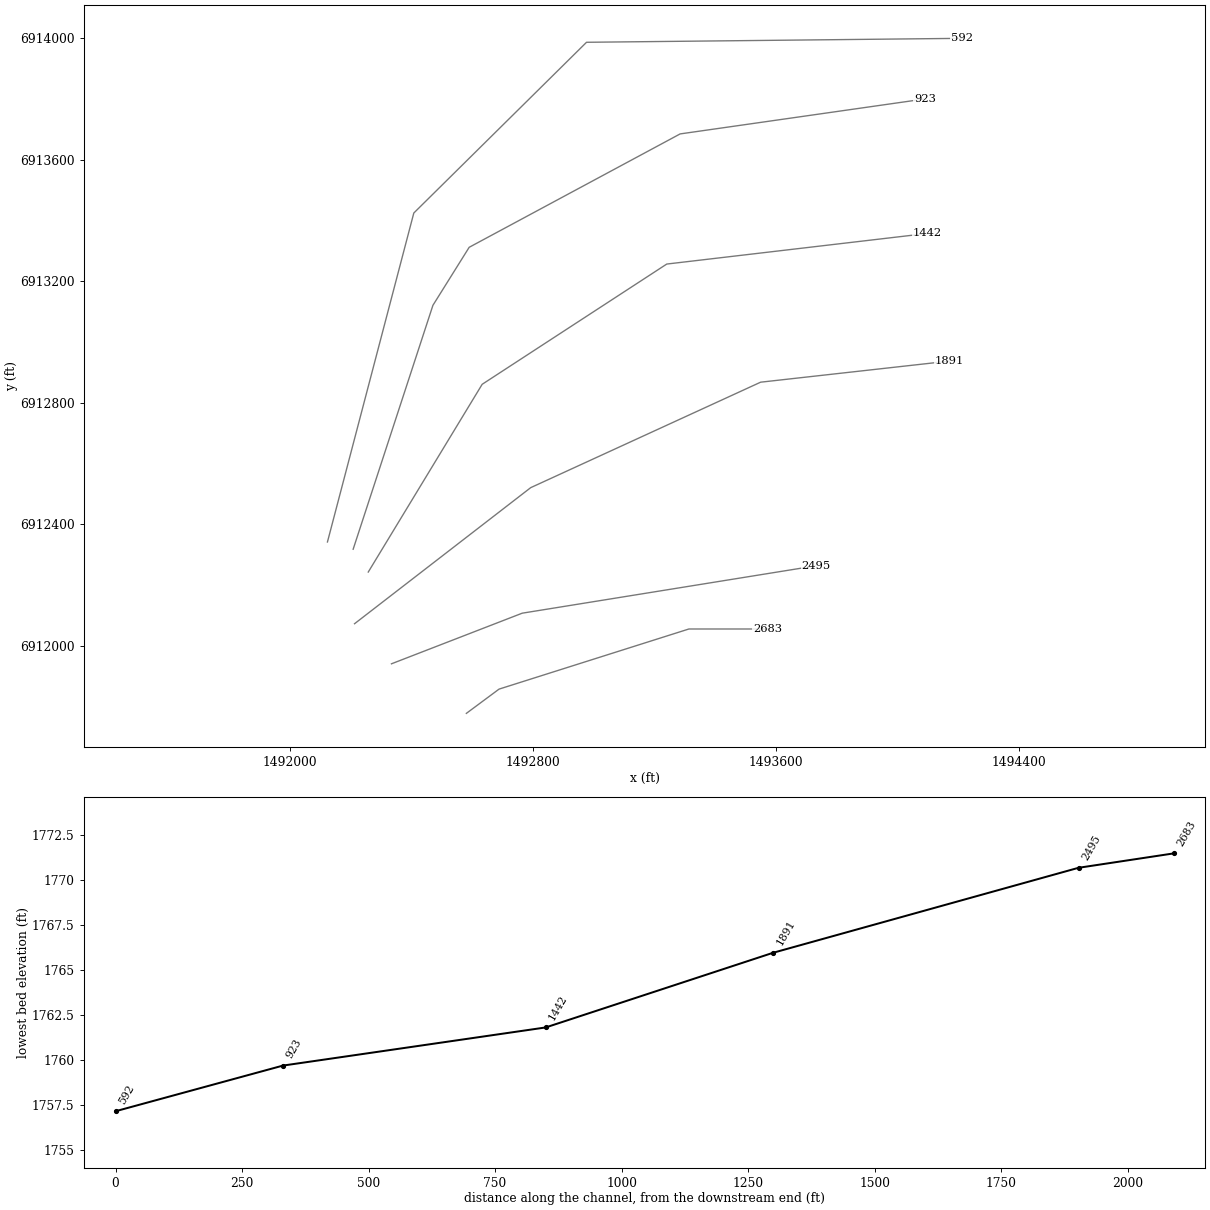
HEC-RAS study NC Unknown Stream 34.prj: NC Unknown Stream 34 Base Level Engineering

--- NC Unknown Stream 34.g01 (geometry) --- (continued)

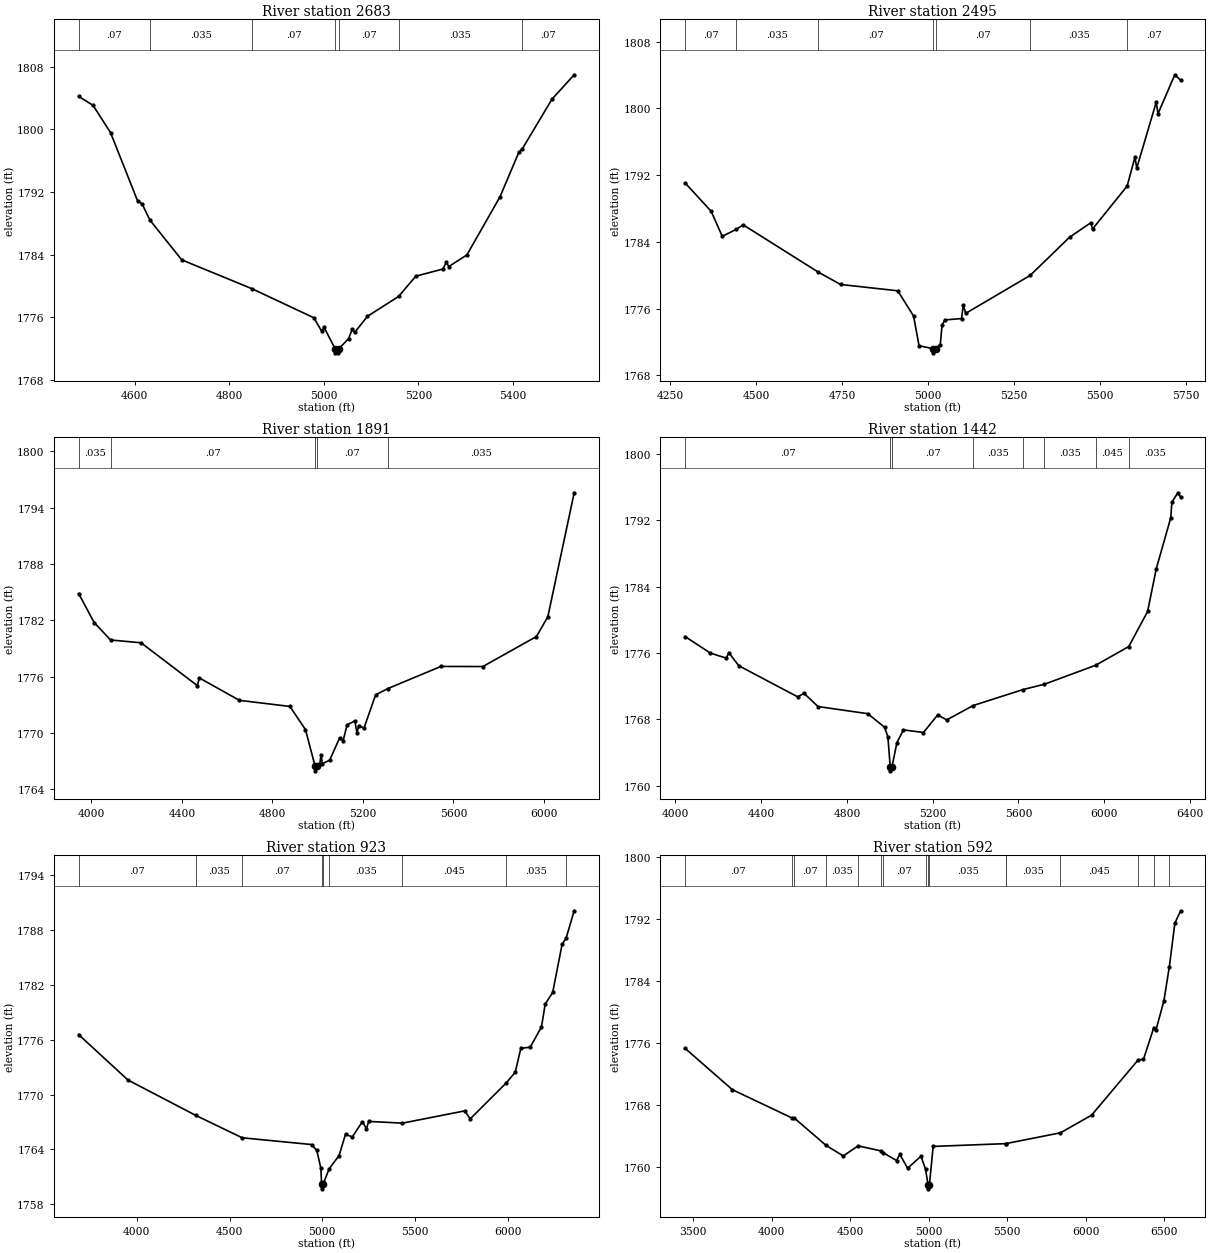
Type RM Length L Ch R = 1,2683,188,188,188
BEGIN DESCRIPTION:
Mapping XS c68cf82a
END DESCRIPTION:
XS GIS Cut Line= 4
      1492580.77      6911778.19      1492688.41      6911858.06
      1493313.41      6912055.98      1493571.89      6912055.98
#Sta/Elev= 30
  4481.4 1804.21  4512.0 1803.05  4548.9 1799.58  4606.0 1790.88  4615.4 1790.52
  4632.1 1788.43  4699.5 1783.35  4848.0 1779.67  4979.0 1775.96  4995.4 1774.25
  5000.7 1774.73  5024.0 1771.99  5024.5 1771.49  5031.0 1771.49  5031.5 1771.99
  5052.4 1773.31  5060.0 1774.48  5065.3 1774.10  5092.3 1776.15  5158.1 1778.68
  5194.5 1781.27  5251.7 1782.18  5259.1 1783.03  5264.3 1782.50  5302.6 1783.98
  5372.6 1791.39  5412.6 1797.09  5419.5 1797.48  5482.6 1803.85  5529.5 1806.96
#Mann=7,-1,0
  4481.4    0.07       0  4632.1   0.035       0  4848.0    0.07       0
  5024.0    0.07       0  5031.5    0.07       0  5158.1   0.035       0
  5419.5    0.07       0
Bank Sta=5024,5031.5
Exp/Cntr=0.3,0.1

Type RM Length L Ch R = 1,2495,604,604,604
BEGIN DESCRIPTION:
Mapping XS 2ad3650f
END DESCRIPTION:
XS GIS Cut Line= 3
      1492334.21      6911941.38      1492764.80      6912108.06
      1493731.78      6912264.03
#Sta/Elev= 30
  4293.5 1791.07  4369.4 1787.66  4401.6 1784.66  4442.2 1785.50  4462.4 1786.04
  4680.9 1780.37  4745.6 1778.89  4912.1 1778.13  4958.0 1775.10  4973.9 1771.54
  5015.0 1771.19  5015.5 1770.69  5022.5 1771.19  5035.7 1771.69  5040.8 1774.02
  5049.2 1774.64  5097.5 1774.80  5102.6 1776.39  5109.9 1775.43  5297.2 1779.98
  5411.5 1784.55  5473.3 1786.29  5478.4 1785.54  5579.1 1790.69  5601.9 1794.16
  5607.0 1792.84  5663.7 1800.75  5668.8 1799.37  5717.7 1804.04  5734.7 1803.39
#Mann=7,-1,0
  4293.5    0.07       0  4442.2   0.035       0  4680.9    0.07       0
  5015.0    0.07       0  5022.5    0.07       0  5297.2   0.035       0
  5579.1    0.07       0
Bank Sta=5015,5022.5
Exp/Cntr=0.3,0.1

Type RM Length L Ch R = 1,1891,449,449,449
BEGIN DESCRIPTION:
Mapping XS 03cb99a0
END DESCRIPTION:
XS GIS Cut Line= 4
      1492212.72      6912073.34      1492792.58      6912521.26
      1493549.53      6912868.48      1494170.56      6912937.87
#Sta/Elev= 30
  3943.5 1784.85  4012.1 1781.76  4084.7 1779.90  4219.5 1779.60  4468.6 1775.03
  4476.8 1775.86  4654.0 1773.47  4877.3 1772.82  4946.3 1770.35  4988.6 1766.46
  4989.1 1765.96  4996.1 1766.46  5008.9 1766.64  5015.3 1767.67  5020.8 1766.72
  5052.9 1767.09  5097.0 1769.45  5112.8 1769.18  5130.0 1770.86  5164.3 1771.28
  5174.0 1770.00  5181.8 1770.78  5204.8 1770.51  5256.2 1774.05  5308.9 1774.71
  5544.7 1777.08  5730.3 1777.07  5967.3 1780.27  6017.6 1782.38  6133.9 1795.58
#Mann=5,-1,0
  3943.5   0.035       0  4084.7    0.07       0  4988.6    0.07       0
  4996.1    0.07       0  5308.9   0.035       0
Bank Sta=4988.6,4996.1
Exp/Cntr=0.3,0.1

Type RM Length L Ch R = 1,1442,519,519,519
BEGIN DESCRIPTION:
Mapping XS af525227
END DESCRIPTION:
XS GIS Cut Line= 4
      1492257.86      6912243.48      1492632.86      6912861.53
      1493240.50      6913257.37      1494098.09      6913358.06
#Sta/Elev= 30
  4045.1 1778.00  4163.2 1776.00  4236.8 1775.40  4249.2 1776.06  4295.0 1774.49
  4570.3 1770.73  4600.1 1771.15  4665.3 1769.56  4897.4 1768.70  4975.8 1767.06
  4991.0 1765.91  5002.0 1762.31  5002.5 1761.81  5010.2 1762.31  5033.1 1765.19
  5063.4 1766.75  5156.9 1766.43  5223.4 1768.55  5265.6 1767.95  5388.6 1769.68
  5621.9 1771.61  5721.3 1772.25  5959.6 1774.53  6114.7 1776.79  6202.6 1781.02
  6242.8 1786.15  6310.8 1792.34  6315.8 1794.19  6343.5 1795.33  6356.7 1794.79
#Mann=8,-1,0
  4045.1    0.07       0  5002.0    0.07       0  5010.2    0.07       0
  5388.6   0.035       0  5621.9   0.045       0  5721.3   0.035       0
  5959.6   0.045       0  6114.7   0.035       0
Bank Sta=5002,5010.2
Exp/Cntr=0.3,0.1

Type RM Length L Ch R = 1,923,331,331,331
BEGIN DESCRIPTION:
Mapping XS 9c490b79
END DESCRIPTION:
XS GIS Cut Line= 5
      1492208.12      6912318.59      1492470.71      6913121.55
      1492590.07      6913312.53      1493284.52      6913685.79
      1494089.63      6913800.81
#Sta/Elev= 30
  3686.1 1776.55  3951.6 1771.59  4318.3 1767.71  4567.9 1765.27  4942.4 1764.53
  4970.0 1763.89  4991.9 1761.97  4996.0 1760.19  4996.5 1759.69  5004.3 1760.19
  5036.5 1761.87  5090.2 1763.33  5125.0 1765.65  5161.6 1765.36  5215.8 1767.03
  5237.9 1766.25  5249.9 1767.06  5432.2 1766.87  5767.2 1768.21  5797.5 1767.34
  5990.8 1771.25  6040.0 1772.43  6070.3 1775.05  6120.8 1775.17  6181.4 1777.38
  6201.6 1779.88  6242.0 1781.16  6292.5 1786.40  6314.4 1787.10  6357.8 1790.08
#Mann=9,-1,0
  3686.1    0.07       0  4318.3   0.035       0  4567.9    0.07       0
  4996.0    0.07       0  5004.3    0.07       0  5036.5   0.035       0
  5432.2   0.045       0  5990.8   0.035       0  6314.4    0.07       0
Bank Sta=4996,5004.3
Exp/Cntr=0.3,0.1

Type RM Length L Ch R = 1,592,0,0,0
BEGIN DESCRIPTION:
NC Unknown Stream 34 1.0
END DESCRIPTION:
XS GIS Cut Line= 4
      1492123.48      6912342.43      1492407.78      6913425.37
      1492976.36      6913987.44      1494211.66      6914000.44
#Sta/Elev= 30
  3448.6 1775.30  3749.5 1769.96  4126.4 1766.33  4142.2 1766.32  4346.1 1762.76
  4455.4 1761.40  4550.0 1762.70  4698.6 1762.04  4710.1 1761.81  4794.4 1760.81
  4815.6 1761.60  4865.1 1759.81  4950.0 1761.36  4979.2 1759.70  4995.4 1757.65
  4995.9 1757.15  5003.7 1757.65  5027.8 1762.63  5491.0 1762.99  5492.6 1763.00
  5838.3 1764.39  6036.4 1766.67  6333.3 1773.82  6366.4 1773.87  6432.3 1777.98
  6446.4 1777.69  6496.4 1781.42  6531.3 1785.86  6566.4 1791.48  6603.1 1793.07
#Mann=16,-1,0
  3448.6    0.07       0  4126.4   0.035       0  4142.2    0.07       0
  4346.1   0.035       0  4550.0    0.07       0  4698.6   0.035       0
  4710.1    0.07       0  4979.2   0.035       0  4995.4   0.035       0
  5003.7   0.035       0  5491.0   0.045       0  5492.6   0.035       0
  5838.3   0.045       0  6333.3   0.035       0  6432.3    0.07       0
  6531.3   0.035       0
Bank Sta=4995.4,5003.7
Exp/Cntr=0.3,0.1

Chan Stop Cuts=-1