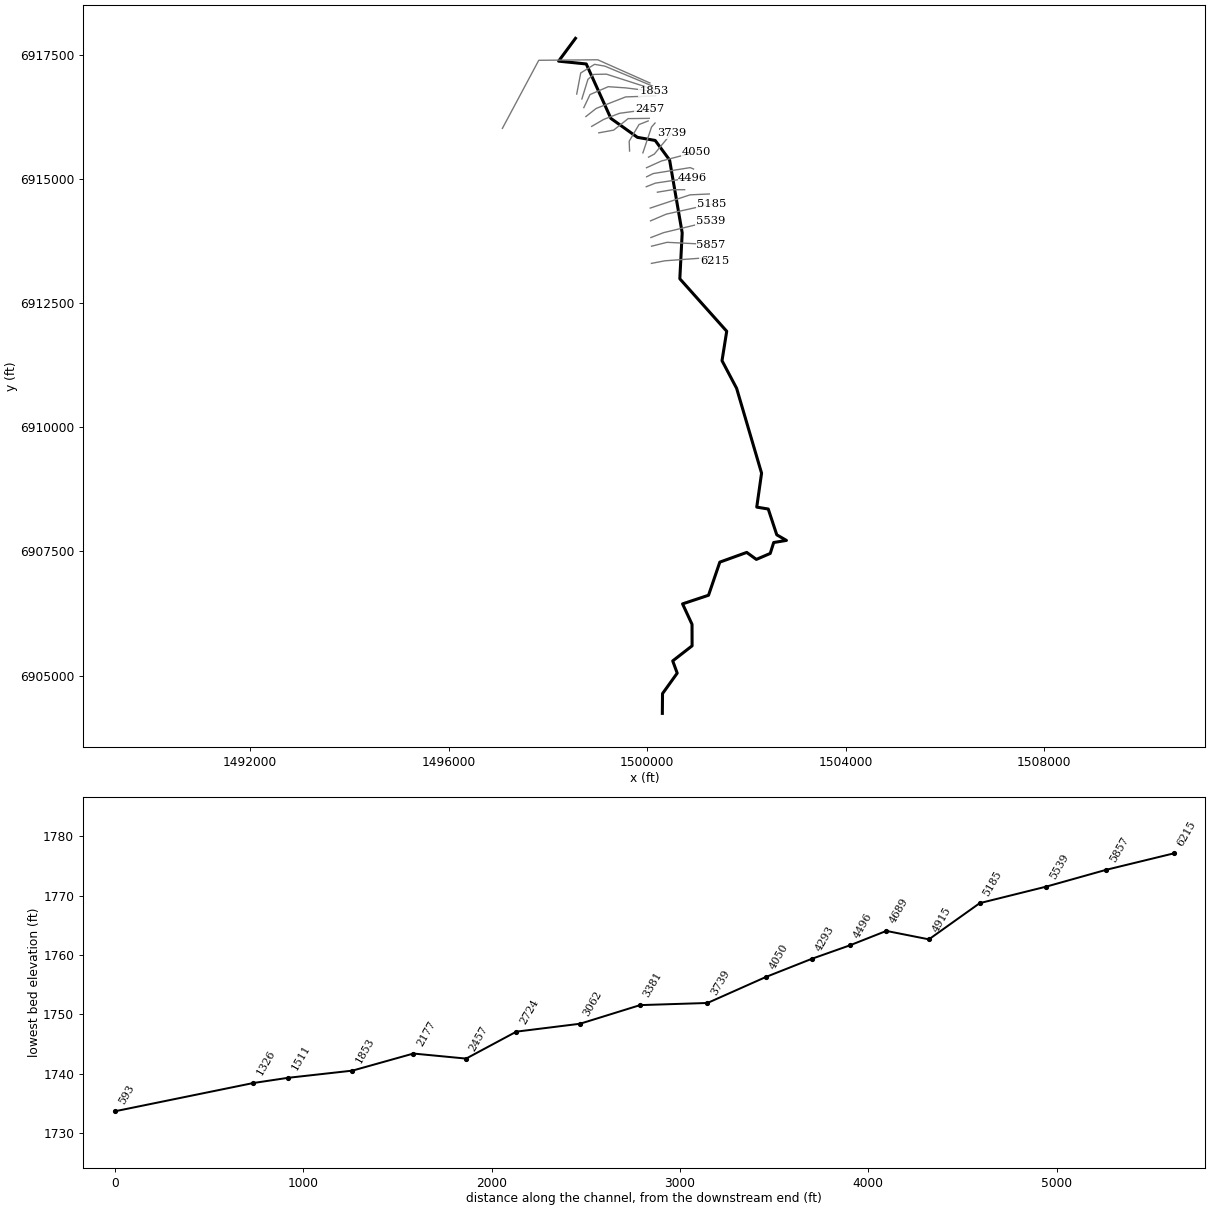
--- NC Unknown Stream 35.prj (project) ---

Proj Title=NC Unknown Stream 35 Base Level Engineering
Current Plan=p01
Default Exp/Contr=0.3,0.1
English Units
Geom File=g01
Flow File=f01
Plan File=p01
BEGIN DESCRIPTION:
NC Unknown Stream 35
END DESCRIPTION:

--- NC Unknown Stream 35.p01 (plan) ---

Plan Title=Multiple Run
Short Identifier=Multiple
Geom File=g01
Flow File=f01
Subcritical Flow
K Sum by GR= 0
Std Step Tol= 0.01
Critical Tol= 0.01
Num of Std Step Trials= 20
Max Error Tol= 0.3
Flow Tol Ratio= 0.001
Split Flow NTrial= 30
Split Flow Tol= 0.02
Split Flow Ratio= 0.02
Log Output Level= 0
Friction Slope Method= 1
Unsteady Friction Slope Method= 2
Unsteady Bridges Friction Slope Method= 1
Parabolic Critical Depth
Global Vel Dist=  1 , 1 , 1
Global Log Level= 0
CheckData=True
Encroach Param= -1, 0, 0, 0
BEGIN DESCRIPTION:
Multiple Run
END DESCRIPTION:

--- NC Unknown Stream 35.f01 (steady flow) ---

Flow Title=Multiple
Number of Profiles=7
Profile Names=10-year,25-year,50-year,1pct_min,100-year,1pct_plu,500-year
River Rch & RM= NC Unknown Strea,Reach-1,6215
     394     551     679     416     830    1656    1254
River Rch & RM= NC Unknown Strea,Reach-1,593
     554     787     983     609    1215    2424    1877
Boundary for River Rch & Prof#=NC Unknown Strea,Reach-1,1
Up Type=0
Dn Type=3
Dn Slope=0.001
Boundary for River Rch & Prof#=NC Unknown Strea,Reach-1,2
Up Type=0
Dn Type=3
Dn Slope=0.001
Boundary for River Rch & Prof#=NC Unknown Strea,Reach-1,3
Up Type=0
Dn Type=3
Dn Slope=0.001
Boundary for River Rch & Prof#=NC Unknown Strea,Reach-1,4
Up Type=0
Dn Type=3
Dn Slope=0.001
Boundary for River Rch & Prof#=NC Unknown Strea,Reach-1,5
Up Type=0
Dn Type=3
Dn Slope=0.001
Boundary for River Rch & Prof#=NC Unknown Strea,Reach-1,6
Up Type=0
Dn Type=3
Dn Slope=0.001
Boundary for River Rch & Prof#=NC Unknown Strea,Reach-1,7
Up Type=0
Dn Type=3
Dn Slope=0.001

--- NC Unknown Stream 35.g01 (geometry) ---

Geom Title=Existing Conditions

River Reach=NC Unknown Strea,Reach-1
Reach XY= 30
      1500305.00      6904238.00      1500308.74      6904636.44
      1500604.47      6905048.47      1500514.01      6905295.02
      1500904.40      6905598.62      1500903.02      6906032.11
      1500712.45      6906444.07      1501235.65      6906617.95
      1501462.97      6907285.07      1502005.22      6907481.00
      1502199.03      6907340.14      1502478.83      6907460.31
      1502548.48      6907680.33      1502805.17      6907722.66
      1502610.41      6907835.29      1502438.73      6908355.23
      1502207.04      6908393.45      1502304.25      6909077.32
      1501801.46      6910786.54      1501507.26      6911343.94
      1501601.91      6911936.36      1500657.26      6912993.94
      1500704.95      6913917.96      1500451.25      6915386.45
      1500161.50      6915780.27      1499802.55      6915843.47
      1499268.37      6916224.68      1498772.14      6917321.73
      1498214.91      6917378.26      1498555.00      6917838.00

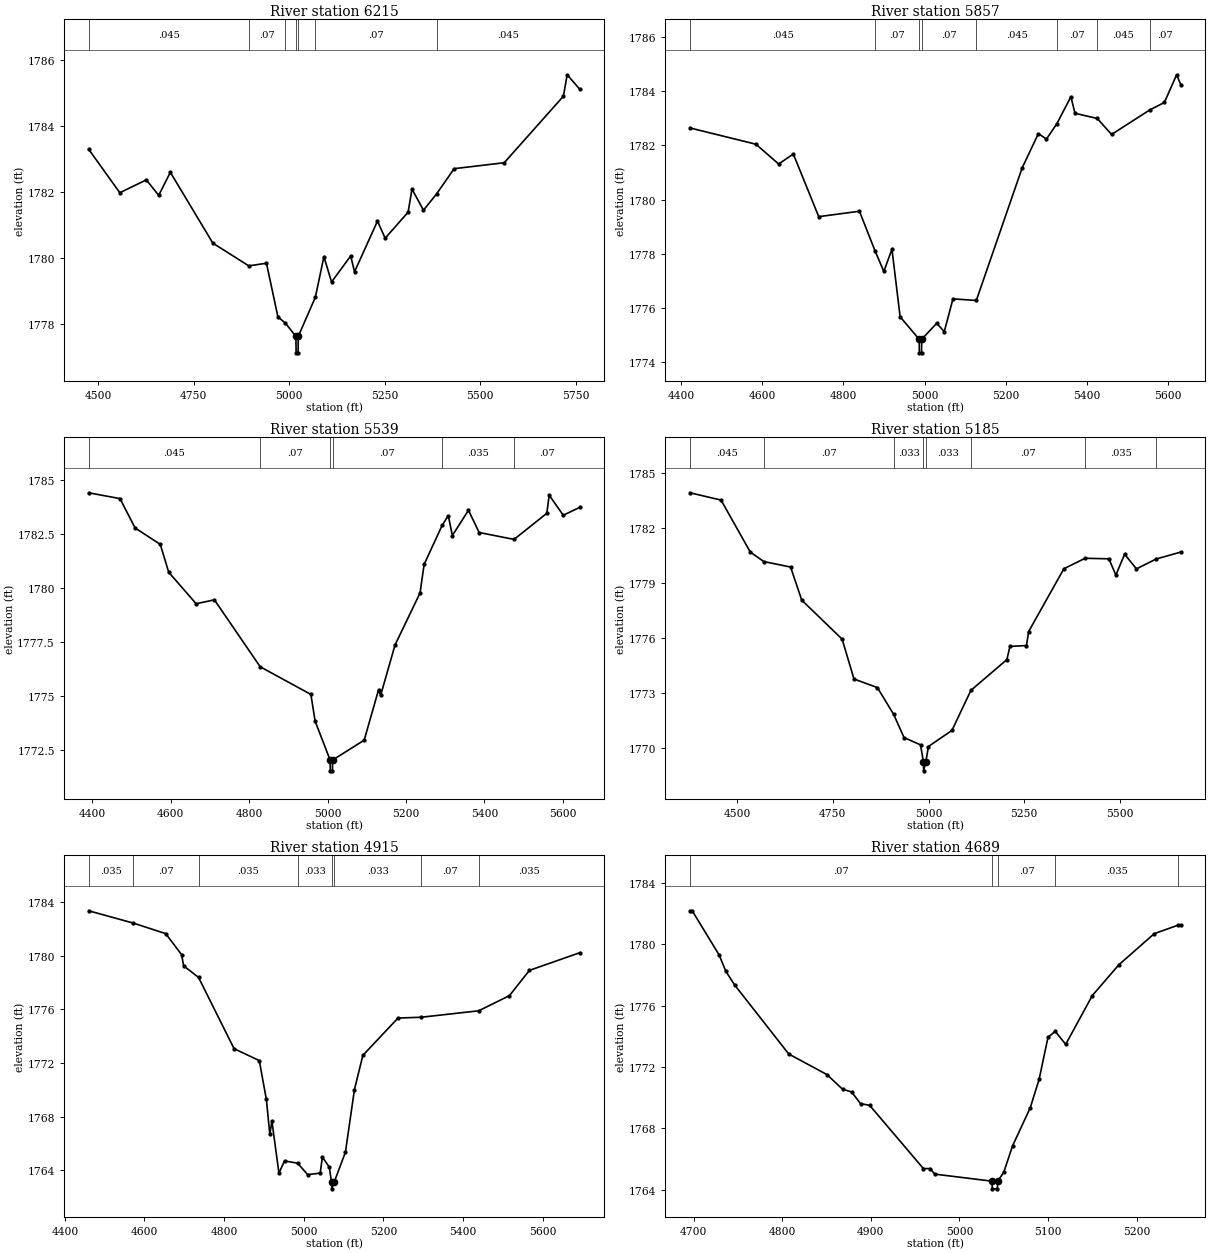
Type RM Length L Ch R = 1,6215,358,358,358
BEGIN DESCRIPTION:
Mapping XS de5f2f18
END DESCRIPTION:
XS GIS Cut Line= 4
      1500084.91      6913303.88      1500355.77      6913355.96
      1501137.02      6913413.25      1501355.78      6913355.96
#Sta/Elev= 30
  4474.7 1783.29  4556.3 1781.97  4625.7 1782.36  4658.1 1781.89  4688.6 1782.59
  4799.9 1780.44  4894.0 1779.75  4940.3 1779.83  4970.3 1778.20  4989.2 1778.02
  5017.4 1777.61  5017.9 1777.11  5023.1 1777.11  5023.6 1777.61  5068.4 1778.80
  5090.7 1780.03  5110.7 1779.26  5160.8 1780.05  5170.9 1779.57  5231.0 1781.11
  5251.1 1780.59  5311.2 1781.38  5321.3 1782.08  5351.4 1781.44  5385.5 1781.93
  5431.6 1782.70  5562.8 1782.88  5717.8 1784.90  5727.6 1785.55  5760.0 1785.12
#Mann=7,-1,0
  4474.7   0.045       0  4894.0    0.07       0  4989.2   0.045       0
  5017.4   0.045       0  5023.6   0.045       0  5068.4    0.07       0
  5385.5   0.045       0
Bank Sta=5017.4,5023.6
Exp/Cntr=0.3,0.1

Type RM Length L Ch R = 1,5857,318,318,318
BEGIN DESCRIPTION:
Mapping XS 03dc41e2
END DESCRIPTION:
XS GIS Cut Line= 3
      1500087.50      6913650.22      1500400.04      6913728.36
      1501285.47      6913684.09
#Sta/Elev= 30
  4422.3 1782.64  4584.7 1782.04  4640.6 1781.31  4676.7 1781.68  4739.3 1779.37
  4839.5 1779.57  4878.2 1778.10  4899.6 1777.35  4919.6 1778.17  4939.7 1775.68
  4986.6 1774.85  4987.1 1774.35  4992.4 1774.35  4992.9 1774.85  5029.8 1775.44
  5048.4 1775.13  5069.8 1776.34  5127.3 1776.28  5240.0 1781.16  5280.1 1782.43
  5300.1 1782.23  5325.8 1782.80  5360.2 1783.79  5370.2 1783.18  5425.1 1782.99
  5460.3 1782.40  5554.0 1783.30  5590.5 1783.58  5620.5 1784.60  5631.0 1784.23
#Mann=8,-1,0
  4422.3   0.045       0  4878.2    0.07       0  4986.6    0.07       0
  4992.9    0.07       0  5127.3   0.045       0  5325.8    0.07       0
  5425.1   0.045       0  5554.0    0.07       0
Bank Sta=4986.6,4992.9
Exp/Cntr=0.3,0.1

Type RM Length L Ch R = 1,5539,354,354,354
BEGIN DESCRIPTION:
Mapping XS 12e4bf6f
END DESCRIPTION:
XS GIS Cut Line= 3
      1500074.48      6913824.70      1500332.33      6913923.67
      1501280.14      6914152.81
#Sta/Elev= 30
  4391.1 1784.40  4471.0 1784.13  4509.5 1782.77  4573.7 1782.01  4595.2 1780.72
  4665.1 1779.26  4711.7 1779.44  4828.4 1776.34  4957.6 1775.06  4968.4 1773.82
  5006.6 1772.02  5007.1 1771.52  5012.5 1771.52  5013.0 1772.02  5093.5 1772.94
  5130.2 1775.28  5135.3 1775.01  5172.1 1777.35  5235.9 1779.76  5246.2 1781.08
  5292.4 1782.90  5307.9 1783.34  5318.2 1782.42  5359.3 1783.59  5386.5 1782.56
  5475.5 1782.24  5559.0 1783.45  5565.1 1784.29  5600.9 1783.36  5642.4 1783.72
#Mann=6,-1,0
  4391.1   0.045       0  4828.4    0.07       0  5006.6    0.07       0
  5013.0    0.07       0  5292.4   0.035       0  5475.5    0.07       0
Bank Sta=5006.6,5013
Exp/Cntr=0.3,0.1

Type RM Length L Ch R = 1,5185,270,270,270
BEGIN DESCRIPTION:
Mapping XS 4f388627
END DESCRIPTION:
XS GIS Cut Line= 3
      1500066.72      6914160.66      1500384.41      6914296.07
      1501298.47      6914499.19
#Sta/Elev= 30
  4377.1 1783.93  4458.2 1783.53  4534.5 1780.69  4569.8 1780.17  4639.8 1779.87
  4668.9 1778.06  4774.3 1775.93  4805.3 1773.75  4866.5 1773.28  4909.0 1771.81
  4935.9 1770.55  4979.1 1770.15  4986.5 1769.23  4987.0 1768.73  4993.0 1769.23
  4999.6 1770.06  5061.1 1770.94  5110.6 1773.13  5204.5 1774.81  5212.5 1775.53
  5255.7 1775.58  5261.2 1776.34  5353.4 1779.78  5408.9 1780.35  5470.9 1780.32
  5489.1 1779.43  5511.8 1780.57  5542.9 1779.77  5594.2 1780.31  5658.8 1780.69
#Mann=8,-1,0
  4377.1   0.045       0  4569.8    0.07       0  4909.0   0.033       0
  4986.5   0.033       0  4993.0   0.033       0  5110.6    0.07       0
  5408.9   0.035       0  5594.2    0.07       0
Bank Sta=4986.5,4993
Exp/Cntr=0.3,0.1

Type RM Length L Ch R = 1,4915,226,226,226
BEGIN DESCRIPTION:
NC Unknown Stream 35 9.0
END DESCRIPTION:
XS GIS Cut Line= 3
      1500061.50      6914418.46      1500863.33      6914684.88
      1501250.81      6914702.28
#Sta/Elev= 30
  4459.8 1783.34  4571.1 1782.43  4653.2 1781.64  4693.1 1780.08  4698.4 1779.24
  4735.7 1778.38  4825.0 1773.07  4888.4 1772.18  4906.1 1769.29  4914.8 1766.69
  4920.0 1767.68  4937.7 1763.80  4951.7 1764.71  4984.6 1764.54  5009.8 1763.69
  5041.4 1763.80  5046.7 1765.00  5064.1 1764.25  5069.8 1763.13  5070.3 1762.63
  5076.4 1763.13  5104.7 1765.36  5127.3 1770.02  5148.4 1772.57  5236.7 1775.35
  5294.7 1775.41  5439.3 1775.89  5516.6 1777.02  5566.7 1778.90  5692.6 1780.21
#Mann=8,-1,0
  4459.8   0.035       0  4571.1    0.07       0  4735.7   0.035       0
  4984.6   0.033       0  5069.8   0.033       0  5076.4   0.033       0
  5294.7    0.07       0  5439.3   0.035       0
Bank Sta=5069.8,5076.4
Exp/Cntr=0.3,0.1

Type RM Length L Ch R = 1,4689,193,193,193
BEGIN DESCRIPTION:
NC Unknown Stream 35 8.0
END DESCRIPTION:
XS GIS Cut Line= 3
      1500205.04      6914738.01      1500505.00      6914788.00
      1500755.00      6914788.00
#Sta/Elev= 30
  4695.9 1782.18  4698.4 1782.18  4728.8 1779.30  4736.4 1778.23  4746.6 1777.32
  4807.4 1772.84  4850.5 1771.50  4868.2 1770.54  4878.3 1770.37  4888.5 1769.60
  4898.6 1769.50  4959.4 1765.37  4967.1 1765.37  4972.1 1765.01  5036.7 1764.55
  5037.2 1764.05  5042.8 1764.05  5043.3 1764.55  5050.0 1765.12  5060.0 1766.85
  5080.0 1769.34  5090.0 1771.19  5100.0 1773.93  5108.2 1774.32  5120.0 1773.47
  5150.0 1776.65  5180.0 1778.66  5220.0 1780.69  5246.8 1781.24  5250.0 1781.25
#Mann=5,-1,0
  4695.9    0.07       0  5036.7    0.07       0  5043.3    0.07       0
  5108.2   0.035       0  5246.8    0.07       0
Bank Sta=5036.7,5043.3
Exp/Cntr=0.3,0.1

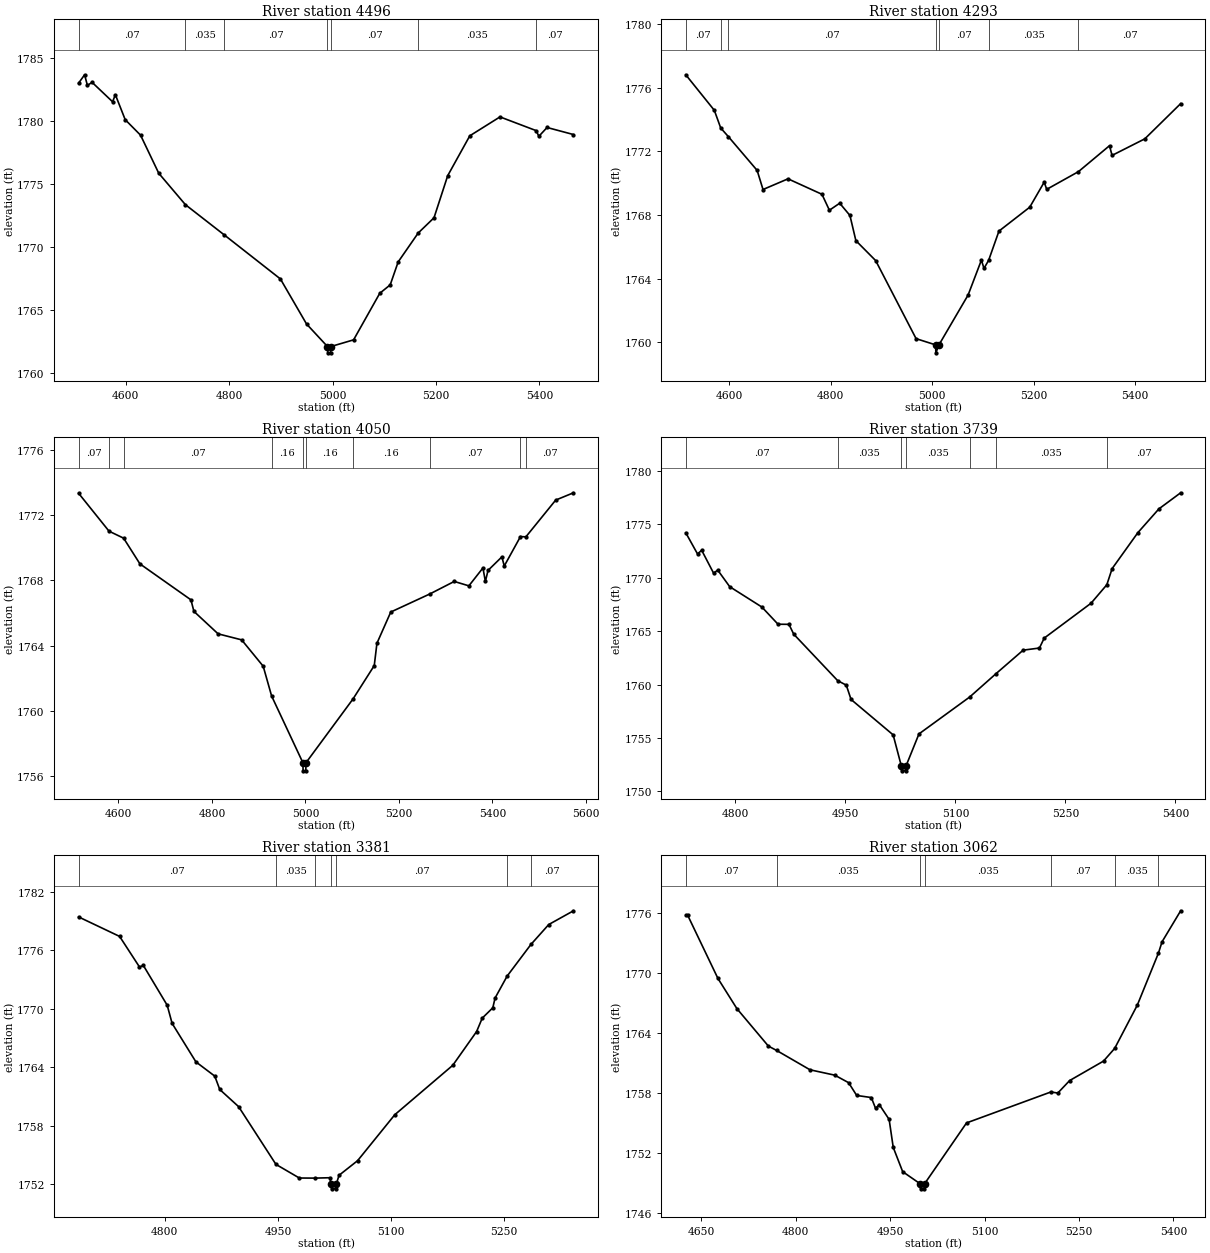
Type RM Length L Ch R = 1,4496,203,203,203
BEGIN DESCRIPTION:
Mapping XS 7da92d6d
END DESCRIPTION:
XS GIS Cut Line= 3
      1499980.76      6914848.15      1500165.66      6914921.07
      1500915.49      6915033.02
#Sta/Elev= 30
  4508.9 1783.02  4520.5 1783.68  4525.9 1782.84  4535.0 1783.08  4574.6 1781.54
  4580.0 1782.10  4599.0 1780.12  4628.7 1778.89  4663.9 1775.87  4715.4 1773.38
  4790.9 1770.97  4899.1 1767.49  4949.6 1763.92  4990.1 1762.13  4990.6 1761.63
  4996.2 1761.63  4996.7 1762.13  5040.6 1762.66  5091.2 1766.35  5111.4 1767.02
  5126.8 1768.84  5165.5 1771.13  5196.1 1772.34  5222.6 1775.68  5265.3 1778.84
  5323.7 1780.34  5393.7 1779.25  5398.8 1778.80  5414.7 1779.50  5465.8 1778.94
#Mann=7,-1,0
  4508.9    0.07       0  4715.4   0.035       0  4790.9    0.07       0
  4990.1    0.07       0  4996.7    0.07       0  5165.5   0.035       0
  5393.7    0.07       0
Bank Sta=4990.1,4996.7
Exp/Cntr=0.3,0.1

Type RM Length L Ch R = 1,4293,243,243,243
BEGIN DESCRIPTION:
Mapping XS d6a42ad3
END DESCRIPTION:
XS GIS Cut Line= 4
      1499988.59      6915048.67      1500121.39      6915113.78
      1500866.18      6915233.57      1500933.91      6915204.92
#Sta/Elev= 30
  4514.2 1776.80  4570.5 1774.57  4583.1 1773.46  4598.4 1772.91  4654.9 1770.80
  4666.5 1769.60  4715.8 1770.27  4782.7 1769.30  4797.4 1768.30  4817.7 1768.74
  4837.9 1767.97  4849.6 1766.39  4888.6 1765.14  4968.3 1760.24  5006.8 1759.85
  5007.3 1759.35  5013.4 1759.85  5070.9 1762.98  5097.1 1765.17  5102.2 1764.65
  5111.4 1765.16  5131.7 1766.99  5192.4 1768.49  5220.9 1770.06  5225.9 1769.61
  5288.4 1770.72  5349.7 1772.35  5354.7 1771.74  5419.3 1772.78  5490.0 1774.99
#Mann=7,-1,0
  4514.2    0.07       0  4583.1   0.035       0  4598.4    0.07       0
  5006.8    0.07       0  5013.4    0.07       0  5111.4   0.035       0
  5288.4    0.07       0
Bank Sta=5006.8,5013.4
Exp/Cntr=0.3,0.1

Type RM Length L Ch R = 1,4050,311,311,311
BEGIN DESCRIPTION:
Mapping XS 603a71f5
END DESCRIPTION:
XS GIS Cut Line= 3
      1499986.01      6915230.98      1500285.46      6915366.38
      1500991.85      6915550.77
#Sta/Elev= 30
  4514.8 1773.36  4579.9 1771.03  4611.1 1770.60  4646.0 1769.02  4755.1 1766.81
  4761.5 1766.10  4813.2 1764.72  4863.6 1764.35  4909.7 1762.73  4927.7 1760.90
  4994.6 1756.80  4995.1 1756.30  5000.8 1756.30  5001.3 1756.80  5101.9 1760.72
  5147.3 1762.77  5153.0 1764.14  5182.6 1766.06  5266.1 1767.17  5318.4 1767.94
  5349.7 1767.67  5379.8 1768.77  5385.0 1767.94  5390.7 1768.62  5420.3 1769.45
  5425.4 1768.89  5460.1 1770.70  5471.6 1770.68  5535.4 1772.94  5573.5 1773.39
#Mann=10,-1,0
  4514.8    0.07       0  4579.9   0.035       0  4611.1    0.07       0
  4927.7    0.16       0  4994.6    0.07       0  5001.3    0.16       0
  5101.9    0.16       0  5266.1    0.07       0  5460.1    0.16       0
  5471.6    0.07       0
Bank Sta=4994.6,5001.3
Exp/Cntr=0.3,0.1

Type RM Length L Ch R = 1,3739,358,358,358
BEGIN DESCRIPTION:
Mapping XS e86585c2
END DESCRIPTION:
XS GIS Cut Line= 3
      1500027.68      6915444.52      1500144.83      6915507.00
      1500488.55      6915926.24
#Sta/Elev= 30
  4732.2 1774.22  4748.2 1772.24  4753.9 1772.58  4770.1 1770.44  4775.8 1770.72
  4792.1 1769.17  4836.0 1767.26  4858.0 1765.65  4872.9 1765.64  4879.4 1764.72
  4939.4 1760.36  4951.1 1759.94  4957.6 1758.60  5015.0 1755.28  5026.0 1752.41
  5026.5 1751.91  5032.3 1751.91  5032.8 1752.41  5050.2 1755.37  5119.4 1758.83
  5155.0 1761.00  5192.3 1763.22  5214.5 1763.42  5221.0 1764.35  5284.9 1767.62
  5306.4 1769.35  5313.6 1770.86  5348.7 1774.23  5377.4 1776.46  5407.1 1777.97
#Mann=7,-1,0
  4732.2    0.07       0  4939.4   0.035       0  5026.0   0.035       0
  5032.8   0.035       0  5119.4    0.07       0  5155.0   0.035       0
  5306.4    0.07       0
Bank Sta=5026,5032.8
Exp/Cntr=0.3,0.1

Type RM Length L Ch R = 1,3381,319,319,319
BEGIN DESCRIPTION:
Mapping XS 051c7dae
END DESCRIPTION:
XS GIS Cut Line= 3
      1499913.06      6915530.45      1500087.54      6916051.28
      1500157.83      6916131.98
#Sta/Elev= 30
  4685.7 1779.44  4740.1 1777.44  4766.4 1774.31  4771.6 1774.46  4803.2 1770.38
  4809.7 1768.52  4841.3 1764.57  4866.3 1763.11  4872.9 1761.74  4897.9 1759.98
  4947.4 1754.06  4978.4 1752.66  4999.3 1752.65  5018.8 1752.69  5020.7 1752.05
  5021.2 1751.55  5027.0 1751.55  5027.5 1752.05  5031.1 1752.94  5055.7 1754.44
  5105.0 1759.15  5181.9 1764.22  5213.5 1767.68  5221.0 1769.06  5235.0 1770.12
  5238.0 1771.12  5254.0 1773.37  5285.6 1776.62  5309.2 1778.66  5342.0 1780.07
#Mann=7,-1,0
  4685.7    0.07       0  4947.4   0.035       0  4999.3    0.07       0
  5020.7    0.07       0  5027.5    0.07       0  5254.0   0.035       0
  5285.6    0.07       0
Bank Sta=5020.7,5027.5
Exp/Cntr=0.3,0.1

Type RM Length L Ch R = 1,3062,338,338,338
BEGIN DESCRIPTION:
Mapping XS 9ebeac33
END DESCRIPTION:
XS GIS Cut Line= 4
      1499644.83      6915566.90      1499637.02      6915764.82
      1499834.93      6916100.75      1500018.96      6916173.33
#Sta/Elev= 30
  4625.6 1775.79  4628.7 1775.79  4676.7 1769.47  4706.8 1766.45  4756.8 1762.70
  4769.7 1762.27  4822.8 1760.33  4862.2 1759.79  4884.1 1759.04  4897.0 1757.76
  4920.2 1757.55  4927.0 1756.46  4932.8 1756.85  4948.5 1755.36  4955.0 1752.56
  4970.0 1750.13  4997.9 1748.91  4998.4 1748.41  5004.2 1748.41  5004.7 1748.91
  5071.4 1755.01  5205.4 1758.11  5216.3 1758.00  5235.1 1759.25  5288.9 1761.20
  5306.6 1762.47  5342.6 1766.81  5376.1 1772.01  5381.8 1773.14  5411.4 1776.25
#Mann=7,-1,0
  4625.6    0.07       0  4769.7   0.035       0  4997.9   0.035       0
  5004.7   0.035       0  5205.4    0.07       0  5306.6   0.035       0
  5376.1    0.07       0
Bank Sta=4997.9,5004.7
Exp/Cntr=0.3,0.1

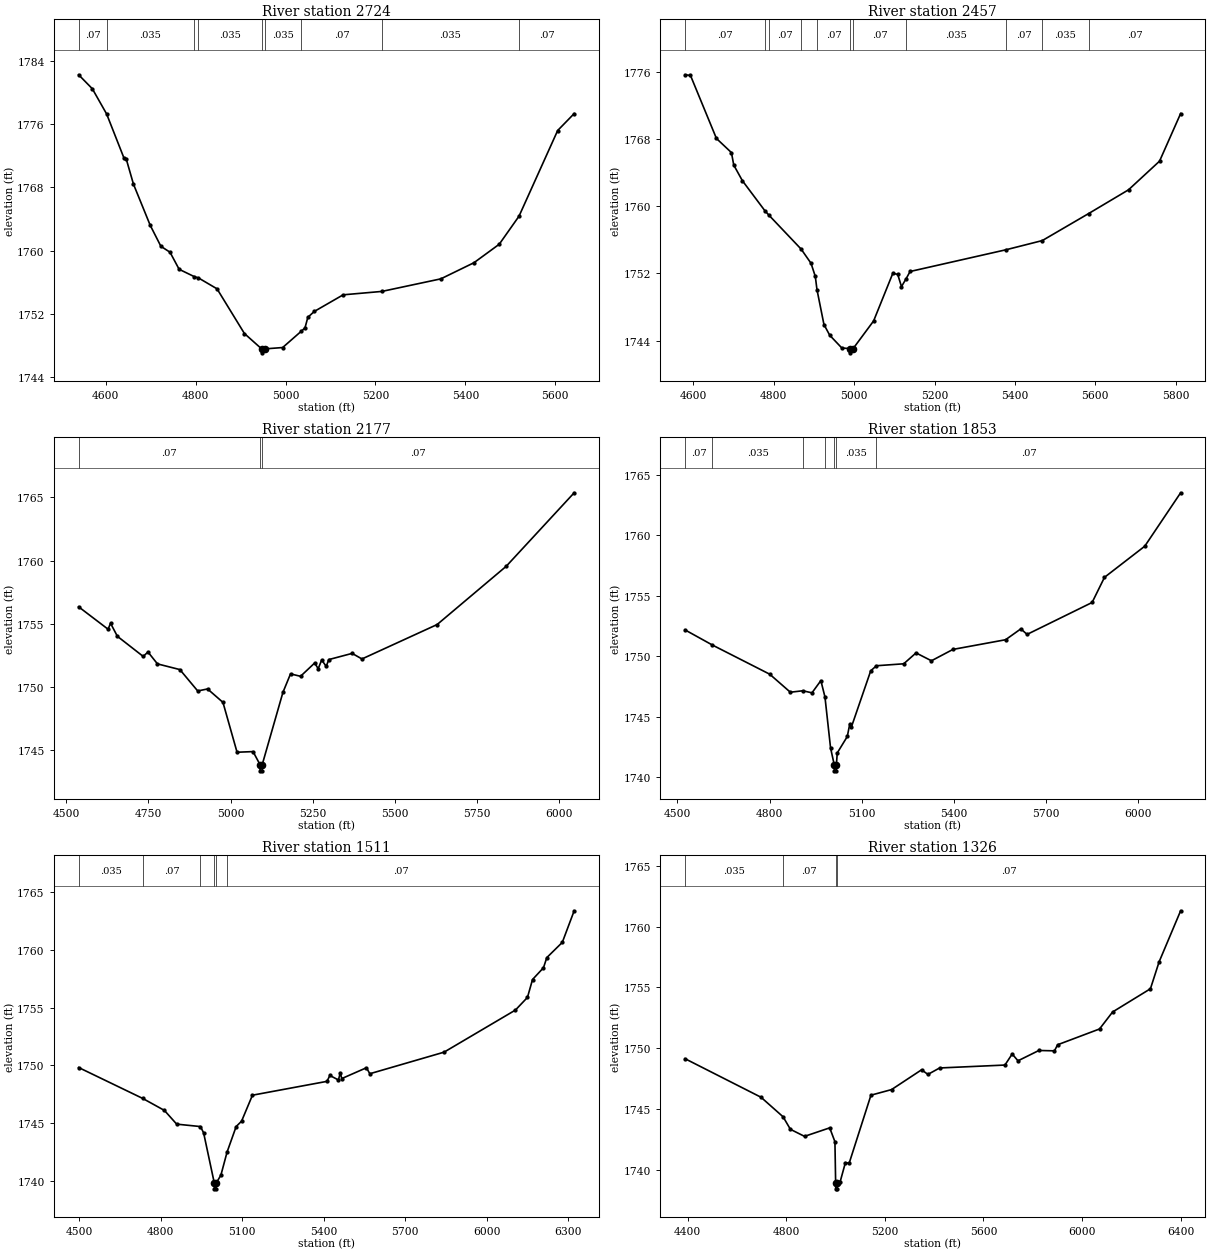
Type RM Length L Ch R = 1,2724,267,267,267
BEGIN DESCRIPTION:
Mapping XS 64eba7c1
END DESCRIPTION:
XS GIS Cut Line= 4
      1499025.01      6915934.08      1499324.52      6915988.78
      1499616.18      6916220.55      1500041.65      6916225.73
#Sta/Elev= 30
  4539.6 1782.26  4570.1 1780.49  4601.9 1777.30  4640.5 1771.72  4645.6 1771.59
  4661.6 1768.42  4698.9 1763.21  4722.6 1760.56  4742.9 1759.81  4763.2 1757.65
  4797.0 1756.72  4806.1 1756.56  4847.5 1755.18  4908.5 1749.52  4946.8 1747.58
  4947.3 1747.08  4953.7 1747.58  4993.5 1747.75  5035.1 1749.82  5043.2 1750.24
  5049.6 1751.58  5064.0 1752.32  5128.1 1754.42  5214.2 1754.85  5345.4 1756.44
  5419.1 1758.48  5475.4 1760.82  5519.4 1764.37  5605.4 1775.21  5642.1 1777.35
#Mann=9,-1,0
  4539.6    0.07       0  4601.9   0.035       0  4797.0    0.07       0
  4806.1   0.035       0  4946.8   0.035       0  4953.7   0.035       0
  5035.1    0.07       0  5214.2   0.035       0  5519.4    0.07       0
Bank Sta=4946.8,4953.7
Exp/Cntr=0.3,0.1

Type RM Length L Ch R = 1,2457,280,280,280
BEGIN DESCRIPTION:
Mapping XS c509bedc
END DESCRIPTION:
XS GIS Cut Line= 4
      1498881.77      6916064.27      1499124.00      6916204.92
      1499441.71      6916327.32      1500048.44      6916410.65
#Sta/Elev= 30
  4579.3 1775.63  4592.7 1775.55  4657.3 1768.05  4694.6 1766.37  4700.4 1764.88
  4721.9 1763.02  4778.0 1759.44  4788.1 1758.91  4868.1 1754.88  4892.6 1753.20
  4903.3 1751.63  4907.4 1750.07  4924.8 1745.91  4939.2 1744.63  4969.2 1743.12
  4990.3 1743.04  4990.8 1742.54  4997.3 1743.04  5048.4 1746.34  5096.2 1752.01
  5108.4 1751.87  5117.7 1750.42  5129.1 1751.35  5139.1 1752.22  5378.1 1754.81
  5468.1 1755.90  5583.2 1759.11  5682.6 1761.94  5759.8 1765.35  5812.3 1771.02
#Mann=11,-1,0
  4579.3    0.07       0  4778.0   0.035       0  4788.1    0.07       0
  4868.1   0.035       0  4907.4    0.07       0  4990.3    0.07       0
  4997.3    0.07       0  5129.1   0.035       0  5378.1    0.07       0
  5468.1   0.035       0  5583.2    0.07       0
Bank Sta=4990.3,4997.3
Exp/Cntr=0.3,0.1

Type RM Length L Ch R = 1,2177,324,324,324
BEGIN DESCRIPTION:
Mapping XS 57d3955a
END DESCRIPTION:
XS GIS Cut Line= 4
      1498764.60      6916262.20      1498972.96      6916426.28
      1499566.71      6916658.05      1500171.76      6916678.82
#Sta/Elev= 30
  4537.6 1756.35  4627.2 1754.58  4634.7 1755.05  4655.5 1754.02  4734.1 1752.43
  4748.6 1752.78  4777.5 1751.84  4845.7 1751.39  4900.0 1749.70  4929.9 1749.86
  4976.8 1748.80  5019.7 1744.86  5068.4 1744.91  5089.4 1743.89  5089.9 1743.39
  5095.9 1743.39  5096.4 1743.89  5159.3 1749.59  5182.4 1751.05  5212.9 1750.86
  5255.9 1751.91  5266.6 1751.46  5277.3 1752.15  5291.1 1751.64  5298.8 1752.18
  5369.9 1752.67  5399.8 1752.23  5628.6 1754.95  5838.7 1759.55  6045.6 1765.36
#Mann=3,-1,0
  4537.6    0.07       0  5089.4    0.07       0  5096.4    0.07       0
Bank Sta=5089.4,5096.4
Exp/Cntr=0.3,0.1

Type RM Length L Ch R = 1,1853,342,342,342
BEGIN DESCRIPTION:
Mapping XS cb7f8a62
END DESCRIPTION:
XS GIS Cut Line= 5
      1498722.97      6916441.92      1498847.96      6916704.92
      1499215.14      6916863.78      1499561.50      6916840.34
      1500130.87      6916770.14
#Sta/Elev= 30
  4525.1 1752.16  4614.0 1750.91  4800.4 1748.50  4867.5 1747.01  4908.0 1747.13
  4937.9 1746.96  4966.8 1747.97  4980.1 1746.62  4998.3 1742.41  5010.3 1741.01
  5010.8 1740.51  5016.8 1740.51  5017.3 1741.01  5020.1 1741.99  5052.8 1743.35
  5060.8 1744.39  5066.2 1744.14  5129.0 1748.78  5147.7 1749.20  5236.3 1749.36
  5276.4 1750.26  5326.5 1749.61  5396.6 1750.55  5567.8 1751.35  5617.4 1752.25
  5637.6 1751.79  5849.2 1754.43  5889.5 1756.51  6020.4 1759.08  6137.2 1763.50
#Mann=7,-1,0
  4525.1    0.07       0  4614.0   0.035       0  4908.0    0.07       0
  4980.1   0.035       0  5010.3   0.035       0  5017.3   0.035       0
  5147.7    0.07       0
Bank Sta=5010.3,5017.3
Exp/Cntr=0.3,0.1

Type RM Length L Ch R = 1,1511,185,185,185
BEGIN DESCRIPTION:
Mapping XS bcbdee6c
END DESCRIPTION:
XS GIS Cut Line= 5
      1498683.91      6916616.43      1498806.29      6917012.21
      1498920.87      6917111.17      1499178.68      6917116.38
      1500130.88      6916809.39
#Sta/Elev= 30
  4497.7 1749.82  4733.5 1747.14  4813.4 1746.10  4858.6 1744.91  4946.2 1744.70
  4957.8 1744.15  4997.1 1739.80  4997.6 1739.30  5003.6 1739.30  5004.1 1739.80
  5021.4 1740.49  5044.1 1742.49  5077.5 1744.70  5097.5 1745.17  5137.5 1747.42
  5411.9 1748.62  5422.4 1749.13  5454.0 1748.74  5460.9 1749.37  5466.2 1748.86
  5557.1 1749.80  5569.5 1749.28  5842.7 1751.15  6105.4 1754.80  6149.8 1755.90
  6168.4 1757.45  6208.7 1758.47  6221.0 1759.35  6278.0 1760.67  6321.7 1763.41
#Mann=6,-1,0
  4497.7   0.035       0  4733.5    0.07       0  4946.2   0.035       0
  4997.1   0.035       0  5004.1   0.035       0  5044.1    0.07       0
Bank Sta=4997.1,5004.1
Exp/Cntr=0.3,0.1

Type RM Length L Ch R = 1,1326,733,733,733
BEGIN DESCRIPTION:
Mapping XS bdc89ec4
END DESCRIPTION:
XS GIS Cut Line= 5
      1498579.72      6916715.32      1498660.46      6917139.82
      1498939.10      6917314.30      1499147.43      6917277.84
      1500105.73      6916876.81
#Sta/Elev= 30
  4389.2 1749.13  4697.3 1745.96  4786.9 1744.35  4816.6 1743.32  4873.9 1742.74
  4976.1 1743.44  4997.3 1742.30  5000.2 1738.92  5000.7 1738.42  5006.7 1738.42
  5007.2 1738.92  5018.5 1739.00  5039.8 1740.58  5055.1 1740.53  5143.5 1746.13
  5227.1 1746.59  5349.0 1748.22  5374.7 1747.84  5422.2 1748.37  5687.3 1748.61
  5716.7 1749.52  5740.3 1748.96  5825.1 1749.81  5888.4 1749.78  5901.0 1750.28
  6071.2 1751.58  6124.3 1752.98  6277.8 1754.89  6312.9 1757.10  6400.4 1761.31
#Mann=4,-1,0
  4389.2   0.035       0  4786.9    0.07       0  5000.2    0.07       0
  5007.2    0.07       0
Bank Sta=5000.2,5007.2
Exp/Cntr=0.3,0.1

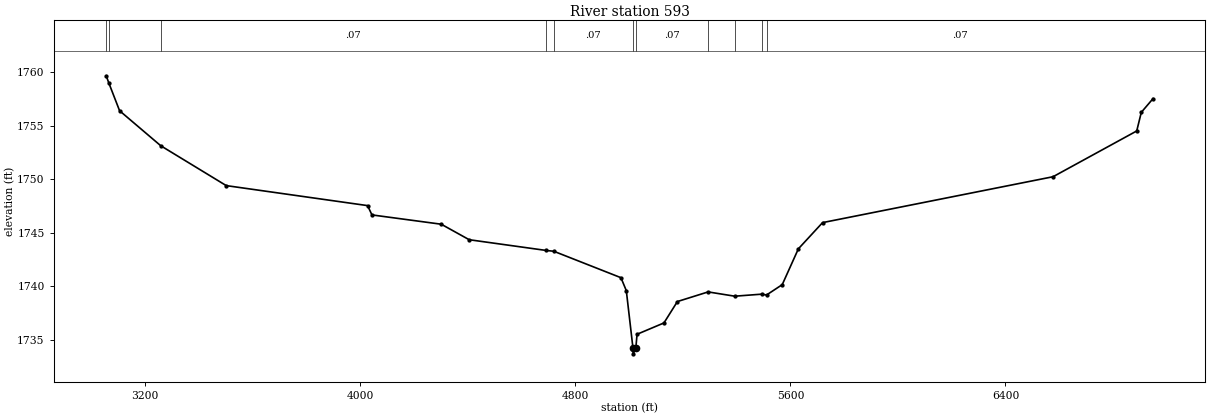
Type RM Length L Ch R = 1,593,0,0,0
BEGIN DESCRIPTION:
NC Unknown Stream 35 1.0
END DESCRIPTION:
XS GIS Cut Line= 4
      1497082.62      6916024.07      1497815.26      6917395.60
      1499002.76      6917406.02      1500054.98      6916938.01
#Sta/Elev= 30
  3055.0 1759.67  3065.2 1758.97  3104.8 1756.40  3257.8 1753.13  3501.6 1749.40
  4027.3 1747.53  4043.5 1746.66  4301.3 1745.79  4405.3 1744.34  4691.0 1743.34
  4720.1 1743.26  4969.7 1740.79  4989.7 1739.58  5014.6 1734.17  5015.1 1733.67
  5024.9 1734.17  5029.7 1735.50  5129.7 1736.56  5179.7 1738.56  5294.0 1739.46
  5393.0 1739.06  5493.6 1739.25  5511.2 1739.17  5569.7 1740.14  5629.7 1743.49
  5719.7 1745.94  6577.0 1750.23  6888.3 1754.51  6905.3 1756.25  6949.1 1757.54
#Mann=11,-1,0
  3055.0    0.07       0  3065.2   0.035       0  3257.8    0.07       0
  4691.0   0.035       0  4720.1    0.07       0  5014.6    0.07       0
  5024.9    0.07       0  5294.0   0.035       0  5393.0    0.07       0
  5493.6   0.035       0  5511.2    0.07       0
Bank Sta=5014.6,5024.9
Exp/Cntr=0.3,0.1

Chan Stop Cuts=-1