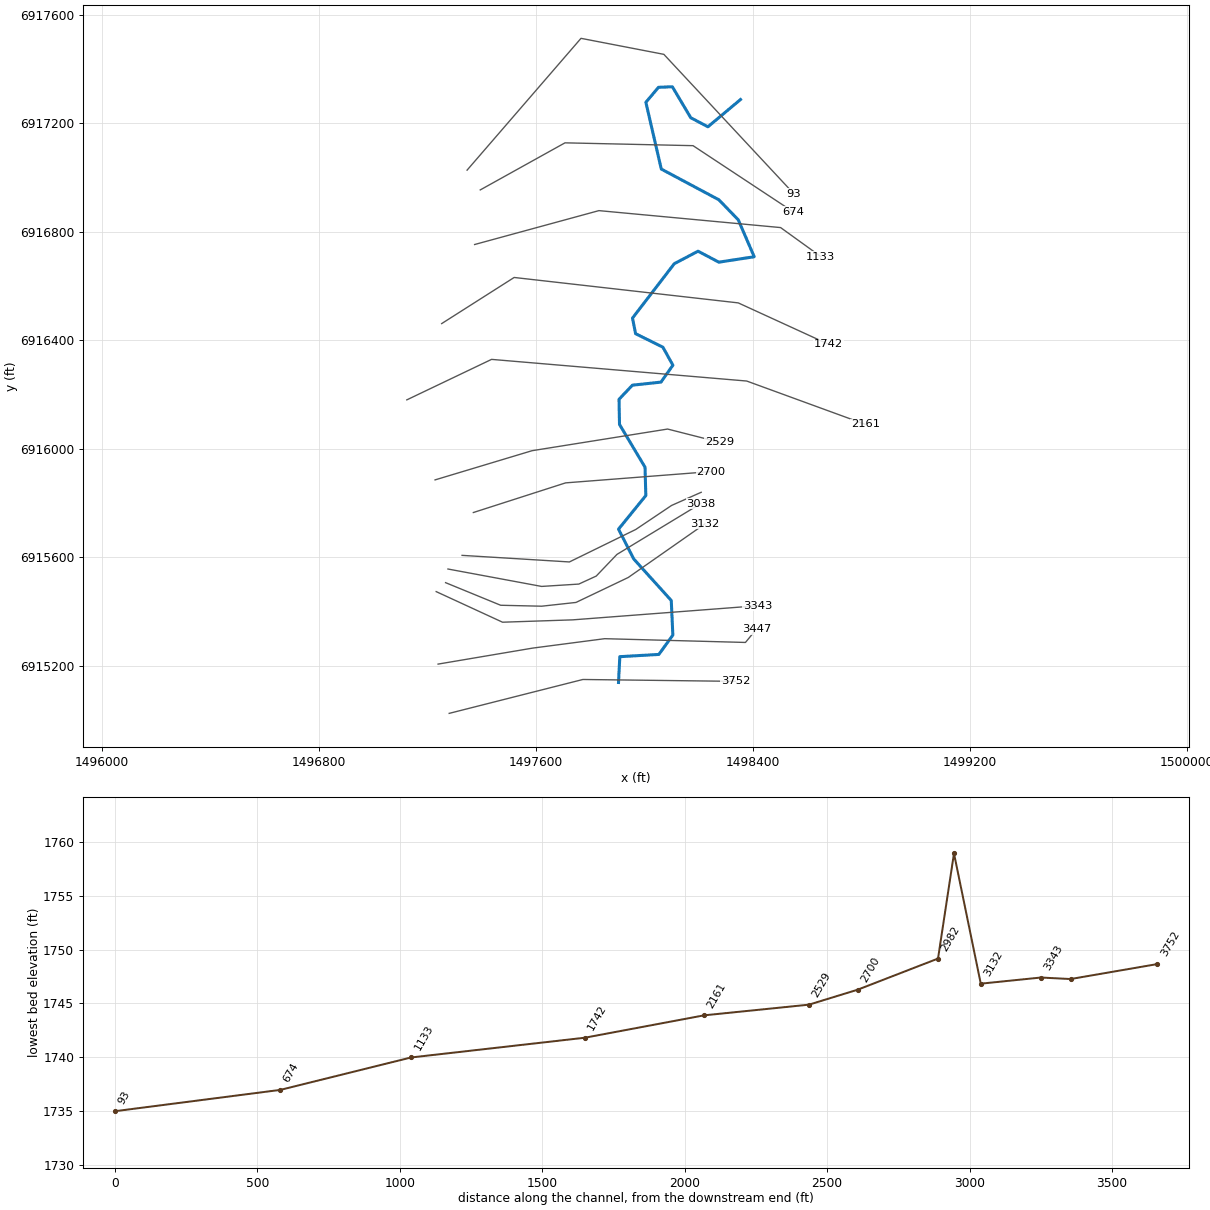
--- NC Unknown Stream 36.prj (project) ---

Proj Title=NC Unknown Stream 36 Base Level Engineering
Current Plan=p01
Default Exp/Contr=0.3,0.1
English Units
Geom File=g01
Flow File=f01
Plan File=p01
BEGIN DESCRIPTION:
NC Unknown Stream 36
END DESCRIPTION:

--- NC Unknown Stream 36.p01 (plan) ---

Plan Title=Multiple Run
Short Identifier=Multiple
Geom File=g01
Flow File=f01
Subcritical Flow
K Sum by GR= 0
Std Step Tol= 0.01
Critical Tol= 0.01
Num of Std Step Trials= 20
Max Error Tol= 0.3
Flow Tol Ratio= 0.001
Split Flow NTrial= 30
Split Flow Tol= 0.02
Split Flow Ratio= 0.02
Log Output Level= 0
Friction Slope Method= 1
Unsteady Friction Slope Method= 2
Unsteady Bridges Friction Slope Method= 1
Parabolic Critical Depth
Global Vel Dist=  1 , 1 , 1
Global Log Level= 0
CheckData=True
Encroach Param= -1, 0, 0, 0
BEGIN DESCRIPTION:
Multiple Run
END DESCRIPTION:

--- NC Unknown Stream 36.f01 (steady flow) ---

Flow Title=Multiple
Number of Profiles=7
Profile Names=10-year,25-year,50-year,1pct_min,100-year,1pct_plu,500-year
River Rch & RM= NC Unknown Strea,Reach-1,3752
     312     437     541     333     664    1325    1014
River Rch & RM= NC Unknown Strea,Reach-1,3447
     308     429     529     325     648    1293     982
Boundary for River Rch & Prof#=NC Unknown Strea,Reach-1,1
Up Type=0
Dn Type=3
Dn Slope=0.001
Boundary for River Rch & Prof#=NC Unknown Strea,Reach-1,2
Up Type=0
Dn Type=3
Dn Slope=0.001
Boundary for River Rch & Prof#=NC Unknown Strea,Reach-1,3
Up Type=0
Dn Type=3
Dn Slope=0.001
Boundary for River Rch & Prof#=NC Unknown Strea,Reach-1,4
Up Type=0
Dn Type=3
Dn Slope=0.001
Boundary for River Rch & Prof#=NC Unknown Strea,Reach-1,5
Up Type=0
Dn Type=3
Dn Slope=0.001
Boundary for River Rch & Prof#=NC Unknown Strea,Reach-1,6
Up Type=0
Dn Type=3
Dn Slope=0.001
Boundary for River Rch & Prof#=NC Unknown Strea,Reach-1,7
Up Type=0
Dn Type=3
Dn Slope=0.001

--- NC Unknown Stream 36.g01 (geometry) ---

Geom Title=Existing Conditions

River Reach=NC Unknown Strea,Reach-1
Reach XY= 30
      1497905.00      6915138.00      1497909.78      6915233.21
      1498053.77      6915241.44      1498105.36      6915312.79
      1498099.53      6915440.45      1497960.95      6915593.76
      1497904.99      6915703.45      1498005.70      6915827.43
      1498002.78      6915932.06      1497908.67      6916089.59
      1497906.88      6916182.31      1497956.25      6916234.48
      1498061.55      6916245.75      1498105.55      6916308.12
      1498068.69      6916374.51      1497967.97      6916424.44
      1497956.56      6916481.91      1498110.62      6916682.44
      1498198.33      6916728.61      1498275.01      6916688.16
      1498405.42      6916708.09      1498346.87      6916844.07
      1498275.13      6916918.23      1498062.74      6917031.54
      1498005.87      6917277.71      1498052.44      6917333.06
      1498103.53      6917335.00      1498171.50      6917220.79
      1498234.76      6917187.47      1498355.00      6917288.00

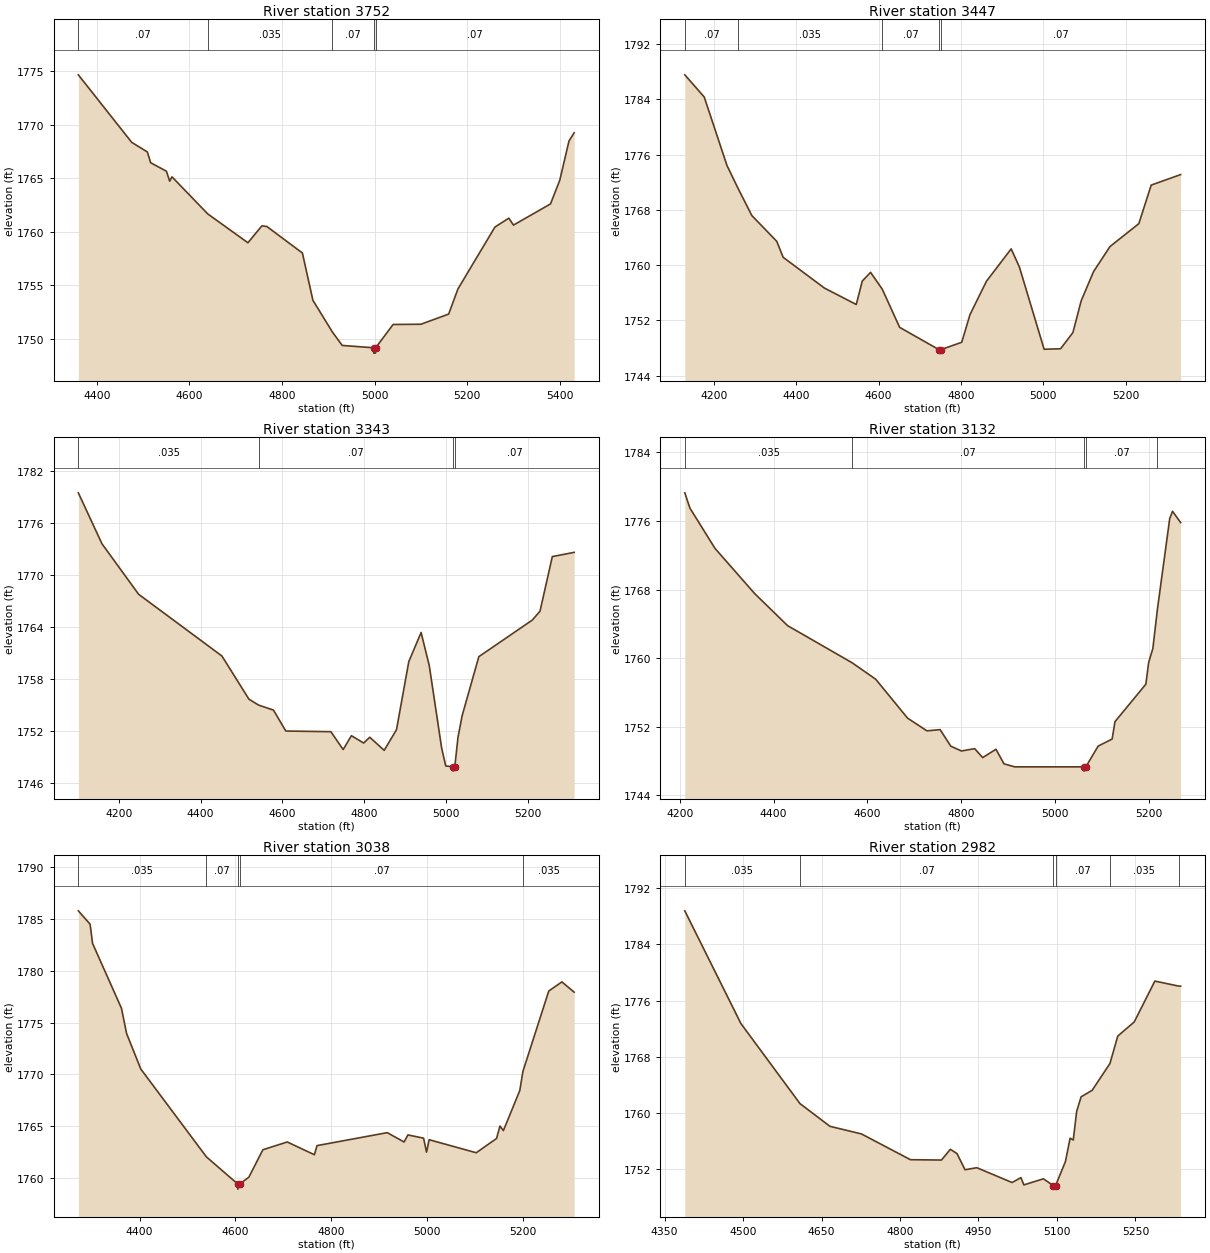
Type RM Length L Ch R = 1,3752,305,305,305
BEGIN DESCRIPTION:
NC Unknown Stream 36 4.0
END DESCRIPTION:
XS GIS Cut Line= 3
      1497280.51      6915024.07      1497773.59      6915149.08
      1498336.07      6915142.13
#Sta/Elev= 30
  4360.0 1774.67  4475.3 1768.36  4509.1 1767.46  4516.3 1766.45  4550.3 1765.66
  4557.3 1764.73  4562.4 1765.13  4639.5 1761.67  4726.4 1758.97  4756.6 1760.55
  4767.3 1760.49  4844.1 1758.01  4866.8 1753.59  4909.1 1750.61  4930.1 1749.37
  4997.9 1749.15  4998.2 1748.65  5002.0 1748.65  5002.3 1749.15  5040.1 1751.33
  5100.1 1751.35  5160.1 1752.30  5180.1 1754.65  5260.1 1760.44  5290.1 1761.27
  5300.1 1760.62  5380.1 1762.60  5400.1 1764.81  5420.1 1768.49  5431.2 1769.25
#Mann=5,-1,0
  4360.0    0.07       0  4639.5   0.035       0  4909.1    0.07       0
  4997.9    0.07       0  5002.3    0.07       0
Bank Sta=4997.9,5002.3
Exp/Cntr=0.3,0.1

Type RM Length L Ch R = 1,3447,104,104,104
BEGIN DESCRIPTION:
Mapping XS 66a207a5
END DESCRIPTION:
XS GIS Cut Line= 5
      1497239.49      6915205.80      1497588.41      6915264.82
      1497854.03      6915299.54      1498373.13      6915285.65
      1498413.53      6915334.46
#Sta/Elev= 30
  4129.4 1787.54  4176.6 1784.33  4231.9 1774.41  4258.4 1771.15  4292.3 1767.17
  4352.8 1763.44  4368.3 1761.13  4468.5 1756.68  4545.9 1754.30  4560.5 1757.69
  4580.7 1758.95  4609.2 1756.50  4651.3 1750.99  4746.9 1747.76  4747.2 1747.26
  4751.3 1747.76  4802.1 1748.83  4822.2 1752.84  4862.2 1757.67  4922.2 1762.35
  4942.2 1759.72  5002.2 1747.82  5042.2 1747.89  5072.2 1750.24  5092.2 1754.82
  5122.3 1759.06  5162.3 1762.69  5232.3 1766.00  5262.3 1771.58  5333.8 1773.10
#Mann=5,-1,0
  4129.4    0.07       0  4258.4   0.035       0  4609.2    0.07       0
  4746.9    0.07       0  4751.3    0.07       0
Bank Sta=4746.9,4751.3
Exp/Cntr=0.3,0.1

Type RM Length L Ch R = 1,3343,211,211,211
BEGIN DESCRIPTION:
Mapping XS 4456daa7
END DESCRIPTION:
XS GIS Cut Line= 4
      1497232.52      6915473.14      1497477.30      6915360.30
      1497735.98      6915368.98      1498418.24      6915421.06
#Sta/Elev= 30
  4101.0 1779.52  4158.8 1773.64  4248.5 1767.81  4452.1 1760.69  4518.3 1755.70
  4542.0 1755.02  4578.3 1754.44  4608.4 1752.03  4718.6 1751.95  4748.7 1749.89
  4768.8 1751.49  4798.9 1750.64  4813.7 1751.31  4849.0 1749.80  4879.1 1752.18
  4909.2 1760.04  4939.3 1763.40  4959.3 1759.57  4989.4 1750.10  4999.5 1748.00
  5017.3 1747.90  5017.6 1747.40  5021.7 1747.90  5029.5 1751.30  5039.6 1753.79
  5080.5 1760.61  5211.4 1764.84  5230.1 1765.86  5260.2 1772.16  5313.6 1772.65
#Mann=4,-1,0
  4101.0   0.035       0  4542.0    0.07       0  5017.3    0.07       0
  5021.7    0.07       0
Bank Sta=5017.3,5021.7
Exp/Cntr=0.3,0.1

Type RM Length L Ch R = 1,3132,94,94,94
BEGIN DESCRIPTION:
Mapping XS 2ceb2214
END DESCRIPTION:
XS GIS Cut Line= 6
      1497267.22      6915506.14      1497470.35      6915422.80
      1497621.39      6915419.33      1497748.13      6915433.22
      1497940.84      6915525.23      1498223.69      6915723.06
#Sta/Elev= 30
  4210.6 1779.29  4221.6 1777.50  4275.0 1772.81  4359.5 1767.54  4429.7 1763.80
  4567.8 1759.45  4617.5 1757.55  4685.5 1753.01  4726.7 1751.53  4754.9 1751.67
  4777.6 1749.74  4800.3 1749.18  4828.5 1749.45  4845.6 1748.41  4873.9 1749.38
  4891.0 1747.68  4913.7 1747.33  5061.1 1747.33  5061.4 1746.83  5065.5 1747.33
  5091.7 1749.75  5121.5 1750.57  5127.6 1752.60  5193.4 1756.97  5199.4 1759.51
  5208.3 1761.13  5217.9 1765.65  5244.2 1776.27  5250.3 1777.14  5267.5 1775.82
#Mann=5,-1,0
  4210.6   0.035       0  4567.8    0.07       0  5061.1    0.07       0
  5065.5    0.07       0  5217.9   0.035       0
Bank Sta=5061.1,5065.5
Exp/Cntr=0.3,0.1

Type RM Length L Ch R = 1,3038,56,56,56
BEGIN DESCRIPTION:
Mapping XS 72cfeecd
END DESCRIPTION:
XS GIS Cut Line= 6
      1497275.93      6915556.48      1497621.39      6915492.25
      1497758.55      6915500.93      1497822.78      6915530.44
      1497899.17      6915610.30      1498208.23      6915797.82
#Sta/Elev= 30
  4272.2 1785.78  4296.8 1784.49  4301.9 1782.64  4362.2 1776.38  4373.0 1773.93
  4402.5 1770.52  4539.4 1762.04  4604.8 1759.42  4605.1 1758.92  4609.2 1759.42
  4628.1 1760.07  4657.4 1762.72  4708.3 1763.47  4764.9 1762.24  4770.4 1763.12
  4917.0 1764.37  4952.1 1763.47  4960.1 1764.15  4992.8 1763.84  4999.0 1762.49
  5004.5 1763.69  5102.7 1762.43  5145.2 1763.81  5152.2 1765.01  5159.4 1764.57
  5193.6 1768.43  5200.2 1770.29  5254.1 1778.04  5281.5 1778.92  5307.1 1777.93
#Mann=5,-1,0
  4272.2   0.035       0  4539.4    0.07       0  4604.8    0.07       0
  4609.2    0.07       0  5200.2   0.035       0
Bank Sta=4604.8,4609.2
Exp/Cntr=0.3,0.1

Type RM Length L Ch R = 1,2982,282,282,282
BEGIN DESCRIPTION:
Mapping XS 952558a1
END DESCRIPTION:
XS GIS Cut Line= 6
      1497328.03      6915606.83      1497555.42      6915592.94
      1497723.82      6915582.53      1497968.62      6915702.32
      1498100.56      6915790.86      1498209.97      6915839.49
#Sta/Elev= 30
  4388.7 1788.78  4495.9 1772.74  4608.8 1761.34  4666.2 1758.10  4726.3 1757.02
  4820.0 1753.35  4879.3 1753.30  4896.2 1754.83  4909.0 1754.22  4924.3 1751.92
  4946.8 1752.21  5014.3 1750.10  5031.2 1750.80  5036.8 1749.76  5074.2 1750.63
  5093.0 1749.66  5093.3 1749.16  5097.4 1749.66  5116.2 1753.08  5125.2 1756.41
  5131.2 1756.15  5137.7 1760.23  5146.2 1762.30  5167.3 1763.23  5201.3 1767.04
  5216.3 1770.95  5247.7 1772.96  5287.2 1778.78  5333.0 1778.06  5336.4 1778.06
#Mann=6,-1,0
  4388.7   0.035       0  4608.8    0.07       0  5093.0    0.07       0
  5097.4    0.07       0  5201.3   0.035       0  5333.0    0.07       0
Bank Sta=5093,5097.4
Exp/Cntr=0.3,0.1

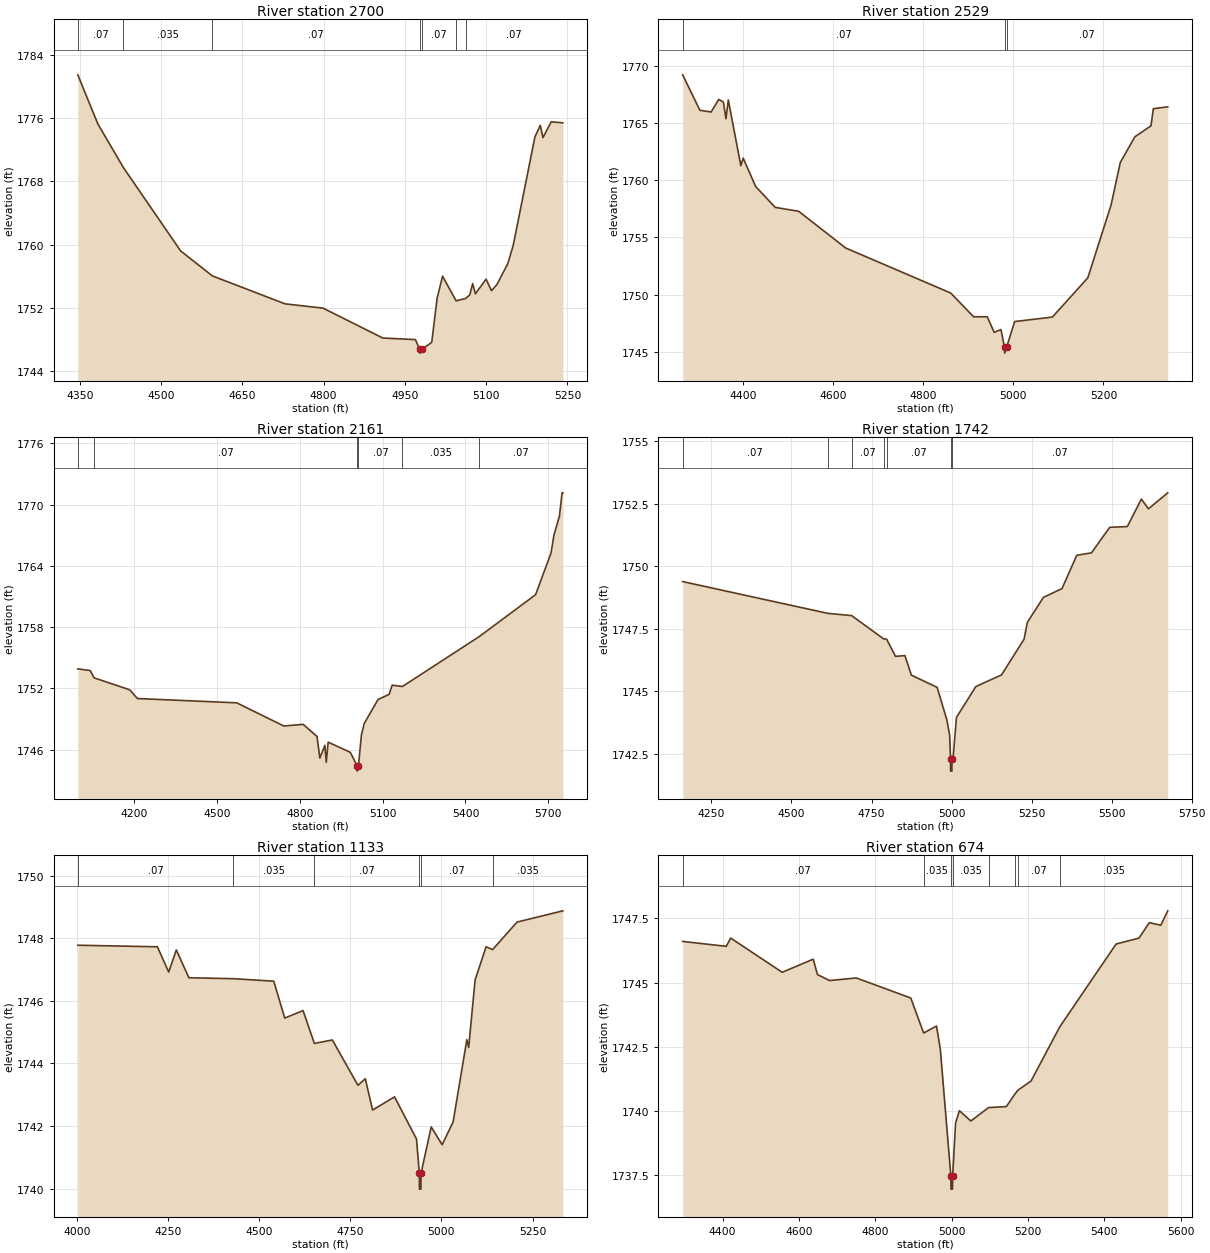
Type RM Length L Ch R = 1,2700,171,171,171
BEGIN DESCRIPTION:
Mapping XS 6b48aa96
END DESCRIPTION:
XS GIS Cut Line= 3
      1497369.66      6915764.82      1497709.93      6915874.19
      1498246.40      6915915.86
#Sta/Elev= 30
  4346.1 1781.46  4383.2 1775.24  4430.4 1769.72  4535.9 1759.20  4594.4 1756.04
  4728.7 1752.50  4798.9 1751.96  4909.2 1748.18  4969.4 1747.98  4977.2 1746.77
  4977.5 1746.27  4981.7 1746.77  4999.5 1747.63  5009.5 1753.23  5019.5 1756.00
  5044.5 1752.88  5062.0 1753.18  5069.7 1753.63  5075.1 1755.06  5080.1 1753.77
  5099.8 1755.62  5109.8 1754.17  5119.8 1754.93  5139.9 1757.58  5149.9 1759.87
  5190.0 1773.61  5199.9 1775.07  5204.9 1773.52  5220.1 1775.52  5241.6 1775.39
#Mann=7,-1,0
  4346.1    0.07       0  4430.4   0.035       0  4594.4    0.07       0
  4977.2    0.07       0  4981.7    0.07       0  5044.5   0.035       0
  5062.0    0.07       0
Bank Sta=4977.2,4981.7
Exp/Cntr=0.3,0.1

Type RM Length L Ch R = 1,2529,368,368,368
BEGIN DESCRIPTION:
Mapping XS abf41cda
END DESCRIPTION:
XS GIS Cut Line= 4
      1497228.43      6915885.18      1497586.09      6915992.83
      1498086.09      6916072.69      1498277.06      6916024.08
#Sta/Elev= 30
  4266.0 1769.21  4304.2 1766.11  4329.1 1765.96  4346.0 1767.06  4356.4 1766.83
  4362.1 1765.37  4367.3 1767.01  4395.1 1761.27  4400.3 1761.93  4428.1 1759.44
  4471.6 1757.62  4523.5 1757.28  4627.9 1754.07  4861.2 1750.13  4911.8 1748.06
  4942.2 1748.06  4957.5 1746.70  4972.6 1746.94  4980.5 1745.38  4980.8 1744.88
  4985.0 1745.38  5003.0 1747.64  5086.7 1748.03  5165.4 1751.46  5216.9 1757.80
  5237.6 1761.55  5269.9 1763.79  5305.7 1764.75  5310.9 1766.25  5342.9 1766.41
#Mann=3,-1,0
  4266.0    0.07       0  4980.5    0.07       0  4985.0    0.07       0
Bank Sta=4980.5,4985
Exp/Cntr=0.3,0.1

Type RM Length L Ch R = 1,2161,419,419,419
BEGIN DESCRIPTION:
Mapping XS 5a738248
END DESCRIPTION:
XS GIS Cut Line= 4
      1497124.26      6916180.31      1497436.79      6916329.63
      1498377.76      6916249.77      1498815.29      6916090.04
#Sta/Elev= 30
  3996.3 1753.91  4041.5 1753.74  4055.0 1753.03  4184.0 1751.86  4212.3 1751.00
  4571.7 1750.58  4742.3 1748.31  4812.6 1748.47  4862.7 1747.28  4872.8 1745.17
  4891.0 1746.42  4896.0 1744.76  4902.9 1746.73  4983.2 1745.73  5008.1 1744.39
  5008.4 1743.89  5012.6 1744.39  5023.3 1747.42  5033.4 1748.55  5083.5 1750.90
  5123.7 1751.41  5134.7 1752.31  5171.9 1752.18  5449.6 1757.06  5654.0 1761.17
  5709.8 1765.24  5720.6 1767.02  5740.3 1768.86  5750.0 1771.15  5752.8 1771.15
#Mann=6,-1,0
  3996.3   0.035       0  4055.0    0.07       0  5008.1    0.07       0
  5012.6    0.07       0  5171.9   0.035       0  5449.6    0.07       0
Bank Sta=5008.1,5012.6
Exp/Cntr=0.3,0.1

Type RM Length L Ch R = 1,1742,609,609,609
BEGIN DESCRIPTION:
Mapping XS 1278c388
END DESCRIPTION:
XS GIS Cut Line= 4
      1497252.79      6916461.60      1497520.12      6916631.72
      1498346.51      6916537.97      1498679.81      6916385.20
#Sta/Elev= 30
  4160.1 1749.39  4613.3 1748.12  4687.8 1748.03  4787.8 1747.10  4797.1 1747.09
  4824.8 1746.40  4854.3 1746.43  4874.4 1745.65  4954.9 1745.16  4985.1 1743.87
  4994.0 1743.26  4996.8 1742.31  4997.1 1741.81  5001.0 1741.81  5001.3 1742.31
  5005.2 1742.40  5015.3 1743.96  5075.7 1745.19  5156.2 1745.66  5226.6 1747.09
  5236.7 1747.76  5287.0 1748.76  5345.0 1749.11  5391.0 1750.44  5437.0 1750.54
  5494.0 1751.56  5549.0 1751.59  5593.0 1752.69  5615.0 1752.30  5675.3 1752.94
#Mann=7,-1,0
  4160.1    0.07       0  4613.3   0.035       0  4687.8    0.07       0
  4787.8   0.035       0  4797.1    0.07       0  4996.8    0.07       0
  5001.3    0.07       0
Bank Sta=4996.8,5001.3
Exp/Cntr=0.3,0.1

Type RM Length L Ch R = 1,1133,459,459,459
BEGIN DESCRIPTION:
Mapping XS de8c25f2
END DESCRIPTION:
XS GIS Cut Line= 4
      1497374.30      6916753.25      1497832.62      6916878.24
      1498502.76      6916815.74      1498651.04      6916708.84
#Sta/Elev= 30
  4002.3 1747.78  4220.7 1747.73  4251.8 1746.92  4272.6 1747.63  4307.1 1746.74
  4428.7 1746.71  4540.0 1746.63  4570.1 1745.45  4620.4 1745.69  4651.4 1744.64
  4700.7 1744.75  4771.0 1743.30  4791.1 1743.51  4811.2 1742.51  4871.4 1742.93
  4931.7 1741.58  4939.4 1740.48  4939.8 1739.98  4943.7 1739.98  4944.0 1740.48
  4971.9 1741.97  5002.0 1741.40  5032.1 1742.13  5069.8 1744.76  5074.8 1744.51
  5092.4 1746.67  5122.5 1747.73  5140.4 1747.64  5207.5 1748.52  5333.2 1748.88
#Mann=6,-1,0
  4002.3    0.07       0  4428.7   0.035       0  4651.4    0.07       0
  4939.4    0.07       0  4944.0    0.07       0  5140.4   0.035       0
Bank Sta=4939.4,4944
Exp/Cntr=0.3,0.1

Type RM Length L Ch R = 1,674,581,581,581
BEGIN DESCRIPTION:
Mapping XS b8c3a8ea
END DESCRIPTION:
XS GIS Cut Line= 4
      1497395.09      6916954.61      1497707.62      6917128.24
      1498179.84      6917117.83      1498547.87      6916874.79
#Sta/Elev= 30
  4295.5 1746.60  4409.8 1746.41  4421.3 1746.73  4556.3 1745.40  4637.5 1745.91
  4648.7 1745.31  4680.4 1745.08  4750.4 1745.18  4893.1 1744.40  4926.8 1743.04
  4960.5 1743.31  4970.5 1742.42  4998.2 1737.47  4998.5 1736.97  5002.4 1736.97
  5002.8 1737.47  5010.5 1739.54  5020.5 1740.02  5050.5 1739.62  5097.0 1740.14
  5143.5 1740.18  5165.6 1740.66  5174.1 1740.82  5208.1 1741.17  5283.5 1743.28
  5431.1 1746.50  5491.1 1746.73  5518.1 1747.33  5548.2 1747.23  5566.4 1747.79
#Mann=8,-1,0
  4295.5    0.07       0  4926.8   0.035       0  4998.2   0.035       0
  5002.8   0.035       0  5097.0    0.07       0  5165.6   0.035       0
  5174.1    0.07       0  5283.5   0.035       0
Bank Sta=4998.2,5002.8
Exp/Cntr=0.3,0.1

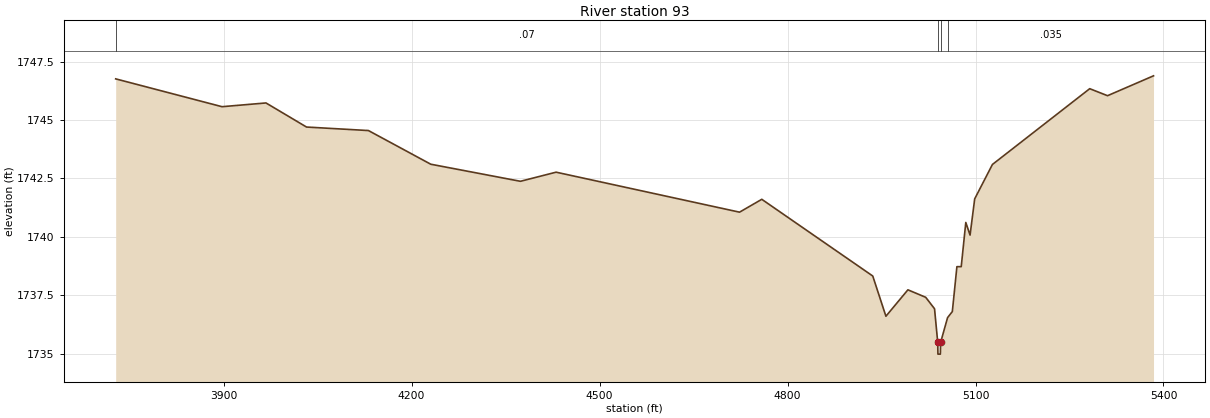
Type RM Length L Ch R = 1,93,0,0,0
BEGIN DESCRIPTION:
NC Unknown Stream 36 1.0
END DESCRIPTION:
XS GIS Cut Line= 4
      1497346.49      6917027.53      1497766.65      6917513.66
      1498072.20      6917454.63      1498551.39      6916940.72
#Sta/Elev= 30
  3727.7 1746.76  3897.4 1745.57  3967.6 1745.73  4032.3 1744.70  4131.1 1744.55
  4230.6 1743.11  4373.7 1742.38  4430.6 1742.77  4723.4 1741.06  4758.9 1741.61
  4936.0 1738.33  4957.0 1736.61  4992.1 1737.74  5020.5 1737.42  5034.6 1736.93
  5039.7 1735.49  5040.0 1734.99  5043.9 1734.99  5044.3 1735.49  5055.4 1736.55
  5063.0 1736.81  5070.3 1738.73  5077.2 1738.73  5084.5 1740.62  5091.3 1740.08
  5098.7 1741.63  5127.0 1743.10  5282.3 1746.34  5310.7 1746.04  5384.1 1746.89
#Mann=4,-1,0
  3727.7    0.07       0  5039.7    0.07       0  5044.3    0.07       0
  5055.4   0.035       0
Bank Sta=5039.7,5044.3
Exp/Cntr=0.3,0.1

Chan Stop Cuts=-1