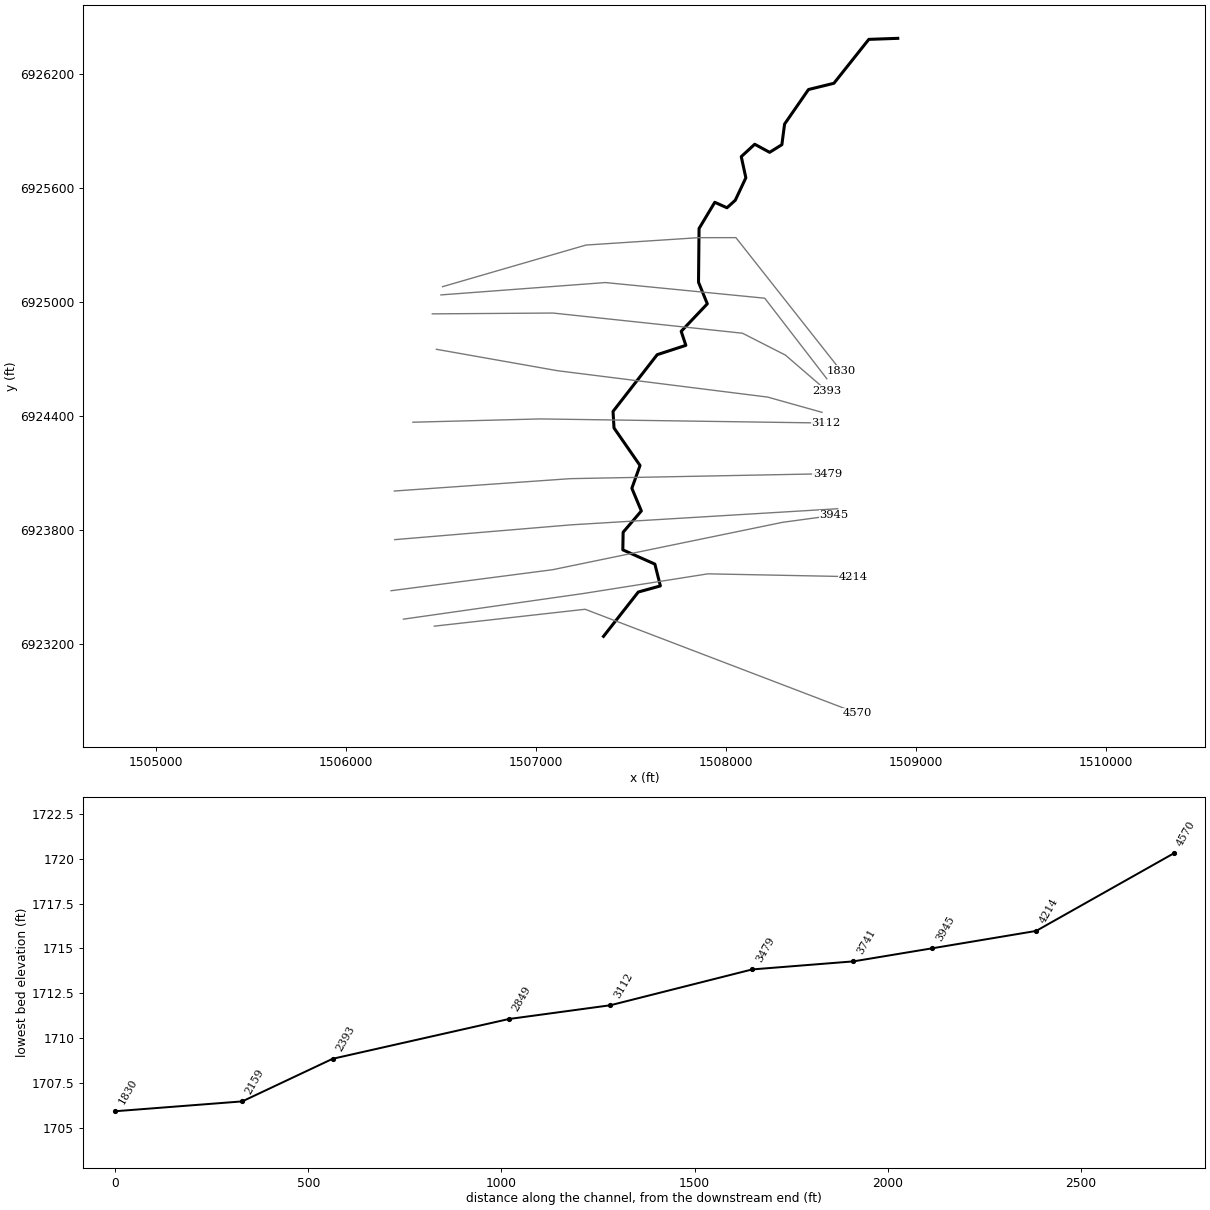
--- NC Unknown Stream 37.prj (project) ---

Proj Title=NC Unknown Stream 37 Base Level Engineering
Current Plan=p01
Default Exp/Contr=0.3,0.1
English Units
Geom File=g01
Flow File=f01
Plan File=p01
BEGIN DESCRIPTION:
NC Unknown Stream 37
END DESCRIPTION:

--- NC Unknown Stream 37.p01 (plan) ---

Plan Title=Multiple Run
Short Identifier=Multiple
Geom File=g01
Flow File=f01
Subcritical Flow
K Sum by GR= 0
Std Step Tol= 0.01
Critical Tol= 0.01
Num of Std Step Trials= 20
Max Error Tol= 0.3
Flow Tol Ratio= 0.001
Split Flow NTrial= 30
Split Flow Tol= 0.02
Split Flow Ratio= 0.02
Log Output Level= 0
Friction Slope Method= 1
Unsteady Friction Slope Method= 2
Unsteady Bridges Friction Slope Method= 1
Parabolic Critical Depth
Global Vel Dist=  1 , 1 , 1
Global Log Level= 0
CheckData=True
Encroach Param= -1, 0, 0, 0
BEGIN DESCRIPTION:
Multiple Run
END DESCRIPTION:

--- NC Unknown Stream 37.f01 (steady flow) ---

Flow Title=Multiple
Number of Profiles=7
Profile Names=10-year,25-year,50-year,1pct_min,100-year,1pct_plu,500-year
River Rch & RM= NC Unknown Strea,Reach-1,4570
     280     392     486     299     597    1192     915
River Rch & RM= NC Unknown Strea,Reach-1,3479
     294     411     508     313     624    1245     954
Boundary for River Rch & Prof#=NC Unknown Strea,Reach-1,1
Up Type=0
Dn Type=3
Dn Slope=0.001
Boundary for River Rch & Prof#=NC Unknown Strea,Reach-1,2
Up Type=0
Dn Type=3
Dn Slope=0.001
Boundary for River Rch & Prof#=NC Unknown Strea,Reach-1,3
Up Type=0
Dn Type=3
Dn Slope=0.001
Boundary for River Rch & Prof#=NC Unknown Strea,Reach-1,4
Up Type=0
Dn Type=3
Dn Slope=0.001
Boundary for River Rch & Prof#=NC Unknown Strea,Reach-1,5
Up Type=0
Dn Type=3
Dn Slope=0.001
Boundary for River Rch & Prof#=NC Unknown Strea,Reach-1,6
Up Type=0
Dn Type=3
Dn Slope=0.001
Boundary for River Rch & Prof#=NC Unknown Strea,Reach-1,7
Up Type=0
Dn Type=3
Dn Slope=0.001

--- NC Unknown Stream 37.g01 (geometry) ---

Geom Title=Existing Conditions

River Reach=NC Unknown Strea,Reach-1
Reach XY= 30
      1507355.00      6923238.00      1507538.27      6923471.53
      1507654.59      6923503.65      1507625.66      6923618.56
      1507456.87      6923693.69      1507458.47      6923786.50
      1507554.39      6923898.62      1507504.43      6924017.95
      1507547.47      6924138.01      1507410.41      6924335.58
      1507405.24      6924422.78      1507637.87      6924721.70
      1507788.80      6924770.88      1507764.31      6924844.66
      1507901.87      6924989.63      1507855.52      6925103.22
      1507858.37      6925386.27      1507941.32      6925524.49
      1508005.20      6925495.48      1508049.17      6925535.16
      1508104.86      6925653.41      1508080.72      6925764.82
      1508151.56      6925830.18      1508230.09      6925787.56
      1508294.61      6925827.78      1508308.83      6925936.41
      1508434.81      6926118.39      1508568.65      6926151.26
      1508752.53      6926382.57      1508905.00      6926388.00

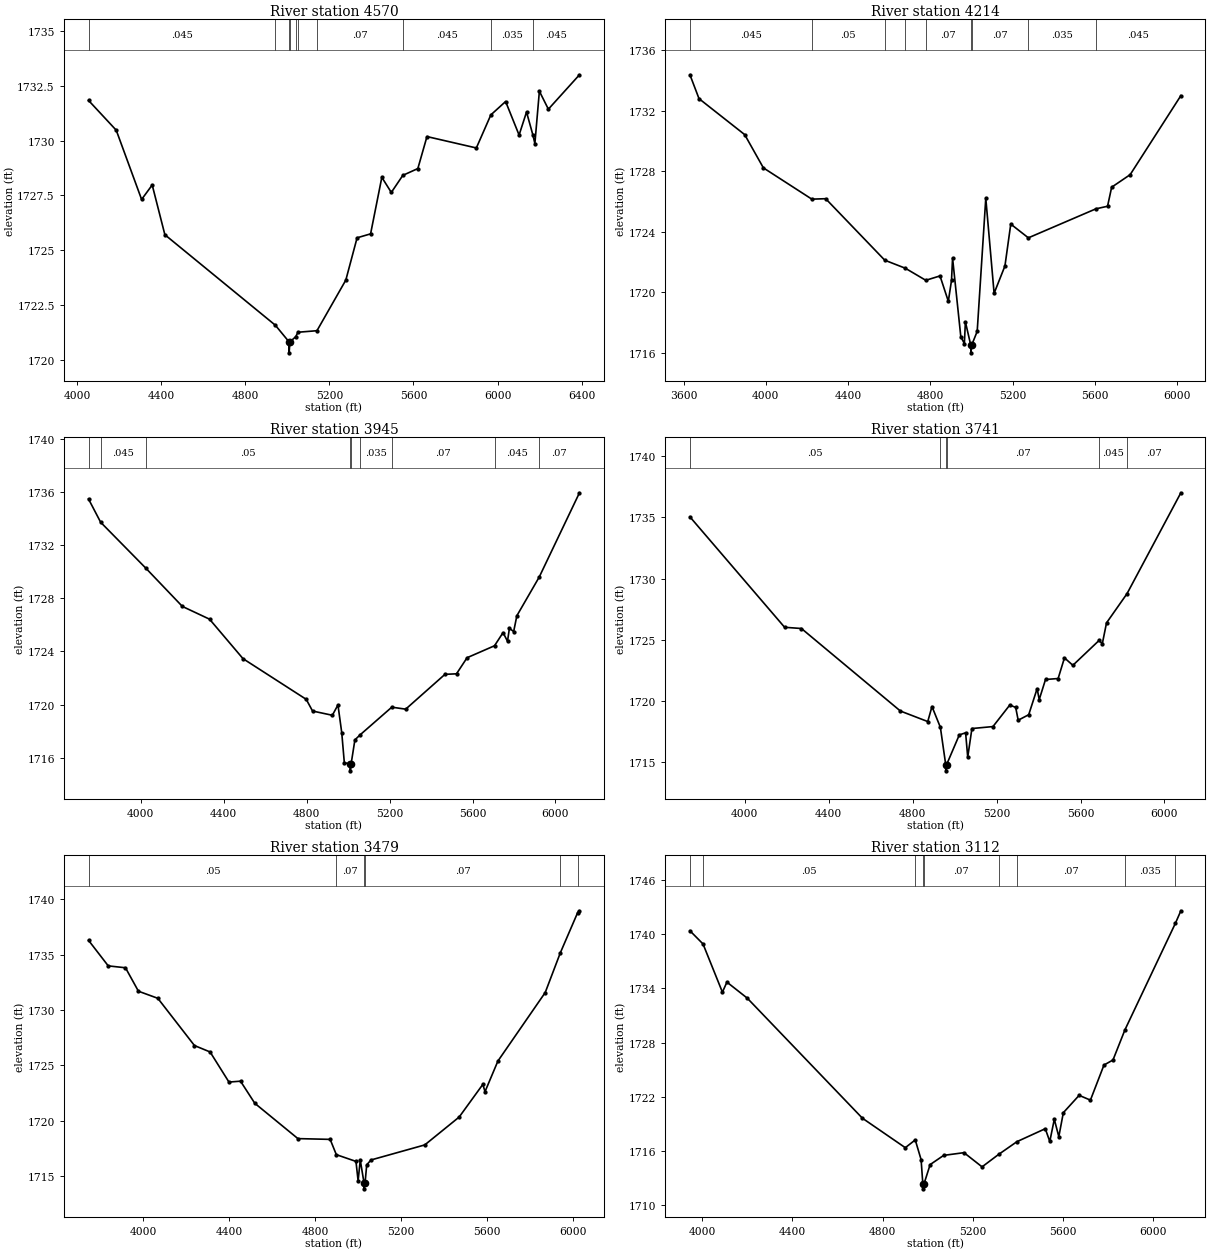
Type RM Length L Ch R = 1,4570,356,356,356
BEGIN DESCRIPTION:
NC Unknown Stream 37 6.0
END DESCRIPTION:
XS GIS Cut Line= 3
      1506464.02      6923291.75      1507258.26      6923380.72
      1508693.14      6922832.35
#Sta/Elev= 30
  4054.3 1731.83  4186.1 1730.47  4306.8 1727.31  4357.2 1727.97  4417.5 1725.70
  4943.0 1721.57  5008.2 1720.81  5008.5 1720.31  5012.2 1720.81  5040.3 1721.05
  5050.2 1721.25  5140.9 1721.32  5278.2 1723.63  5331.8 1725.56  5396.0 1725.74
  5449.5 1728.32  5494.6 1727.63  5549.4 1728.41  5620.8 1728.72  5664.2 1730.18
  5899.1 1729.66  5968.1 1731.17  6038.3 1731.78  6102.4 1730.25  6137.8 1731.30
  6168.4 1730.24  6177.5 1729.86  6198.9 1732.25  6241.7 1731.43  6389.6 1733.00
#Mann=10,-1,0
  4054.3   0.045       0  4943.0    0.07       0  5008.2    0.07       0
  5012.2    0.07       0  5040.3   0.045       0  5050.2   0.035       0
  5140.9    0.07       0  5549.4   0.045       0  5968.1   0.035       0
  6168.4   0.045       0
Bank Sta=5008.2,5012.2
Exp/Cntr=0.3,0.1

Type RM Length L Ch R = 1,4214,269,269,269
BEGIN DESCRIPTION:
Mapping XS 9a4c335e
END DESCRIPTION:
XS GIS Cut Line= 4
      1506301.27      6923328.65      1507245.24      6923463.19
      1507904.97      6923567.36      1508671.60      6923552.20
#Sta/Elev= 30
  3630.6 1734.38  3674.8 1732.80  3897.0 1730.42  3987.9 1728.22  4223.6 1726.15
  4290.9 1726.18  4578.4 1722.11  4678.2 1721.58  4778.0 1720.78  4847.1 1721.07
  4887.6 1719.39  4903.1 1720.78  4908.2 1722.25  4948.3 1717.05  4965.6 1716.59
  4970.6 1718.03  4996.9 1716.48  4997.2 1715.98  5000.9 1716.48  5028.0 1717.40
  5069.8 1726.21  5110.3 1719.92  5163.0 1721.73  5191.3 1724.50  5276.9 1723.59
  5605.6 1725.51  5662.1 1725.68  5682.1 1726.94  5772.1 1727.77  6018.8 1733.00
#Mann=9,-1,0
  3630.6   0.045       0  4223.6    0.05       0  4578.4    0.07       0
  4678.2   0.035       0  4778.0    0.07       0  4996.9    0.07       0
  5000.9    0.07       0  5276.9   0.035       0  5605.6   0.045       0
Bank Sta=4996.9,5000.9
Exp/Cntr=0.3,0.1

Type RM Length L Ch R = 1,3945,204,204,204
BEGIN DESCRIPTION:
Mapping XS e3447a8e
END DESCRIPTION:
XS GIS Cut Line= 4
      1506236.15      6923478.38      1507086.82      6923589.06
      1508297.76      6923838.62      1508569.04      6923875.52
#Sta/Elev= 30
  3747.7 1735.46  3806.3 1733.71  4023.9 1730.26  4200.3 1727.38  4331.4 1726.42
  4492.8 1723.45  4797.7 1720.39  4828.3 1719.51  4923.8 1719.19  4950.8 1719.97
  4969.0 1717.89  4981.5 1715.63  5010.1 1715.51  5010.3 1715.01  5014.1 1715.51
  5032.5 1717.34  5058.6 1717.73  5210.5 1719.80  5277.5 1719.65  5466.9 1722.27
  5522.6 1722.31  5573.6 1723.52  5705.9 1724.42  5747.2 1725.41  5768.6 1724.76
  5777.8 1725.73  5798.3 1725.49  5813.8 1726.68  5921.6 1729.59  6115.7 1735.93
#Mann=9,-1,0
  3747.7    0.05       0  3806.3   0.045       0  4023.9    0.05       0
  5010.1    0.05       0  5014.1    0.05       0  5058.6   0.035       0
  5210.5    0.07       0  5705.9   0.045       0  5921.6    0.07       0
Bank Sta=5010.1,5014.1
Exp/Cntr=0.3,0.1

Type RM Length L Ch R = 1,3741,262,262,262
BEGIN DESCRIPTION:
Mapping XS 99e87873
END DESCRIPTION:
XS GIS Cut Line= 3
      1506255.61      6923747.47      1507186.65      6923825.60
      1508588.59      6923910.24
#Sta/Elev= 30
  3739.2 1735.05  4190.2 1726.02  4270.4 1725.92  4742.0 1719.17  4872.2 1718.31
  4892.3 1719.54  4932.3 1717.84  4957.8 1714.78  4958.0 1714.28  4961.8 1714.78
  5022.5 1717.22  5052.5 1717.39  5062.6 1715.40  5082.6 1717.74  5182.8 1717.90
  5262.9 1719.66  5291.0 1719.47  5303.0 1718.42  5353.1 1718.87  5393.2 1721.00
  5403.2 1720.11  5433.2 1721.75  5493.3 1721.83  5523.4 1723.52  5563.5 1722.91
  5688.7 1724.95  5703.7 1724.67  5723.8 1726.38  5821.5 1728.77  6078.0 1737.02
#Mann=6,-1,0
  3739.2    0.05       0  4932.3    0.07       0  4957.8    0.07       0
  4961.8    0.07       0  5688.7   0.045       0  5821.5    0.07       0
Bank Sta=4957.8,4961.8
Exp/Cntr=0.3,0.1

Type RM Length L Ch R = 1,3479,367,367,367
BEGIN DESCRIPTION:
Mapping XS 99747a8c
END DESCRIPTION:
XS GIS Cut Line= 3
      1506253.50      6924003.55      1507180.14      6924068.66
      1508534.27      6924094.70
#Sta/Elev= 30
  3745.3 1736.29  3837.0 1733.98  3917.2 1733.81  3977.4 1731.69  4067.6 1731.05
  4238.0 1726.78  4310.7 1726.20  4398.4 1723.48  4452.2 1723.56  4518.7 1721.56
  4719.1 1718.37  4869.1 1718.30  4897.8 1716.92  4989.1 1716.31  4999.1 1714.56
  5009.1 1716.43  5026.9 1714.33  5027.2 1713.83  5031.3 1714.33  5039.1 1716.00
  5059.2 1716.44  5309.2 1717.80  5469.2 1720.32  5579.2 1723.27  5589.3 1722.61
  5649.3 1725.38  5869.3 1731.57  5939.8 1735.17  6019.7 1738.77  6028.6 1738.96
#Mann=6,-1,0
  3745.3    0.05       0  4897.8    0.07       0  5026.9    0.07       0
  5031.3    0.07       0  5939.8   0.035       0  6019.7    0.07       0
Bank Sta=5026.9,5031.3
Exp/Cntr=0.3,0.1

Type RM Length L Ch R = 1,3112,263,263,263
BEGIN DESCRIPTION:
Mapping XS 9978537d
END DESCRIPTION:
XS GIS Cut Line= 3
      1506351.14      6924365.97      1507021.72      6924383.33
      1508525.66      6924361.63
#Sta/Elev= 30
  3946.7 1740.37  4004.7 1738.91  4090.6 1733.58  4110.6 1734.69  4200.6 1732.92
  4710.8 1719.64  4900.8 1716.38  4944.9 1717.24  4970.8 1715.06  4978.6 1712.33
  4978.9 1711.83  4983.1 1712.33  5010.8 1714.51  5070.8 1715.53  5160.8 1715.83
  5240.9 1714.26  5313.9 1715.63  5395.6 1717.05  5520.9 1718.48  5540.9 1717.07
  5560.9 1719.52  5580.9 1717.60  5600.9 1720.25  5670.9 1722.17  5720.9 1721.64
  5780.9 1725.52  5820.9 1726.08  5874.1 1729.43  6097.4 1741.20  6121.6 1742.58
#Mann=9,-1,0
  3946.7    0.07       0  4004.7    0.05       0  4944.9    0.07       0
  4978.6    0.07       0  4983.1    0.07       0  5313.9    0.16       0
  5395.6    0.07       0  5874.1   0.035       0  6097.4   0.045       0
Bank Sta=4978.6,4983.1
Exp/Cntr=0.3,0.1

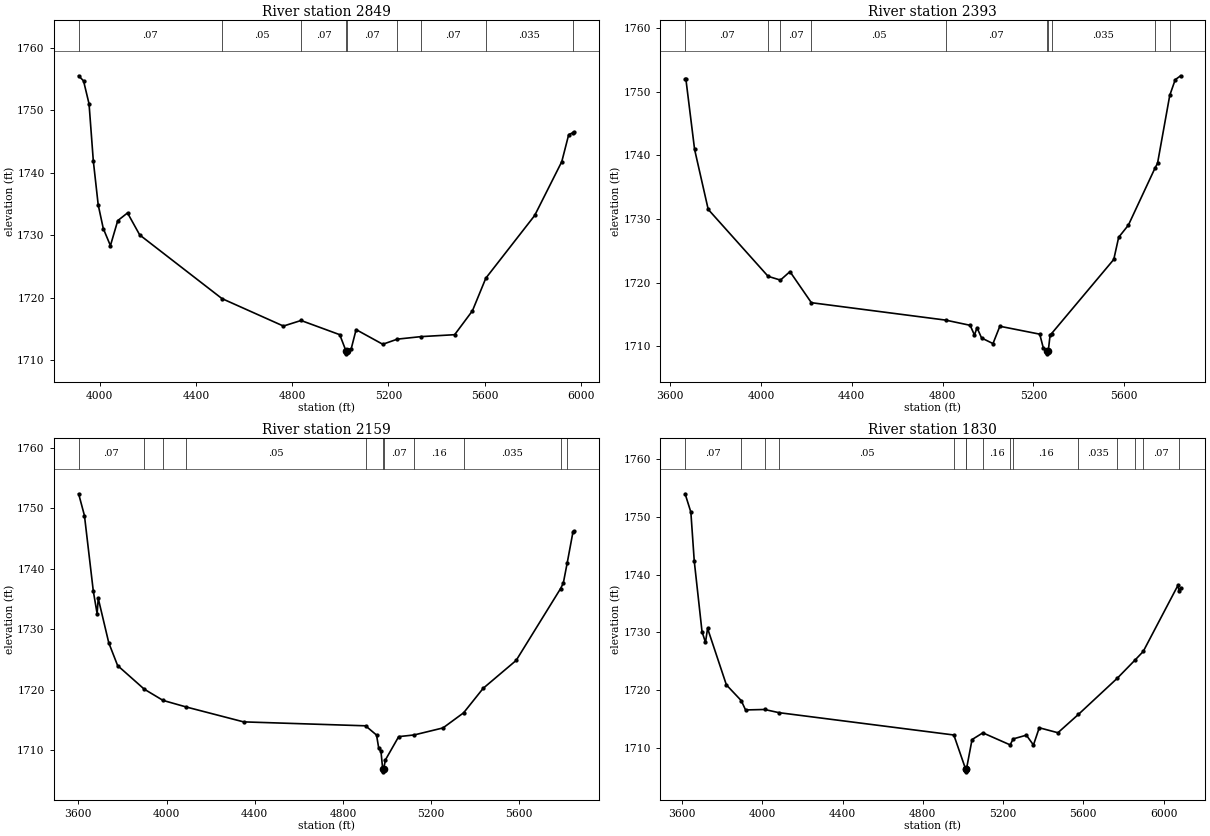
Type RM Length L Ch R = 1,2849,456,456,456
BEGIN DESCRIPTION:
Mapping XS 673c41d6
END DESCRIPTION:
XS GIS Cut Line= 4
      1506474.81      6924750.09      1507112.86      6924637.23
      1508219.64      6924498.35      1508506.08      6924418.05
#Sta/Elev= 30
  3911.8 1755.50  3932.3 1754.68  3955.1 1751.02  3972.9 1741.88  3993.2 1734.87
  4014.3 1731.09  4044.0 1728.35  4074.5 1732.35  4115.1 1733.58  4165.9 1730.06
  4507.9 1719.89  4763.5 1715.50  4836.8 1716.39  4997.8 1714.12  5023.3 1711.56
  5023.6 1711.06  5027.8 1711.56  5045.7 1711.91  5065.8 1714.93  5176.7 1712.59
  5237.4 1713.41  5335.3 1713.81  5475.6 1714.12  5549.6 1717.94  5605.2 1723.15
  5808.4 1733.17  5921.1 1741.77  5950.0 1746.10  5966.2 1746.38  5972.7 1746.53
#Mann=9,-1,0
  3911.8    0.07       0  4507.9    0.05       0  4836.8    0.07       0
  5023.3    0.07       0  5027.8    0.07       0  5237.4    0.16       0
  5335.3    0.07       0  5605.2   0.035       0  5966.2   0.045       0
Bank Sta=5023.3,5027.8
Exp/Cntr=0.3,0.1

Type RM Length L Ch R = 1,2393,234,234,234
BEGIN DESCRIPTION:
Mapping XS 1709a221
END DESCRIPTION:
XS GIS Cut Line= 5
      1506453.17      6924936.71      1507088.99      6924941.05
      1508087.26      6924834.72      1508312.95      6924719.70
      1508532.10      6924530.93
#Sta/Elev= 30
  3666.0 1752.00  3669.4 1752.00  3707.8 1740.94  3767.8 1731.52  4031.6 1721.01
  4085.8 1720.42  4127.8 1721.75  4222.1 1716.87  4812.8 1714.14  4921.3 1713.32
  4940.4 1711.78  4951.5 1712.95  4971.6 1711.33  5021.9 1710.45  5052.1 1713.17
  5227.8 1711.93  5243.1 1709.82  5261.0 1709.34  5261.3 1708.84  5265.5 1709.34
  5273.3 1711.75  5280.1 1712.03  5553.8 1723.66  5575.4 1727.14  5618.2 1729.05
  5736.1 1738.06  5746.5 1738.75  5800.4 1749.43  5824.5 1751.89  5848.3 1752.50
#Mann=10,-1,0
  3666.0    0.07       0  4031.6    0.16       0  4085.8    0.07       0
  4222.1    0.05       0  4812.8    0.07       0  5261.0    0.07       0
  5265.5    0.07       0  5280.1   0.035       0  5736.1    0.07       0
  5800.4   0.035       0
Bank Sta=5261,5265.5
Exp/Cntr=0.3,0.1

Type RM Length L Ch R = 1,2159,329,329,329
BEGIN DESCRIPTION:
Mapping XS eed44a70
END DESCRIPTION:
XS GIS Cut Line= 4
      1506498.69      6925036.54      1507364.60      6925101.64
      1508204.44      6925019.18      1508531.05      6924595.24
#Sta/Elev= 30
  3601.2 1752.43  3627.6 1748.82  3667.7 1736.35  3685.1 1732.60  3690.1 1735.14
  3737.9 1727.79  3778.0 1724.03  3898.7 1720.13  3984.0 1718.27  4089.4 1717.18
  4349.4 1714.72  4902.5 1714.07  4952.3 1712.54  4962.3 1710.36  4972.4 1709.83
  4980.1 1706.96  4980.5 1706.46  4984.7 1706.96  4992.5 1708.43  5052.7 1712.28
  5123.1 1712.56  5253.7 1713.72  5347.2 1716.22  5436.0 1720.27  5585.5 1724.88
  5787.0 1736.76  5799.3 1737.66  5816.9 1740.98  5842.8 1746.05  5848.6 1746.20
#Mann=11,-1,0
  3601.2    0.07       0  3898.7    0.16       0  3984.0    0.07       0
  4089.4    0.05       0  4902.5    0.07       0  4980.1    0.07       0
  4984.7    0.07       0  5123.1    0.16       0  5347.2   0.035       0
  5787.0    0.07       0  5816.9   0.035       0
Bank Sta=4980.1,4984.7
Exp/Cntr=0.3,0.1

Type RM Length L Ch R = 1,1830,0,0,0
BEGIN DESCRIPTION:
NC Unknown Stream 37 2.0
END DESCRIPTION:
XS GIS Cut Line= 5
      1506507.39      6925079.94      1507262.60      6925299.13
      1507855.00      6925338.00      1508052.53      6925338.19
      1508605.01      6924637.98
#Sta/Elev= 30
  3615.5 1753.98  3644.2 1750.81  3661.1 1742.36  3699.9 1730.13  3717.1 1728.29
  3727.5 1730.71  3821.3 1720.94  3895.1 1718.23  3916.8 1716.61  4011.6 1716.69
  4083.2 1716.14  4954.7 1712.28  5013.2 1706.41  5013.5 1705.91  5017.8 1706.41
  5045.5 1711.49  5099.3 1712.65  5235.3 1710.57  5250.4 1711.60  5316.2 1712.25
  5351.5 1710.55  5380.4 1713.53  5473.4 1712.67  5575.9 1715.85  5769.5 1722.10
  5856.4 1725.19  5898.5 1726.72  6071.4 1738.14  6076.9 1737.19  6085.0 1737.66
#Mann=15,-1,0
  3615.5    0.07       0  3895.1    0.16       0  4011.6    0.07       0
  4083.2    0.05       0  4954.7    0.07       0  5013.2    0.07       0
  5017.8    0.07       0  5099.3    0.16       0  5235.3    0.07       0
  5250.4    0.16       0  5575.9   0.035       0  5769.5    0.07       0
  5856.4   0.035       0  5898.5    0.07       0  6076.9   0.035       0
Bank Sta=5013.2,5017.8
Exp/Cntr=0.3,0.1

Chan Stop Cuts=-1