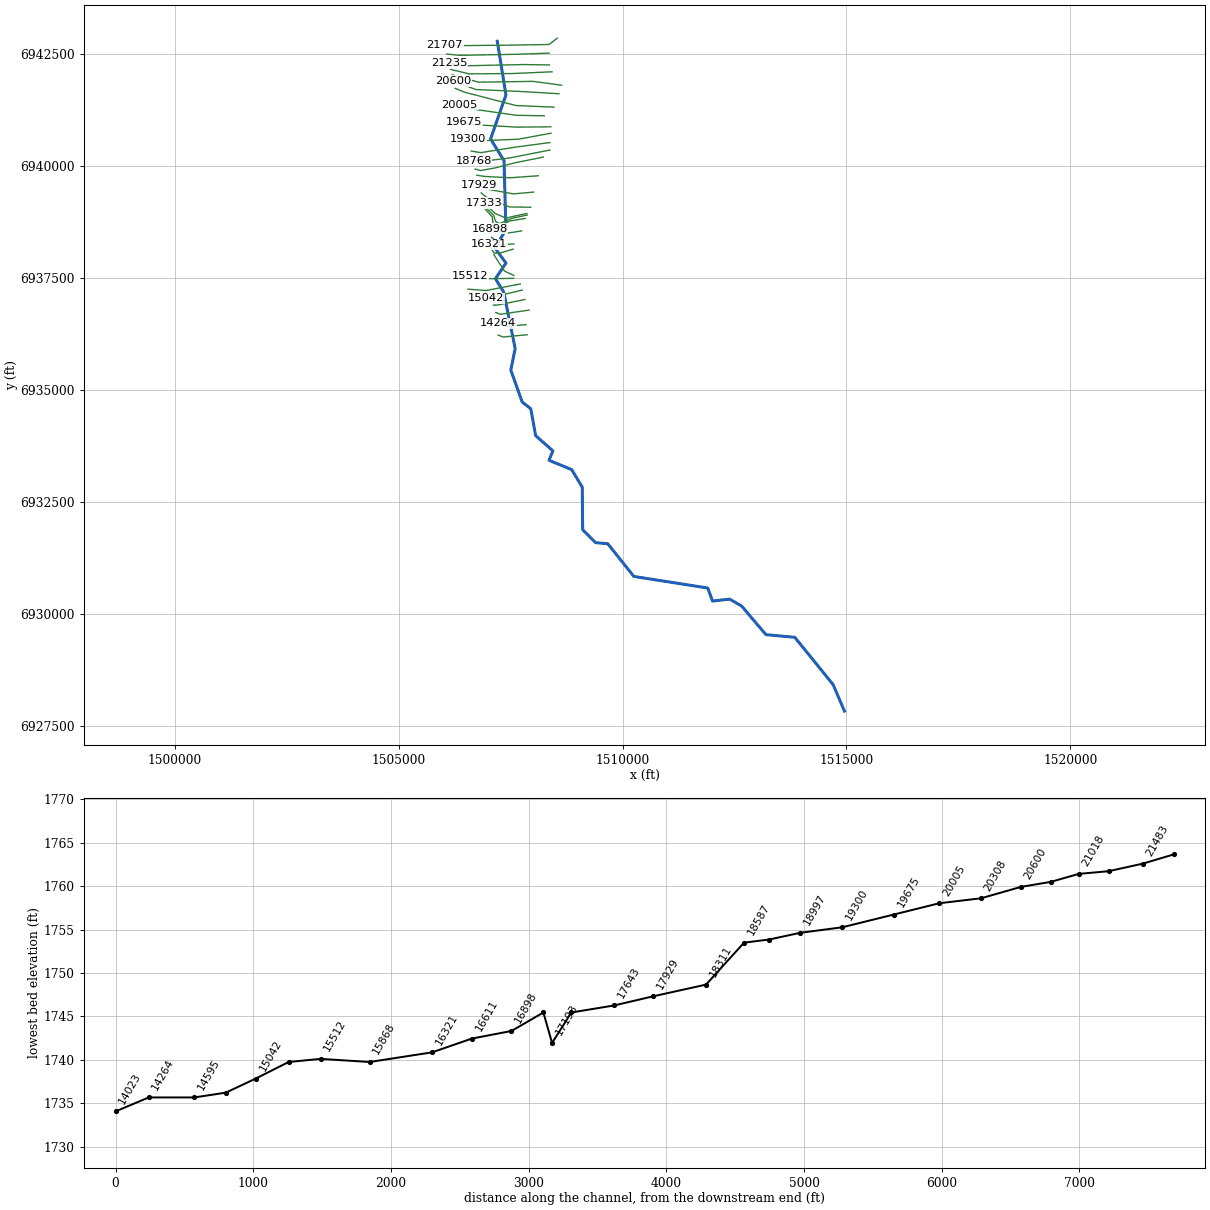
--- NC Unknown Stream 38.prj (project) ---

Proj Title=NC Unknown Stream 38 Base Level Engineering
Current Plan=p01
Default Exp/Contr=0.3,0.1
English Units
Geom File=g01
Flow File=f01
Plan File=p01
BEGIN DESCRIPTION:
NC Unknown Stream 38
END DESCRIPTION:

--- NC Unknown Stream 38.p01 (plan) ---

Plan Title=Multiple Run
Short Identifier=Multiple
Geom File=g01
Flow File=f01
Subcritical Flow
K Sum by GR= 0
Std Step Tol= 0.01
Critical Tol= 0.01
Num of Std Step Trials= 20
Max Error Tol= 0.3
Flow Tol Ratio= 0.001
Split Flow NTrial= 30
Split Flow Tol= 0.02
Split Flow Ratio= 0.02
Log Output Level= 0
Friction Slope Method= 1
Unsteady Friction Slope Method= 2
Unsteady Bridges Friction Slope Method= 1
Parabolic Critical Depth
Global Vel Dist=  1 , 1 , 1
Global Log Level= 0
CheckData=True
Encroach Param= -1, 0, 0, 0
BEGIN DESCRIPTION:
Multiple Run
END DESCRIPTION:

--- NC Unknown Stream 38.f01 (steady flow) ---

Flow Title=Multiple
Number of Profiles=7
Profile Names=10-year,25-year,50-year,1pct_min,100-year,1pct_plu,500-year
River Rch & RM= NC Unknown Strea,Reach-1,21707
     265     367     451     276     550    1097     828
River Rch & RM= NC Unknown Strea,Reach-1,20600
     349     490     608     374     747    1491    1143
River Rch & RM= NC Unknown Strea,Reach-1,15512
     459     652     815     505    1008    2012    1563
River Rch & RM= NC Unknown Strea,Reach-1,12738
     620     889    1116     695    1387    2768    2170
Boundary for River Rch & Prof#=NC Unknown Strea,Reach-1,1
Up Type=0
Dn Type=3
Dn Slope=0.001
Boundary for River Rch & Prof#=NC Unknown Strea,Reach-1,2
Up Type=0
Dn Type=3
Dn Slope=0.001
Boundary for River Rch & Prof#=NC Unknown Strea,Reach-1,3
Up Type=0
Dn Type=3
Dn Slope=0.001
Boundary for River Rch & Prof#=NC Unknown Strea,Reach-1,4
Up Type=0
Dn Type=3
Dn Slope=0.001
Boundary for River Rch & Prof#=NC Unknown Strea,Reach-1,5
Up Type=0
Dn Type=3
Dn Slope=0.001
Boundary for River Rch & Prof#=NC Unknown Strea,Reach-1,6
Up Type=0
Dn Type=3
Dn Slope=0.001
Boundary for River Rch & Prof#=NC Unknown Strea,Reach-1,7
Up Type=0
Dn Type=3
Dn Slope=0.001

--- NC Unknown Stream 38.g01 (geometry) ---

Geom Title=Existing Conditions

River Reach=NC Unknown Strea,Reach-1
Reach XY= 30
      1507205.00      6942788.00      1507397.47      6941587.99
      1507054.70      6940608.18      1507354.62      6940122.73
      1507397.45      6938588.00      1507154.61      6938167.87
      1507397.94      6937838.00      1507162.78      6937488.10
      1507347.11      6937191.58      1507603.80      6935927.50
      1507506.10      6935448.55      1507760.42      6934735.33
      1507951.87      6934586.38      1508060.75      6933985.63
      1508446.01      6933645.02      1508360.08      6933435.69
      1508865.11      6933227.62      1509101.39      6932836.50
      1509110.52      6931885.57      1509398.27      6931597.15
      1509672.13      6931571.70      1510252.70      6930843.09
      1511903.56      6930584.46      1512010.08      6930293.02
      1512394.71      6930337.00      1512661.17      6930180.14
      1513202.34      6929543.20      1513846.53      6929484.49
      1514701.49      6928429.52      1514955.00      6927838.00

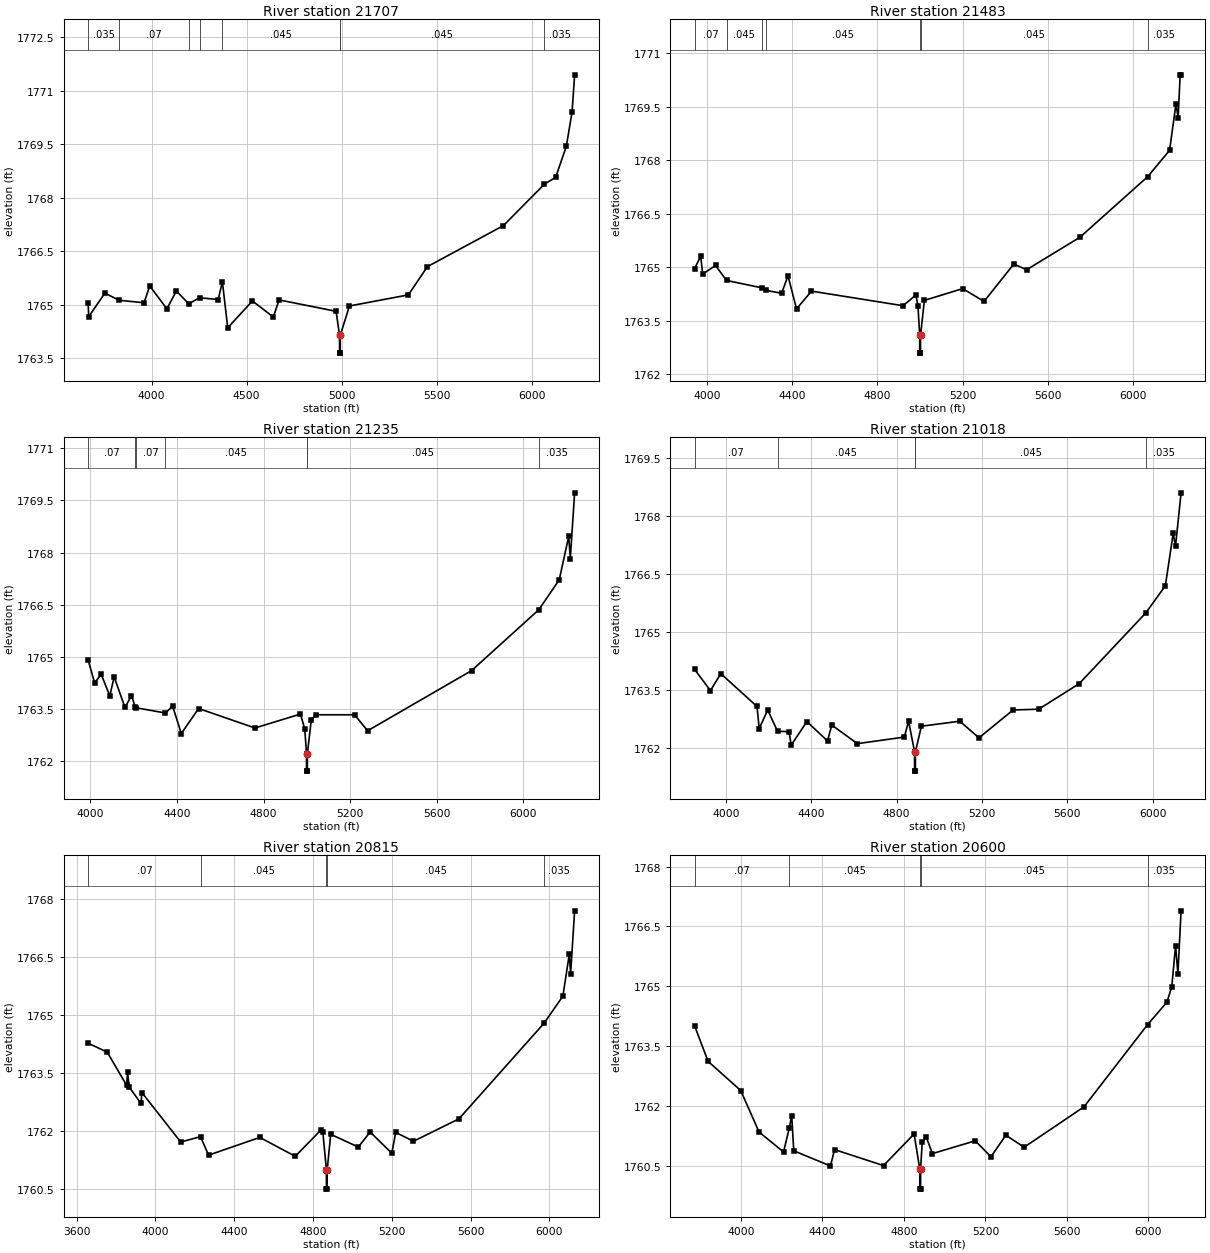
Type RM Length L Ch R = 1,21707,224,224,224
BEGIN DESCRIPTION:
Mapping XS fe72ffdf
END DESCRIPTION:
XS GIS Cut Line= 5
      1508541.90      6942855.34      1508359.66      6942715.74
      1507424.92      6942699.89      1506268.67      6942689.47
      1506031.66      6942712.91
#Sta/Elev= 30
  3666.0 1765.05  3669.1 1764.67  3754.3 1765.33  3828.1 1765.13  3960.2 1765.06
  3990.2 1765.53  4080.2 1764.89  4130.3 1765.39  4195.2 1765.03  4252.0 1765.20
  4350.3 1765.15  4372.2 1765.65  4400.3 1764.36  4530.3 1765.11  4640.3 1764.66
  4670.3 1765.14  4970.4 1764.82  4988.4 1764.15  4988.6 1763.65  4992.1 1763.65
  4992.4 1764.15  5040.4 1764.97  5350.4 1765.28  5450.4 1766.07  5850.4 1767.22
  6066.2 1768.38  6125.1 1768.57  6181.3 1769.44  6211.5 1770.40  6224.9 1771.44
#Mann=8,-1,0
  3666.0   0.035       0  3828.1    0.07       0  4195.2   0.045       0
  4252.0    0.07       0  4372.2   0.045       0  4988.4   0.045       0
  4992.4   0.045       0  6066.2   0.035       0
Bank Sta=4988.4,4992.4
Exp/Cntr=0.3,0.1

Type RM Length L Ch R = 1,21483,248,248,248
BEGIN DESCRIPTION:
Mapping XS 4557143d
END DESCRIPTION:
XS GIS Cut Line= 4
      1508363.42      6942523.00      1507628.04      6942496.76
      1506357.21      6942473.32      1506081.19      6942501.97
#Sta/Elev= 30
  3941.4 1764.96  3969.8 1765.31  3979.8 1764.81  4039.9 1765.05  4091.4 1764.63
  4258.6 1764.42  4277.0 1764.35  4350.1 1764.27  4380.1 1764.76  4420.1 1763.83
  4490.2 1764.33  4920.3 1763.92  4980.3 1764.22  4990.3 1763.92  4998.3 1763.09
  4998.6 1762.59  5002.1 1762.59  5002.3 1763.09  5020.4 1764.07  5200.4 1764.40
  5300.4 1764.04  5440.4 1765.09  5500.4 1764.93  5750.5 1765.84  6068.6 1767.54
  6171.7 1768.28  6201.9 1769.59  6211.9 1769.19  6221.4 1770.40  6225.8 1770.40
#Mann=7,-1,0
  3941.4    0.07       0  4091.4   0.045       0  4258.6    0.07       0
  4277.0   0.045       0  4998.3   0.045       0  5002.3   0.045       0
  6068.6   0.035       0
Bank Sta=4998.3,5002.3
Exp/Cntr=0.3,0.1

Type RM Length L Ch R = 1,21235,217,217,217
BEGIN DESCRIPTION:
Mapping XS 29e5525f
END DESCRIPTION:
XS GIS Cut Line= 4
      1508365.06      6942259.78      1507794.71      6942267.59
      1506419.71      6942238.95      1506125.45      6942298.84
#Sta/Elev= 30
  3990.2 1764.92  4020.3 1764.25  4050.3 1764.51  4090.3 1763.88  4110.3 1764.43
  4160.3 1763.55  4190.3 1763.89  4208.6 1763.55  4213.1 1763.54  4347.3 1763.39
  4380.3 1763.59  4420.3 1762.80  4500.3 1763.52  4760.4 1762.96  4970.4 1763.36
  4990.4 1762.93  4998.4 1762.22  4998.7 1761.72  5002.2 1761.72  5002.4 1762.22
  5020.4 1763.19  5040.4 1763.34  5220.5 1763.34  5280.5 1762.88  5760.6 1764.61
  6071.0 1766.36  6165.2 1767.22  6209.0 1768.47  6216.2 1767.83  6236.2 1769.72
#Mann=7,-1,0
  3990.2    0.07       0  4208.6   0.045       0  4213.1    0.07       0
  4347.3   0.045       0  4998.4   0.045       0  5002.4   0.045       0
  6071.0   0.035       0
Bank Sta=4998.4,5002.4
Exp/Cntr=0.3,0.1

Type RM Length L Ch R = 1,21018,203,203,203
BEGIN DESCRIPTION:
Mapping XS 337a648f
END DESCRIPTION:
XS GIS Cut Line= 4
      1508427.55      6942106.14      1507542.10      6942067.07
      1506575.96      6942059.26      1506159.63      6942160.74
#Sta/Elev= 30
  3853.0 1764.04  3927.4 1763.49  3975.7 1763.93  4145.8 1763.08  4156.0 1762.51
  4195.9 1762.99  4241.9 1762.44  4296.0 1762.43  4306.0 1762.08  4379.5 1762.69
  4476.2 1762.19  4496.2 1762.60  4616.3 1762.12  4836.4 1762.29  4856.4 1762.70
  4884.4 1761.91  4884.7 1761.41  4888.2 1761.41  4888.4 1761.91  4916.4 1762.57
  5096.4 1762.70  5186.4 1762.27  5346.4 1762.99  5466.4 1763.01  5656.4 1763.67
  5968.9 1765.50  6060.3 1766.20  6096.9 1767.55  6107.9 1767.23  6134.0 1768.60
#Mann=5,-1,0
  3853.0    0.07       0  4241.9   0.045       0  4884.4   0.045       0
  4888.4   0.045       0  5968.9   0.035       0
Bank Sta=4884.4,4888.4
Exp/Cntr=0.3,0.1

Type RM Length L Ch R = 1,20815,215,215,215
BEGIN DESCRIPTION:
Mapping XS 0ffbc26b
END DESCRIPTION:
XS GIS Cut Line= 4
      1508641.03      6941806.66      1508000.44      6941892.59
      1506784.29      6941874.37      1506199.20      6942038.19
#Sta/Elev= 30
  3658.1 1764.27  3755.0 1764.04  3853.5 1763.18  3858.6 1763.52  3866.0 1763.14
  3926.4 1762.71  3931.5 1762.99  4128.3 1761.71  4228.8 1761.85  4269.6 1761.37
  4529.9 1761.83  4709.9 1761.34  4839.9 1762.02  4849.9 1761.97  4867.9 1760.99
  4868.2 1760.49  4871.7 1760.49  4871.9 1760.99  4889.9 1761.91  5029.9 1761.58
  5090.0 1761.97  5200.0 1761.42  5220.0 1761.96  5310.0 1761.73  5540.7 1762.31
  5973.4 1764.79  6068.6 1765.49  6101.5 1766.58  6107.9 1766.07  6128.3 1767.70
#Mann=5,-1,0
  3658.1    0.07       0  4228.8   0.045       0  4867.9   0.045       0
  4871.9   0.045       0  5973.4   0.035       0
Bank Sta=4867.9,4871.9
Exp/Cntr=0.3,0.1

Type RM Length L Ch R = 1,20600,292,292,292
BEGIN DESCRIPTION:
Mapping XS acebf732
END DESCRIPTION:
XS GIS Cut Line= 4
      1508581.16      6941616.55      1507690.54      6941668.64
      1506724.39      6941710.30      1506229.83      6941900.32
#Sta/Elev= 30
  3772.0 1764.01  3838.3 1763.12  3998.5 1762.39  4088.7 1761.35  4208.9 1760.85
  4236.5 1761.44  4249.0 1761.75  4259.0 1760.88  4439.3 1760.50  4459.3 1760.91
  4699.7 1760.51  4849.9 1761.30  4877.9 1760.42  4878.1 1759.92  4881.6 1759.92
  4881.9 1760.42  4889.9 1761.10  4909.9 1761.22  4939.9 1760.81  5150.1 1761.13
  5227.4 1760.73  5300.3 1761.27  5390.4 1760.97  5684.1 1761.98  5996.4 1764.04
  6091.2 1764.60  6115.3 1764.99  6134.0 1766.02  6145.3 1765.31  6161.0 1766.89
#Mann=5,-1,0
  3772.0    0.07       0  4236.5   0.045       0  4877.9   0.045       0
  4881.9   0.045       0  5996.4   0.035       0
Bank Sta=4877.9,4881.9
Exp/Cntr=0.3,0.1

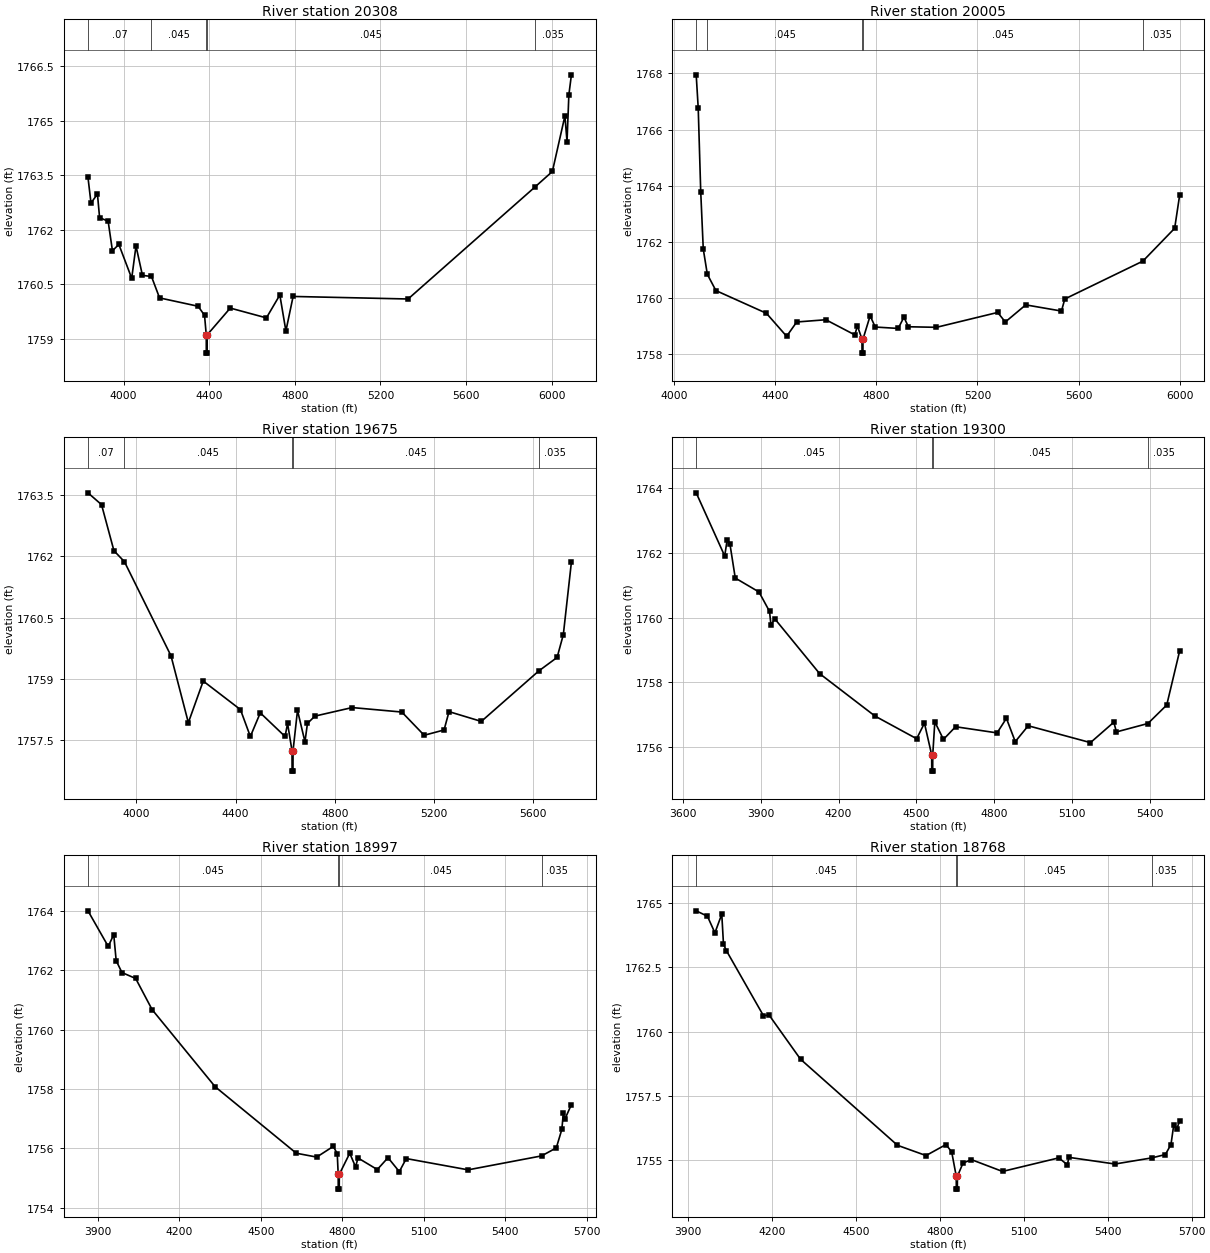
Type RM Length L Ch R = 1,20308,303,303,303
BEGIN DESCRIPTION:
Mapping XS f8c12a06
END DESCRIPTION:
XS GIS Cut Line= 4
      1508469.23      6941317.07      1507620.23      6941353.53
      1506466.58      6941653.01      1506266.08      6941736.34
#Sta/Elev= 30
  3833.6 1763.44  3847.8 1762.73  3877.9 1762.98  3887.9 1762.33  3927.9 1762.23
  3947.9 1761.42  3978.0 1761.59  4038.0 1760.66  4058.0 1761.55  4088.1 1760.74
  4130.3 1760.71  4168.1 1760.12  4348.3 1759.89  4378.3 1759.64  4386.3 1759.10
  4386.6 1758.60  4390.1 1758.60  4390.3 1759.10  4498.4 1759.84  4667.3 1759.57
  4730.1 1760.20  4758.4 1759.21  4792.1 1760.16  5329.3 1760.09  5923.6 1763.18
  6003.5 1763.60  6062.1 1765.13  6071.9 1764.42  6080.5 1765.71  6092.4 1766.26
#Mann=5,-1,0
  3833.6    0.07       0  4130.3   0.045       0  4386.3   0.045       0
  4390.3   0.045       0  5923.6   0.035       0
Bank Sta=4386.3,4390.3
Exp/Cntr=0.3,0.1

Type RM Length L Ch R = 1,20005,330,330,330
BEGIN DESCRIPTION:
Mapping XS 1e8ed88e
END DESCRIPTION:
XS GIS Cut Line= 4
      1508253.01      6941124.37      1507633.25      6941134.78
      1506591.58      6941283.22      1506366.74      6941373.67
#Sta/Elev= 30
  4086.1 1767.95  4094.1 1766.77  4104.1 1763.77  4114.1 1761.74  4130.2 1760.84
  4164.1 1760.26  4364.2 1759.45  4444.2 1758.63  4484.2 1759.14  4599.5 1759.22
  4714.3 1758.68  4724.4 1759.00  4742.6 1758.53  4742.8 1758.03  4746.3 1758.03
  4746.6 1758.53  4774.9 1759.36  4795.1 1758.96  4886.0 1758.91  4908.6 1759.31
  4926.4 1758.97  5037.5 1758.95  5279.9 1759.48  5310.2 1759.14  5391.1 1759.75
  5532.5 1759.53  5545.8 1759.96  5855.0 1761.31  5980.8 1762.48  6000.5 1763.66
#Mann=5,-1,0
  4086.1    0.07       0  4130.2   0.045       0  4742.6   0.045       0
  4746.6   0.045       0  5855.0   0.035       0
Bank Sta=4742.6,4746.6
Exp/Cntr=0.3,0.1

Type RM Length L Ch R = 1,19675,375,375,375
BEGIN DESCRIPTION:
Mapping XS f4772414
END DESCRIPTION:
XS GIS Cut Line= 4
      1508399.74      6940877.84      1507651.48      6940870.89
      1506661.89      6940926.45      1506459.37      6940981.84
#Sta/Elev= 30
  3804.4 1763.56  3859.1 1763.27  3909.1 1762.14  3951.4 1761.87  4139.2 1759.56
  4209.2 1757.92  4269.2 1758.94  4419.2 1758.24  4459.2 1757.58  4499.2 1758.16
  4599.2 1757.58  4609.3 1757.90  4627.2 1757.23  4627.5 1756.73  4631.1 1756.73
  4631.3 1757.23  4649.3 1758.22  4679.4 1757.45  4689.4 1757.90  4719.4 1758.08
  4869.7 1758.29  5070.0 1758.18  5160.1 1757.61  5240.3 1757.74  5260.3 1758.19
  5390.5 1757.95  5622.5 1759.19  5696.1 1759.52  5721.2 1760.08  5753.8 1761.86
#Mann=5,-1,0
  3804.4    0.07       0  3951.4   0.045       0  4627.2   0.045       0
  4631.3   0.045       0  5622.5   0.035       0
Bank Sta=4627.2,4631.3
Exp/Cntr=0.3,0.1

Type RM Length L Ch R = 1,19300,303,303,303
BEGIN DESCRIPTION:
Mapping XS a97bab7b
END DESCRIPTION:
XS GIS Cut Line= 4
      1508403.21      6940735.48      1507679.26      6940601.80
      1506656.69      6940560.13      1506558.86      6940599.60
#Sta/Elev= 30
  3650.9 1763.85  3760.9 1761.90  3770.4 1762.40  3781.3 1762.26  3801.6 1761.22
  3893.1 1760.79  3933.8 1760.19  3939.4 1759.77  3954.2 1759.96  4127.0 1758.27
  4340.6 1756.96  4501.4 1756.26  4531.5 1756.74  4559.4 1755.76  4559.7 1755.26
  4563.3 1755.26  4563.5 1755.76  4571.5 1756.78  4604.8 1756.24  4651.6 1756.63
  4811.7 1756.44  4847.7 1756.89  4881.8 1756.17  4931.8 1756.66  5172.0 1756.14
  5262.1 1756.77  5272.1 1756.47  5393.6 1756.73  5466.2 1757.30  5516.0 1758.97
#Mann=4,-1,0
  3650.9   0.045       0  4559.4   0.045       0  4563.5   0.045       0
  5393.6   0.035       0
Bank Sta=4559.4,4563.5
Exp/Cntr=0.3,0.1

Type RM Length L Ch R = 1,18997,229,229,229
BEGIN DESCRIPTION:
Mapping XS 226d7e0b
END DESCRIPTION:
XS GIS Cut Line= 4
      1508378.96      6940527.15      1507618.49      6940426.45
      1506832.03      6940301.45      1506620.18      6940337.92
#Sta/Elev= 30
  3864.5 1764.01  3939.1 1762.81  3959.3 1763.21  3968.3 1762.33  3989.5 1761.93
  4040.0 1761.73  4100.5 1760.68  4332.5 1758.08  4630.8 1755.84  4706.0 1755.71
  4766.8 1756.07  4781.5 1755.83  4785.0 1755.13  4785.2 1754.63  4788.8 1754.63
  4789.1 1755.13  4827.5 1755.84  4848.8 1755.38  4857.9 1755.68  4928.8 1755.29
  4968.2 1755.69  5009.8 1755.22  5035.5 1755.66  5262.9 1755.28  5533.2 1755.75
  5587.3 1756.02  5607.6 1756.64  5613.3 1757.19  5618.4 1756.98  5642.9 1757.48
#Mann=4,-1,0
  3864.5   0.045       0  4785.0   0.045       0  4789.1   0.045       0
  5533.2   0.035       0
Bank Sta=4785,4789.1
Exp/Cntr=0.3,0.1

Type RM Length L Ch R = 1,18768,181,181,181
BEGIN DESCRIPTION:
Mapping XS f644cd85
END DESCRIPTION:
XS GIS Cut Line= 4
      1508380.68      6940360.48      1507463.98      6940179.92
      1507054.26      6940131.31      1506674.06      6940119.16
#Sta/Elev= 30
  3929.9 1764.71  3970.0 1764.50  3996.8 1763.85  4021.3 1764.58  4027.4 1763.41
  4037.6 1763.16  4170.1 1760.62  4190.5 1760.64  4302.6 1758.92  4649.1 1755.56
  4751.1 1755.16  4822.4 1755.59  4842.8 1755.30  4859.1 1754.35  4859.3 1753.85
  4862.9 1753.85  4863.2 1754.35  4883.3 1754.87  4913.5 1755.00  5024.3 1754.54
  5225.7 1755.07  5255.9 1754.80  5261.7 1755.09  5426.1 1754.83  5558.3 1755.07
  5606.2 1755.20  5626.2 1755.59  5636.2 1756.36  5646.3 1756.18  5657.2 1756.51
#Mann=4,-1,0
  3929.9   0.045       0  4859.1   0.045       0  4863.2   0.045       0
  5558.3   0.035       0
Bank Sta=4859.1,4863.2
Exp/Cntr=0.3,0.1

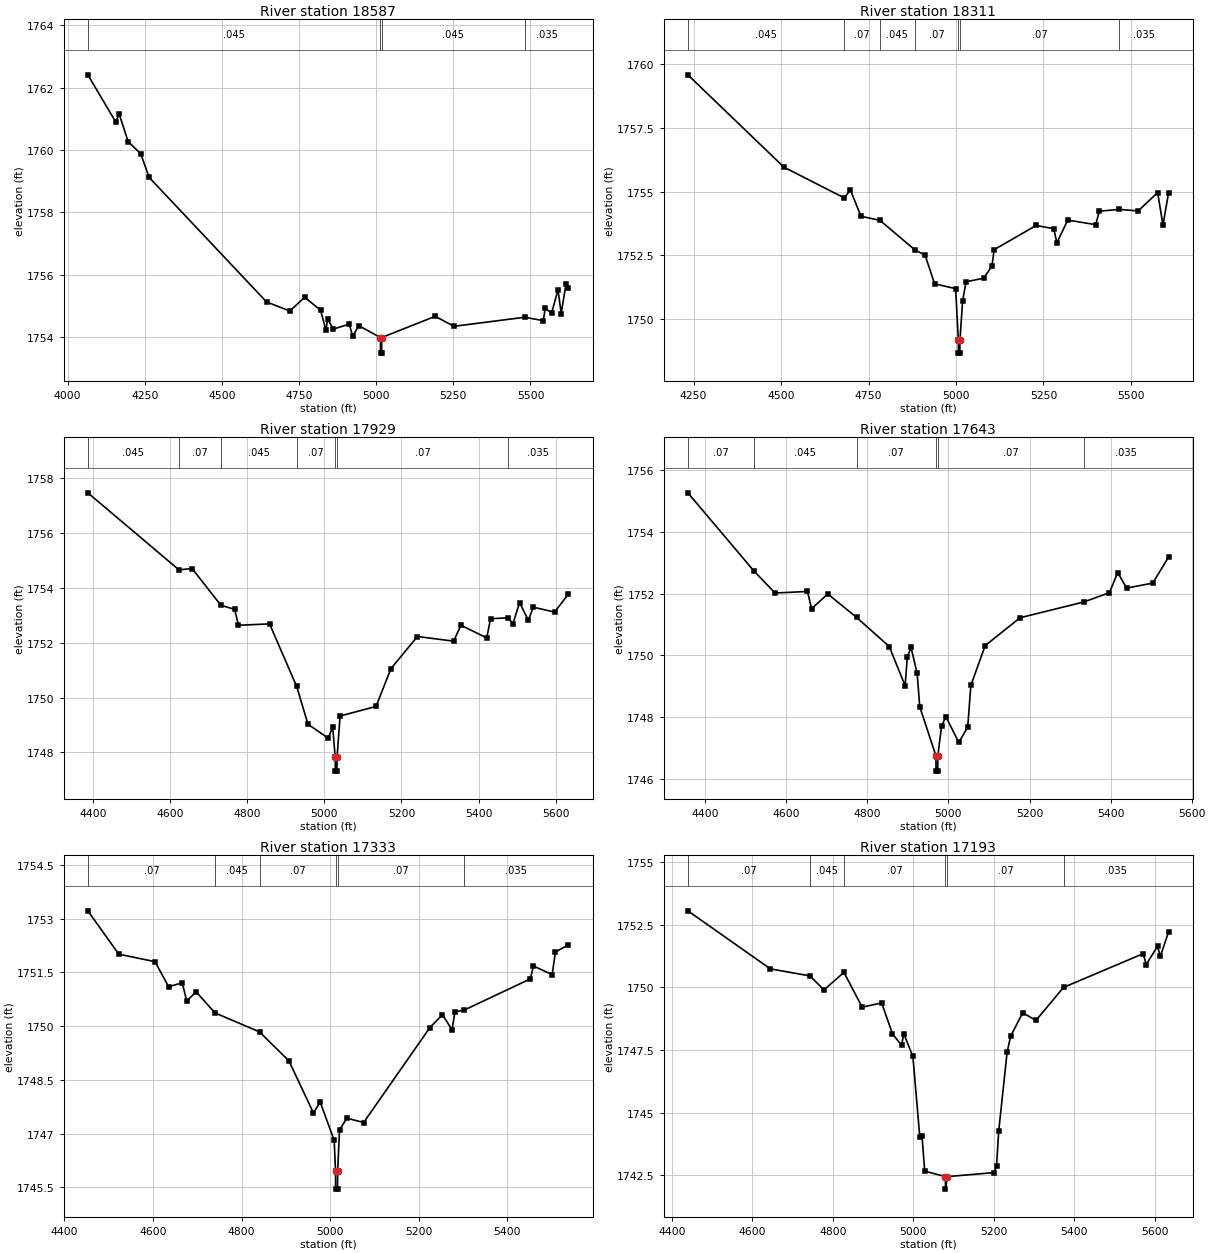
Type RM Length L Ch R = 1,18587,276,276,276
BEGIN DESCRIPTION:
Mapping XS 7fdb6fb8
END DESCRIPTION:
XS GIS Cut Line= 5
      1508233.08      6940202.49      1507609.81      6940077.49
      1507151.48      6939959.44      1506830.30      6939902.14
      1506712.24      6939935.13
#Sta/Elev= 30
  4065.5 1762.41  4155.3 1760.91  4167.6 1761.14  4196.1 1760.27  4236.9 1759.88
  4264.4 1759.12  4644.9 1755.13  4720.4 1754.84  4768.1 1755.28  4819.7 1754.87
  4837.3 1754.22  4842.5 1754.59  4861.0 1754.26  4912.7 1754.42  4923.9 1754.03
  4943.7 1754.37  5013.8 1753.99  5014.1 1753.49  5017.7 1753.49  5018.0 1753.99
  5191.2 1754.67  5252.2 1754.35  5481.8 1754.64  5541.8 1754.53  5547.8 1754.93
  5568.5 1754.77  5589.3 1755.52  5599.7 1754.76  5615.3 1755.71  5623.3 1755.58
#Mann=4,-1,0
  4065.5   0.045       0  5013.8   0.045       0  5018.0   0.045       0
  5481.8   0.035       0
Bank Sta=5013.8,5018
Exp/Cntr=0.3,0.1

Type RM Length L Ch R = 1,18311,382,382,382
BEGIN DESCRIPTION:
Mapping XS f5c77fe5
END DESCRIPTION:
XS GIS Cut Line= 4
      1508118.45      6939785.82      1507488.28      6939740.69
      1506924.05      6939770.20      1506749.32      6939797.88
#Sta/Elev= 30
  4233.6 1759.58  4507.8 1755.96  4680.5 1754.75  4698.2 1755.06  4728.3 1754.03
  4782.6 1753.87  4881.7 1752.72  4911.7 1752.50  4938.8 1751.38  4998.9 1751.19
  5006.6 1749.16  5006.9 1748.66  5010.8 1748.66  5011.2 1749.16  5018.9 1750.72
  5028.9 1751.46  5079.0 1751.60  5102.6 1752.07  5109.0 1752.72  5229.2 1753.67
  5279.2 1753.54  5288.4 1752.99  5319.3 1753.88  5399.4 1753.70  5409.4 1754.23
  5466.8 1754.30  5520.6 1754.24  5576.2 1754.96  5591.4 1753.69  5607.3 1754.93
#Mann=7,-1,0
  4233.6   0.045       0  4680.5    0.07       0  4782.6   0.045       0
  4881.7    0.07       0  5006.6    0.07       0  5011.2    0.07       0
  5466.8   0.035       0
Bank Sta=5006.6,5011.2
Exp/Cntr=0.3,0.1

Type RM Length L Ch R = 1,17929,286,286,286
BEGIN DESCRIPTION:
Mapping XS ea3fe81f
END DESCRIPTION:
XS GIS Cut Line= 4
      1508014.30      6939421.24      1507564.67      6939381.31
      1507031.69      6939476.80      1506802.52      6939586.17
#Sta/Elev= 30
  4386.6 1757.47  4623.1 1754.66  4657.0 1754.71  4731.7 1753.37  4767.4 1753.22
  4777.4 1752.64  4858.0 1752.69  4928.3 1750.41  4957.7 1749.03  5010.4 1748.52
  5021.7 1748.94  5028.3 1747.82  5028.6 1747.32  5032.7 1747.32  5033.1 1747.82
  5040.9 1749.33  5134.2 1749.68  5172.9 1751.06  5241.7 1752.23  5335.5 1752.06
  5354.3 1752.64  5421.4 1752.18  5431.2 1752.88  5476.1 1752.91  5489.4 1752.70
  5506.6 1753.47  5529.3 1752.82  5542.0 1753.30  5597.3 1753.12  5633.4 1753.78
#Mann=7,-1,0
  4386.6   0.045       0  4623.1    0.07       0  4731.7   0.045       0
  4928.3    0.07       0  5028.3    0.07       0  5033.1    0.07       0
  5476.1   0.035       0
Bank Sta=5028.3,5033.1
Exp/Cntr=0.3,0.1

Type RM Length L Ch R = 1,17643,310,310,310
BEGIN DESCRIPTION:
Mapping XS 75cb1cce
END DESCRIPTION:
XS GIS Cut Line= 4
      1507950.06      6939082.70      1507476.13      6939089.64
      1506998.70      6939278.88      1506844.72      6939403.45
#Sta/Elev= 30
  4357.3 1755.26  4519.8 1752.74  4572.4 1752.02  4652.4 1752.07  4662.4 1751.51
  4702.4 1751.99  4773.6 1751.23  4854.0 1750.29  4893.2 1749.02  4898.5 1749.94
  4907.8 1750.26  4922.9 1749.42  4929.3 1748.34  4969.1 1746.76  4969.5 1746.26
  4973.6 1746.26  4974.0 1746.76  4983.1 1747.72  4993.8 1748.02  5025.5 1747.19
  5047.6 1747.68  5055.3 1749.03  5090.7 1750.32  5176.7 1751.22  5333.9 1751.73
  5396.9 1752.03  5417.7 1752.68  5439.6 1752.18  5504.0 1752.34  5542.9 1753.18
#Mann=6,-1,0
  4357.3    0.07       0  4519.8   0.045       0  4773.6    0.07       0
  4969.1    0.07       0  4974.0    0.07       0  5333.9   0.035       0
Bank Sta=4969.1,4974
Exp/Cntr=0.3,0.1

Type RM Length L Ch R = 1,17333,140,140,140
BEGIN DESCRIPTION:
Mapping XS cb5cf6a1
END DESCRIPTION:
XS GIS Cut Line= 5
      1507863.33      6938943.82      1507502.17      6938865.69
      1507403.21      6938837.91      1507158.42      6938943.81
      1506903.23      6939178.17
#Sta/Elev= 30
  4452.8 1753.22  4522.7 1752.01  4604.6 1751.80  4635.3 1751.10  4666.0 1751.21
  4676.2 1750.70  4697.4 1750.96  4740.0 1750.37  4840.6 1749.84  4907.0 1749.03
  4962.2 1747.58  4977.6 1747.88  5009.2 1746.81  5012.2 1745.95  5012.5 1745.45
  5016.7 1745.45  5017.1 1745.95  5021.2 1747.11  5038.1 1747.43  5075.7 1747.31
  5225.3 1749.96  5253.7 1750.32  5275.2 1749.90  5282.0 1750.40  5303.0 1750.45
  5452.2 1751.32  5459.0 1751.68  5501.5 1751.44  5508.7 1752.07  5538.3 1752.27
#Mann=6,-1,0
  4452.8    0.07       0  4740.0   0.045       0  4840.6    0.07       0
  5012.2    0.07       0  5017.1    0.07       0  5303.0   0.035       0
Bank Sta=5012.2,5017.1
Exp/Cntr=0.3,0.1

Type RM Length L Ch R = 1,17193,63,63,63
BEGIN DESCRIPTION:
Mapping XS f1d59571
END DESCRIPTION:
XS GIS Cut Line= 6
      1507875.39      6938910.81      1507533.42      6938836.17
      1507255.64      6938718.12      1507165.37      6938766.73
      1507125.44      6938900.41      1506917.10      6939108.74
#Sta/Elev= 30
  4439.7 1753.06  4644.8 1750.74  4743.3 1750.46  4777.9 1749.90  4827.6 1750.60
  4872.8 1749.21  4921.3 1749.38  4948.2 1748.14  4970.8 1747.69  4976.3 1748.15
  4998.9 1747.24  5016.0 1744.03  5021.5 1744.08  5028.2 1742.66  5079.6 1742.44
  5079.9 1741.94  5084.5 1742.44  5200.4 1742.60  5206.7 1742.86  5212.2 1744.27
  5233.1 1747.42  5241.8 1748.05  5271.8 1748.99  5304.6 1748.68  5373.2 1750.00
  5571.4 1751.35  5578.5 1750.91  5606.8 1751.64  5613.8 1751.24  5634.1 1752.21
#Mann=6,-1,0
  4439.7    0.07       0  4743.3   0.045       0  4827.6    0.07       0
  5079.6    0.07       0  5084.5    0.07       0  5373.2   0.035       0
Bank Sta=5079.6,5084.5
Exp/Cntr=0.3,0.1

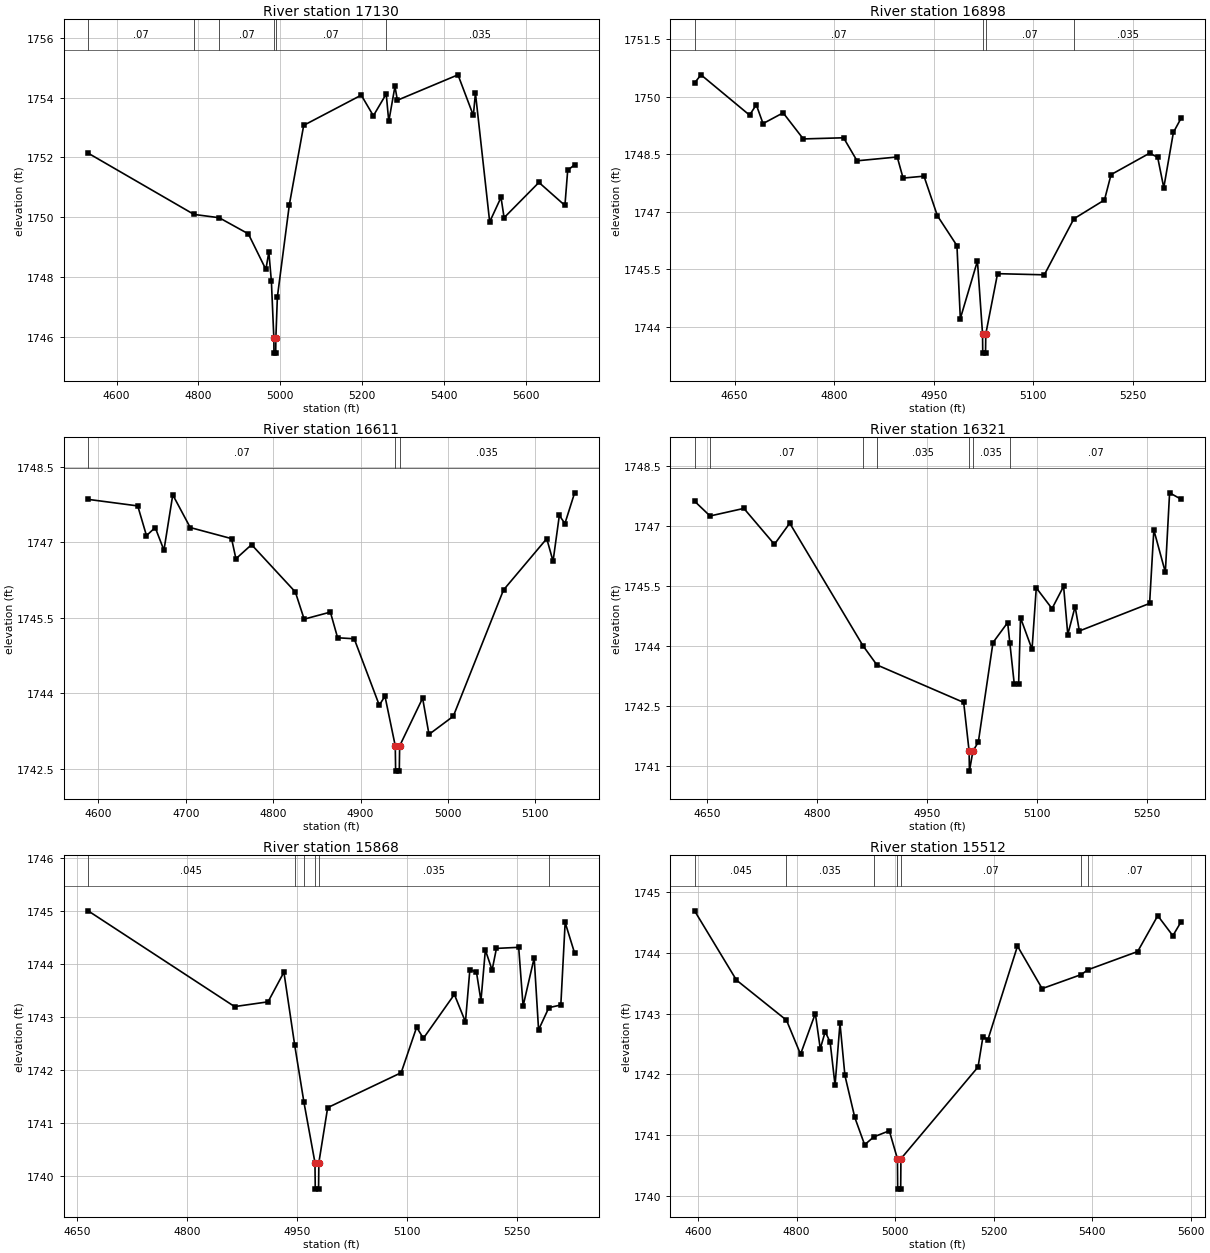
Type RM Length L Ch R = 1,17130,232,232,232
BEGIN DESCRIPTION:
Mapping XS 2d1b7e8d
END DESCRIPTION:
XS GIS Cut Line= 6
      1507828.55      6938832.70      1507481.34      6938777.14
      1507226.13      6938636.52      1507111.55      6938699.02
      1507092.45      6938867.42      1506934.50      6939041.00
#Sta/Elev= 30
  4530.4 1752.14  4789.0 1750.09  4850.5 1749.98  4921.8 1749.44  4964.6 1748.25
  4971.9 1748.83  4978.1 1747.85  4984.1 1745.95  4984.4 1745.45  4988.6 1745.45
  4989.0 1745.95  4992.7 1747.33  5022.0 1750.42  5057.0 1753.07  5197.6 1754.08
  5227.2 1753.39  5258.6 1754.12  5264.8 1753.20  5279.9 1754.37  5285.9 1753.91
  5433.9 1754.76  5471.4 1753.40  5476.5 1754.15  5511.3 1749.84  5539.0 1750.66
  5546.5 1749.98  5631.6 1751.16  5695.1 1750.39  5701.9 1751.57  5718.8 1751.75
#Mann=6,-1,0
  4530.4    0.07       0  4789.0   0.045       0  4850.5    0.07       0
  4984.1    0.07       0  4989.0    0.07       0  5258.6   0.035       0
Bank Sta=4984.1,4989
Exp/Cntr=0.3,0.1

Type RM Length L Ch R = 1,16898,287,287,287
BEGIN DESCRIPTION:
Mapping XS 10621e3d
END DESCRIPTION:
XS GIS Cut Line= 4
      1507746.93      6938554.92      1507458.77      6938509.78
      1507120.23      6938551.45      1507035.19      6938605.25
#Sta/Elev= 30
  4589.6 1750.36  4599.3 1750.57  4672.5 1749.52  4682.6 1749.79  4692.8 1749.30
  4723.1 1749.58  4753.5 1748.90  4814.2 1748.93  4834.5 1748.33  4895.1 1748.43
  4903.9 1747.88  4935.4 1747.93  4955.6 1746.90  4985.1 1746.12  4990.2 1744.22
  5016.0 1745.72  5023.7 1743.82  5024.0 1743.32  5028.2 1743.32  5028.6 1743.82
  5046.3 1745.39  5116.8 1745.36  5161.4 1746.82  5207.5 1747.31  5217.4 1747.97
  5275.7 1748.53  5287.7 1748.42  5296.9 1747.63  5311.4 1749.07  5323.0 1749.44
#Mann=4,-1,0
  4589.6    0.07       0  5023.7    0.07       0  5028.6    0.07       0
  5161.4   0.035       0
Bank Sta=5023.7,5028.6
Exp/Cntr=0.3,0.1

Type RM Length L Ch R = 1,16611,290,290,290
BEGIN DESCRIPTION:
Mapping XS 45c2bfae
END DESCRIPTION:
XS GIS Cut Line= 3
      1507571.61      6938264.99      1507283.42      6938244.16
      1507075.88      6938413.65
#Sta/Elev= 30
  4588.2 1747.85  4645.0 1747.72  4655.0 1747.13  4665.0 1747.29  4675.0 1746.84
  4685.1 1747.94  4705.1 1747.29  4752.4 1747.07  4757.4 1746.67  4775.3 1746.95
  4825.4 1746.01  4835.5 1745.47  4865.5 1745.61  4873.8 1745.10  4892.8 1745.08
  4921.5 1743.76  4928.0 1743.94  4939.8 1742.95  4940.2 1742.45  4944.4 1742.45
  4944.8 1742.95  4971.1 1743.90  4978.4 1743.18  5006.2 1743.54  5063.7 1746.05
  5113.2 1747.07  5120.4 1746.62  5127.6 1747.53  5134.0 1747.37  5145.1 1747.98
#Mann=3,-1,0
  4588.2    0.07       0  4939.8   0.035       0  4944.8   0.035       0
Bank Sta=4939.8,4944.8
Exp/Cntr=0.3,0.1

Type RM Length L Ch R = 1,16321,453,453,453
BEGIN DESCRIPTION:
Mapping XS 44072002
END DESCRIPTION:
XS GIS Cut Line= 4
      1507559.44      6938148.66      1507264.33      6938060.13
      1507132.09      6938058.52      1507019.41      6938251.93
#Sta/Elev= 30
  4632.6 1747.62  4653.7 1747.25  4699.9 1747.44  4741.6 1746.54  4762.5 1747.07
  4862.5 1744.00  4881.5 1743.52  5000.0 1742.58  5007.4 1741.36  5007.8 1740.86
  5012.6 1741.36  5020.0 1741.59  5040.0 1744.08  5060.0 1744.58  5063.0 1744.07
  5069.0 1743.05  5075.0 1743.05  5077.6 1744.70  5093.3 1743.91  5099.1 1745.45
  5120.6 1744.93  5136.4 1745.49  5142.1 1744.28  5152.1 1744.98  5157.9 1744.37
  5253.8 1745.06  5259.6 1746.90  5275.3 1745.84  5281.1 1747.83  5296.8 1747.67
#Mann=7,-1,0
  4632.6   0.045       0  4653.7    0.07       0  4862.5   0.045       0
  4881.5   0.035       0  5007.4   0.035       0  5012.6   0.035       0
  5063.0    0.07       0
Bank Sta=5007.4,5012.6
Exp/Cntr=0.3,0.1

Type RM Length L Ch R = 1,15868,356,356,356
BEGIN DESCRIPTION:
Mapping XS e170f935
END DESCRIPTION:
XS GIS Cut Line= 3
      1507575.10      6937560.12      1507365.02      6937659.09
      1507130.66      6938020.18
#Sta/Elev= 30
  4665.3 1745.01  4864.8 1743.20  4910.4 1743.29  4932.0 1743.85  4946.6 1742.48
  4959.3 1741.39  4974.3 1740.25  4974.7 1739.75  4979.2 1739.75  4979.6 1740.25
  4991.6 1741.29  5091.7 1741.95  5112.8 1742.81  5122.0 1742.60  5164.2 1743.43
  5179.3 1742.91  5185.3 1743.90  5194.3 1743.85  5200.4 1743.31  5206.4 1744.27
  5215.6 1743.89  5221.5 1744.30  5251.8 1744.32  5257.8 1743.21  5272.9 1744.12
  5278.9 1742.76  5292.9 1743.18  5309.2 1743.23  5315.1 1744.79  5328.0 1744.21
#Mann=6,-1,0
  4665.3   0.045       0  4946.6    0.07       0  4959.3   0.035       0
  4974.3   0.035       0  4979.6   0.035       0  5292.9    0.07       0
Bank Sta=4974.3,4979.6
Exp/Cntr=0.3,0.1

Type RM Length L Ch R = 1,15512,232,232,232
BEGIN DESCRIPTION:
Mapping XS c0c4c443
END DESCRIPTION:
XS GIS Cut Line= 3
      1507569.86      6937495.89      1506851.13      6937485.48
      1506588.64      6937539.01
#Sta/Elev= 30
  4593.2 1744.69  4678.1 1743.55  4779.6 1742.89  4808.1 1742.33  4838.1 1743.00
  4848.1 1742.42  4858.1 1742.70  4868.1 1742.53  4878.1 1741.82  4888.1 1742.84
  4898.1 1741.98  4918.1 1741.29  4938.1 1740.84  4956.7 1740.97  4988.1 1741.07
  5004.6 1740.61  5005.1 1740.11  5011.2 1740.11  5011.7 1740.61  5168.1 1742.12
  5178.1 1742.62  5188.1 1742.57  5248.1 1744.11  5298.1 1743.41  5377.1 1743.64
  5390.9 1743.72  5491.8 1744.02  5532.6 1744.61  5563.2 1744.28  5579.9 1744.51
#Mann=7,-1,0
  4593.2   0.045       0  4779.6   0.035       0  4956.7    0.07       0
  5004.6    0.07       0  5011.7    0.07       0  5377.1   0.035       0
  5390.9    0.07       0
Bank Sta=5004.6,5011.7
Exp/Cntr=0.3,0.1

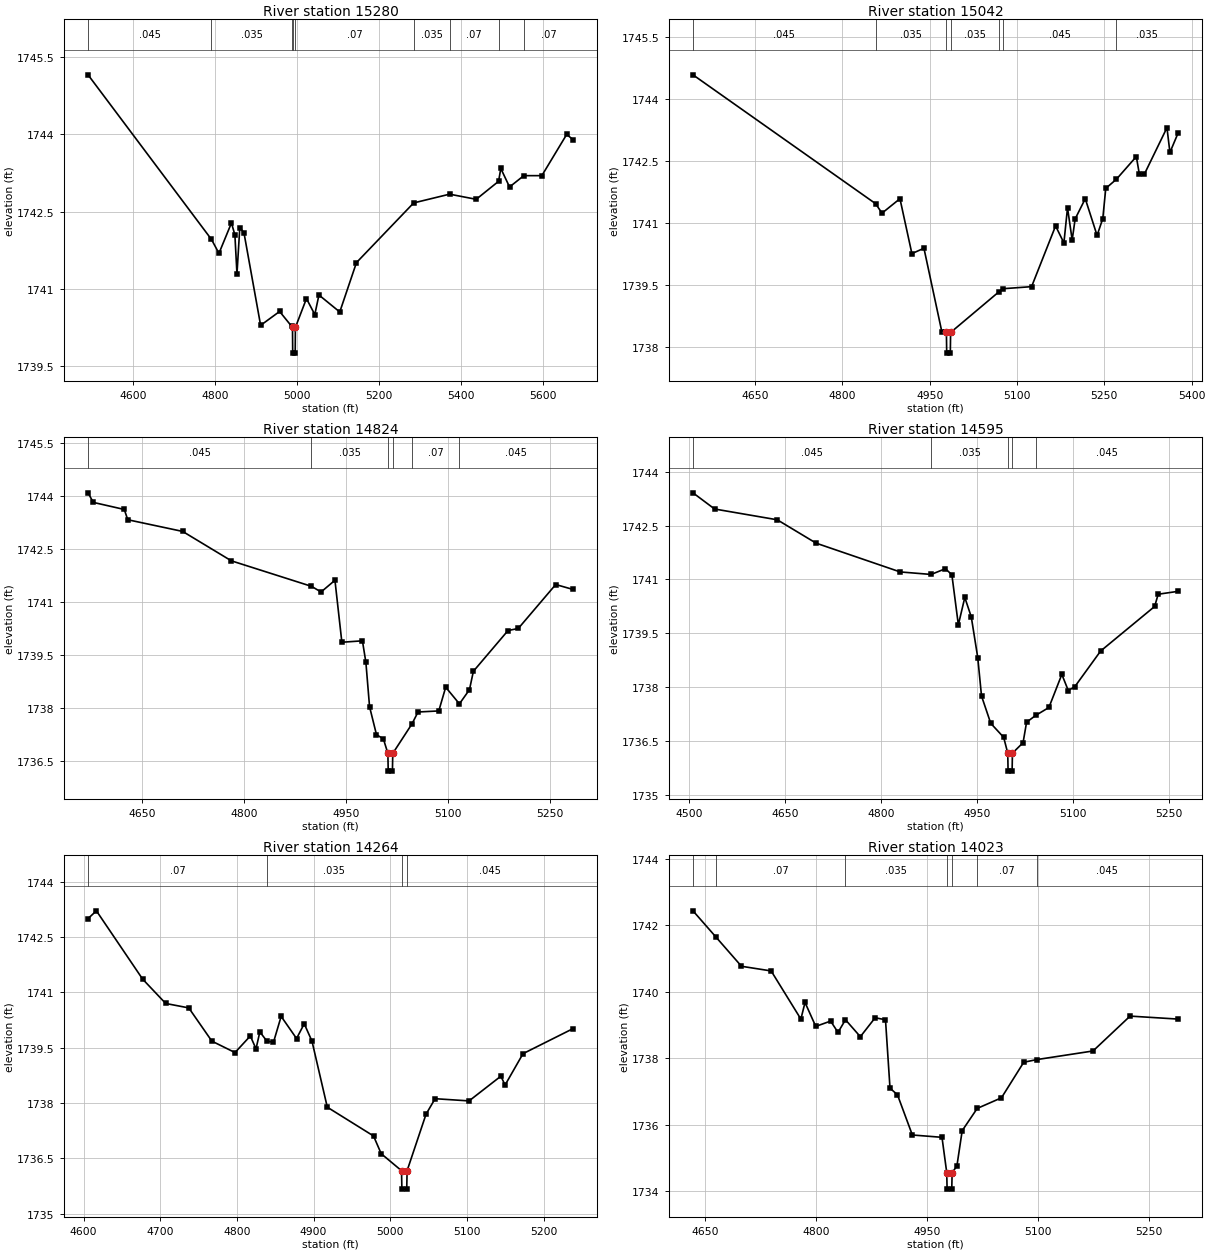
Type RM Length L Ch R = 1,15280,238,238,238
BEGIN DESCRIPTION:
Mapping XS 0333c30d
END DESCRIPTION:
XS GIS Cut Line= 3
      1507719.22      6937370.90      1506955.30      6937225.06
      1506548.68      6937254.47
#Sta/Elev= 30
  4489.3 1745.16  4790.9 1741.96  4809.2 1741.69  4839.7 1742.28  4848.1 1742.05
  4853.2 1741.29  4860.1 1742.19  4870.3 1742.09  4911.0 1740.29  4957.4 1740.56
  4986.9 1740.27  4988.9 1740.25  4989.4 1739.75  4995.5 1739.75  4996.0 1740.25
  5023.0 1740.81  5043.4 1740.50  5053.5 1740.88  5104.4 1740.55  5145.2 1741.51
  5285.0 1742.67  5372.8 1742.84  5437.8 1742.74  5492.5 1743.09  5497.9 1743.34
  5519.3 1742.98  5554.1 1743.20  5598.2 1743.20  5658.8 1744.00  5674.7 1743.90
#Mann=9,-1,0
  4489.3   0.045       0  4790.9   0.035       0  4986.9    0.07       0
  4988.9    0.07       0  4996.0    0.07       0  5285.0   0.035       0
  5372.8    0.07       0  5492.5   0.035       0  5554.1    0.07       0
Bank Sta=4988.9,4996
Exp/Cntr=0.3,0.1

Type RM Length L Ch R = 1,15042,218,218,218
BEGIN DESCRIPTION:
Mapping XS ac14cbfe
END DESCRIPTION:
XS GIS Cut Line= 3
      1507760.82      6937233.73      1507141.06      6937086.17
      1506948.31      6937050.03
#Sta/Elev= 30
  4543.5 1744.59  4857.1 1741.47  4868.2 1741.24  4899.0 1741.59  4919.5 1740.26
  4940.2 1740.39  4970.9 1738.37  4978.8 1738.35  4979.3 1737.85  4985.5 1737.85
  4986.0 1738.35  5069.4 1739.34  5076.1 1739.41  5125.1 1739.46  5166.3 1740.93
  5180.6 1740.52  5186.8 1741.37  5194.8 1740.59  5199.9 1741.10  5217.3 1741.59
  5237.6 1740.70  5247.4 1741.11  5252.5 1741.84  5270.7 1742.06  5305.0 1742.61
  5310.1 1742.19  5319.0 1742.19  5357.6 1743.31  5362.7 1742.71  5376.7 1743.18
#Mann=7,-1,0
  4543.5   0.045       0  4857.1   0.035       0  4978.8   0.035       0
  4986.0   0.035       0  5069.4    0.07       0  5076.1   0.045       0
  5270.7   0.035       0
Bank Sta=4978.8,4986
Exp/Cntr=0.3,0.1

Type RM Length L Ch R = 1,14824,229,229,229
BEGIN DESCRIPTION:
Mapping XS 73392520
END DESCRIPTION:
XS GIS Cut Line= 3
      1507821.65      6937023.68      1507200.09      6936898.67
      1507119.29      6936898.67
#Sta/Elev= 30
  4569.9 1744.08  4577.6 1743.81  4623.3 1743.61  4628.4 1743.32  4709.3 1742.99
  4781.0 1742.16  4899.0 1741.44  4913.3 1741.28  4933.7 1741.61  4943.9 1739.86
  4974.2 1739.90  4979.3 1739.29  4984.7 1738.04  4994.9 1737.25  5005.1 1737.13
  5011.7 1736.72  5012.2 1736.22  5018.4 1736.22  5018.9 1736.72  5047.4 1737.56
  5056.1 1737.89  5086.7 1737.92  5096.9 1738.59  5117.1 1738.12  5131.9 1738.52
  5137.7 1739.04  5188.7 1740.19  5203.9 1740.25  5259.0 1741.49  5284.7 1741.35
#Mann=6,-1,0
  4569.9   0.045       0  4899.0   0.035       0  5011.7   0.035       0
  5018.9   0.035       0  5047.4    0.07       0  5117.1   0.045       0
Bank Sta=5011.7,5018.9
Exp/Cntr=0.3,0.1

Type RM Length L Ch R = 1,14595,331,331,331
BEGIN DESCRIPTION:
Mapping XS c7ab9b73
END DESCRIPTION:
XS GIS Cut Line= 3
      1507915.38      6936787.56      1507278.21      6936695.55
      1507170.47      6936733.17
#Sta/Elev= 30
  4505.8 1743.41  4539.6 1742.96  4637.5 1742.66  4698.2 1742.01  4829.5 1741.21
  4877.9 1741.14  4900.2 1741.30  4910.3 1741.13  4920.4 1739.74  4930.5 1740.50
  4940.6 1739.96  4950.7 1738.83  4956.6 1737.76  4971.0 1737.00  4991.2 1736.61
  4997.6 1736.17  4998.1 1735.67  5004.4 1735.67  5004.9 1736.17  5021.5 1736.46
  5027.0 1737.03  5041.3 1737.22  5061.9 1737.44  5082.1 1738.36  5092.2 1737.91
  5102.4 1738.02  5142.7 1739.01  5227.1 1740.25  5232.6 1740.59  5263.7 1740.67
#Mann=5,-1,0
  4505.8   0.045       0  4877.9   0.035       0  4997.6   0.035       0
  5004.9   0.035       0  5041.3   0.045       0
Bank Sta=4997.6,5004.9
Exp/Cntr=0.3,0.1

Type RM Length L Ch R = 1,14264,241,241,241
BEGIN DESCRIPTION:
Mapping XS b725f7aa
END DESCRIPTION:
XS GIS Cut Line= 3
      1507845.88      6936462.90      1507384.12      6936421.24
      1507228.90      6936488.50
#Sta/Elev= 30
  4605.8 1743.00  4616.7 1743.21  4677.0 1741.36  4707.1 1740.70  4737.2 1740.58
  4767.3 1739.68  4797.5 1739.37  4817.5 1739.82  4824.9 1739.47  4829.9 1739.93
  4839.1 1739.68  4847.7 1739.65  4857.7 1740.35  4877.8 1739.75  4887.8 1740.15
  4897.9 1739.68  4917.9 1737.89  4978.2 1737.11  4988.2 1736.63  5014.7 1736.17
  5015.2 1735.67  5021.5 1735.67  5022.0 1736.17  5046.7 1737.70  5058.5 1738.12
  5102.8 1738.06  5144.3 1738.73  5149.8 1738.49  5173.2 1739.34  5238.6 1740.02
#Mann=4,-1,0
  4605.8    0.07       0  4839.1   0.035       0  5014.7   0.035       0
  5022.0   0.045       0
Bank Sta=5014.7,5022
Exp/Cntr=0.3,0.1

Type RM Length L Ch R = 1,14023,176,176,176
BEGIN DESCRIPTION:
Mapping XS ff04e1bd
END DESCRIPTION:
XS GIS Cut Line= 3
      1507870.27      6936237.22      1507333.77      6936186.87
      1507224.39      6936228.53
#Sta/Elev= 30
  4633.1 1742.44  4663.8 1741.66  4698.7 1740.77  4738.8 1740.63  4779.0 1739.18
  4784.6 1739.68  4799.1 1738.96  4819.2 1739.12  4829.2 1738.78  4839.3 1739.16
  4859.4 1738.65  4879.4 1739.22  4893.4 1739.16  4899.5 1737.10  4909.6 1736.90
  4929.7 1735.69  4969.8 1735.62  4976.2 1734.56  4976.7 1734.06  4983.0 1734.06
  4983.5 1734.56  4989.9 1734.75  4997.1 1735.82  5017.4 1736.49  5050.2 1736.81
  5080.3 1737.88  5097.8 1737.96  5174.0 1738.22  5224.1 1739.27  5289.0 1739.18
#Mann=7,-1,0
  4633.1   0.035       0  4663.8    0.07       0  4839.3   0.035       0
  4976.2   0.035       0  4983.5   0.035       0  5017.4    0.07       0
  5097.8   0.045       0
Bank Sta=4976.2,4983.5
Exp/Cntr=0.3,0.1