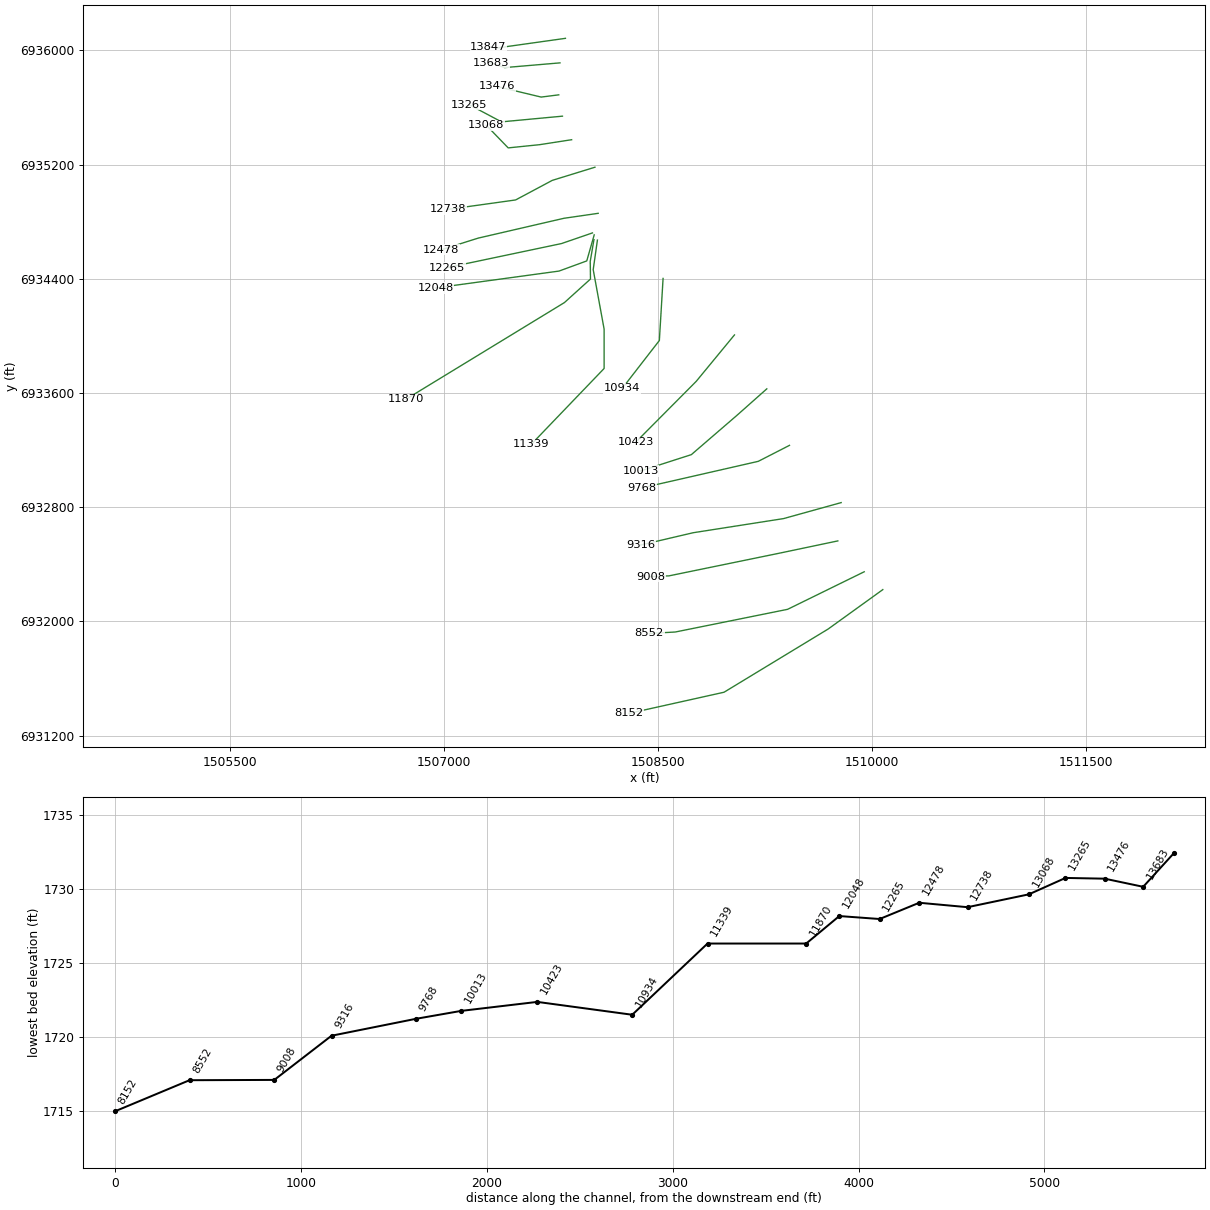
HEC-RAS study NC Unknown Stream 38.prj: NC Unknown Stream 38 Base Level Engineering

--- NC Unknown Stream 38.g01 (geometry) --- (continued)

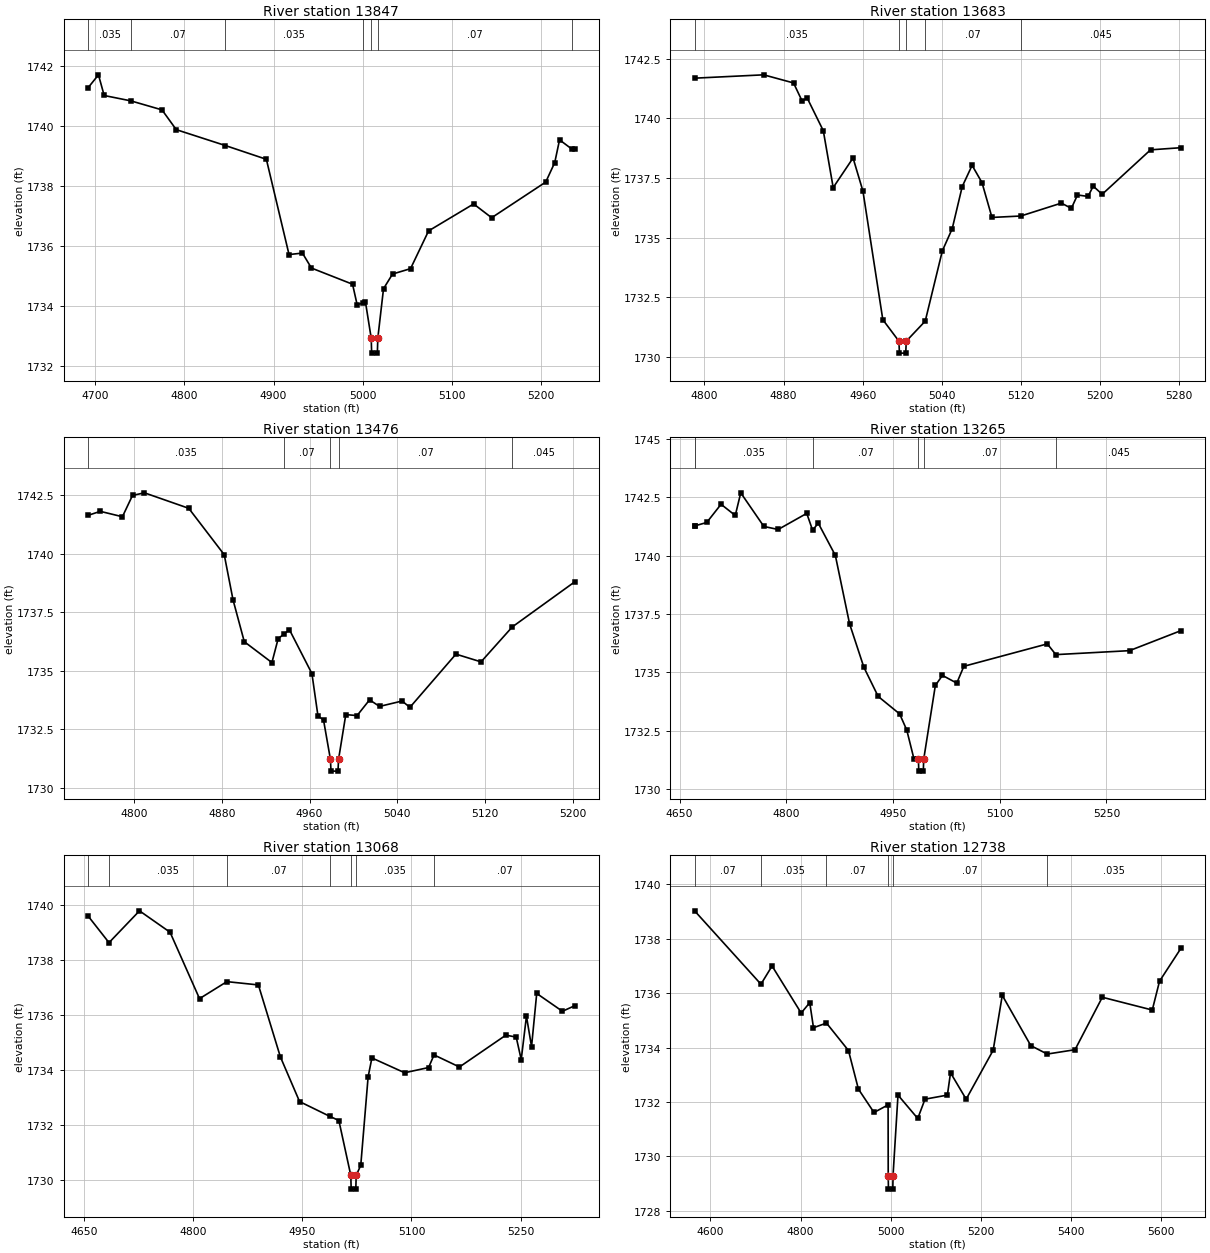
Type RM Length L Ch R = 1,13847,164,164,164
BEGIN DESCRIPTION:
Mapping XS 1157578e
END DESCRIPTION:
XS GIS Cut Line= 3
      1507852.84      6936084.43      1507371.96      6936016.73
      1507312.91      6936025.41
#Sta/Elev= 30
  4692.2 1741.29  4703.8 1741.72  4710.2 1741.03  4740.2 1740.85  4775.0 1740.55
  4791.0 1739.89  4846.0 1739.36  4892.0 1738.90  4917.4 1735.72  4932.4 1735.77
  4942.5 1735.27  4988.6 1734.73  4993.7 1734.05  5000.0 1734.10  5003.1 1734.13
  5009.5 1732.93  5010.0 1732.43  5016.4 1732.43  5016.9 1732.93  5023.3 1734.58
  5033.4 1735.07  5053.6 1735.25  5073.8 1736.51  5124.3 1737.41  5144.5 1736.95
  5205.1 1738.14  5215.2 1738.79  5220.6 1739.55  5234.0 1739.25  5237.5 1739.25
#Mann=7,-1,0
  4692.2   0.035       0  4740.2    0.07       0  4846.0   0.035       0
  5000.0    0.07       0  5009.5    0.07       0  5016.9    0.07       0
  5234.0   0.045       0
Bank Sta=5009.5,5016.9
Exp/Cntr=0.3,0.1

Type RM Length L Ch R = 1,13683,207,207,207
BEGIN DESCRIPTION:
Mapping XS 9abb51f1
END DESCRIPTION:
XS GIS Cut Line= 3
      1507814.69      6935912.56      1507427.52      6935879.57
      1507329.30      6935912.31
#Sta/Elev= 30
  4790.0 1741.68  4859.9 1741.82  4890.1 1741.48  4898.8 1740.72  4903.9 1740.85
  4920.2 1739.48  4930.2 1737.10  4950.3 1738.34  4960.3 1736.95  4980.4 1731.57
  4996.7 1730.67  4997.2 1730.17  5003.6 1730.17  5004.1 1730.67  5023.3 1731.51
  5040.6 1734.45  5050.6 1735.38  5060.7 1737.14  5070.7 1738.03  5080.7 1737.31
  5090.8 1735.85  5120.0 1735.91  5161.0 1736.45  5171.1 1736.23  5177.3 1736.79
  5188.0 1736.73  5193.2 1737.16  5202.3 1736.82  5251.2 1738.68  5282.1 1738.77
#Mann=5,-1,0
  4790.0   0.035       0  4996.7   0.035       0  5004.1   0.035       0
  5023.3    0.07       0  5120.0   0.045       0
Bank Sta=4996.7,5004.1
Exp/Cntr=0.3,0.1

Type RM Length L Ch R = 1,13476,211,211,211
BEGIN DESCRIPTION:
Mapping XS 9ecd4dd1
END DESCRIPTION:
XS GIS Cut Line= 3
      1507806.03      6935688.61      1507682.73      6935672.98
      1507371.96      6935747.63
#Sta/Elev= 30
  4758.0 1741.63  4769.1 1741.80  4789.3 1741.57  4798.5 1742.48  4809.4 1742.59
  4849.8 1741.93  4882.2 1739.95  4890.2 1738.03  4900.5 1736.24  4925.7 1735.35
  4931.4 1736.37  4936.8 1736.57  4941.7 1736.75  4962.2 1734.88  4967.7 1733.08
  4972.8 1732.90  4979.1 1731.22  4979.6 1730.72  4986.0 1730.72  4986.5 1731.22
  4993.1 1733.13  5003.4 1733.09  5014.8 1733.76  5023.9 1733.48  5044.5 1733.71
  5051.6 1733.44  5093.6 1735.71  5116.5 1735.38  5145.0 1736.87  5201.9 1738.79
#Mann=5,-1,0
  4758.0   0.035       0  4936.8    0.07       0  4979.1    0.07       0
  4986.5    0.07       0  5145.0   0.045       0
Bank Sta=4979.1,4986.5
Exp/Cntr=0.3,0.1

Type RM Length L Ch R = 1,13265,197,197,197
BEGIN DESCRIPTION:
Mapping XS 1dad7fb9
END DESCRIPTION:
XS GIS Cut Line= 3
      1507832.00      6935539.29      1507404.95      6935499.37
      1507179.63      6935618.96
#Sta/Elev= 30
  4671.0 1741.26  4672.0 1741.28  4688.1 1741.42  4708.2 1742.20  4728.2 1741.72
  4735.9 1742.69  4768.4 1741.25  4788.5 1741.12  4828.7 1741.81  4836.9 1741.09
  4844.9 1741.39  4868.9 1740.01  4888.9 1737.08  4909.0 1735.22  4929.1 1733.97
  4959.3 1733.22  4969.3 1732.53  4979.3 1731.31  4985.7 1731.27  4986.2 1730.77
  4992.6 1730.77  4993.1 1731.27  5009.5 1734.44  5019.5 1734.87  5039.6 1734.54
  5049.6 1735.26  5166.9 1736.22  5178.9 1735.76  5282.5 1735.93  5355.0 1736.79
#Mann=6,-1,0
  4671.0    0.07       0  4672.0   0.035       0  4836.9    0.07       0
  4985.7    0.07       0  4993.1    0.07       0  5178.9   0.045       0
Bank Sta=4985.7,4993.1
Exp/Cntr=0.3,0.1

Type RM Length L Ch R = 1,13068,330,330,330
BEGIN DESCRIPTION:
Mapping XS 8f21d586
END DESCRIPTION:
XS GIS Cut Line= 4
      1507896.29      6935374.37      1507672.31      6935339.64
      1507451.83      6935317.07      1507298.65      6935475.41
#Sta/Elev= 30
  4655.6 1739.61  4684.3 1738.64  4726.2 1739.80  4768.2 1739.02  4808.7 1736.60
  4846.3 1737.22  4889.6 1737.10  4919.8 1734.48  4946.2 1732.85  4987.9 1732.31
  5000.2 1732.16  5016.6 1730.16  5017.1 1729.66  5023.5 1729.66  5024.0 1730.16
  5030.3 1730.53  5040.4 1733.75  5045.6 1734.44  5090.6 1733.90  5123.5 1734.09
  5131.0 1734.55  5165.9 1734.11  5229.7 1735.27  5243.9 1735.20  5250.8 1734.38
  5258.0 1735.96  5265.0 1734.85  5272.1 1736.79  5307.4 1736.14  5324.2 1736.34
#Mann=7,-1,0
  4655.6    0.07       0  4684.3   0.035       0  4846.3    0.07       0
  4987.9   0.035       0  5016.6   0.035       0  5024.0   0.035       0
  5131.0    0.07       0
Bank Sta=5016.6,5024
Exp/Cntr=0.3,0.1

Type RM Length L Ch R = 1,12738,260,260,260
BEGIN DESCRIPTION:
Mapping XS f246de2d
END DESCRIPTION:
XS GIS Cut Line= 4
      1508059.49      6935181.67      1507760.85      6935089.64
      1507503.91      6934952.49      1507031.65      6934886.51
#Sta/Elev= 30
  4564.7 1739.03  4712.1 1736.33  4736.8 1737.00  4801.4 1735.27  4820.5 1735.65
  4828.8 1734.73  4857.7 1734.90  4906.5 1733.89  4928.6 1732.47  4963.2 1731.61
  4994.5 1731.89  4994.8 1729.29  4995.3 1728.79  5005.0 1728.79  5005.5 1729.29
  5016.5 1732.25  5060.4 1731.39  5076.5 1732.10  5126.2 1732.25  5133.2 1733.07
  5167.9 1732.10  5227.9 1733.90  5248.1 1735.92  5311.5 1734.07  5348.0 1733.76
  5409.7 1733.92  5470.3 1735.85  5581.3 1735.38  5597.4 1736.44  5645.3 1737.66
#Mann=6,-1,0
  4564.7    0.07       0  4712.1   0.035       0  4857.7    0.07       0
  4994.8    0.07       0  5005.5    0.07       0  5348.0   0.035       0
Bank Sta=4994.8,5005.5
Exp/Cntr=0.3,0.1

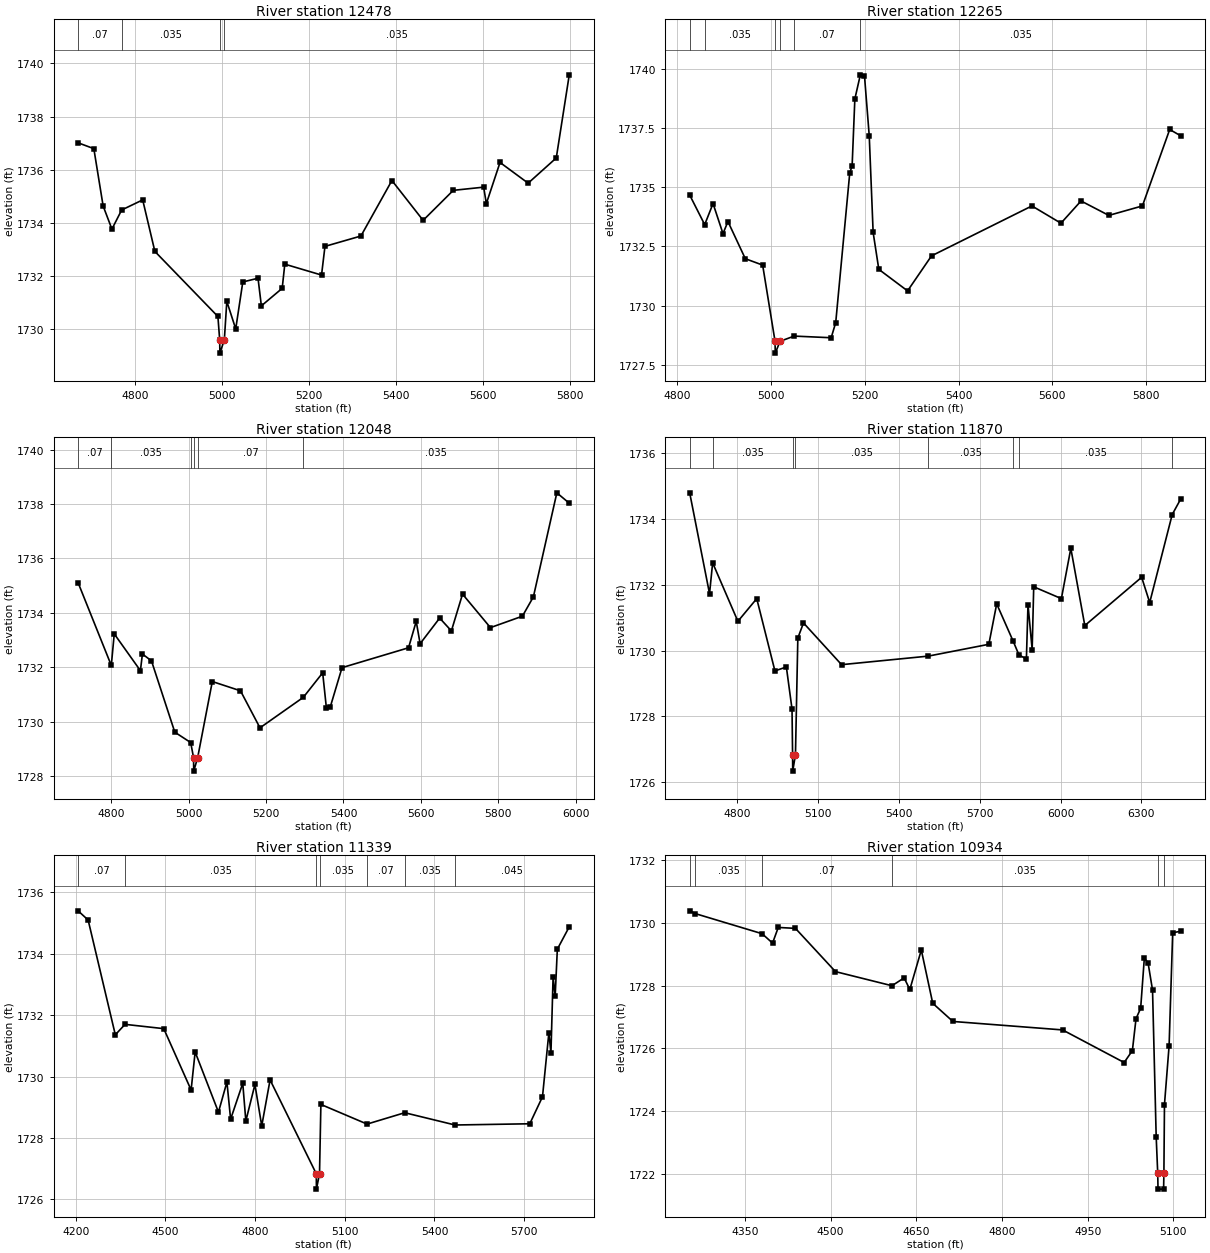
Type RM Length L Ch R = 1,12478,213,213,213
BEGIN DESCRIPTION:
Mapping XS a62879c0
END DESCRIPTION:
XS GIS Cut Line= 4
      1508082.02      6934858.74      1507842.45      6934824.02
      1507241.76      6934685.13      1506983.03      6934603.52
#Sta/Elev= 30
  4668.3 1737.01  4704.5 1736.79  4725.9 1734.63  4746.1 1733.76  4768.5 1734.48
  4816.9 1734.86  4844.9 1732.92  4989.9 1730.47  4994.0 1729.59  4994.5 1729.09
  5004.7 1729.59  5010.4 1731.04  5030.9 1730.00  5047.2 1731.77  5082.2 1731.91
  5089.9 1730.87  5137.8 1731.53  5143.8 1732.44  5228.3 1732.03  5236.2 1733.11
  5318.9 1733.50  5390.2 1735.59  5462.0 1734.09  5531.4 1735.22  5601.3 1735.34
  5607.4 1734.72  5638.9 1736.27  5703.6 1735.49  5768.3 1736.44  5798.2 1739.57
#Mann=4,-1,0
  4668.3    0.07       0  4768.5   0.035       0  4994.0   0.035       0
  5004.7   0.035       0
Bank Sta=4994,5004.7
Exp/Cntr=0.3,0.1

Type RM Length L Ch R = 1,12265,217,217,217
BEGIN DESCRIPTION:
Mapping XS 44d57332
END DESCRIPTION:
XS GIS Cut Line= 3
      1508042.12      6934721.60      1507825.09      6934646.94
      1507024.73      6934478.53
#Sta/Elev= 30
  4826.7 1734.67  4858.7 1733.42  4876.5 1734.31  4897.7 1733.04  4908.3 1733.55
  4945.3 1731.98  4982.3 1731.71  5008.7 1728.49  5009.2 1727.99  5019.4 1728.49
  5049.5 1728.71  5128.4 1728.64  5138.1 1729.28  5168.0 1735.60  5173.1 1735.91
  5178.9 1738.73  5190.6 1739.75  5199.4 1739.72  5209.6 1737.17  5217.9 1733.09
  5230.0 1731.53  5291.3 1730.62  5342.4 1732.10  5556.5 1734.21  5618.4 1733.48
  5661.2 1734.42  5720.5 1733.81  5792.1 1734.21  5850.3 1737.44  5874.1 1737.17
#Mann=6,-1,0
  4826.7    0.07       0  4858.7   0.035       0  5008.7   0.035       0
  5019.4   0.035       0  5049.5    0.07       0  5190.6   0.035       0
Bank Sta=5008.7,5019.4
Exp/Cntr=0.3,0.1

Type RM Length L Ch R = 1,12048,178,178,178
BEGIN DESCRIPTION:
Mapping XS 4ba1d351
END DESCRIPTION:
XS GIS Cut Line= 4
      1508054.25      6934707.68      1508002.17      6934525.41
      1507807.73      6934454.23      1506943.18      6934336.18
#Sta/Elev= 30
  4714.2 1735.11  4800.0 1732.07  4807.6 1733.23  4875.2 1731.88  4880.4 1732.49
  4903.8 1732.24  4964.1 1729.62  5005.1 1729.24  5012.5 1728.69  5013.0 1728.19
  5023.2 1728.69  5061.0 1731.48  5133.8 1731.14  5184.2 1729.78  5296.2 1730.90
  5346.2 1731.80  5355.8 1730.51  5365.9 1730.55  5396.2 1731.99  5568.1 1732.72
  5587.9 1733.69  5598.0 1732.87  5648.5 1733.81  5678.8 1733.34  5707.6 1734.69
  5779.7 1733.46  5862.3 1733.88  5890.7 1734.59  5951.3 1738.41  5983.4 1738.03
#Mann=6,-1,0
  4714.2    0.07       0  4800.0   0.035       0  5005.1    0.07       0
  5012.5   0.035       0  5023.2    0.07       0  5296.2   0.035       0
Bank Sta=5012.5,5023.2
Exp/Cntr=0.3,0.1

Type RM Length L Ch R = 1,11870,531,531,531
BEGIN DESCRIPTION:
Mapping XS 4590d3f6
END DESCRIPTION:
XS GIS Cut Line= 5
      1508052.53      6934674.76      1508026.48      6934521.94
      1508028.21      6934398.67      1507845.92      6934233.74
      1506736.21      6933556.85
#Sta/Elev= 30
  4622.8 1734.80  4696.5 1731.73  4708.0 1732.67  4801.8 1730.89  4871.8 1731.58
  4939.3 1729.38  4981.8 1729.50  5002.8 1728.22  5004.9 1726.83  5005.4 1726.33
  5015.6 1726.83  5024.4 1730.38  5045.4 1730.84  5186.8 1729.57  5508.5 1729.83
  5733.7 1730.19  5762.9 1731.42  5824.3 1730.28  5845.4 1729.87  5873.2 1729.74
  5879.1 1731.40  5894.6 1730.03  5900.4 1731.94  6003.1 1731.58  6038.2 1733.11
  6090.1 1730.76  6301.2 1732.23  6331.1 1731.46  6414.7 1734.14  6446.8 1734.62
#Mann=8,-1,0
  4622.8    0.07       0  4708.0   0.035       0  5004.9   0.035       0
  5015.6   0.035       0  5508.5   0.035       0  5824.3    0.07       0
  5845.4   0.035       0  6414.7   0.045       0
Bank Sta=5004.9,5015.6
Exp/Cntr=0.3,0.1

Type RM Length L Ch R = 1,11339,405,405,405
BEGIN DESCRIPTION:
Mapping XS 07f01c5a
END DESCRIPTION:
XS GIS Cut Line= 5
      1508076.82      6934671.22      1508047.31      6934464.64
      1508123.70      6934047.98      1508123.70      6933771.94
      1507614.64      6933241.80
#Sta/Elev= 30
  4207.7 1735.40  4241.3 1735.10  4332.2 1731.36  4364.8 1731.70  4494.3 1731.56
  4585.8 1729.56  4599.3 1730.80  4677.3 1728.84  4705.6 1729.82  4718.0 1728.61
  4758.6 1729.78  4768.9 1728.55  4799.3 1729.74  4822.1 1728.39  4850.0 1729.89
  5004.6 1726.83  5005.1 1726.33  5015.4 1726.83  5020.0 1729.09  5174.5 1728.45
  5300.5 1728.82  5468.9 1728.42  5718.9 1728.46  5761.4 1729.34  5782.8 1731.43
  5789.7 1730.77  5796.9 1733.25  5803.8 1732.61  5811.1 1734.15  5851.0 1734.88
#Mann=7,-1,0
  4207.7    0.07       0  4364.8   0.035       0  5004.6   0.035       0
  5015.4   0.035       0  5174.5    0.07       0  5300.5   0.035       0
  5468.9   0.045       0
Bank Sta=5004.6,5015.4
Exp/Cntr=0.3,0.1

Type RM Length L Ch R = 1,10934,511,511,511
BEGIN DESCRIPTION:
Mapping XS 6a2ec5e9
END DESCRIPTION:
XS GIS Cut Line= 3
      1508536.72      6934402.86      1508510.68      6933967.94
      1508250.66      6933632.52
#Sta/Elev= 30
  4253.1 1730.39  4263.1 1730.30  4379.9 1729.66  4398.2 1729.36  4408.2 1729.86
  4438.3 1729.83  4508.4 1728.45  4607.3 1728.00  4628.6 1728.25  4638.6 1727.88
  4658.7 1729.14  4678.7 1727.44  4714.0 1726.86  4906.1 1726.59  5013.9 1725.55
  5028.3 1725.93  5034.7 1726.95  5042.8 1727.28  5049.2 1728.87  5055.7 1728.74
  5063.6 1727.86  5070.0 1723.18  5072.7 1722.01  5073.2 1721.51  5083.0 1721.51
  5083.5 1722.01  5084.5 1724.21  5092.6 1726.08  5098.9 1729.69  5113.2 1729.74
#Mann=6,-1,0
  4253.1    0.07       0  4263.1   0.035       0  4379.9    0.07       0
  4607.3   0.035       0  5072.7   0.035       0  5083.5   0.035       0
Bank Sta=5072.7,5083.5
Exp/Cntr=0.3,0.1

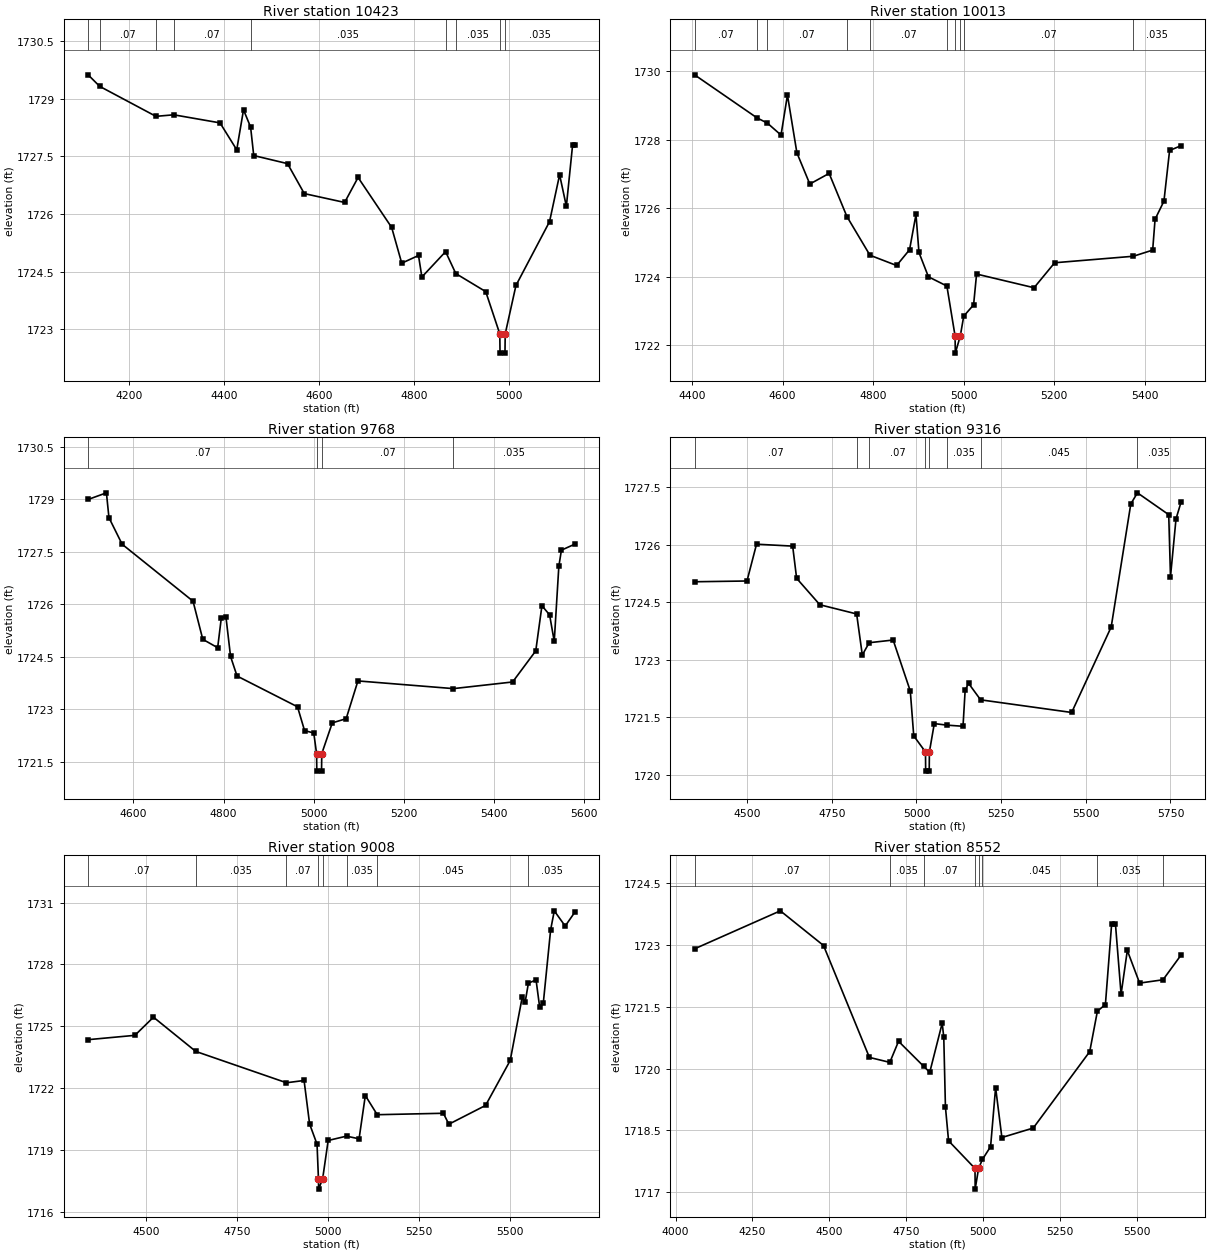
Type RM Length L Ch R = 1,10423,410,410,410
BEGIN DESCRIPTION:
Mapping XS 68a8df27
END DESCRIPTION:
XS GIS Cut Line= 3
      1509036.74      6934007.03      1508768.49      6933681.48
      1508344.00      6933254.39
#Sta/Elev= 30
  4113.6 1729.62  4138.0 1729.32  4256.4 1728.54  4293.9 1728.58  4391.2 1728.37
  4426.4 1727.67  4440.7 1728.71  4455.6 1728.26  4462.2 1727.52  4533.3 1727.31
  4568.6 1726.53  4653.5 1726.30  4681.8 1726.95  4752.5 1725.65  4773.7 1724.72
  4809.0 1724.92  4816.1 1724.36  4866.0 1725.02  4887.5 1724.45  4950.5 1723.98
  4980.1 1722.88  4980.6 1722.38  4991.0 1722.38  4991.5 1722.88  5014.1 1724.14
  5084.8 1725.80  5106.0 1727.02  5120.2 1726.20  5133.3 1727.79  5137.6 1727.79
#Mann=9,-1,0
  4113.6   0.035       0  4138.0    0.07       0  4256.4   0.035       0
  4293.9    0.07       0  4455.6   0.035       0  4866.0    0.07       0
  4887.5   0.035       0  4980.1   0.035       0  4991.5   0.035       0
Bank Sta=4980.1,4991.5
Exp/Cntr=0.3,0.1

Type RM Length L Ch R = 1,10013,245,245,245
BEGIN DESCRIPTION:
Mapping XS 3764281c
END DESCRIPTION:
XS GIS Cut Line= 4
      1509263.30      6933629.42      1509054.95      6933444.50
      1508734.64      6933168.46      1508378.95      6933054.23
#Sta/Elev= 30
  4405.4 1729.90  4543.6 1728.64  4566.2 1728.49  4596.4 1728.14  4610.6 1729.31
  4631.5 1727.62  4660.0 1726.71  4702.7 1727.02  4742.0 1725.76  4792.9 1724.63
  4851.8 1724.33  4880.4 1724.79  4894.6 1725.82  4901.2 1724.71  4922.1 1724.00
  4962.9 1723.73  4981.0 1722.27  4981.5 1721.77  4992.5 1722.27  5000.1 1722.85
  5021.9 1723.18  5028.5 1724.08  5155.5 1723.68  5201.0 1724.41  5374.9 1724.60
  5417.6 1724.78  5422.9 1725.68  5442.5 1726.21  5455.0 1727.69  5480.4 1727.83
#Mann=10,-1,0
  4405.4    0.07       0  4543.6   0.035       0  4566.2    0.07       0
  4742.0   0.035       0  4792.9    0.07       0  4962.9   0.035       0
  4981.0   0.035       0  4992.5   0.035       0  5000.1    0.07       0
  5374.9   0.035       0
Bank Sta=4981,4992.5
Exp/Cntr=0.3,0.1

Type RM Length L Ch R = 1,9768,452,452,452
BEGIN DESCRIPTION:
Mapping XS bb686970
END DESCRIPTION:
XS GIS Cut Line= 4
      1509422.13      6933233.56      1509203.39      6933121.59
      1508575.78      6932978.36      1508390.89      6932936.69
#Sta/Elev= 30
  4499.4 1729.00  4540.0 1729.19  4545.6 1728.48  4574.8 1727.72  4732.1 1726.09
  4753.7 1725.00  4786.7 1724.76  4794.8 1725.61  4805.0 1725.65  4815.3 1724.51
  4829.7 1723.95  4963.8 1723.07  4979.4 1722.39  4999.9 1722.32  5006.1 1721.73
  5006.6 1721.23  5017.1 1721.23  5017.6 1721.73  5040.9 1722.61  5071.7 1722.73
  5097.8 1723.81  5309.5 1723.59  5440.9 1723.78  5492.2 1724.67  5505.9 1725.96
  5522.9 1725.70  5533.2 1724.94  5543.4 1727.09  5549.1 1727.55  5578.4 1727.72
#Mann=4,-1,0
  4499.4    0.07       0  5006.1    0.07       0  5017.6    0.07       0
  5309.5   0.035       0
Bank Sta=5006.1,5017.6
Exp/Cntr=0.3,0.1

Type RM Length L Ch R = 1,9316,308,308,308
BEGIN DESCRIPTION:
Mapping XS 9e485891
END DESCRIPTION:
XS GIS Cut Line= 4
      1509784.09      6932832.52      1509380.47      6932720.55
      1508747.66      6932621.59      1508380.44      6932535.64
#Sta/Elev= 30
  4344.8 1725.03  4499.5 1725.05  4527.7 1726.01  4634.4 1725.96  4646.1 1725.12
  4714.7 1724.43  4823.3 1724.19  4840.0 1723.12  4860.4 1723.44  4931.1 1723.51
  4981.7 1722.18  4991.9 1721.01  5026.6 1720.59  5027.1 1720.09  5037.6 1720.09
  5038.1 1720.59  5052.6 1721.33  5089.5 1721.29  5137.4 1721.26  5143.7 1722.20
  5153.8 1722.38  5189.3 1721.95  5458.2 1721.62  5574.9 1723.85  5632.8 1727.06
  5652.4 1727.35  5744.8 1726.78  5750.0 1725.16  5766.3 1726.67  5781.3 1727.11
#Mann=8,-1,0
  4344.8    0.07       0  4823.3   0.035       0  4860.4    0.07       0
  5026.6    0.07       0  5038.1    0.07       0  5089.5   0.035       0
  5189.3   0.045       0  5652.4   0.035       0
Bank Sta=5026.6,5038.1
Exp/Cntr=0.3,0.1

Type RM Length L Ch R = 1,9008,456,456,456
BEGIN DESCRIPTION:
Mapping XS 05bef729
END DESCRIPTION:
XS GIS Cut Line= 4
      1509760.72      6932564.31      1509351.83      6932478.36
      1508578.39      6932319.50      1508449.11      6932314.33
#Sta/Elev= 30
  4340.8 1724.35  4469.3 1724.56  4520.4 1725.44  4636.6 1723.78  4885.8 1722.26
  4934.2 1722.37  4949.4 1720.26  4969.8 1719.28  4973.7 1717.60  4974.2 1717.10
  4985.2 1717.60  5000.4 1719.46  5050.8 1719.67  5085.3 1719.54  5102.5 1721.64
  5135.2 1720.71  5316.9 1720.78  5332.1 1720.25  5432.9 1721.16  5500.6 1723.34
  5533.6 1726.41  5541.5 1726.16  5550.6 1727.09  5571.6 1727.25  5581.6 1725.92
  5591.6 1726.14  5611.7 1729.68  5621.7 1730.60  5651.7 1729.86  5677.6 1730.52
#Mann=8,-1,0
  4340.8    0.07       0  4636.6   0.035       0  4885.8    0.07       0
  4973.7    0.07       0  4985.2    0.07       0  5050.8   0.035       0
  5135.2   0.045       0  5550.6   0.035       0
Bank Sta=4973.7,4985.2
Exp/Cntr=0.3,0.1

Type RM Length L Ch R = 1,8552,400,400,400
BEGIN DESCRIPTION:
Mapping XS fae19f90
END DESCRIPTION:
XS GIS Cut Line= 4
      1509945.58      6932348.15      1509409.12      6932085.13
      1508622.66      6931926.28      1508440.37      6931915.86
#Sta/Elev= 30
  4061.9 1722.90  4340.8 1723.82  4481.3 1722.98  4630.5 1720.27  4696.9 1720.15
  4725.3 1720.66  4807.6 1720.05  4826.8 1719.91  4867.3 1721.10  4872.4 1720.76
  4877.8 1719.07  4888.0 1718.25  4974.0 1717.58  4974.5 1717.08  4985.6 1717.58
  4998.2 1717.80  5024.7 1718.11  5041.0 1719.54  5061.4 1718.33  5163.5 1718.56
  5347.1 1720.41  5372.1 1721.39  5398.1 1721.55  5418.5 1723.51  5430.8 1723.50
  5449.1 1721.80  5469.4 1722.86  5509.4 1722.07  5585.5 1722.15  5644.3 1722.75
#Mann=8,-1,0
  4061.9    0.07       0  4696.9   0.035       0  4807.6    0.07       0
  4974.0   0.045       0  4985.6    0.07       0  4998.2   0.045       0
  5372.1   0.035       0  5585.5   0.045       0
Bank Sta=4974,4985.6
Exp/Cntr=0.3,0.1

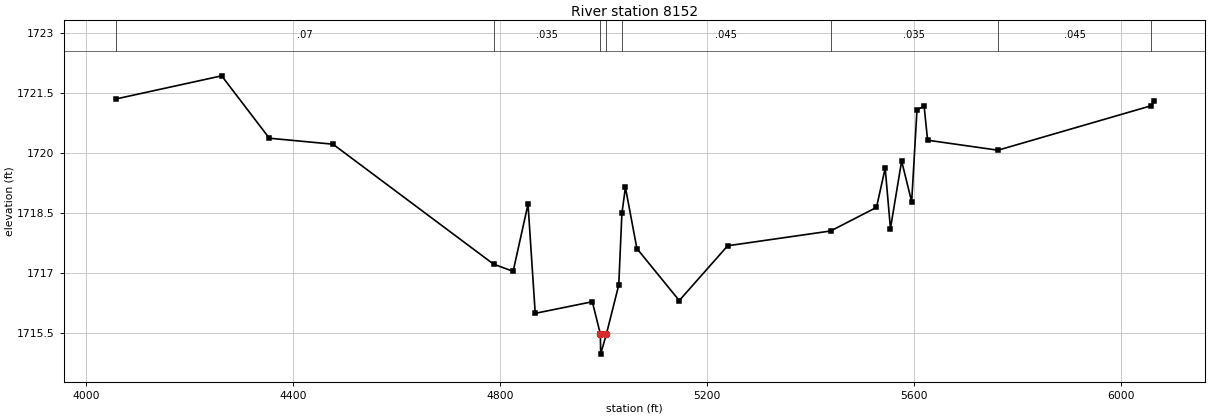
Type RM Length L Ch R = 1,8152,558,558,558
BEGIN DESCRIPTION:
Mapping XS 8cb5df28
END DESCRIPTION:
XS GIS Cut Line= 4
      1510075.79      6932223.15      1509692.97      6931947.11
      1508963.80      6931504.40      1508298.59      6931356.29
#Sta/Elev= 30
  4057.0 1721.36  4261.9 1721.94  4354.0 1720.38  4477.1 1720.23  4787.6 1717.23
  4825.4 1717.05  4854.2 1718.73  4868.1 1716.00  4978.5 1716.29  4994.1 1715.48
  4994.6 1714.98  5005.7 1715.48  5029.6 1716.71  5035.7 1718.50  5042.5 1719.15
  5064.7 1717.62  5146.6 1716.32  5240.2 1717.69  5439.3 1718.06  5527.9 1718.65
  5544.7 1719.63  5554.9 1718.12  5576.5 1719.81  5595.9 1718.79  5606.2 1721.09
  5620.0 1721.18  5626.7 1720.33  5762.7 1720.08  6058.5 1721.19  6063.5 1721.30
#Mann=8,-1,0
  4057.0    0.07       0  4787.6   0.035       0  4994.1    0.07       0
  5005.7   0.035       0  5035.7   0.045       0  5439.3   0.035       0
  5762.7   0.045       0  6058.5    0.07       0
Bank Sta=4994.1,5005.7
Exp/Cntr=0.3,0.1