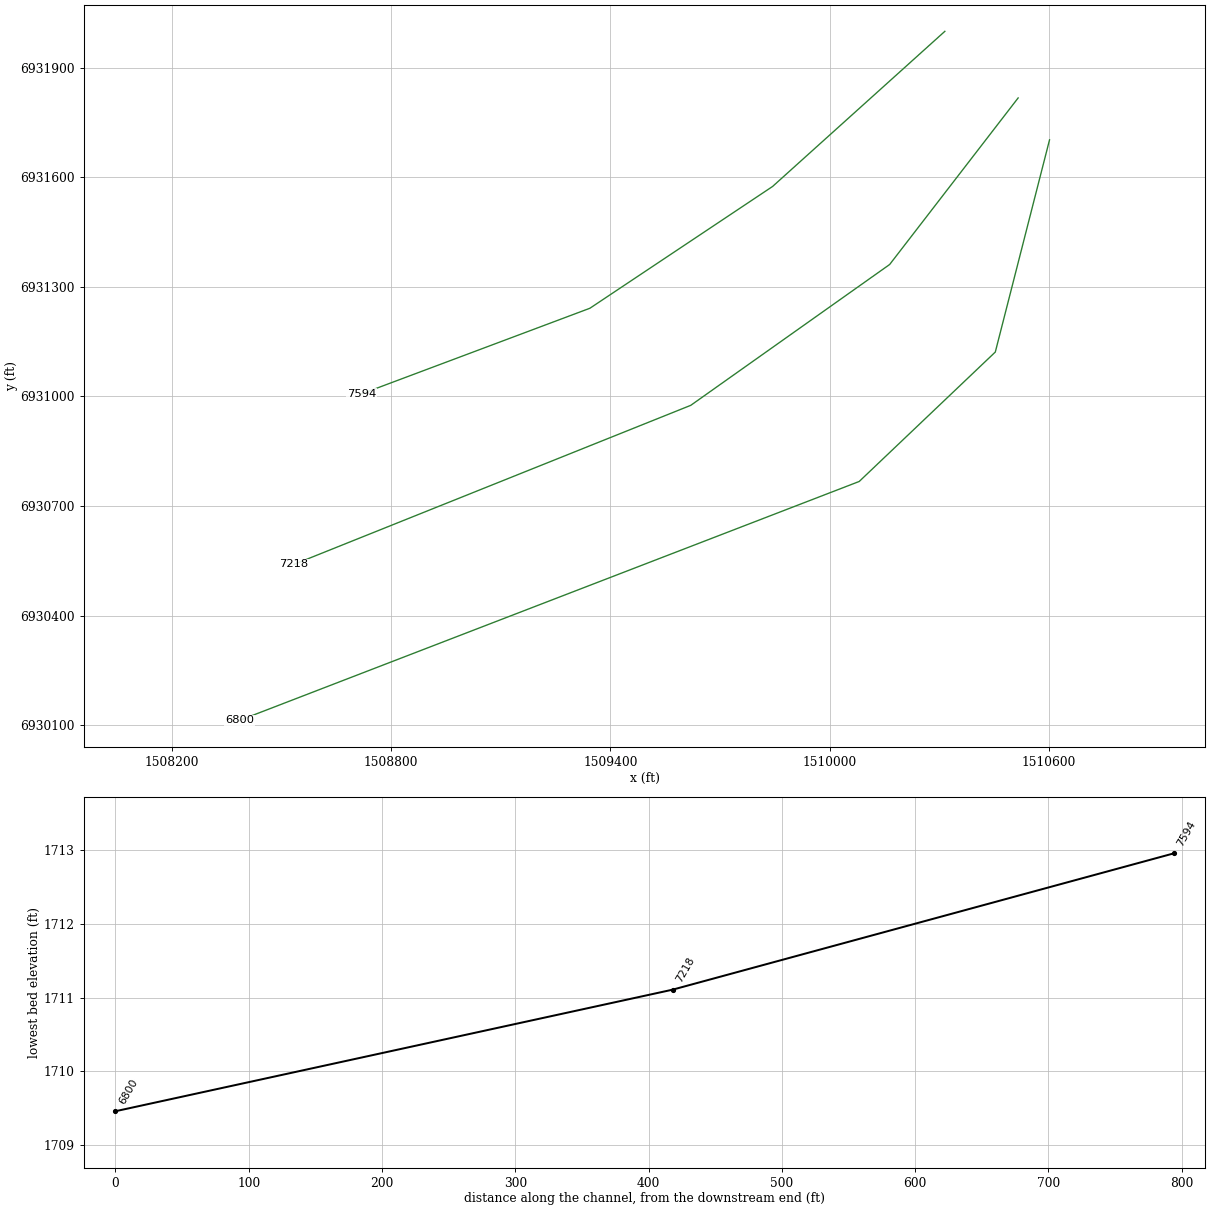
HEC-RAS study NC Unknown Stream 38.prj: NC Unknown Stream 38 Base Level Engineering

--- NC Unknown Stream 38.g01 (geometry) --- (continued)

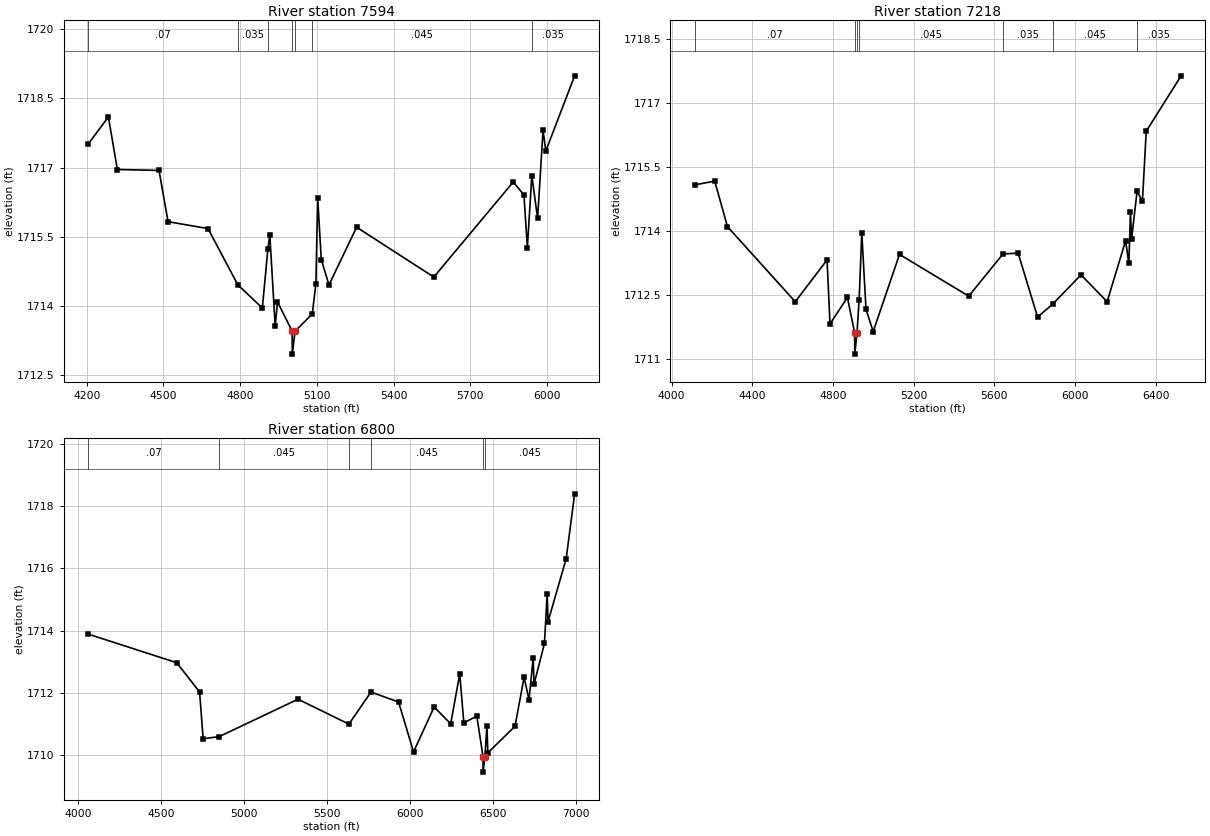
Type RM Length L Ch R = 1,7594,376,376,376
BEGIN DESCRIPTION:
Mapping XS 14bc299e
END DESCRIPTION:
XS GIS Cut Line= 4
      1510315.40      6931999.22      1509844.01      6931574.71
      1509344.01      6931241.38      1508719.46      6931007.17
#Sta/Elev= 30
  4205.8 1717.51  4285.1 1718.10  4320.2 1716.96  4483.1 1716.94  4518.3 1715.83
  4674.5 1715.68  4791.4 1714.46  4887.0 1713.96  4908.6 1715.23  4916.2 1715.54
  4937.3 1713.57  4946.3 1714.09  5003.6 1713.46  5004.1 1712.96  5015.2 1713.46
  5082.3 1713.83  5096.5 1714.49  5103.4 1716.34  5117.5 1715.01  5147.6 1714.46
  5255.7 1715.71  5557.5 1714.63  5868.1 1716.69  5909.9 1716.41  5923.3 1715.27
  5940.8 1716.83  5963.3 1715.90  5984.7 1717.81  5995.4 1717.36  6108.1 1718.99
#Mann=7,-1,0
  4205.8    0.07       0  4791.4   0.035       0  4908.6    0.07       0
  5003.6    0.07       0  5015.2    0.07       0  5082.3   0.045       0
  5940.8   0.035       0
Bank Sta=5003.6,5015.2
Exp/Cntr=0.3,0.1

Type RM Length L Ch R = 1,7218,418,418,418
BEGIN DESCRIPTION:
Mapping XS d240b828
END DESCRIPTION:
XS GIS Cut Line= 4
      1510515.89      6931816.90      1510164.33      6931361.17
      1509620.05      6930975.75      1508534.59      6930540.69
#Sta/Elev= 30
  4114.0 1715.08  4213.7 1715.17  4277.1 1714.10  4613.1 1712.34  4770.7 1713.32
  4785.4 1711.82  4871.6 1712.44  4907.6 1711.61  4908.1 1711.11  4919.2 1711.61
  4929.7 1712.39  4943.0 1713.95  4963.9 1712.16  4999.5 1711.64  5129.9 1713.45
  5473.2 1712.47  5642.8 1713.46  5718.1 1713.48  5814.4 1711.98  5888.5 1712.28
  6029.9 1712.97  6159.2 1712.34  6250.8 1713.77  6266.9 1713.24  6275.0 1714.45
  6280.4 1713.81  6307.7 1714.93  6334.2 1714.70  6353.1 1716.34  6525.9 1717.64
#Mann=7,-1,0
  4114.0    0.07       0  4907.6   0.045       0  4919.2    0.07       0
  4929.7   0.045       0  5642.8   0.035       0  5888.5   0.045       0
  6307.7   0.035       0
Bank Sta=4907.6,4919.2
Exp/Cntr=0.3,0.1

Type RM Length L Ch R = 1,6800,0,0,0
BEGIN DESCRIPTION:
Mapping XS 44b93fed
END DESCRIPTION:
XS GIS Cut Line= 4
      1510601.82      6931702.30      1510453.39      6931121.59
      1510080.99      6930767.42      1508385.36      6930113.64
#Sta/Elev= 30
  4059.4 1713.89  4593.5 1712.97  4730.9 1712.03  4752.3 1710.53  4849.3 1710.60
  5323.9 1711.80  5630.2 1711.00  5763.3 1712.03  5929.4 1711.71  6019.7 1710.11
  6143.7 1711.55  6243.4 1711.01  6298.0 1712.61  6322.6 1711.04  6400.9 1711.26
  6438.0 1709.96  6438.5 1709.46  6449.6 1709.96  6461.8 1710.95  6467.1 1710.08
  6630.9 1710.93  6685.5 1712.50  6715.5 1711.79  6740.1 1713.12  6745.4 1712.28
  6808.2 1713.59  6824.6 1715.17  6830.0 1714.29  6939.2 1716.31  6990.0 1718.39
#Mann=6,-1,0
  4059.4    0.07       0  4849.3   0.045       0  5630.2   0.035       0
  5763.3   0.045       0  6438.0   0.045       0  6449.6   0.045       0
Bank Sta=6438,6449.6
Exp/Cntr=0.3,0.1

Chan Stop Cuts=-1