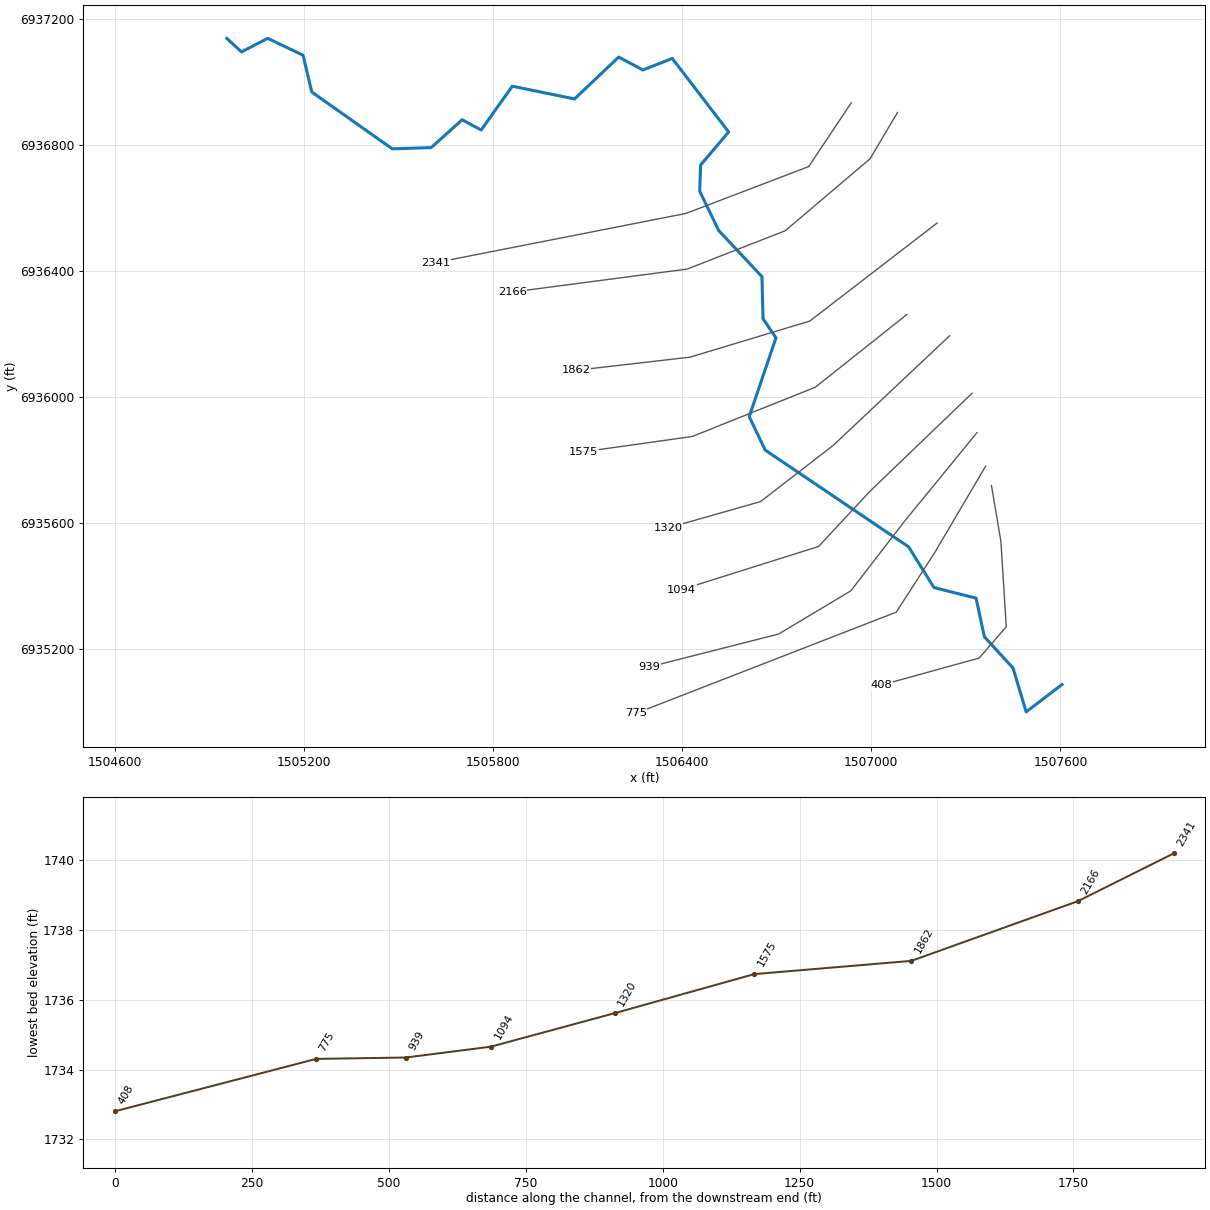
--- NC Unknown Stream 39.prj (project) ---

Proj Title=NC Unknown Stream 39 Base Level Engineering
Current Plan=p01
Default Exp/Contr=0.3,0.1
English Units
Geom File=g01
Flow File=f01
Plan File=p01
BEGIN DESCRIPTION:
NC Unknown Stream 39
END DESCRIPTION:

--- NC Unknown Stream 39.p01 (plan) ---

Plan Title=Multiple Run
Short Identifier=Multiple
Geom File=g01
Flow File=f01
Subcritical Flow
K Sum by GR= 0
Std Step Tol= 0.01
Critical Tol= 0.01
Num of Std Step Trials= 20
Max Error Tol= 0.3
Flow Tol Ratio= 0.001
Split Flow NTrial= 30
Split Flow Tol= 0.02
Split Flow Ratio= 0.02
Log Output Level= 0
Friction Slope Method= 1
Unsteady Friction Slope Method= 2
Unsteady Bridges Friction Slope Method= 1
Parabolic Critical Depth
Global Vel Dist=  1 , 1 , 1
Global Log Level= 0
CheckData=True
Encroach Param= -1, 0, 0, 0
BEGIN DESCRIPTION:
Multiple Run
END DESCRIPTION:

--- NC Unknown Stream 39.f01 (steady flow) ---

Flow Title=Multiple
Number of Profiles=7
Profile Names=10-year,25-year,50-year,1pct_min,100-year,1pct_plu,500-year
River Rch & RM= NC Unknown Strea,Reach-1,2341
     248     340     416     253     505    1008     752
River Rch & RM= NC Unknown Strea,Reach-1,1575
     292     405     498     305     608    1212     914
Boundary for River Rch & Prof#=NC Unknown Strea,Reach-1,1
Up Type=0
Dn Type=3
Dn Slope=0.001
Boundary for River Rch & Prof#=NC Unknown Strea,Reach-1,2
Up Type=0
Dn Type=3
Dn Slope=0.001
Boundary for River Rch & Prof#=NC Unknown Strea,Reach-1,3
Up Type=0
Dn Type=3
Dn Slope=0.001
Boundary for River Rch & Prof#=NC Unknown Strea,Reach-1,4
Up Type=0
Dn Type=3
Dn Slope=0.001
Boundary for River Rch & Prof#=NC Unknown Strea,Reach-1,5
Up Type=0
Dn Type=3
Dn Slope=0.001
Boundary for River Rch & Prof#=NC Unknown Strea,Reach-1,6
Up Type=0
Dn Type=3
Dn Slope=0.001
Boundary for River Rch & Prof#=NC Unknown Strea,Reach-1,7
Up Type=0
Dn Type=3
Dn Slope=0.001

--- NC Unknown Stream 39.g01 (geometry) ---

Geom Title=Existing Conditions

River Reach=NC Unknown Strea,Reach-1
Reach XY= 30
      1504955.00      6937138.00      1505001.56      6937095.27
      1505084.82      6937138.26      1505196.85      6937084.63
      1505224.62      6936967.83      1505479.89      6936787.68
      1505603.53      6936791.55      1505701.68      6936879.98
      1505761.95      6936847.19      1505860.87      6936986.42
      1506058.33      6936945.98      1506198.27      6937078.85
      1506275.16      6937037.91      1506368.38      6937074.46
      1506547.16      6936841.23      1506458.48      6936736.50
      1506455.36      6936653.27      1506515.76      6936528.32
      1506652.93      6936382.14      1506656.40      6936248.44
      1506697.44      6936188.00      1506612.53      6935937.99
      1506663.11      6935831.93      1507118.56      6935524.51
      1507198.55      6935395.75      1507332.32      6935362.01
      1507358.63      6935239.51      1507449.46      6935140.41
      1507491.24      6935001.21      1507605.00      6935088.00

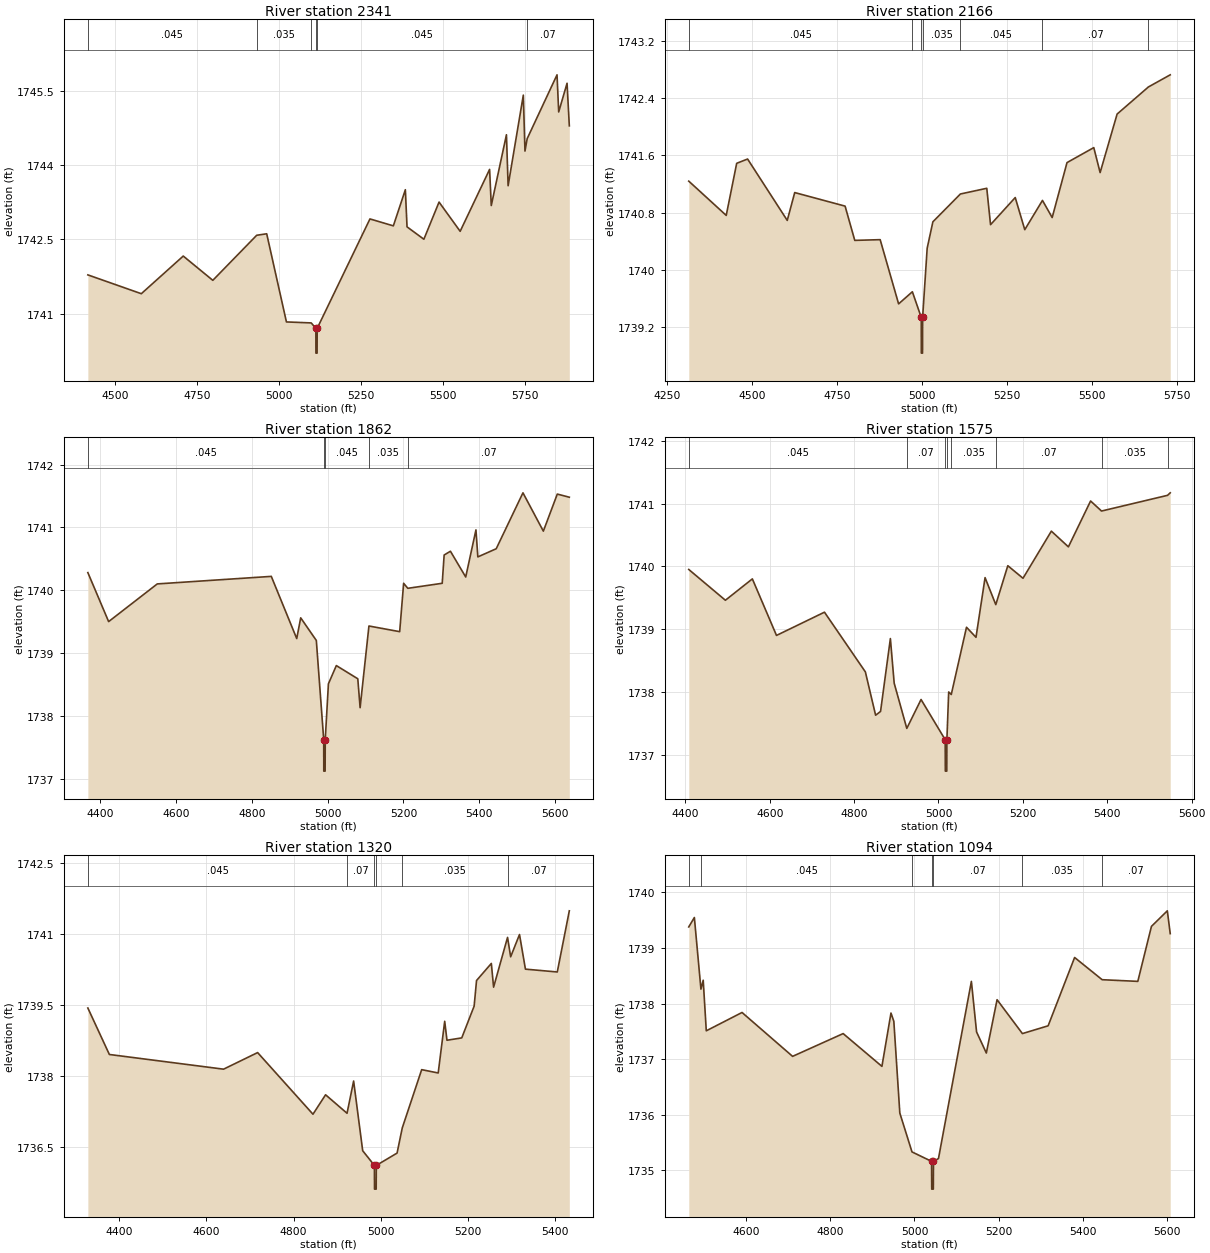
Type RM Length L Ch R = 1,2341,175,175,175
BEGIN DESCRIPTION:
NC Unknown Stream 39 2.0
END DESCRIPTION:
XS GIS Cut Line= 4
      1506936.19      6936933.68      1506801.29      6936731.37
      1506411.72      6936582.66      1505618.24      6936426.73
#Sta/Elev= 30
  4416.0 1741.78  4579.1 1741.40  4707.0 1742.16  4797.2 1741.67  4931.1 1742.58
  4961.6 1742.61  5021.8 1740.83  5097.4 1740.81  5111.6 1740.70  5111.8 1740.20
  5115.3 1740.20  5115.6 1740.70  5276.6 1742.91  5348.0 1742.77  5384.6 1743.50
  5389.7 1742.75  5441.1 1742.50  5487.4 1743.25  5551.8 1742.66  5641.6 1743.91
  5646.7 1743.18  5693.0 1744.61  5698.1 1743.58  5744.5 1745.41  5749.5 1744.28
  5756.2 1744.53  5847.3 1745.82  5852.4 1745.07  5877.9 1745.65  5884.8 1744.79
#Mann=6,-1,0
  4416.0   0.045       0  4931.1   0.035       0  5097.4   0.045       0
  5111.6   0.035       0  5115.6   0.045       0  5756.2    0.07       0
Bank Sta=5111.6,5115.6
Exp/Cntr=0.3,0.1

Type RM Length L Ch R = 1,2166,304,304,304
BEGIN DESCRIPTION:
Mapping XS edf83608
END DESCRIPTION:
XS GIS Cut Line= 5
      1507082.90      6936902.87      1506995.67      6936755.74
      1506726.65      6936527.68      1506415.89      6936406.15
      1505860.36      6936333.24
#Sta/Elev= 30
  4313.1 1741.24  4423.4 1740.76  4454.2 1741.49  4486.3 1741.55  4603.1 1740.69
  4625.1 1741.08  4773.4 1740.89  4801.9 1740.41  4876.7 1740.42  4931.0 1739.52
  4971.5 1739.69  4997.7 1739.33  4997.9 1738.83  5001.4 1738.83  5001.7 1739.33
  5015.1 1740.30  5031.9 1740.67  5112.9 1741.06  5190.6 1741.14  5201.7 1740.63
  5274.4 1741.01  5302.5 1740.56  5354.6 1740.97  5383.2 1740.73  5426.9 1741.50
  5505.7 1741.71  5524.4 1741.36  5574.4 1742.18  5666.6 1742.56  5730.8 1742.73
#Mann=7,-1,0
  4313.1   0.045       0  4971.5   0.035       0  4997.7   0.035       0
  5001.7   0.035       0  5112.9   0.045       0  5354.6    0.07       0
  5666.6   0.045       0
Bank Sta=4997.7,5001.7
Exp/Cntr=0.3,0.1

Type RM Length L Ch R = 1,1862,287,287,287
BEGIN DESCRIPTION:
Mapping XS 29cecb8d
END DESCRIPTION:
XS GIS Cut Line= 4
      1507208.46      6936552.09      1506804.78      6936241.22
      1506424.57      6936126.64      1506063.47      6936084.97
#Sta/Elev= 30
  4367.6 1740.28  4422.4 1739.50  4550.7 1740.10  4851.5 1740.22  4918.6 1739.23
  4929.1 1739.56  4970.3 1739.20  4989.8 1737.62  4990.0 1737.12  4993.5 1737.12
  4993.8 1737.62  5002.2 1738.51  5023.1 1738.80  5079.7 1738.59  5085.8 1738.13
  5109.1 1739.43  5190.2 1739.34  5200.6 1740.11  5211.6 1740.03  5302.4 1740.11
  5307.5 1740.56  5324.1 1740.62  5364.4 1740.21  5391.4 1740.96  5396.4 1740.53
  5444.9 1740.66  5515.4 1741.55  5569.2 1740.94  5606.0 1741.53  5637.7 1741.48
#Mann=5,-1,0
  4367.6   0.045       0  4989.8   0.045       0  4993.8   0.045       0
  5109.1   0.035       0  5211.6    0.07       0
Bank Sta=4989.8,4993.8
Exp/Cntr=0.3,0.1

Type RM Length L Ch R = 1,1575,255,255,255
BEGIN DESCRIPTION:
Mapping XS ff5ac93f
END DESCRIPTION:
XS GIS Cut Line= 4
      1507112.97      6936262.16      1506822.14      6936031.15
      1506431.51      6935874.90      1506086.04      6935826.29
#Sta/Elev= 30
  4408.2 1739.95  4495.0 1739.46  4558.9 1739.80  4616.1 1738.90  4729.8 1739.27
  4826.7 1738.32  4851.0 1737.63  4862.7 1737.69  4886.0 1738.85  4895.0 1738.14
  4924.9 1737.42  4958.7 1737.88  5015.9 1737.24  5016.2 1736.74  5019.7 1736.74
  5019.9 1737.24  5024.2 1738.00  5030.3 1737.96  5066.4 1739.03  5088.9 1738.87
  5110.4 1739.82  5135.8 1739.39  5164.3 1740.01  5200.3 1739.81  5267.5 1740.56
  5307.9 1740.31  5360.5 1741.04  5386.4 1740.88  5542.8 1741.13  5549.2 1741.17
#Mann=8,-1,0
  4408.2   0.045       0  4924.9    0.07       0  5015.9    0.07       0
  5019.9    0.07       0  5030.3   0.035       0  5135.8    0.07       0
  5386.4   0.035       0  5542.8    0.07       0
Bank Sta=5015.9,5019.9
Exp/Cntr=0.3,0.1

Type RM Length L Ch R = 1,1320,226,226,226
BEGIN DESCRIPTION:
Mapping XS 7d3498a7
END DESCRIPTION:
XS GIS Cut Line= 4
      1507248.39      6936194.46      1506879.43      6935847.12
      1506648.53      6935668.30      1506355.11      6935584.97
#Sta/Elev= 30
  4328.3 1739.44  4377.6 1738.46  4639.4 1738.15  4717.5 1738.50  4844.4 1737.20
  4873.3 1737.61  4922.5 1737.22  4937.6 1737.90  4958.4 1736.43  4985.2 1736.12
  4985.5 1735.62  4989.3 1735.62  4989.6 1736.12  5037.2 1736.38  5049.1 1736.91
  5093.6 1738.14  5131.5 1738.07  5146.4 1739.16  5151.6 1738.76  5185.5 1738.81
  5213.9 1739.48  5219.4 1740.02  5253.3 1740.38  5258.5 1739.88  5290.5 1740.93
  5297.6 1740.52  5317.9 1740.99  5331.5 1740.26  5404.5 1740.20  5432.1 1741.49
#Mann=6,-1,0
  4328.3   0.045       0  4922.5    0.07       0  4985.2    0.07       0
  4989.6    0.07       0  5049.1   0.035       0  5290.5    0.07       0
Bank Sta=4985.2,4989.6
Exp/Cntr=0.3,0.1

Type RM Length L Ch R = 1,1094,155,155,155
BEGIN DESCRIPTION:
Mapping XS c4e834ef
END DESCRIPTION:
XS GIS Cut Line= 4
      1507319.58      6936012.17      1506997.49      6935703.03
      1506832.55      6935525.94      1506398.39      6935389.29
#Sta/Elev= 30
  4463.9 1739.38  4477.2 1739.55  4492.8 1738.26  4498.2 1738.42  4505.5 1737.51
  4590.4 1737.84  4710.5 1737.05  4830.6 1737.46  4922.7 1736.87  4944.2 1737.83
  4951.0 1737.68  4965.2 1736.03  4994.1 1735.33  5040.6 1735.16  5041.0 1734.66
  5044.8 1734.66  5045.1 1735.16  5057.0 1735.21  5135.2 1738.40  5147.5 1737.49
  5170.7 1737.11  5196.2 1738.07  5256.4 1737.46  5317.5 1737.60  5380.4 1738.83
  5445.8 1738.43  5530.5 1738.40  5562.9 1739.39  5600.6 1739.67  5607.5 1739.26
#Mann=7,-1,0
  4463.9    0.07       0  4492.8   0.045       0  4994.1    0.07       0
  5040.6    0.07       0  5045.1    0.07       0  5256.4   0.035       0
  5445.8    0.07       0
Bank Sta=5040.6,5045.1
Exp/Cntr=0.3,0.1

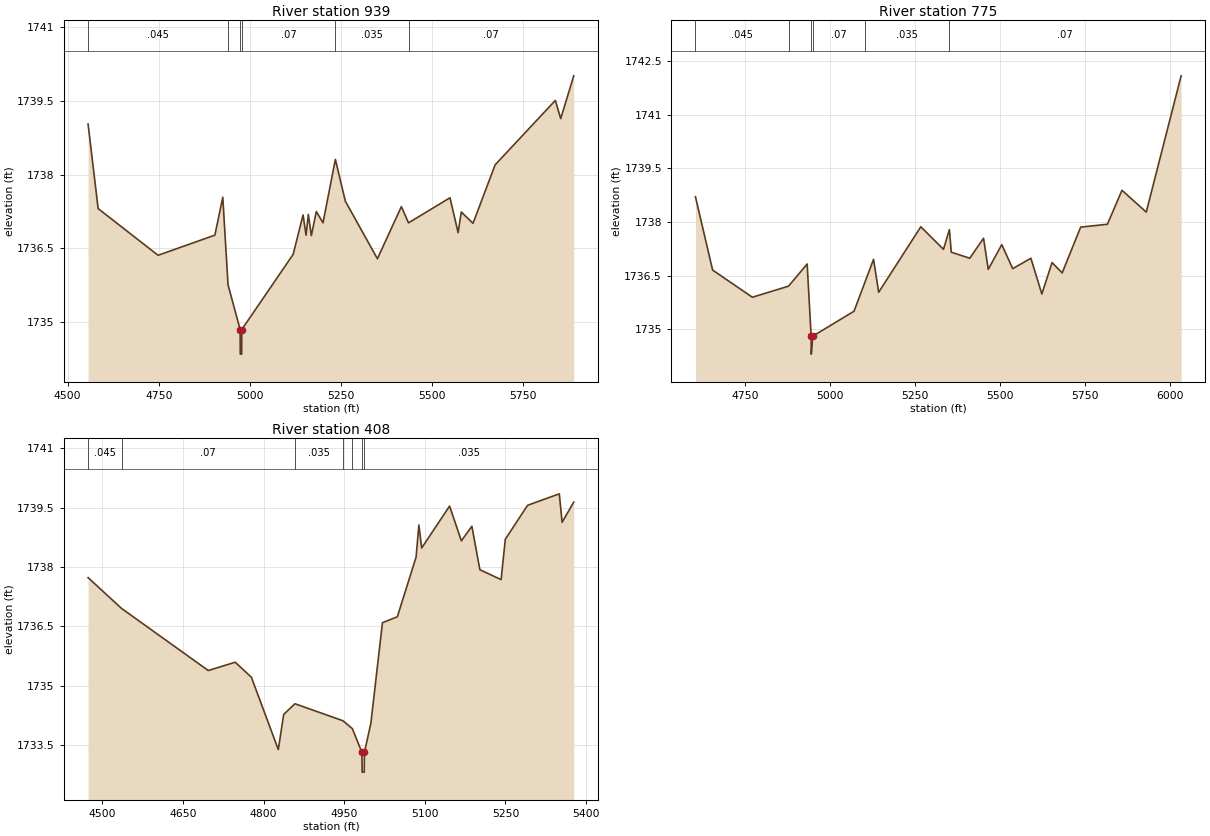
Type RM Length L Ch R = 1,939,164,164,164
BEGIN DESCRIPTION:
Mapping XS 8af75e2e
END DESCRIPTION:
XS GIS Cut Line= 5
      1507335.19      6935887.17      1507105.12      6935605.80
      1506934.99      6935385.32      1506705.82      6935248.16
      1506296.08      6935143.99
#Sta/Elev= 30
  4556.3 1739.03  4583.9 1737.31  4748.3 1736.36  4904.0 1736.77  4925.7 1737.54
  4940.1 1735.76  4973.3 1734.85  4973.6 1734.35  4977.4 1734.35  4977.8 1734.85
  5118.7 1736.38  5145.8 1737.18  5154.0 1736.77  5160.3 1737.19  5168.5 1736.76
  5182.2 1737.25  5200.5 1737.02  5234.4 1738.31  5261.8 1737.46  5349.7 1736.29
  5415.4 1737.35  5435.0 1737.02  5548.7 1737.53  5571.0 1736.82  5579.7 1737.24
  5611.9 1737.01  5672.5 1738.20  5837.6 1739.51  5852.3 1739.14  5888.1 1740.01
#Mann=6,-1,0
  4556.3   0.045       0  4940.1    0.07       0  4973.3    0.07       0
  4977.8    0.07       0  5234.4   0.035       0  5435.0    0.07       0
Bank Sta=4973.3,4977.8
Exp/Cntr=0.3,0.1

Type RM Length L Ch R = 1,775,367,367,367
BEGIN DESCRIPTION:
Mapping XS 5657900e
END DESCRIPTION:
XS GIS Cut Line= 4
      1507362.95      6935781.24      1507202.35      6935508.58
      1507079.08      6935317.61      1506252.65      6934996.41
#Sta/Elev= 30
  4602.7 1738.71  4653.3 1736.66  4770.4 1735.90  4876.9 1736.21  4931.7 1736.83
  4943.5 1734.81  4943.9 1734.31  4948.0 1734.81  5069.8 1735.51  5101.5 1736.31
  5127.2 1736.96  5142.4 1736.04  5266.5 1737.87  5333.2 1737.24  5350.6 1737.79
  5356.2 1737.16  5410.6 1736.99  5451.2 1737.55  5465.1 1736.68  5504.9 1737.37
  5537.1 1736.70  5590.7 1736.99  5622.9 1735.99  5652.9 1736.87  5682.8 1736.58
  5737.2 1737.86  5816.0 1737.94  5858.9 1738.89  5930.4 1738.28  6033.1 1742.09
#Mann=6,-1,0
  4602.7   0.045       0  4876.9    0.07       0  4943.5    0.07       0
  4948.0    0.07       0  5101.5   0.035       0  5350.6    0.07       0
Bank Sta=4943.5,4948
Exp/Cntr=0.3,0.1

Type RM Length L Ch R = 1,408,0,0,0
BEGIN DESCRIPTION:
Mapping XS d0bf1d31
END DESCRIPTION:
XS GIS Cut Line= 5
      1507381.19      6935719.14      1507411.13      6935542.09
      1507428.06      6935271.26      1507342.12      6935171.87
      1507032.21      6935086.36
#Sta/Elev= 30
  4473.3 1737.73  4535.7 1736.95  4697.0 1735.38  4747.1 1735.59  4777.2 1735.21
  4827.3 1733.38  4837.3 1734.27  4858.3 1734.54  4947.5 1734.11  4965.1 1733.91
  4982.9 1733.31  4983.3 1732.81  4987.2 1732.81  4987.5 1733.31  4999.5 1734.04
  5021.1 1736.59  5048.8 1736.74  5083.7 1738.25  5088.9 1739.06  5094.1 1738.48
  5146.0 1739.54  5168.0 1738.66  5187.5 1739.03  5202.4 1737.93  5241.9 1737.68
  5249.7 1738.70  5291.2 1739.56  5350.2 1739.85  5355.4 1739.13  5377.1 1739.64
#Mann=7,-1,0
  4473.3   0.045       0  4535.7    0.07       0  4858.3   0.035       0
  4947.5    0.07       0  4965.1   0.035       0  4982.9   0.035       0
  4987.5   0.035       0
Bank Sta=4982.9,4987.5
Exp/Cntr=0.3,0.1

Chan Stop Cuts=-1