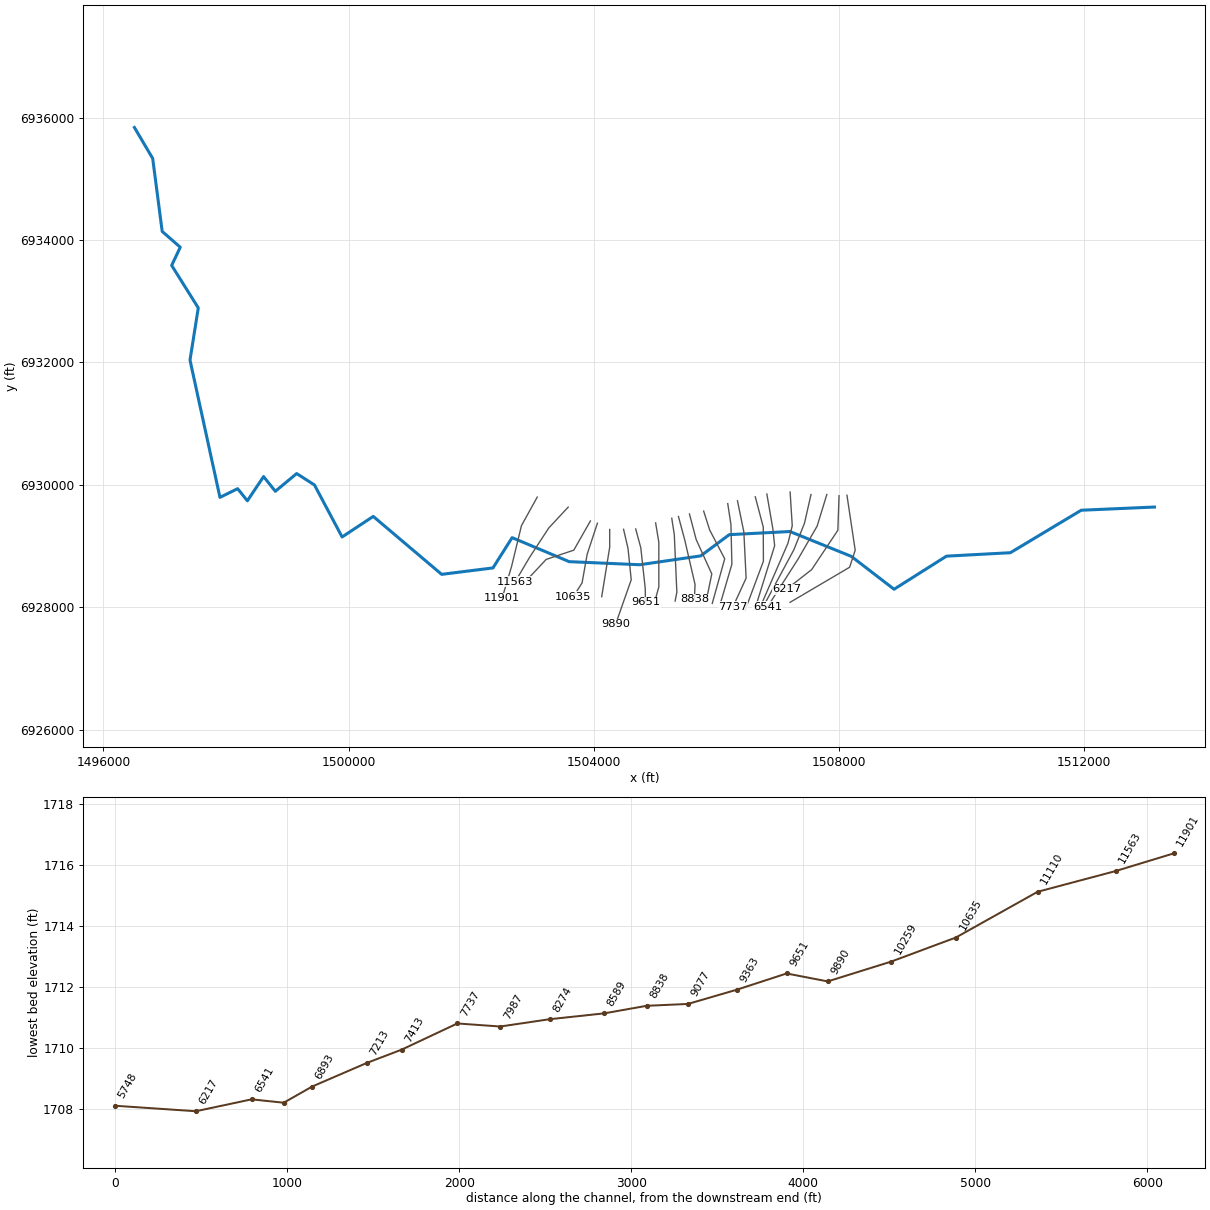
--- NC Unknown Stream 40.prj (project) ---

Proj Title=NC Unknown Stream 40 Base Level Engineering
Current Plan=p01
Default Exp/Contr=0.3,0.1
English Units
Geom File=g01
Flow File=f01
Plan File=p01
BEGIN DESCRIPTION:
NC Unknown Stream 40
END DESCRIPTION:

--- NC Unknown Stream 40.p01 (plan) ---

Plan Title=Multiple Run
Short Identifier=Multiple
Geom File=g01
Flow File=f01
Subcritical Flow
K Sum by GR= 0
Std Step Tol= 0.01
Critical Tol= 0.01
Num of Std Step Trials= 20
Max Error Tol= 0.3
Flow Tol Ratio= 0.001
Split Flow NTrial= 30
Split Flow Tol= 0.02
Split Flow Ratio= 0.02
Log Output Level= 0
Friction Slope Method= 1
Unsteady Friction Slope Method= 2
Unsteady Bridges Friction Slope Method= 1
Parabolic Critical Depth
Global Vel Dist=  1 , 1 , 1
Global Log Level= 0
CheckData=True
Encroach Param= -1, 0, 0, 0
BEGIN DESCRIPTION:
Multiple Run
END DESCRIPTION:

--- NC Unknown Stream 40.f01 (steady flow) ---

Flow Title=Multiple
Number of Profiles=7
Profile Names=10-year,25-year,50-year,1pct_min,100-year,1pct_plu,500-year
River Rch & RM= NC Unknown Strea,Reach-1,11901
     539     767     960     596    1188    2371    1843
River Rch & RM= NC Unknown Strea,Reach-1,6893
     647     926    1162     722    1441    2875    2245
Boundary for River Rch & Prof#=NC Unknown Strea,Reach-1,1
Up Type=0
Dn Type=3
Dn Slope=0.001
Boundary for River Rch & Prof#=NC Unknown Strea,Reach-1,2
Up Type=0
Dn Type=3
Dn Slope=0.001
Boundary for River Rch & Prof#=NC Unknown Strea,Reach-1,3
Up Type=0
Dn Type=3
Dn Slope=0.001
Boundary for River Rch & Prof#=NC Unknown Strea,Reach-1,4
Up Type=0
Dn Type=3
Dn Slope=0.001
Boundary for River Rch & Prof#=NC Unknown Strea,Reach-1,5
Up Type=0
Dn Type=3
Dn Slope=0.001
Boundary for River Rch & Prof#=NC Unknown Strea,Reach-1,6
Up Type=0
Dn Type=3
Dn Slope=0.001
Boundary for River Rch & Prof#=NC Unknown Strea,Reach-1,7
Up Type=0
Dn Type=3
Dn Slope=0.001

--- NC Unknown Stream 40.g01 (geometry) ---

Geom Title=Existing Conditions

River Reach=NC Unknown Strea,Reach-1
Reach XY= 30
      1496505.00      6935838.00      1496803.42      6935332.13
      1496958.37      6934139.73      1497253.44      6933881.92
      1497113.07      6933584.69      1497547.41      6932891.35
      1497412.33      6932037.90      1497901.38      6929795.48
      1498189.80      6929938.11      1498348.86      6929739.73
      1498613.51      6930135.43      1498805.01      6929895.07
      1499153.60      6930184.94      1499444.37      6929998.12
      1499894.98      6929148.94      1500403.37      6929484.87
      1501520.16      6928538.39      1502357.74      6928643.34
      1502670.36      6929138.11      1503601.59      6928745.82
      1504755.01      6928695.53      1505749.03      6928840.33
      1506215.50      6929186.81      1507205.00      6929238.00
      1508207.29      6928832.15      1508905.08      6928295.30
      1509760.93      6928835.76      1510803.42      6928891.83
      1511960.94      6929585.74      1513155.00      6929638.00

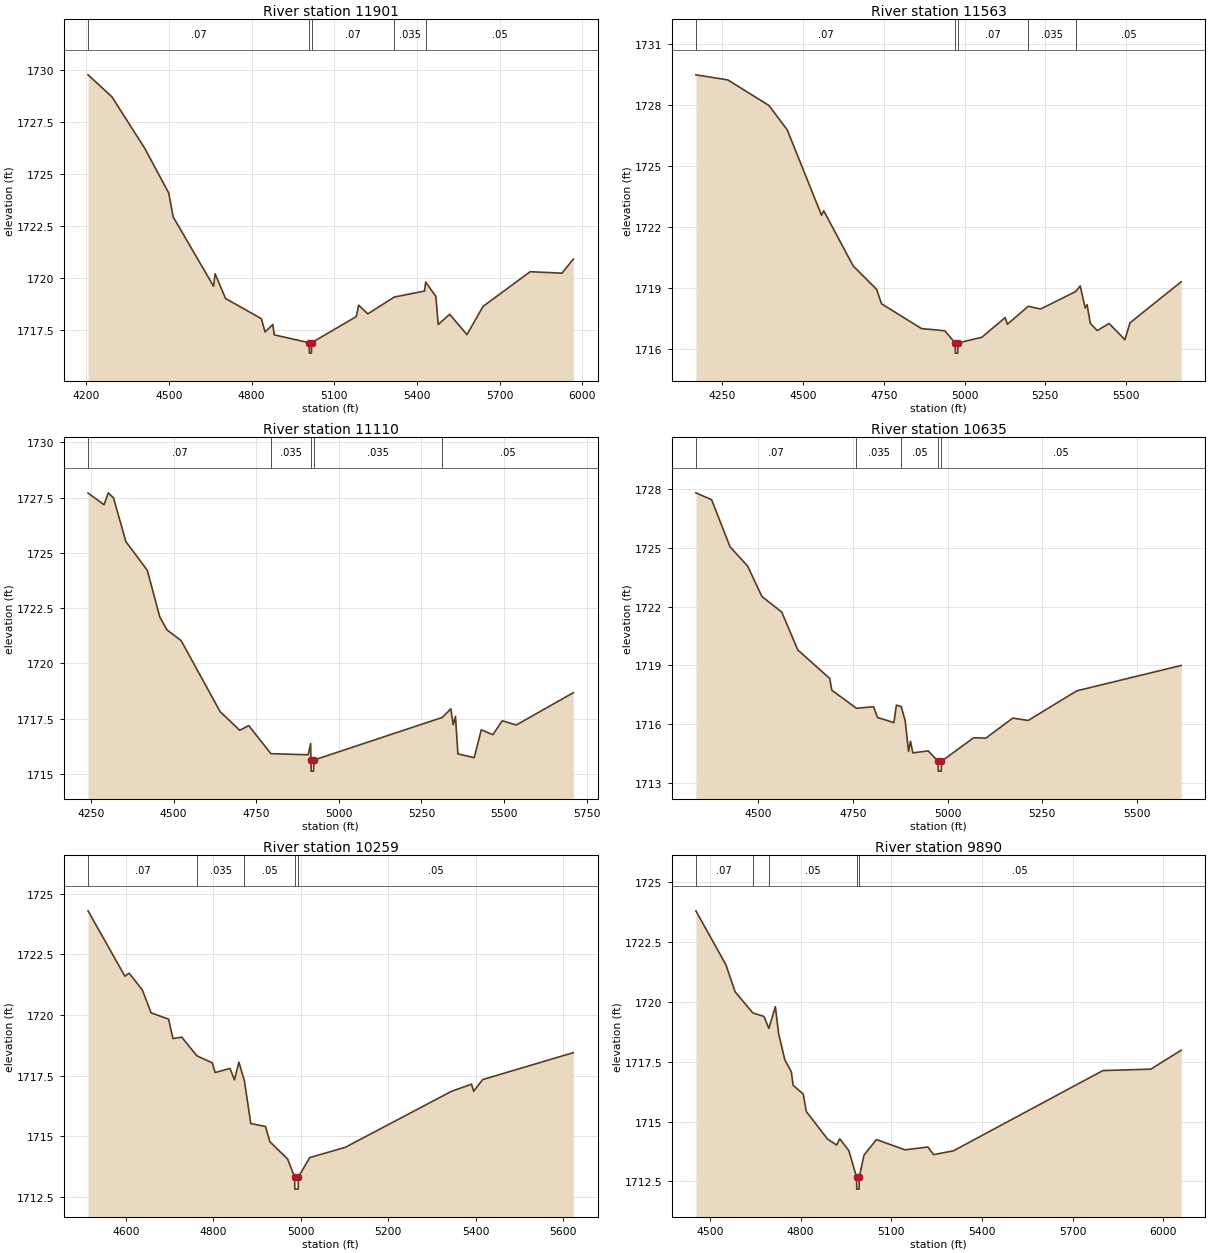
Type RM Length L Ch R = 1,11901,338,338,338
BEGIN DESCRIPTION:
Mapping XS 0818c394
END DESCRIPTION:
XS GIS Cut Line= 4
      1503080.84      6929800.83      1502823.01      6929334.64
      1502661.55      6928667.98      1502506.95      6928147.95
#Sta/Elev= 30
  4206.5 1729.78  4293.2 1728.72  4412.3 1726.24  4499.3 1724.09  4515.4 1722.94
  4662.0 1719.60  4667.7 1720.20  4705.5 1719.01  4835.3 1718.04  4849.0 1717.40
  4877.1 1717.76  4882.2 1717.26  5009.4 1716.88  5009.9 1716.38  5017.3 1716.38
  5017.8 1716.88  5180.1 1718.14  5188.5 1718.69  5221.9 1718.27  5317.9 1719.08
  5427.8 1719.37  5431.8 1719.80  5468.9 1719.11  5477.3 1717.76  5519.0 1718.25
  5581.6 1717.27  5640.1 1718.63  5811.2 1720.30  5926.5 1720.23  5967.7 1720.91
#Mann=5,-1,0
  4206.5    0.07       0  5009.4    0.07       0  5017.8    0.07       0
  5317.9   0.035       0  5431.8    0.05       0
Bank Sta=5009.4,5017.8
Exp/Cntr=0.3,0.1

Type RM Length L Ch R = 1,11563,453,453,453
BEGIN DESCRIPTION:
Mapping XS b24ea3ef
END DESCRIPTION:
XS GIS Cut Line= 4
      1503586.05      6929636.75      1503268.32      6929295.58
      1502955.82      6928816.42      1502719.40      6928416.32
#Sta/Elev= 30
  4167.7 1729.50  4266.6 1729.25  4394.1 1727.99  4450.7 1726.79  4556.8 1722.59
  4563.6 1722.81  4655.0 1720.09  4727.4 1718.94  4742.6 1718.23  4866.3 1717.01
  4938.7 1716.90  4970.8 1716.30  4971.3 1715.80  4978.7 1715.80  4979.2 1716.30
  5053.4 1716.58  5125.8 1717.55  5132.5 1717.22  5197.4 1718.11  5235.1 1717.97
  5343.9 1718.83  5358.0 1719.11  5373.6 1718.02  5379.4 1718.19  5389.2 1717.27
  5410.7 1716.91  5447.8 1717.26  5496.5 1716.46  5512.1 1717.29  5670.7 1719.31
#Mann=5,-1,0
  4167.7    0.07       0  4970.8    0.07       0  4979.2    0.07       0
  5197.4   0.035       0  5343.9    0.05       0
Bank Sta=4970.8,4979.2
Exp/Cntr=0.3,0.1

Type RM Length L Ch R = 1,11110,475,475,475
BEGIN DESCRIPTION:
Mapping XS 52184657
END DESCRIPTION:
XS GIS Cut Line= 4
      1503948.01      6929410.18      1503677.17      6928933.60
      1503226.65      6928782.56      1502921.96      6928457.04
#Sta/Elev= 30
  4240.8 1727.71  4289.3 1727.18  4302.0 1727.72  4317.9 1727.49  4355.4 1725.51
  4420.3 1724.21  4457.8 1722.11  4479.4 1721.52  4522.6 1721.03  4640.8 1717.81
  4700.0 1716.97  4727.3 1717.18  4794.6 1715.91  4907.3 1715.86  4914.6 1716.37
  4915.7 1715.62  4916.2 1715.12  4923.6 1715.12  4924.1 1715.62  5313.3 1717.55
  5339.1 1717.94  5346.4 1717.22  5353.2 1717.60  5360.5 1715.90  5409.9 1715.73
  5431.4 1716.99  5466.5 1716.77  5494.9 1717.40  5537.4 1717.21  5710.0 1718.67
#Mann=5,-1,0
  4240.8    0.07       0  4794.6   0.035       0  4915.7   0.035       0
  4924.1   0.035       0  5313.3    0.05       0
Bank Sta=4915.7,4924.1
Exp/Cntr=0.3,0.1

Type RM Length L Ch R = 1,10635,376,376,376
BEGIN DESCRIPTION:
Mapping XS 19c92baa
END DESCRIPTION:
XS GIS Cut Line= 4
      1504062.60      6929373.75      1503895.92      6928868.50
      1503812.59      6928399.75      1503666.74      6928167.95
#Sta/Elev= 30
  4335.0 1727.79  4376.6 1727.44  4425.3 1725.04  4471.8 1724.06  4509.5 1722.51
  4561.8 1721.72  4604.3 1719.79  4688.5 1718.34  4694.1 1717.74  4759.2 1716.82
  4804.4 1716.90  4814.9 1716.35  4858.2 1716.09  4864.7 1716.98  4877.3 1716.91
  4887.9 1716.19  4896.9 1714.62  4902.0 1715.14  4908.2 1714.55  4948.8 1714.65
  4974.9 1714.12  4975.4 1713.62  4983.2 1713.62  4983.7 1714.12  5068.9 1715.32
  5101.1 1715.30  5172.2 1716.32  5212.9 1716.20  5341.5 1717.71  5617.0 1719.00
#Mann=5,-1,0
  4335.0    0.07       0  4759.2   0.035       0  4877.3    0.05       0
  4974.9    0.05       0  4983.7    0.05       0
Bank Sta=4974.9,4983.7
Exp/Cntr=0.3,0.1

Type RM Length L Ch R = 1,10259,369,369,369
BEGIN DESCRIPTION:
Mapping XS a065cbd1
END DESCRIPTION:
XS GIS Cut Line= 3
      1504263.11      6929272.10      1504263.11      6928980.48
      1504132.91      6928173.24
#Sta/Elev= 30
  4513.5 1724.29  4597.6 1721.60  4607.6 1721.72  4637.6 1721.03  4657.6 1720.09
  4697.6 1719.83  4707.6 1719.03  4727.6 1719.09  4762.2 1718.32  4797.6 1718.03
  4803.9 1717.63  4838.0 1717.80  4848.2 1717.33  4858.3 1718.06  4870.9 1717.29
  4885.5 1715.53  4919.1 1715.41  4929.2 1714.78  4969.7 1714.07  4985.6 1713.33
  4986.1 1712.83  4993.9 1712.83  4994.4 1713.33  5020.3 1714.13  5101.4 1714.55
  5344.5 1716.86  5390.0 1717.15  5395.1 1716.86  5415.4 1717.34  5622.8 1718.45
#Mann=5,-1,0
  4513.5    0.07       0  4762.2   0.035       0  4870.9    0.05       0
  4985.6    0.05       0  4994.4    0.05       0
Bank Sta=4985.6,4994.4
Exp/Cntr=0.3,0.1

Type RM Length L Ch R = 1,9890,239,239,239
BEGIN DESCRIPTION:
Mapping XS 3a3ac423
END DESCRIPTION:
XS GIS Cut Line= 4
      1504489.67      6929274.76      1504562.59      6928959.64
      1504614.67      6928449.23      1504359.79      6927723.60
#Sta/Elev= 30
  4453.8 1723.80  4553.1 1721.55  4583.6 1720.42  4641.9 1719.54  4679.2 1719.39
  4695.2 1718.89  4716.8 1719.80  4727.6 1718.67  4748.1 1717.58  4769.8 1717.07
  4775.5 1716.52  4809.0 1716.15  4819.1 1715.42  4889.5 1714.27  4919.6 1714.02
  4929.7 1714.28  4959.8 1713.79  4985.6 1712.68  4986.1 1712.18  4993.9 1712.18
  4994.4 1712.68  5010.1 1713.60  5051.3 1714.25  5145.8 1713.82  5221.2 1713.94
  5240.3 1713.62  5306.0 1713.78  5800.4 1717.13  5959.3 1717.19  6059.4 1717.98
#Mann=5,-1,0
  4453.8    0.07       0  4641.9   0.035       0  4695.2    0.05       0
  4985.6    0.05       0  4994.4    0.05       0
Bank Sta=4985.6,4994.4
Exp/Cntr=0.3,0.1

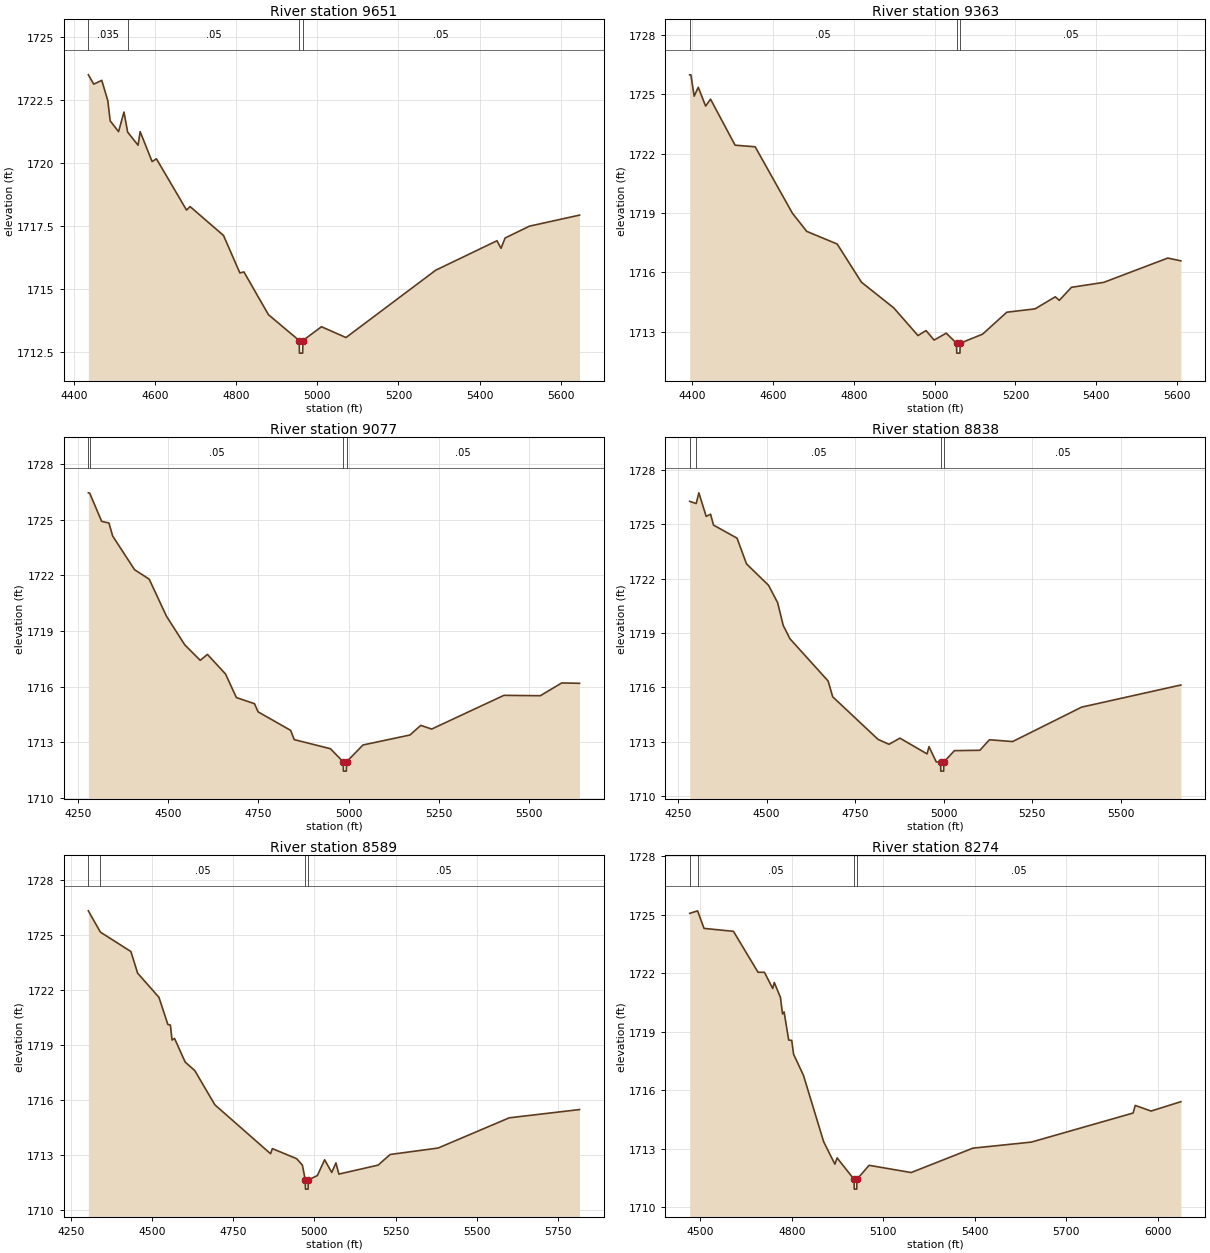
Type RM Length L Ch R = 1,9651,288,288,288
BEGIN DESCRIPTION:
Mapping XS 3afef87b
END DESCRIPTION:
XS GIS Cut Line= 4
      1504687.60      6929279.93      1504770.92      6928972.67
      1504843.84      6928303.39      1504846.44      6928084.61
#Sta/Elev= 30
  4435.7 1723.51  4449.1 1723.14  4468.8 1723.29  4483.7 1722.48  4489.5 1721.68
  4510.2 1721.25  4523.5 1722.03  4532.6 1721.23  4558.2 1720.71  4563.4 1721.25
  4592.8 1720.06  4603.5 1720.17  4677.7 1718.13  4686.4 1718.27  4768.8 1717.12
  4809.1 1715.63  4819.1 1715.67  4879.5 1713.97  4955.4 1712.94  4955.9 1712.44
  4963.9 1712.44  4964.4 1712.94  5010.2 1713.49  5070.6 1713.06  5291.9 1715.74
  5442.7 1716.91  5452.7 1716.61  5462.7 1717.02  5522.7 1717.49  5646.1 1717.93
#Mann=4,-1,0
  4435.7   0.035       0  4532.6    0.05       0  4955.4    0.05       0
  4964.4    0.05       0
Bank Sta=4955.4,4964.4
Exp/Cntr=0.3,0.1

Type RM Length L Ch R = 1,9363,286,286,286
BEGIN DESCRIPTION:
Mapping XS 305616f0
END DESCRIPTION:
XS GIS Cut Line= 4
      1505013.11      6929378.95      1505065.19      6929061.21
      1505065.19      6928332.04      1505020.91      6928173.14
#Sta/Elev= 30
  4393.5 1725.99  4396.5 1725.99  4404.6 1724.91  4414.7 1725.36  4433.0 1724.41
  4445.1 1724.76  4505.9 1722.43  4555.6 1722.35  4647.8 1718.99  4683.3 1718.07
  4758.7 1717.43  4818.7 1715.50  4898.7 1714.20  4958.7 1712.80  4978.7 1713.05
  4998.7 1712.57  5028.7 1712.92  5054.2 1712.41  5054.7 1711.91  5062.7 1711.91
  5063.2 1712.41  5118.7 1712.87  5178.7 1713.98  5248.7 1714.15  5298.7 1714.76
  5308.7 1714.58  5338.7 1715.24  5418.7 1715.49  5577.2 1716.72  5609.6 1716.58
#Mann=3,-1,0
  4393.5    0.05       0  5054.2    0.05       0  5063.2    0.05       0
Bank Sta=5054.2,5063.2
Exp/Cntr=0.3,0.1

Type RM Length L Ch R = 1,9077,239,239,239
BEGIN DESCRIPTION:
Mapping XS 76de6346
END DESCRIPTION:
XS GIS Cut Line= 4
      1505276.13      6929454.44      1505317.80      6929188.81
      1505359.46      6928246.10      1505331.09      6928101.67
#Sta/Elev= 30
  4279.6 1726.46  4283.4 1726.44  4316.5 1724.92  4336.7 1724.83  4346.9 1724.13
  4407.6 1722.31  4448.1 1721.80  4495.9 1719.80  4546.4 1718.26  4589.3 1717.42
  4609.3 1717.74  4659.4 1716.68  4689.4 1715.41  4739.5 1715.08  4749.5 1714.64
  4839.6 1713.64  4849.6 1713.14  4949.7 1712.65  4985.2 1711.94  4985.7 1711.44
  4993.8 1711.44  4994.3 1711.94  5039.8 1712.85  5169.9 1713.39  5199.9 1713.91
  5230.0 1713.71  5430.1 1715.53  5530.9 1715.51  5590.0 1716.20  5639.3 1716.18
#Mann=4,-1,0
  4279.6   0.035       0  4283.4    0.05       0  4985.2    0.05       0
  4994.3    0.05       0
Bank Sta=4985.2,4994.3
Exp/Cntr=0.3,0.1

Type RM Length L Ch R = 1,8838,249,249,249
BEGIN DESCRIPTION:
Mapping XS 9ad80ee0
END DESCRIPTION:
XS GIS Cut Line= 4
      1505385.52      6929483.04      1505487.07      6929105.48
      1505656.34      6928373.71      1505645.92      6928128.90
#Sta/Elev= 30
  4282.8 1726.26  4301.2 1726.14  4308.7 1726.73  4329.4 1725.43  4341.8 1725.55
  4350.1 1724.95  4416.5 1724.23  4443.3 1722.81  4505.5 1721.63  4531.2 1720.67
  4546.9 1719.42  4566.0 1718.68  4673.8 1716.35  4686.7 1715.48  4814.8 1713.13
  4845.7 1712.86  4876.5 1713.20  4953.2 1712.33  4958.6 1712.73  4979.1 1711.89
  4991.4 1711.88  4991.9 1711.38  5000.0 1711.38  5000.5 1711.88  5030.4 1712.51
  5102.3 1712.53  5129.2 1713.11  5194.7 1713.01  5389.7 1714.91  5669.9 1716.13
#Mann=4,-1,0
  4282.8   0.035       0  4301.2    0.05       0  4991.4    0.05       0
  5000.5    0.05       0
Bank Sta=4991.4,5000.5
Exp/Cntr=0.3,0.1

Type RM Length L Ch R = 1,8589,315,315,315
BEGIN DESCRIPTION:
Mapping XS e8c1b3c7
END DESCRIPTION:
XS GIS Cut Line= 4
      1505565.20      6929524.74      1505674.57      6929108.08
      1505929.78      6928545.58      1505836.36      6928091.45
#Sta/Elev= 30
  4304.2 1726.31  4341.2 1725.15  4435.2 1724.09  4455.9 1722.91  4521.6 1721.59
  4549.0 1720.11  4556.8 1720.08  4561.9 1719.26  4569.6 1719.35  4602.3 1718.06
  4631.7 1717.60  4693.7 1715.73  4865.2 1713.06  4870.7 1713.34  4945.5 1712.79
  4963.1 1712.44  4972.1 1711.63  4972.6 1711.13  4980.7 1711.13  4981.2 1711.63
  5009.2 1711.87  5031.6 1712.73  5053.5 1712.04  5066.4 1712.56  5075.5 1711.95
  5196.3 1712.44  5233.4 1713.02  5380.8 1713.37  5600.0 1715.02  5816.3 1715.47
#Mann=4,-1,0
  4304.2   0.035       0  4341.2    0.05       0  4972.1    0.05       0
  4981.2    0.05       0
Bank Sta=4972.1,4981.2
Exp/Cntr=0.3,0.1

Type RM Length L Ch R = 1,8274,287,287,287
BEGIN DESCRIPTION:
Mapping XS 7a3cd923
END DESCRIPTION:
XS GIS Cut Line= 4
      1505796.96      6929571.65      1505895.92      6929261.73
      1506140.71      6928792.98      1505937.59      6928063.80
#Sta/Elev= 30
  4464.9 1725.07  4490.9 1725.20  4511.9 1724.30  4608.4 1724.15  4689.2 1722.05
  4710.2 1722.05  4737.2 1721.22  4742.4 1721.53  4762.7 1720.76  4769.3 1719.92
  4774.6 1720.02  4789.6 1718.58  4799.6 1718.56  4805.7 1717.85  4838.1 1716.77
  4904.3 1713.37  4941.1 1712.22  4948.5 1712.54  5004.2 1711.44  5004.7 1710.94
  5012.9 1710.94  5013.4 1711.44  5053.3 1712.16  5191.4 1711.79  5394.0 1713.04
  5585.7 1713.35  5919.5 1714.84  5926.3 1715.23  5978.2 1714.94  6076.0 1715.42
#Mann=4,-1,0
  4464.9   0.035       0  4490.9    0.05       0  5004.2    0.05       0
  5013.4    0.05       0
Bank Sta=5004.2,5013.4
Exp/Cntr=0.3,0.1

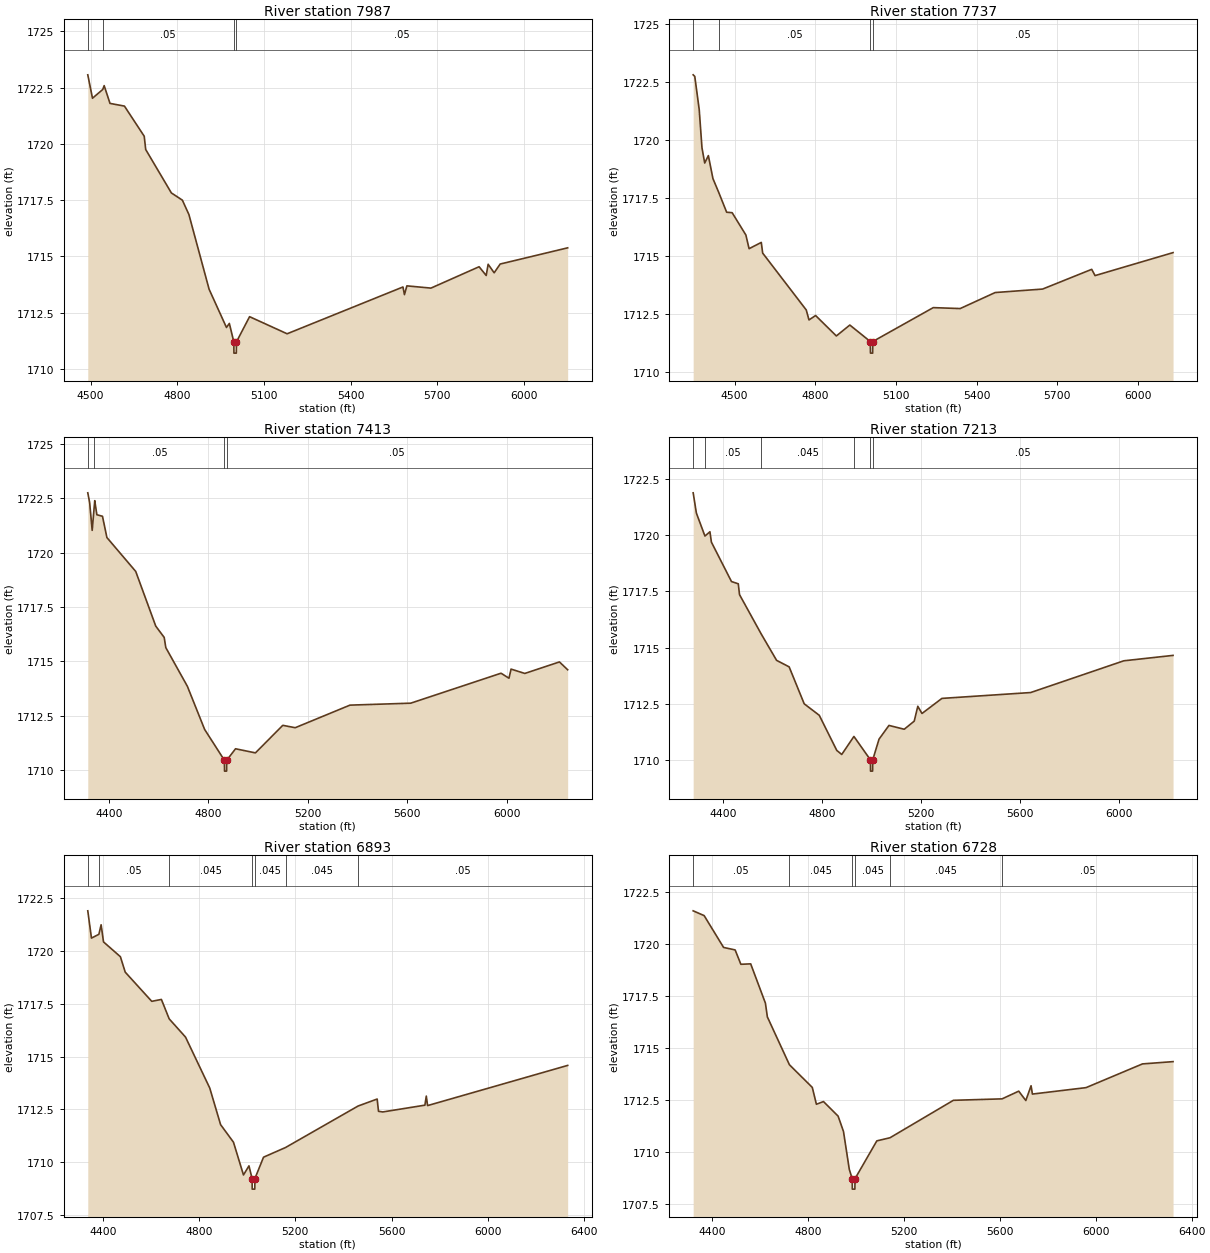
Type RM Length L Ch R = 1,7987,250,250,250
BEGIN DESCRIPTION:
Mapping XS d0e305ca
END DESCRIPTION:
XS GIS Cut Line= 4
      1506190.19      6929694.07      1506242.28      6929352.87
      1506257.90      6928704.44      1506070.39      6928063.78
#Sta/Elev= 30
  4490.4 1723.07  4506.7 1722.03  4542.3 1722.42  4547.1 1722.59  4567.3 1721.80
  4617.3 1721.68  4685.8 1720.34  4690.9 1719.75  4779.8 1717.82  4817.8 1717.50
  4840.5 1716.86  4910.4 1713.54  4970.5 1711.84  4980.5 1712.02  4995.9 1711.20
  4996.4 1710.70  5004.6 1710.70  5005.1 1711.20  5050.5 1712.32  5180.5 1711.56
  5581.5 1713.64  5586.7 1713.30  5595.1 1713.69  5678.4 1713.59  5845.1 1714.54
  5869.7 1714.15  5876.4 1714.65  5897.2 1714.27  5918.1 1714.66  6151.7 1715.38
#Mann=4,-1,0
  4490.4   0.035       0  4542.3    0.05       0  4995.9    0.05       0
  5005.1    0.05       0
Bank Sta=4995.9,5005.1
Exp/Cntr=0.3,0.1

Type RM Length L Ch R = 1,7737,324,324,324
BEGIN DESCRIPTION:
Mapping XS 07aaa357
END DESCRIPTION:
XS GIS Cut Line= 4
      1506349.04      6929740.05      1506453.21      6929230.04
      1506490.11      6928477.01      1506277.54      6928012.84
#Sta/Elev= 30
  4345.8 1722.79  4351.8 1722.72  4368.3 1721.29  4378.5 1719.65  4388.7 1718.99
  4402.3 1719.31  4419.3 1718.32  4440.3 1717.74  4470.4 1716.87  4490.8 1716.85
  4541.8 1715.89  4553.8 1715.30  4599.2 1715.57  4604.3 1715.11  4766.4 1712.66
  4776.6 1712.23  4801.2 1712.42  4878.4 1711.54  4928.5 1712.01  5004.7 1711.30
  5005.2 1710.80  5013.4 1710.80  5013.9 1711.30  5238.8 1712.76  5338.9 1712.72
  5469.1 1713.41  5645.6 1713.56  5828.2 1714.41  5840.7 1714.14  6130.8 1715.13
#Mann=4,-1,0
  4345.8   0.035       0  4440.3    0.05       0  5004.7    0.05       0
  5013.9    0.05       0
Bank Sta=5004.7,5013.9
Exp/Cntr=0.3,0.1

Type RM Length L Ch R = 1,7413,200,200,200
BEGIN DESCRIPTION:
Mapping XS a64921b4
END DESCRIPTION:
XS GIS Cut Line= 4
      1506639.85      6929805.12      1506770.05      6929310.34
      1506772.22      6928752.61      1506471.46      6927946.98
#Sta/Elev= 30
  4315.7 1722.76  4323.1 1722.32  4333.4 1721.03  4341.6 1722.12  4343.7 1722.40
  4352.2 1721.75  4374.8 1721.68  4392.6 1720.70  4508.4 1719.14  4589.0 1716.62
  4622.9 1716.10  4629.4 1715.63  4716.0 1713.85  4785.5 1711.86  4865.0 1710.44
  4865.5 1709.94  4873.8 1709.94  4874.3 1710.44  4909.7 1710.97  4989.7 1710.78
  5099.7 1712.05  5149.7 1711.94  5369.7 1712.98  5614.1 1713.07  5977.1 1714.45
  6009.1 1714.22  6017.4 1714.64  6072.7 1714.44  6211.9 1714.97  6245.0 1714.61
#Mann=4,-1,0
  4315.7   0.035       0  4341.6    0.05       0  4865.0    0.05       0
  4874.3    0.05       0
Bank Sta=4865,4874.3
Exp/Cntr=0.3,0.1

Type RM Length L Ch R = 1,7213,320,320,320
BEGIN DESCRIPTION:
Mapping XS 7c039bd5
END DESCRIPTION:
XS GIS Cut Line= 4
      1506828.64      6929850.74      1506926.30      6929284.30
      1506955.93      6929006.60      1506632.93      6927967.83
#Sta/Elev= 30
  4277.7 1721.87  4290.7 1720.97  4325.3 1719.95  4345.5 1720.14  4351.5 1719.68
  4432.7 1717.93  4460.2 1717.83  4465.2 1717.35  4553.1 1715.60  4615.3 1714.43
  4666.1 1714.14  4727.0 1712.50  4787.9 1711.99  4858.8 1710.43  4878.9 1710.25
  4928.2 1711.05  4995.0 1710.01  4995.5 1709.51  5003.8 1709.51  5004.3 1710.01
  5029.8 1710.93  5070.0 1711.54  5131.8 1711.37  5172.2 1711.73  5186.7 1712.39
  5203.6 1712.07  5284.3 1712.74  5643.4 1713.00  6020.4 1714.41  6219.6 1714.65
#Mann=6,-1,0
  4277.7   0.035       0  4325.3    0.05       0  4553.1   0.045       0
  4928.2    0.05       0  4995.0    0.05       0  5004.3    0.05       0
Bank Sta=4995,5004.3
Exp/Cntr=0.3,0.1

Type RM Length L Ch R = 1,6893,165,165,165
BEGIN DESCRIPTION:
Mapping XS 176e2692
END DESCRIPTION:
XS GIS Cut Line= 4
      1507208.42      6929883.27      1507243.14      6929332.04
      1507173.70      6929047.75      1506716.24      6927993.82
#Sta/Elev= 30
  4337.8 1721.89  4353.1 1720.60  4383.9 1720.78  4393.2 1721.23  4403.2 1720.42
  4473.3 1719.72  4493.4 1718.99  4603.6 1717.61  4643.7 1717.70  4676.1 1716.78
  4743.9 1715.92  4844.6 1713.51  4889.6 1711.78  4943.1 1710.95  4984.7 1709.40
  5007.5 1709.83  5020.5 1709.23  5021.0 1708.73  5031.7 1708.73  5032.2 1709.23
  5068.0 1710.24  5159.9 1710.70  5460.9 1712.66  5540.2 1712.99  5545.7 1712.41
  5563.7 1712.38  5738.5 1712.70  5744.3 1713.13  5749.7 1712.68  6331.7 1714.58
#Mann=7,-1,0
  4337.8   0.035       0  4383.9    0.05       0  4676.1   0.045       0
  5020.5   0.045       0  5032.2   0.045       0  5159.9   0.045       0
  5460.9    0.05       0
Bank Sta=5020.5,5032.2
Exp/Cntr=0.3,0.1

Type RM Length L Ch R = 1,6728,187,187,187
BEGIN DESCRIPTION:
Mapping XS a334b13b
END DESCRIPTION:
XS GIS Cut Line= 4
      1507549.14      6929842.05      1507442.80      6929373.27
      1507269.19      6928939.25      1506769.16      6928011.01
#Sta/Elev= 30
  4319.9 1721.58  4365.7 1721.35  4446.8 1719.82  4495.0 1719.70  4518.9 1719.01
  4559.9 1719.03  4621.4 1717.14  4629.5 1716.48  4721.5 1714.18  4817.0 1713.09
  4834.1 1712.28  4863.7 1712.41  4924.7 1711.71  4947.2 1710.97  4971.4 1709.15
  4983.5 1708.70  4984.0 1708.20  4994.7 1708.20  4995.2 1708.70  5086.3 1710.52
  5141.3 1710.67  5405.8 1712.47  5609.0 1712.54  5678.4 1712.91  5708.0 1712.46
  5729.9 1713.17  5735.5 1712.77  5959.4 1713.08  6194.7 1714.22  6322.4 1714.33
#Mann=6,-1,0
  4319.9    0.05       0  4721.5   0.045       0  4983.5    0.05       0
  4995.2   0.045       0  5141.3   0.045       0  5609.0    0.05       0
Bank Sta=4983.5,4995.2
Exp/Cntr=0.3,0.1

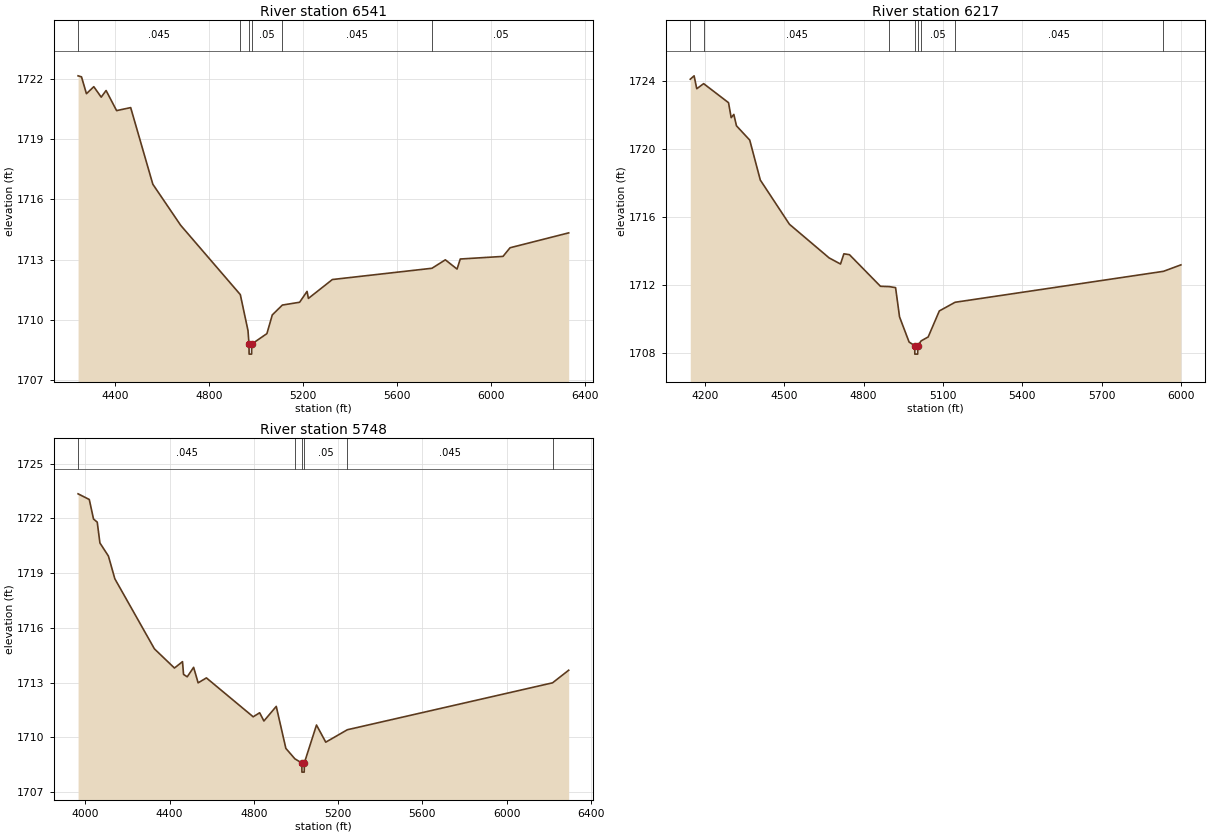
Type RM Length L Ch R = 1,6541,324,324,324
BEGIN DESCRIPTION:
Mapping XS 3f6425a8
END DESCRIPTION:
XS GIS Cut Line= 4
      1507807.37      6929842.00      1507648.96      6929325.53
      1507336.46      6928785.17      1506839.30      6928007.89
#Sta/Elev= 30
  4242.0 1722.15  4256.6 1722.10  4277.6 1721.26  4308.9 1721.61  4340.4 1721.09
  4361.2 1721.42  4405.9 1720.42  4465.8 1720.57  4560.0 1716.76  4678.3 1714.72
  4932.2 1711.27  4964.9 1709.48  4969.1 1708.81  4969.6 1708.31  4980.3 1708.31
  4980.8 1708.81  5045.3 1709.33  5068.2 1710.26  5111.0 1710.75  5184.5 1710.89
  5216.1 1711.43  5221.8 1711.08  5323.8 1712.02  5747.5 1712.58  5804.4 1713.00
  5854.2 1712.54  5867.9 1713.04  6049.7 1713.17  6079.7 1713.60  6329.1 1714.34
#Mann=6,-1,0
  4242.0   0.045       0  4932.2    0.05       0  4969.1    0.05       0
  4980.8    0.05       0  5111.0   0.045       0  5747.5    0.05       0
Bank Sta=4969.1,4980.8
Exp/Cntr=0.3,0.1

Type RM Length L Ch R = 1,6217,469,469,469
BEGIN DESCRIPTION:
Mapping XS cd7429c3
END DESCRIPTION:
XS GIS Cut Line= 4
      1508007.03      6929822.52      1507987.50      6929258.26
      1507559.99      6928615.89      1507152.02      6928296.90
#Sta/Elev= 30
  4144.8 1724.09  4159.3 1724.29  4169.3 1723.53  4195.3 1723.83  4289.4 1722.71
  4299.4 1721.83  4309.4 1722.02  4319.4 1721.35  4369.5 1720.51  4409.5 1718.16
  4519.5 1715.56  4669.6 1713.58  4712.6 1713.22  4725.3 1713.82  4746.4 1713.77
  4863.6 1711.91  4897.6 1711.89  4920.7 1711.83  4935.7 1710.11  4971.8 1708.63
  4993.0 1708.42  4993.5 1707.92  5004.2 1707.92  5004.7 1708.42  5017.4 1708.70
  5043.9 1708.93  5086.0 1710.46  5145.5 1710.97  5933.0 1712.79  5998.9 1713.17
#Mann=8,-1,0
  4144.8   0.035       0  4195.3   0.045       0  4897.6    0.07       0
  4993.0    0.07       0  5004.7    0.07       0  5017.4    0.05       0
  5145.5   0.045       0  5933.0    0.05       0
Bank Sta=4993,5004.7
Exp/Cntr=0.3,0.1

Type RM Length L Ch R = 1,5748,0,0,0
BEGIN DESCRIPTION:
NC Unknown Stream 40 6.0
END DESCRIPTION:
XS GIS Cut Line= 4
      1508136.16      6929830.59      1508270.71      6928932.19
      1508179.56      6928654.41      1507207.37      6928081.52
#Sta/Elev= 30
  3965.2 1723.34  4018.4 1723.03  4038.6 1721.96  4056.2 1721.79  4068.9 1720.65
  4109.4 1719.93  4139.7 1718.69  4327.7 1714.85  4422.8 1713.80  4461.0 1714.15
  4466.0 1713.45  4483.5 1713.32  4513.8 1713.84  4535.2 1712.99  4574.5 1713.26
  4796.6 1711.13  4827.3 1711.35  4847.5 1710.90  4906.1 1711.70  4951.7 1709.40
  4994.4 1708.83  5027.5 1708.60  5028.0 1708.10  5038.8 1708.10  5039.3 1708.60
  5097.1 1710.68  5141.1 1709.74  5243.4 1710.42  6217.8 1712.99  6294.4 1713.68
#Mann=6,-1,0
  3965.2   0.045       0  4994.4    0.05       0  5027.5    0.05       0
  5039.3    0.05       0  5243.4   0.045       0  6217.8    0.05       0
Bank Sta=5027.5,5039.3
Exp/Cntr=0.3,0.1

Chan Stop Cuts=-1