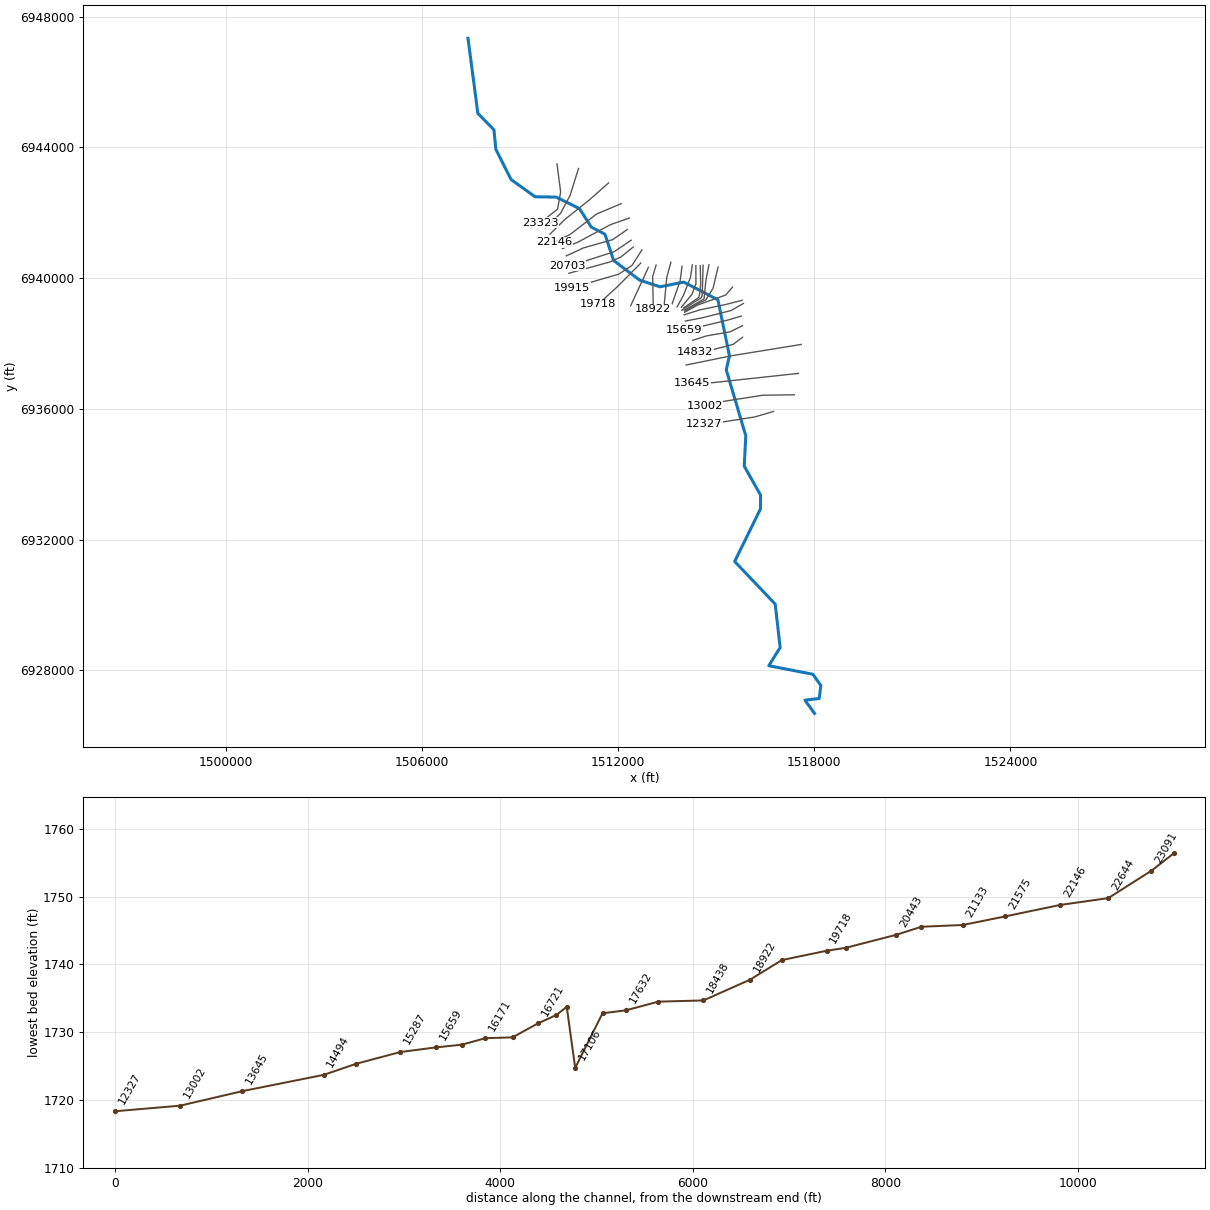
--- NC Unknown Stream 44.prj (project) ---

Proj Title=NC Unknown Stream 44 Base Level Engineering
Current Plan=p01
Default Exp/Contr=0.3,0.1
English Units
Geom File=g01
Flow File=f01
Plan File=p01
Y Axis Title=Elevation
X Axis Title(PF)=Main Channel Distance
X Axis Title(XS)=Station
BEGIN DESCRIPTION:
NC Unknown Stream 44
END DESCRIPTION:
DSS Export Rating Curves= 0
DSS Export Rating Curve Sorted= 0
DSS Export Volume Flow Curves= 0
DXF OffsetX= 0
DXF OffsetY= 0
DXF ScaleX= 1
DXF ScaleY= 10

--- NC Unknown Stream 44.p01 (plan) ---

Plan Title=Multiple Run
Short Identifier=Multiple
Geom File=g01
Flow File=f01
Subcritical Flow
K Sum by GR= 0
Std Step Tol= 0.01
Critical Tol= 0.01
Num of Std Step Trials= 20
Max Error Tol= 0.3
Flow Tol Ratio= 0.001
Split Flow NTrial= 30
Split Flow Tol= 0.02
Split Flow Ratio= 0.02
Log Output Level= 0
Friction Slope Method= 1
Unsteady Friction Slope Method= 2
Unsteady Bridges Friction Slope Method= 1
Parabolic Critical Depth
Global Vel Dist=  1 , 1 , 1
Global Log Level= 0
CheckData=True
Encroach Param= -1, 0, 0, 0
BEGIN DESCRIPTION:
Multiple Run
END DESCRIPTION:

--- NC Unknown Stream 44.f01 (steady flow) ---

Flow Title=Multiple
Program Version=4.10
Number of Profiles= 7
Profile Names=10-year,25-year,50-year,1pct_min,100-year,1pct_plu,500-year
River Rch & RM=NC Unknown Strea,Reach-1         ,23323
     360     506     628     387     773    1542    1187
River Rch & RM=NC Unknown Strea,Reach-1         ,21133
     438     621     775     480     958    1912    1486
River Rch & RM=NC Unknown Strea,Reach-1         ,14494
     794    1152    1461     918    1832    3655    2922
River Rch & RM=NC Unknown Strea,Reach-1         ,13002
     794    1152    1461     918    1832    3655    2922
River Rch & RM=NC Unknown Strea,Reach-1         ,7547
     777    1120    1412     882    1760    3512    2775
River Rch & RM=NC Unknown Strea,Reach-1         ,5945
     851    1227    1548     968    1931    3853    3046
River Rch & RM=NC Unknown Strea,Reach-1         ,2022
     851    1227    1548     968    1931    3853    3046
Boundary for River Rch & Prof#=NC Unknown Strea,Reach-1         , 1
Up Type= 0
Dn Type= 3
Dn Slope=0.001
Boundary for River Rch & Prof#=NC Unknown Strea,Reach-1         , 2
Up Type= 0
Dn Type= 3
Dn Slope=0.001
Boundary for River Rch & Prof#=NC Unknown Strea,Reach-1         , 3
Up Type= 0
Dn Type= 3
Dn Slope=0.001
Boundary for River Rch & Prof#=NC Unknown Strea,Reach-1         , 4
Up Type= 0
Dn Type= 3
Dn Slope=0.001
Boundary for River Rch & Prof#=NC Unknown Strea,Reach-1         , 5
Up Type= 0
Dn Type= 3
Dn Slope=0.001
Boundary for River Rch & Prof#=NC Unknown Strea,Reach-1         , 6
Up Type= 0
Dn Type= 3
Dn Slope=0.001
Boundary for River Rch & Prof#=NC Unknown Strea,Reach-1         , 7
Up Type= 0
Dn Type= 3
Dn Slope=0.001
DSS Import GetInterval= 0
DSS Import GetPeak= 0
DSS Import FillOption= 0

--- NC Unknown Stream 44.g01 (geometry) ---

Geom Title=Existing Conditions

River Reach=NC Unknown Strea,Reach-1
Reach XY= 30
      1507405.00      6947338.00      1507707.14      6945043.97
      1508199.17      6944540.30      1508258.62      6943939.50
      1508724.62      6943017.52      1509456.59      6942491.82
      1510108.58      6942480.12      1510815.05      6942127.37
      1511178.31      6941563.72      1511593.76      6941348.00
      1511860.25      6940543.44      1512652.53      6939943.45
      1513279.79      6939737.67      1514008.33      6939880.38
      1515049.91      6939340.30      1515404.48      6937622.78
      1515306.08      6937198.55      1515903.80      6935177.50
      1515856.22      6934248.50      1516355.04      6933368.02
      1516351.25      6932939.55      1515563.04      6931334.68
      1516802.74      6930032.06      1516954.62      6928703.16
      1516607.90      6928145.91      1517953.81      6927884.55
      1518199.66      6927540.74      1518149.59      6927143.17
      1517712.47      6927091.62      1518005.00      6926688.00

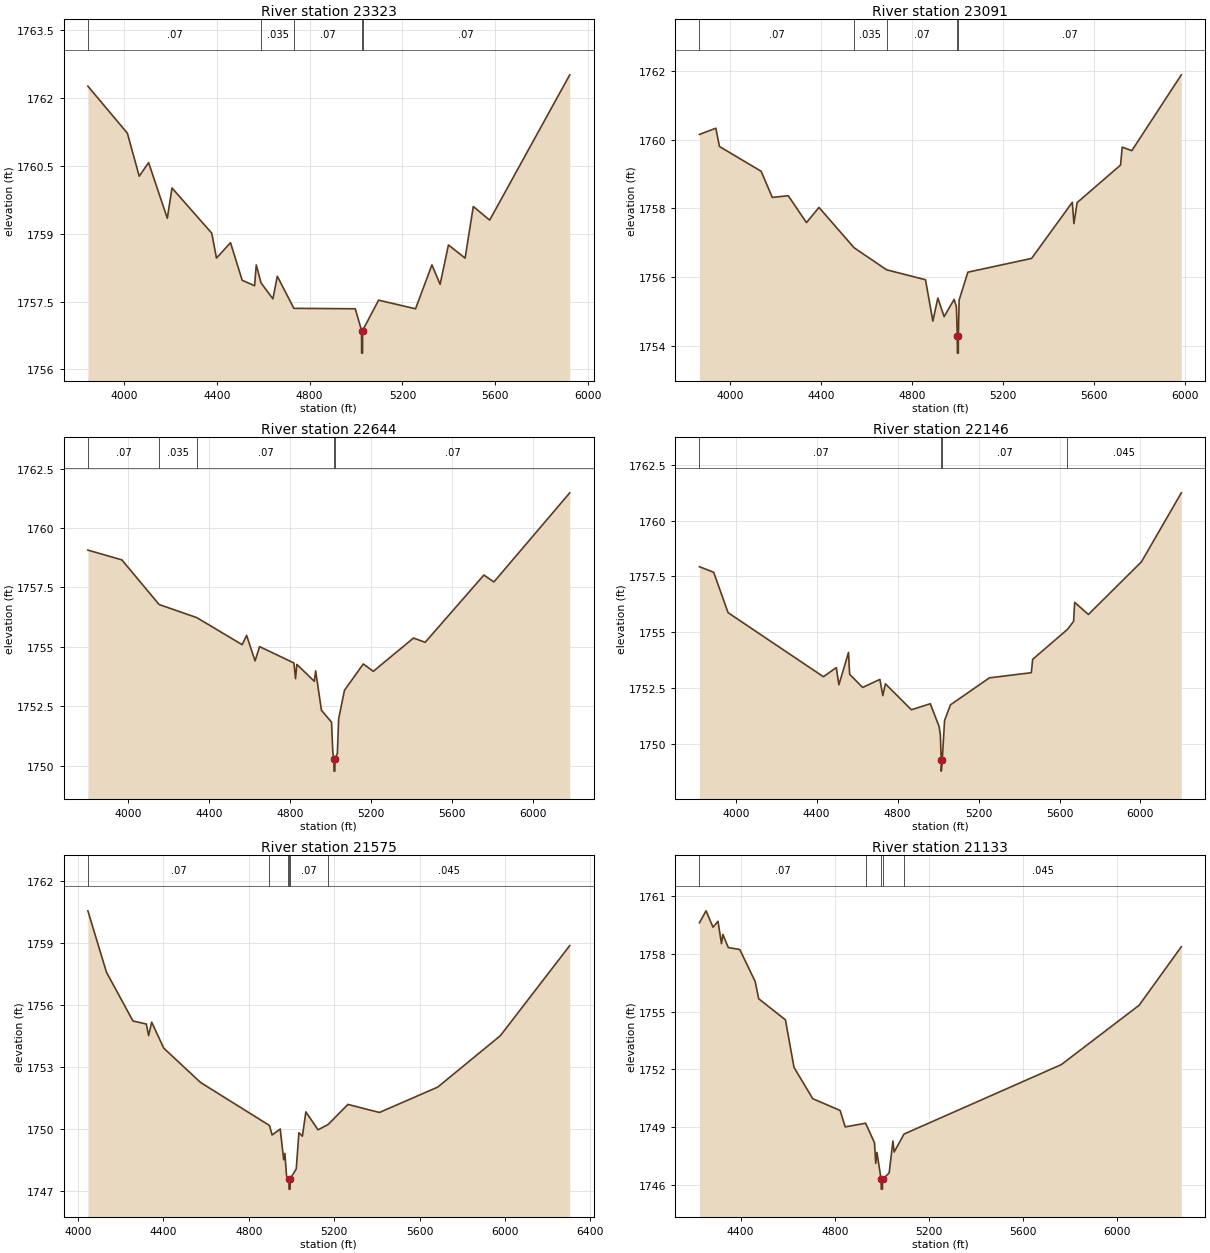
Type RM Length L Ch R = 1,23323,232,232,232
BEGIN DESCRIPTION:
Mapping XS 80690373
END DESCRIPTION:
XS GIS Cut Line= 4
      1510127.46      6943497.47      1510239.44      6942638.08
      1510145.69      6942112.04      1509611.83      6941697.97
#Sta/Elev= 30
  3844.3 1762.26  4014.5 1761.22  4065.6 1760.27  4106.0 1760.57  4186.6 1759.34
  4206.8 1760.01  4378.2 1759.01  4398.4 1758.46  4458.9 1758.80  4509.3 1757.97
  4562.7 1757.85  4569.9 1758.31  4590.7 1757.91  4641.7 1757.56  4660.6 1758.06
  4731.9 1757.35  4996.6 1757.34  5023.6 1756.86  5024.0 1756.36  5027.9 1756.36
  5028.2 1756.86  5097.0 1757.53  5256.3 1757.34  5326.9 1758.31  5362.2 1757.88
  5398.0 1758.75  5469.9 1758.46  5505.2 1759.60  5575.8 1759.30  5920.9 1762.51
#Mann=5,-1,0
  3844.3    0.07       0  4590.7   0.035       0  4731.9    0.07       0
  5023.6    0.07       0  5028.2    0.07       0
Bank Sta=5023.6,5028.2
Exp/Cntr=0.3,0.1

Type RM Length L Ch R = 1,23091,447,447,447
BEGIN DESCRIPTION:
Mapping XS f9f23420
END DESCRIPTION:
XS GIS Cut Line= 4
      1510786.32      6943356.84      1510528.50      6942533.91
      1510236.84      6941984.44      1509781.11      6941544.34
#Sta/Elev= 30
  3867.0 1760.15  3939.1 1760.33  3954.9 1759.80  4138.2 1759.08  4187.3 1758.32
  4257.4 1758.37  4337.4 1757.59  4392.4 1758.03  4546.7 1756.86  4689.5 1756.22
  4860.6 1755.93  4892.9 1754.73  4914.8 1755.40  4942.5 1754.86  4986.5 1755.36
  4996.5 1755.14  5000.4 1754.30  5000.8 1753.80  5004.8 1753.80  5005.1 1754.30
  5008.4 1755.34  5046.8 1756.15  5326.9 1756.55  5505.9 1758.18  5512.9 1757.56
  5527.0 1758.17  5717.9 1759.26  5725.1 1759.78  5767.6 1759.68  5985.0 1761.88
#Mann=5,-1,0
  3867.0    0.07       0  4546.7   0.035       0  4689.5    0.07       0
  5000.4    0.07       0  5005.1    0.07       0
Bank Sta=5000.4,5005.1
Exp/Cntr=0.3,0.1

Type RM Length L Ch R = 1,22644,498,498,498
BEGIN DESCRIPTION:
Mapping XS 3ad19f97
END DESCRIPTION:
XS GIS Cut Line= 4
      1511705.56      6942914.10      1511109.23      6942388.08
      1510361.84      6941791.73      1509913.93      6941349.03
#Sta/Elev= 30
  3801.6 1759.07  3969.3 1758.66  4153.7 1756.78  4339.4 1756.23  4564.1 1755.09
  4585.9 1755.48  4627.8 1754.41  4650.0 1755.01  4819.7 1754.32  4827.7 1753.66
  4834.1 1754.26  4920.6 1753.55  4927.0 1753.99  4955.8 1752.33  5005.5 1751.83
  5011.9 1750.56  5017.4 1750.27  5017.7 1749.77  5022.0 1749.77  5022.4 1750.27
  5034.3 1750.52  5040.7 1751.97  5069.5 1753.17  5162.4 1754.28  5212.0 1753.97
  5410.6 1755.37  5468.2 1755.19  5758.4 1758.02  5807.9 1757.73  6182.7 1761.48
#Mann=5,-1,0
  3801.6    0.07       0  4153.7   0.035       0  4339.4    0.07       0
  5017.4    0.07       0  5022.4    0.07       0
Bank Sta=5017.4,5022.4
Exp/Cntr=0.3,0.1

Type RM Length L Ch R = 1,22146,571,571,571
BEGIN DESCRIPTION:
Mapping XS 07ea3c65
END DESCRIPTION:
XS GIS Cut Line= 4
      1512088.38      6942278.70      1511338.40      6941963.60
      1510541.52      6941346.41      1510037.76      6941102.32
#Sta/Elev= 30
  3820.7 1757.93  3891.0 1757.68  3962.2 1755.87  4433.2 1753.00  4496.9 1753.41
  4509.9 1752.64  4557.4 1754.09  4562.8 1753.11  4627.0 1752.52  4712.4 1752.88
  4726.9 1752.15  4739.7 1752.68  4868.1 1751.52  4961.4 1751.79  5004.9 1750.77
  5011.2 1750.39  5015.4 1749.27  5015.8 1748.77  5020.5 1749.27  5032.0 1751.04
  5061.0 1751.74  5253.8 1752.95  5460.6 1753.18  5467.5 1753.78  5639.1 1755.12
  5669.5 1755.48  5675.0 1756.33  5742.7 1755.79  6005.0 1758.15  6201.9 1761.24
#Mann=4,-1,0
  3820.7    0.07       0  5015.4    0.07       0  5020.5    0.07       0
  5639.1   0.045       0
Bank Sta=5015.4,5020.5
Exp/Cntr=0.3,0.1

Type RM Length L Ch R = 1,21575,442,442,442
BEGIN DESCRIPTION:
Mapping XS e72d6bf3
END DESCRIPTION:
XS GIS Cut Line= 4
      1512343.63      6941841.21      1511762.88      6941638.08
      1510781.11      6941109.44      1510294.08      6940906.29
#Sta/Elev= 30
  4045.8 1760.55  4132.8 1757.58  4257.0 1755.22  4319.8 1755.07  4330.4 1754.51
  4344.8 1755.16  4401.6 1753.90  4574.1 1752.24  4896.8 1750.16  4909.0 1749.70
  4947.1 1749.99  4963.3 1748.50  4969.0 1748.81  4976.7 1747.72  4985.7 1747.60
  4987.9 1747.58  4988.4 1747.08  4993.4 1747.08  4993.9 1747.58  5022.1 1748.06
  5034.7 1749.81  5051.0 1749.64  5067.2 1750.82  5124.3 1749.95  5171.9 1750.21
  5264.3 1751.18  5412.0 1750.79  5685.4 1752.02  5978.9 1754.51  6303.8 1758.87
#Mann=6,-1,0
  4045.8    0.07       0  4896.8   0.045       0  4985.7    0.07       0
  4987.9    0.07       0  4993.9    0.07       0  5171.9   0.045       0
Bank Sta=4987.9,4993.9
Exp/Cntr=0.3,0.1

Type RM Length L Ch R = 1,21133,430,430,430
BEGIN DESCRIPTION:
Mapping XS 5bee3e91
END DESCRIPTION:
XS GIS Cut Line= 4
      1512275.88      6941487.03      1511830.59      6941179.75
      1510937.36      6940927.14      1510412.03      6940682.69
#Sta/Elev= 30
  4224.8 1759.59  4252.9 1760.21  4282.6 1759.36  4303.6 1759.67  4318.5 1758.51
  4324.5 1758.99  4347.4 1758.31  4396.2 1758.21  4461.8 1756.55  4476.7 1755.66
  4590.4 1754.57  4626.8 1752.11  4706.5 1750.49  4822.9 1749.88  4844.4 1749.03
  4931.2 1749.22  4969.1 1748.21  4974.3 1747.14  4979.5 1747.71  4997.2 1746.31
  4997.7 1745.81  5002.8 1745.81  5003.3 1746.31  5031.4 1746.65  5047.4 1748.30
  5052.6 1747.73  5094.6 1748.66  5762.9 1752.25  6093.8 1755.32  6273.5 1758.35
#Mann=5,-1,0
  4224.8    0.07       0  4931.2   0.045       0  4997.2    0.07       0
  5003.3   0.045       0  5094.6   0.045       0
Bank Sta=4997.2,5003.3
Exp/Cntr=0.3,0.1

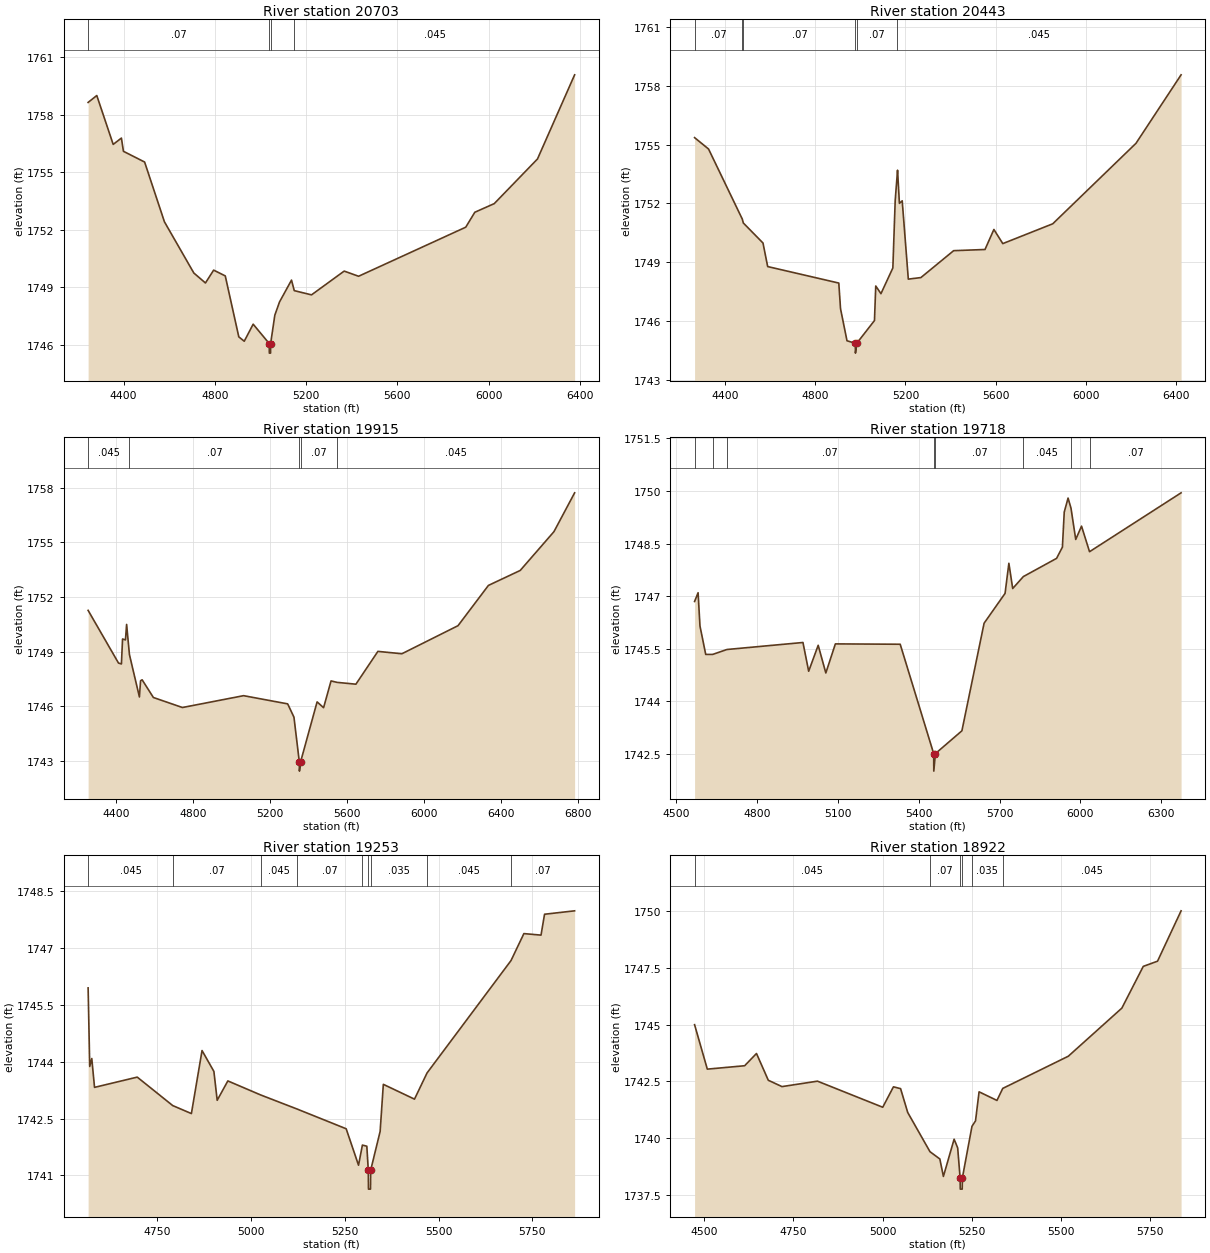
Type RM Length L Ch R = 1,20703,260,260,260
BEGIN DESCRIPTION:
Mapping XS 342425fc
END DESCRIPTION:
XS GIS Cut Line= 4
      1512395.68      6941161.51      1511877.46      6940809.96
      1511054.55      6940546.94      1510434.71      6940380.26
#Sta/Elev= 30
  4244.5 1758.63  4282.5 1758.99  4354.4 1756.44  4390.4 1756.77  4399.3 1756.08
  4492.1 1755.52  4579.0 1752.40  4707.8 1749.73  4758.7 1749.21  4794.6 1749.88
  4845.5 1749.58  4904.8 1746.40  4928.7 1746.17  4967.8 1747.06  5038.2 1746.05
  5038.7 1745.55  5043.9 1745.55  5044.4 1746.05  5062.7 1747.53  5083.3 1748.22
  5135.8 1749.36  5147.9 1748.81  5223.5 1748.59  5366.7 1749.83  5429.7 1749.56
  5899.3 1752.12  5939.2 1752.90  6024.3 1753.35  6213.8 1755.68  6376.5 1760.07
#Mann=4,-1,0
  4244.5    0.07       0  5038.2    0.07       0  5044.4    0.07       0
  5147.9   0.045       0
Bank Sta=5038.2,5044.4
Exp/Cntr=0.3,0.1

Type RM Length L Ch R = 1,20443,528,528,528
BEGIN DESCRIPTION:
Mapping XS cac55e66
END DESCRIPTION:
XS GIS Cut Line= 4
      1512463.40      6940955.79      1512077.98      6940645.89
      1511736.84      6940494.85      1510492.07      6940151.11
#Sta/Elev= 30
  4264.2 1755.35  4326.2 1754.77  4475.9 1751.20  4480.6 1751.00  4567.8 1749.98
  4588.6 1748.78  4904.2 1747.94  4911.9 1746.63  4940.6 1745.00  4977.6 1744.87
  4978.1 1744.37  4983.9 1744.87  5062.5 1746.03  5068.2 1747.79  5091.3 1747.40
  5144.1 1748.71  5154.5 1752.15  5162.0 1753.26  5164.9 1753.69  5173.2 1752.00
  5185.6 1752.13  5212.7 1748.14  5268.6 1748.22  5413.9 1749.59  5553.0 1749.65
  5592.5 1750.67  5632.0 1749.95  5853.7 1750.96  6223.0 1755.06  6423.2 1758.55
#Mann=6,-1,0
  4264.2    0.07       0  4475.9   0.045       0  4480.6    0.07       0
  4977.6    0.07       0  4983.9    0.07       0  5162.0   0.045       0
Bank Sta=4977.6,4983.9
Exp/Cntr=0.3,0.1

Type RM Length L Ch R = 1,19915,197,197,197
BEGIN DESCRIPTION:
Mapping XS 19e54fdb
END DESCRIPTION:
XS GIS Cut Line= 5
      1512726.42      6940864.65      1512421.73      6940390.69
      1512015.48      6940122.46      1511445.17      6939958.39
      1510593.60      6939703.18
#Sta/Elev= 30
  4252.3 1751.26  4410.5 1748.37  4425.7 1748.32  4431.6 1749.69  4446.8 1749.64
  4452.7 1750.49  4467.5 1748.83  4519.4 1746.51  4525.4 1747.40  4533.6 1747.45
  4592.1 1746.48  4743.3 1745.93  5061.6 1746.58  5291.2 1746.13  5323.9 1745.40
  5351.9 1742.94  5352.4 1742.44  5358.2 1742.94  5444.4 1746.24  5478.1 1745.92
  5517.0 1747.39  5547.9 1747.31  5646.4 1747.21  5760.9 1749.01  5885.8 1748.88
  6178.0 1750.42  6336.3 1752.63  6501.7 1753.45  6677.5 1755.58  6785.0 1757.71
#Mann=5,-1,0
  4252.3   0.045       0  4467.5    0.07       0  5351.9    0.07       0
  5358.2    0.07       0  5547.9   0.045       0
Bank Sta=5351.9,5358.2
Exp/Cntr=0.3,0.1

Type RM Length L Ch R = 1,19718,465,465,465
BEGIN DESCRIPTION:
Mapping XS 5b251256
END DESCRIPTION:
XS GIS Cut Line= 3
      1512689.93      6940461.42      1511992.70      6939756.79
      1511393.74      6939207.31
#Sta/Elev= 30
  4569.2 1746.85  4582.2 1747.10  4589.2 1746.15  4610.5 1745.34  4636.4 1745.34
  4689.2 1745.48  4971.1 1745.68  4992.3 1744.86  5027.6 1745.60  5055.9 1744.81
  5091.3 1745.64  5331.7 1745.63  5455.8 1742.51  5456.3 1742.01  5462.2 1742.51
  5560.5 1743.16  5642.8 1746.23  5720.5 1747.08  5734.7 1747.94  5748.9 1747.22
  5788.3 1747.56  5911.6 1748.08  5933.2 1748.40  5940.0 1749.40  5954.2 1749.80
  5965.1 1749.51  5982.6 1748.62  6004.1 1749.00  6033.8 1748.27  6373.3 1749.95
#Mann=8,-1,0
  4569.2    0.07       0  4636.4   0.045       0  4689.2    0.07       0
  5455.8    0.07       0  5462.2    0.07       0  5788.3   0.045       0
  5965.1   0.035       0  6033.8    0.07       0
Bank Sta=5455.8,5462.2
Exp/Cntr=0.3,0.1

Type RM Length L Ch R = 1,19253,331,331,331
BEGIN DESCRIPTION:
Mapping XS f0364695
END DESCRIPTION:
XS GIS Cut Line= 3
      1512923.24      6940333.59      1512807.80      6940077.10
      1512380.71      6939155.20
#Sta/Elev= 30
  4565.3 1745.94  4569.6 1743.87  4575.1 1744.08  4582.4 1743.32  4696.3 1743.59
  4791.0 1742.84  4840.7 1742.63  4869.1 1744.29  4900.7 1743.74  4909.5 1742.98
  4937.9 1743.49  5025.5 1743.12  5122.4 1742.75  5253.4 1742.23  5286.4 1741.27
  5296.7 1741.80  5308.5 1741.77  5312.4 1741.14  5312.9 1740.64  5318.3 1740.64
  5318.8 1741.14  5344.0 1742.16  5352.5 1743.40  5435.6 1743.01  5469.1 1743.70
  5693.0 1746.66  5727.3 1747.37  5773.0 1747.33  5782.4 1747.88  5862.6 1747.97
#Mann=9,-1,0
  4565.3   0.045       0  4791.0    0.07       0  5025.5   0.045       0
  5122.4    0.07       0  5296.7   0.035       0  5312.4    0.07       0
  5318.8   0.035       0  5469.1   0.045       0  5693.0    0.07       0
Bank Sta=5312.4,5318.8
Exp/Cntr=0.3,0.1

Type RM Length L Ch R = 1,18922,484,484,484
BEGIN DESCRIPTION:
Mapping XS df25e2f6
END DESCRIPTION:
XS GIS Cut Line= 3
      1513159.38      6940400.06      1513055.20      6940051.06
      1513073.41      6939052.04
#Sta/Elev= 30
  4472.8 1745.00  4508.5 1743.04  4613.1 1743.19  4646.3 1743.73  4679.4 1742.55
  4717.8 1742.27  4817.2 1742.51  5000.1 1741.36  5030.1 1742.26  5050.1 1742.18
  5070.1 1741.13  5132.5 1739.40  5160.1 1739.08  5170.1 1738.31  5200.1 1739.95
  5210.1 1739.57  5216.9 1738.25  5217.4 1737.75  5222.8 1737.75  5223.3 1738.25
  5250.2 1740.52  5260.1 1740.76  5270.1 1742.04  5320.2 1741.66  5336.4 1742.19
  5520.2 1743.61  5670.2 1745.73  5730.2 1747.57  5770.2 1747.80  5836.2 1750.02
#Mann=6,-1,0
  4472.8   0.045       0  5132.5    0.07       0  5216.9   0.045       0
  5223.3    0.07       0  5250.2   0.035       0  5336.4   0.045       0
Bank Sta=5216.9,5223.3
Exp/Cntr=0.3,0.1

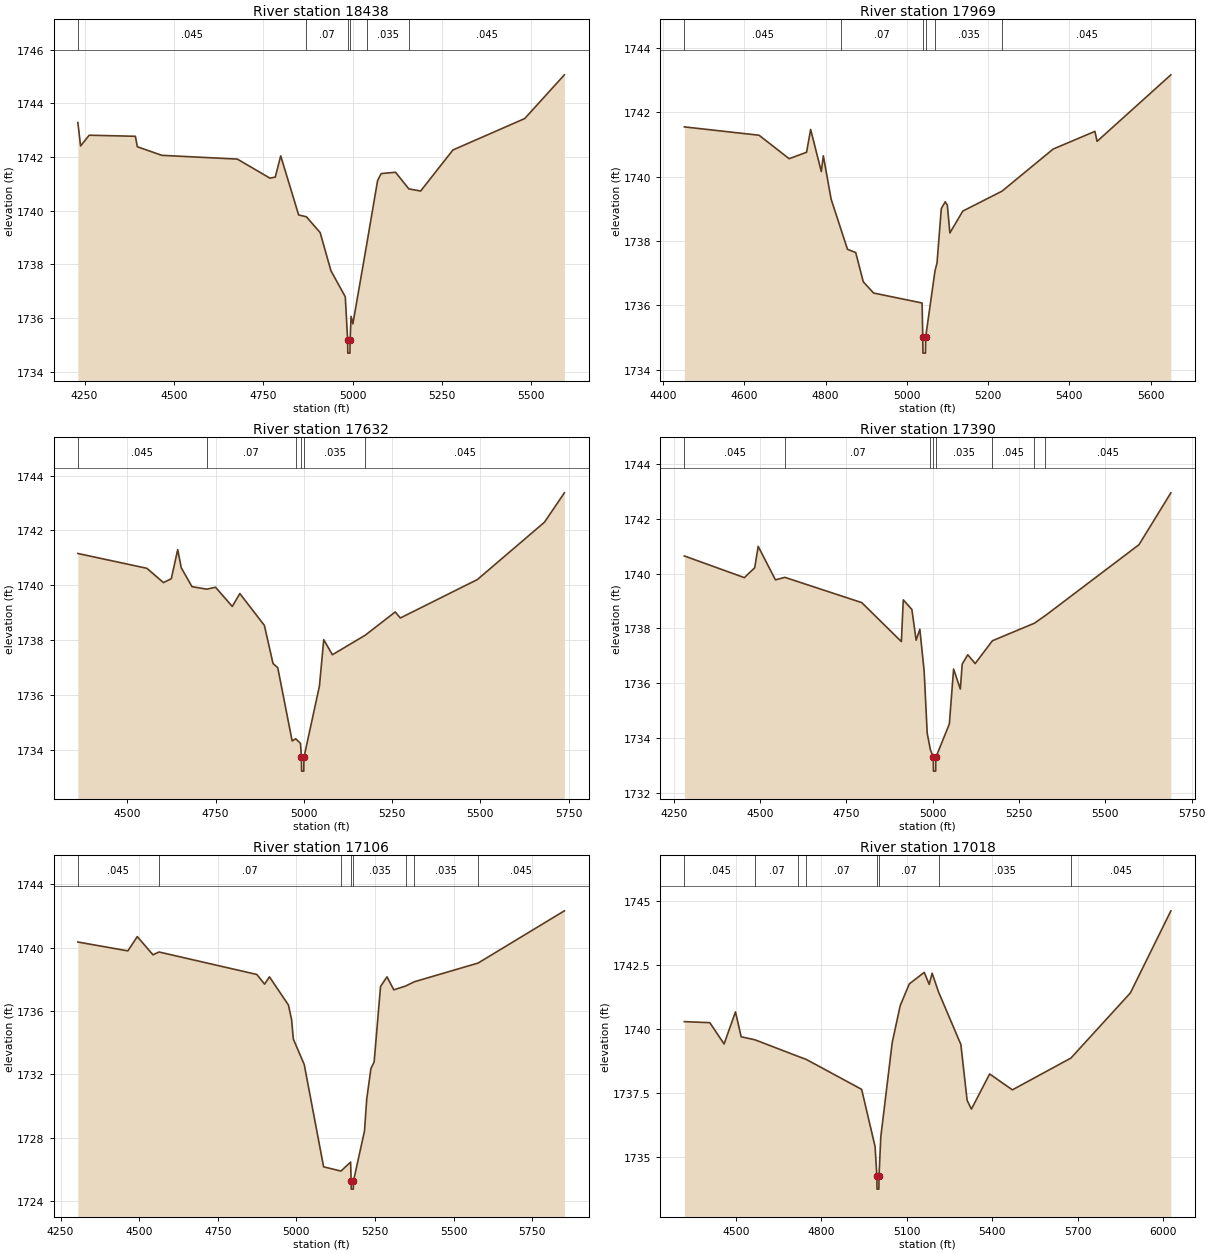
Type RM Length L Ch R = 1,18438,469,469,469
BEGIN DESCRIPTION:
Mapping XS 71c63dfe
END DESCRIPTION:
XS GIS Cut Line= 3
      1513612.49      6940488.56      1513487.49      6940032.83
      1513404.15      6939147.40
#Sta/Elev= 30
  4231.2 1743.28  4238.8 1742.41  4262.9 1742.81  4392.2 1742.77  4397.7 1742.38
  4466.3 1742.06  4677.7 1741.92  4768.9 1741.21  4783.8 1741.25  4799.0 1742.04
  4849.2 1739.84  4871.0 1739.77  4909.5 1739.18  4939.6 1737.76  4979.8 1736.79
  4986.3 1735.19  4986.8 1734.69  4992.8 1734.69  4993.3 1735.19  4996.0 1736.06
  5001.0 1735.78  5039.7 1738.74  5070.2 1741.12  5080.2 1741.38  5120.4 1741.43
  5157.7 1740.81  5190.7 1740.73  5281.1 1742.26  5482.0 1743.43  5593.1 1745.06
#Mann=6,-1,0
  4231.2   0.045       0  4871.0    0.07       0  4986.3    0.07       0
  4993.3    0.07       0  5039.7   0.035       0  5157.7   0.045       0
Bank Sta=4986.3,4993.3
Exp/Cntr=0.3,0.1

Type RM Length L Ch R = 1,17969,337,337,337
BEGIN DESCRIPTION:
Mapping XS a557dd41
END DESCRIPTION:
XS GIS Cut Line= 3
      1513953.63      6940366.17      1513896.34      6939926.06
      1513649.55      6939214.25
#Sta/Elev= 30
  4452.6 1741.55  4636.5 1741.29  4710.5 1740.56  4753.3 1740.76  4763.4 1741.47
  4789.6 1740.16  4794.6 1740.65  4813.8 1739.30  4838.3 1738.35  4854.1 1737.74
  4874.3 1737.64  4892.9 1736.73  4918.3 1736.38  5037.6 1736.07  5039.3 1735.01
  5039.8 1734.51  5045.9 1734.51  5046.4 1735.01  5069.5 1737.08  5074.3 1737.31
  5084.9 1739.01  5094.6 1739.22  5099.8 1739.11  5106.0 1738.25  5137.8 1738.93
  5234.3 1739.55  5360.1 1740.86  5462.9 1741.41  5468.2 1741.10  5649.8 1743.17
#Mann=6,-1,0
  4452.6   0.045       0  4838.3    0.07       0  5039.3    0.07       0
  5046.4    0.07       0  5069.5   0.035       0  5234.3   0.045       0
Bank Sta=5039.3,5046.4
Exp/Cntr=0.3,0.1

Type RM Length L Ch R = 1,17632,242,242,242
BEGIN DESCRIPTION:
Mapping XS 83dfeafc
END DESCRIPTION:
XS GIS Cut Line= 4
      1514268.74      6940407.81      1514211.45      6940025.02
      1513995.30      6939472.93      1513802.58      6939123.96
#Sta/Elev= 30
  4359.5 1741.16  4555.1 1740.62  4602.0 1740.10  4624.2 1740.24  4642.4 1741.30
  4652.5 1740.64  4682.9 1739.95  4725.1 1739.86  4749.6 1739.93  4797.0 1739.23
  4818.5 1739.70  4888.0 1738.54  4912.5 1737.15  4925.9 1737.00  4966.7 1734.33
  4976.8 1734.41  4990.4 1734.24  4993.0 1733.73  4993.5 1733.23  4999.6 1733.23
  5000.1 1733.73  5044.0 1736.33  5056.2 1738.02  5080.7 1737.47  5173.5 1738.18
  5258.8 1739.03  5273.3 1738.81  5491.5 1740.21  5681.7 1742.30  5738.1 1743.37
#Mann=6,-1,0
  4359.5   0.045       0  4725.1    0.07       0  4976.8   0.035       0
  4993.0   0.035       0  5000.1   0.035       0  5173.5   0.045       0
Bank Sta=4993,5000.1
Exp/Cntr=0.3,0.1

Type RM Length L Ch R = 1,17390,284,284,284
BEGIN DESCRIPTION:
Mapping XS d5254ad3
END DESCRIPTION:
XS GIS Cut Line= 4
      1514375.51      6940381.79      1514378.11      6939827.10
      1514258.32      6939509.39      1513931.02      6939111.96
#Sta/Elev= 30
  4280.7 1740.64  4454.5 1739.85  4484.5 1740.21  4494.5 1740.99  4544.5 1739.77
  4571.9 1739.86  4794.5 1738.94  4909.2 1737.52  4914.8 1739.04  4939.7 1738.69
  4952.0 1737.57  4962.7 1737.97  4975.2 1736.45  4984.1 1734.18  4993.1 1733.59
  5001.7 1733.30  5002.2 1732.80  5008.6 1732.80  5009.1 1733.30  5048.2 1734.52
  5060.5 1736.52  5080.0 1735.79  5085.4 1736.70  5101.6 1737.04  5123.0 1736.72
  5172.9 1737.55  5294.6 1738.19  5326.5 1738.47  5597.4 1741.05  5689.8 1742.94
#Mann=8,-1,0
  4280.7   0.045       0  4571.9    0.07       0  4993.1   0.035       0
  5001.7   0.035       0  5009.1   0.035       0  5172.9   0.045       0
  5294.6   0.035       0  5326.5   0.045       0
Bank Sta=5001.7,5009.1
Exp/Cntr=0.3,0.1

Type RM Length L Ch R = 1,17106,88,88,88
BEGIN DESCRIPTION:
Mapping XS f932b13b
END DESCRIPTION:
XS GIS Cut Line= 5
      1514510.93      6940386.97      1514523.95      6939829.70
      1514490.09      6939519.81      1514469.26      6939415.64
      1514000.49      6939087.50
#Sta/Elev= 30
  4304.9 1740.36  4463.9 1739.80  4493.9 1740.70  4543.9 1739.55  4562.9 1739.73
  4874.1 1738.31  4898.9 1737.70  4914.3 1738.16  4974.7 1736.38  4984.7 1735.47
  4990.3 1734.23  5025.0 1732.62  5086.6 1726.16  5141.8 1725.89  5172.5 1726.46
  5174.1 1725.25  5174.6 1724.75  5181.0 1724.75  5181.5 1725.25  5216.7 1728.43
  5223.7 1730.43  5237.1 1732.37  5247.3 1732.78  5267.7 1737.55  5288.2 1738.16
  5309.9 1737.34  5347.4 1737.58  5375.3 1737.85  5577.9 1739.03  5852.5 1742.33
#Mann=8,-1,0
  4304.9   0.045       0  4562.9    0.07       0  5141.8   0.035       0
  5174.1    0.07       0  5181.5   0.035       0  5347.4   0.045       0
  5375.3   0.035       0  5577.9   0.045       0
Bank Sta=5174.1,5181.5
Exp/Cntr=0.3,0.1

Type RM Length L Ch R = 1,17018,108,108,108
BEGIN DESCRIPTION:
Mapping XS 2183c8df
END DESCRIPTION:
XS GIS Cut Line= 6
      1514596.86      6940397.43      1514581.24      6939803.66
      1514565.61      6939457.31      1514529.15      6939389.60
      1514326.03      6939267.20      1513945.86      6939019.83
#Sta/Elev= 30
  4319.0 1740.28  4408.5 1740.24  4458.5 1739.41  4498.5 1740.66  4518.5 1739.69
  4567.4 1739.57  4717.3 1738.93  4746.6 1738.81  4941.5 1737.64  4988.7 1735.41
  4995.0 1734.25  4995.5 1733.75  5002.0 1733.75  5002.5 1734.25  5008.7 1735.78
  5048.8 1739.46  5076.8 1740.90  5108.8 1741.75  5161.3 1742.20  5178.9 1741.73
  5188.9 1742.17  5211.8 1741.43  5289.9 1739.39  5311.9 1737.21  5327.0 1736.87
  5391.0 1738.24  5470.7 1737.62  5676.4 1738.86  5885.2 1741.40  6027.3 1744.60
#Mann=8,-1,0
  4319.0   0.045       0  4567.4    0.07       0  4717.3   0.045       0
  4746.6    0.07       0  4995.0    0.07       0  5002.5    0.07       0
  5211.8   0.035       0  5676.4   0.045       0
Bank Sta=4995,5002.5
Exp/Cntr=0.3,0.1

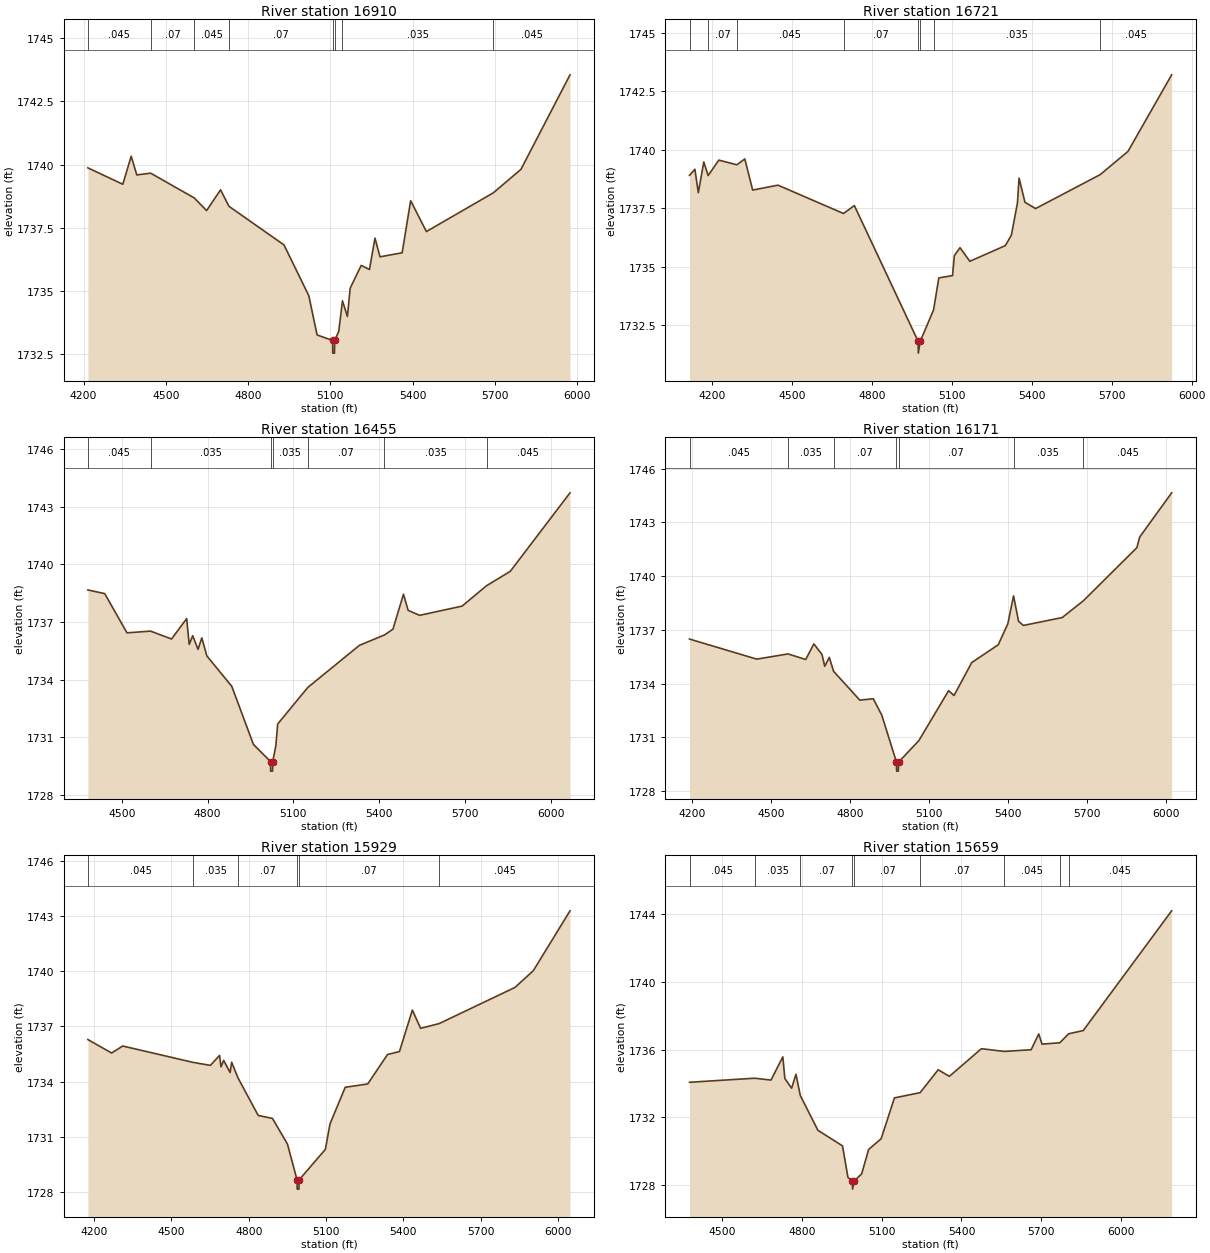
Type RM Length L Ch R = 1,16910,189,189,189
BEGIN DESCRIPTION:
Mapping XS 0706d1e2
END DESCRIPTION:
XS GIS Cut Line= 4
      1514776.55      6940413.04      1514682.80      6939926.06
      1514625.51      6939363.56      1514019.36      6939020.16
#Sta/Elev= 30
  4216.0 1739.87  4343.3 1739.22  4373.9 1740.33  4394.3 1739.59  4444.9 1739.66
  4603.7 1738.68  4648.8 1738.18  4699.8 1739.00  4730.3 1738.35  4931.1 1736.82
  5021.6 1734.81  5051.7 1733.26  5108.3 1733.04  5108.8 1732.54  5115.3 1732.54
  5115.8 1733.04  5130.7 1733.40  5144.3 1734.61  5162.3 1733.99  5172.4 1735.11
  5212.6 1736.01  5242.7 1735.85  5262.8 1737.09  5281.1 1736.35  5361.9 1736.51
  5392.9 1738.57  5450.3 1737.35  5694.1 1738.88  5795.1 1739.81  5974.0 1743.55
#Mann=8,-1,0
  4216.0   0.045       0  4444.9    0.07       0  4603.7   0.045       0
  4730.3    0.07       0  5108.3    0.07       0  5115.8    0.07       0
  5144.3   0.035       0  5694.1   0.045       0
Bank Sta=5108.3,5115.8
Exp/Cntr=0.3,0.1

Type RM Length L Ch R = 1,16721,266,266,266
BEGIN DESCRIPTION:
Mapping XS 9926ceab
END DESCRIPTION:
XS GIS Cut Line= 5
      1515055.19      6940340.11      1514904.15      6939699.50
      1514685.40      6939337.52      1514424.99      6939212.52
      1514042.18      6938996.37
#Sta/Elev= 30
  4115.3 1738.91  4135.4 1739.17  4148.3 1738.17  4168.8 1739.48  4185.2 1738.90
  4225.2 1739.56  4292.8 1739.36  4322.9 1739.61  4352.2 1738.28  4447.2 1738.49
  4693.2 1737.28  4733.9 1737.62  4973.5 1731.82  4974.0 1731.32  4981.1 1731.82
  5031.4 1733.17  5051.0 1734.53  5102.4 1734.63  5109.2 1735.48  5130.6 1735.82
  5167.4 1735.24  5300.8 1735.91  5323.4 1736.36  5346.1 1737.73  5352.2 1738.79
  5374.3 1737.76  5414.0 1737.49  5656.7 1738.94  5760.9 1739.93  5924.9 1743.20
#Mann=8,-1,0
  4115.3   0.045       0  4185.2    0.07       0  4292.8   0.045       0
  4693.2    0.07       0  4973.5    0.07       0  4981.1    0.07       0
  5031.4   0.035       0  5656.7   0.045       0
Bank Sta=4973.5,4981.1
Exp/Cntr=0.3,0.1

Type RM Length L Ch R = 1,16455,284,284,284
BEGIN DESCRIPTION:
Mapping XS 3b301868
END DESCRIPTION:
XS GIS Cut Line= 4
      1515497.91      6939728.15      1515289.57      6939485.95
      1514440.61      6939183.87      1514031.72      6938959.89
#Sta/Elev= 30
  4381.4 1738.67  4440.2 1738.48  4518.2 1736.44  4600.6 1736.53  4674.0 1736.12
  4727.0 1737.18  4735.9 1735.84  4748.2 1736.29  4766.7 1735.58  4780.0 1736.18
  4797.6 1735.24  4884.8 1733.66  4960.5 1730.64  5020.3 1729.75  5020.8 1729.25
  5027.5 1729.25  5028.0 1729.75  5038.9 1730.56  5045.4 1731.70  5150.7 1733.60
  5331.4 1735.79  5419.0 1736.33  5448.7 1736.63  5485.6 1738.45  5501.8 1737.61
  5541.9 1737.35  5690.5 1737.83  5776.2 1738.89  5859.3 1739.64  6068.2 1743.72
#Mann=7,-1,0
  4381.4   0.045       0  4600.6   0.035       0  5020.3   0.035       0
  5028.0   0.035       0  5150.7    0.07       0  5419.0   0.035       0
  5776.2   0.045       0
Bank Sta=5020.3,5028
Exp/Cntr=0.3,0.1

Type RM Length L Ch R = 1,16171,242,242,242
BEGIN DESCRIPTION:
Mapping XS 734668e4
END DESCRIPTION:
XS GIS Cut Line= 4
      1515792.14      6939324.49      1515260.93      6939189.08
      1514492.70      6939030.23      1514019.33      6938879.37
#Sta/Elev= 30
  4190.3 1736.49  4445.3 1735.37  4564.1 1735.66  4631.1 1735.35  4662.1 1736.22
  4693.0 1735.63  4703.3 1734.97  4720.7 1735.47  4737.0 1734.69  4836.5 1733.08
  4887.5 1733.16  4920.0 1732.24  4975.6 1729.62  4976.1 1729.12  4982.8 1729.12
  4983.3 1729.62  5060.4 1730.82  5173.4 1733.61  5193.9 1733.34  5261.3 1735.18
  5361.7 1736.17  5398.1 1737.34  5419.8 1738.90  5438.9 1737.48  5457.1 1737.25
  5604.5 1737.69  5684.3 1738.62  5887.9 1741.59  5898.4 1742.18  6019.8 1744.65
#Mann=7,-1,0
  4190.3   0.045       0  4564.1   0.035       0  4737.0    0.07       0
  4975.6    0.07       0  4983.3    0.07       0  5419.8   0.035       0
  5684.3   0.045       0
Bank Sta=4975.6,4983.3
Exp/Cntr=0.3,0.1

Type RM Length L Ch R = 1,15929,270,270,270
BEGIN DESCRIPTION:
Mapping XS 4aef8d3f
END DESCRIPTION:
XS GIS Cut Line= 4
      1515831.23      6939228.14      1515456.24      6939012.00
      1514578.63      6938790.64      1514055.21      6938689.08
#Sta/Elev= 30
  4175.9 1736.29  4268.0 1735.56  4311.1 1735.94  4584.6 1735.05  4651.3 1734.89
  4686.9 1735.43  4692.5 1734.81  4702.8 1735.16  4727.9 1734.50  4733.8 1735.06
  4758.0 1734.22  4836.9 1732.17  4892.2 1732.01  4950.3 1730.62  4987.7 1728.67
  4988.2 1728.17  4995.0 1728.17  4995.5 1728.67  5097.6 1730.33  5115.3 1731.70
  5174.6 1733.70  5261.9 1733.88  5338.8 1735.48  5385.1 1735.64  5435.1 1737.89
  5467.2 1736.90  5539.4 1737.16  5833.3 1739.12  5904.6 1740.03  6047.0 1743.28
#Mann=6,-1,0
  4175.9   0.045       0  4584.6   0.035       0  4758.0    0.07       0
  4987.7    0.07       0  4995.5    0.07       0  5539.4   0.045       0
Bank Sta=4987.7,4995.5
Exp/Cntr=0.3,0.1

Type RM Length L Ch R = 1,15659,372,372,372
BEGIN DESCRIPTION:
Mapping XS 107fb7e3
END DESCRIPTION:
XS GIS Cut Line= 4
      1515768.73      6938842.72      1515367.70      6938722.93
      1514503.11      6938514.60      1514005.74      6938420.85
#Sta/Elev= 30
  4376.8 1734.07  4621.6 1734.31  4683.3 1734.20  4727.8 1735.57  4735.5 1734.29
  4760.9 1733.72  4777.3 1734.54  4793.6 1733.29  4859.8 1731.24  4952.4 1730.32
  4973.0 1728.45  4989.6 1728.27  4990.1 1727.77  4997.4 1728.27  5024.4 1728.67
  5050.7 1730.11  5097.7 1730.74  5147.8 1733.15  5244.5 1733.46  5312.4 1734.81
  5354.4 1734.42  5475.0 1736.05  5560.6 1735.89  5662.2 1735.99  5690.6 1736.92
  5703.1 1736.32  5770.0 1736.40  5803.3 1736.93  5858.1 1737.12  6190.8 1744.18
#Mann=9,-1,0
  4376.8   0.045       0  4621.6   0.035       0  4793.6    0.07       0
  4989.6   0.035       0  4997.4    0.07       0  5244.5    0.07       0
  5560.6   0.045       0  5770.0    0.07       0  5803.3   0.045       0
Bank Sta=4989.6,4997.4
Exp/Cntr=0.3,0.1

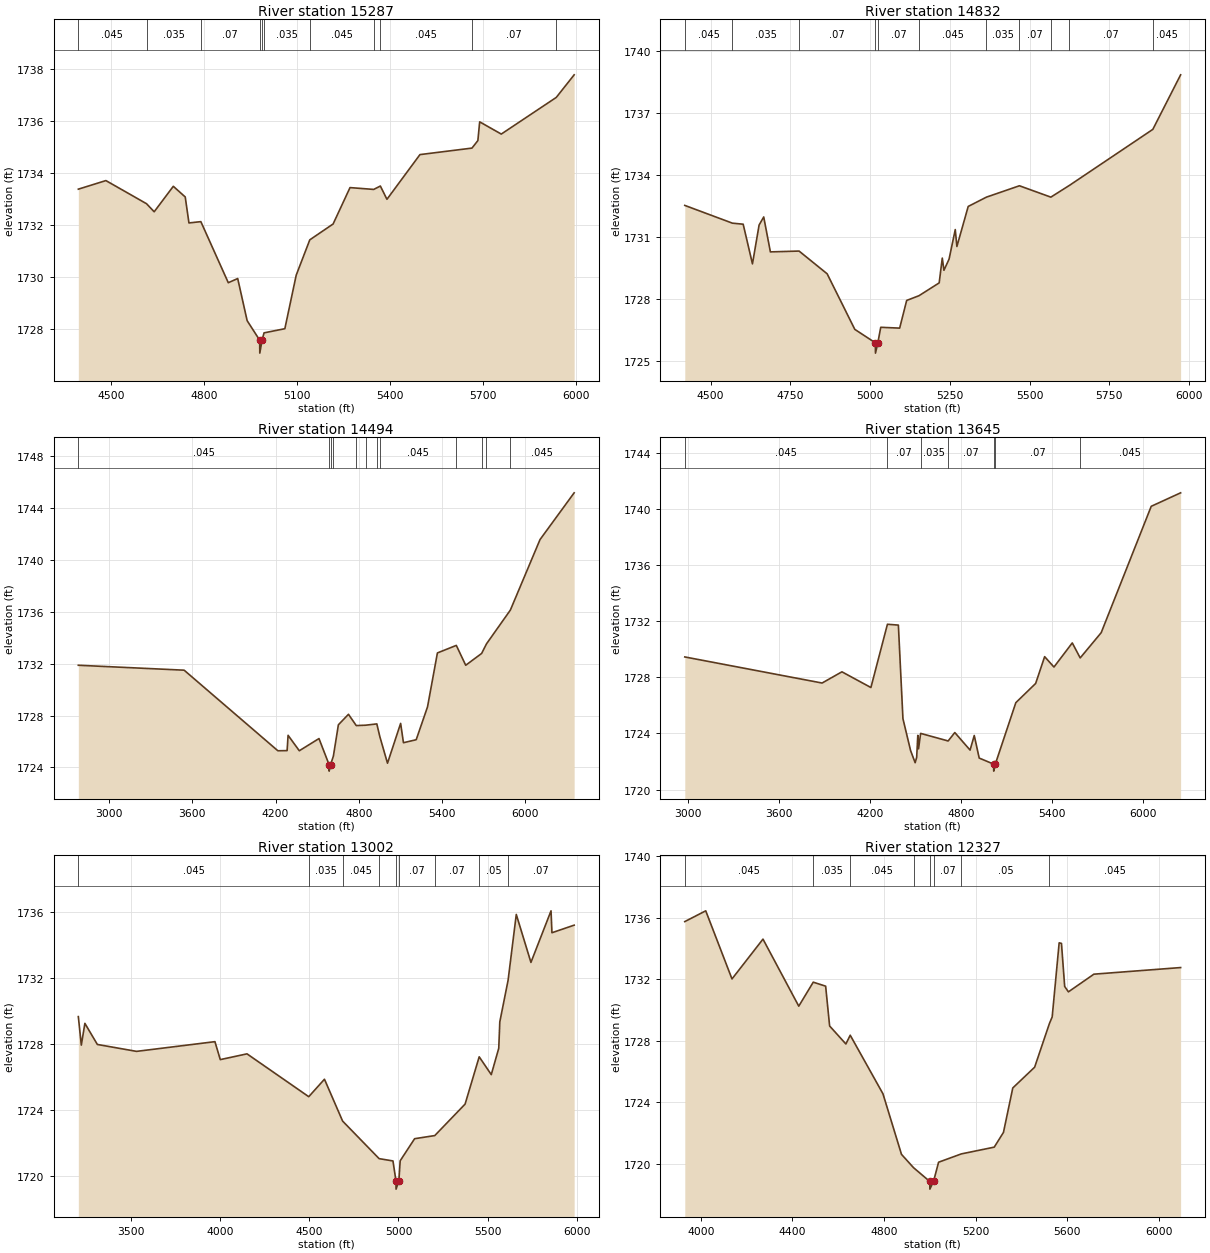
Type RM Length L Ch R = 1,15287,455,455,455
BEGIN DESCRIPTION:
Mapping XS 99b86b15
END DESCRIPTION:
XS GIS Cut Line= 4
      1515804.94      6938548.39      1515422.99      6938360.89
      1514704.24      6938235.89      1514278.56      6938100.92
#Sta/Elev= 30
  4393.4 1733.39  4482.5 1733.72  4613.7 1732.83  4638.4 1732.52  4700.2 1733.50
  4738.7 1733.09  4750.7 1732.09  4789.2 1732.14  4877.8 1729.79  4908.2 1729.95
  4938.7 1728.33  4979.1 1727.58  4979.6 1727.08  4986.9 1727.58  4993.3 1727.86
  5060.5 1728.02  5097.2 1730.08  5141.1 1731.44  5216.4 1732.05  5271.0 1733.45
  5347.5 1733.38  5369.0 1733.51  5390.3 1733.00  5496.9 1734.72  5664.9 1734.97
  5684.0 1735.26  5689.8 1735.98  5759.6 1735.51  5937.2 1736.92  5995.0 1737.79
#Mann=11,-1,0
  4393.4   0.045       0  4613.7   0.035       0  4789.2    0.07       0
  4979.1   0.035       0  4986.9    0.07       0  4993.3   0.035       0
  5141.1   0.045       0  5347.5   0.035       0  5369.0   0.045       0
  5664.9    0.07       0  5937.2   0.045       0
Bank Sta=4979.1,4986.9
Exp/Cntr=0.3,0.1

Type RM Length L Ch R = 1,14832,338,338,338
BEGIN DESCRIPTION:
Mapping XS 10da964b
END DESCRIPTION:
XS GIS Cut Line= 4
      1515804.94      6938194.23      1515516.74      6937975.47
      1514884.80      6937812.28      1514350.04      6937739.36
#Sta/Elev= 30
  4419.1 1732.51  4568.4 1731.65  4602.1 1731.60  4631.2 1729.68  4652.0 1731.56
  4666.5 1731.95  4687.4 1730.26  4777.3 1730.30  4865.3 1729.20  4952.0 1726.51
  5016.3 1725.86  5016.8 1725.36  5024.2 1725.86  5033.3 1726.61  5092.6 1726.57
  5114.6 1727.91  5153.3 1728.14  5216.5 1728.76  5226.2 1729.96  5231.4 1729.37
  5247.5 1729.91  5266.9 1731.34  5272.0 1730.52  5307.5 1732.46  5364.6 1732.91
  5468.0 1733.46  5566.5 1732.91  5624.9 1733.48  5886.2 1736.19  5973.3 1738.83
#Mann=11,-1,0
  4419.1   0.045       0  4568.4   0.035       0  4777.3    0.07       0
  5016.3    0.07       0  5024.2    0.07       0  5153.3   0.045       0
  5364.6   0.035       0  5468.0    0.07       0  5566.5   0.035       0
  5624.9    0.07       0  5886.2   0.045       0
Bank Sta=5016.3,5024.2
Exp/Cntr=0.3,0.1

Type RM Length L Ch R = 1,14494,849,849,849
BEGIN DESCRIPTION:
NC Unknown Stream 44 8.0
END DESCRIPTION:
XS GIS Cut Line= 3
      1517598.38      6937973.74      1515478.55      6937629.99
      1514078.74      6937343.78
#Sta/Elev= 30
  2777.5 1731.88  3540.7 1731.50  4216.7 1725.29  4283.4 1725.30  4290.4 1726.48
  4371.4 1725.29  4513.3 1726.23  4586.1 1724.22  4586.6 1723.72  4597.0 1724.22
  4617.2 1724.88  4653.2 1727.29  4726.0 1728.10  4782.2 1727.23  4849.9 1727.26
  4930.6 1727.36  4951.9 1726.39  5007.5 1724.33  5102.2 1727.40  5122.6 1725.91
  5214.5 1726.14  5296.1 1728.67  5367.5 1732.83  5503.8 1733.41  5571.7 1731.88
  5686.4 1732.79  5721.5 1733.53  5893.6 1736.13  6107.8 1741.57  6353.8 1745.17
#Mann=12,-1,0
  2777.5   0.045       0  4586.1   0.045       0  4597.0   0.045       0
  4617.2   0.035       0  4782.2    0.07       0  4849.9   0.045       0
  4930.6    0.07       0  4951.9   0.045       0  5503.8    0.07       0
  5686.4   0.035       0  5721.5    0.07       0  5893.6   0.045       0
Bank Sta=4586.1,4597
Exp/Cntr=0.3,0.1

Type RM Length L Ch R = 1,13645,643,643,643
BEGIN DESCRIPTION:
NC Unknown Stream 44 7.0
END DESCRIPTION:
XS GIS Cut Line= 3
      1517515.01      6937088.32      1514861.25      6936801.54
      1514261.26      6936801.54
#Sta/Elev= 30
  2977.9 1729.45  3883.2 1727.59  4013.9 1728.39  4205.0 1727.27  4314.0 1731.78
  4386.1 1731.72  4416.2 1725.05  4466.5 1722.78  4496.7 1721.91  4506.8 1722.29
  4514.2 1723.86  4519.2 1722.90  4532.8 1724.00  4714.4 1723.46  4758.2 1724.06
  4858.8 1722.81  4886.4 1723.85  4919.1 1722.24  5014.2 1721.81  5014.7 1721.31
  5025.3 1721.81  5160.5 1726.19  5291.3 1727.56  5350.5 1729.47  5412.0 1728.73
  5532.7 1730.45  5585.0 1729.38  5723.4 1731.18  6053.4 1740.19  6247.1 1741.15
#Mann=7,-1,0
  2977.9   0.045       0  4314.0    0.07       0  4532.8   0.035       0
  4714.4    0.07       0  5014.2    0.07       0  5025.3    0.07       0
  5585.0   0.045       0
Bank Sta=5014.2,5025.3
Exp/Cntr=0.3,0.1

Type RM Length L Ch R = 1,13002,675,675,675
BEGIN DESCRIPTION:
Mapping XS 3ad181ab
END DESCRIPTION:
XS GIS Cut Line= 4
      1517391.77      6936433.81      1516422.99      6936419.92
      1515200.77      6936228.94      1514639.15      6936093.74
#Sta/Elev= 30
  3202.8 1729.65  3219.6 1727.92  3239.6 1729.24  3309.6 1727.96  3529.6 1727.54
  3969.7 1728.13  3999.7 1727.04  4149.7 1727.39  4496.4 1724.79  4584.6 1725.85
  4686.5 1723.31  4891.5 1721.03  4969.2 1720.89  4986.1 1719.68  4986.6 1719.18
  5002.3 1719.68  5009.7 1720.90  5090.7 1722.24  5203.9 1722.43  5374.1 1724.34
  5453.3 1727.21  5521.1 1726.13  5563.1 1727.73  5569.0 1729.33  5615.4 1731.85
  5661.5 1735.85  5743.8 1732.94  5856.6 1736.07  5861.7 1734.74  5986.4 1735.20
#Mann=9,-1,0
  3202.8   0.045       0  4496.4   0.035       0  4686.5   0.045       0
  4891.5    0.07       0  4986.1    0.05       0  5002.3    0.07       0
  5203.9    0.07       0  5453.3    0.05       0  5615.4    0.07       0
Bank Sta=4986.1,5002.3
Exp/Cntr=0.3,0.1

Type RM Length L Ch R = 1,12327,572,572,572
BEGIN DESCRIPTION:
Mapping XS e8bf1d20
END DESCRIPTION:
XS GIS Cut Line= 4
      1516752.82      6935923.38      1516166.05      6935753.25
      1515023.69      6935576.17      1514628.88      6935531.15
#Sta/Elev= 30
  3930.1 1735.76  4021.5 1736.46  4136.1 1732.03  4271.4 1734.62  4427.6 1730.26
  4490.8 1731.82  4544.9 1731.56  4562.3 1728.97  4633.2 1727.80  4652.2 1728.37
  4795.1 1724.56  4876.0 1720.62  4928.9 1719.75  4999.4 1718.86  4999.9 1718.36
  5015.8 1718.86  5037.9 1720.11  5137.0 1720.65  5280.8 1721.09  5321.1 1722.05
  5361.8 1724.94  5457.2 1726.29  5521.7 1729.13  5533.8 1729.56  5564.2 1734.38
  5574.3 1734.34  5588.3 1731.54  5604.6 1731.19  5715.8 1732.34  6094.4 1732.77
#Mann=8,-1,0
  3930.1   0.045       0  4490.8   0.035       0  4652.2   0.045       0
  4928.9    0.07       0  4999.4    0.07       0  5015.8    0.07       0
  5137.0    0.05       0  5521.7   0.045       0
Bank Sta=4999.4,5015.8
Exp/Cntr=0.3,0.1