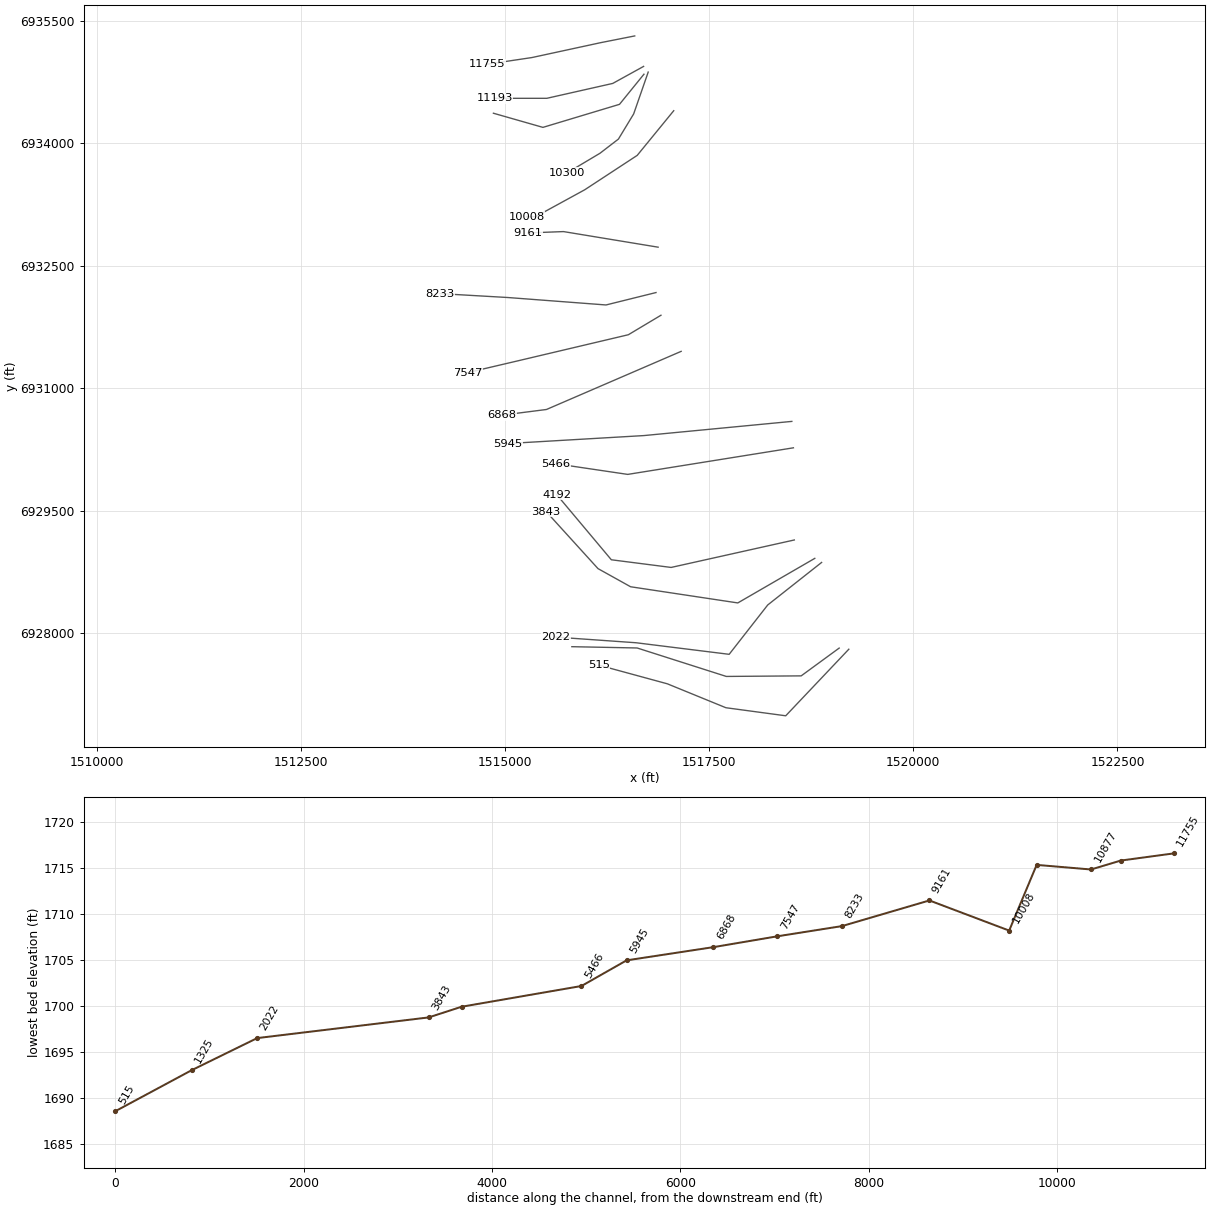
HEC-RAS study NC Unknown Stream 44.prj: NC Unknown Stream 44 Base Level Engineering

--- NC Unknown Stream 44.g01 (geometry) --- (continued)

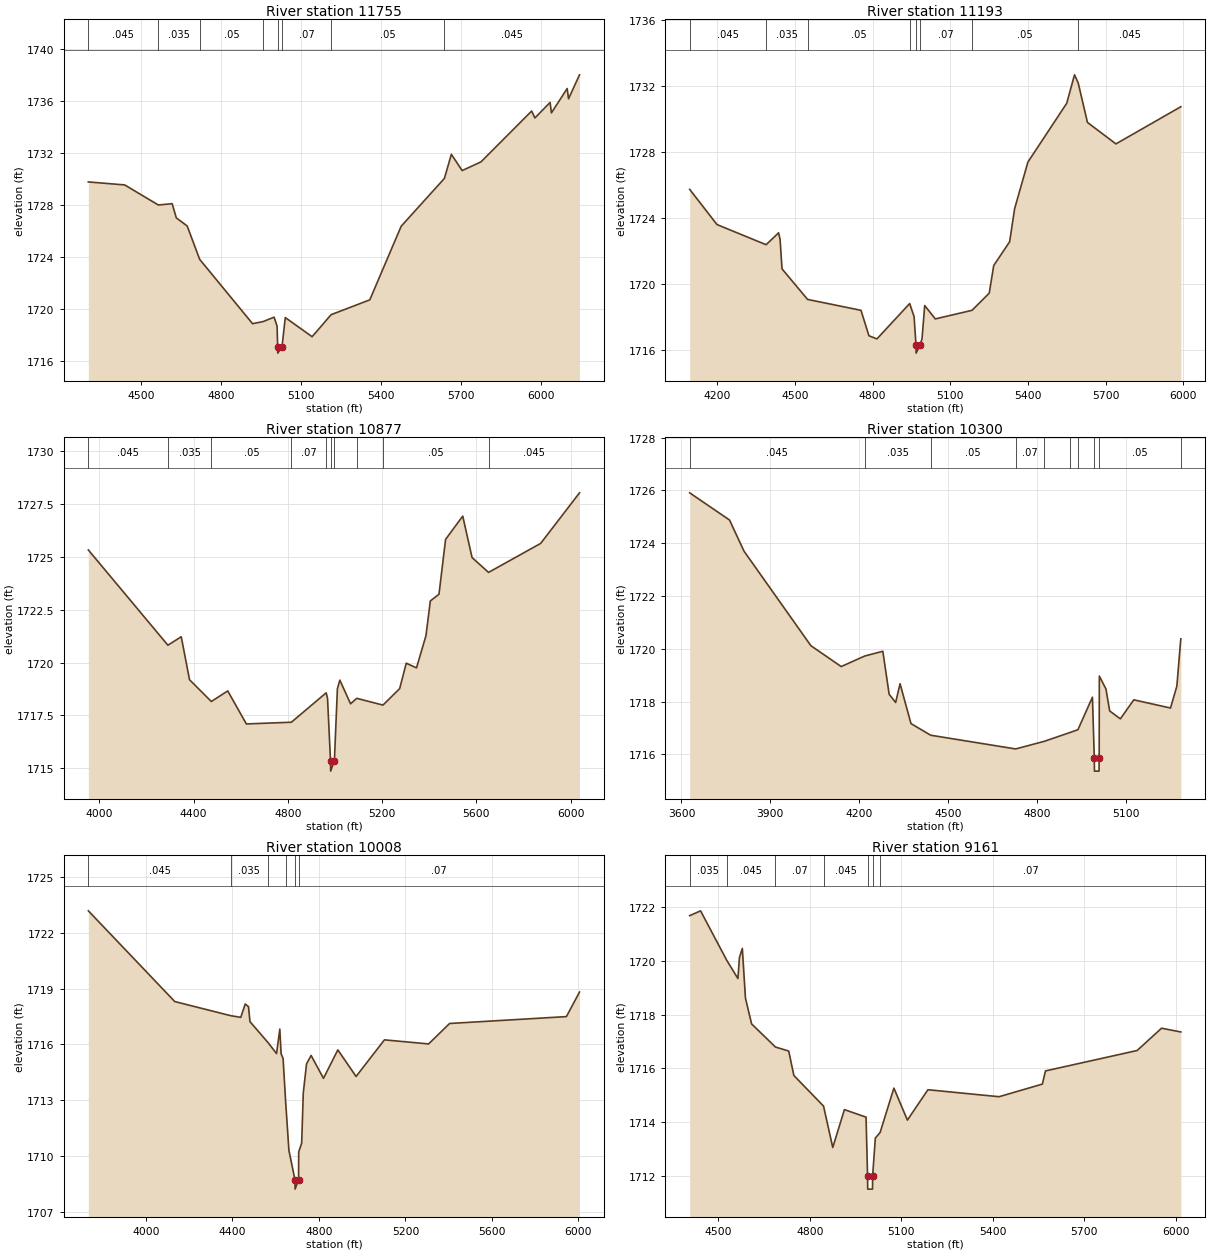
Type RM Length L Ch R = 1,11755,562,562,562
BEGIN DESCRIPTION:
Mapping XS de06d2bd
END DESCRIPTION:
XS GIS Cut Line= 4
      1516588.79      6935314.01      1516172.12      6935231.55
      1515330.11      6935049.26      1514779.41      6934966.87
#Sta/Elev= 30
  4301.3 1729.76  4437.7 1729.53  4563.9 1727.99  4615.8 1728.09  4631.4 1727.00
  4672.2 1726.38  4719.0 1723.82  4917.5 1718.88  4956.8 1719.04  4998.5 1719.38
  5009.6 1718.68  5011.6 1717.12  5012.1 1716.62  5028.1 1717.12  5040.3 1719.35
  5141.0 1717.88  5212.2 1719.57  5357.5 1720.71  5475.2 1726.36  5637.4 1730.03
  5663.5 1731.88  5704.0 1730.63  5774.7 1731.30  5964.8 1735.20  5977.0 1734.67
  6034.0 1735.86  6039.0 1735.06  6098.1 1736.93  6103.2 1736.14  6144.4 1737.98
#Mann=8,-1,0
  4301.3   0.045       0  4563.9   0.035       0  4719.0    0.05       0
  4956.8    0.07       0  5011.6    0.07       0  5028.1    0.07       0
  5212.2    0.05       0  5637.4   0.045       0
Bank Sta=5011.6,5028.1
Exp/Cntr=0.3,0.1

Type RM Length L Ch R = 1,11193,316,316,316
BEGIN DESCRIPTION:
Mapping XS 83f6f456
END DESCRIPTION:
XS GIS Cut Line= 4
      1516697.26      6934940.73      1516319.69      6934732.42
      1515512.40      6934550.13      1514874.34      6934550.13
#Sta/Elev= 30
  4093.7 1725.75  4199.1 1723.62  4388.8 1722.40  4437.1 1723.12  4442.8 1722.72
  4450.3 1720.94  4549.0 1719.09  4755.3 1718.43  4786.0 1716.89  4816.8 1716.70
  4943.3 1718.84  4960.3 1718.05  4967.7 1716.34  4968.2 1715.84  4984.2 1716.34
  4991.1 1716.72  5001.3 1718.72  5042.3 1717.91  5184.0 1718.43  5250.6 1719.47
  5267.9 1721.14  5329.4 1722.58  5348.6 1724.58  5399.9 1727.40  5549.9 1730.96
  5579.9 1732.68  5594.0 1732.20  5629.9 1729.80  5739.9 1728.50  5990.6 1730.75
#Mann=8,-1,0
  4093.7   0.045       0  4388.8   0.035       0  4549.0    0.05       0
  4943.3    0.07       0  4967.7    0.07       0  4984.2    0.07       0
  5184.0    0.05       0  5594.0   0.045       0
Bank Sta=4967.7,4984.2
Exp/Cntr=0.3,0.1

Type RM Length L Ch R = 1,10877,577,577,577
BEGIN DESCRIPTION:
Mapping XS 638f16c8
END DESCRIPTION:
XS GIS Cut Line= 4
      1516701.62      6934845.24      1516402.16      6934476.34
      1515464.66      6934194.22      1514858.49      6934367.41
#Sta/Elev= 30
  3953.2 1725.32  4290.9 1720.82  4347.5 1721.22  4382.6 1719.19  4475.1 1718.16
  4544.8 1718.66  4623.8 1717.10  4814.8 1717.18  4962.6 1718.57  4968.4 1718.30
  4981.0 1715.37  4981.5 1714.87  4997.5 1715.37  5010.2 1718.76  5020.6 1719.17
  5066.1 1718.05  5092.3 1718.31  5203.6 1717.99  5274.6 1718.77  5302.4 1719.97
  5345.9 1719.75  5386.1 1721.27  5404.6 1722.91  5441.4 1723.23  5469.4 1725.82
  5542.2 1726.92  5581.8 1724.96  5651.7 1724.26  5873.0 1725.63  6037.8 1728.02
#Mann=10,-1,0
  3953.2   0.045       0  4290.9   0.035       0  4475.1    0.05       0
  4814.8    0.07       0  4962.6    0.05       0  4981.0    0.05       0
  4997.5    0.05       0  5092.3    0.07       0  5203.6    0.05       0
  5651.7   0.045       0
Bank Sta=4981,4997.5
Exp/Cntr=0.3,0.1

Type RM Length L Ch R = 1,10300,292,292,292
BEGIN DESCRIPTION:
Mapping XS dd379cad
END DESCRIPTION:
XS GIS Cut Line= 5
      1516753.73      6934871.32      1516575.77      6934359.15
      1516389.14      6934050.99      1516163.44      6933877.38
      1515758.53      6933636.03
#Sta/Elev= 30
  3627.9 1725.91  3762.4 1724.88  3811.4 1723.70  4037.2 1720.12  4139.6 1719.33
  4219.1 1719.73  4280.1 1719.91  4301.5 1718.28  4323.4 1717.97  4338.3 1718.68
  4375.2 1717.17  4441.6 1716.73  4728.6 1716.21  4825.6 1716.50  4911.4 1716.83
  4939.0 1716.94  4987.9 1718.17  4994.2 1715.87  4994.7 1715.37  5010.2 1715.37
  5010.7 1715.87  5011.2 1718.97  5033.6 1718.48  5046.1 1717.65  5082.2 1717.35
  5127.6 1718.07  5251.6 1717.76  5273.0 1718.59  5285.4 1720.26  5286.5 1720.38
#Mann=10,-1,0
  3627.9   0.045       0  4219.1   0.035       0  4441.6    0.05       0
  4728.6    0.07       0  4825.6    0.05       0  4911.4    0.07       0
  4939.0    0.05       0  4994.2    0.05       0  5010.7    0.05       0
  5285.4    0.07       0
Bank Sta=4994.2,5010.7
Exp/Cntr=0.3,0.1

Type RM Length L Ch R = 1,10008,847,847,847
BEGIN DESCRIPTION:
Mapping XS a1975cb2
END DESCRIPTION:
XS GIS Cut Line= 5
      1517066.19      6934398.18      1516619.17      6933851.34
      1515976.81      6933430.33      1515375.90      6933101.61
      1515264.41      6933098.99
#Sta/Elev= 30
  3734.3 1723.19  4133.8 1718.31  4392.3 1717.55  4438.9 1717.46  4459.7 1718.18
  4474.8 1718.03  4481.5 1717.23  4565.2 1716.10  4604.4 1715.51  4619.5 1716.83
  4625.5 1715.50  4634.6 1715.25  4646.5 1712.92  4661.6 1710.30  4689.6 1708.72
  4690.1 1708.22  4706.1 1708.72  4706.9 1710.22  4720.6 1710.70  4728.0 1713.39
  4743.1 1714.96  4764.2 1715.41  4821.4 1714.18  4887.8 1715.71  4972.1 1714.28
  5103.2 1716.25  5307.4 1716.03  5404.5 1717.13  5944.5 1717.50  6005.1 1718.82
#Mann=6,-1,0
  3734.3   0.045       0  4392.3   0.035       0  4565.2   0.045       0
  4646.5    0.07       0  4689.6    0.07       0  4706.1    0.07       0
Bank Sta=4689.6,4706.1
Exp/Cntr=0.3,0.1

Type RM Length L Ch R = 1,9161,928,928,928
BEGIN DESCRIPTION:
Mapping XS 0a842e7d
END DESCRIPTION:
XS GIS Cut Line= 3
      1516875.22      6932727.21      1515716.39      6932918.18
      1515281.77      6932901.64
#Sta/Elev= 30
  4406.8 1721.68  4442.4 1721.86  4528.2 1720.02  4564.8 1719.34  4569.8 1720.12
  4579.3 1720.46  4589.5 1718.61  4609.7 1717.65  4687.8 1716.79  4731.3 1716.64
  4748.2 1715.73  4845.4 1714.59  4875.6 1713.05  4913.8 1714.46  4984.7 1714.18
  4989.6 1712.00  4990.1 1711.50  5005.8 1711.50  5006.3 1712.00  5015.1 1713.40
  5030.8 1713.61  5075.9 1715.26  5120.2 1714.07  5187.4 1715.20  5420.5 1714.94
  5562.4 1715.41  5572.5 1715.90  5872.9 1716.66  5952.9 1717.49  6016.2 1717.35
#Mann=7,-1,0
  4406.8   0.035       0  4528.2   0.045       0  4687.8    0.07       0
  4845.4   0.045       0  4989.6   0.045       0  5006.3   0.045       0
  5030.8    0.07       0
Bank Sta=4989.6,5006.3
Exp/Cntr=0.3,0.1

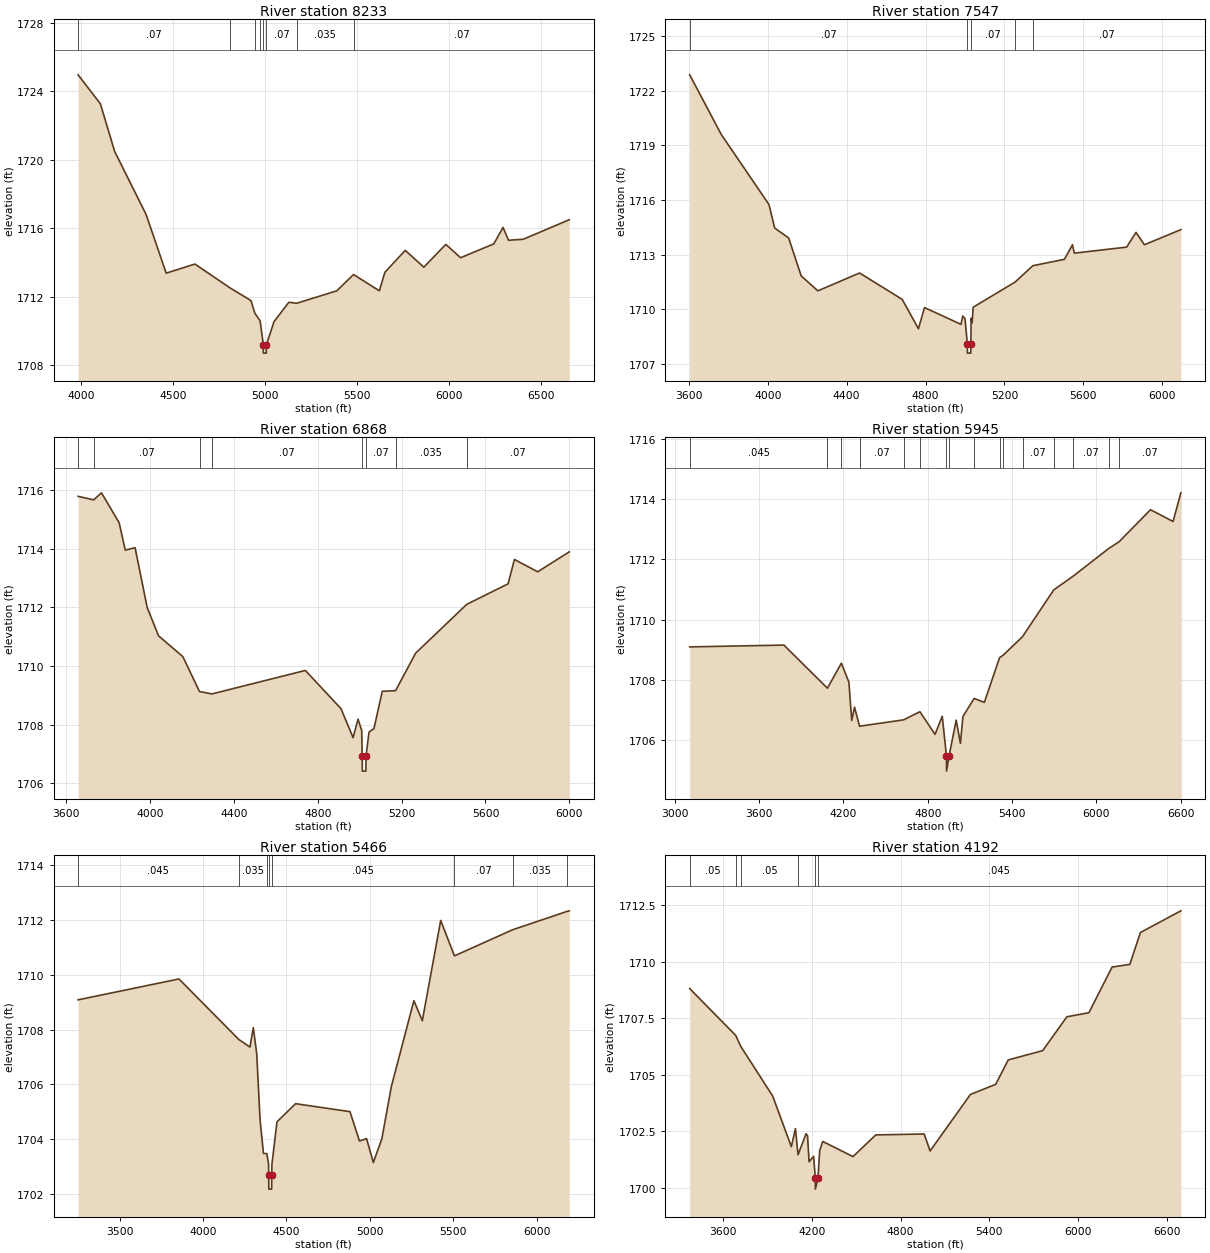
Type RM Length L Ch R = 1,8233,686,686,686
BEGIN DESCRIPTION:
Mapping XS 1b1daad6
END DESCRIPTION:
XS GIS Cut Line= 4
      1516849.20      6932171.65      1516237.23      6932019.74
      1515034.97      6932110.89      1514205.99      6932158.63
#Sta/Elev= 30
  3984.5 1724.96  4105.4 1723.27  4182.9 1720.49  4353.5 1716.81  4462.8 1713.38
  4618.7 1713.91  4810.7 1712.51  4922.9 1711.78  4944.2 1711.04  4972.6 1710.60
  4990.0 1709.21  4990.5 1708.71  5006.2 1708.71  5006.7 1709.21  5048.5 1710.55
  5128.7 1711.68  5171.0 1711.62  5389.5 1712.35  5479.8 1713.30  5620.1 1712.35
  5650.2 1713.43  5760.5 1714.71  5861.6 1713.73  5981.0 1715.06  6061.1 1714.28
  6241.4 1715.09  6291.5 1716.05  6321.5 1715.30  6401.7 1715.36  6651.1 1716.50
#Mann=8,-1,0
  3984.5    0.07       0  4810.7   0.035       0  4944.2    0.16       0
  4972.6    0.07       0  4990.0    0.07       0  5006.7    0.07       0
  5171.0   0.035       0  5479.8    0.07       0
Bank Sta=4990,5006.7
Exp/Cntr=0.3,0.1

Type RM Length L Ch R = 1,7547,679,679,679
BEGIN DESCRIPTION:
Mapping XS 55462d24
END DESCRIPTION:
XS GIS Cut Line= 4
      1516909.93      6931893.85      1516510.67      6931655.16
      1515169.52      6931338.32      1514540.22      6931190.76
#Sta/Elev= 30
  3604.5 1722.88  3764.8 1719.60  4006.4 1715.76  4035.2 1714.47  4106.3 1713.92
  4169.6 1711.84  4254.2 1711.02  4465.7 1712.00  4681.7 1710.55  4763.9 1708.94
  4794.8 1710.10  4979.7 1709.18  4988.6 1709.64  5000.3 1709.48  5011.8 1708.10
  5012.3 1707.60  5029.3 1707.60  5029.8 1708.10  5030.9 1709.52  5036.1 1709.26
  5041.4 1710.12  5253.8 1711.50  5344.0 1712.40  5503.7 1712.75  5544.8 1713.55
  5554.3 1713.09  5819.2 1713.42  5866.8 1714.23  5909.3 1713.55  6094.1 1714.38
#Mann=5,-1,0
  3604.5    0.07       0  5011.8    0.07       0  5029.8    0.07       0
  5253.8   0.035       0  5344.0    0.07       0
Bank Sta=5011.8,5029.8
Exp/Cntr=0.3,0.1

Type RM Length L Ch R = 1,6868,923,923,923
BEGIN DESCRIPTION:
NC Unknown Stream 44 6.0
END DESCRIPTION:
XS GIS Cut Line= 3
      1517157.38      6931451.71      1515508.06      6930739.90
      1514965.55      6930670.46
#Sta/Elev= 30
  3656.4 1715.78  3730.6 1715.66  3767.9 1715.90  3852.3 1714.88  3881.3 1713.95
  3928.3 1714.03  3986.2 1711.99  4040.2 1711.03  4156.2 1710.32  4235.7 1709.13
  4295.0 1709.05  4740.5 1709.85  4910.5 1708.55  4968.4 1707.56  4991.9 1708.19
  5009.5 1707.80  5011.9 1706.92  5012.4 1706.42  5029.4 1706.42  5029.9 1706.92
  5044.4 1707.75  5067.9 1707.87  5107.6 1709.14  5171.0 1709.16  5266.9 1710.44
  5510.3 1712.10  5707.9 1712.80  5738.1 1713.63  5849.0 1713.21  5999.7 1713.89
#Mann=8,-1,0
  3656.4   0.035       0  3730.6    0.07       0  4235.7   0.035       0
  4295.0    0.07       0  5011.9    0.07       0  5029.9    0.07       0
  5171.0   0.035       0  5510.3    0.07       0
Bank Sta=5011.9,5029.9
Exp/Cntr=0.3,0.1

Type RM Length L Ch R = 1,5945,479,479,479
BEGIN DESCRIPTION:
NC Unknown Stream 44 5.0
END DESCRIPTION:
XS GIS Cut Line= 3
      1518512.30      6930593.96      1516700.28      6930420.35
      1515029.65      6930322.72
#Sta/Elev= 30
  3106.8 1709.10  3777.2 1709.16  4086.5 1707.73  4185.7 1708.56  4239.3 1707.93
  4259.4 1706.66  4279.4 1707.10  4315.2 1706.47  4628.2 1706.68  4744.4 1706.95
  4852.1 1706.20  4903.3 1706.80  4933.3 1705.48  4933.8 1704.98  4951.5 1705.48
  5002.5 1706.67  5032.6 1705.90  5050.4 1706.79  5130.3 1707.39  5202.9 1707.26
  5310.8 1708.74  5338.0 1708.83  5474.4 1709.44  5696.3 1710.99  5835.5 1711.45
  6086.5 1712.36  6161.8 1712.59  6384.9 1713.65  6545.2 1713.26  6600.6 1714.21
#Mann=16,-1,0
  3106.8   0.045       0  4086.5    0.07       0  4185.7   0.035       0
  4315.2    0.07       0  4628.2   0.035       0  4744.4    0.07       0
  4933.3    0.07       0  4951.5    0.07       0  5130.3   0.035       0
  5310.8    0.07       0  5338.0   0.035       0  5474.4    0.07       0
  5696.3   0.035       0  5835.5    0.07       0  6086.5   0.035       0
  6161.8    0.07       0
Bank Sta=4933.3,4951.5
Exp/Cntr=0.3,0.1

Type RM Length L Ch R = 1,5466,1274,1274,1274
BEGIN DESCRIPTION:
NC Unknown Stream 44 4.0
END DESCRIPTION:
XS GIS Cut Line= 3
      1518531.87      6930270.61      1516502.80      6929945.09
      1515623.91      6930075.30
#Sta/Elev= 30
  3251.5 1709.08  3856.0 1709.84  4214.1 1707.64  4281.4 1707.36  4301.6 1708.07
  4321.9 1707.12  4342.1 1704.71  4362.4 1703.49  4382.9 1703.48  4392.8 1703.11
  4393.8 1702.69  4394.3 1702.19  4411.5 1702.19  4412.0 1702.69  4413.0 1703.09
  4443.4 1704.64  4554.8 1705.30  4880.9 1705.01  4937.8 1703.94  4980.2 1704.03
  5020.7 1703.16  5071.8 1704.02  5128.7 1705.92  5263.8 1709.05  5314.4 1708.32
  5424.6 1711.97  5506.9 1710.68  5855.0 1711.63  6182.5 1712.30  6195.0 1712.32
#Mann=8,-1,0
  3251.5   0.045       0  4214.1   0.035       0  4382.9   0.045       0
  4393.8   0.045       0  4412.0   0.045       0  5506.9    0.07       0
  5855.0   0.035       0  6182.5    0.07       0
Bank Sta=4393.8,4412
Exp/Cntr=0.3,0.1

Type RM Length L Ch R = 1,4192,349,349,349
BEGIN DESCRIPTION:
NC Unknown Stream 44 3.0
END DESCRIPTION:
XS GIS Cut Line= 4
      1518542.74      6929142.14      1517034.48      6928805.77
      1516302.33      6928899.63      1515635.81      6929694.25
#Sta/Elev= 30
  3374.6 1708.81  3686.2 1706.73  3720.9 1706.24  3935.8 1704.05  4061.8 1701.81
  4089.5 1702.61  4107.1 1701.45  4161.2 1702.38  4171.4 1702.29  4181.7 1701.14
  4212.4 1701.38  4223.8 1700.43  4224.3 1699.93  4242.0 1700.43  4253.4 1701.63
  4273.9 1702.04  4478.8 1701.37  4632.5 1702.33  4959.7 1702.37  5000.0 1701.62
  5272.3 1704.12  5443.6 1704.57  5528.3 1705.65  5761.0 1706.06  5924.9 1707.56
  6073.6 1707.74  6230.2 1709.76  6350.3 1709.88  6421.8 1711.29  6695.2 1712.25
#Mann=6,-1,0
  3374.6    0.05       0  3686.2   0.045       0  3720.9    0.05       0
  4107.1   0.045       0  4223.8   0.045       0  4242.0   0.045       0
Bank Sta=4223.8,4242
Exp/Cntr=0.3,0.1

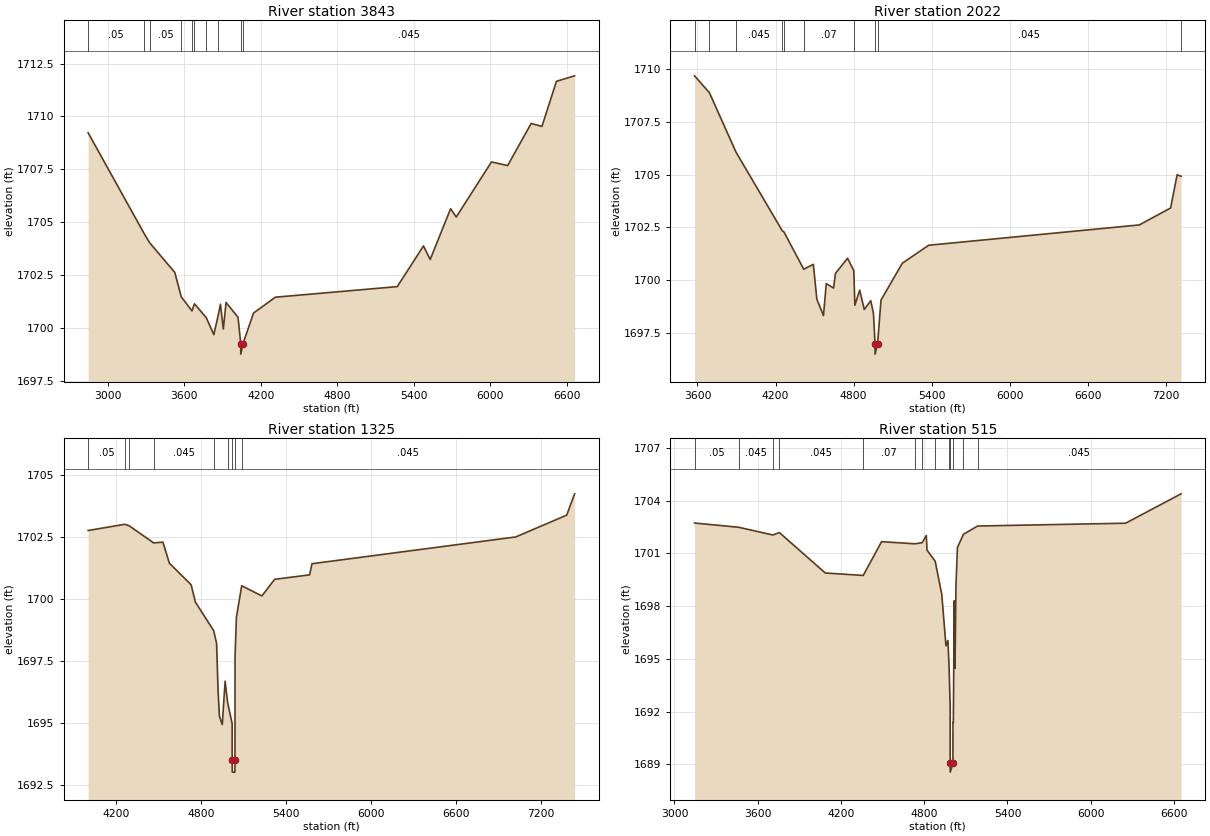
Type RM Length L Ch R = 1,3843,1821,1821,1821
BEGIN DESCRIPTION:
NC Unknown Stream 44 2.0
END DESCRIPTION:
XS GIS Cut Line= 5
      1518793.62      6928916.97      1517850.78      6928371.25
      1516538.28      6928569.17      1516138.98      6928791.39
      1515504.55      6929489.35
#Sta/Elev= 30
  2845.1 1709.23  3281.6 1704.50  3327.0 1704.04  3525.2 1702.63  3575.7 1701.48
  3659.8 1700.81  3679.6 1701.15  3772.4 1700.49  3831.3 1699.69  3867.4 1700.65
  3883.4 1701.13  3905.9 1699.96  3927.4 1701.21  4021.2 1700.51  4042.5 1699.27
  4043.0 1698.77  4060.7 1699.27  4142.5 1700.71  4314.5 1701.46  5270.5 1701.96
  5476.3 1703.88  5528.8 1703.24  5689.0 1705.64  5733.3 1705.25  6009.7 1707.85
  6136.7 1707.68  6321.2 1709.67  6405.7 1709.53  6519.2 1711.66  6662.0 1711.92
#Mann=10,-1,0
  2845.1    0.05       0  3281.6   0.045       0  3327.0    0.05       0
  3575.7   0.045       0  3659.8    0.07       0  3679.6    0.05       0
  3772.4    0.07       0  3867.4   0.045       0  4042.5   0.045       0
  4060.7   0.045       0
Bank Sta=4042.5,4060.7
Exp/Cntr=0.3,0.1

Type RM Length L Ch R = 1,2022,697,697,697
BEGIN DESCRIPTION:
Mapping XS b147210c
END DESCRIPTION:
XS GIS Cut Line= 5
      1518876.95      6928866.98      1518217.21      6928346.13
      1517744.99      6927741.97      1516604.82      6927883.64
      1515624.65      6927952.62
#Sta/Elev= 30
  3578.1 1709.66  3692.4 1708.86  3896.2 1706.06  4253.5 1702.33  4264.0 1702.30
  4416.9 1700.53  4490.7 1700.76  4517.9 1699.11  4568.6 1698.34  4590.2 1699.85
  4646.3 1699.64  4660.7 1700.33  4753.9 1701.05  4801.7 1700.46  4810.0 1698.83
  4847.0 1699.54  4882.3 1698.63  4932.0 1699.04  4952.8 1698.44  4964.8 1697.02
  4965.3 1696.52  4984.6 1697.02  5010.7 1699.07  5174.4 1700.81  5376.9 1701.66
  6995.9 1702.62  7236.5 1703.42  7286.6 1704.99  7316.9 1704.92  7317.0 1704.92
#Mann=10,-1,0
  3578.1   0.045       0  3692.4    0.05       0  3896.2   0.045       0
  4253.5    0.05       0  4264.0   0.045       0  4416.9    0.07       0
  4801.7   0.045       0  4964.8   0.045       0  4984.6   0.045       0
  7316.9    0.12       0
Bank Sta=4964.8,4984.6
Exp/Cntr=0.3,0.1

Type RM Length L Ch R = 1,1325,810,810,810
BEGIN DESCRIPTION:
Mapping XS a626a7d2
END DESCRIPTION:
XS GIS Cut Line= 5
      1519092.18      6927818.34      1518626.93      6927478.08
      1517710.26      6927471.13      1516617.72      6927819.67
      1515818.86      6927835.41
#Sta/Elev= 30
  4002.0 1702.77  4261.1 1703.02  4292.4 1702.96  4465.1 1702.27  4530.6 1702.30
  4576.5 1701.45  4730.3 1700.58  4760.3 1699.88  4889.6 1698.73  4910.3 1698.21
  4920.3 1696.36  4930.3 1695.27  4950.3 1694.94  4970.3 1696.69  4988.6 1695.81
  5020.3 1694.97  5020.4 1693.52  5020.9 1693.02  5039.7 1693.02  5040.2 1693.52
  5040.3 1697.64  5050.3 1699.27  5087.6 1700.54  5230.4 1700.13  5320.4 1700.80
  5567.9 1700.98  5584.6 1701.43  7024.7 1702.51  7384.8 1703.39  7440.9 1704.25
#Mann=9,-1,0
  4002.0    0.05       0  4261.1   0.045       0  4292.4    0.05       0
  4465.1   0.045       0  4889.6    0.16       0  4988.6    0.07       0
  5020.4    0.07       0  5040.2    0.07       0  5087.6   0.045       0
Bank Sta=5020.4,5040.2
Exp/Cntr=0.3,0.1

Type RM Length L Ch R = 1,515,0,0,0
BEGIN DESCRIPTION:
NC Unknown Stream 44 1.0
END DESCRIPTION:
XS GIS Cut Line= 5
      1519210.23      6927804.43      1518437.59      6926989.31
      1517705.00      6927088.00      1516988.04      6927380.85
      1516148.80      6927609.43
#Sta/Elev= 30
  3144.9 1702.72  3461.5 1702.48  3709.6 1702.04  3755.8 1702.18  4086.9 1699.88
  4360.4 1699.74  4492.6 1701.66  4731.8 1701.54  4784.9 1701.60  4815.2 1702.01
  4820.3 1701.18  4879.0 1700.55  4926.5 1698.67  4956.8 1695.74  4970.8 1696.04
  4979.3 1694.53  4987.0 1692.33  4987.2 1689.06  4987.7 1688.56  5007.1 1689.06
  5007.2 1691.38  5009.9 1691.38  5016.5 1698.30  5021.9 1694.46  5028.8 1699.16
  5039.6 1701.33  5082.9 1702.08  5185.1 1702.55  6251.5 1702.71  6651.5 1704.38
#Mann=13,-1,0
  3144.9    0.05       0  3461.5   0.045       0  3709.6    0.05       0
  3755.8   0.045       0  4360.4    0.07       0  4731.8   0.045       0
  4784.9    0.07       0  4879.0    0.16       0  4979.3   0.045       0
  4987.2   0.045       0  5007.1   0.045       0  5082.9    0.16       0
  5185.1   0.045       0
Bank Sta=4987.2,5007.1
Exp/Cntr=0.3,0.1

Chan Stop Cuts=-1