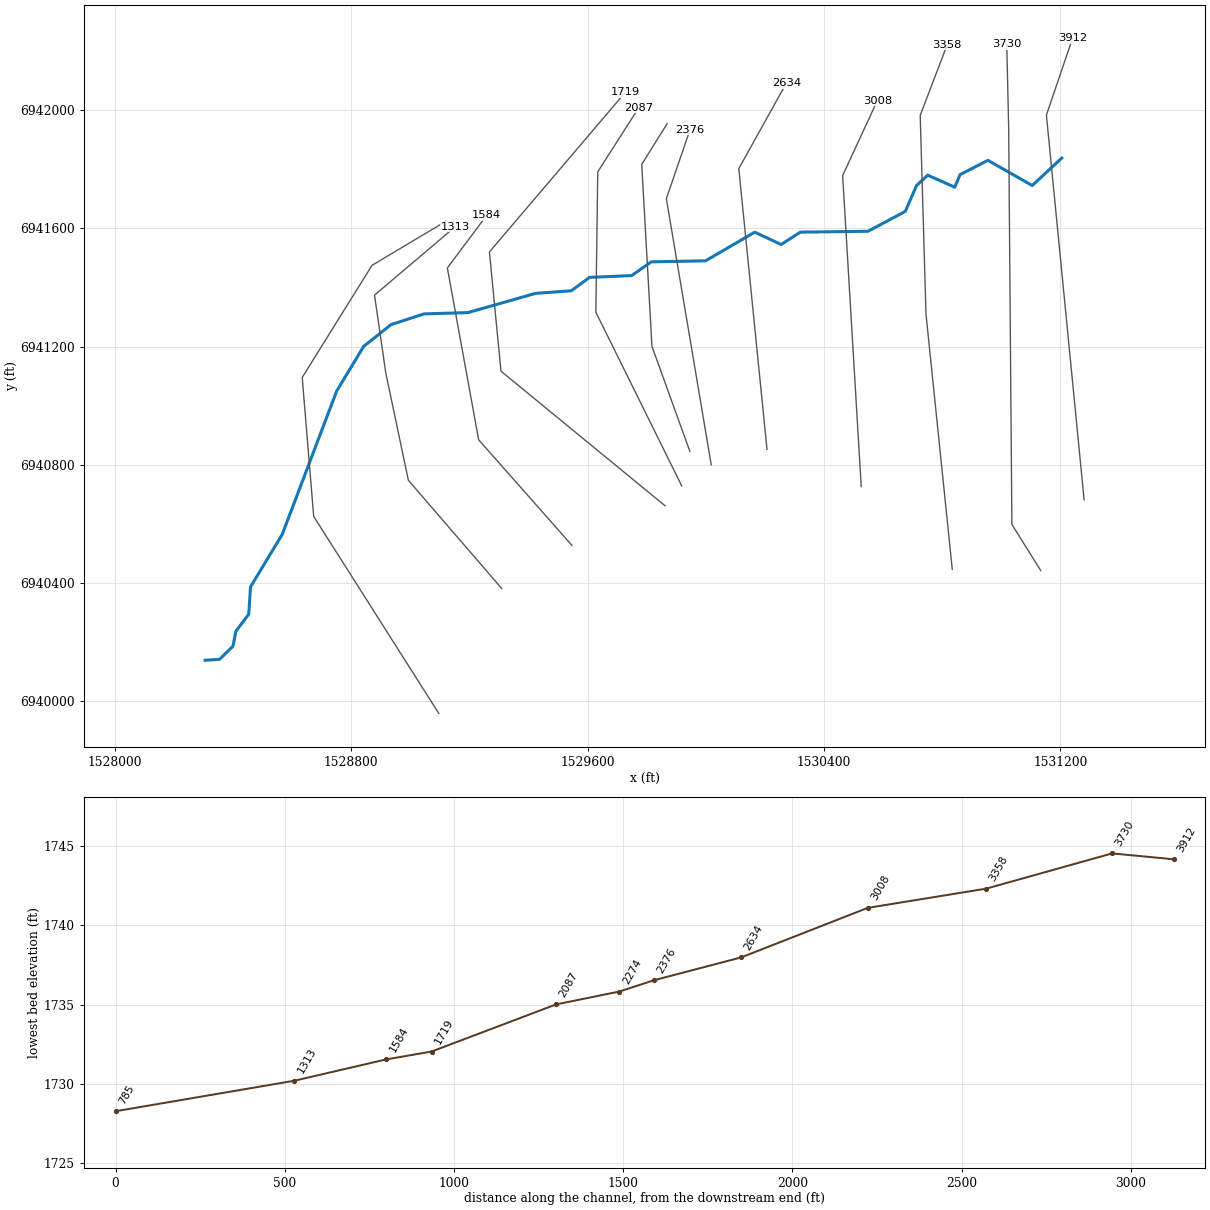
--- NC Unknown Stream 48.prj (project) ---

Proj Title=NC Unknown Stream 48 Base Level Engineering
Current Plan=p01
Default Exp/Contr=0.3,0.1
English Units
Geom File=g01
Flow File=f01
Plan File=p01
BEGIN DESCRIPTION:
NC Unknown Stream 48
END DESCRIPTION:

--- NC Unknown Stream 48.p01 (plan) ---

Plan Title=Multiple Run
Short Identifier=Multiple
Geom File=g01
Flow File=f01
Subcritical Flow
K Sum by GR= 0
Std Step Tol= 0.01
Critical Tol= 0.01
Num of Std Step Trials= 20
Max Error Tol= 0.3
Flow Tol Ratio= 0.001
Split Flow NTrial= 30
Split Flow Tol= 0.02
Split Flow Ratio= 0.02
Log Output Level= 0
Friction Slope Method= 1
Unsteady Friction Slope Method= 2
Unsteady Bridges Friction Slope Method= 1
Parabolic Critical Depth
Global Vel Dist=  1 , 1 , 1
Global Log Level= 0
CheckData=True
Encroach Param= -1, 0, 0, 0
BEGIN DESCRIPTION:
Multiple Run
END DESCRIPTION:

--- NC Unknown Stream 48.f01 (steady flow) ---

Flow Title=Multiple
Number of Profiles=7
Profile Names=10-year,25-year,50-year,1pct_min,100-year,1pct_plu,500-year
River Rch & RM= NC Unknown Strea,Reach-1,3912
     208     285     347     211     421     841     628
River Rch & RM= NC Unknown Strea,Reach-1,1719
     220     302     369     225     448     895     670
Boundary for River Rch & Prof#=NC Unknown Strea,Reach-1,1
Up Type=0
Dn Type=3
Dn Slope=0.001
Boundary for River Rch & Prof#=NC Unknown Strea,Reach-1,2
Up Type=0
Dn Type=3
Dn Slope=0.001
Boundary for River Rch & Prof#=NC Unknown Strea,Reach-1,3
Up Type=0
Dn Type=3
Dn Slope=0.001
Boundary for River Rch & Prof#=NC Unknown Strea,Reach-1,4
Up Type=0
Dn Type=3
Dn Slope=0.001
Boundary for River Rch & Prof#=NC Unknown Strea,Reach-1,5
Up Type=0
Dn Type=3
Dn Slope=0.001
Boundary for River Rch & Prof#=NC Unknown Strea,Reach-1,6
Up Type=0
Dn Type=3
Dn Slope=0.001
Boundary for River Rch & Prof#=NC Unknown Strea,Reach-1,7
Up Type=0
Dn Type=3
Dn Slope=0.001

--- NC Unknown Stream 48.g01 (geometry) ---

Geom Title=Existing Conditions

River Reach=NC Unknown Strea,Reach-1
Reach XY= 30
      1531205.00      6941838.00      1531105.09      6941745.19
      1530954.97      6941830.51      1530860.77      6941781.93
      1530842.84      6941739.52      1530751.37      6941780.27
      1530713.16      6941744.67      1530675.47      6941657.63
      1530549.07      6941590.24      1530320.16      6941587.34
      1530254.99      6941545.59      1530165.70      6941587.20
      1529999.07      6941490.24      1529815.51      6941486.78
      1529749.06      6941440.27      1529606.57      6941434.23
      1529544.73      6941388.77      1529423.82      6941380.05
      1529194.22      6941314.87      1529046.09      6941310.58
      1528934.39      6941274.20      1528841.94      6941200.77
      1528750.51      6941049.52      1528566.35      6940564.67
      1528458.83      6940386.42      1528452.67      6940293.96
      1528409.20      6940236.24      1528399.32      6940185.48
      1528353.97      6940141.14      1528305.00      6940138.00

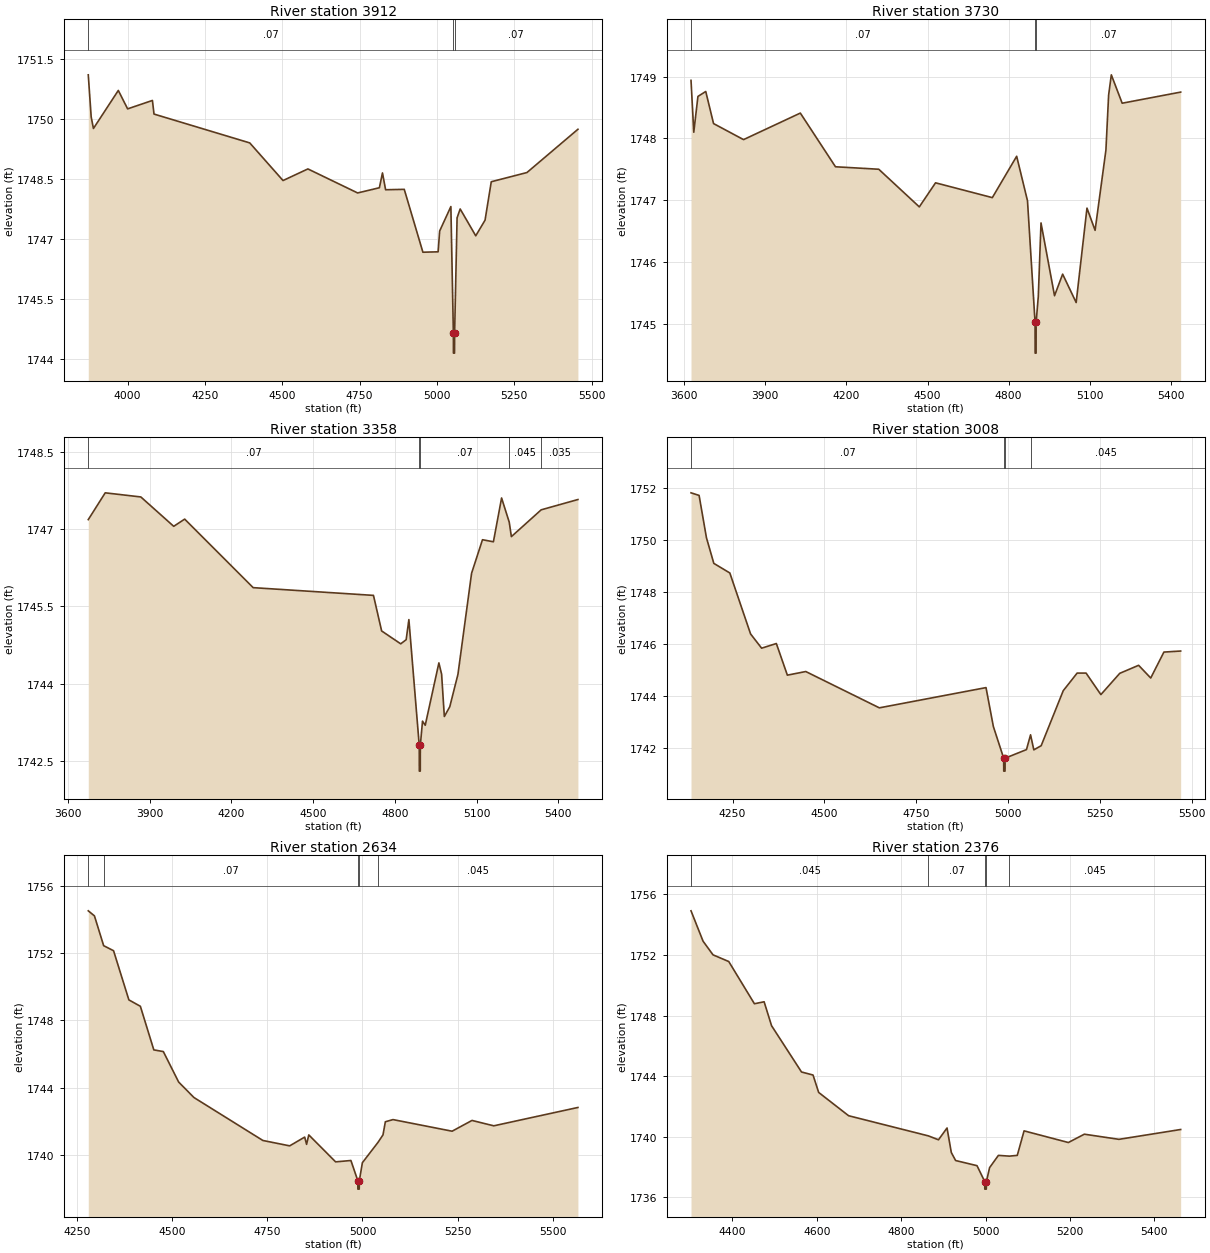
Type RM Length L Ch R = 1,3912,182,182,182
BEGIN DESCRIPTION:
NC Unknown Stream 48 3.0
END DESCRIPTION:
XS GIS Cut Line= 3
      1531280.70      6940681.39      1531153.10      6941983.44
      1531241.50      6942243.43
#Sta/Elev= 30
  3872.6 1751.10  3882.0 1750.05  3889.3 1749.76  3969.7 1750.71  3999.8 1750.25
  4080.0 1750.46  4085.1 1750.12  4394.6 1749.40  4502.2 1748.46  4582.6 1748.75
  4743.4 1748.15  4813.7 1748.28  4823.7 1748.65  4833.8 1748.23  4894.1 1748.24
  4954.4 1746.67  5003.6 1746.68  5008.6 1747.20  5044.8 1747.81  5052.9 1744.65
  5053.1 1744.15  5056.6 1744.15  5056.9 1744.65  5064.9 1747.53  5074.9 1747.75
  5125.2 1747.08  5155.3 1747.47  5175.4 1748.43  5290.8 1748.66  5455.5 1749.74
#Mann=3,-1,0
  3872.6    0.07       0  5052.9    0.07       0  5056.9    0.07       0
Bank Sta=5052.9,5056.9
Exp/Cntr=0.3,0.1

Type RM Length L Ch R = 1,3730,372,372,372
BEGIN DESCRIPTION:
Mapping XS ab20b38c
END DESCRIPTION:
XS GIS Cut Line= 4
      1531133.84      6940441.80      1531036.20      6940598.03
      1531025.35      6941939.17      1531018.87      6942224.28
#Sta/Elev= 30
  3625.4 1748.94  3635.6 1748.10  3651.0 1748.68  3679.9 1748.76  3708.7 1748.24
  3819.6 1747.98  4029.6 1748.41  4159.6 1747.54  4319.6 1747.50  4469.6 1746.89
  4529.6 1747.28  4739.6 1747.04  4829.6 1747.71  4869.6 1746.99  4897.6 1745.02
  4897.9 1744.52  4901.4 1744.52  4901.6 1745.02  4909.6 1745.44  4919.6 1746.63
  4969.6 1745.45  4999.6 1745.80  5049.6 1745.34  5089.6 1746.87  5119.6 1746.51
  5159.6 1747.81  5169.6 1748.70  5179.6 1749.03  5219.7 1748.57  5436.0 1748.75
#Mann=3,-1,0
  3625.4    0.07       0  4897.6    0.07       0  4901.6    0.07       0
Bank Sta=4897.6,4901.6
Exp/Cntr=0.3,0.1

Type RM Length L Ch R = 1,3358,350,350,350
BEGIN DESCRIPTION:
Mapping XS 7fd5746a
END DESCRIPTION:
XS GIS Cut Line= 4
      1530834.38      6940446.08      1530745.41      6941309.83
      1530725.87      6941982.58      1530817.03      6942221.32
#Sta/Elev= 30
  3674.8 1747.18  3737.0 1747.70  3867.7 1747.62  3988.4 1747.05  4028.6 1747.19
  4279.9 1745.86  4721.4 1745.71  4751.4 1745.02  4821.4 1744.77  4841.4 1744.85
  4851.4 1745.24  4889.4 1742.80  4889.7 1742.30  4893.2 1742.30  4893.4 1742.80
  4901.4 1743.27  4911.4 1743.19  4961.5 1744.40  4971.5 1744.18  4981.5 1743.36
  5001.5 1743.55  5031.5 1744.18  5081.5 1746.14  5121.5 1746.79  5161.6 1746.75
  5191.6 1747.60  5219.7 1747.13  5227.5 1746.85  5336.9 1747.37  5471.7 1747.57
#Mann=5,-1,0
  3674.8    0.07       0  4889.4    0.07       0  4893.4    0.07       0
  5219.7   0.045       0  5336.9   0.035       0
Bank Sta=4889.4,4893.4
Exp/Cntr=0.3,0.1

Type RM Length L Ch R = 1,3008,374,374,374
BEGIN DESCRIPTION:
Mapping XS 7d4fba6d
END DESCRIPTION:
XS GIS Cut Line= 3
      1530526.22      6940726.06      1530463.29      6941778.58
      1530580.24      6942031.99
#Sta/Elev= 30
  4136.7 1751.82  4158.7 1751.72  4178.7 1750.09  4198.8 1749.10  4242.4 1748.73
  4298.9 1746.38  4329.0 1745.83  4369.1 1746.01  4399.1 1744.79  4449.2 1744.93
  4649.6 1743.53  4940.1 1744.31  4960.1 1742.81  4988.2 1741.59  4988.4 1741.09
  4991.9 1741.09  4992.2 1741.59  5050.3 1741.92  5061.4 1742.49  5070.3 1741.91
  5090.3 1742.07  5150.4 1744.19  5188.3 1744.87  5212.6 1744.87  5252.9 1744.04
  5304.3 1744.86  5355.7 1745.17  5388.7 1744.68  5424.6 1745.68  5470.2 1745.72
#Mann=4,-1,0
  4136.7    0.07       0  4988.2    0.07       0  4992.2    0.07       0
  5061.4   0.045       0
Bank Sta=4988.2,4992.2
Exp/Cntr=0.3,0.1

Type RM Length L Ch R = 1,2634,258,258,258
BEGIN DESCRIPTION:
Mapping XS 579bb1ac
END DESCRIPTION:
XS GIS Cut Line= 3
      1530207.22      6940851.89      1530111.72      6941802.45
      1530272.29      6942091.05
#Sta/Elev= 30
  4280.0 1754.50  4296.2 1754.20  4320.4 1752.43  4346.4 1752.13  4386.6 1749.21
  4416.8 1748.83  4452.1 1746.24  4477.1 1746.14  4517.3 1744.33  4557.5 1743.41
  4738.4 1740.86  4808.8 1740.54  4848.2 1741.06  4853.2 1740.63  4859.0 1741.19
  4929.4 1739.59  4969.6 1739.67  4987.7 1738.47  4987.9 1737.97  4991.4 1737.97
  4991.7 1738.47  4999.7 1739.54  5040.8 1740.75  5053.8 1741.19  5060.0 1741.97
  5080.1 1742.10  5235.3 1741.41  5287.5 1742.05  5344.7 1741.73  5565.6 1742.82
#Mann=5,-1,0
  4280.0   0.045       0  4320.4    0.07       0  4987.7    0.07       0
  4991.7    0.07       0  5040.8   0.045       0
Bank Sta=4987.7,4991.7
Exp/Cntr=0.3,0.1

Type RM Length L Ch R = 1,2376,102,102,102
BEGIN DESCRIPTION:
Mapping XS a3a91772
END DESCRIPTION:
XS GIS Cut Line= 3
      1530018.41      6940799.84      1529866.50      6941700.46
      1529946.48      6941933.90
#Sta/Elev= 30
  4302.1 1754.92  4330.7 1752.91  4354.3 1752.01  4391.5 1751.57  4452.3 1748.78
  4475.3 1748.91  4492.9 1747.33  4563.9 1744.27  4591.2 1744.07  4604.5 1742.92
  4675.5 1741.38  4864.3 1740.05  4888.4 1739.79  4908.7 1740.57  4918.8 1738.95
  4929.0 1738.42  4979.7 1738.08  4998.0 1737.03  4998.2 1736.53  5001.7 1736.53
  5002.0 1737.03  5009.5 1737.95  5030.4 1738.76  5056.4 1738.71  5075.1 1738.76
  5091.2 1740.38  5196.1 1739.61  5234.0 1740.16  5316.0 1739.82  5462.2 1740.47
#Mann=5,-1,0
  4302.1   0.045       0  4864.3    0.07       0  4998.0    0.07       0
  5002.0    0.07       0  5056.4   0.045       0
Bank Sta=4998,5002
Exp/Cntr=0.3,0.1

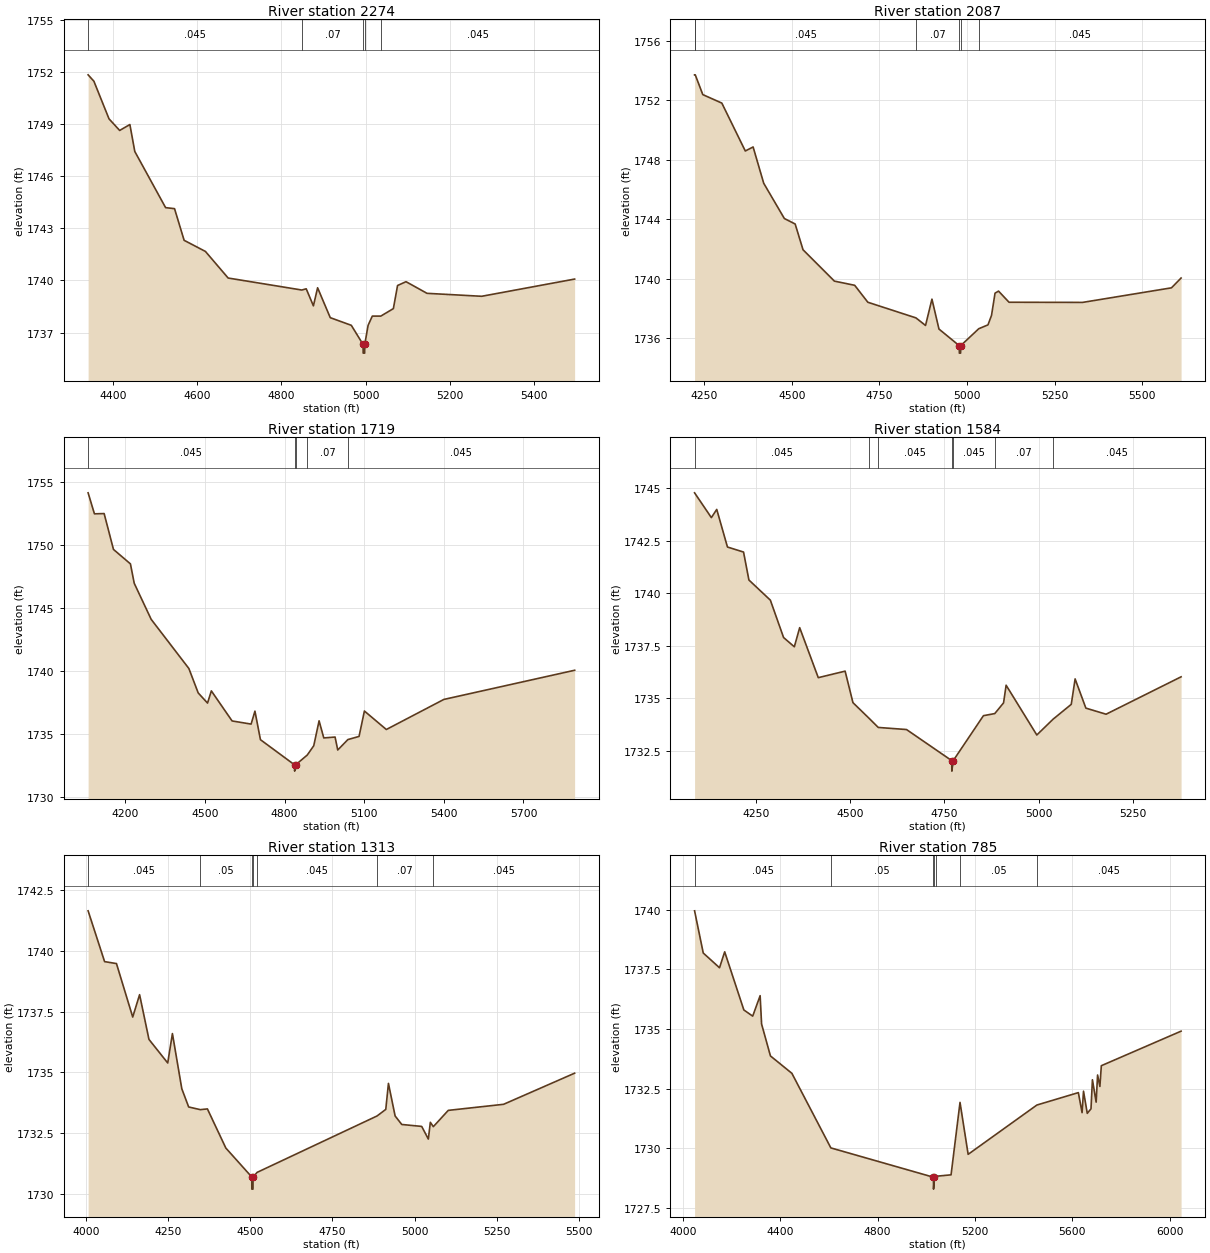
Type RM Length L Ch R = 1,2274,187,187,187
BEGIN DESCRIPTION:
Mapping XS eb6ac2d8
END DESCRIPTION:
XS GIS Cut Line= 4
      1529946.28      6940844.52      1529817.80      6941200.45
      1529783.08      6941816.77      1529869.04      6941954.31
#Sta/Elev= 30
  4339.8 1751.83  4353.6 1751.46  4389.5 1749.30  4414.9 1748.63  4439.2 1748.97
  4450.9 1747.42  4524.2 1744.19  4545.5 1744.13  4568.3 1742.31  4619.0 1741.67
  4673.1 1740.14  4848.4 1739.45  4858.9 1739.52  4876.0 1738.54  4886.0 1739.58
  4916.1 1737.86  4966.2 1737.42  4994.2 1736.32  4994.5 1735.82  4998.0 1735.82
  4998.2 1736.32  5006.2 1737.42  5016.2 1737.95  5036.4 1737.95  5066.3 1738.38
  5076.3 1739.71  5096.4 1739.93  5146.4 1739.26  5276.6 1739.09  5497.7 1740.08
#Mann=5,-1,0
  4339.8   0.045       0  4848.4    0.07       0  4994.2    0.07       0
  4998.2    0.07       0  5036.4   0.045       0
Bank Sta=4994.2,4998.2
Exp/Cntr=0.3,0.1

Type RM Length L Ch R = 1,2087,368,368,368
BEGIN DESCRIPTION:
Mapping XS 93e93f2c
END DESCRIPTION:
XS GIS Cut Line= 4
      1529918.58      6940728.24      1529627.78      6941316.34
      1529634.29      6941791.60      1529773.17      6942008.59
#Sta/Elev= 30
  4222.1 1753.72  4224.0 1753.72  4245.6 1752.39  4299.9 1751.82  4366.9 1748.60
  4389.2 1748.87  4419.5 1746.43  4478.4 1744.06  4509.3 1743.69  4531.7 1741.96
  4621.4 1739.85  4679.2 1739.57  4716.8 1738.43  4854.1 1737.38  4881.5 1736.87
  4899.8 1738.64  4919.8 1736.63  4977.8 1735.51  4978.1 1735.01  4981.6 1735.01
  4981.8 1735.51  5033.4 1736.65  5059.8 1736.91  5069.9 1737.55  5079.9 1739.04
  5089.9 1739.18  5119.9 1738.43  5329.9 1738.42  5583.7 1739.40  5611.1 1740.06
#Mann=6,-1,0
  4222.1    0.07       0  4224.0   0.045       0  4854.1    0.07       0
  4977.8    0.07       0  4981.8    0.07       0  5033.4   0.045       0
Bank Sta=4977.8,4981.8
Exp/Cntr=0.3,0.1

Type RM Length L Ch R = 1,1719,135,135,135
BEGIN DESCRIPTION:
Mapping XS 01bdca14
END DESCRIPTION:
XS GIS Cut Line= 4
      1529862.17      6940660.95      1529306.60      6941116.69
      1529267.54      6941520.34      1529727.61      6942060.71
#Sta/Elev= 30
  4059.1 1754.17  4082.9 1752.50  4119.5 1752.52  4154.7 1749.67  4218.6 1748.52
  4232.9 1746.98  4296.8 1744.11  4438.9 1740.20  4474.0 1738.26  4509.2 1737.45
  4523.6 1738.42  4601.8 1736.03  4673.5 1735.78  4687.9 1736.81  4708.7 1734.54
  4837.3 1732.54  4837.5 1732.04  4841.3 1732.54  4885.2 1733.32  4909.6 1734.06
  4929.7 1736.04  4947.4 1734.68  4990.0 1734.75  5000.0 1733.72  5038.3 1734.55
  5080.4 1734.80  5100.5 1736.82  5183.2 1735.35  5399.9 1737.74  5892.9 1740.06
#Mann=5,-1,0
  4059.1   0.045       0  4837.3    0.07       0  4841.3   0.045       0
  4885.2    0.07       0  5038.3   0.045       0
Bank Sta=4837.3,4841.3
Exp/Cntr=0.3,0.1

Type RM Length L Ch R = 1,1584,271,271,271
BEGIN DESCRIPTION:
Mapping XS d514d6b9
END DESCRIPTION:
XS GIS Cut Line= 4
      1529547.00      6940526.80      1529230.99      6940884.47
      1529125.09      6941466.07      1529258.05      6941643.93
#Sta/Elev= 30
  4087.4 1744.79  4131.9 1743.61  4146.2 1744.00  4174.6 1742.21  4217.3 1741.97
  4231.5 1740.64  4288.4 1739.68  4323.5 1737.90  4352.0 1737.46  4366.2 1738.37
  4415.5 1735.99  4486.7 1736.30  4507.5 1734.80  4551.1 1734.04  4574.6 1733.62
  4649.6 1733.52  4769.5 1732.04  4769.8 1731.54  4773.5 1732.04  4853.6 1734.18
  4883.7 1734.28  4907.0 1734.79  4913.8 1735.63  4995.2 1733.26  5038.2 1734.01
  5086.6 1734.72  5096.8 1735.93  5125.3 1734.54  5178.9 1734.25  5377.9 1736.03
#Mann=7,-1,0
  4087.4   0.045       0  4551.1    0.05       0  4574.6   0.045       0
  4769.5    0.07       0  4773.5   0.045       0  4883.7    0.07       0
  5038.2   0.045       0
Bank Sta=4769.5,4773.5
Exp/Cntr=0.3,0.1

Type RM Length L Ch R = 1,1313,528,528,528
BEGIN DESCRIPTION:
Mapping XS cf6cec07
END DESCRIPTION:
XS GIS Cut Line= 5
      1529309.15      6940380.96      1528993.15      6940747.32
      1528916.76      6941110.17      1528878.56      6941374.06
      1529151.40      6941605.45
#Sta/Elev= 30
  4007.3 1741.65  4057.4 1739.56  4093.5 1739.48  4142.9 1737.28  4163.8 1738.20
  4192.3 1736.36  4249.3 1735.39  4263.6 1736.60  4292.1 1734.33  4313.0 1733.58
  4348.4 1733.47  4370.0 1733.50  4426.0 1731.89  4504.8 1730.70  4505.0 1730.20
  4508.5 1730.20  4508.8 1730.70  4521.2 1730.89  4885.7 1733.21  4912.2 1733.48
  4920.3 1734.55  4940.6 1733.21  4960.8 1732.86  5021.4 1732.78  5041.6 1732.26
  5047.7 1732.95  5056.8 1732.77  5102.2 1733.44  5270.4 1733.69  5486.3 1734.97
#Mann=7,-1,0
  4007.3   0.045       0  4348.4    0.05       0  4504.8    0.07       0
  4508.8    0.05       0  4521.2   0.045       0  4885.7    0.07       0
  5056.8   0.045       0
Bank Sta=4504.8,4508.8
Exp/Cntr=0.3,0.1

Type RM Length L Ch R = 1,785,0,0,0
BEGIN DESCRIPTION:
NC Unknown Stream 48 1.0
END DESCRIPTION:
XS GIS Cut Line= 5
      1529096.04      6939958.22      1528672.63      6940624.94
      1528633.77      6941095.41      1528869.88      6941474.75
      1529119.03      6941623.55
#Sta/Elev= 30
  4048.4 1739.96  4084.0 1738.19  4150.9 1737.57  4172.1 1738.24  4250.8 1735.80
  4287.2 1735.54  4317.7 1736.40  4323.7 1735.21  4360.1 1733.87  4448.2 1733.14
  4608.3 1730.01  5029.9 1728.78  5030.2 1728.28  5034.0 1728.78  5041.0 1728.82
  5102.2 1728.88  5139.0 1731.92  5172.4 1729.74  5454.9 1731.81  5625.2 1732.33
  5640.5 1731.49  5646.4 1732.39  5661.8 1731.46  5677.1 1731.65  5683.0 1732.87
  5698.3 1731.93  5704.2 1733.07  5713.7 1732.59  5719.6 1733.46  6047.3 1734.91
#Mann=7,-1,0
  4048.4   0.045       0  4608.3    0.05       0  5029.9    0.05       0
  5034.0    0.05       0  5041.0    0.07       0  5139.0    0.05       0
  5454.9   0.045       0
Bank Sta=5029.9,5034
Exp/Cntr=0.3,0.1

Chan Stop Cuts=-1