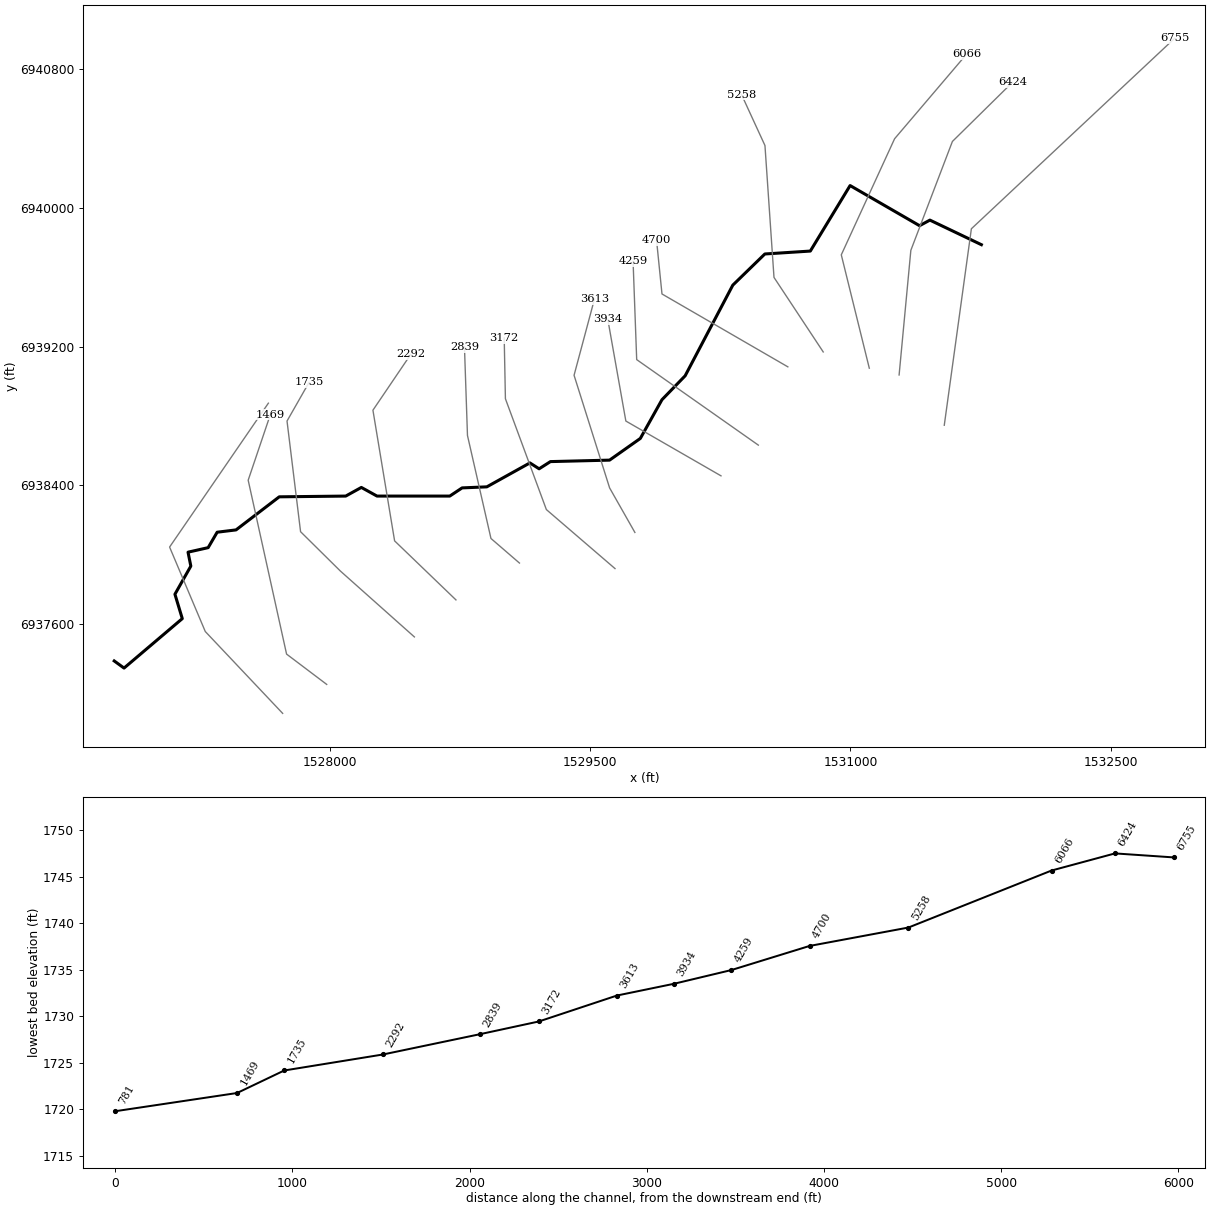
--- NC Unknown Stream 49.prj (project) ---

Proj Title=NC Unknown Stream 49 Base Level Engineering
Current Plan=p01
Default Exp/Contr=0.3,0.1
English Units
Geom File=g01
Flow File=f01
Plan File=p01
BEGIN DESCRIPTION:
NC Unknown Stream 49
END DESCRIPTION:

--- NC Unknown Stream 49.p01 (plan) ---

Plan Title=Multiple Run
Short Identifier=Multiple
Geom File=g01
Flow File=f01
Subcritical Flow
K Sum by GR= 0
Std Step Tol= 0.01
Critical Tol= 0.01
Num of Std Step Trials= 20
Max Error Tol= 0.3
Flow Tol Ratio= 0.001
Split Flow NTrial= 30
Split Flow Tol= 0.02
Split Flow Ratio= 0.02
Log Output Level= 0
Friction Slope Method= 1
Unsteady Friction Slope Method= 2
Unsteady Bridges Friction Slope Method= 1
Parabolic Critical Depth
Global Vel Dist=  1 , 1 , 1
Global Log Level= 0
CheckData=True
Encroach Param= -1, 0, 0, 0
BEGIN DESCRIPTION:
Multiple Run
END DESCRIPTION:

--- NC Unknown Stream 49.f01 (steady flow) ---

Flow Title=Multiple
Number of Profiles=7
Profile Names=10-year,25-year,50-year,1pct_min,100-year,1pct_plu,500-year
River Rch & RM= NC Unknown Strea,Reach-1,6755
     252     348     426     260     519    1036     779
Boundary for River Rch & Prof#=NC Unknown Strea,Reach-1,1
Up Type=0
Dn Type=3
Dn Slope=0.001
Boundary for River Rch & Prof#=NC Unknown Strea,Reach-1,2
Up Type=0
Dn Type=3
Dn Slope=0.001
Boundary for River Rch & Prof#=NC Unknown Strea,Reach-1,3
Up Type=0
Dn Type=3
Dn Slope=0.001
Boundary for River Rch & Prof#=NC Unknown Strea,Reach-1,4
Up Type=0
Dn Type=3
Dn Slope=0.001
Boundary for River Rch & Prof#=NC Unknown Strea,Reach-1,5
Up Type=0
Dn Type=3
Dn Slope=0.001
Boundary for River Rch & Prof#=NC Unknown Strea,Reach-1,6
Up Type=0
Dn Type=3
Dn Slope=0.001
Boundary for River Rch & Prof#=NC Unknown Strea,Reach-1,7
Up Type=0
Dn Type=3
Dn Slope=0.001

--- NC Unknown Stream 49.g01 (geometry) ---

Geom Title=Existing Conditions

River Reach=NC Unknown Strea,Reach-1
Reach XY= 30
      1531755.00      6939788.00      1531458.22      6939929.72
      1531398.45      6939897.58      1530997.99      6940129.01
      1530768.67      6939751.23      1530506.46      6939734.46
      1530321.64      6939554.68      1530046.86      6939031.94
      1529913.16      6938894.05      1529788.50      6938670.95
      1529611.19      6938545.83      1529270.16      6938537.35
      1529204.90      6938495.80      1529151.77      6938529.76
      1528903.44      6938391.76      1528760.94      6938385.73
      1528689.78      6938338.52      1528270.21      6938338.54
      1528180.00      6938388.40      1528089.79      6938338.54
      1527706.55      6938334.25      1527457.42      6938143.53
      1527348.57      6938130.21      1527296.64      6938041.19
      1527180.60      6938015.12      1527196.74      6937934.78
      1527105.08      6937772.61      1527147.52      6937631.94
      1526811.66      6937346.79      1526755.00      6937388.00

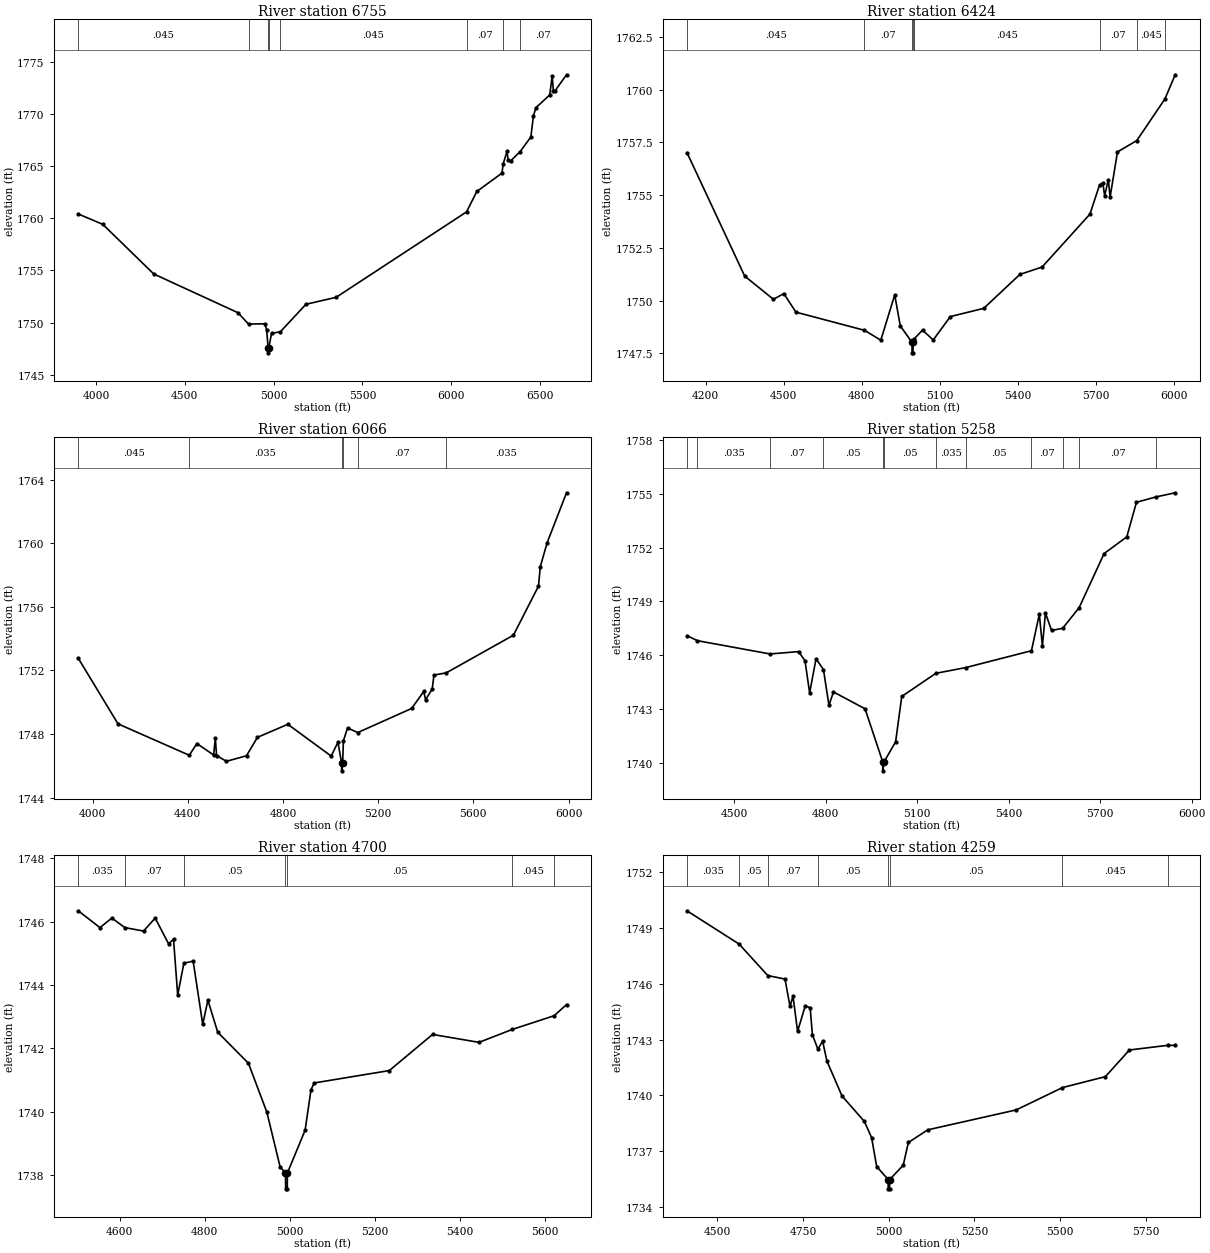
Type RM Length L Ch R = 1,6755,331,331,331
BEGIN DESCRIPTION:
NC Unknown Stream 49 5.0
END DESCRIPTION:
XS GIS Cut Line= 3
      1531540.98      6938746.93      1531697.23      6939879.71
      1532869.13      6940977.82
#Sta/Elev= 30
  3899.8 1760.42  4038.1 1759.42  4324.9 1754.66  4799.3 1750.94  4858.7 1749.85
  4950.7 1749.88  4960.8 1749.29  4968.8 1747.59  4969.1 1747.09  4973.1 1747.59
  4988.2 1748.96  5037.8 1749.11  5181.9 1751.75  5351.9 1752.42  6086.4 1760.62
  6144.2 1762.58  6285.9 1764.34  6292.7 1765.23  6314.2 1766.42  6321.0 1765.56
  6335.2 1765.52  6388.4 1766.41  6448.5 1767.81  6462.7 1769.80  6476.9 1770.62
  6554.5 1771.84  6568.7 1773.65  6575.5 1772.21  6582.9 1772.20  6649.3 1773.78
#Mann=8,-1,0
  3899.8   0.045       0  4858.7    0.07       0  4968.8    0.07       0
  4973.1    0.07       0  5037.8   0.045       0  6086.4    0.07       0
  6292.7   0.045       0  6388.4    0.07       0
Bank Sta=4968.8,4973.1
Exp/Cntr=0.3,0.1

Type RM Length L Ch R = 1,6424,358,358,358
BEGIN DESCRIPTION:
Mapping XS e1b47ba8
END DESCRIPTION:
XS GIS Cut Line= 4
      1531280.56      6939036.79      1531348.27      6939755.58
      1531587.85      6940383.18      1531933.50      6940723.63
#Sta/Elev= 30
  4127.5 1757.02  4349.7 1751.16  4460.2 1750.06  4500.3 1750.33  4546.8 1749.45
  4810.3 1748.59  4873.5 1748.12  4927.0 1750.27  4948.4 1748.80  4993.4 1748.02
  4993.7 1747.52  4997.4 1747.52  4997.7 1748.02  5000.9 1748.17  5034.0 1748.60
  5075.1 1748.13  5141.1 1749.24  5269.5 1749.63  5408.7 1751.24  5494.1 1751.59
  5678.2 1754.10  5715.2 1755.48  5727.8 1755.59  5734.8 1754.97  5748.9 1755.73
  5755.9 1754.91  5784.2 1757.05  5858.6 1757.59  5966.6 1759.56  6006.4 1760.71
#Mann=8,-1,0
  4127.5   0.045       0  4810.3    0.07       0  4993.4    0.07       0
  4997.7    0.07       0  5000.9   0.045       0  5715.2    0.07       0
  5858.6   0.045       0  5966.6    0.07       0
Bank Sta=4993.4,4997.7
Exp/Cntr=0.3,0.1

Type RM Length L Ch R = 1,6066,808,808,808
BEGIN DESCRIPTION:
Mapping XS 3ccb0a3d
END DESCRIPTION:
XS GIS Cut Line= 4
      1531108.68      6939075.94      1530947.23      6939729.54
      1531254.52      6940398.81      1531670.62      6940887.72
#Sta/Elev= 30
  3939.7 1752.77  4106.6 1748.64  4406.3 1746.66  4438.0 1747.40  4508.4 1746.68
  4515.7 1747.74  4520.9 1746.64  4562.3 1746.28  4646.7 1746.63  4692.6 1747.79
  4820.3 1748.61  5002.5 1746.61  5030.9 1747.48  5046.2 1746.18  5046.5 1745.68
  5050.6 1746.18  5053.9 1747.58  5071.4 1748.38  5114.2 1748.09  5340.8 1749.61
  5391.5 1750.68  5399.2 1750.16  5427.1 1750.83  5434.3 1751.71  5485.9 1751.85
  5768.2 1754.22  5873.6 1757.31  5881.3 1758.54  5909.9 1760.04  5991.4 1763.19
#Mann=6,-1,0
  3939.7   0.045       0  4406.3   0.035       0  5046.2   0.035       0
  5050.6   0.035       0  5114.2    0.07       0  5485.9   0.035       0
Bank Sta=5046.2,5050.6
Exp/Cntr=0.3,0.1

Type RM Length L Ch R = 1,5258,558,558,558
BEGIN DESCRIPTION:
Mapping XS f827df95
END DESCRIPTION:
XS GIS Cut Line= 4
      1530843.04      6939169.67      1530559.21      6939599.33
      1530507.12      6940359.75      1530371.95      6940653.50
#Sta/Elev= 30
  4345.6 1747.09  4380.0 1746.81  4617.7 1746.07  4711.6 1746.20  4732.6 1745.69
  4747.7 1743.90  4768.7 1745.80  4793.0 1745.20  4811.0 1743.21  4825.9 1743.95
  4929.4 1743.01  4987.3 1740.05  4987.6 1739.55  4991.7 1740.05  5029.6 1741.17
  5049.7 1743.70  5161.6 1744.99  5259.5 1745.31  5474.9 1746.25  5500.7 1748.29
  5510.7 1746.51  5520.8 1748.35  5540.8 1747.38  5577.1 1747.50  5631.1 1748.65
  5713.0 1751.67  5787.4 1752.60  5819.0 1754.53  5883.3 1754.83  5946.1 1755.06
#Mann=12,-1,0
  4345.6   0.045       0  4380.0   0.035       0  4617.7    0.07       0
  4793.0    0.05       0  4987.3    0.05       0  4991.7    0.05       0
  5161.6   0.035       0  5259.5    0.05       0  5474.9    0.07       0
  5577.1   0.045       0  5631.1    0.07       0  5883.3   0.045       0
Bank Sta=4987.3,4991.7
Exp/Cntr=0.3,0.1

Type RM Length L Ch R = 1,4700,441,441,441
BEGIN DESCRIPTION:
Mapping XS 17e3d063
END DESCRIPTION:
XS GIS Cut Line= 3
      1530639.05      6939083.72      1529913.37      6939503.84
      1529882.13      6939812.85
#Sta/Elev= 30
  4502.1 1746.34  4553.0 1745.81  4581.2 1746.11  4611.7 1745.81  4655.8 1745.70
  4683.1 1746.11  4714.6 1745.30  4726.3 1745.44  4736.1 1743.68  4750.7 1744.69
  4772.5 1744.75  4795.0 1742.76  4807.2 1743.52  4830.3 1742.51  4902.6 1741.53
  4945.9 1739.99  4977.2 1738.26  4989.8 1738.07  4990.1 1737.57  4994.0 1737.57
  4994.3 1738.07  5036.0 1739.42  5049.9 1740.70  5057.6 1740.91  5234.1 1741.30
  5335.9 1742.44  5445.3 1742.19  5524.0 1742.60  5622.1 1743.03  5651.2 1743.38
#Mann=7,-1,0
  4502.1   0.035       0  4611.7    0.07       0  4750.7    0.05       0
  4989.8    0.05       0  4994.3    0.05       0  5524.0   0.045       0
  5622.1   0.035       0
Bank Sta=4989.8,4994.3
Exp/Cntr=0.3,0.1

Type RM Length L Ch R = 1,4259,325,325,325
BEGIN DESCRIPTION:
Mapping XS 41c1631a
END DESCRIPTION:
XS GIS Cut Line= 3
      1530468.90      6938632.33      1529767.54      6939125.37
      1529746.71      6939691.37
#Sta/Elev= 30
  4411.8 1749.92  4563.9 1748.13  4647.5 1746.44  4697.7 1746.25  4712.3 1744.78
  4721.0 1745.33  4734.4 1743.44  4756.7 1744.81  4771.1 1744.71  4777.6 1743.26
  4793.6 1742.48  4807.3 1742.92  4820.0 1741.84  4863.9 1739.97  4929.2 1738.60
  4950.2 1737.73  4965.0 1736.18  4998.4 1735.48  4998.7 1734.98  5002.6 1734.98
  5003.0 1735.48  5042.5 1736.25  5057.3 1737.47  5114.0 1738.15  5371.8 1739.22
  5506.8 1740.42  5632.0 1741.01  5702.0 1742.44  5813.2 1742.69  5835.5 1742.69
#Mann=8,-1,0
  4411.8   0.035       0  4563.9    0.05       0  4647.5    0.07       0
  4793.6    0.05       0  4998.4    0.05       0  5003.0    0.05       0
  5506.8   0.045       0  5813.2   0.035       0
Bank Sta=4998.4,5003
Exp/Cntr=0.3,0.1

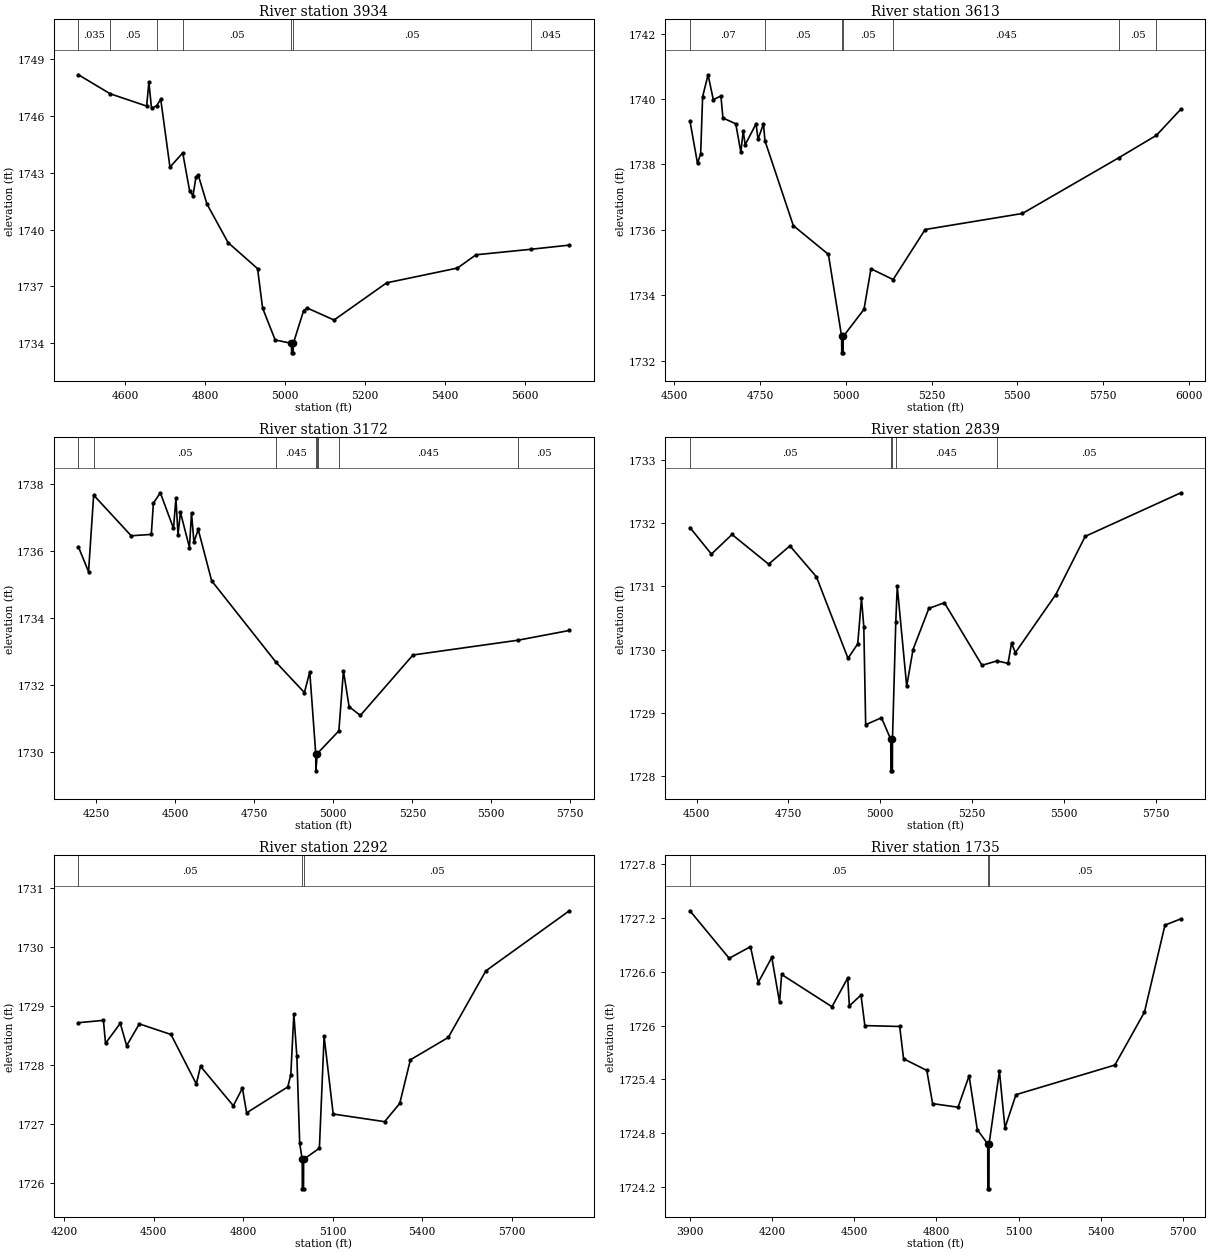
Type RM Length L Ch R = 1,3934,321,321,321
BEGIN DESCRIPTION:
Mapping XS f5ebb5a2
END DESCRIPTION:
XS GIS Cut Line= 3
      1530253.62      6938455.25      1529705.04      6938771.20
      1529600.88      6939357.97
#Sta/Elev= 30
  4482.4 1748.16  4561.9 1747.16  4653.2 1746.51  4658.9 1747.76  4665.4 1746.40
  4678.0 1746.52  4688.5 1746.87  4711.6 1743.29  4743.6 1744.04  4761.0 1742.02
  4769.3 1741.79  4776.8 1742.78  4782.5 1742.87  4804.1 1741.35  4857.2 1739.31
  4930.9 1737.94  4943.5 1735.86  4975.0 1734.18  5015.8 1734.00  5016.1 1733.50
  5020.1 1733.50  5020.4 1734.00  5046.3 1735.73  5055.5 1735.86  5122.4 1735.23
  5254.0 1737.19  5431.3 1737.97  5477.8 1738.67  5615.2 1738.96  5711.4 1739.18
#Mann=7,-1,0
  4482.4   0.035       0  4561.9    0.05       0  4678.0    0.07       0
  4743.6    0.05       0  5015.8    0.05       0  5020.4    0.05       0
  5615.2   0.045       0
Bank Sta=5015.8,5020.4
Exp/Cntr=0.3,0.1

Type RM Length L Ch R = 1,3613,441,441,441
BEGIN DESCRIPTION:
Mapping XS fd55c200
END DESCRIPTION:
XS GIS Cut Line= 4
      1529757.14      6938128.81      1529611.29      6938385.79
      1529406.43      6939035.09      1529524.09      6939474.58
#Sta/Elev= 30
  4545.4 1739.33  4567.5 1738.03  4576.7 1738.33  4582.4 1740.07  4598.3 1740.74
  4613.5 1739.98  4635.8 1740.09  4641.6 1739.42  4679.1 1739.24  4693.9 1738.37
  4700.7 1739.03  4706.4 1738.60  4738.2 1739.24  4743.9 1738.77  4759.8 1739.24
  4764.2 1738.72  4846.8 1736.13  4949.1 1735.25  4987.7 1732.74  4988.0 1732.24
  4992.0 1732.24  4992.3 1732.74  5052.9 1733.57  5073.2 1734.81  5137.8 1734.48
  5231.2 1736.01  5514.7 1736.50  5795.2 1738.20  5905.6 1738.89  5976.7 1739.69
#Mann=7,-1,0
  4545.4    0.07       0  4764.2    0.05       0  4987.7    0.05       0
  4992.3    0.05       0  5137.8   0.045       0  5795.2    0.05       0
  5905.6   0.045       0
Bank Sta=4987.7,4992.3
Exp/Cntr=0.3,0.1

Type RM Length L Ch R = 1,3172,333,333,333
BEGIN DESCRIPTION:
Mapping XS f5dc4707
END DESCRIPTION:
XS GIS Cut Line= 4
      1529642.56      6937920.49      1529246.71      6938260.79
      1529010.60      6938899.68      1529003.65      6939250.37
#Sta/Elev= 30
  4193.0 1736.12  4225.1 1735.38  4241.3 1737.66  4360.1 1736.45  4423.8 1736.49
  4430.3 1737.42  4452.3 1737.73  4494.0 1736.67  4501.7 1737.56  4508.3 1736.48
  4515.9 1737.15  4544.5 1736.10  4551.0 1737.13  4558.7 1736.26  4572.2 1736.64
  4614.7 1735.11  4818.8 1732.68  4908.4 1731.78  4925.3 1732.40  4944.3 1729.95
  4944.6 1729.45  4948.9 1729.95  4950.8 1729.98  5017.4 1730.64  5031.9 1732.43
  5049.8 1731.36  5085.5 1731.10  5252.0 1732.90  5584.4 1733.34  5746.9 1733.63
#Mann=8,-1,0
  4193.0    0.07       0  4241.3    0.05       0  4818.8   0.045       0
  4944.3    0.05       0  4948.9   0.045       0  4950.8    0.05       0
  5017.4   0.045       0  5584.4    0.05       0
Bank Sta=4944.3,4948.9
Exp/Cntr=0.3,0.1

Type RM Length L Ch R = 1,2839,547,547,547
BEGIN DESCRIPTION:
Mapping XS e78cc737
END DESCRIPTION:
XS GIS Cut Line= 4
      1529091.54      6937952.39      1528927.26      6938094.12
      1528791.85      6938687.87      1528774.48      6939198.31
#Sta/Elev= 30
  4482.0 1731.93  4540.5 1731.51  4596.5 1731.82  4696.3 1731.35  4754.2 1731.64
  4826.4 1731.15  4912.4 1729.86  4938.9 1730.09  4949.1 1730.81  4955.4 1730.36
  4960.5 1728.81  5003.5 1728.92  5028.8 1728.58  5029.2 1728.08  5033.2 1728.08
  5033.5 1728.58  5042.5 1730.44  5046.5 1731.00  5072.2 1729.42  5089.5 1730.00
  5132.5 1730.65  5174.8 1730.74  5277.3 1729.75  5318.3 1729.82  5348.1 1729.78
  5357.7 1730.10  5368.1 1729.95  5478.2 1730.87  5558.2 1731.79  5818.7 1732.48
#Mann=5,-1,0
  4482.0    0.05       0  5028.8    0.05       0  5033.5    0.05       0
  5042.5   0.045       0  5318.3    0.05       0
Bank Sta=5028.8,5033.5
Exp/Cntr=0.3,0.1

Type RM Length L Ch R = 1,2292,557,557,557
BEGIN DESCRIPTION:
Mapping XS 5ae68787
END DESCRIPTION:
XS GIS Cut Line= 4
      1528725.39      6937739.91      1528371.71      6938080.23
      1528246.71      6938833.70      1528465.44      6939156.60
#Sta/Elev= 30
  4248.1 1728.72  4331.9 1728.76  4339.0 1728.37  4388.4 1728.71  4409.7 1728.33
  4452.2 1728.70  4558.2 1728.52  4643.1 1727.68  4657.2 1727.98  4767.1 1727.31
  4797.5 1727.61  4811.6 1727.19  4949.5 1727.63  4959.7 1727.84  4969.8 1728.87
  4979.9 1728.15  4989.4 1726.67  4997.9 1726.40  4998.2 1725.90  5002.2 1725.90
  5002.6 1726.40  5055.4 1726.59  5071.2 1728.49  5101.6 1727.17  5273.9 1727.04
  5324.6 1727.35  5360.2 1728.09  5487.2 1728.47  5613.0 1729.60  5892.7 1730.62
#Mann=3,-1,0
  4248.1    0.05       0  4997.9    0.05       0  5002.6    0.05       0
Bank Sta=4997.9,5002.6
Exp/Cntr=0.3,0.1

Type RM Length L Ch R = 1,1735,266,266,266
BEGIN DESCRIPTION:
Mapping XS f6f23e4c
END DESCRIPTION:
XS GIS Cut Line= 5
      1528485.76      6937526.41      1528058.68      6937906.61
      1527829.52      6938133.17      1527751.39      6938771.19
      1527878.40      6938994.11
#Sta/Elev= 30
  3899.5 1727.28  4042.9 1726.75  4120.7 1726.88  4149.1 1726.48  4198.5 1726.76
  4226.9 1726.26  4234.4 1726.57  4418.4 1726.21  4475.8 1726.53  4481.9 1726.22
  4524.4 1726.34  4538.5 1726.00  4665.8 1725.99  4679.9 1725.63  4764.8 1725.50
  4786.0 1725.13  4879.0 1725.09  4919.3 1725.44  4949.3 1724.84  4987.4 1724.68
  4987.8 1724.18  4991.9 1724.18  4992.2 1724.68  5030.1 1725.49  5050.3 1724.86
  5090.6 1725.23  5451.8 1725.56  5559.9 1726.15  5634.8 1727.12  5692.9 1727.19
#Mann=3,-1,0
  3899.5    0.05       0  4987.4    0.05       0  4992.2    0.05       0
Bank Sta=4987.4,4992.2
Exp/Cntr=0.3,0.1

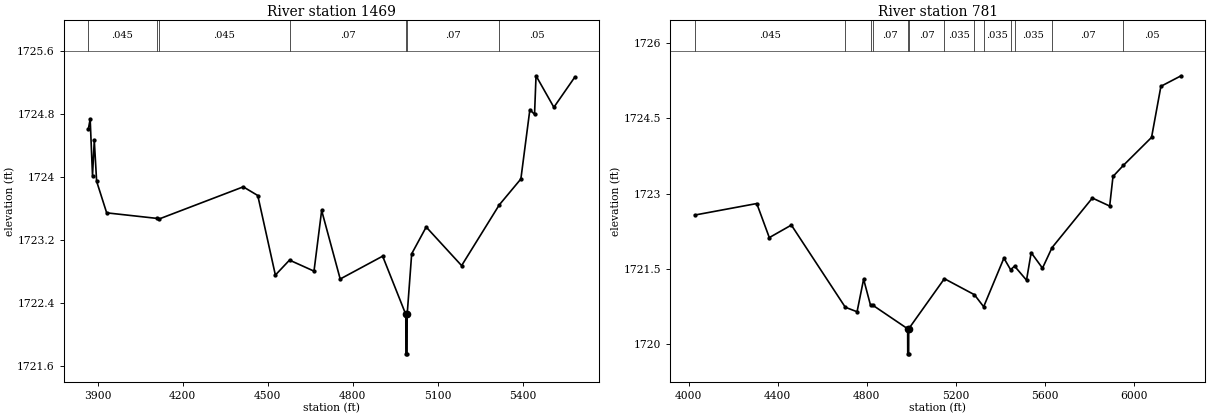
Type RM Length L Ch R = 1,1469,688,688,688
BEGIN DESCRIPTION:
Mapping XS 4e8c2b1e
END DESCRIPTION:
XS GIS Cut Line= 4
      1527980.12      6937252.72      1527748.79      6937427.44
      1527527.43      6938430.05      1527655.03      6938807.62
#Sta/Elev= 30
  3867.2 1724.61  3873.8 1724.74  3882.1 1724.02  3888.3 1724.47  3896.6 1723.95
  3932.0 1723.55  4108.1 1723.48  4115.5 1723.47  4413.7 1723.88  4464.9 1723.77
  4527.0 1722.76  4576.8 1722.95  4663.2 1722.81  4690.2 1723.58  4755.6 1722.71
  4905.3 1723.00  4987.0 1722.26  4987.3 1721.76  4991.4 1721.76  4991.8 1722.26
  5007.7 1723.03  5058.9 1723.37  5183.8 1722.88  5316.4 1723.65  5392.8 1723.98
  5424.5 1724.86  5441.0 1724.80  5446.3 1725.29  5509.2 1724.89  5582.4 1725.27
#Mann=7,-1,0
  3867.2   0.045       0  4108.1    0.07       0  4115.5   0.045       0
  4576.8    0.07       0  4987.0    0.07       0  4991.8    0.07       0
  5316.4    0.05       0
Bank Sta=4987,4991.8
Exp/Cntr=0.3,0.1

Type RM Length L Ch R = 1,781,0,0,0
BEGIN DESCRIPTION:
NC Unknown Stream 49 1.0
END DESCRIPTION:
XS GIS Cut Line= 4
      1527726.20      6937085.64      1527280.04      6937557.65
      1527074.31      6938044.63      1527643.83      6938874.20
#Sta/Elev= 30
  4027.4 1722.57  4305.9 1722.80  4362.2 1722.12  4461.3 1722.37  4703.5 1720.73
  4756.4 1720.64  4785.8 1721.29  4816.8 1720.77  4827.2 1720.77  4983.6 1720.30
  4984.0 1719.80  4988.1 1719.80  4988.4 1720.30  5148.6 1721.30  5283.6 1720.98
  5325.0 1720.74  5415.9 1721.71  5445.9 1721.48  5464.0 1721.55  5517.5 1721.27
  5538.4 1721.82  5589.2 1721.51  5632.1 1721.92  5813.2 1722.91  5891.0 1722.75
  5905.9 1723.34  5952.1 1723.56  6079.1 1724.12  6121.1 1725.14  6211.8 1725.35
#Mann=13,-1,0
  4027.4   0.045       0  4703.5    0.07       0  4816.8   0.045       0
  4827.2    0.07       0  4983.6    0.07       0  4988.4    0.07       0
  5148.6   0.035       0  5283.6    0.07       0  5325.0   0.035       0
  5445.9    0.07       0  5464.0   0.035       0  5632.1    0.07       0
  5952.1    0.05       0
Bank Sta=4983.6,4988.4
Exp/Cntr=0.3,0.1

Chan Stop Cuts=-1