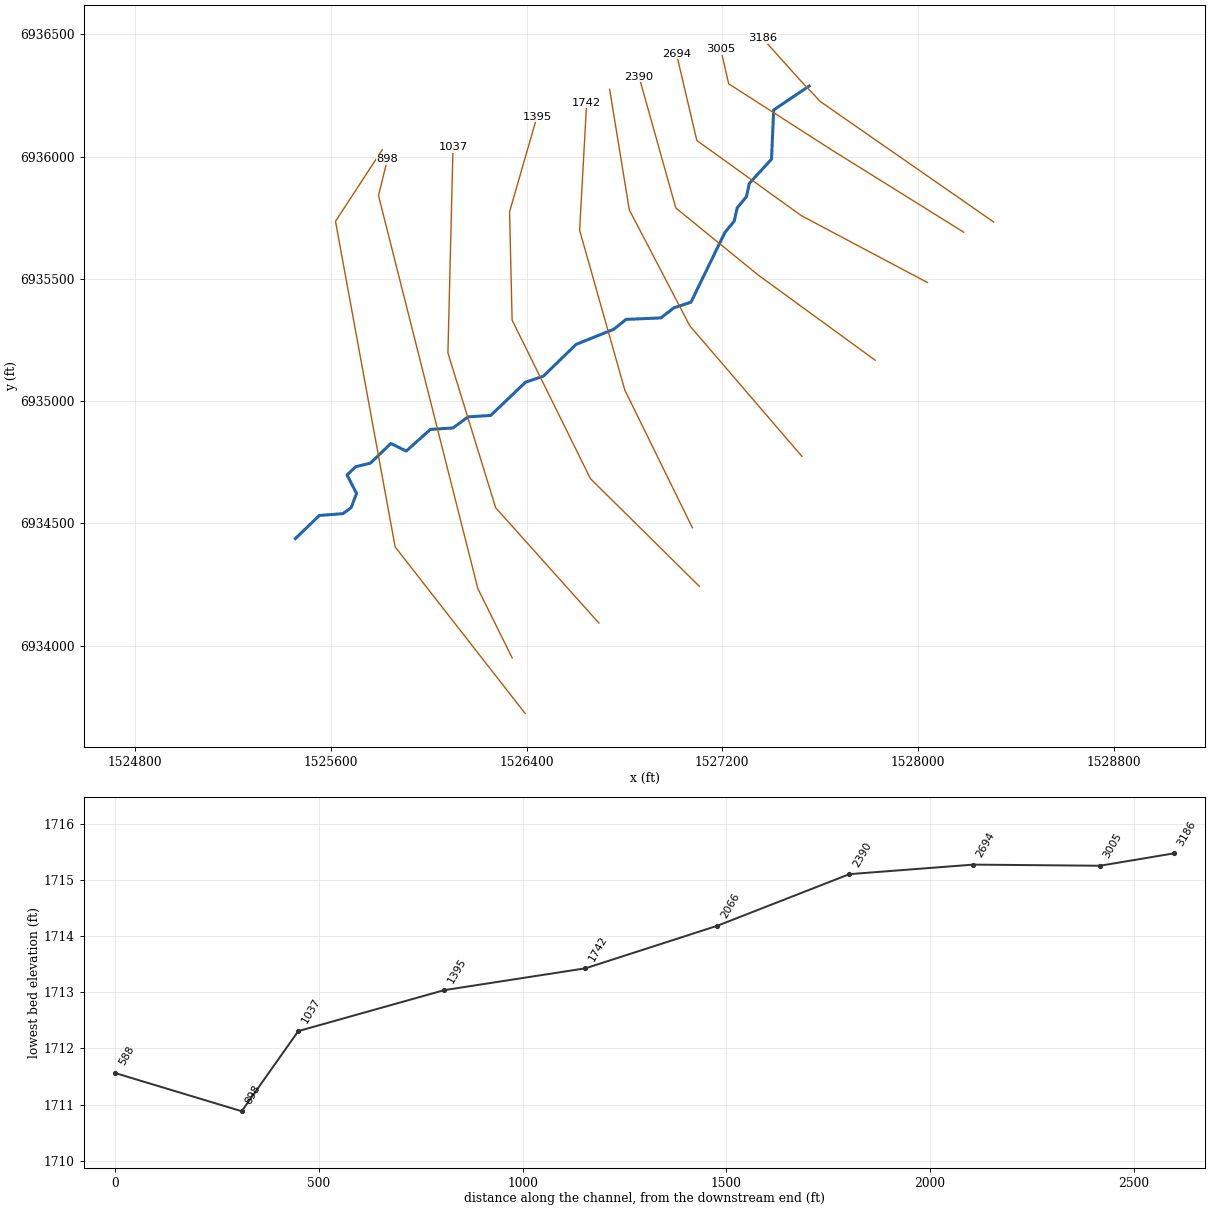
--- NC Unknown Stream 51.prj (project) ---

Proj Title=NC Unknown Stream 51 Base Level Engineering
Current Plan=p01
Default Exp/Contr=0.3,0.1
English Units
Geom File=g01
Flow File=f01
Plan File=p01
BEGIN DESCRIPTION:
NC Unknown Stream 51
END DESCRIPTION:

--- NC Unknown Stream 51.p01 (plan) ---

Plan Title=Multiple Run
Short Identifier=Multiple
Geom File=g01
Flow File=f01
Subcritical Flow
K Sum by GR= 0
Std Step Tol= 0.01
Critical Tol= 0.01
Num of Std Step Trials= 20
Max Error Tol= 0.3
Flow Tol Ratio= 0.001
Split Flow NTrial= 30
Split Flow Tol= 0.02
Split Flow Ratio= 0.02
Log Output Level= 0
Friction Slope Method= 1
Unsteady Friction Slope Method= 2
Unsteady Bridges Friction Slope Method= 1
Parabolic Critical Depth
Global Vel Dist=  1 , 1 , 1
Global Log Level= 0
CheckData=True
Encroach Param= -1, 0, 0, 0
BEGIN DESCRIPTION:
Multiple Run
END DESCRIPTION:

--- NC Unknown Stream 51.f01 (steady flow) ---

Flow Title=Multiple
Number of Profiles=7
Profile Names=10-year,25-year,50-year,1pct_min,100-year,1pct_plu,500-year
River Rch & RM= NC Unknown Strea,Reach-1,3186
     234     324     397     243     485     967     731
River Rch & RM= NC Unknown Strea,Reach-1,3005
     326     458     568     351     700    1396    1076
Boundary for River Rch & Prof#=NC Unknown Strea,Reach-1,1
Up Type=0
Dn Type=3
Dn Slope=0.001
Boundary for River Rch & Prof#=NC Unknown Strea,Reach-1,2
Up Type=0
Dn Type=3
Dn Slope=0.001
Boundary for River Rch & Prof#=NC Unknown Strea,Reach-1,3
Up Type=0
Dn Type=3
Dn Slope=0.001
Boundary for River Rch & Prof#=NC Unknown Strea,Reach-1,4
Up Type=0
Dn Type=3
Dn Slope=0.001
Boundary for River Rch & Prof#=NC Unknown Strea,Reach-1,5
Up Type=0
Dn Type=3
Dn Slope=0.001
Boundary for River Rch & Prof#=NC Unknown Strea,Reach-1,6
Up Type=0
Dn Type=3
Dn Slope=0.001
Boundary for River Rch & Prof#=NC Unknown Strea,Reach-1,7
Up Type=0
Dn Type=3
Dn Slope=0.001

--- NC Unknown Stream 51.g01 (geometry) ---

Geom Title=Existing Conditions

River Reach=NC Unknown Strea,Reach-1
Reach XY= 30
      1527555.00      6936288.00      1527410.35      6936190.70
      1527401.45      6935989.47      1527310.85      6935890.29
      1527298.90      6935835.81      1527261.08      6935790.20
      1527248.92      6935735.80      1527211.08      6935690.20
      1527072.06      6935404.48      1527002.85      6935381.85
      1526949.07      6935340.25      1526806.56      6935334.24
      1526757.18      6935294.12      1526602.70      6935232.17
      1526468.21      6935101.63      1526395.32      6935077.22
      1526253.50      6934941.61      1526160.98      6934935.64
      1526099.02      6934890.36      1526006.50      6934884.36
      1525908.33      6934796.02      1525845.01      6934826.74
      1525761.01      6934746.20      1525702.15      6934732.15
      1525665.98      6934698.37      1525704.85      6934622.58
      1525682.49      6934564.05      1525649.34      6934540.08
      1525552.55      6934532.54      1525455.00      6934438.00

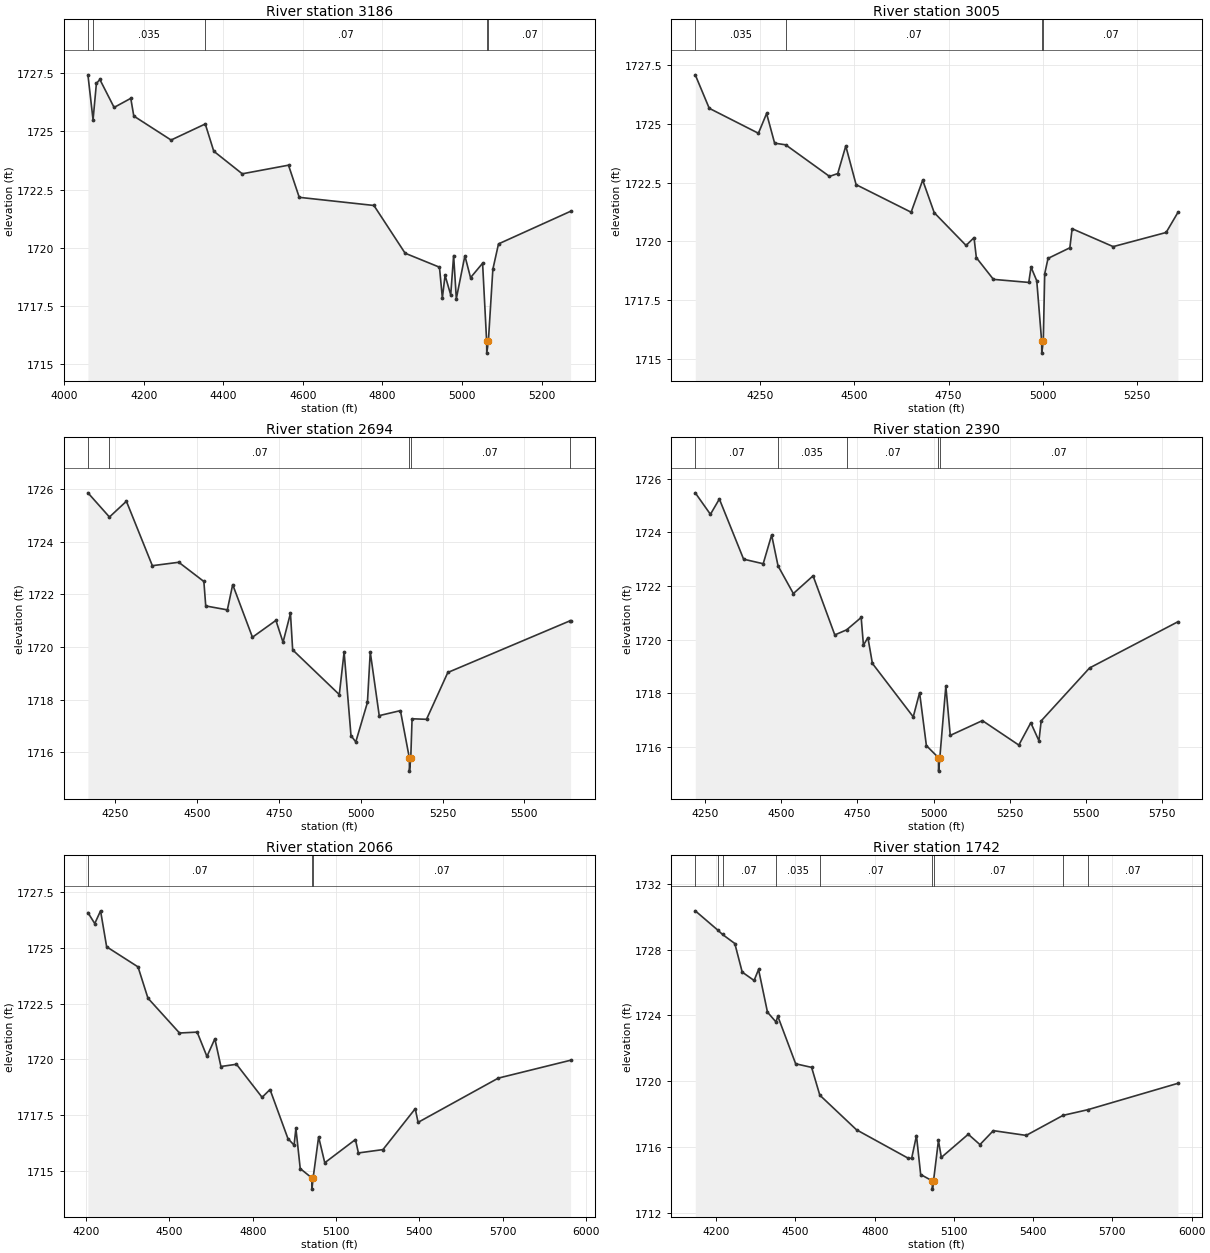
Type RM Length L Ch R = 1,3186,181,181,181
BEGIN DESCRIPTION:
Stream 51 2.0
END DESCRIPTION:
XS GIS Cut Line= 4
      1528309.68      6935732.40      1527601.32      6936224.60
      1527515.39      6936315.75      1527364.98      6936483.31
#Sta/Elev= 30
  4060.0 1727.43  4072.9 1725.50  4081.3 1727.06  4090.0 1727.23  4125.8 1726.03
  4167.7 1726.42  4175.3 1725.66  4269.0 1724.63  4354.9 1725.32  4376.3 1724.15
  4447.9 1723.18  4564.1 1723.55  4591.1 1722.17  4778.8 1721.82  4857.2 1719.77
  4943.5 1719.17  4950.8 1717.85  4957.6 1718.82  4971.8 1717.98  4979.1 1719.67
  4985.9 1717.82  5007.4 1719.66  5021.6 1718.72  5051.9 1719.34  5062.1 1715.98
  5062.4 1715.48  5066.4 1715.98  5077.7 1719.08  5091.9 1720.17  5273.0 1721.57
#Mann=5,-1,0
  4060.0    0.07       0  4072.9   0.035       0  4354.9    0.07       0
  5062.1    0.07       0  5066.4    0.07       0
Bank Sta=5062.1,5066.4
Exp/Cntr=0.3,0.1

Type RM Length L Ch R = 1,3005,311,311,311
BEGIN DESCRIPTION:
Mapping XS a34ca494
END DESCRIPTION:
XS GIS Cut Line= 4
      1528187.26      6935690.75      1527648.20      6936026.69
      1527226.32      6936297.52      1527194.10      6936438.08
#Sta/Elev= 30
  4078.0 1727.07  4115.1 1725.65  4245.6 1724.59  4267.3 1725.43  4288.6 1724.17
  4317.9 1724.10  4434.2 1722.76  4456.1 1722.88  4477.4 1724.05  4504.8 1722.41
  4650.8 1721.24  4681.5 1722.60  4712.1 1721.22  4796.6 1719.83  4817.7 1720.16
  4823.9 1719.31  4869.2 1718.39  4963.0 1718.26  4969.0 1718.91  4984.2 1718.33
  4997.2 1715.76  4997.5 1715.26  5001.5 1715.76  5005.3 1718.63  5014.1 1719.28
  5072.0 1719.73  5078.0 1720.54  5187.0 1719.78  5327.5 1720.38  5358.7 1721.23
#Mann=4,-1,0
  4078.0   0.035       0  4317.9    0.07       0  4997.2    0.07       0
  5001.5    0.07       0
Bank Sta=4997.2,5001.5
Exp/Cntr=0.3,0.1

Type RM Length L Ch R = 1,2694,304,304,304
BEGIN DESCRIPTION:
Mapping XS b99d5532
END DESCRIPTION:
XS GIS Cut Line= 4
      1528038.82      6935485.02      1527523.20      6935758.46
      1527096.11      6936065.75      1527012.79      6936419.90
#Sta/Elev= 30
  4167.3 1725.86  4233.0 1724.94  4284.8 1725.54  4364.0 1723.09  4444.7 1723.22
  4521.3 1722.49  4527.0 1721.56  4593.0 1721.41  4609.3 1722.37  4669.6 1720.37
  4741.3 1721.01  4763.0 1720.18  4785.7 1721.28  4792.4 1719.89  4934.8 1718.19
  4949.5 1719.81  4970.5 1716.63  4985.1 1716.39  5020.7 1717.89  5029.3 1719.81
  5056.7 1717.39  5121.4 1717.58  5148.7 1715.78  5149.0 1715.28  5153.0 1715.78
  5157.0 1717.27  5201.1 1717.25  5266.1 1719.03  5638.4 1720.99  5640.9 1720.99
#Mann=5,-1,0
  4167.3   0.035       0  4233.0    0.07       0  5148.7    0.07       0
  5153.0    0.07       0  5638.4   0.045       0
Bank Sta=5148.7,5153
Exp/Cntr=0.3,0.1

Type RM Length L Ch R = 1,2390,324,324,324
BEGIN DESCRIPTION:
Mapping XS 049e5a9c
END DESCRIPTION:
XS GIS Cut Line= 4
      1527825.25      6935167.33      1527346.11      6935516.27
      1527010.18      6935789.71      1526859.57      6936327.22
#Sta/Elev= 30
  4217.6 1725.47  4267.4 1724.67  4296.7 1725.24  4376.3 1723.00  4440.6 1722.83
  4468.3 1723.90  4489.3 1722.75  4539.6 1721.72  4604.3 1722.38  4675.6 1720.18
  4714.5 1720.37  4762.2 1720.83  4769.6 1719.80  4784.3 1720.08  4799.0 1719.12
  4933.1 1717.13  4953.9 1718.03  4976.2 1716.06  5015.9 1715.61  5016.2 1715.11
  5020.3 1715.61  5040.1 1718.28  5054.5 1716.44  5160.0 1716.99  5279.6 1716.08
  5318.9 1716.91  5345.6 1716.24  5353.0 1716.98  5511.7 1718.95  5801.7 1720.67
#Mann=5,-1,0
  4217.6    0.07       0  4489.3   0.035       0  4714.5    0.07       0
  5015.9    0.07       0  5020.3    0.07       0
Bank Sta=5015.9,5020.3
Exp/Cntr=0.3,0.1

Type RM Length L Ch R = 1,2066,324,324,324
BEGIN DESCRIPTION:
Mapping XS d83bf505
END DESCRIPTION:
XS GIS Cut Line= 4
      1527525.81      6934774.07      1527067.47      6935307.94
      1526820.07      6935781.90      1526739.65      6936274.81
#Sta/Elev= 30
  4206.6 1726.57  4231.2 1726.08  4252.1 1726.65  4274.0 1725.04  4387.0 1724.14
  4422.7 1722.74  4536.3 1721.18  4599.9 1721.22  4635.1 1720.13  4663.6 1720.92
  4685.5 1719.68  4741.5 1719.78  4833.7 1718.30  4862.2 1718.65  4926.8 1716.45
  4948.9 1716.16  4955.4 1716.91  4971.0 1715.11  5012.9 1714.69  5013.2 1714.19
  5017.4 1714.69  5037.2 1716.53  5059.3 1715.37  5169.7 1716.41  5180.5 1715.81
  5268.9 1715.96  5385.0 1717.79  5395.4 1717.18  5684.1 1719.16  5944.3 1719.96
#Mann=3,-1,0
  4206.6    0.07       0  5012.9    0.07       0  5017.4    0.07       0
Bank Sta=5012.9,5017.4
Exp/Cntr=0.3,0.1

Type RM Length L Ch R = 1,1742,347,347,347
BEGIN DESCRIPTION:
Mapping XS c0b72136
END DESCRIPTION:
XS GIS Cut Line= 4
      1527077.88      6934482.44      1526801.84      6935044.92
      1526616.95      6935698.56      1526645.60      6936219.42
#Sta/Elev= 30
  4120.5 1730.37  4204.8 1729.21  4223.9 1728.93  4270.3 1728.38  4298.3 1726.64
  4343.3 1726.13  4360.2 1726.80  4394.0 1724.20  4425.9 1723.61  4433.2 1723.95
  4500.7 1721.06  4561.1 1720.84  4592.1 1719.15  4731.2 1717.04  4926.9 1715.31
  4940.0 1715.31  4958.1 1716.69  4974.0 1714.32  5018.2 1713.93  5018.5 1713.43
  5022.7 1713.93  5041.3 1716.39  5052.3 1715.36  5154.2 1716.77  5198.5 1716.14
  5249.1 1716.99  5373.5 1716.70  5513.2 1717.92  5605.9 1718.26  5948.0 1719.87
#Mann=9,-1,0
  4120.5    0.07       0  4204.8   0.035       0  4223.9    0.07       0
  4425.9   0.035       0  4592.1    0.07       0  5018.2    0.07       0
  5022.7    0.07       0  5513.2   0.035       0  5605.9    0.07       0
Bank Sta=5018.2,5022.7
Exp/Cntr=0.3,0.1

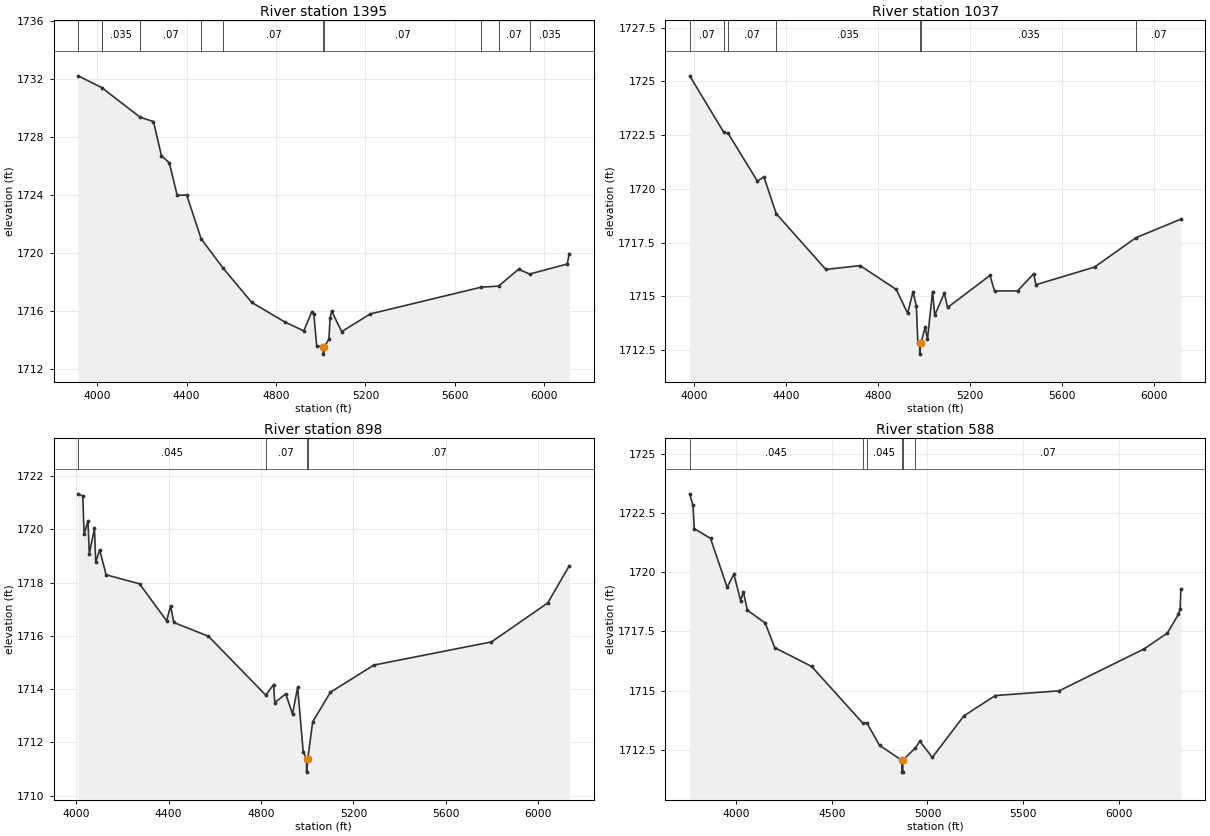
Type RM Length L Ch R = 1,1395,358,358,358
BEGIN DESCRIPTION:
Mapping XS 783fdec9
END DESCRIPTION:
XS GIS Cut Line= 5
      1527106.52      6934242.84      1526661.22      6934682.94
      1526340.91      6935331.38      1526330.49      6935774.08
      1526442.47      6936162.10
#Sta/Elev= 30
  3915.1 1732.22  4020.7 1731.41  4193.0 1729.36  4252.2 1729.07  4287.5 1726.72
  4322.9 1726.22  4358.2 1723.98  4400.7 1724.01  4465.1 1720.99  4564.2 1718.95
  4691.8 1716.60  4839.9 1715.25  4924.1 1714.64  4959.5 1715.95  4969.0 1715.81
  4981.8 1713.62  5011.6 1713.54  5011.9 1713.04  5016.1 1713.54  5036.3 1714.06
  5041.9 1715.56  5048.7 1716.01  5093.4 1714.59  5221.5 1715.81  5716.0 1717.65
  5795.3 1717.73  5884.4 1718.89  5933.9 1718.56  6101.9 1719.25  6111.1 1719.96
#Mann=10,-1,0
  3915.1    0.07       0  4020.7   0.035       0  4193.0    0.07       0
  4465.1   0.035       0  4564.2    0.07       0  5011.6    0.07       0
  5016.1    0.07       0  5716.0   0.035       0  5795.3    0.07       0
  5933.9   0.035       0
Bank Sta=5011.6,5016.1
Exp/Cntr=0.3,0.1

Type RM Length L Ch R = 1,1037,139,139,139
BEGIN DESCRIPTION:
Mapping XS 934188c0
END DESCRIPTION:
XS GIS Cut Line= 4
      1526695.67      6934092.76      1526273.79      6934564.12
      1526078.48      6935196.93      1526099.31      6936038.12
#Sta/Elev= 30
  3979.2 1725.26  4127.0 1722.64  4146.6 1722.58  4273.7 1720.36  4302.1 1720.56
  4355.2 1718.85  4571.3 1716.25  4720.5 1716.43  4877.5 1715.32  4927.2 1714.21
  4950.7 1715.22  4965.1 1714.54  4971.7 1712.83  4979.3 1712.81  4979.8 1712.31
  4984.9 1712.81  5003.1 1713.55  5013.5 1713.02  5035.6 1715.22  5044.9 1714.12
  5086.8 1715.15  5100.9 1714.48  5285.1 1715.97  5305.1 1715.25  5405.2 1715.25
  5475.2 1716.05  5485.2 1715.54  5739.9 1716.36  5920.7 1717.73  6115.5 1718.59
#Mann=7,-1,0
  3979.2    0.07       0  4127.0   0.035       0  4146.6    0.07       0
  4355.2   0.035       0  4979.3   0.035       0  4984.9   0.035       0
  5920.7    0.07       0
Bank Sta=4979.3,4984.9
Exp/Cntr=0.3,0.1

Type RM Length L Ch R = 1,898,310,310,310
BEGIN DESCRIPTION:
Mapping XS 7e2a2a7e
END DESCRIPTION:
XS GIS Cut Line= 4
      1526341.48      6933949.58      1526200.87      6934233.39
      1525794.62      6935840.16      1525831.08      6935988.58
#Sta/Elev= 30
  4007.9 1721.33  4028.3 1721.25  4033.9 1719.81  4050.7 1720.31  4056.3 1719.07
  4078.7 1720.03  4084.3 1718.76  4101.2 1719.23  4129.2 1718.29  4274.0 1717.95
  4391.3 1716.56  4408.3 1717.12  4422.2 1716.50  4572.4 1715.98  4820.7 1713.77
  4854.4 1714.17  4859.6 1713.49  4907.0 1713.82  4936.5 1713.06  4958.6 1714.07
  4982.6 1711.65  4997.0 1711.38  4997.5 1710.88  5002.6 1711.38  5023.7 1712.77
  5100.6 1713.88  5288.7 1714.90  5798.0 1715.77  6041.4 1717.23  6134.8 1718.63
#Mann=4,-1,0
  4007.9   0.045       0  4820.7    0.07       0  4997.0    0.07       0
  5002.6    0.07       0
Bank Sta=4997,5002.6
Exp/Cntr=0.3,0.1

Type RM Length L Ch R = 1,588,0,0,0
BEGIN DESCRIPTION:
Stream 51 1.0
END DESCRIPTION:
XS GIS Cut Line= 4
      1526393.99      6933723.43      1525862.76      6934403.96
      1525618.84      6935735.12      1525810.32      6936028.40
#Sta/Elev= 30
  3757.2 1723.30  3774.6 1722.81  3781.0 1721.83  3866.0 1721.42  3952.8 1719.36
  3988.1 1719.91  4023.4 1718.80  4037.9 1719.17  4058.7 1718.39  4151.8 1717.85
  4201.6 1716.81  4394.2 1716.02  4661.5 1713.63  4682.8 1713.64  4749.3 1712.69
  4865.8 1712.06  4866.3 1711.56  4871.0 1711.56  4871.4 1712.06  4937.2 1712.59
  4960.1 1712.86  5025.2 1712.18  5189.8 1713.93  5354.3 1714.79  5688.5 1714.99
  6132.5 1716.76  6254.1 1717.43  6311.7 1718.22  6320.6 1718.46  6324.1 1719.28
#Mann=6,-1,0
  3757.2   0.045       0  4661.5    0.07       0  4682.8   0.045       0
  4865.8    0.07       0  4871.4   0.045       0  4937.2    0.07       0
Bank Sta=4865.8,4871.4
Exp/Cntr=0.3,0.1

Chan Stop Cuts=-1