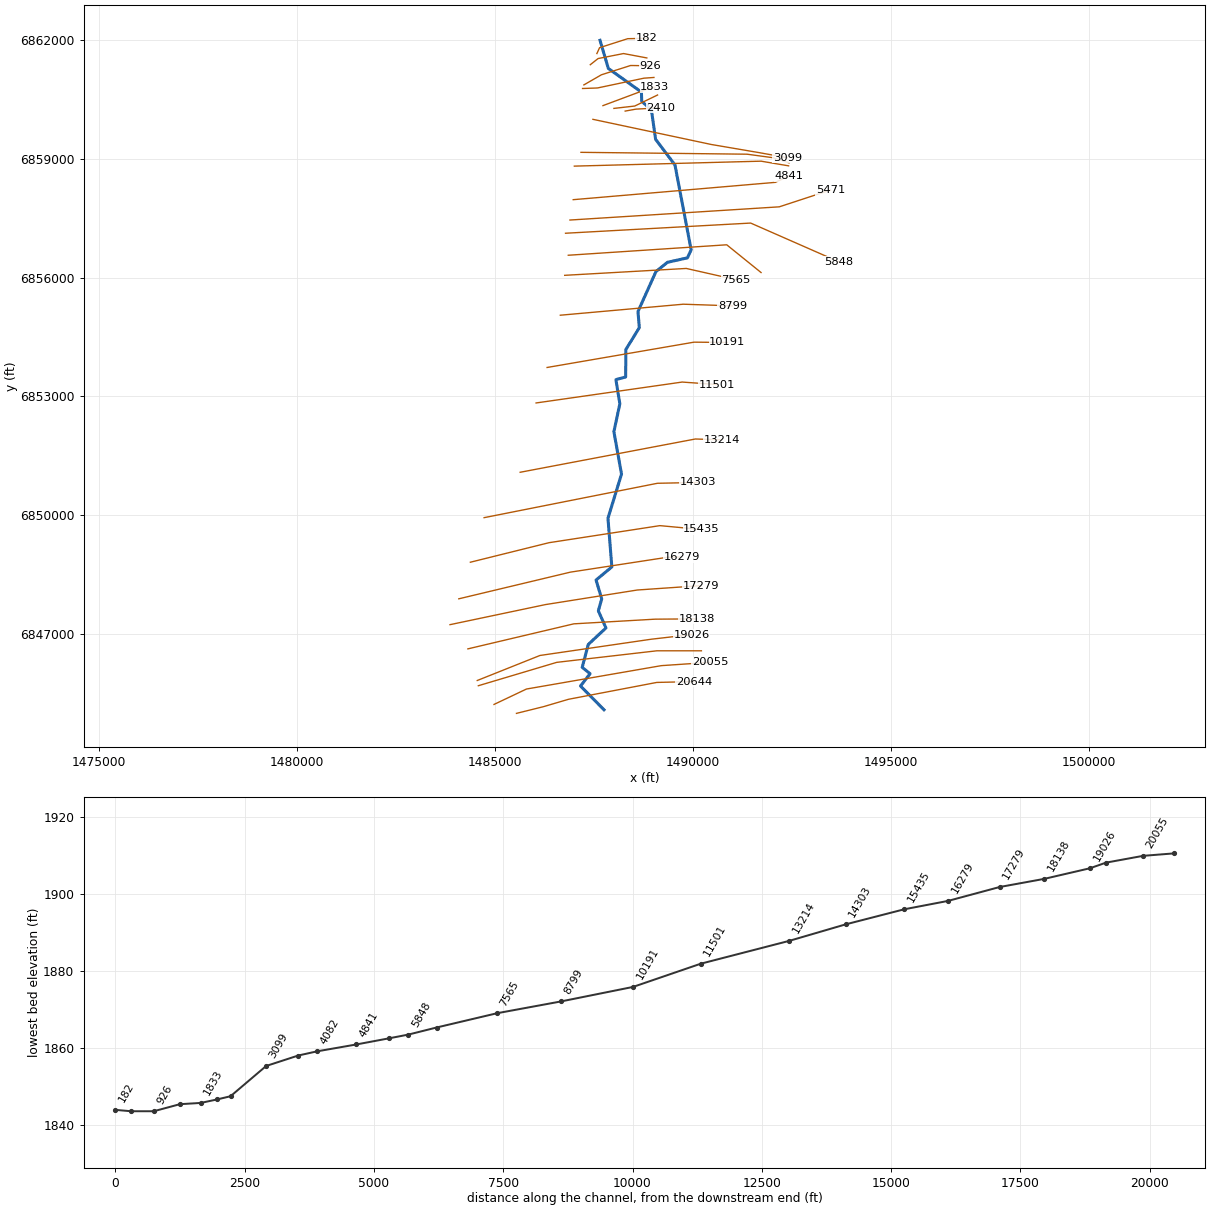
--- NC Unknown Stream 58.prj (project) ---

Proj Title=NC Unknown Stream 58 Base Level Engineering
Current Plan=p01
Default Exp/Contr=0.3,0.1
English Units
Geom File=g01
Flow File=f01
Plan File=p01
BEGIN DESCRIPTION:
NC Unknown Stream 58
END DESCRIPTION:

--- NC Unknown Stream 58.p01 (plan) ---

Plan Title=Multiple Run
Short Identifier=Multiple
Geom File=g01
Flow File=f01
Subcritical Flow
K Sum by GR= 0
Std Step Tol= 0.01
Critical Tol= 0.01
Num of Std Step Trials= 20
Max Error Tol= 0.3
Flow Tol Ratio= 0.001
Split Flow NTrial= 30
Split Flow Tol= 0.02
Split Flow Ratio= 0.02
Log Output Level= 0
Friction Slope Method= 1
Unsteady Friction Slope Method= 2
Unsteady Bridges Friction Slope Method= 1
Parabolic Critical Depth
Global Vel Dist=  1 , 1 , 1
Global Log Level= 0
CheckData=True
Encroach Param= -1, 0, 0, 0
BEGIN DESCRIPTION:
Multiple Run
END DESCRIPTION:

--- NC Unknown Stream 58.f01 (steady flow) ---

Flow Title=Multiple
Number of Profiles=7
Profile Names=10-year,25-year,50-year,1pct_min,100-year,1pct_plu,500-year
River Rch & RM= NC Unknown Strea,Reach-1,20644
     218     298     362     219     437     872     644
River Rch & RM= NC Unknown Strea,Reach-1,18138
     326     454     559     342     682    1360    1027
River Rch & RM= NC Unknown Strea,Reach-1,13214
     436     615     764     471     939    1874    1439
River Rch & RM= NC Unknown Strea,Reach-1,7565
     464     657     817     504    1006    2008    1545
River Rch & RM= NC Unknown Strea,Reach-1,2410
     582     831    1040     645    1288    2570    1999
Boundary for River Rch & Prof#=NC Unknown Strea,Reach-1,1
Up Type=0
Dn Type=3
Dn Slope=0.001
Boundary for River Rch & Prof#=NC Unknown Strea,Reach-1,2
Up Type=0
Dn Type=3
Dn Slope=0.001
Boundary for River Rch & Prof#=NC Unknown Strea,Reach-1,3
Up Type=0
Dn Type=3
Dn Slope=0.001
Boundary for River Rch & Prof#=NC Unknown Strea,Reach-1,4
Up Type=0
Dn Type=3
Dn Slope=0.001
Boundary for River Rch & Prof#=NC Unknown Strea,Reach-1,5
Up Type=0
Dn Type=3
Dn Slope=0.001
Boundary for River Rch & Prof#=NC Unknown Strea,Reach-1,6
Up Type=0
Dn Type=3
Dn Slope=0.001
Boundary for River Rch & Prof#=NC Unknown Strea,Reach-1,7
Up Type=0
Dn Type=3
Dn Slope=0.001

--- NC Unknown Stream 58.g01 (geometry) ---

Geom Title=Existing Conditions

River Reach=NC Unknown Strea,Reach-1
Reach XY= 30
      1487755.00      6845088.00      1487162.20      6845687.70
      1487404.47      6845998.69      1487204.73      6846157.94
      1487358.45      6846736.75      1487804.76      6847153.22
      1487612.50      6847584.42      1487697.64      6847888.08
      1487554.70      6848363.13      1487952.94      6848693.85
      1487855.51      6849922.79      1488197.67      6851037.90
      1488004.96      6852107.98      1488155.29      6852812.88
      1488055.52      6853422.45      1488301.94      6853489.40
      1488306.97      6854182.11      1488647.31      6854734.33
      1488612.99      6855141.34      1489066.11      6856148.32
      1489356.46      6856384.47      1489861.07      6856496.13
      1489955.50      6856698.17      1489547.18      6858841.41
      1489058.45      6859489.25      1488951.25      6860236.45
      1488708.06      6860446.28      1488699.82      6860682.56
      1487865.34      6861277.88      1487655.00      6861988.00

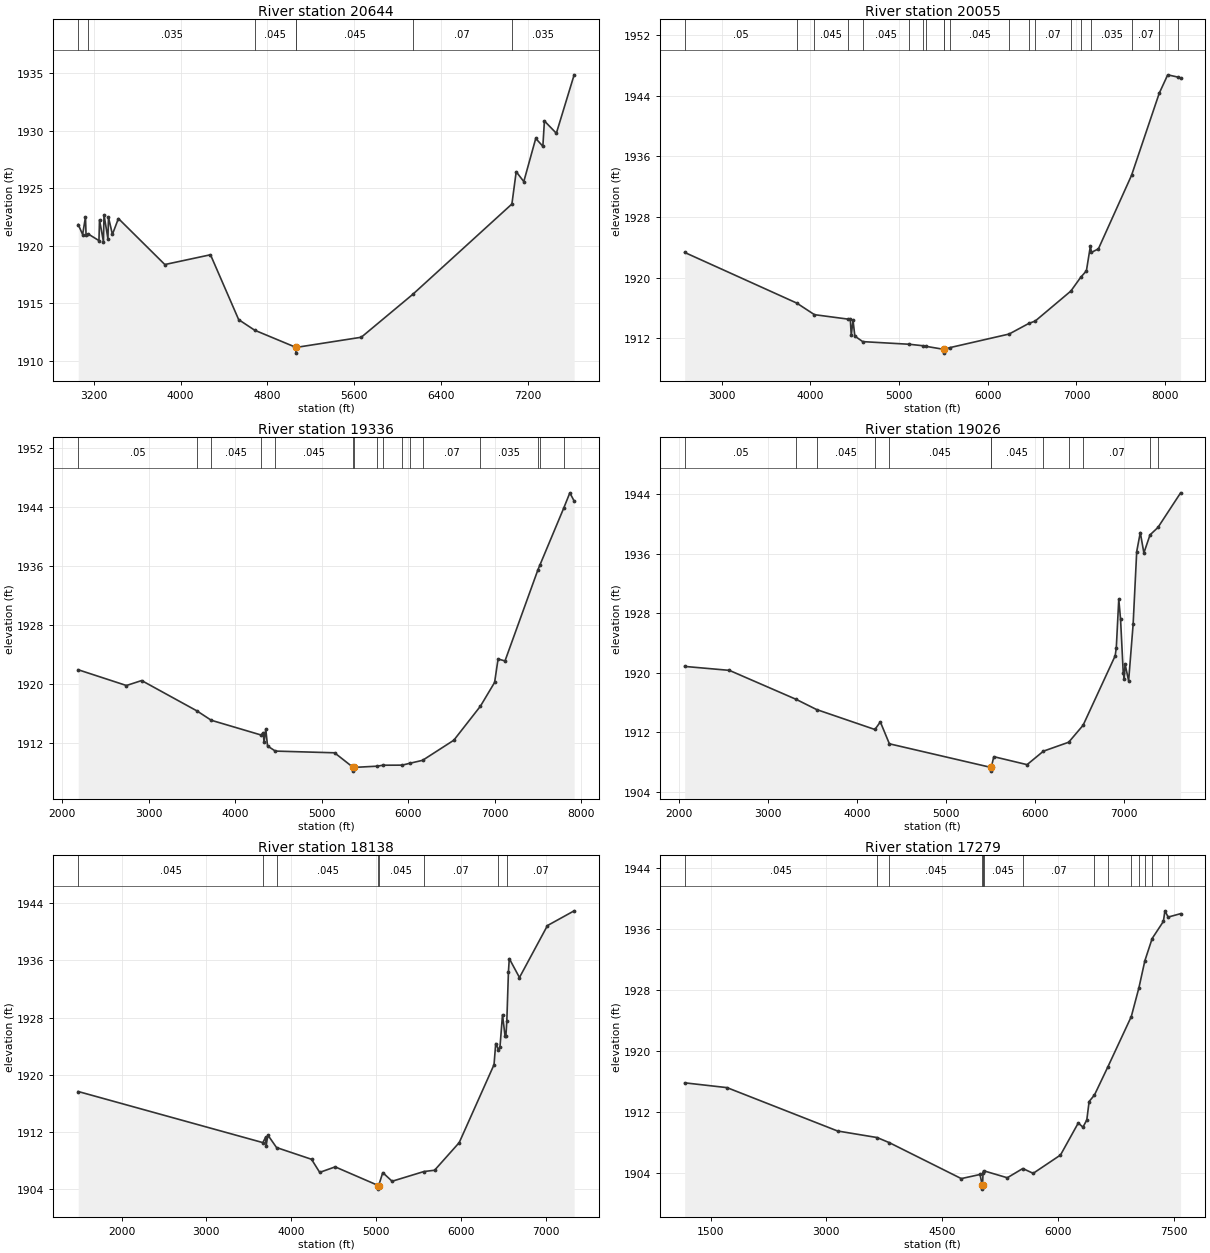
Type RM Length L Ch R = 1,20644,589,589,589
BEGIN DESCRIPTION:
Mapping XS dbc294ec
END DESCRIPTION:
XS GIS Cut Line= 5
      1485545.47      6844996.67      1486226.91      6845165.95
      1486860.59      6845352.58      1489087.16      6845777.93
      1490029.03      6845799.63
#Sta/Elev= 30
  3056.1 1921.83  3096.8 1920.96  3123.2 1922.49  3128.4 1920.90  3149.5 1921.00
  3247.3 1920.43  3252.4 1922.24  3288.6 1920.34  3293.8 1922.68  3330.0 1920.60
  3335.1 1922.46  3371.3 1920.97  3426.6 1922.35  3854.7 1918.35  4275.5 1919.20
  4535.3 1913.56  4683.2 1912.64  5063.2 1911.15  5063.5 1910.65  5067.2 1911.15
  5665.4 1912.03  6139.0 1915.75  7053.9 1923.61  7093.6 1926.42  7163.6 1925.56
  7273.7 1929.31  7339.4 1928.63  7353.7 1930.83  7463.7 1929.76  7627.8 1934.84
#Mann=7,-1,0
  3056.1    0.07       0  3149.5   0.035       0  4683.2   0.045       0
  5063.2   0.045       0  5067.2   0.045       0  6139.0    0.07       0
  7053.9   0.035       0
Bank Sta=5063.2,5067.2
Exp/Cntr=0.3,0.1

Type RM Length L Ch R = 1,20055,719,719,719
BEGIN DESCRIPTION:
Mapping XS d5182024
END DESCRIPTION:
XS GIS Cut Line= 4
      1484978.69      6845222.39      1485798.09      6845611.26
      1489200.87      6846201.54      1490430.06      6846284.87
#Sta/Elev= 30
  2582.5 1923.32  3846.5 1916.63  4045.8 1915.10  4426.5 1914.51  4450.5 1914.50
  4460.7 1912.37  4481.0 1914.36  4501.3 1912.27  4590.3 1911.54  5116.8 1911.19
  5274.0 1910.99  5302.8 1910.92  5504.1 1910.52  5504.3 1910.02  5508.1 1910.52
  5574.5 1910.75  6240.8 1912.54  6464.3 1913.95  6534.7 1914.25  6937.4 1918.22
  7046.7 1920.01  7112.6 1920.89  7157.7 1924.17  7169.7 1923.33  7247.9 1923.79
  7621.5 1933.50  7934.3 1944.36  8029.7 1946.78  8145.0 1946.48  8175.1 1946.38
#Mann=20,-1,0
  2582.5    0.05       0  3846.5   0.035       0  4045.8   0.045       0
  4426.5   0.035       0  4590.3   0.045       0  5116.8    0.07       0
  5274.0   0.045       0  5302.8    0.07       0  5504.1   0.045       0
  5508.1    0.07       0  5574.5   0.045       0  6240.8    0.07       0
  6464.3   0.035       0  6534.7    0.07       0  6937.4   0.035       0
  7046.7    0.07       0  7169.7   0.035       0  7621.5    0.07       0
  7934.3   0.035       0  8145.0   0.045       0
Bank Sta=5504.1,5508.1
Exp/Cntr=0.3,0.1

Type RM Length L Ch R = 1,19336,310,310,310
BEGIN DESCRIPTION:
Mapping XS 9812ce7a
END DESCRIPTION:
XS GIS Cut Line= 4
      1484582.81      6845694.59      1486561.98      6846284.87
      1489089.76      6846576.54      1490214.79      6846576.54
#Sta/Elev= 30
  2185.9 1921.96  2743.3 1919.83  2919.5 1920.50  3559.7 1916.39  3724.3 1915.13
  4302.2 1913.13  4325.9 1913.45  4334.8 1912.13  4354.9 1913.94  4375.1 1911.65
  4465.7 1910.96  5150.2 1910.73  5365.8 1908.75  5366.1 1908.25  5369.8 1908.75
  5643.0 1908.92  5710.5 1909.05  5932.7 1909.06  6026.8 1909.33  6167.8 1909.71
  6529.3 1912.43  6836.7 1917.03  7001.0 1920.25  7041.0 1923.42  7121.0 1923.15
  7502.5 1935.50  7522.9 1936.07  7799.8 1943.81  7871.0 1945.89  7920.8 1944.78
#Mann=16,-1,0
  2185.9    0.05       0  3559.7   0.035       0  3724.3   0.045       0
  4302.2   0.035       0  4465.7   0.045       0  5365.8   0.045       0
  5369.8   0.045       0  5643.0    0.07       0  5710.5   0.045       0
  5932.7    0.07       0  6026.8   0.045       0  6167.8    0.07       0
  6836.7   0.035       0  7502.5    0.07       0  7522.9   0.035       0
  7799.8    0.07       0
Bank Sta=5365.8,5369.8
Exp/Cntr=0.3,0.1

Type RM Length L Ch R = 1,19026,888,888,888
BEGIN DESCRIPTION:
Mapping XS 1ac40f45
END DESCRIPTION:
XS GIS Cut Line= 4
      1484555.03      6845826.54      1486138.37      6846458.48
      1488943.93      6846868.20      1489964.72      6846986.26
#Sta/Elev= 30
  2065.4 1920.85  2567.2 1920.32  3318.3 1916.42  3546.1 1915.06  4200.9 1912.38
  4262.0 1913.40  4363.5 1910.46  5503.0 1907.29  5503.3 1906.79  5507.0 1907.29
  5535.9 1908.73  5909.3 1907.66  6092.7 1909.47  6376.4 1910.67  6538.2 1912.95
  6898.5 1922.28  6911.0 1923.34  6938.8 1929.88  6958.9 1927.18  6989.1 1919.95
  6999.8 1919.22  7009.3 1921.18  7049.5 1918.91  7099.9 1926.50  7140.1 1936.27
  7180.4 1938.83  7220.7 1936.09  7289.5 1938.51  7378.5 1939.51  7633.1 1944.16
#Mann=12,-1,0
  2065.4    0.05       0  3318.3   0.035       0  3546.1   0.045       0
  4200.9   0.035       0  4363.5   0.045       0  5503.0   0.045       0
  5507.0   0.045       0  6092.7    0.07       0  6376.4   0.035       0
  6538.2    0.07       0  7289.5   0.035       0  7378.5    0.07       0
Bank Sta=5503,5507
Exp/Cntr=0.3,0.1

Type RM Length L Ch R = 1,18138,859,859,859
BEGIN DESCRIPTION:
Mapping XS a2d35238
END DESCRIPTION:
XS GIS Cut Line= 4
      1484318.93      6846625.15      1486992.54      6847257.09
      1489048.09      6847375.15      1490089.75      6847382.09
#Sta/Elev= 30
  1488.5 1917.66  3665.8 1910.52  3697.6 1911.26  3704.0 1910.03  3724.5 1911.58
  3827.2 1909.83  4239.5 1908.19  4336.1 1906.36  4518.7 1907.13  5027.5 1904.52
  5027.7 1904.02  5031.6 1904.52  5079.6 1906.33  5189.8 1905.12  5565.4 1906.48
  5690.6 1906.66  5981.1 1910.52  6391.6 1921.41  6411.6 1924.37  6443.5 1923.51
  6461.6 1923.85  6491.6 1928.40  6521.6 1925.41  6531.6 1925.42  6542.5 1927.52
  6561.6 1934.41  6571.6 1936.23  6691.6 1933.59  7021.6 1940.85  7336.4 1942.91
#Mann=8,-1,0
  1488.5   0.045       0  3665.8   0.035       0  3827.2   0.045       0
  5027.5   0.045       0  5031.6   0.045       0  5565.4    0.07       0
  6443.5   0.035       0  6542.5    0.07       0
Bank Sta=5027.5,5031.6
Exp/Cntr=0.3,0.1

Type RM Length L Ch R = 1,17279,1000,1000,1000
BEGIN DESCRIPTION:
Mapping XS 2b3bb7fe
END DESCRIPTION:
XS GIS Cut Line= 4
      1483867.53      6847236.26      1486277.26      6847743.20
      1488596.71      6848111.26      1490207.83      6848222.37
#Sta/Elev= 30
  1163.7 1915.84  1712.9 1915.21  3144.1 1909.53  3657.1 1908.67  3817.4 1907.99
  4747.8 1903.29  4990.8 1903.83  5019.0 1902.41  5019.3 1901.91  5023.4 1902.41
  5029.4 1904.04  5035.9 1904.32  5343.9 1903.40  5544.7 1904.61  5679.3 1903.98
  6033.1 1906.38  6263.6 1910.58  6323.8 1910.03  6373.9 1910.97  6404.0 1913.39
  6473.6 1914.25  6648.7 1917.97  6950.4 1924.52  7049.4 1928.30  7126.1 1931.83
  7220.6 1934.75  7366.2 1936.99  7386.3 1938.38  7428.1 1937.56  7589.6 1938.01
#Mann=15,-1,0
  1163.7   0.045       0  3657.1   0.035       0  3817.4   0.045       0
  5019.0   0.045       0  5023.4   0.045       0  5029.4    0.07       0
  5035.9   0.045       0  5544.7    0.07       0  6473.6   0.035       0
  6648.7    0.07       0  6950.4   0.035       0  7049.4    0.07       0
  7126.1   0.035       0  7220.6    0.07       0  7428.1   0.045       0
Bank Sta=5019,5023.4
Exp/Cntr=0.3,0.1

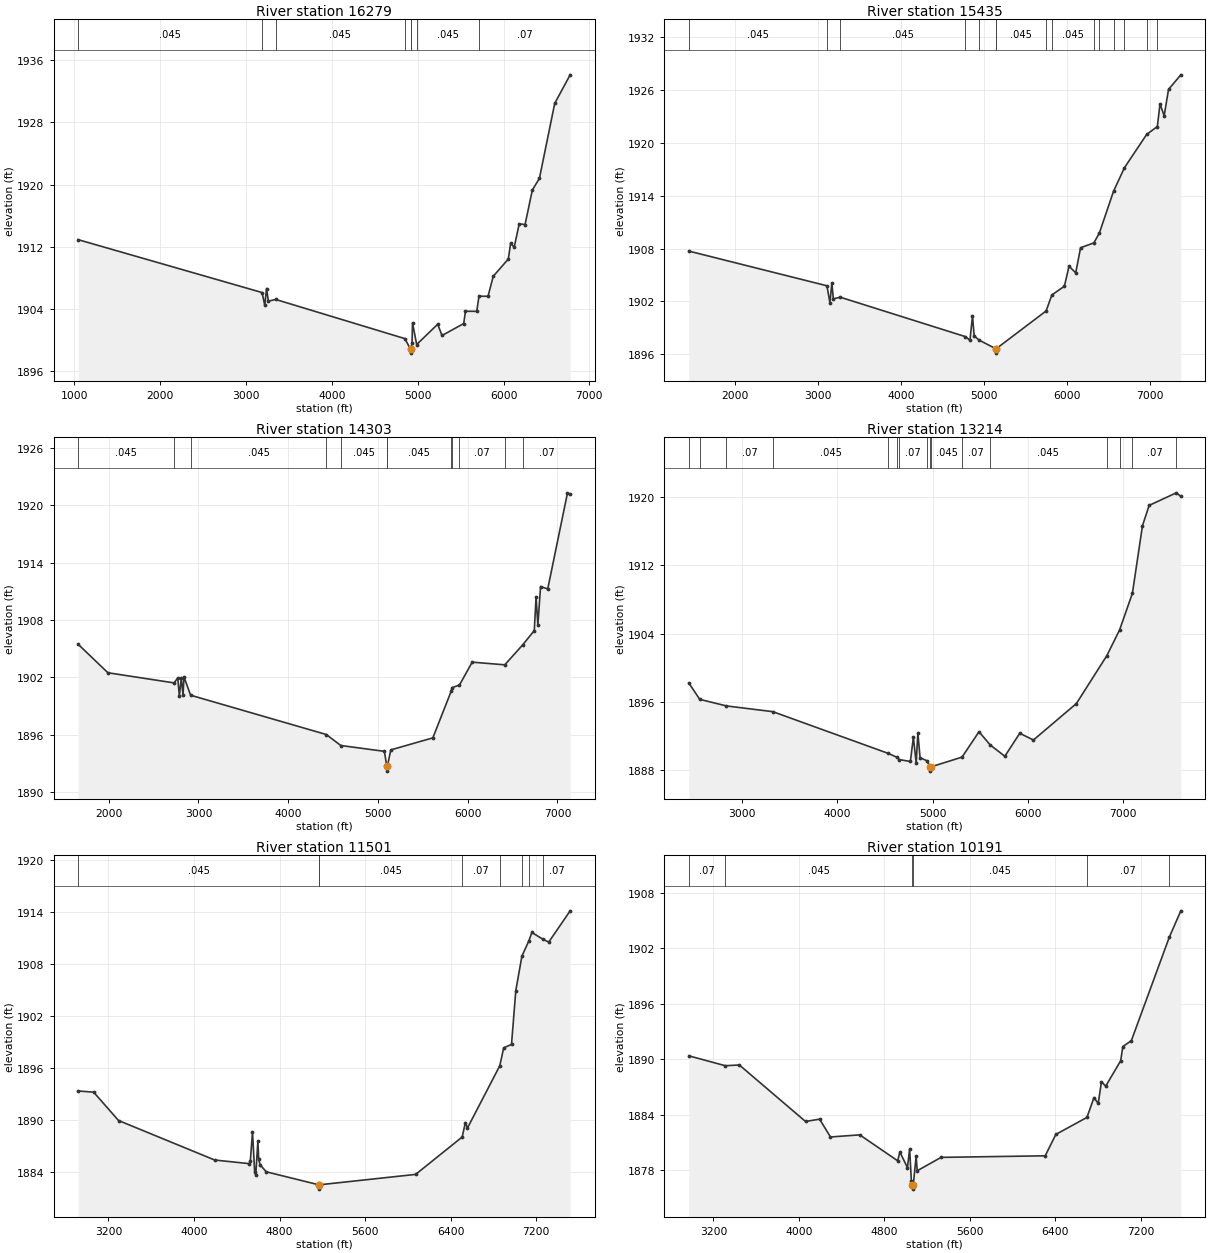
Type RM Length L Ch R = 1,16279,844,844,844
BEGIN DESCRIPTION:
Mapping XS 930301aa
END DESCRIPTION:
XS GIS Cut Line= 4
      1484089.78      6847889.04      1486909.21      6848562.65
      1489353.65      6848937.65      1489714.77      6848944.59
#Sta/Elev= 30
  1042.7 1912.90  3185.7 1906.09  3217.4 1904.45  3238.0 1906.61  3259.1 1904.98
  3344.7 1905.20  4849.5 1900.16  4916.2 1898.79  4916.5 1898.29  4921.0 1898.79
  4933.4 1899.61  4938.8 1902.19  4987.6 1899.40  5232.2 1902.01  5282.8 1900.56
  5535.7 1902.10  5555.9 1903.68  5687.5 1903.67  5713.5 1905.62  5819.0 1905.61
  5879.7 1908.19  6055.4 1910.40  6082.0 1912.44  6123.8 1911.92  6182.1 1914.93
  6250.5 1914.85  6334.9 1919.28  6417.7 1920.79  6595.9 1930.44  6775.7 1934.12
#Mann=8,-1,0
  1042.7   0.045       0  3185.7   0.035       0  3344.7   0.045       0
  4849.5   0.035       0  4916.2   0.045       0  4921.0   0.035       0
  4987.6   0.045       0  5713.5    0.07       0
Bank Sta=4916.2,4921
Exp/Cntr=0.3,0.1

Type RM Length L Ch R = 1,15435,1132,1132,1132
BEGIN DESCRIPTION:
Mapping XS 2d537dda
END DESCRIPTION:
XS GIS Cut Line= 4
      1484381.43      6848812.65      1486367.54      6849305.70
      1489166.15      6849736.26      1490214.72      6849639.04
#Sta/Elev= 30
  1445.3 1907.71  3110.2 1903.77  3146.2 1901.86  3169.7 1904.09  3187.5 1902.29
  3271.5 1902.47  4780.5 1897.99  4834.8 1897.58  4865.1 1900.36  4885.4 1898.07
  4948.6 1897.58  5145.9 1896.62  5146.3 1896.12  5151.0 1896.62  5752.5 1900.91
  5821.9 1902.73  5973.0 1903.72  6028.7 1905.99  6109.6 1905.24  6167.8 1908.09
  6327.8 1908.64  6394.1 1909.75  6565.4 1914.51  6696.8 1917.18  6964.6 1920.96
  7093.4 1921.86  7125.5 1924.43  7175.7 1923.08  7228.0 1926.07  7376.3 1927.73
#Mann=15,-1,0
  1445.3   0.045       0  3110.2   0.035       0  3271.5   0.045       0
  4780.5   0.035       0  4948.6   0.045       0  5145.9   0.045       0
  5151.0   0.045       0  5752.5    0.07       0  5821.9   0.045       0
  6327.8    0.07       0  6394.1   0.045       0  6565.4    0.07       0
  6696.8   0.045       0  6964.6    0.07       0  7093.4   0.045       0
Bank Sta=5145.9,5151
Exp/Cntr=0.3,0.1

Type RM Length L Ch R = 1,14303,1089,1089,1089
BEGIN DESCRIPTION:
Mapping XS d6301ecb
END DESCRIPTION:
XS GIS Cut Line= 3
      1484728.62      6849937.64      1489103.65      6850805.70
      1490124.52      6850826.54
#Sta/Elev= 30
  1659.8 1905.47  1991.5 1902.49  2728.2 1901.43  2769.4 1901.94  2787.7 1900.05
  2808.1 1901.92  2828.5 1900.20  2838.7 1902.06  2913.0 1900.14  4424.4 1896.03
  4586.2 1894.88  5071.4 1894.27  5099.0 1892.70  5099.5 1892.20  5104.9 1892.70
  5142.8 1894.42  5611.7 1895.68  5815.0 1900.54  5826.5 1900.93  5908.3 1901.21
  6049.9 1903.60  6413.0 1903.32  6610.9 1905.39  6741.6 1906.90  6761.6 1910.41
  6781.6 1907.47  6811.6 1911.51  6891.6 1911.26  7111.7 1921.31  7141.2 1921.14
#Mann=12,-1,0
  1659.8   0.045       0  2728.2   0.035       0  2913.0   0.045       0
  4424.4   0.035       0  4586.2   0.045       0  5099.0   0.045       0
  5104.9   0.045       0  5815.0    0.07       0  5826.5   0.045       0
  5908.3    0.07       0  6413.0   0.035       0  6610.9    0.07       0
Bank Sta=5099,5104.9
Exp/Cntr=0.3,0.1

Type RM Length L Ch R = 1,13214,1713,1713,1713
BEGIN DESCRIPTION:
Mapping XS 6425d64a
END DESCRIPTION:
XS GIS Cut Line= 3
      1485638.40      6851083.49      1490061.98      6851923.76
      1490727.48      6851902.96
#Sta/Elev= 30
  2438.2 1898.24  2553.0 1896.32  2833.9 1895.55  3320.2 1894.88  4534.9 1889.99
  4628.2 1889.52  4648.5 1889.27  4765.7 1889.05  4797.3 1891.89  4826.8 1888.87
  4844.5 1892.39  4867.5 1889.49  4936.1 1889.15  4976.3 1888.42  4976.8 1887.92
  4982.5 1888.42  5308.3 1889.56  5486.6 1892.53  5604.0 1890.99  5758.0 1889.66
  5914.7 1892.35  6058.4 1891.56  6509.7 1895.83  6827.8 1901.40  6963.4 1904.44
  7098.1 1908.73  7204.0 1916.65  7274.1 1919.02  7559.6 1920.49  7606.7 1920.08
#Mann=16,-1,0
  2438.2   0.035       0  2553.0   0.045       0  2833.9    0.07       0
  3320.2   0.045       0  4534.9    0.07       0  4628.2   0.045       0
  4648.5    0.07       0  4936.1   0.045       0  4976.3   0.045       0
  4982.5   0.045       0  5308.3    0.07       0  5604.0   0.045       0
  6827.8    0.07       0  6963.4   0.035       0  7098.1    0.07       0
  7559.6   0.045       0
Bank Sta=4976.3,4982.5
Exp/Cntr=0.3,0.1

Type RM Length L Ch R = 1,11501,1310,1310,1310
BEGIN DESCRIPTION:
Mapping XS 4eb33d2a
END DESCRIPTION:
XS GIS Cut Line= 3
      1486041.17      6852833.49      1489728.65      6853361.26
      1490601.87      6853298.89
#Sta/Elev= 30
  2916.9 1893.30  3062.2 1893.16  3294.5 1889.89  4193.6 1885.33  4516.9 1884.91
  4527.0 1885.22  4547.2 1888.54  4567.4 1884.00  4577.5 1883.61  4597.7 1887.51
  4605.1 1885.43  4617.9 1884.79  4675.7 1883.97  5167.1 1882.47  5167.6 1881.97
  5173.4 1882.47  6072.6 1883.67  6508.3 1887.99  6537.3 1889.65  6557.5 1889.03
  6859.2 1896.20  6896.1 1898.28  6969.1 1898.67  7009.2 1904.88  7066.2 1908.85
  7130.7 1910.61  7159.6 1911.59  7261.5 1910.82  7317.2 1910.48  7517.4 1914.09
#Mann=8,-1,0
  2916.9   0.045       0  5167.1   0.045       0  5173.4   0.045       0
  6508.3    0.07       0  6859.2   0.035       0  7066.2    0.07       0
  7130.7   0.035       0  7261.5    0.07       0
Bank Sta=5167.1,5173.4
Exp/Cntr=0.3,0.1

Type RM Length L Ch R = 1,10191,1392,1392,1392
BEGIN DESCRIPTION:
Mapping XS 5c233ce0
END DESCRIPTION:
XS GIS Cut Line= 3
      1486318.93      6853729.32      1490027.26      6854368.20
      1490867.57      6854361.26
#Sta/Elev= 30
  2969.9 1890.37  3311.6 1889.30  3442.8 1889.38  4061.8 1883.26  4193.7 1883.51
  4295.2 1881.58  4569.2 1881.81  4924.3 1879.00  4944.6 1879.95  5015.7 1878.26
  5036.0 1880.29  5052.1 1876.83  5062.4 1876.43  5062.9 1875.93  5070.5 1876.43
  5096.9 1879.51  5106.9 1877.92  5330.2 1879.37  6304.4 1879.54  6404.3 1881.86
  6695.0 1883.70  6760.6 1885.84  6800.6 1885.21  6830.6 1887.56  6870.6 1887.09
  7010.6 1889.84  7030.6 1891.37  7110.6 1892.02  7466.0 1903.24  7573.2 1906.08
#Mann=6,-1,0
  2969.9    0.07       0  3311.6   0.045       0  5062.4   0.045       0
  5070.5   0.045       0  6695.0    0.07       0  7466.0   0.045       0
Bank Sta=5062.4,5070.5
Exp/Cntr=0.3,0.1

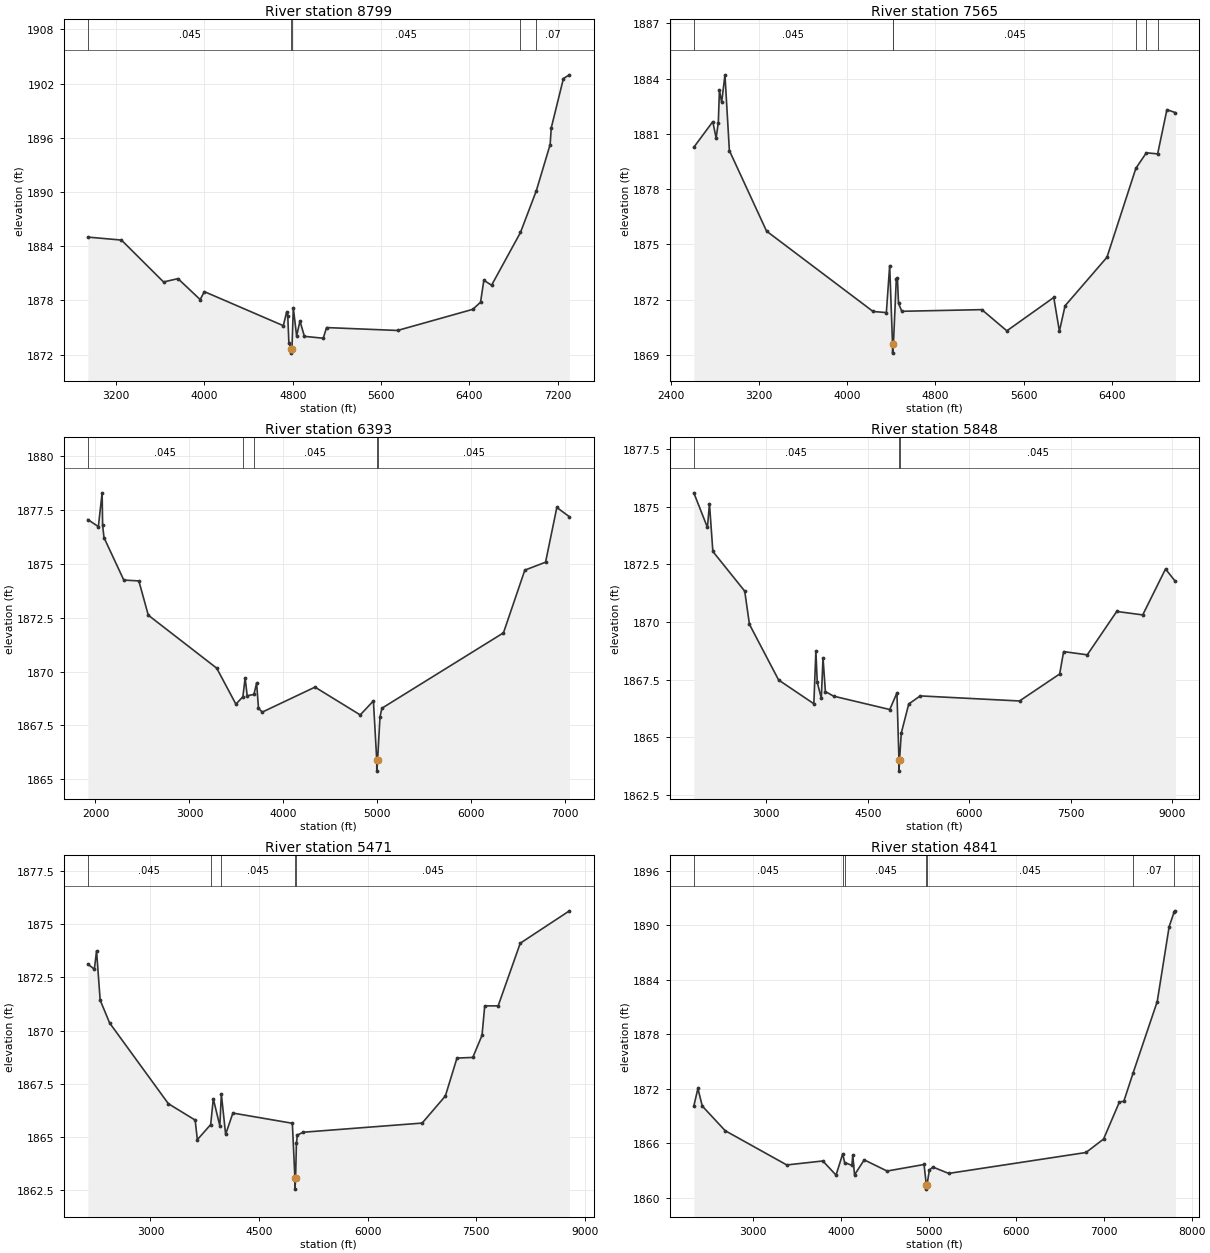
Type RM Length L Ch R = 1,8799,1234,1234,1234
BEGIN DESCRIPTION:
Mapping XS 25e64469
END DESCRIPTION:
XS GIS Cut Line= 3
      1486652.30      6855048.76      1489756.43      6855326.54
      1490999.49      6855284.87
#Sta/Elev= 30
  2944.9 1885.01  3248.8 1884.68  3630.3 1880.04  3760.9 1880.41  3961.7 1878.09
  3999.5 1878.97  4714.6 1875.20  4744.8 1876.72  4754.8 1876.30  4764.8 1873.33
  4784.6 1872.66  4785.1 1872.16  4792.9 1872.66  4805.0 1877.19  4835.1 1874.05
  4865.2 1875.72  4905.4 1874.02  5076.1 1873.81  5106.2 1874.99  5748.8 1874.67
  6430.2 1877.01  6500.3 1877.80  6530.3 1880.23  6600.3 1879.68  6861.7 1885.52
  7005.0 1890.13  7130.6 1895.26  7140.6 1897.11  7250.7 1902.57  7305.2 1902.98
#Mann=5,-1,0
  2944.9   0.045       0  4784.6   0.045       0  4792.9   0.045       0
  6861.7   0.035       0  7005.0    0.07       0
Bank Sta=4784.6,4792.9
Exp/Cntr=0.3,0.1

Type RM Length L Ch R = 1,7565,1172,1172,1172
BEGIN DESCRIPTION:
Mapping XS b58f73d3
END DESCRIPTION:
XS GIS Cut Line= 3
      1486763.34      6856055.70      1489832.82      6856229.32
      1491089.79      6855944.59
#Sta/Elev= 30
  2610.3 1880.27  2782.2 1881.66  2812.3 1880.77  2832.3 1881.61  2842.3 1883.37
  2862.4 1882.71  2892.4 1884.20  2932.5 1880.09  3269.4 1875.72  4234.5 1871.36
  4354.7 1871.30  4384.8 1873.85  4410.6 1869.60  4411.1 1869.10  4419.0 1869.60
  4444.9 1873.14  4454.9 1873.18  4464.9 1871.80  4495.0 1871.37  5219.9 1871.46
  5446.5 1870.31  5871.5 1872.12  5922.7 1870.29  5974.0 1871.67  6353.4 1874.30
  6615.6 1879.13  6710.5 1879.97  6812.7 1879.91  6896.8 1882.31  6973.5 1882.15
#Mann=6,-1,0
  2610.3   0.045       0  4410.6   0.045       0  4419.0   0.045       0
  6615.6    0.07       0  6710.5   0.035       0  6812.7    0.07       0
Bank Sta=4410.6,4419
Exp/Cntr=0.3,0.1

Type RM Length L Ch R = 1,6393,545,545,545
BEGIN DESCRIPTION:
Mapping XS 38d88aa7
END DESCRIPTION:
XS GIS Cut Line= 3
      1486853.63      6856562.65      1490853.65      6856826.54
      1491720.83      6856125.85
#Sta/Elev= 30
  1919.3 1877.06  2030.9 1876.73  2071.0 1878.30  2076.3 1876.79  2091.0 1876.22
  2301.5 1874.25  2461.8 1874.21  2562.1 1872.62  3290.2 1870.16  3494.1 1868.49
  3568.5 1868.83  3592.5 1869.71  3614.3 1868.88  3686.0 1868.94  3714.6 1869.47
  3734.6 1868.30  3774.7 1868.12  4335.9 1869.28  4817.0 1867.99  4957.3 1868.64
  4992.9 1865.88  4993.4 1865.38  5001.7 1865.88  5027.4 1867.90  5047.5 1868.30
  6341.0 1871.80  6568.1 1874.71  6788.8 1875.08  6908.8 1877.62  7042.9 1877.19
#Mann=5,-1,0
  1919.3   0.045       0  3568.5    0.07       0  3686.0   0.045       0
  4992.9   0.045       0  5001.7   0.045       0
Bank Sta=4992.9,5001.7
Exp/Cntr=0.3,0.1

Type RM Length L Ch R = 1,5848,377,377,377
BEGIN DESCRIPTION:
Mapping XS ac06d9a0
END DESCRIPTION:
XS GIS Cut Line= 3
      1486784.16      6857118.20      1491457.82      6857375.15
      1493687.03      6856395.96
#Sta/Elev= 30
  1928.5 1875.60  2129.6 1874.10  2159.7 1875.13  2209.8 1873.06  2680.5 1871.34
  2750.6 1869.90  3181.2 1867.49  3702.0 1866.46  3732.1 1868.75  3752.1 1867.39
  3812.2 1866.70  3837.4 1868.45  3872.3 1866.99  3992.5 1866.79  4823.7 1866.21
  4929.7 1866.93  4959.5 1864.04  4960.0 1863.54  4968.4 1864.04  4994.0 1865.19
  5104.1 1866.45  5274.4 1866.80  6740.8 1866.58  7334.1 1867.75  7392.5 1868.72
  7742.0 1868.58  8177.3 1870.46  8561.2 1870.31  8898.3 1872.30  9044.0 1871.76
#Mann=3,-1,0
  1928.5   0.045       0  4959.5   0.045       0  4968.4   0.045       0
Bank Sta=4959.5,4968.4
Exp/Cntr=0.3,0.1

Type RM Length L Ch R = 1,5471,630,630,630
BEGIN DESCRIPTION:
Mapping XS 1de7b0e2
END DESCRIPTION:
XS GIS Cut Line= 3
      1486895.35      6857451.54      1492180.04      6857784.87
      1493470.90      6858208.22
#Sta/Elev= 30
  2135.1 1873.12  2224.9 1872.88  2255.0 1873.74  2305.1 1871.43  2435.3 1870.36
  3247.0 1866.57  3617.7 1865.80  3647.8 1864.88  3832.0 1865.59  3868.2 1866.80
  3958.4 1865.53  3979.3 1867.02  4038.5 1865.13  4138.7 1866.13  4960.4 1865.65
  4996.0 1863.06  4996.5 1862.56  5004.9 1863.06  5016.6 1864.72  5030.5 1865.10
  5110.7 1865.23  6753.9 1865.66  7074.5 1866.93  7234.9 1868.71  7453.8 1868.74
  7581.2 1869.78  7618.3 1871.16  7803.9 1871.16  8109.1 1874.10  8788.8 1875.62
#Mann=5,-1,0
  2135.1   0.045       0  3832.0    0.07       0  3979.3   0.045       0
  4996.0   0.045       0  5004.9   0.045       0
Bank Sta=4996,5004.9
Exp/Cntr=0.3,0.1

Type RM Length L Ch R = 1,4841,759,759,759
BEGIN DESCRIPTION:
Mapping XS 37adc012
END DESCRIPTION:
XS GIS Cut Line= 3
      1486978.68      6857965.43      1492082.82      6858402.93
      1492416.17      6858562.66
#Sta/Elev= 30
  2322.1 1870.11  2368.6 1872.05  2418.8 1870.11  2679.7 1867.40  3382.3 1863.63
  3793.8 1864.07  3944.3 1862.51  4020.4 1864.86  4042.1 1863.89  4125.0 1863.59
  4135.0 1864.73  4155.1 1862.54  4265.5 1864.19  4526.5 1862.96  4948.0 1863.68
  4973.6 1861.47  4974.1 1860.97  4982.6 1861.47  5008.2 1863.06  5048.4 1863.40
  5229.0 1862.70  6794.8 1865.00  6995.5 1866.48  7176.2 1870.56  7226.3 1870.63
  7333.7 1873.79  7607.6 1881.61  7743.6 1889.86  7801.8 1891.50  7814.6 1891.59
#Mann=7,-1,0
  2322.1   0.045       0  4020.4    0.07       0  4042.1   0.045       0
  4973.6   0.045       0  4982.6   0.045       0  7333.7    0.07       0
  7801.8   0.035       0
Bank Sta=4973.6,4982.6
Exp/Cntr=0.3,0.1

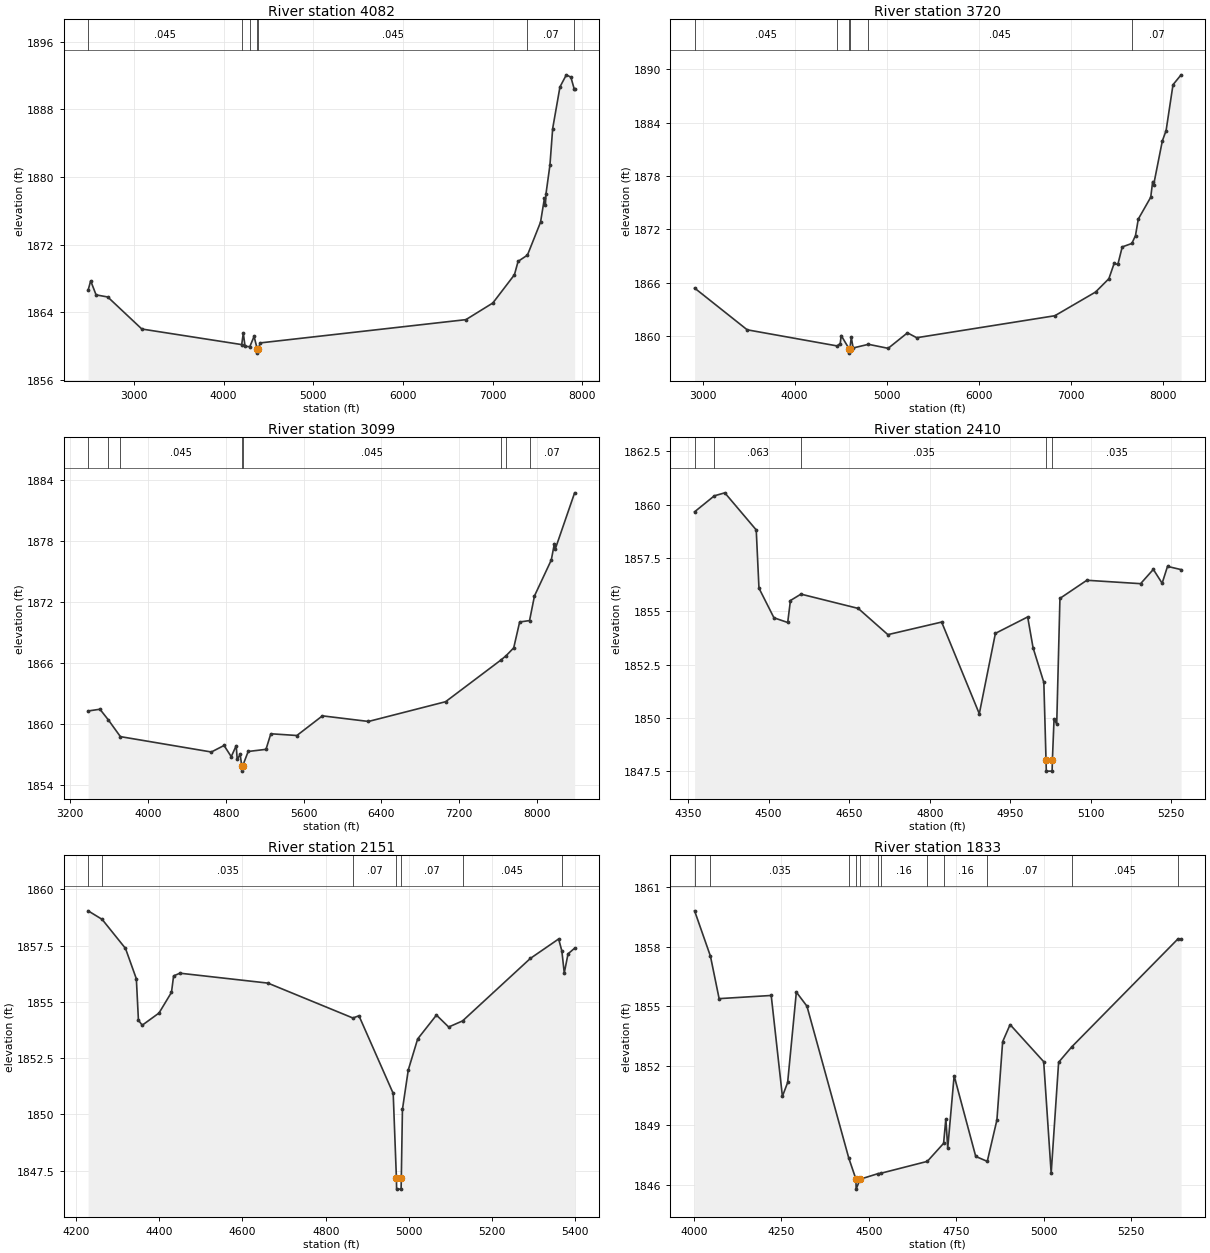
Type RM Length L Ch R = 1,4082,362,362,362
BEGIN DESCRIPTION:
Mapping XS c86cbc19
END DESCRIPTION:
XS GIS Cut Line= 3
      1487006.44      6858812.65      1491721.71      6858937.65
      1492416.12      6858819.60
#Sta/Elev= 30
  2491.0 1866.62  2519.6 1867.73  2579.6 1866.07  2709.6 1865.82  3089.8 1862.03
  4202.4 1860.19  4220.2 1861.54  4240.2 1859.97  4292.9 1859.95  4340.2 1861.15
  4375.7 1859.68  4376.2 1859.18  4384.7 1859.68  4410.2 1860.39  6701.0 1863.14
  7001.1 1865.11  7241.7 1868.45  7282.3 1870.03  7386.5 1870.77  7532.4 1874.66
  7576.4 1877.53  7586.6 1876.69  7592.7 1877.98  7637.3 1881.42  7667.7 1885.74
  7748.9 1890.66  7819.9 1892.09  7870.6 1891.81  7909.3 1890.36  7912.3 1890.37
#Mann=7,-1,0
  2491.0   0.045       0  4202.4    0.07       0  4292.9   0.045       0
  4375.7   0.045       0  4384.7   0.045       0  7386.5    0.07       0
  7909.3   0.035       0
Bank Sta=4375.7,4384.7
Exp/Cntr=0.3,0.1

Type RM Length L Ch R = 1,3720,621,621,621
BEGIN DESCRIPTION:
Mapping XS 34e12e63
END DESCRIPTION:
XS GIS Cut Line= 4
      1487173.94      6859160.74      1491366.67      6859113.86
      1492017.71      6859025.32      1492429.17      6858895.11
#Sta/Elev= 30
  2913.8 1865.41  3484.9 1860.72  4461.0 1858.91  4495.0 1859.17  4505.3 1860.08
  4590.4 1858.60  4590.9 1858.10  4599.5 1858.60  4615.0 1859.87  4635.0 1858.68
  4801.3 1859.09  5015.0 1858.64  5225.0 1860.38  5325.0 1859.83  6825.1 1862.30
  7266.6 1864.96  7411.5 1866.46  7468.4 1868.17  7508.8 1868.06  7556.3 1870.03
  7661.0 1870.42  7700.5 1871.31  7730.8 1873.16  7865.8 1875.61  7886.9 1877.37
  7897.3 1877.00  7991.7 1881.93  8032.6 1883.10  8107.7 1888.25  8195.4 1889.36
#Mann=6,-1,0
  2913.8   0.045       0  4461.0    0.07       0  4590.4   0.045       0
  4599.5    0.07       0  4801.3   0.045       0  7661.0    0.07       0
Bank Sta=4590.4,4599.5
Exp/Cntr=0.3,0.1

Type RM Length L Ch R = 1,3099,689,689,689
BEGIN DESCRIPTION:
Mapping XS 51de7588
END DESCRIPTION:
XS GIS Cut Line= 4
      1487476.09      6859994.06      1490465.63      6859358.66
      1491658.34      6859155.53      1492381.14      6859025.53
#Sta/Elev= 30
  3385.5 1861.29  3507.1 1861.46  3592.9 1860.42  3717.3 1858.77  4652.1 1857.26
  4782.7 1857.90  4856.6 1856.80  4907.7 1857.88  4917.9 1856.53  4948.6 1857.03
  4964.5 1855.88  4965.0 1855.38  4973.6 1855.88  5030.7 1857.31  5213.8 1857.52
  5263.4 1859.05  5531.3 1858.88  5793.8 1860.81  6267.4 1860.26  7060.0 1862.20
  7627.9 1866.29  7682.0 1866.72  7760.1 1867.49  7821.0 1870.03  7922.8 1870.17
  7973.4 1872.59  8146.2 1876.12  8178.1 1877.73  8186.8 1877.19  8386.1 1882.72
#Mann=8,-1,0
  3385.5   0.045       0  3592.9    0.07       0  3717.3   0.045       0
  4964.5   0.045       0  4973.6   0.045       0  7627.9    0.07       0
  7682.0   0.045       0  7922.8    0.07       0
Bank Sta=4964.5,4973.6
Exp/Cntr=0.3,0.1

Type RM Length L Ch R = 1,2410,259,259,259
BEGIN DESCRIPTION:
Mapping XS f7bd91a7
END DESCRIPTION:
XS GIS Cut Line= 4
      1488289.61      6860202.08      1488563.06      6860251.56
      1489138.58      6860282.81      1489190.32      6860282.81
#Sta/Elev= 30
  4362.1 1859.67  4398.9 1860.42  4418.4 1860.56  4476.9 1858.82  4482.0 1856.09
  4509.9 1854.70  4535.5 1854.48  4540.6 1855.51  4560.2 1855.81  4666.8 1855.14
  4722.1 1853.91  4822.2 1854.50  4892.3 1850.20  4922.3 1853.97  4982.4 1854.74
  4992.4 1853.30  5012.5 1851.67  5016.6 1848.01  5017.1 1847.51  5027.9 1847.51
  5028.4 1848.01  5031.5 1849.94  5036.5 1849.72  5042.5 1855.61  5092.6 1856.46
  5192.7 1856.30  5216.4 1856.97  5232.8 1856.32  5242.8 1857.11  5268.1 1856.96
#Mann=5,-1,0
  4362.1   0.094       0  4398.9   0.063       0  4560.2   0.035       0
  5016.6   0.035       0  5028.4   0.035       0
Bank Sta=5016.6,5028.4
Exp/Cntr=0.3,0.1

Type RM Length L Ch R = 1,2151,318,318,318
BEGIN DESCRIPTION:
Mapping XS 77cffebb
END DESCRIPTION:
XS GIS Cut Line= 3
      1488005.79      6860269.79      1488531.81      6860329.68
      1489107.38      6860608.35
#Sta/Elev= 30
  4229.2 1859.04  4262.9 1858.66  4319.0 1857.37  4345.1 1856.02  4350.1 1854.18
  4359.2 1853.96  4399.5 1854.50  4429.5 1855.42  4434.6 1856.15  4449.8 1856.27
  4661.2 1855.83  4865.4 1854.28  4879.9 1854.38  4962.2 1850.93  4969.9 1847.18
  4970.4 1846.68  4981.2 1846.68  4981.7 1847.18  4984.4 1850.22  4998.4 1851.97
  5021.0 1853.35  5066.1 1854.41  5095.5 1853.88  5128.8 1854.15  5292.0 1856.93
  5359.7 1857.79  5367.4 1857.26  5373.2 1856.28  5382.3 1857.13  5398.1 1857.38
#Mann=7,-1,0
  4229.2   0.063       0  4262.9   0.035       0  4865.4    0.07       0
  4969.9    0.07       0  4981.7    0.07       0  5128.8   0.045       0
  5367.4   0.035       0
Bank Sta=4969.9,4981.7
Exp/Cntr=0.3,0.1

Type RM Length L Ch R = 1,1833,403,403,403
BEGIN DESCRIPTION:
Mapping XS f81667fd
END DESCRIPTION:
XS GIS Cut Line= 3
      1487729.70      6860340.09      1488857.33      6860761.97
      1489039.66      6860806.25
#Sta/Elev= 30
  4001.4 1859.81  4046.8 1857.52  4071.6 1855.38  4220.6 1855.54  4252.6 1850.45
  4267.6 1851.15  4292.5 1855.71  4322.8 1855.00  4442.4 1847.34  4463.0 1846.27
  4463.5 1845.77  4474.8 1846.27  4525.8 1846.55  4534.1 1846.57  4667.1 1847.17
  4713.7 1848.08  4720.1 1849.32  4725.5 1847.84  4743.8 1851.49  4805.6 1847.42
  4838.6 1847.17  4866.2 1849.26  4882.6 1853.21  4903.9 1854.07  5000.0 1852.20
  5021.4 1846.57  5042.7 1852.17  5080.4 1852.95  5384.4 1858.40  5393.0 1858.39
#Mann=12,-1,0
  4001.4   0.094       0  4046.8   0.035       0  4442.4    0.16       0
  4463.0    0.07       0  4474.8    0.16       0  4525.8    0.07       0
  4534.1    0.16       0  4667.1    0.07       0  4713.7    0.16       0
  4838.6    0.07       0  5080.4   0.045       0  5384.4   0.035       0
Bank Sta=4463,4474.8
Exp/Cntr=0.3,0.1

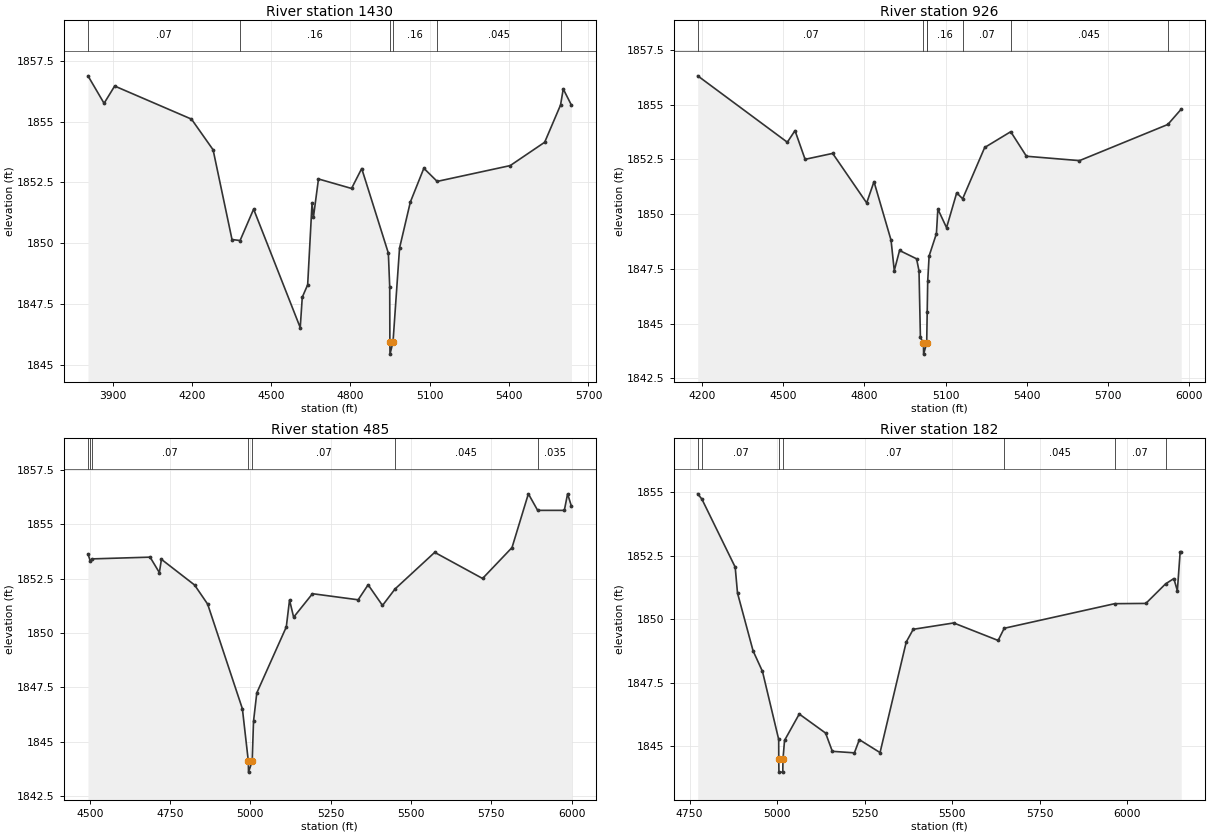
Type RM Length L Ch R = 1,1430,504,504,504
BEGIN DESCRIPTION:
Mapping XS 714b46ba
END DESCRIPTION:
XS GIS Cut Line= 4
      1487214.11      6860772.39      1487589.10      6860785.41
      1488763.58      6861032.81      1489016.15      6861051.03
#Sta/Elev= 30
  3807.1 1856.88  3868.0 1855.75  3908.1 1856.46  4198.6 1855.10  4280.3 1853.84
  4351.9 1850.15  4382.4 1850.11  4433.6 1851.40  4609.9 1846.53  4617.6 1847.78
  4638.0 1848.29  4654.6 1851.65  4659.7 1851.06  4678.9 1852.64  4804.0 1852.25
  4842.4 1853.07  4943.2 1849.59  4948.3 1848.21  4948.9 1845.94  4949.4 1845.44
  4960.8 1845.94  4985.5 1849.80  5026.3 1851.69  5077.4 1853.08  5127.8 1852.54
  5404.0 1853.19  5534.4 1854.15  5594.4 1855.68  5604.6 1856.34  5635.8 1855.67
#Mann=6,-1,0
  3807.1    0.07       0  4382.4    0.16       0  4948.9    0.07       0
  4960.8    0.16       0  5127.8   0.045       0  5594.4   0.035       0
Bank Sta=4948.9,4960.8
Exp/Cntr=0.3,0.1

Type RM Length L Ch R = 1,926,441,441,441
BEGIN DESCRIPTION:
Mapping XS b7b15b08
END DESCRIPTION:
XS GIS Cut Line= 4
      1487247.92      6860863.51      1487690.67      6861118.74
      1488427.65      6861353.12      1488931.39      6861345.33
#Sta/Elev= 30
  4183.5 1856.31  4514.9 1853.28  4543.3 1853.81  4580.6 1852.50  4682.6 1852.77
  4808.4 1850.51  4835.4 1851.48  4898.5 1848.81  4910.4 1847.42  4930.0 1848.34
  4992.9 1847.96  5001.9 1847.41  5007.1 1844.37  5018.4 1844.11  5018.9 1843.61
  5030.3 1844.11  5032.2 1845.53  5034.1 1846.94  5039.3 1848.09  5066.3 1849.11
  5071.6 1850.23  5103.8 1849.38  5141.3 1850.97  5163.3 1850.70  5244.8 1853.04
  5341.1 1853.76  5399.2 1852.64  5595.3 1852.44  5922.1 1854.09  5971.7 1854.79
#Mann=7,-1,0
  4183.5    0.07       0  5018.4    0.07       0  5030.3    0.07       0
  5032.2    0.16       0  5163.3    0.07       0  5341.1   0.045       0
  5922.1   0.035       0
Bank Sta=5018.4,5030.3
Exp/Cntr=0.3,0.1

Type RM Length L Ch R = 1,485,303,303,303
BEGIN DESCRIPTION:
Mapping XS 057a337b
END DESCRIPTION:
XS GIS Cut Line= 4
      1487409.00      6861372.58      1487606.46      6861528.81
      1488248.82      6861654.68      1488836.93      6861544.00
#Sta/Elev= 30
  4494.6 1853.63  4502.2 1853.30  4507.8 1853.41  4687.9 1853.49  4716.8 1852.78
  4723.2 1853.39  4826.4 1852.21  4867.1 1851.33  4975.2 1846.52  4993.7 1844.11
  4994.2 1843.61  5005.7 1844.11  5009.8 1845.94  5020.0 1847.25  5111.8 1850.28
  5121.9 1851.52  5134.7 1850.73  5193.3 1851.81  5335.5 1851.53  5366.5 1852.22
  5411.2 1851.27  5450.4 1852.03  5573.7 1853.71  5722.7 1852.51  5814.3 1853.93
  5865.2 1856.40  5894.1 1855.64  5977.1 1855.64  5987.3 1856.40  5999.4 1855.82
#Mann=7,-1,0
  4494.6    0.07       0  4502.2   0.045       0  4507.8    0.07       0
  4993.7    0.07       0  5005.7    0.07       0  5450.4   0.045       0
  5894.1   0.035       0
Bank Sta=4993.7,5005.7
Exp/Cntr=0.3,0.1

Type RM Length L Ch R = 1,182,0,0,0
BEGIN DESCRIPTION:
NC Unknown Stream 58 1.0
END DESCRIPTION:
XS GIS Cut Line= 4
      1487576.07      6861654.67      1487643.35      6861802.25
      1488355.16      6862030.11      1488826.10      6862038.79
#Sta/Elev= 30
  4773.3 1854.94  4785.3 1854.73  4880.3 1852.05  4886.9 1851.03  4931.4 1848.75
  4958.2 1847.94  5004.5 1845.26  5004.7 1844.47  5005.2 1843.97  5016.2 1843.97
  5016.7 1844.47  5021.2 1845.22  5063.2 1846.26  5138.4 1845.51  5157.7 1844.79
  5220.7 1844.73  5234.8 1845.25  5293.9 1844.74  5368.7 1849.10  5388.7 1849.60
  5504.2 1849.85  5631.1 1849.16  5648.4 1849.64  5963.9 1850.61  6052.8 1850.62
  6109.1 1851.39  6132.8 1851.60  6142.8 1851.12  6150.8 1852.65  6153.9 1852.65
#Mann=7,-1,0
  4773.3   0.045       0  4785.3    0.07       0  5004.7    0.07       0
  5016.7    0.07       0  5648.4   0.045       0  5963.9    0.07       0
  6109.1   0.035       0
Bank Sta=5004.7,5016.7
Exp/Cntr=0.3,0.1

Chan Stop Cuts=-1