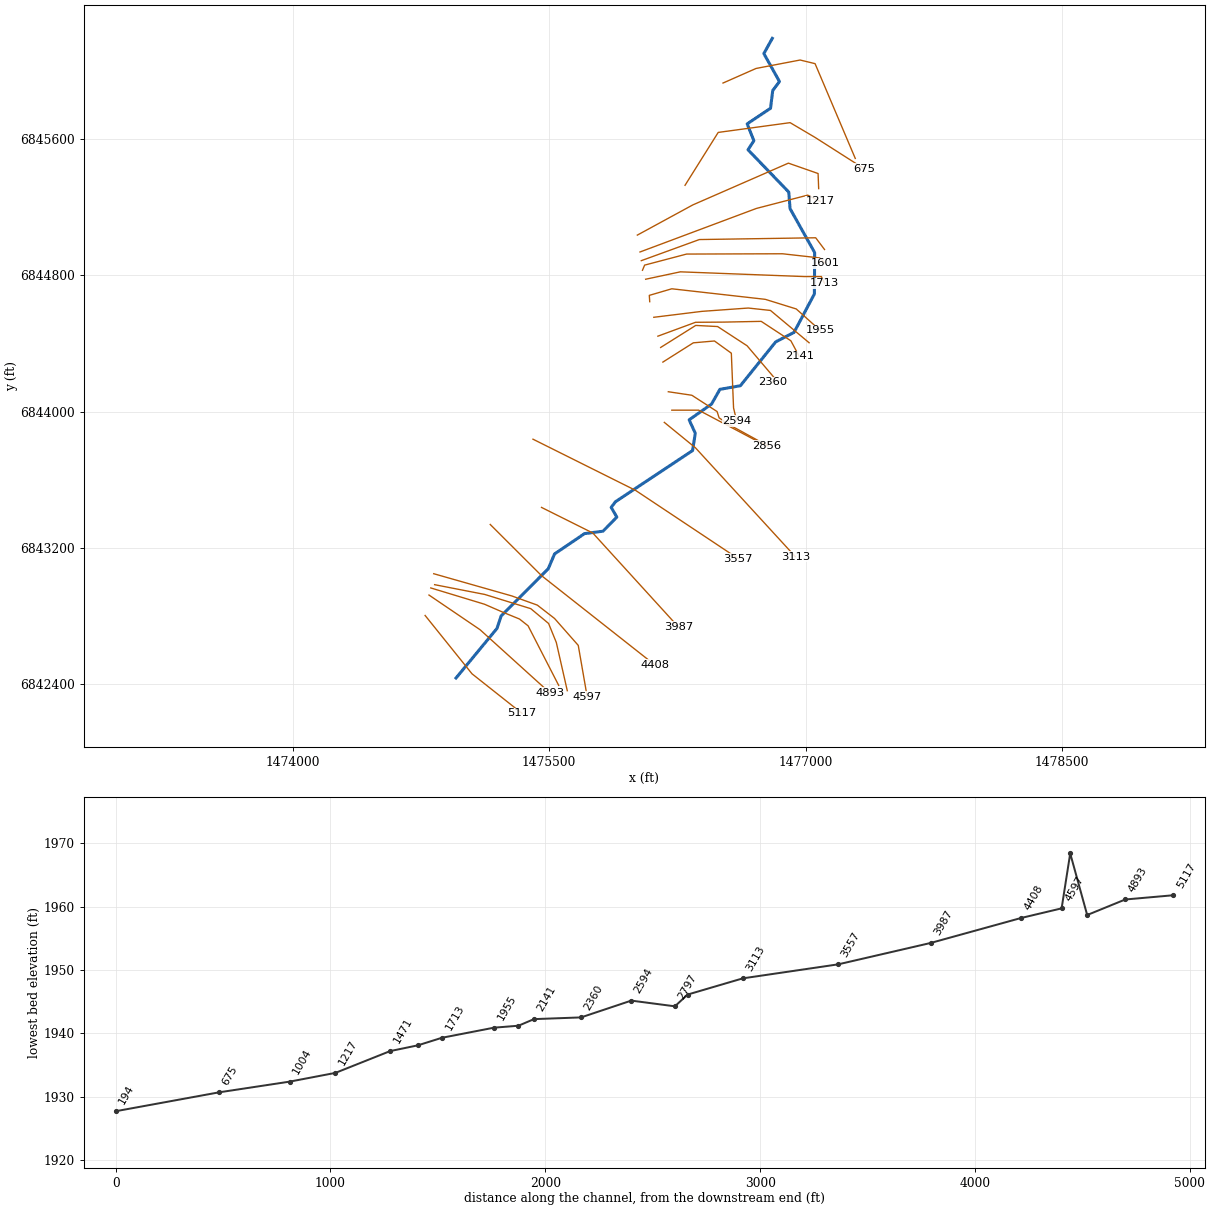
--- NC Unknown Stream 61.prj (project) ---

Proj Title=NC Unknown Stream 61 Base Level Engineering
Current Plan=p01
Default Exp/Contr=0.3,0.1
English Units
Geom File=g01
Flow File=f01
Plan File=p01
Y Axis Title=Elevation
X Axis Title(PF)=Main Channel Distance
X Axis Title(XS)=Station
BEGIN DESCRIPTION:
NC Unknown Stream 61
END DESCRIPTION:
DSS Export Rating Curves= 0
DSS Export Rating Curve Sorted= 0
DSS Export Volume Flow Curves= 0
DXF OffsetX= 0
DXF OffsetY= 0
DXF ScaleX= 1
DXF ScaleY= 10

--- NC Unknown Stream 61.p01 (plan) ---

Plan Title=Multiple Run
Short Identifier=Multiple
Geom File=g01
Flow File=f01
Subcritical Flow
K Sum by GR= 0
Std Step Tol= 0.01
Critical Tol= 0.01
Num of Std Step Trials= 20
Max Error Tol= 0.3
Flow Tol Ratio= 0.001
Split Flow NTrial= 30
Split Flow Tol= 0.02
Split Flow Ratio= 0.02
Log Output Level= 0
Friction Slope Method= 1
Unsteady Friction Slope Method= 2
Unsteady Bridges Friction Slope Method= 1
Parabolic Critical Depth
Global Vel Dist=  1 , 1 , 1
Global Log Level= 0
CheckData=True
Encroach Param= -1, 0, 0, 0
BEGIN DESCRIPTION:
Multiple Run
END DESCRIPTION:

--- NC Unknown Stream 61.f01 (steady flow) ---

Flow Title=Multiple
Program Version=4.10
Number of Profiles= 7
Profile Names=10-year,25-year,50-year,1pct_min,100-year,1pct_plu,500-year
River Rch & RM=NC Unknown Strea,Reach-1         ,5117
     470     696     896     575    1147    2289    1901
River Rch & RM=NC Unknown Strea,Reach-1         ,3113
     384     556     704     444     886    1768    1419
Boundary for River Rch & Prof#=NC Unknown Strea,Reach-1         , 1
Up Type= 0
Dn Type= 3
Dn Slope=0.07
Boundary for River Rch & Prof#=NC Unknown Strea,Reach-1         , 2
Up Type= 0
Dn Type= 3
Dn Slope=0.07
Boundary for River Rch & Prof#=NC Unknown Strea,Reach-1         , 3
Up Type= 0
Dn Type= 3
Dn Slope=0.07
Boundary for River Rch & Prof#=NC Unknown Strea,Reach-1         , 4
Up Type= 0
Dn Type= 3
Dn Slope=0.07
Boundary for River Rch & Prof#=NC Unknown Strea,Reach-1         , 5
Up Type= 0
Dn Type= 3
Dn Slope=0.07
Boundary for River Rch & Prof#=NC Unknown Strea,Reach-1         , 6
Up Type= 0
Dn Type= 3
Dn Slope=0.07
Boundary for River Rch & Prof#=NC Unknown Strea,Reach-1         , 7
Up Type= 0
Dn Type= 3
Dn Slope=0.07
DSS Import GetInterval= 0
DSS Import GetPeak= 0
DSS Import FillOption= 0

--- NC Unknown Stream 61.g01 (geometry) ---

Geom Title=Existing Conditions

River Reach=NC Unknown Strea,Reach-1
Reach XY= 30
      1474955.00      6842438.00      1475194.22      6842728.32
      1475218.63      6842801.21      1475494.21      6843078.34
      1475531.16      6843165.14      1475706.50      6843284.37
      1475814.83      6843298.52      1475895.70      6843381.32
      1475862.47      6843438.21      1475887.47      6843471.35
      1476338.61      6843771.21      1476354.48      6843872.78
      1476318.52      6843951.41      1476449.36      6844043.65
      1476498.56      6844130.21      1476618.30      6844151.40
      1476824.77      6844408.41      1476932.14      6844464.16
      1477051.25      6844689.55      1477052.76      6844932.07
      1476908.83      6845189.59      1476901.39      6845286.50
      1476662.99      6845534.66      1476697.16      6845587.91
      1476658.07      6845686.57      1476794.61      6845777.90
      1476807.56      6845882.10      1476846.95      6845934.71
      1476755.66      6846098.62      1476805.00      6846188.00

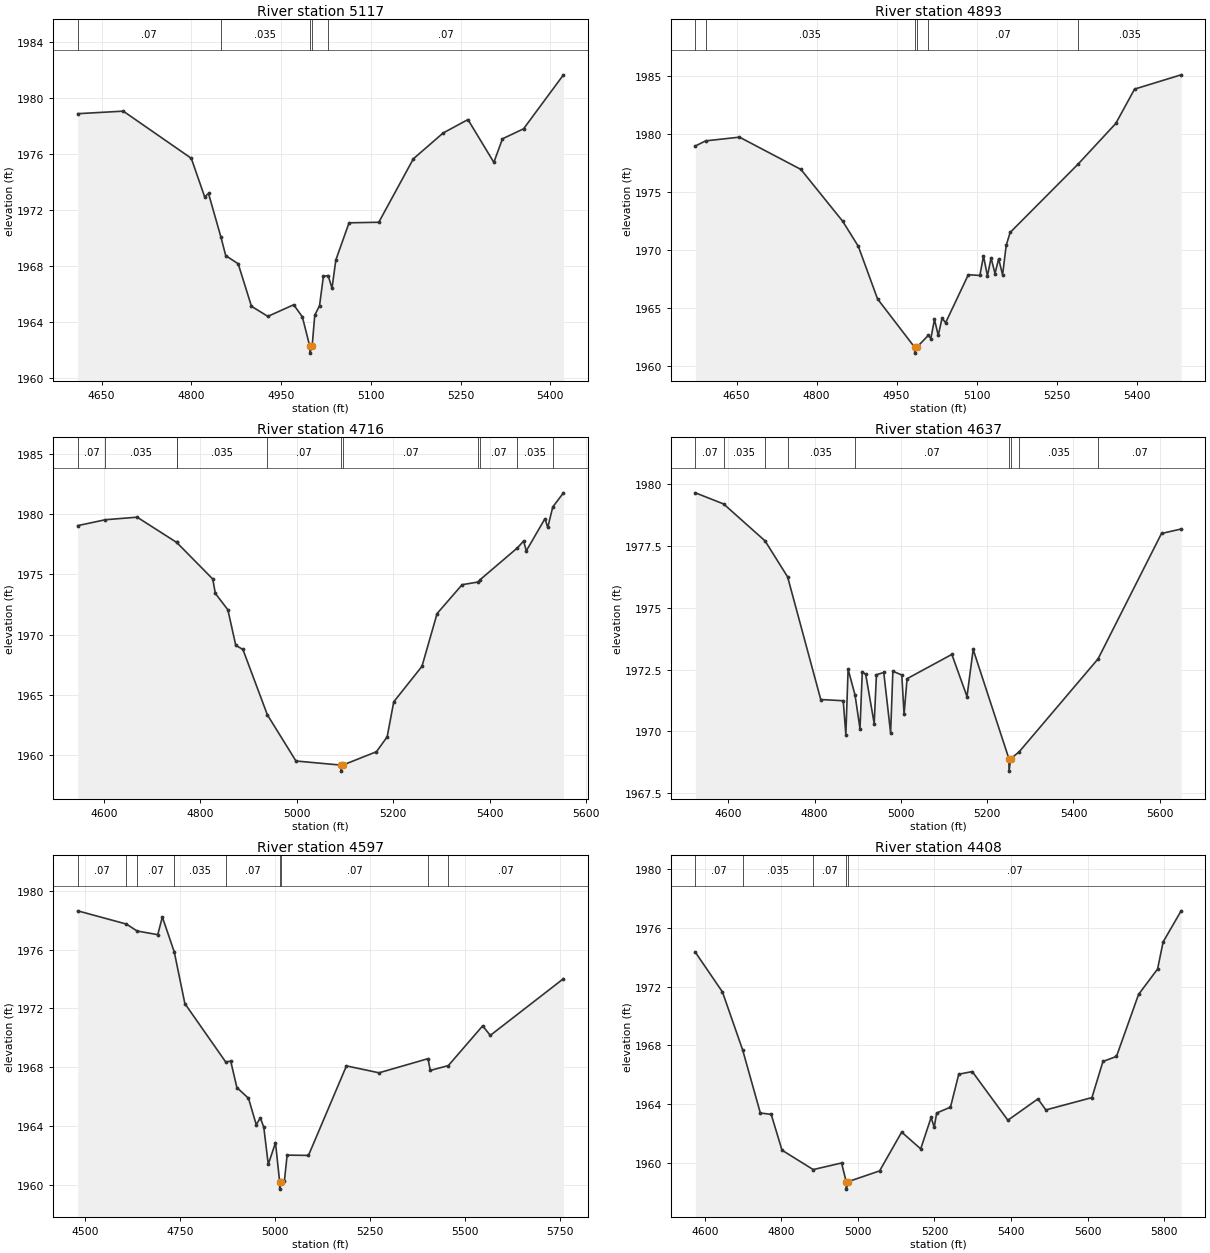
Type RM Length L Ch R = 1,5117,224,224,224
BEGIN DESCRIPTION:
NC Unknown Stream 61 6.0
END DESCRIPTION:
XS GIS Cut Line= 3
      1474774.07      6842804.55      1475048.40      6842462.50
      1475340.93      6842230.56
#Sta/Elev= 30
  4610.1 1978.87  4686.3 1979.05  4799.9 1975.69  4822.3 1972.94  4828.7 1973.18
  4849.4 1970.08  4857.5 1968.75  4878.3 1968.17  4900.5 1965.14  4927.9 1964.42
  4971.1 1965.25  4985.5 1964.39  4997.9 1962.30  4998.2 1961.80  5001.9 1962.30
  5006.3 1964.50  5014.3 1965.19  5020.7 1967.27  5028.7 1967.33  5035.1 1966.43
  5041.5 1968.44  5063.6 1971.09  5113.3 1971.13  5171.0 1975.65  5220.7 1977.49
  5262.3 1978.45  5305.6 1975.40  5320.0 1977.08  5355.2 1977.79  5421.9 1981.64
#Mann=5,-1,0
  4610.1    0.07       0  4849.4   0.035       0  4997.9   0.035       0
  5001.9   0.035       0  5028.7    0.07       0
Bank Sta=4997.9,5001.9
Exp/Cntr=0.3,0.1

Type RM Length L Ch R = 1,4893,177,177,177
BEGIN DESCRIPTION:
Mapping XS 6bd0a09b
END DESCRIPTION:
XS GIS Cut Line= 3
      1474796.63      6842924.33      1475095.28      6842721.18
      1475502.35      6842352.22
#Sta/Elev= 30
  4572.9 1978.98  4592.2 1979.42  4655.6 1979.74  4770.7 1976.96  4849.1 1972.49
  4878.4 1970.33  4914.4 1965.80  4984.0 1961.63  4984.2 1961.13  4988.0 1961.63
  5009.9 1962.68  5014.3 1962.38  5021.1 1964.03  5028.2 1962.66  5035.3 1964.14
  5042.0 1963.75  5084.6 1967.89  5106.2 1967.82  5113.0 1969.50  5120.4 1967.78
  5127.2 1969.33  5134.6 1967.99  5141.4 1969.26  5148.8 1967.87  5155.6 1970.42
  5163.0 1971.53  5290.0 1977.40  5361.0 1980.92  5396.2 1983.88  5483.5 1985.11
#Mann=6,-1,0
  4572.9    0.07       0  4592.2   0.035       0  4984.0   0.035       0
  4988.0   0.035       0  5009.9    0.07       0  5290.0   0.035       0
Bank Sta=4984,4988
Exp/Cntr=0.3,0.1

Type RM Length L Ch R = 1,4716,79,79,79
BEGIN DESCRIPTION:
Mapping XS 8173cc49
END DESCRIPTION:
XS GIS Cut Line= 6
      1474807.04      6842965.99      1475121.32      6842870.49
      1475228.96      6842823.61      1475326.18      6842783.68
      1475376.53      6842743.75      1475555.33      6842394.83
#Sta/Elev= 30
  4545.6 1979.04  4603.1 1979.53  4668.9 1979.74  4750.7 1977.65  4750.8 1977.65
  4825.7 1974.61  4831.0 1973.42  4857.0 1972.06  4873.4 1969.11  4888.2 1968.77
  4938.9 1963.35  4998.2 1959.52  5091.2 1959.18  5091.5 1958.68  5095.2 1959.18
  5165.1 1960.29  5187.3 1961.52  5201.0 1964.43  5259.5 1967.37  5290.9 1971.75
  5342.7 1974.14  5376.7 1974.37  5379.6 1974.54  5457.3 1977.19  5470.2 1977.76
  5475.9 1976.95  5514.6 1979.62  5520.3 1978.89  5530.8 1980.59  5552.9 1981.76
#Mann=11,-1,0
  4545.6    0.07       0  4603.1   0.035       0  4750.7    0.07       0
  4750.8   0.035       0  4938.9    0.07       0  5091.2    0.07       0
  5095.2    0.07       0  5376.7   0.035       0  5379.6    0.07       0
  5457.3   0.035       0  5530.8    0.07       0
Bank Sta=5091.2,5095.2
Exp/Cntr=0.3,0.1

Type RM Length L Ch R = 1,4637,40,40,40
BEGIN DESCRIPTION:
Mapping XS c87c9adb
END DESCRIPTION:
XS GIS Cut Line= 6
      1474829.67      6842985.07      1475123.05      6842927.78
      1475392.15      6842844.45      1475496.32      6842757.64
      1475541.46      6842646.53      1475605.68      6842363.59
#Sta/Elev= 30
  4523.4 1979.63  4589.0 1979.18  4685.0 1977.69  4737.2 1976.24  4814.1 1971.29
  4866.2 1971.24  4872.3 1969.87  4877.5 1972.51  4893.6 1971.47  4905.1 1970.11
  4910.4 1972.41  4918.4 1972.30  4938.0 1970.32  4943.2 1972.29  4960.2 1972.38
  4976.1 1969.94  4981.3 1972.43  5002.0 1972.28  5007.3 1970.69  5014.2 1972.13
  5118.1 1973.11  5153.2 1971.41  5167.5 1973.31  5250.4 1968.90  5250.7 1968.40
  5254.4 1968.90  5274.2 1969.18  5457.1 1972.93  5604.2 1977.99  5649.7 1978.17
#Mann=9,-1,0
  4523.4    0.07       0  4589.0   0.035       0  4685.0    0.07       0
  4737.2   0.035       0  4893.6    0.07       0  5250.4    0.07       0
  5254.4    0.07       0  5274.2   0.035       0  5457.1    0.07       0
Bank Sta=5250.4,5254.4
Exp/Cntr=0.3,0.1

Type RM Length L Ch R = 1,4597,189,189,189
BEGIN DESCRIPTION:
Mapping XS a9dff292
END DESCRIPTION:
XS GIS Cut Line= 6
      1474824.47      6843049.30      1475281.04      6842919.10
      1475430.34      6842865.28      1475531.04      6842787.16
      1475669.93      6842629.17      1475722.02      6842328.77
#Sta/Elev= 30
  4481.6 1978.63  4609.7 1977.73  4637.7 1977.26  4692.0 1977.01  4704.1 1978.21
  4735.5 1975.83  4763.3 1972.33  4870.5 1968.37  4883.8 1968.42  4900.0 1966.63
  4930.5 1965.90  4950.9 1964.11  4961.8 1964.57  4970.8 1963.92  4982.5 1961.41
  5001.5 1962.88  5012.4 1960.23  5012.6 1959.73  5016.4 1960.23  5025.0 1960.31
  5032.1 1962.04  5088.2 1962.02  5188.0 1968.10  5273.6 1967.63  5402.4 1968.59
  5408.3 1967.79  5455.8 1968.12  5546.1 1970.82  5566.1 1970.17  5758.4 1974.02
#Mann=9,-1,0
  4481.6    0.07       0  4609.7   0.035       0  4637.7    0.07       0
  4735.5   0.035       0  4870.5    0.07       0  5012.4    0.07       0
  5016.4    0.07       0  5402.4   0.035       0  5455.8    0.07       0
Bank Sta=5012.4,5016.4
Exp/Cntr=0.3,0.1

Type RM Length L Ch R = 1,4408,421,421,421
BEGIN DESCRIPTION:
NC Unknown Stream 61 5.0
END DESCRIPTION:
XS GIS Cut Line= 3
      1475154.98      6843338.02      1475455.00      6843038.00
      1476117.87      6842514.57
#Sta/Elev= 30
  4575.5 1974.33  4646.2 1971.63  4699.0 1967.68  4745.2 1963.39  4773.5 1963.30
  4801.8 1960.86  4883.3 1959.54  4957.4 1959.99  4969.5 1958.71  4969.8 1958.21
  4973.5 1958.71  5056.7 1959.45  5114.4 1962.09  5164.1 1960.95  5191.3 1963.09
  5199.4 1962.42  5205.8 1963.39  5241.9 1963.79  5263.5 1966.03  5298.8 1966.21
  5391.8 1962.90  5470.3 1964.35  5491.1 1963.60  5611.4 1964.44  5640.2 1966.90
  5675.5 1967.24  5733.2 1971.46  5782.9 1973.19  5797.3 1975.03  5844.4 1977.15
#Mann=5,-1,0
  4575.5    0.07       0  4699.0   0.035       0  4883.3    0.07       0
  4969.5    0.07       0  4973.5    0.07       0
Bank Sta=4969.5,4973.5
Exp/Cntr=0.3,0.1

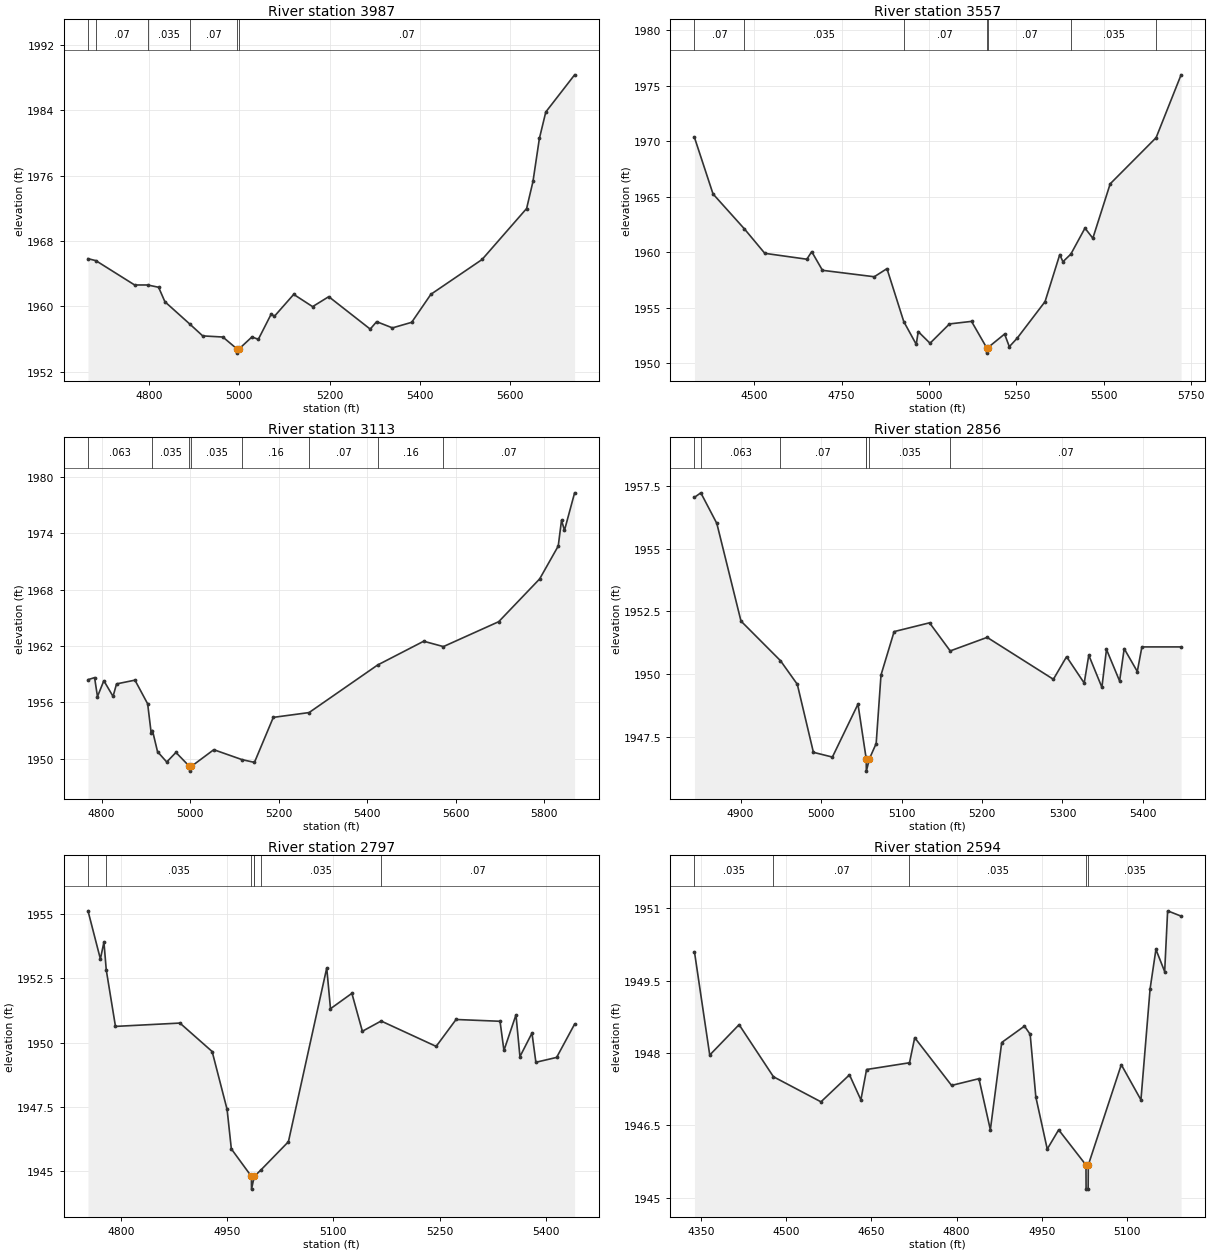
Type RM Length L Ch R = 1,3987,430,430,430
BEGIN DESCRIPTION:
NC Unknown Stream 61 4.0
END DESCRIPTION:
XS GIS Cut Line= 3
      1475455.03      6843437.99      1475755.00      6843288.00
      1476255.01      6842737.99
#Sta/Elev= 30
  4664.6 1965.83  4682.0 1965.59  4768.0 1962.61  4797.0 1962.61  4821.1 1962.33
  4835.1 1960.56  4891.2 1957.78  4918.9 1956.38  4963.6 1956.24  4995.2 1954.77
  4995.4 1954.27  4999.2 1954.77  5028.0 1956.25  5042.2 1955.96  5070.6 1959.04
  5078.0 1958.79  5120.6 1961.46  5162.5 1959.96  5198.3 1961.18  5290.2 1957.21
  5304.4 1958.12  5339.5 1957.36  5382.1 1958.04  5424.7 1961.47  5538.2 1965.73
  5636.9 1971.97  5651.0 1975.28  5665.2 1980.54  5679.4 1983.78  5743.3 1988.33
#Mann=6,-1,0
  4664.6   0.035       0  4682.0    0.07       0  4797.0   0.035       0
  4891.2    0.07       0  4995.2    0.07       0  4999.2    0.07       0
Bank Sta=4995.2,4999.2
Exp/Cntr=0.3,0.1

Type RM Length L Ch R = 1,3557,444,444,444
BEGIN DESCRIPTION:
NC Unknown Stream 61 3.0
END DESCRIPTION:
XS GIS Cut Line= 3
      1475405.04      6843837.98      1476005.00      6843538.00
      1476605.01      6843137.99
#Sta/Elev= 30
  4329.0 1970.33  4382.1 1965.24  4471.9 1962.09  4530.2 1959.89  4650.4 1959.36
  4664.4 1960.04  4695.1 1958.36  4843.3 1957.78  4879.6 1958.51  4927.7 1953.74
  4963.4 1951.69  4969.0 1952.84  5002.8 1951.79  5058.4 1953.53  5121.5 1953.76
  5164.5 1951.40  5164.8 1950.90  5168.5 1951.40  5216.1 1952.62  5229.6 1951.48
  5252.2 1952.25  5331.8 1955.54  5373.9 1959.78  5382.9 1959.13  5405.6 1959.82
  5446.0 1962.16  5468.5 1961.25  5518.1 1966.15  5649.5 1970.31  5720.9 1975.97
#Mann=7,-1,0
  4329.0    0.07       0  4471.9   0.035       0  4927.7    0.07       0
  5164.5    0.07       0  5168.5    0.07       0  5405.6   0.035       0
  5649.5    0.16       0
Bank Sta=5164.5,5168.5
Exp/Cntr=0.3,0.1

Type RM Length L Ch R = 1,3113,257,257,257
BEGIN DESCRIPTION:
NC Unknown Stream 61 2.0
END DESCRIPTION:
XS GIS Cut Line= 3
      1476173.37      6843936.49      1476355.00      6843788.00
      1476938.99      6843150.04
#Sta/Elev= 30
  4769.4 1958.42  4784.3 1958.64  4790.8 1956.62  4805.2 1958.31  4826.0 1956.64
  4833.9 1957.97  4875.5 1958.37  4904.2 1955.85  4912.1 1952.77  4915.1 1953.01
  4926.5 1950.76  4947.3 1949.66  4968.1 1950.68  4998.7 1949.19  4999.0 1948.69
  5002.8 1949.19  5053.6 1950.97  5117.6 1949.91  5145.5 1949.62  5188.1 1954.41
  5268.9 1954.92  5423.8 1959.98  5527.9 1962.51  5572.4 1961.94  5697.4 1964.59
  5789.9 1969.14  5831.9 1972.64  5839.3 1975.38  5846.0 1974.31  5868.9 1978.30
#Mann=8,-1,0
  4769.4   0.063       0  4915.1   0.035       0  4998.7   0.035       0
  5002.8   0.035       0  5117.6    0.16       0  5268.9    0.07       0
  5423.8    0.16       0  5572.4    0.07       0
Bank Sta=4998.7,5002.8
Exp/Cntr=0.3,0.1

Type RM Length L Ch R = 1,2856,59,59,59
BEGIN DESCRIPTION:
Mapping XS 9fdb0819
END DESCRIPTION:
XS GIS Cut Line= 3
      1476217.20      6844008.09      1476374.32      6844008.09
      1476769.76      6843798.44
#Sta/Elev= 30
  4842.7 1957.04  4850.6 1957.22  4870.5 1956.00  4900.5 1952.11  4949.6 1950.53
  4970.5 1949.59  4990.5 1946.88  5014.1 1946.69  5045.9 1948.80  5055.8 1946.69
  5056.1 1946.63  5056.3 1946.13  5060.2 1946.63  5068.5 1947.23  5074.5 1949.96
  5090.8 1951.69  5134.8 1952.04  5160.5 1950.92  5206.4 1951.46  5288.7 1949.79
  5305.1 1950.69  5327.0 1949.64  5332.7 1950.75  5349.0 1949.47  5354.7 1950.98
  5371.0 1949.72  5376.7 1951.01  5393.0 1950.10  5398.7 1951.08  5447.4 1951.08
#Mann=7,-1,0
  4842.7    0.07       0  4850.6   0.063       0  4949.6    0.07       0
  5055.8   0.035       0  5056.1    0.07       0  5060.2   0.035       0
  5160.5    0.07       0
Bank Sta=5056.1,5060.2
Exp/Cntr=0.3,0.1

Type RM Length L Ch R = 1,2797,203,203,203
BEGIN DESCRIPTION:
Mapping XS 3c0b22e0
END DESCRIPTION:
XS GIS Cut Line= 6
      1476196.61      6844116.16      1476334.39      6844095.55
      1476481.96      6844000.06      1476493.90      6843963.17
      1476547.07      6843926.28      1476780.74      6843797.86
#Sta/Elev= 30
  4753.6 1955.14  4771.1 1953.26  4776.1 1953.92  4779.4 1952.83  4792.4 1950.63
  4883.4 1950.76  4928.9 1949.65  4950.0 1947.39  4956.0 1945.85  4984.3 1944.78
  4984.5 1944.28  4988.4 1944.78  4988.5 1944.78  4997.5 1945.02  5036.6 1946.13
  5090.7 1952.91  5096.0 1951.32  5126.2 1951.92  5141.0 1950.44  5167.5 1950.84
  5245.2 1949.85  5273.3 1950.90  5335.4 1950.83  5340.9 1949.69  5357.9 1951.08
  5363.5 1949.45  5380.5 1950.37  5386.0 1949.23  5415.3 1949.42  5440.7 1950.72
#Mann=7,-1,0
  4753.6    0.07       0  4779.4   0.035       0  4984.3   0.035       0
  4988.4   0.035       0  4988.5    0.07       0  4997.5   0.035       0
  5167.5    0.07       0
Bank Sta=4984.3,4988.4
Exp/Cntr=0.3,0.1

Type RM Length L Ch R = 1,2594,234,234,234
BEGIN DESCRIPTION:
Mapping XS 9239f106
END DESCRIPTION:
XS GIS Cut Line= 6
      1476164.98      6844290.04      1476342.94      6844402.89
      1476466.64      6844413.74      1476565.38      6844342.12
      1476578.40      6844020.94      1476596.85      6843944.98
#Sta/Elev= 30
  4338.4 1950.10  4365.3 1947.96  4417.0 1948.59  4477.5 1947.51  4561.2 1946.99
  4611.4 1947.55  4631.5 1947.03  4641.5 1947.66  4717.1 1947.80  4726.3 1948.32
  4791.2 1947.33  4839.4 1947.47  4859.5 1946.41  4879.5 1948.22  4919.6 1948.56
  4929.6 1948.39  4939.6 1947.09  4959.7 1946.01  4979.8 1946.41  5027.9 1945.68
  5028.1 1945.18  5031.7 1945.18  5032.0 1945.68  5090.1 1947.76  5124.7 1947.03
  5140.8 1949.33  5151.1 1950.15  5166.5 1949.69  5171.7 1950.95  5195.4 1950.84
#Mann=5,-1,0
  4338.4   0.035       0  4477.5    0.07       0  4717.1   0.035       0
  5027.9   0.035       0  5032.0   0.035       0
Bank Sta=5027.9,5032
Exp/Cntr=0.3,0.1

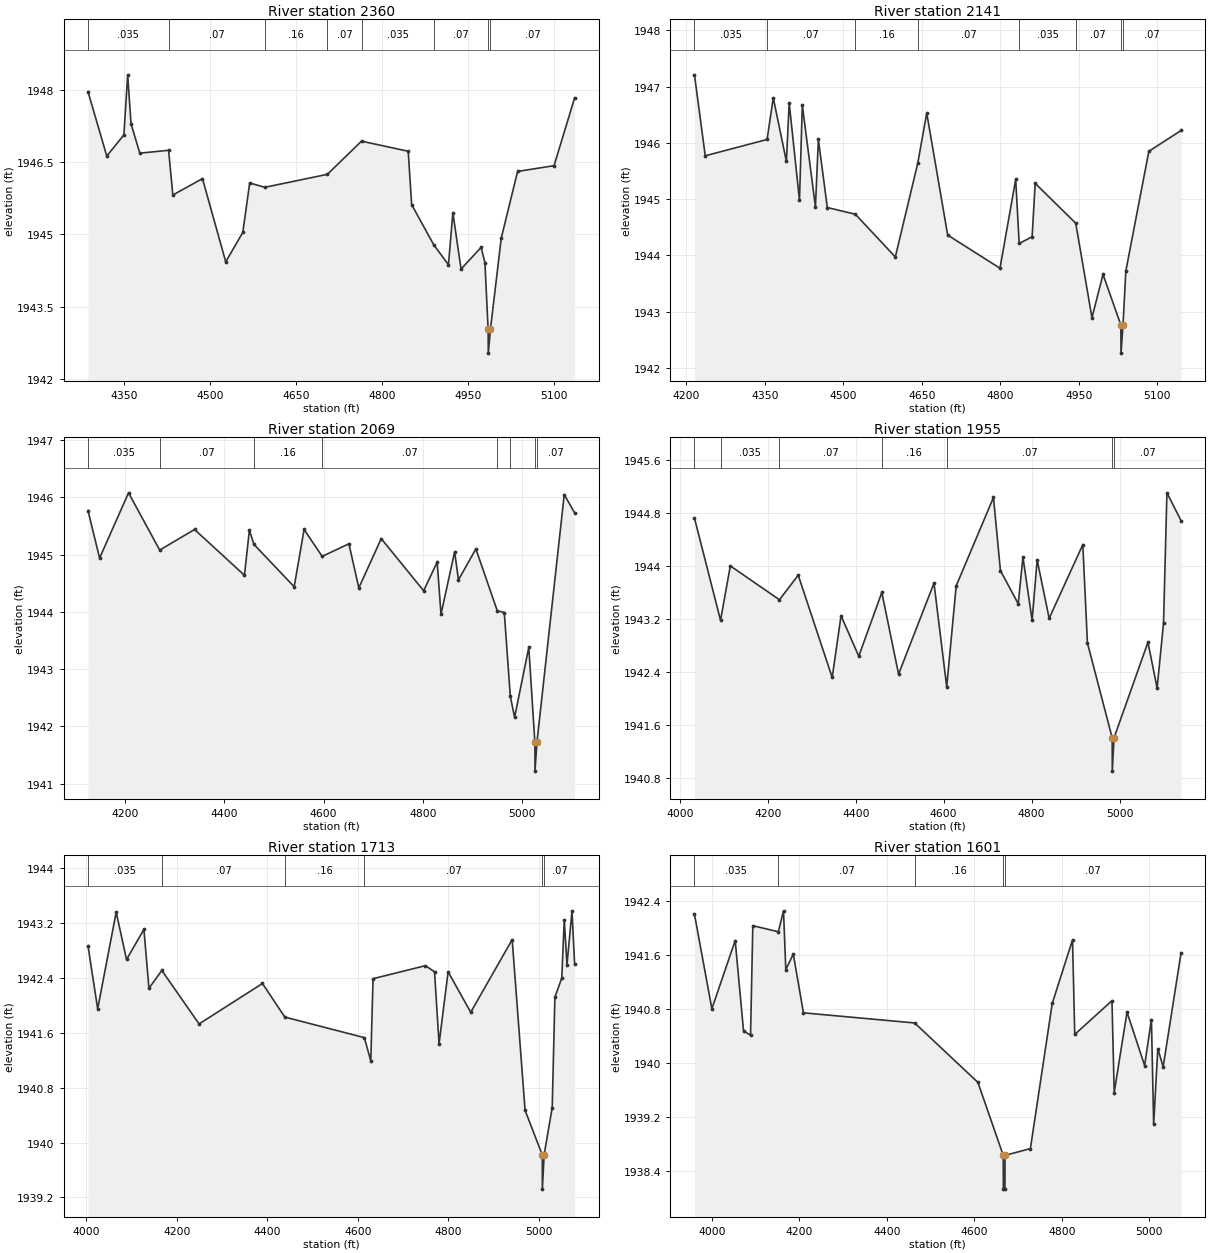
Type RM Length L Ch R = 1,2360,219,219,219
BEGIN DESCRIPTION:
Mapping XS 5a6605be
END DESCRIPTION:
XS GIS Cut Line= 6
      1476151.93      6844375.74      1476357.04      6844504.89
      1476485.08      6844498.37      1476657.61      6844385.53
      1476816.03      6844198.90      1476808.86      6844171.26
#Sta/Elev= 30
  4286.3 1947.97  4319.1 1946.63  4349.0 1947.07  4355.6 1948.32  4361.5 1947.30
  4376.8 1946.69  4427.1 1946.75  4434.5 1945.82  4486.3 1946.16  4526.9 1944.43
  4556.7 1945.04  4568.8 1946.07  4595.3 1945.98  4704.5 1946.25  4764.1 1946.94
  4845.7 1946.73  4851.7 1945.62  4890.5 1944.78  4916.0 1944.37  4923.7 1945.45
  4938.0 1944.28  4973.1 1944.73  4979.7 1944.41  4985.3 1943.03  4985.6 1942.53
  4989.4 1943.03  5008.2 1944.92  5036.8 1946.31  5100.5 1946.43  5136.4 1947.84
#Mann=8,-1,0
  4286.3   0.035       0  4427.1    0.07       0  4595.3    0.16       0
  4704.5    0.07       0  4764.1   0.035       0  4890.5    0.07       0
  4985.3    0.07       0  4989.4    0.07       0
Bank Sta=4985.3,4989.4
Exp/Cntr=0.3,0.1

Type RM Length L Ch R = 1,2141,72,72,72
BEGIN DESCRIPTION:
Mapping XS cf08c379
END DESCRIPTION:
XS GIS Cut Line= 6
      1476135.69      6844441.95      1476355.96      6844523.33
      1476523.06      6844524.42      1476740.07      6844528.76
      1476913.68      6844414.82      1476962.49      6844323.71
#Sta/Elev= 30
  4215.3 1947.21  4235.9 1945.77  4354.1 1946.06  4365.9 1946.80  4391.0 1945.67
  4396.3 1946.71  4416.0 1944.98  4421.4 1946.67  4446.5 1944.86  4452.1 1946.06
  4469.2 1944.85  4522.8 1944.73  4599.2 1943.97  4642.1 1945.64  4659.2 1946.53
  4699.2 1944.36  4799.2 1943.77  4829.2 1945.35  4835.9 1944.21  4860.6 1944.33
  4866.5 1945.28  4944.0 1944.57  4975.0 1942.89  4996.1 1943.66  5030.2 1942.76
  5030.5 1942.26  5034.3 1942.76  5039.7 1943.72  5083.7 1945.85  5145.3 1946.22
#Mann=8,-1,0
  4215.3   0.035       0  4354.1    0.07       0  4522.8    0.16       0
  4642.1    0.07       0  4835.9   0.035       0  4944.0    0.07       0
  5030.2    0.07       0  5034.3    0.07       0
Bank Sta=5030.2,5034.3
Exp/Cntr=0.3,0.1

Type RM Length L Ch R = 1,2069,114,114,114
BEGIN DESCRIPTION:
Mapping XS dccf7f72
END DESCRIPTION:
XS GIS Cut Line= 5
      1476111.80      6844552.63      1476392.85      6844587.35
      1476664.12      6844606.88      1476794.33      6844592.78
      1477020.40      6844403.30
#Sta/Elev= 30
  4125.1 1945.77  4148.5 1944.94  4206.8 1946.08  4269.7 1945.08  4339.9 1945.44
  4440.5 1944.64  4450.5 1945.43  4459.6 1945.18  4540.8 1944.44  4560.8 1945.44
  4597.2 1944.97  4651.1 1945.19  4671.1 1944.42  4716.3 1945.28  4801.8 1944.37
  4829.1 1944.87  4836.8 1943.96  4864.3 1945.05  4872.0 1944.56  4907.1 1945.10
  4950.3 1944.02  4964.4 1943.99  4976.5 1942.53  4985.2 1942.16  5013.8 1943.38
  5026.1 1941.72  5026.3 1941.22  5030.2 1941.72  5085.3 1946.05  5106.2 1945.73
#Mann=8,-1,0
  4125.1   0.035       0  4269.7    0.07       0  4459.6    0.16       0
  4597.2    0.07       0  4950.3   0.035       0  4976.5    0.07       0
  5026.1    0.07       0  5030.2    0.07       0
Bank Sta=5026.1,5030.2
Exp/Cntr=0.3,0.1

Type RM Length L Ch R = 1,1955,242,242,242
BEGIN DESCRIPTION:
Mapping XS f7a7af5b
END DESCRIPTION:
XS GIS Cut Line= 6
      1476087.95      6844644.00      1476085.55      6844681.11
      1476217.07      6844719.73      1476763.94      6844657.88
      1476945.15      6844601.46      1477084.04      6844476.69
#Sta/Elev= 30
  4033.5 1944.72  4092.8 1943.18  4115.0 1944.00  4226.7 1943.49  4269.4 1943.86
  4346.6 1942.32  4366.7 1943.25  4407.0 1942.64  4459.4 1943.60  4497.5 1942.37
  4578.0 1943.74  4606.9 1942.18  4628.5 1943.70  4713.2 1945.03  4729.0 1943.93
  4769.5 1943.43  4780.2 1944.13  4801.1 1943.18  4812.5 1944.09  4839.8 1943.21
  4916.3 1944.32  4926.8 1942.84  4983.1 1941.41  4983.3 1940.91  4987.2 1941.41
  5064.4 1942.85  5085.2 1942.16  5099.8 1943.14  5107.5 1945.10  5139.7 1944.68
#Mann=7,-1,0
  4033.5    0.07       0  4092.8   0.035       0  4226.7    0.07       0
  4459.4    0.16       0  4606.9    0.07       0  4983.1    0.07       0
  4987.2    0.07       0
Bank Sta=4983.1,4987.2
Exp/Cntr=0.3,0.1

Type RM Length L Ch R = 1,1713,112,112,112
BEGIN DESCRIPTION:
Mapping XS 94b51e0b
END DESCRIPTION:
XS GIS Cut Line= 5
      1476064.11      6844775.73      1476267.20      6844819.12
      1476992.89      6844791.34      1477091.85      6844791.34
      1477109.88      6844752.70
#Sta/Elev= 30
  4003.9 1942.87  4025.3 1941.95  4066.2 1943.36  4089.1 1942.67  4127.5 1943.11
  4138.6 1942.25  4167.1 1942.51  4249.4 1941.73  4389.5 1942.32  4438.9 1941.83
  4614.7 1941.53  4628.9 1941.19  4633.9 1942.39  4749.8 1942.58  4769.8 1942.49
  4779.8 1941.44  4799.8 1942.49  4849.8 1941.90  4941.4 1942.96  4969.9 1940.47
  5007.9 1939.82  5008.1 1939.32  5012.0 1939.82  5029.9 1940.51  5035.8 1942.12
  5051.0 1942.40  5056.5 1943.25  5062.5 1942.59  5073.6 1943.38  5079.4 1942.60
#Mann=6,-1,0
  4003.9   0.035       0  4167.1    0.07       0  4438.9    0.16       0
  4614.7    0.07       0  5007.9    0.07       0  5012.0    0.07       0
Bank Sta=5007.9,5012
Exp/Cntr=0.3,0.1

Type RM Length L Ch R = 1,1601,130,130,130
BEGIN DESCRIPTION:
Mapping XS 4000595a
END DESCRIPTION:
XS GIS Cut Line= 6
      1476045.62      6844828.33      1476058.02      6844858.47
      1476303.66      6844923.29      1476864.42      6844925.02
      1477081.44      6844900.72      1477116.17      6844869.46
#Sta/Elev= 30
  3960.4 1942.20  4000.2 1940.80  4053.5 1941.81  4072.6 1940.47  4088.6 1940.41
  4093.8 1942.03  4152.2 1941.94  4164.0 1942.25  4169.2 1941.38  4186.4 1941.61
  4209.5 1940.74  4463.8 1940.59  4608.4 1939.71  4666.3 1938.63  4666.6 1938.13
  4670.2 1938.13  4670.4 1938.63  4728.4 1938.73  4778.4 1940.88  4824.7 1941.82
  4829.8 1940.42  4914.9 1940.92  4920.0 1939.56  4949.3 1940.75  4989.5 1939.96
  5005.1 1940.64  5010.2 1939.09  5019.7 1940.21  5031.9 1939.94  5072.9 1941.63
#Mann=5,-1,0
  3960.4   0.035       0  4152.2    0.07       0  4463.8    0.16       0
  4666.3    0.07       0  4670.4    0.07       0
Bank Sta=4666.3,4670.4
Exp/Cntr=0.3,0.1

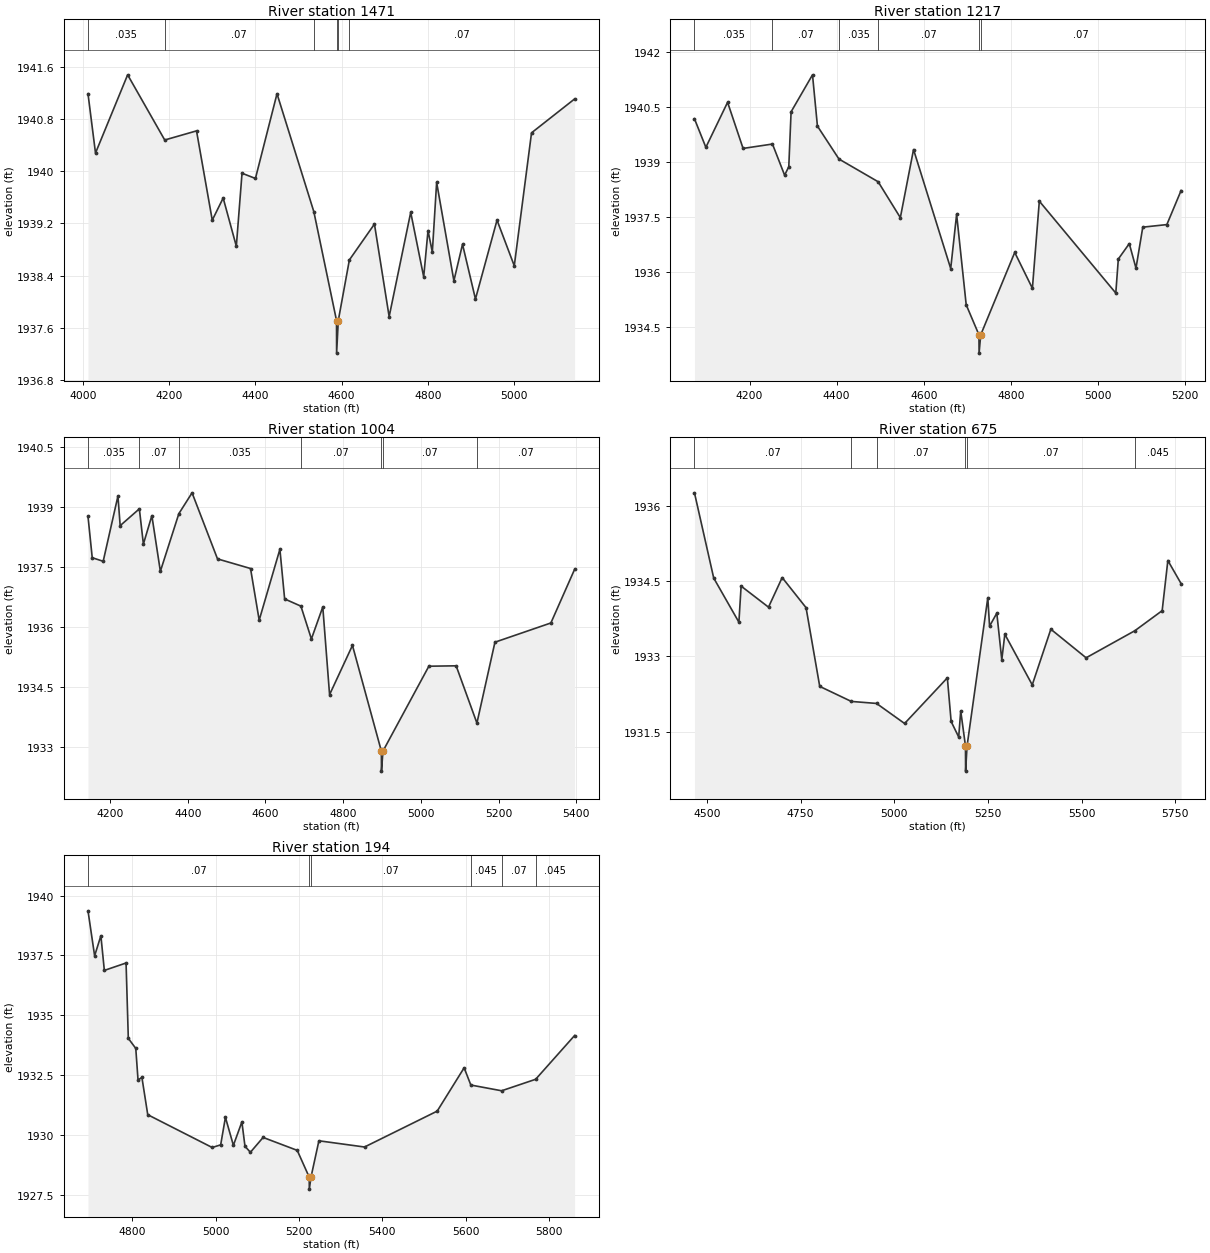
Type RM Length L Ch R = 1,1471,254,254,254
BEGIN DESCRIPTION:
Mapping XS c1ea74f0
END DESCRIPTION:
XS GIS Cut Line= 4
      1476038.65      6844884.59      1476378.31      6845008.36
      1477058.87      6845018.77      1477110.50      6844949.93
#Sta/Elev= 30
  4012.2 1941.19  4029.6 1940.28  4104.1 1941.48  4190.1 1940.48  4263.8 1940.62
  4300.3 1939.25  4325.6 1939.59  4356.1 1938.85  4369.3 1939.97  4400.4 1939.89
  4450.4 1941.19  4535.8 1939.38  4588.4 1937.71  4588.6 1937.21  4592.5 1937.71
  4618.2 1938.64  4676.3 1939.19  4710.4 1937.77  4760.4 1939.37  4790.5 1938.38
  4800.5 1939.09  4810.5 1938.76  4820.5 1939.83  4860.5 1938.32  4880.5 1938.88
  4910.5 1938.04  4960.5 1939.25  5000.5 1938.55  5040.5 1940.59  5140.4 1941.11
#Mann=6,-1,0
  4012.2   0.035       0  4190.1    0.07       0  4535.8    0.16       0
  4588.4    0.07       0  4592.5    0.16       0  4618.2    0.07       0
Bank Sta=4588.4,4592.5
Exp/Cntr=0.3,0.1

Type RM Length L Ch R = 1,1217,213,213,213
BEGIN DESCRIPTION:
Mapping XS 5ff87342
END DESCRIPTION:
XS GIS Cut Line= 4
      1476031.07      6844935.43      1476711.64      6845190.65
      1477011.99      6845268.77      1477084.27      6845232.64
#Sta/Elev= 30
  4073.3 1940.18  4099.5 1939.40  4149.4 1940.63  4185.0 1939.37  4252.5 1939.49
  4280.4 1938.64  4290.0 1938.87  4295.3 1940.37  4344.5 1941.38  4355.8 1939.98
  4405.3 1939.08  4495.3 1938.46  4546.3 1937.48  4576.6 1939.34  4662.0 1936.09
  4675.6 1937.57  4697.6 1935.10  4726.9 1934.28  4727.2 1933.78  4731.0 1934.28
  4809.1 1936.53  4849.7 1935.55  4865.6 1937.93  5041.3 1935.42  5047.1 1936.35
  5072.3 1936.77  5087.7 1936.10  5103.3 1937.22  5158.6 1937.29  5191.3 1938.22
#Mann=6,-1,0
  4073.3   0.035       0  4252.5    0.07       0  4405.3   0.035       0
  4495.3    0.07       0  4726.9    0.07       0  4731.0    0.07       0
Bank Sta=4726.9,4731
Exp/Cntr=0.3,0.1

Type RM Length L Ch R = 1,1004,329,329,329
BEGIN DESCRIPTION:
Mapping XS ed0a6d53
END DESCRIPTION:
XS GIS Cut Line= 5
      1476015.43      6845034.38      1476340.12      6845211.48
      1476899.14      6845456.27      1477072.76      6845395.51
      1477076.23      6845306.93
#Sta/Elev= 30
  4143.2 1938.76  4154.1 1937.73  4182.3 1937.64  4220.3 1939.27  4226.0 1938.53
  4275.4 1938.95  4285.8 1938.07  4307.6 1938.78  4329.5 1937.39  4377.1 1938.83
  4411.1 1939.35  4476.6 1937.70  4561.6 1937.46  4583.9 1936.17  4637.2 1937.94
  4649.4 1936.70  4691.3 1936.52  4718.3 1935.70  4747.6 1936.50  4765.1 1934.31
  4824.0 1935.54  4898.4 1932.90  4898.7 1932.40  4902.5 1932.90  5020.7 1935.02
  5090.9 1935.03  5144.4 1933.60  5190.8 1935.62  5334.8 1936.10  5395.9 1937.44
#Mann=7,-1,0
  4143.2   0.035       0  4275.4    0.07       0  4377.1   0.035       0
  4691.3    0.07       0  4898.4    0.07       0  4902.5    0.07       0
  5144.4    0.07       0
Bank Sta=4898.4,4902.5
Exp/Cntr=0.3,0.1

Type RM Length L Ch R = 1,675,481,481,481
BEGIN DESCRIPTION:
Mapping XS ad7b5954
END DESCRIPTION:
XS GIS Cut Line= 5
      1476294.54      6845326.49      1476488.55      6845636.40
      1476909.13      6845693.69      1477056.26      6845606.45
      1477340.67      6845424.63
#Sta/Elev= 30
  4466.7 1936.26  4518.1 1934.56  4585.3 1933.68  4591.2 1934.40  4664.3 1933.98
  4700.8 1934.57  4764.5 1933.97  4801.0 1932.40  4885.3 1932.10  4952.6 1932.06
  5027.5 1931.66  5141.6 1932.57  5151.7 1931.70  5171.9 1931.39  5177.3 1931.91
  5190.0 1931.21  5190.3 1930.71  5194.2 1931.21  5249.6 1934.17  5254.2 1933.60
  5273.6 1933.86  5286.9 1932.93  5295.0 1933.44  5368.2 1932.43  5417.8 1933.54
  5511.9 1932.97  5642.0 1933.51  5714.9 1933.91  5730.1 1934.91  5765.4 1934.45
#Mann=6,-1,0
  4466.7    0.07       0  4885.3    0.16       0  4952.6    0.07       0
  5190.0    0.07       0  5194.2    0.07       0  5642.0   0.045       0
Bank Sta=5190,5194.2
Exp/Cntr=0.3,0.1

Type RM Length L Ch R = 1,194,0,0,0
BEGIN DESCRIPTION:
Mapping XS 4e755295
END DESCRIPTION:
XS GIS Cut Line= 5
      1476516.77      6845925.96      1476709.91      6846011.40
      1476967.72      6846060.87      1477055.19      6846039.58
      1477290.35      6845483.92
#Sta/Elev= 30
  4694.1 1939.36  4710.0 1937.48  4725.0 1938.32  4733.3 1936.87  4785.4 1937.18
  4790.8 1934.03  4808.7 1933.61  4814.1 1932.29  4823.4 1932.40  4837.4 1930.84
  4991.9 1929.47  5012.3 1929.58  5023.7 1930.73  5042.8 1929.56  5063.2 1930.54
  5070.6 1929.52  5083.6 1929.27  5114.1 1929.89  5195.9 1929.35  5224.7 1928.23
  5224.9 1927.73  5228.9 1928.23  5247.9 1929.75  5357.3 1929.49  5531.6 1930.99
  5596.2 1932.80  5612.3 1932.08  5686.1 1931.84  5767.7 1932.32  5861.2 1934.15
#Mann=6,-1,0
  4694.1    0.07       0  5224.7    0.07       0  5228.9    0.07       0
  5612.3   0.045       0  5686.1    0.07       0  5767.7   0.045       0
Bank Sta=5224.7,5228.9
Exp/Cntr=0.3,0.1

Chan Stop Cuts=-1