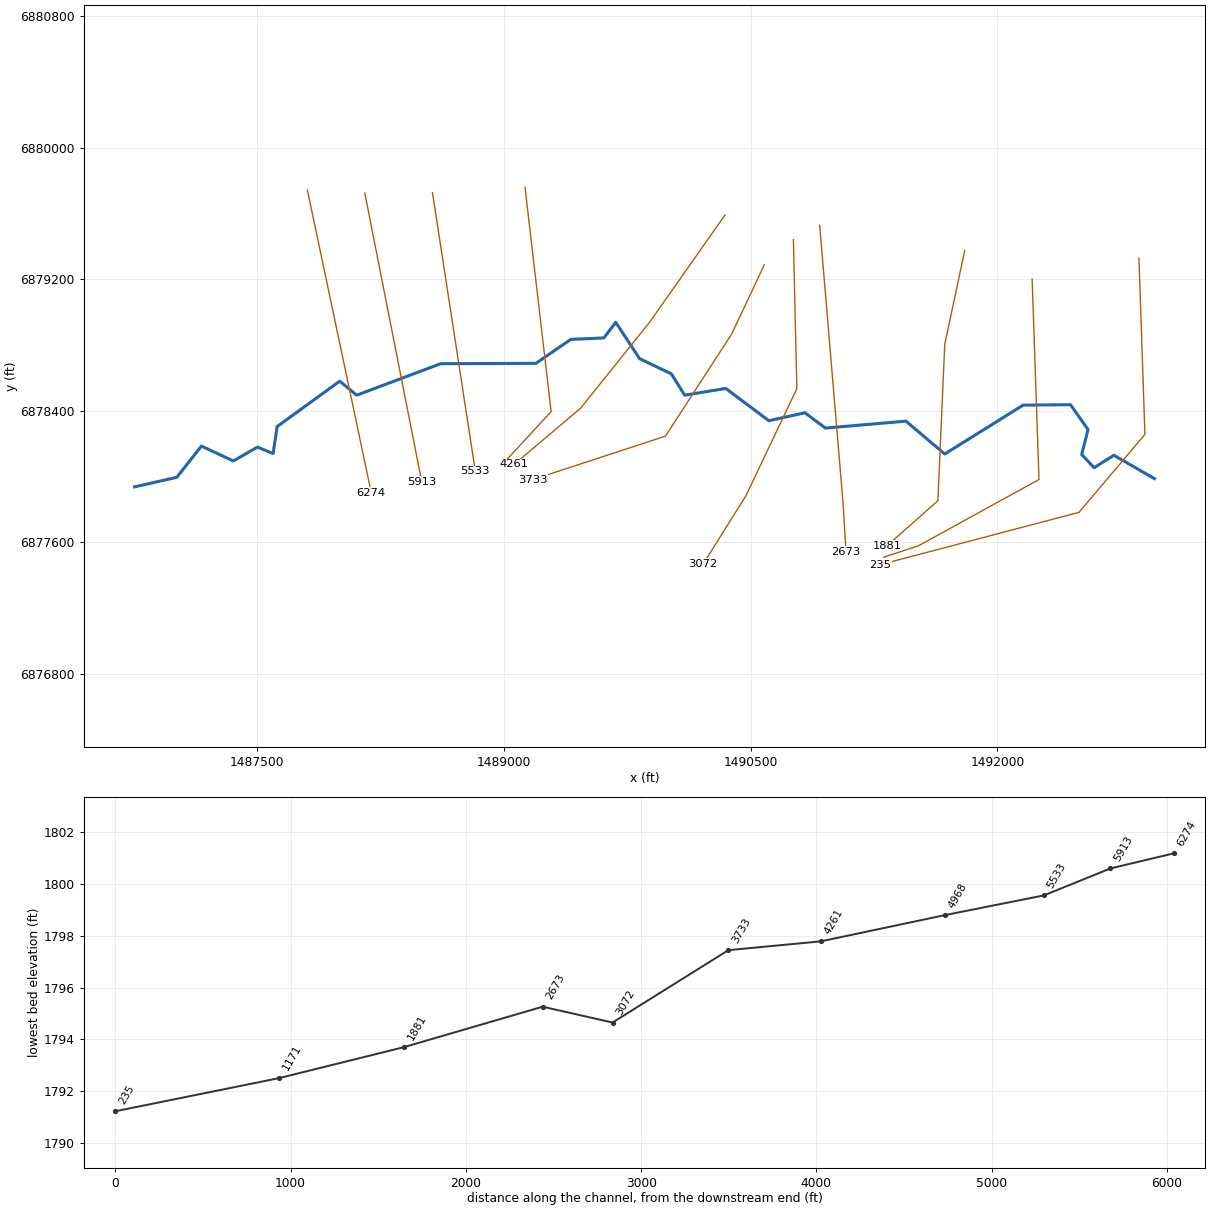
--- NC Unknown Stream 64.prj (project) ---

Proj Title=NC Unknown Stream 64 Base Level Engineering
Current Plan=p01
Default Exp/Contr=0.3,0.1
English Units
Geom File=g01
Flow File=f01
Plan File=p01
BEGIN DESCRIPTION:
NC Unknown Stream 64
END DESCRIPTION:

--- NC Unknown Stream 64.p01 (plan) ---

Plan Title=Multiple Run
Short Identifier=Multiple
Geom File=g01
Flow File=f01
Subcritical Flow
K Sum by GR= 0
Std Step Tol= 0.01
Critical Tol= 0.01
Num of Std Step Trials= 20
Max Error Tol= 0.3
Flow Tol Ratio= 0.001
Split Flow NTrial= 30
Split Flow Tol= 0.02
Split Flow Ratio= 0.02
Log Output Level= 0
Friction Slope Method= 1
Unsteady Friction Slope Method= 2
Unsteady Bridges Friction Slope Method= 1
Parabolic Critical Depth
Global Vel Dist=  1 , 1 , 1
Global Log Level= 0
CheckData=True
Encroach Param= -1, 0, 0, 0
BEGIN DESCRIPTION:
Multiple Run
END DESCRIPTION:

--- NC Unknown Stream 64.f01 (steady flow) ---

Flow Title=Multiple
Number of Profiles=7
Profile Names=10-year,25-year,50-year,1pct_min,100-year,1pct_plu,500-year
River Rch & RM= NC Unknown Strea,Reach-1,6274
     430     608     757     467     932    1859    1431
River Rch & RM= NC Unknown Strea,Reach-1,4261
     426     598     739     454     905    1806    1374
Boundary for River Rch & Prof#=NC Unknown Strea,Reach-1,1
Up Type=0
Dn Type=3
Dn Slope=0.001
Boundary for River Rch & Prof#=NC Unknown Strea,Reach-1,2
Up Type=0
Dn Type=3
Dn Slope=0.001
Boundary for River Rch & Prof#=NC Unknown Strea,Reach-1,3
Up Type=0
Dn Type=3
Dn Slope=0.001
Boundary for River Rch & Prof#=NC Unknown Strea,Reach-1,4
Up Type=0
Dn Type=3
Dn Slope=0.001
Boundary for River Rch & Prof#=NC Unknown Strea,Reach-1,5
Up Type=0
Dn Type=3
Dn Slope=0.001
Boundary for River Rch & Prof#=NC Unknown Strea,Reach-1,6
Up Type=0
Dn Type=3
Dn Slope=0.001
Boundary for River Rch & Prof#=NC Unknown Strea,Reach-1,7
Up Type=0
Dn Type=3
Dn Slope=0.001

--- NC Unknown Stream 64.g01 (geometry) ---

Geom Title=Existing Conditions

River Reach=NC Unknown Strea,Reach-1
Reach XY= 30
      1486755.00      6877938.00      1487011.38      6877996.01
      1487160.94      6878185.87      1487354.92      6878095.30
      1487501.72      6878179.92      1487596.89      6878140.51
      1487621.43      6878304.76      1488001.67      6878580.38
      1488104.91      6878495.31      1488615.50      6878686.78
      1489194.30      6878688.80      1489406.47      6878834.45
      1489607.69      6878843.40      1489680.00      6878938.65
      1489824.62      6878717.52      1490018.56      6878624.52
      1490098.67      6878495.39      1490348.88      6878536.17
      1490610.86      6878340.05      1490830.04      6878388.49
      1490954.90      6878295.33      1491444.51      6878337.42
      1491680.00      6878137.58      1492156.65      6878434.83
      1492444.51      6878437.42      1492551.32      6878286.42
      1492512.80      6878134.55      1492588.26      6878054.20
      1492708.23      6878130.15      1492955.00      6877988.00

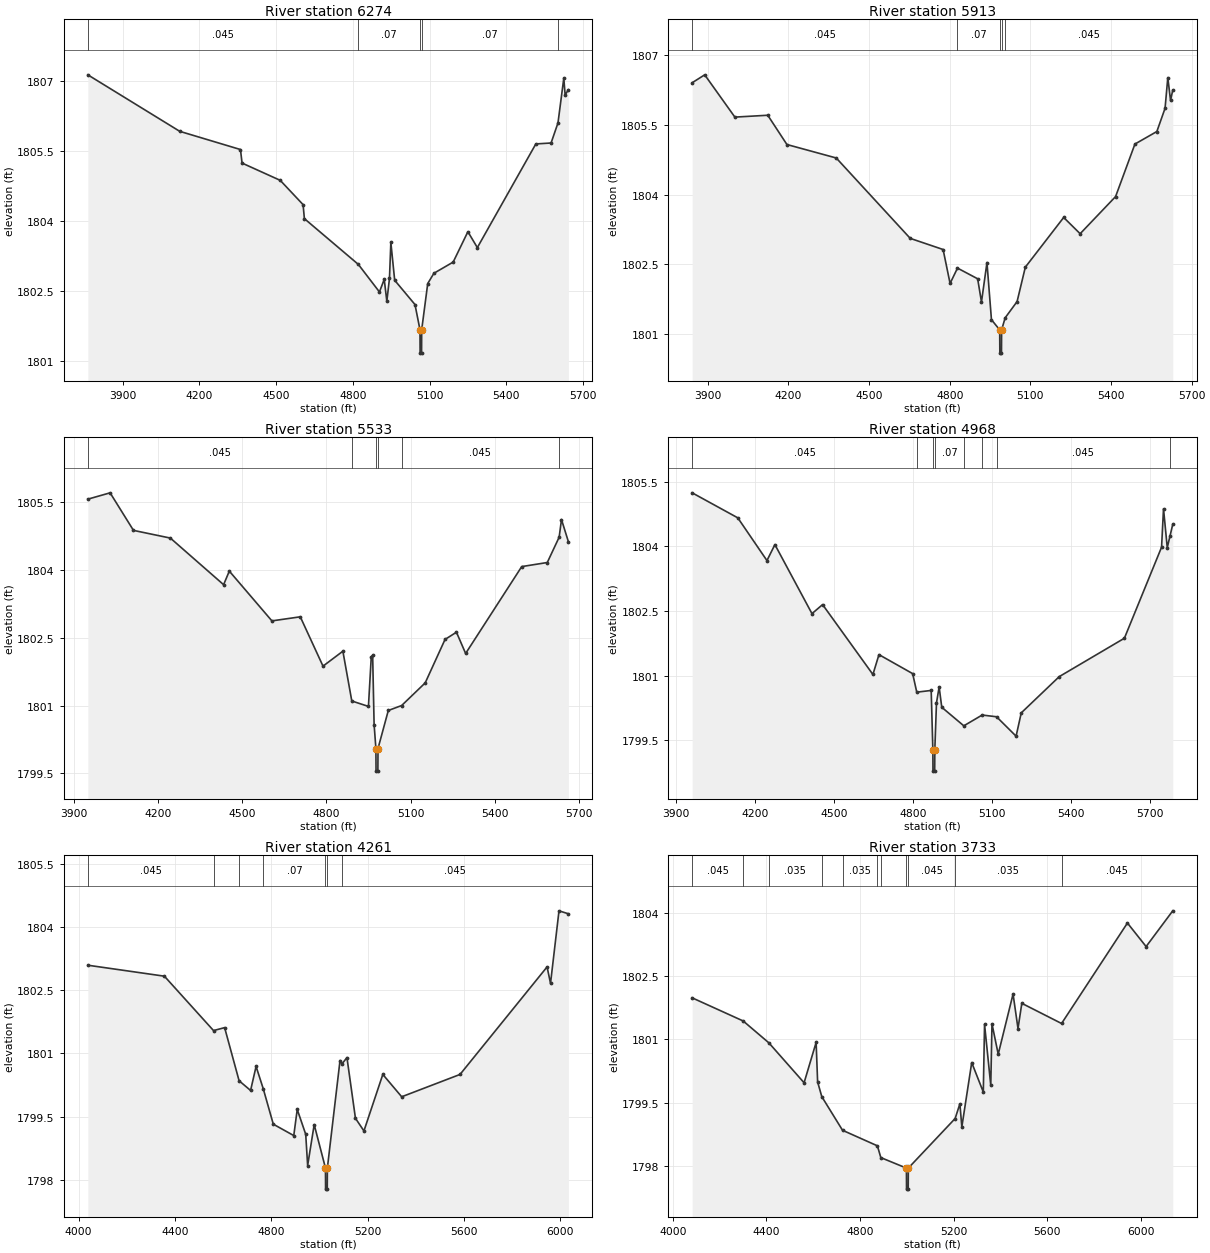
Type RM Length L Ch R = 1,6274,361,361,361
BEGIN DESCRIPTION:
Mapping XS 4af156d1
END DESCRIPTION:
XS GIS Cut Line= 2
      1487805.24      6879742.05      1488193.28      6877903.45
#Sta/Elev= 30
  3763.5 1807.13  4122.9 1805.92  4360.4 1805.53  4366.6 1805.24  4515.9 1804.87
  4605.2 1804.35  4610.3 1804.05  4821.3 1803.07  4903.8 1802.48  4922.5 1802.75
  4932.7 1802.28  4943.0 1802.77  4948.4 1803.54  4963.4 1802.73  5042.8 1802.21
  5062.3 1801.67  5062.8 1801.17  5068.5 1801.17  5069.0 1801.67  5092.6 1802.66
  5116.7 1802.88  5192.1 1803.12  5249.6 1803.77  5286.6 1803.43  5515.3 1805.65
  5574.9 1805.67  5601.9 1806.10  5624.7 1807.06  5629.8 1806.70  5642.6 1806.81
#Mann=5,-1,0
  3763.5   0.045       0  4821.3    0.07       0  5062.3    0.07       0
  5069.0    0.07       0  5601.9   0.035       0
Bank Sta=5062.3,5069
Exp/Cntr=0.3,0.1

Type RM Length L Ch R = 1,5913,380,380,380
BEGIN DESCRIPTION:
Mapping XS 9dcfd3bf
END DESCRIPTION:
XS GIS Cut Line= 2
      1488154.21      6879723.77      1488500.28      6877969.99
#Sta/Elev= 30
  3842.1 1806.41  3888.7 1806.58  4000.9 1805.67  4123.2 1805.71  4194.5 1805.08
  4378.0 1804.79  4653.2 1803.06  4775.5 1802.82  4801.4 1802.09  4829.0 1802.42
  4904.0 1802.19  4918.2 1801.69  4938.6 1802.54  4955.3 1801.31  4986.0 1801.09
  4986.5 1800.59  4992.6 1800.59  4993.1 1801.09  5006.3 1801.35  5050.7 1801.70
  5081.3 1802.44  5224.0 1803.51  5285.2 1803.16  5417.1 1803.96  5489.0 1805.09
  5570.6 1805.36  5601.1 1805.86  5611.3 1806.52  5621.5 1806.03  5629.7 1806.25
#Mann=5,-1,0
  3842.1   0.045       0  4829.0    0.07       0  4986.0    0.07       0
  4993.1    0.07       0  5006.3   0.045       0
Bank Sta=4986,4993.1
Exp/Cntr=0.3,0.1

Type RM Length L Ch R = 1,5533,565,565,565
BEGIN DESCRIPTION:
Mapping XS 920d558a
END DESCRIPTION:
XS GIS Cut Line= 2
      1488565.66      6879726.43      1488826.09      6878033.64
#Sta/Elev= 30
  3949.4 1805.56  4028.8 1805.70  4112.1 1804.87  4243.6 1804.70  4433.3 1803.67
  4453.7 1803.97  4605.5 1802.87  4706.6 1802.96  4787.6 1801.87  4858.4 1802.20
  4890.2 1801.10  4949.5 1800.98  4959.5 1802.07  4964.5 1802.11  4969.7 1800.58
  4976.1 1800.05  4976.6 1799.55  4983.1 1799.55  4983.6 1800.05  5020.3 1800.89
  5067.9 1801.00  5151.8 1801.50  5222.5 1802.46  5263.1 1802.62  5295.9 1802.15
  5495.8 1804.07  5586.9 1804.16  5629.2 1804.72  5637.5 1805.11  5662.1 1804.62
#Mann=6,-1,0
  3949.4   0.045       0  4890.2    0.07       0  4976.1    0.07       0
  4983.6    0.07       0  5067.9   0.045       0  5629.2   0.035       0
Bank Sta=4976.1,4983.6
Exp/Cntr=0.3,0.1

Type RM Length L Ch R = 1,4968,707,707,707
BEGIN DESCRIPTION:
Mapping XS 8293dd78
END DESCRIPTION:
XS GIS Cut Line= 3
      1489128.16      6879760.28      1489287.02      6878395.65
      1488980.21      6878062.84
#Sta/Elev= 30
  3961.6 1805.24  4135.0 1804.66  4245.8 1803.67  4276.0 1804.04  4416.9 1802.44
  4457.2 1802.65  4648.5 1801.03  4671.5 1801.49  4799.5 1801.05  4815.2 1800.62
  4870.0 1800.66  4876.3 1799.29  4876.8 1798.79  4883.3 1798.79  4883.8 1799.29
  4890.1 1800.37  4900.2 1800.74  4910.2 1800.27  4994.0 1799.84  5063.7 1800.09
  5118.4 1800.05  5192.7 1799.60  5212.3 1800.14  5356.6 1800.98  5604.3 1801.87
  5745.6 1803.98  5753.0 1804.87  5767.2 1803.97  5777.3 1804.23  5788.1 1804.51
#Mann=8,-1,0
  3961.6   0.045       0  4815.2    0.07       0  4876.3   0.045       0
  4883.8    0.07       0  4994.0   0.045       0  5063.7    0.07       0
  5118.4   0.045       0  5777.3   0.035       0
Bank Sta=4876.3,4883.8
Exp/Cntr=0.3,0.1

Type RM Length L Ch R = 1,4261,528,528,528
BEGIN DESCRIPTION:
Mapping XS 9fc34558
END DESCRIPTION:
XS GIS Cut Line= 4
      1490344.29      6879590.93      1489888.58      6878942.53
      1489466.71      6878416.49      1489063.09      6878075.36
#Sta/Elev= 30
  4038.0 1803.09  4355.9 1802.83  4559.9 1801.54  4606.0 1801.61  4666.1 1800.35
  4713.8 1800.12  4736.6 1800.69  4766.4 1800.16  4808.1 1799.32  4893.1 1799.05
  4907.5 1799.67  4942.7 1799.08  4950.7 1798.34  4977.9 1799.31  5024.7 1798.28
  5025.2 1797.78  5032.1 1797.78  5032.6 1798.28  5085.1 1800.83  5093.4 1800.75
  5113.9 1800.90  5149.2 1799.46  5184.4 1799.16  5262.8 1800.50  5341.2 1799.97
  5583.4 1800.50  5944.8 1803.05  5959.1 1802.66  5994.3 1804.38  6033.3 1804.31
#Mann=7,-1,0
  4038.0   0.045       0  4559.9    0.07       0  4666.1   0.035       0
  4766.4    0.07       0  5024.7    0.07       0  5032.6    0.07       0
  5093.4   0.045       0
Bank Sta=5024.7,5032.6
Exp/Cntr=0.3,0.1

Type RM Length L Ch R = 1,3733,661,661,661
BEGIN DESCRIPTION:
Mapping XS b280ea74
END DESCRIPTION:
XS GIS Cut Line= 4
      1490583.03      6879288.03      1490385.11      6878867.88
      1489982.33      6878246.35      1489176.81      6877982.47
#Sta/Elev= 30
  4083.0 1801.99  4300.8 1801.44  4410.5 1800.92  4561.0 1799.97  4612.4 1800.93
  4618.8 1799.99  4636.6 1799.64  4725.2 1798.84  4874.1 1798.47  4888.8 1798.19
  4998.1 1797.94  4998.6 1797.44  5005.7 1797.44  5006.2 1797.94  5206.2 1799.12
  5226.5 1799.47  5234.8 1798.92  5277.0 1800.45  5326.5 1799.75  5331.8 1801.36
  5358.4 1799.91  5363.6 1801.37  5390.2 1800.65  5453.6 1802.08  5474.7 1801.26
  5491.0 1801.86  5660.8 1801.38  5942.1 1803.77  6021.9 1803.21  6135.7 1804.06
#Mann=11,-1,0
  4083.0   0.045       0  4300.8    0.07       0  4410.5   0.035       0
  4636.6    0.07       0  4725.2   0.035       0  4874.1    0.07       0
  4888.8   0.045       0  4998.1   0.045       0  5006.2   0.045       0
  5206.2   0.035       0  5660.8   0.045       0
Bank Sta=4998.1,5006.2
Exp/Cntr=0.3,0.1

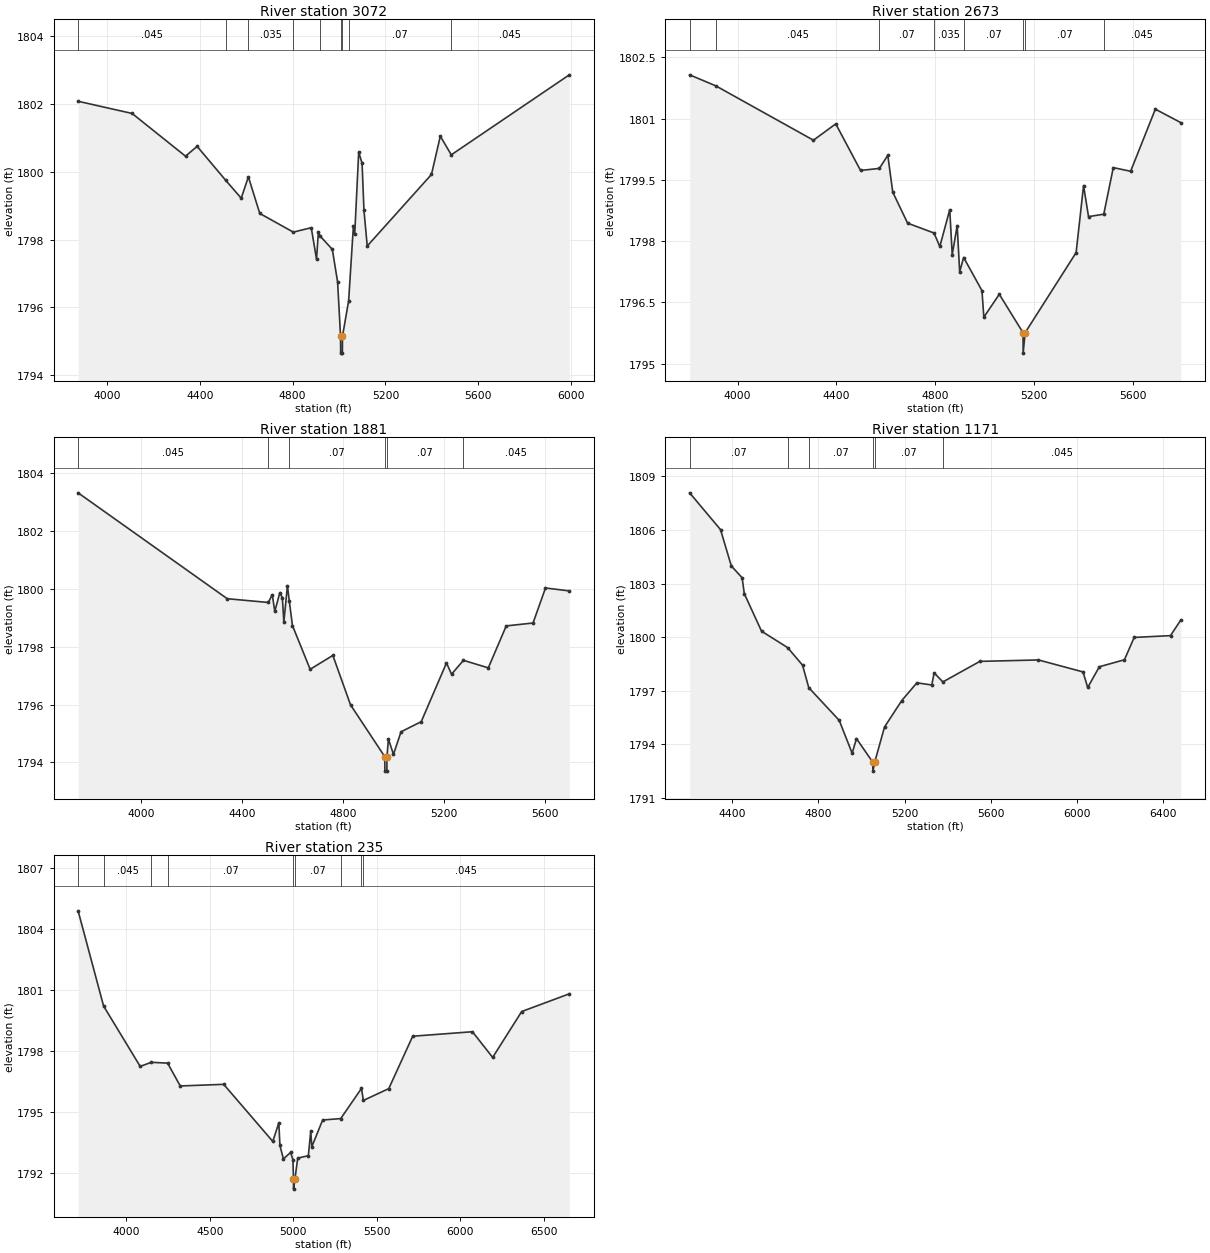
Type RM Length L Ch R = 1,3072,399,399,399
BEGIN DESCRIPTION:
Mapping XS e5c5bc59
END DESCRIPTION:
XS GIS Cut Line= 4
      1490760.11      6879440.77      1490780.95      6878534.54
      1490471.92      6877885.24      1490211.51      6877468.58
#Sta/Elev= 30
  3875.4 1802.08  4108.2 1801.72  4338.3 1800.46  4388.3 1800.75  4511.3 1799.75
  4578.4 1799.22  4609.2 1799.85  4658.4 1798.77  4802.8 1798.22  4880.2 1798.35
  4902.9 1797.42  4910.9 1798.23  4917.6 1798.11  4971.0 1797.71  4993.7 1796.75
  5006.4 1795.15  5006.9 1794.65  5014.3 1794.65  5014.8 1795.15  5041.2 1796.19
  5061.9 1798.41  5067.4 1798.15  5084.6 1800.58  5099.2 1800.25  5107.3 1798.86
  5121.4 1797.81  5398.2 1799.92  5436.3 1801.05  5483.6 1800.50  5992.3 1802.86
#Mann=9,-1,0
  3875.4   0.045       0  4511.3    0.07       0  4609.2   0.035       0
  4802.8    0.07       0  4917.6   0.035       0  5006.4   0.035       0
  5014.8   0.035       0  5041.2    0.07       0  5483.6   0.045       0
Bank Sta=5006.4,5014.8
Exp/Cntr=0.3,0.1

Type RM Length L Ch R = 1,2673,792,792,792
BEGIN DESCRIPTION:
Mapping XS 0ef97777
END DESCRIPTION:
XS GIS Cut Line= 3
      1490919.83      6879527.62      1491062.20      6877836.63
      1491079.56      6877544.92
#Sta/Elev= 30
  3805.5 1802.07  3911.6 1801.80  4306.9 1800.47  4397.2 1800.87  4497.6 1799.73
  4573.9 1799.78  4608.0 1800.10  4628.0 1799.20  4688.2 1798.44  4794.9 1798.20
  4818.7 1797.87  4858.8 1798.77  4868.9 1797.67  4888.9 1798.38  4899.0 1797.25
  4915.1 1797.60  4989.3 1796.79  4996.9 1796.14  5059.5 1796.70  5155.6 1795.76
  5156.1 1795.26  5164.1 1795.76  5370.6 1797.72  5400.7 1799.36  5420.8 1798.60
  5482.5 1798.66  5521.1 1799.80  5591.3 1799.71  5691.4 1801.23  5794.7 1800.90
#Mann=8,-1,0
  3805.5    0.07       0  3911.6   0.045       0  4573.9    0.07       0
  4794.9   0.035       0  4915.1    0.07       0  5155.6    0.07       0
  5164.1    0.07       0  5482.5   0.045       0
Bank Sta=5155.6,5164.1
Exp/Cntr=0.3,0.1

Type RM Length L Ch R = 1,1881,710,710,710
BEGIN DESCRIPTION:
Mapping XS 07d461a9
END DESCRIPTION:
XS GIS Cut Line= 4
      1491801.78      6879374.81      1491680.25      6878805.38
      1491638.58      6877853.99      1491329.75      6877579.86
#Sta/Elev= 30
  3748.9 1803.32  4340.2 1799.66  4502.9 1799.53  4518.7 1799.80  4528.7 1799.22
  4548.7 1799.87  4558.7 1799.69  4564.6 1798.85  4578.8 1800.11  4586.0 1799.59
  4598.8 1798.73  4668.9 1797.22  4758.9 1797.70  4829.0 1795.99  4964.7 1794.20
  4965.2 1793.70  4973.0 1793.70  4973.5 1794.20  4979.1 1794.81  4999.2 1794.28
  5029.2 1795.06  5109.3 1795.41  5209.4 1797.44  5229.4 1797.05  5276.6 1797.53
  5375.2 1797.27  5446.3 1798.72  5552.5 1798.82  5601.9 1800.03  5696.4 1799.93
#Mann=6,-1,0
  3748.9   0.045       0  4502.9   0.035       0  4586.0    0.07       0
  4964.7    0.07       0  4973.5    0.07       0  5276.6   0.045       0
Bank Sta=4964.7,4973.5
Exp/Cntr=0.3,0.1

Type RM Length L Ch R = 1,1171,936,936,936
BEGIN DESCRIPTION:
Mapping XS 84694af1
END DESCRIPTION:
XS GIS Cut Line= 4
      1492211.50      6879201.17      1492253.17      6877982.46
      1491520.53      6877579.68      1491309.36      6877510.45
#Sta/Elev= 30
  4203.1 1808.08  4346.4 1806.02  4396.4 1803.99  4446.4 1803.33  4456.6 1802.44
  4536.5 1800.34  4657.6 1799.42  4726.6 1798.44  4755.5 1797.18  4896.7 1795.35
  4956.7 1793.51  4976.7 1794.33  5052.3 1793.01  5052.8 1792.51  5061.2 1793.01
  5106.8 1794.98  5186.8 1796.46  5256.9 1797.45  5325.9 1797.33  5336.9 1798.01
  5377.3 1797.50  5548.8 1798.65  5820.7 1798.73  6027.2 1798.06  6048.9 1797.19
  6102.9 1798.35  6219.2 1798.74  6264.4 1799.99  6432.8 1800.09  6480.8 1800.97
#Mann=6,-1,0
  4203.1    0.07       0  4657.6   0.035       0  4755.5    0.07       0
  5052.3    0.07       0  5061.2    0.07       0  5377.3   0.045       0
Bank Sta=5052.3,5061.2
Exp/Cntr=0.3,0.1

Type RM Length L Ch R = 1,235,0,0,0
BEGIN DESCRIPTION:
NC Unknown Stream 64 1.0
END DESCRIPTION:
XS GIS Cut Line= 4
      1492860.81      6879329.66      1492897.26      6878256.77
      1492496.22      6877782.81      1491288.93      6877465.37
#Sta/Elev= 30
  3710.7 1804.88  3863.4 1800.21  4082.6 1797.25  4149.4 1797.45  4246.9 1797.41
  4322.7 1796.29  4582.9 1796.37  4876.9 1793.57  4913.2 1794.48  4919.7 1793.37
  4940.6 1792.71  4983.4 1793.03  4997.7 1792.68  5000.8 1791.73  5001.3 1791.23
  5009.7 1791.73  5026.3 1792.75  5090.0 1792.87  5104.3 1794.07  5110.9 1793.31
  5175.6 1794.62  5283.9 1794.69  5408.3 1796.17  5419.6 1795.58  5571.8 1796.16
  5715.1 1798.73  6073.1 1798.95  6194.1 1797.69  6368.0 1799.94  6653.4 1800.81
#Mann=9,-1,0
  3710.7    0.07       0  3863.4   0.045       0  4149.4   0.035       0
  4246.9    0.07       0  5000.8    0.07       0  5009.7    0.07       0
  5283.9   0.045       0  5408.3    0.07       0  5419.6   0.045       0
Bank Sta=5000.8,5009.7
Exp/Cntr=0.3,0.1

Chan Stop Cuts=-1