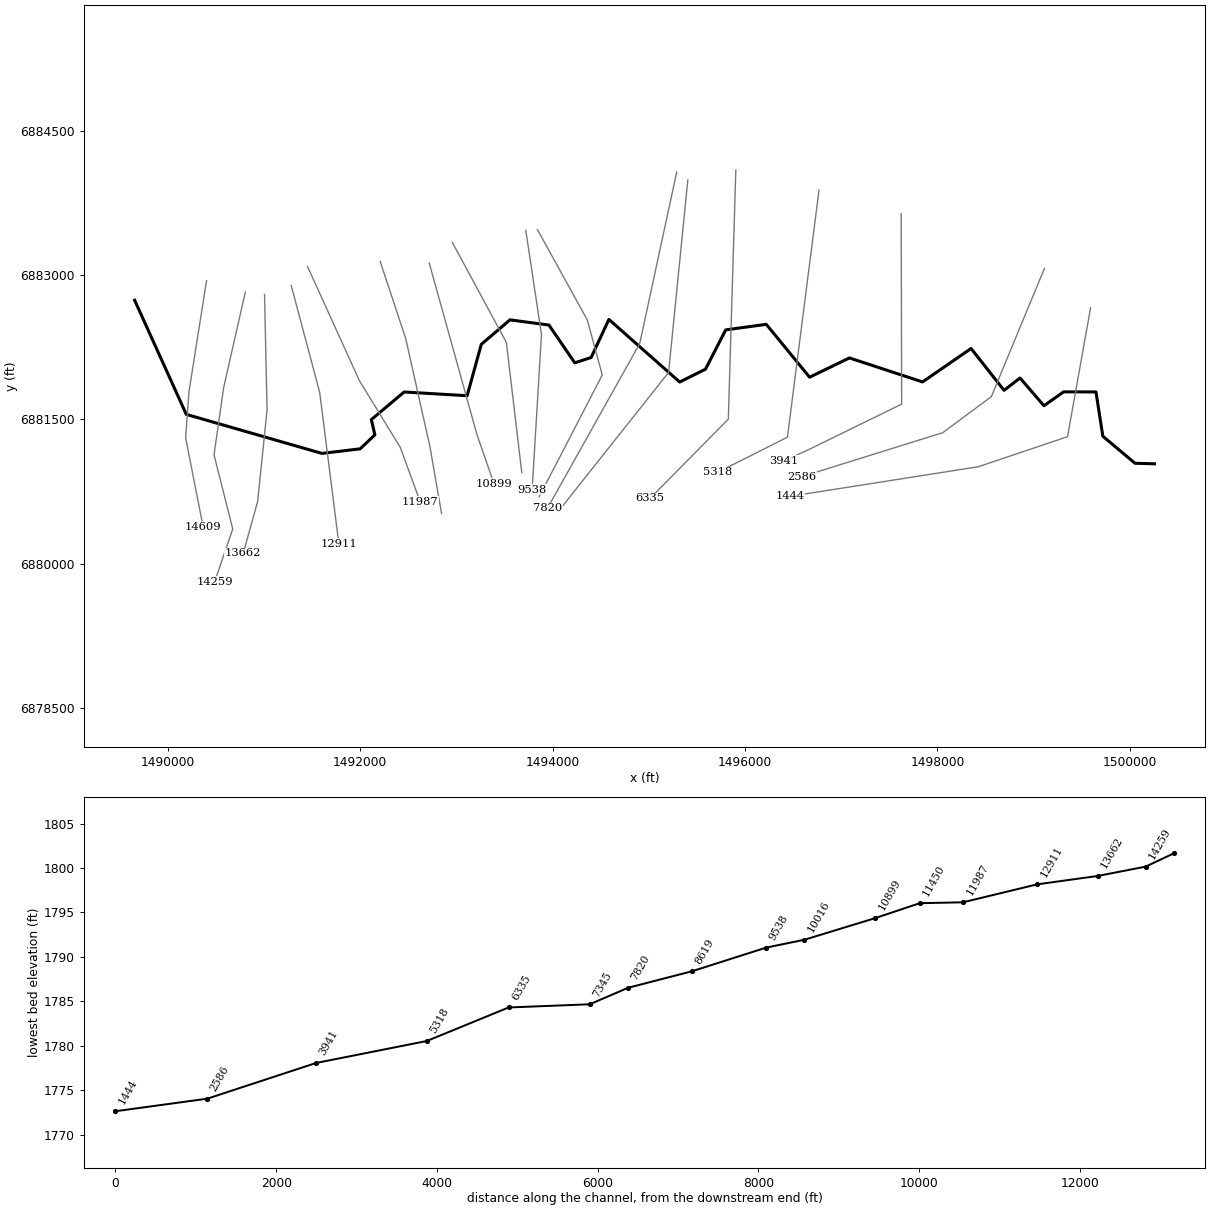
--- NC Unknown Stream 65.prj (project) ---

Proj Title=NC Unknown Stream 65 Base Level Engineering
Current Plan=p01
Default Exp/Contr=0.3,0.1
English Units
Geom File=g01
Flow File=f01
Plan File=p01
BEGIN DESCRIPTION:
NC Unknown Stream 65
END DESCRIPTION:

--- NC Unknown Stream 65.p01 (plan) ---

Plan Title=Multiple Run
Short Identifier=Multiple
Geom File=g01
Flow File=f01
Subcritical Flow
K Sum by GR= 0
Std Step Tol= 0.01
Critical Tol= 0.01
Num of Std Step Trials= 20
Max Error Tol= 0.3
Flow Tol Ratio= 0.001
Split Flow NTrial= 30
Split Flow Tol= 0.02
Split Flow Ratio= 0.02
Log Output Level= 0
Friction Slope Method= 1
Unsteady Friction Slope Method= 2
Unsteady Bridges Friction Slope Method= 1
Parabolic Critical Depth
Global Vel Dist=  1 , 1 , 1
Global Log Level= 0
CheckData=True
Encroach Param= -1, 0, 0, 0
BEGIN DESCRIPTION:
Multiple Run
END DESCRIPTION:

--- NC Unknown Stream 65.f01 (steady flow) ---

Flow Title=Multiple
Number of Profiles=7
Profile Names=10-year,25-year,50-year,1pct_min,100-year,1pct_plu,500-year
River Rch & RM= NC Unknown Strea,Reach-1,14609
     325     452     556     340     678    1353    1021
River Rch & RM= NC Unknown Strea,Reach-1,7820
     551     782     976     604    1204    2403    1857
Boundary for River Rch & Prof#=NC Unknown Strea,Reach-1,1
Up Type=0
Dn Type=3
Dn Slope=0.001
Boundary for River Rch & Prof#=NC Unknown Strea,Reach-1,2
Up Type=0
Dn Type=3
Dn Slope=0.001
Boundary for River Rch & Prof#=NC Unknown Strea,Reach-1,3
Up Type=0
Dn Type=3
Dn Slope=0.001
Boundary for River Rch & Prof#=NC Unknown Strea,Reach-1,4
Up Type=0
Dn Type=3
Dn Slope=0.001
Boundary for River Rch & Prof#=NC Unknown Strea,Reach-1,5
Up Type=0
Dn Type=3
Dn Slope=0.001
Boundary for River Rch & Prof#=NC Unknown Strea,Reach-1,6
Up Type=0
Dn Type=3
Dn Slope=0.001
Boundary for River Rch & Prof#=NC Unknown Strea,Reach-1,7
Up Type=0
Dn Type=3
Dn Slope=0.001

--- NC Unknown Stream 65.g01 (geometry) ---

Geom Title=Existing Conditions

River Reach=NC Unknown Strea,Reach-1
Reach XY= 30
      1489655.00      6882738.00      1490191.76      6881551.61
      1491601.68      6881146.04      1491999.37      6881193.59
      1492151.96      6881339.42      1492115.18      6881497.71
      1492456.45      6881784.47      1493111.19      6881745.75
      1493258.07      6882279.70      1493556.55      6882534.25
      1493961.19      6882480.18      1494229.69      6882087.39
      1494399.89      6882143.11      1494584.50      6882538.69
      1495320.34      6881887.95      1495588.37      6882021.29
      1495798.79      6882430.20      1496220.41      6882487.68
      1496670.36      6881937.90      1497084.39      6882138.50
      1497844.71      6881889.01      1498349.12      6882236.47
      1498691.61      6881801.50      1498858.10      6881930.23
      1499106.65      6881641.10      1499310.85      6881785.94
      1499647.46      6881784.94      1499718.62      6881324.76
      1500052.70      6881043.83      1500255.00      6881038.00

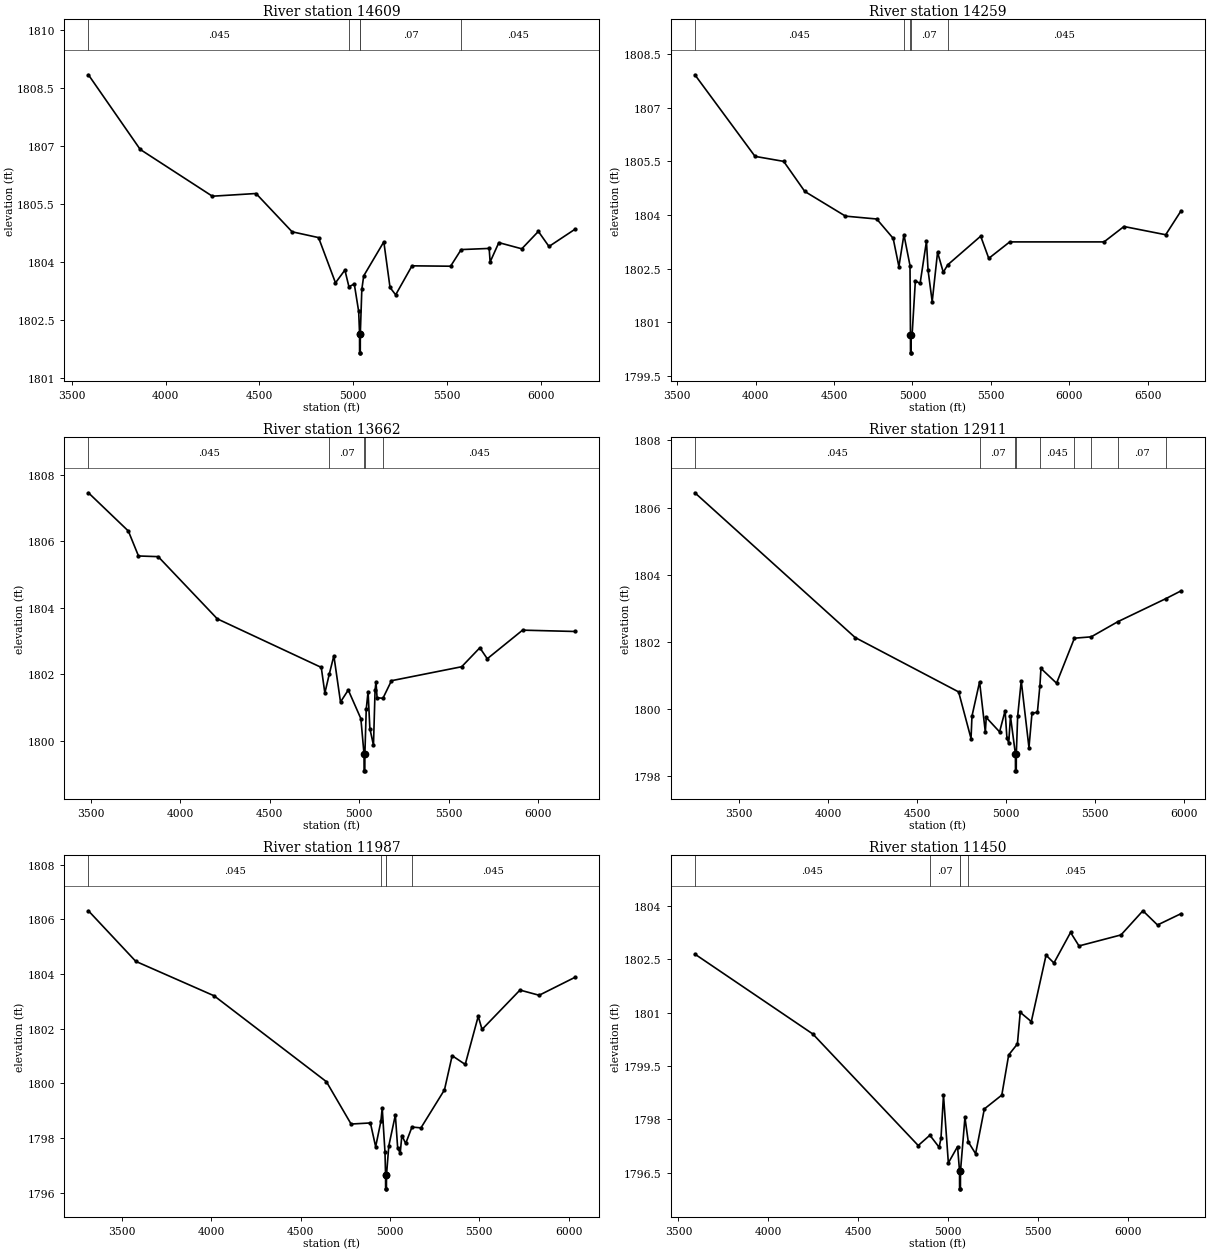
Type RM Length L Ch R = 1,14609,350,350,350
BEGIN DESCRIPTION:
Mapping XS f7b14873
END DESCRIPTION:
XS GIS Cut Line= 4
      1490401.91      6882940.69      1490219.62      6881786.19
      1490184.89      6881308.76      1490366.89      6880381.45
#Sta/Elev= 30
  3588.6 1808.83  3864.7 1806.90  4249.4 1805.69  4482.2 1805.76  4674.6 1804.77
  4815.7 1804.62  4906.0 1803.45  4956.1 1803.78  4977.6 1803.35  5006.2 1803.42
  5029.6 1802.71  5034.3 1802.14  5034.5 1801.64  5038.1 1801.64  5038.4 1802.14
  5046.4 1803.28  5056.4 1803.63  5163.7 1804.51  5196.8 1803.33  5226.8 1803.14
  5313.9 1803.89  5519.7 1803.88  5576.1 1804.31  5725.4 1804.34  5730.5 1803.99
  5776.9 1804.49  5899.3 1804.33  5987.7 1804.78  6044.3 1804.39  6181.1 1804.83
#Mann=5,-1,0
  3588.6   0.045       0  4977.6    0.07       0  5034.3    0.07       0
  5038.4    0.07       0  5576.1   0.045       0
Bank Sta=5034.3,5038.4
Exp/Cntr=0.3,0.1

Type RM Length L Ch R = 1,14259,597,597,597
BEGIN DESCRIPTION:
Mapping XS b329dd12
END DESCRIPTION:
XS GIS Cut Line= 5
      1490805.57      6882823.57      1490579.86      6881829.60
      1490480.03      6881130.81      1490674.70      6880360.59
      1490486.87      6879813.64
#Sta/Elev= 30
  3613.5 1807.92  3996.7 1805.64  4179.3 1805.50  4313.7 1804.66  4572.9 1803.97
  4772.0 1803.89  4876.8 1803.35  4913.4 1802.56  4945.4 1803.45  4984.1 1802.59
  4987.0 1800.65  4987.3 1800.15  4991.0 1800.15  4991.3 1800.65  4998.0 1800.69
  5018.2 1802.16  5048.5 1802.09  5089.0 1803.27  5099.1 1802.46  5125.5 1801.58
  5159.7 1802.96  5196.2 1802.40  5224.5 1802.61  5434.4 1803.41  5486.0 1802.79
  5619.5 1803.25  6220.4 1803.25  6347.3 1803.68  6613.2 1803.45  6711.4 1804.12
#Mann=5,-1,0
  3613.5   0.045       0  4945.4    0.07       0  4987.0    0.07       0
  4991.3    0.07       0  5224.5   0.045       0
Bank Sta=4987,4991.3
Exp/Cntr=0.3,0.1

Type RM Length L Ch R = 1,13662,751,751,751
BEGIN DESCRIPTION:
Mapping XS e7eaf221
END DESCRIPTION:
XS GIS Cut Line= 4
      1491005.21      6882797.52      1491031.25      6881595.22
      1490933.41      6880646.57      1490783.75      6880107.94
#Sta/Elev= 30
  3488.1 1807.46  3711.1 1806.31  3767.7 1805.56  3877.7 1805.54  4207.8 1803.67
  4788.4 1802.21  4808.5 1801.44  4833.8 1802.02  4858.8 1802.56  4895.9 1801.17
  4939.2 1801.53  5009.6 1800.67  5027.3 1799.60  5027.6 1799.10  5031.7 1799.10
  5032.0 1799.60  5039.7 1800.96  5049.8 1801.48  5059.9 1800.37  5080.0 1799.87
  5088.9 1801.52  5093.9 1801.78  5100.1 1801.30  5132.7 1801.28  5180.5 1801.81
  5572.6 1802.23  5674.0 1802.80  5715.5 1802.47  5912.7 1803.33  6203.4 1803.29
#Mann=5,-1,0
  3488.1   0.045       0  4833.8    0.07       0  5027.3    0.07       0
  5032.0    0.07       0  5132.7   0.045       0
Bank Sta=5027.3,5032
Exp/Cntr=0.3,0.1

Type RM Length L Ch R = 1,12911,924,924,924
BEGIN DESCRIPTION:
Mapping XS 838fa5a2
END DESCRIPTION:
XS GIS Cut Line= 3
      1491282.99      6882888.60      1491578.12      6881781.85
      1491777.77      6880206.38
#Sta/Elev= 30
  3250.6 1806.44  4151.6 1802.13  4733.4 1800.51  4803.1 1799.12  4808.4 1799.79
  4851.2 1800.81  4883.5 1799.31  4888.5 1799.75  4963.6 1799.32  4994.6 1799.95
  5004.7 1799.15  5014.8 1798.99  5024.9 1799.78  5052.6 1798.66  5053.0 1798.16
  5057.3 1798.16  5057.7 1798.66  5065.2 1799.78  5085.3 1800.84  5128.8 1798.85
  5145.8 1799.88  5176.1 1799.90  5190.4 1800.70  5196.2 1801.21  5283.9 1800.77
  5384.3 1802.11  5478.7 1802.15  5627.9 1802.60  5899.2 1803.29  5984.1 1803.52
#Mann=9,-1,0
  3250.6   0.045       0  4851.2    0.07       0  5052.6    0.07       0
  5057.7    0.07       0  5190.4   0.045       0  5384.3    0.07       0
  5478.7   0.045       0  5627.9    0.07       0  5899.2   0.045       0
Bank Sta=5052.6,5057.7
Exp/Cntr=0.3,0.1

Type RM Length L Ch R = 1,11987,537,537,537
BEGIN DESCRIPTION:
Mapping XS 7ff0787b
END DESCRIPTION:
XS GIS Cut Line= 4
      1491452.26      6883088.27      1491990.45      6881903.38
      1492415.80      6881208.94      1492623.65      6880641.66
#Sta/Elev= 30
  3313.2 1806.31  3578.2 1804.46  4016.4 1803.20  4644.4 1800.06  4782.6 1798.51
  4890.6 1798.55  4920.0 1797.68  4949.3 1798.61  4956.7 1799.10  4972.2 1797.48
  4975.4 1796.64  4975.8 1796.14  4980.2 1796.14  4980.6 1796.64  4993.5 1797.71
  5030.2 1798.84  5043.1 1797.64  5057.4 1797.44  5066.5 1798.09  5088.2 1797.80
  5123.1 1798.40  5173.4 1798.37  5304.9 1799.76  5348.0 1801.01  5421.0 1800.69
  5493.8 1802.45  5515.1 1801.97  5727.3 1803.41  5834.6 1803.22  6033.1 1803.87
#Mann=5,-1,0
  3313.2   0.045       0  4949.3    0.07       0  4975.4    0.07       0
  4980.6    0.07       0  5123.1   0.045       0
Bank Sta=4975.4,4980.6
Exp/Cntr=0.3,0.1

Type RM Length L Ch R = 1,11450,551,551,551
BEGIN DESCRIPTION:
Mapping XS 4287417c
END DESCRIPTION:
XS GIS Cut Line= 4
      1492207.45      6883140.39      1492472.22      6882341.75
      1492723.96      6881217.62      1492845.48      6880518.87
#Sta/Elev= 30
  3591.1 1802.65  4246.8 1800.40  4832.5 1797.26  4897.3 1797.55  4948.7 1797.21
  4959.0 1797.46  4972.9 1798.68  5000.0 1796.77  5051.2 1797.23  5062.1 1796.54
  5062.5 1796.04  5067.0 1796.04  5067.4 1796.54  5092.2 1798.05  5110.8 1797.36
  5151.5 1797.03  5200.0 1798.29  5297.1 1798.68  5335.3 1799.81  5383.8 1800.12
  5399.6 1801.01  5461.1 1800.75  5543.1 1802.62  5586.8 1802.40  5679.3 1803.26
  5726.2 1802.88  5959.6 1803.19  6081.4 1803.87  6162.6 1803.47  6293.7 1803.79
#Mann=5,-1,0
  3591.1   0.045       0  4897.3    0.07       0  5062.1    0.07       0
  5067.4    0.07       0  5110.8   0.045       0
Bank Sta=5062.1,5067.4
Exp/Cntr=0.3,0.1

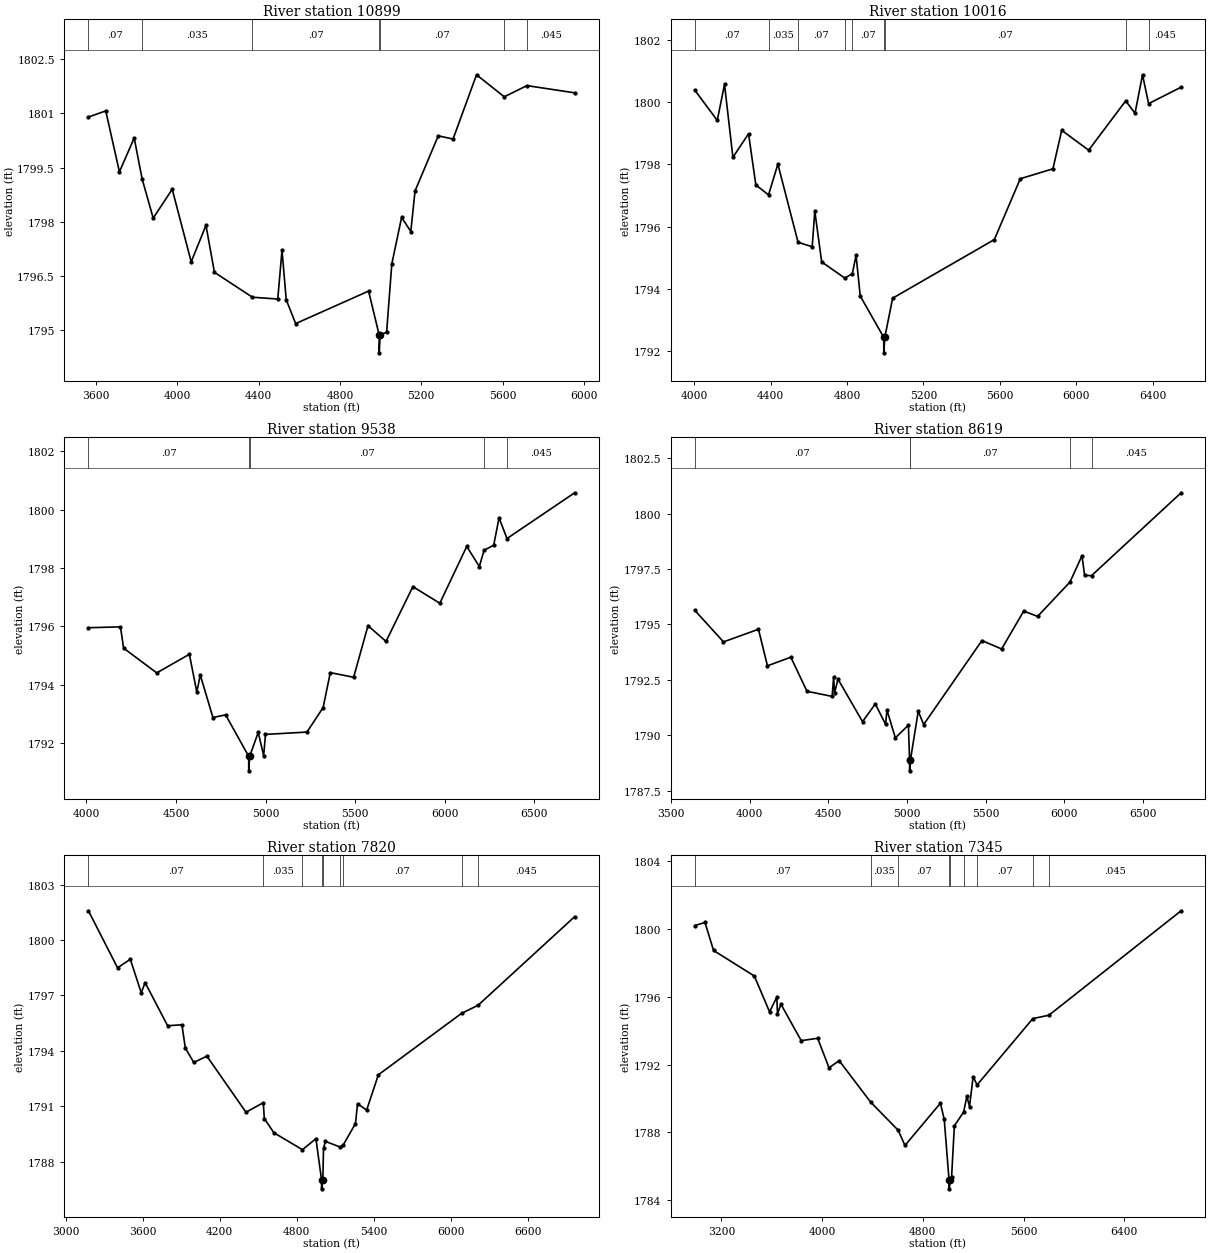
Type RM Length L Ch R = 1,10899,883,883,883
BEGIN DESCRIPTION:
Mapping XS 49840dca
END DESCRIPTION:
XS GIS Cut Line= 3
      1492717.00      6883124.78      1493213.54      6881340.01
      1493389.73      6880832.16
#Sta/Elev= 30
  3563.6 1800.90  3648.9 1801.07  3716.0 1799.38  3788.6 1800.32  3827.5 1799.19
  3882.0 1798.10  3975.5 1798.90  4068.9 1796.89  4141.5 1797.90  4183.0 1796.60
  4369.7 1795.91  4494.4 1795.86  4515.2 1797.21  4536.0 1795.84  4582.4 1795.18
  4940.8 1796.08  4992.6 1794.87  4993.0 1794.37  4997.9 1794.87  5029.4 1794.94
  5054.9 1796.83  5103.1 1798.12  5148.4 1797.73  5169.1 1798.85  5283.3 1800.38
  5356.0 1800.29  5471.4 1802.07  5607.8 1801.46  5719.2 1801.77  5953.7 1801.57
#Mann=7,-1,0
  3563.6    0.07       0  3827.5   0.035       0  4369.7    0.07       0
  4992.6    0.07       0  4997.9    0.07       0  5607.8   0.035       0
  5719.2   0.045       0
Bank Sta=4992.6,4997.9
Exp/Cntr=0.3,0.1

Type RM Length L Ch R = 1,10016,478,478,478
BEGIN DESCRIPTION:
Mapping XS 4201efe3
END DESCRIPTION:
XS GIS Cut Line= 3
      1492956.58      6883340.04      1493519.10      6882298.35
      1493678.82      6880947.62
#Sta/Elev= 30
  4004.1 1800.39  4121.1 1799.42  4159.2 1800.58  4203.0 1798.23  4284.9 1798.99
  4323.0 1797.34  4389.5 1797.02  4438.3 1798.01  4544.1 1795.49  4618.0 1795.35
  4631.5 1796.50  4667.5 1794.86  4788.2 1794.34  4827.9 1794.48  4847.4 1795.07
  4869.3 1793.76  4992.2 1792.43  4992.6 1791.93  4997.8 1792.43  5038.7 1793.69
  5571.0 1795.58  5706.7 1797.54  5877.5 1797.86  5923.4 1799.10  6064.4 1798.46
  6258.2 1800.05  6306.9 1799.65  6346.3 1800.89  6378.0 1799.96  6548.1 1800.49
#Mann=9,-1,0
  4004.1    0.07       0  4389.5   0.035       0  4544.1    0.07       0
  4788.2   0.035       0  4827.9    0.07       0  4992.2    0.07       0
  4997.8    0.07       0  6258.2   0.035       0  6378.0   0.045       0
Bank Sta=4992.2,4997.8
Exp/Cntr=0.3,0.1

Type RM Length L Ch R = 1,9538,919,919,919
BEGIN DESCRIPTION:
Mapping XS 7d10e7dd
END DESCRIPTION:
XS GIS Cut Line= 3
      1493720.49      6883465.01      1493883.68      6882381.68
      1493786.46      6880767.06
#Sta/Elev= 30
  4011.8 1795.95  4190.8 1795.98  4208.0 1795.25  4393.1 1794.40  4575.1 1795.04
  4616.7 1793.74  4635.8 1794.33  4706.6 1792.87  4777.4 1792.96  4906.0 1791.54
  4906.4 1791.04  4911.7 1791.54  4959.4 1792.36  4989.7 1791.56  4999.8 1792.29
  5231.3 1792.37  5321.4 1793.21  5361.5 1794.41  5491.7 1794.25  5571.9 1796.02
  5672.4 1795.48  5822.3 1797.36  5972.6 1796.79  6122.9 1798.74  6193.0 1798.05
  6219.8 1798.61  6273.1 1798.78  6303.2 1799.72  6347.4 1799.01  6724.9 1800.58
#Mann=5,-1,0
  4011.8    0.07       0  4906.0    0.07       0  4911.7    0.07       0
  6219.8   0.035       0  6347.4   0.045       0
Bank Sta=4906,4911.7
Exp/Cntr=0.3,0.1

Type RM Length L Ch R = 1,8619,799,799,799
BEGIN DESCRIPTION:
Mapping XS 7efe11ce
END DESCRIPTION:
XS GIS Cut Line= 4
      1493842.00      6883471.98      1494359.37      6882534.46
      1494515.62      6881961.54      1493859.67      6880694.75
#Sta/Elev= 30
  3651.1 1795.63  3833.0 1794.21  4055.3 1794.78  4112.5 1793.13  4261.0 1793.52
  4363.8 1791.98  4523.7 1791.75  4533.2 1792.62  4538.9 1791.90  4560.7 1792.53
  4717.0 1790.61  4798.1 1791.41  4863.4 1790.49  4872.4 1791.13  4925.5 1789.88
  5008.5 1790.45  5016.0 1788.89  5016.4 1788.39  5021.7 1788.89  5071.1 1791.08
  5105.6 1790.48  5476.0 1794.27  5601.3 1793.89  5741.6 1795.60  5830.1 1795.36
  6035.6 1796.91  6112.3 1798.10  6128.8 1797.21  6172.7 1797.20  6742.3 1800.94
#Mann=5,-1,0
  3651.1    0.07       0  5016.0    0.07       0  5021.7    0.07       0
  6035.6   0.035       0  6172.7   0.045       0
Bank Sta=5016,5021.7
Exp/Cntr=0.3,0.1

Type RM Length L Ch R = 1,7820,475,475,475
BEGIN DESCRIPTION:
NC Unknown Stream 65 5.0
END DESCRIPTION:
XS GIS Cut Line= 3
      1495289.22      6884069.83      1494905.00      6882288.00
      1493945.50      6880575.11
#Sta/Elev= 30
  3177.4 1801.59  3404.3 1798.50  3503.7 1798.96  3588.5 1797.15  3619.2 1797.69
  3794.3 1795.36  3905.6 1795.41  3932.0 1794.15  3997.7 1793.37  4100.0 1793.71
  4404.5 1790.67  4539.1 1791.19  4547.2 1790.33  4621.7 1789.56  4844.1 1788.64
  4949.0 1789.24  4992.5 1787.02  4993.0 1786.52  5002.8 1787.02  5008.2 1788.73
  5023.1 1789.09  5140.0 1788.78  5161.9 1788.90  5257.0 1790.06  5273.0 1791.13
  5344.0 1790.79  5435.1 1792.70  6082.9 1796.03  6212.0 1796.47  6963.5 1801.27
#Mann=9,-1,0
  3177.4    0.07       0  4539.1   0.035       0  4844.1    0.07       0
  4992.5    0.07       0  5002.8    0.07       0  5140.0   0.035       0
  5161.9    0.07       0  6082.9   0.035       0  6212.0   0.045       0
Bank Sta=4992.5,5002.8
Exp/Cntr=0.3,0.1

Type RM Length L Ch R = 1,7345,1010,1010,1010
BEGIN DESCRIPTION:
NC Unknown Stream 65 4.0
END DESCRIPTION:
XS GIS Cut Line= 3
      1495405.00      6883987.96      1495205.00      6881988.00
      1494055.01      6880538.01
#Sta/Elev= 30
  2989.8 1800.20  3070.2 1800.38  3138.0 1798.73  3462.1 1797.22  3582.7 1795.11
  3640.5 1795.98  3645.5 1794.99  3673.2 1795.56  3833.9 1793.41  3964.6 1793.55
  4055.0 1791.81  4135.4 1792.23  4385.9 1789.78  4603.4 1788.13  4658.0 1787.23
  4939.4 1789.72  4969.6 1788.77  5008.1 1785.17  5008.6 1784.67  5018.6 1785.17
  5027.8 1785.34  5050.2 1788.39  5123.7 1789.20  5149.6 1790.13  5170.4 1789.52
  5199.2 1791.29  5230.5 1790.80  5673.0 1794.71  5800.8 1794.91  6850.4 1801.07
#Mann=9,-1,0
  2989.8    0.07       0  4385.9   0.035       0  4603.4    0.07       0
  5008.1    0.07       0  5018.6    0.07       0  5123.7   0.035       0
  5230.5    0.07       0  5673.0   0.035       0  5800.8   0.045       0
Bank Sta=5008.1,5018.6
Exp/Cntr=0.3,0.1

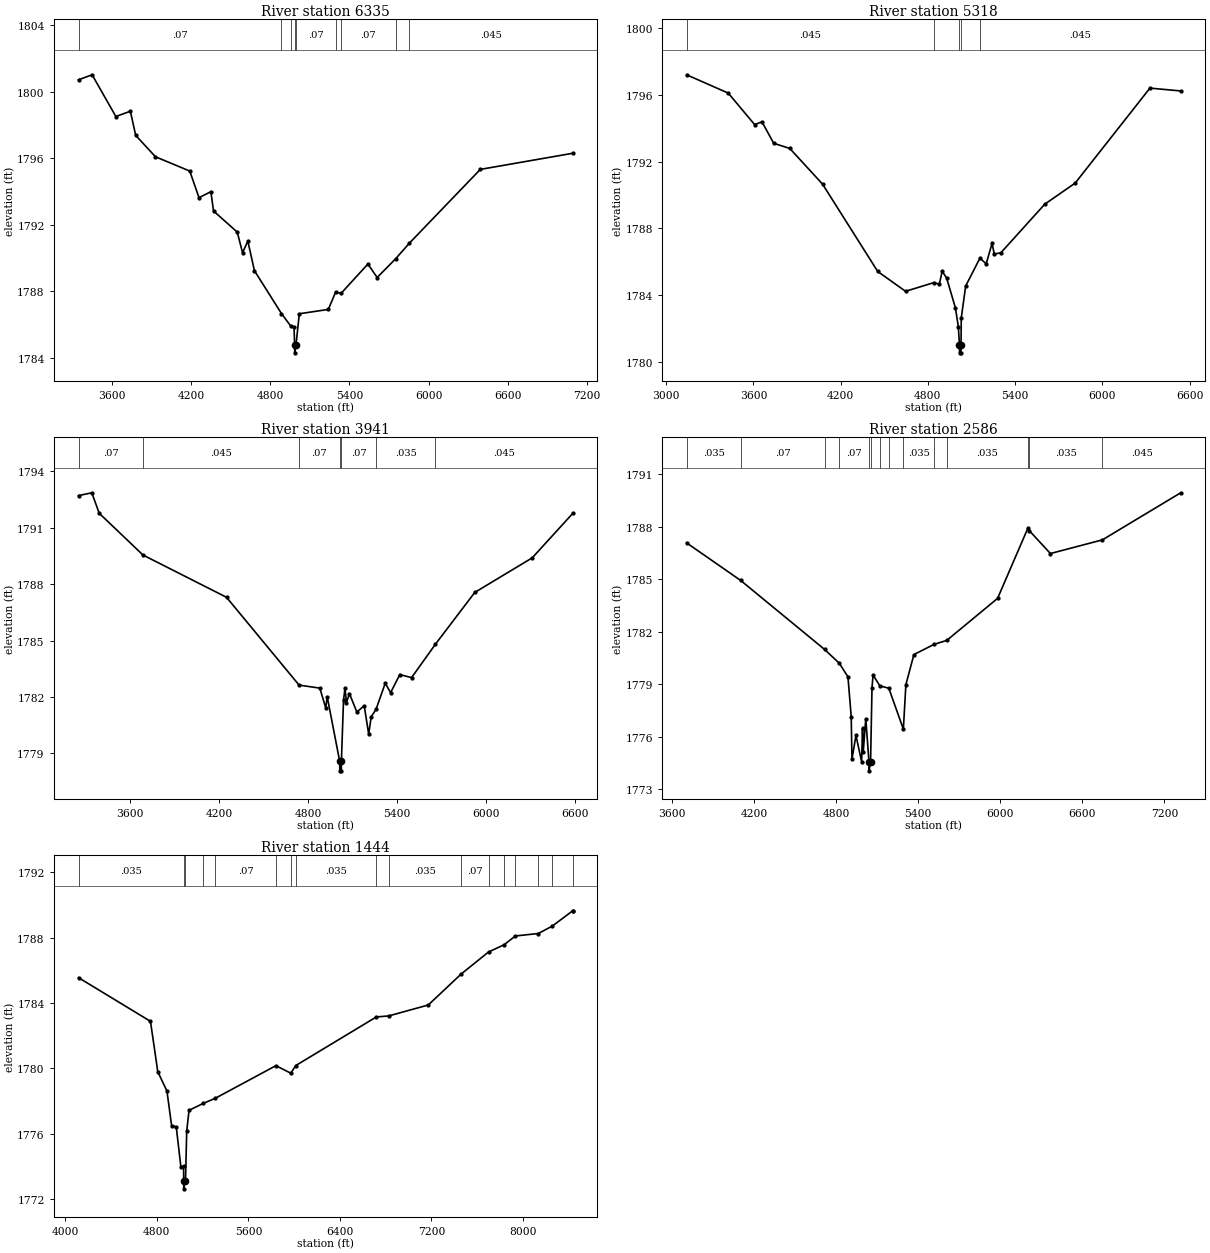
Type RM Length L Ch R = 1,6335,1017,1017,1017
BEGIN DESCRIPTION:
NC Unknown Stream 65 3.0
END DESCRIPTION:
XS GIS Cut Line= 3
      1495903.82      6884090.69      1495825.69      6881502.17
      1495013.22      6880679.28
#Sta/Elev= 30
  3347.0 1800.73  3449.7 1801.03  3629.8 1798.52  3739.9 1798.84  3779.9 1797.39
  3930.0 1796.10  4190.1 1795.24  4260.1 1793.64  4350.1 1794.00  4370.2 1792.84
  4550.2 1791.57  4590.3 1790.33  4630.3 1791.03  4680.3 1789.25  4885.4 1786.67
  4955.0 1785.93  4980.4 1785.86  4985.0 1784.81  4985.5 1784.31  4995.8 1784.81
  5020.5 1786.66  5240.6 1786.92  5296.7 1787.98  5336.4 1787.88  5540.7 1789.65
  5610.7 1788.84  5751.3 1789.97  5855.6 1790.91  6392.7 1795.34  7093.1 1796.31
#Mann=9,-1,0
  3347.0    0.07       0  4885.4   0.035       0  4955.0    0.07       0
  4985.0    0.07       0  4995.8    0.07       0  5296.7   0.035       0
  5336.4    0.07       0  5751.3   0.035       0  5855.6   0.045       0
Bank Sta=4985,4995.8
Exp/Cntr=0.3,0.1

Type RM Length L Ch R = 1,5318,1377,1377,1377
BEGIN DESCRIPTION:
NC Unknown Stream 65 2.0
END DESCRIPTION:
XS GIS Cut Line= 3
      1496768.40      6883882.39      1496440.28      6881314.67
      1495716.30      6880950.07
#Sta/Elev= 30
  3140.2 1797.22  3426.9 1796.12  3608.4 1794.23  3658.8 1794.40  3739.4 1793.11
  3850.3 1792.80  4075.7 1790.66  4455.2 1785.42  4646.7 1784.23  4840.2 1784.75
  4878.6 1784.66  4898.8 1785.43  4929.0 1785.03  4989.5 1783.24  5009.7 1782.11
  5017.4 1781.04  5017.9 1780.54  5027.8 1780.54  5028.3 1781.04  5029.8 1782.63
  5060.1 1784.55  5158.1 1786.22  5201.2 1785.88  5241.5 1787.10  5257.2 1786.47
  5302.0 1786.54  5604.5 1789.46  5813.1 1790.72  6327.7 1796.42  6539.4 1796.25
#Mann=5,-1,0
  3140.2   0.045       0  4840.2    0.07       0  5017.4    0.07       0
  5028.3    0.07       0  5158.1   0.045       0
Bank Sta=5017.4,5028.3
Exp/Cntr=0.3,0.1

Type RM Length L Ch R = 1,3941,1355,1355,1355
BEGIN DESCRIPTION:
Mapping XS 983758b1
END DESCRIPTION:
XS GIS Cut Line= 4
      1497622.57      6883637.54      1497627.78      6881658.42
      1496659.03      6881184.46      1496403.78      6881069.86
#Sta/Elev= 30
  3250.3 1792.71  3339.8 1792.86  3389.8 1791.77  3685.3 1789.55  4249.8 1787.30
  4739.7 1782.63  4879.8 1782.47  4919.8 1781.42  4929.8 1782.01  5014.2 1778.57
  5014.7 1778.07  5025.0 1778.07  5025.5 1778.57  5039.8 1781.82  5049.8 1782.47
  5059.8 1781.70  5079.8 1782.18  5129.8 1781.20  5179.8 1781.53  5209.8 1780.03
  5227.1 1780.95  5259.5 1781.34  5321.6 1782.73  5358.0 1782.23  5420.0 1783.19
  5499.7 1783.03  5661.1 1784.81  5926.4 1787.56  6314.6 1789.40  6587.7 1791.76
#Mann=7,-1,0
  3250.3    0.07       0  3685.3   0.045       0  4739.7    0.07       0
  5014.2    0.07       0  5025.5    0.07       0  5259.5   0.035       0
  5661.1   0.045       0
Bank Sta=5014.2,5025.5
Exp/Cntr=0.3,0.1

Type RM Length L Ch R = 1,2586,1142,1142,1142
BEGIN DESCRIPTION:
Mapping XS 1f214133
END DESCRIPTION:
XS GIS Cut Line= 4
      1499112.17      6883069.92      1498560.07      6881736.54
      1498054.86      6881361.54      1496586.15      6880903.22
#Sta/Elev= 30
  3707.6 1787.07  4101.7 1784.93  4716.6 1780.98  4824.0 1780.19  4886.8 1779.42
  4910.7 1777.14  4916.1 1774.72  4945.4 1776.07  4986.8 1774.57  4993.2 1776.47
  4998.6 1775.14  5017.1 1777.03  5040.6 1774.55  5041.1 1774.05  5052.1 1774.55
  5062.6 1778.80  5070.3 1779.52  5120.2 1778.90  5185.4 1778.77  5291.7 1776.43
  5310.2 1778.97  5368.7 1780.69  5514.9 1781.27  5609.0 1781.50  5980.3 1783.90
  6201.2 1787.90  6211.7 1787.77  6366.4 1786.46  6746.1 1787.24  7318.5 1789.93
#Mann=14,-1,0
  3707.6   0.035       0  4101.7    0.07       0  4716.6   0.035       0
  4824.0    0.07       0  5040.6    0.07       0  5052.1    0.07       0
  5120.2    0.16       0  5185.4    0.07       0  5291.7   0.035       0
  5514.9    0.07       0  5609.0   0.035       0  6201.2    0.07       0
  6211.7   0.035       0  6746.1   0.045       0
Bank Sta=5040.6,5052.1
Exp/Cntr=0.3,0.1

Type RM Length L Ch R = 1,1444,0,0,0
BEGIN DESCRIPTION:
NC Unknown Stream 65 1.0
END DESCRIPTION:
XS GIS Cut Line= 4
      1499591.32      6882658.42      1499351.74      6881319.87
      1498424.65      6881007.37      1496468.15      6880700.37
#Sta/Elev= 30
  4115.8 1785.55  4744.3 1782.88  4808.2 1779.80  4888.3 1778.62  4928.9 1776.51
  4969.6 1776.43  5010.2 1773.97  5033.5 1774.03  5034.8 1773.14  5035.3 1772.64
  5046.5 1773.14  5050.8 1773.17  5061.0 1776.18  5081.3 1777.44  5204.5 1777.86
  5309.1 1778.17  5840.7 1780.17  5970.8 1779.71  6014.5 1780.18  6718.6 1783.15
  6825.1 1783.21  7172.3 1783.88  7459.2 1785.77  7698.8 1787.12  7834.2 1787.56
  7933.9 1788.10  8133.5 1788.25  8255.4 1788.70  8432.8 1789.63  8434.4 1789.64
#Mann=17,-1,0
  4115.8   0.035       0  5034.8   0.035       0  5046.5   0.035       0
  5204.5    0.16       0  5309.1    0.07       0  5840.7   0.035       0
  5970.8    0.07       0  6014.5   0.035       0  6718.6    0.07       0
  6825.1   0.035       0  7459.2    0.07       0  7698.8   0.035       0
  7834.2    0.07       0  7933.9   0.045       0  8133.5   0.035       0
  8255.4   0.045       0  8432.8   0.035       0
Bank Sta=5034.8,5046.5
Exp/Cntr=0.3,0.1

Chan Stop Cuts=-1