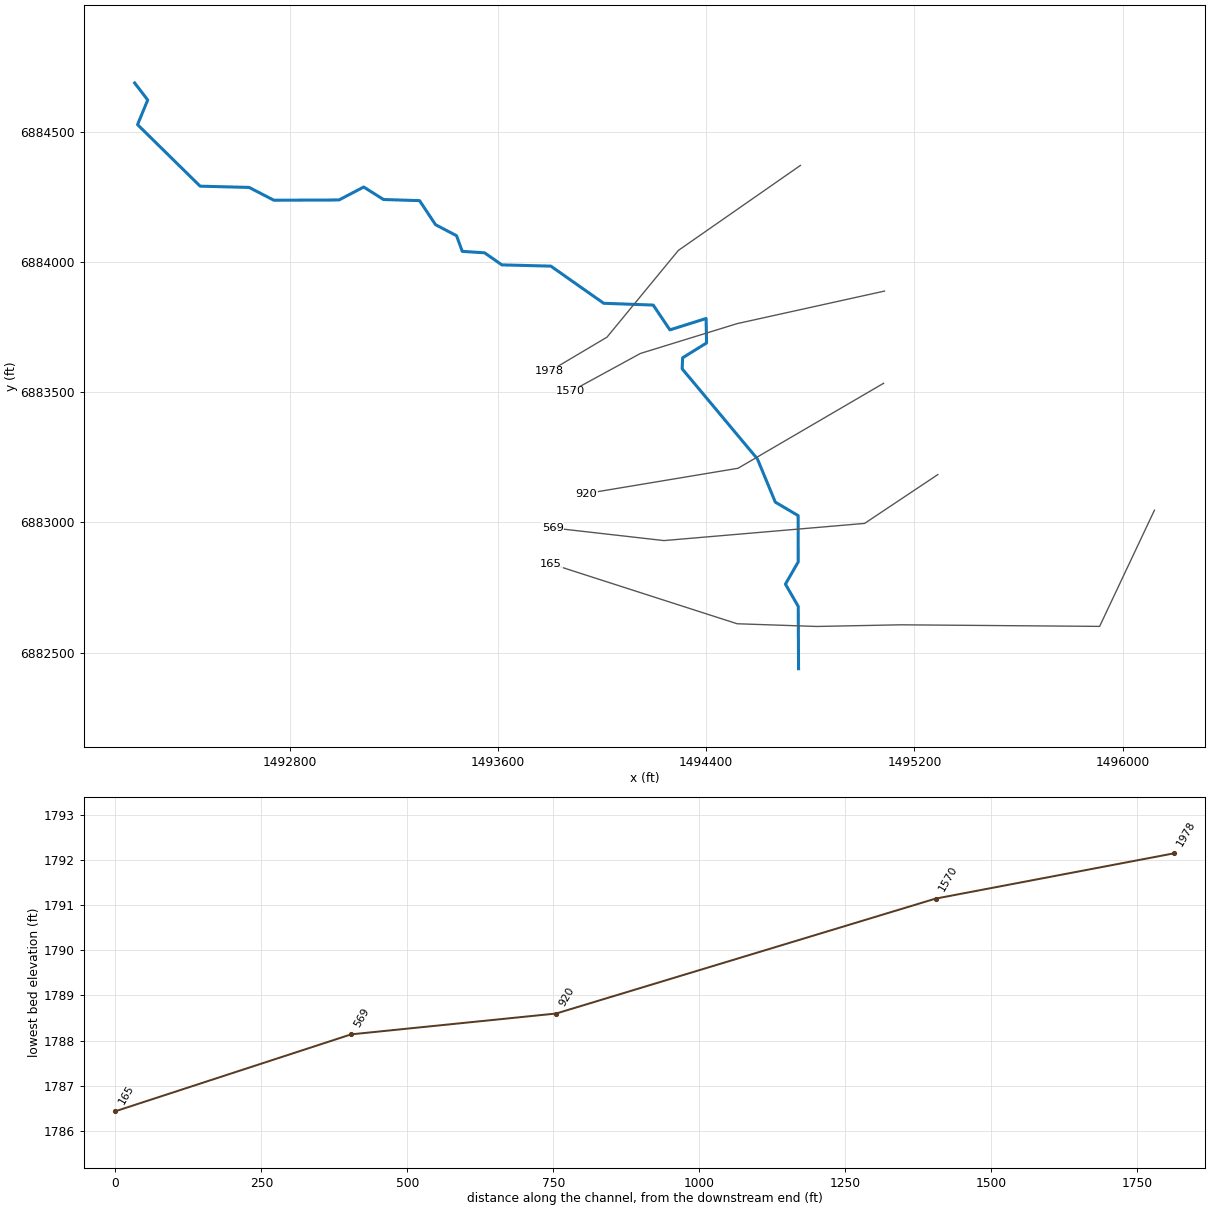
--- NC Unknown Stream 66.prj (project) ---

Proj Title=NC Unknown Stream 66 Base Level Engineering
Current Plan=p01
Default Exp/Contr=0.3,0.1
English Units
Geom File=g01
Flow File=f01
Plan File=p01
BEGIN DESCRIPTION:
NC Unknown Stream 66
END DESCRIPTION:

--- NC Unknown Stream 66.p01 (plan) ---

Plan Title=Multiple Run
Short Identifier=Multiple
Geom File=g01
Flow File=f01
Subcritical Flow
K Sum by GR= 0
Std Step Tol= 0.01
Critical Tol= 0.01
Num of Std Step Trials= 20
Max Error Tol= 0.3
Flow Tol Ratio= 0.001
Split Flow NTrial= 30
Split Flow Tol= 0.02
Split Flow Ratio= 0.02
Log Output Level= 0
Friction Slope Method= 1
Unsteady Friction Slope Method= 2
Unsteady Bridges Friction Slope Method= 1
Parabolic Critical Depth
Global Vel Dist=  1 , 1 , 1
Global Log Level= 0
CheckData=True
Encroach Param= -1, 0, 0, 0
BEGIN DESCRIPTION:
Multiple Run
END DESCRIPTION:

--- NC Unknown Stream 66.f01 (steady flow) ---

Flow Title=Multiple
Number of Profiles=7
Profile Names=10-year,25-year,50-year,1pct_min,100-year,1pct_plu,500-year
River Rch & RM= NC Unknown Strea,Reach-1,1978
     377     535     667     414     825    1646    1277
Boundary for River Rch & Prof#=NC Unknown Strea,Reach-1,1
Up Type=0
Dn Type=3
Dn Slope=0.001
Boundary for River Rch & Prof#=NC Unknown Strea,Reach-1,2
Up Type=0
Dn Type=3
Dn Slope=0.001
Boundary for River Rch & Prof#=NC Unknown Strea,Reach-1,3
Up Type=0
Dn Type=3
Dn Slope=0.001
Boundary for River Rch & Prof#=NC Unknown Strea,Reach-1,4
Up Type=0
Dn Type=3
Dn Slope=0.001
Boundary for River Rch & Prof#=NC Unknown Strea,Reach-1,5
Up Type=0
Dn Type=3
Dn Slope=0.001
Boundary for River Rch & Prof#=NC Unknown Strea,Reach-1,6
Up Type=0
Dn Type=3
Dn Slope=0.001
Boundary for River Rch & Prof#=NC Unknown Strea,Reach-1,7
Up Type=0
Dn Type=3
Dn Slope=0.001

--- NC Unknown Stream 66.g01 (geometry) ---

Geom Title=Existing Conditions

River Reach=NC Unknown Strea,Reach-1
Reach XY= 30
      1492205.00      6884688.00      1492255.17      6884622.57
      1492216.10      6884527.95      1492456.46      6884291.54
      1492644.49      6884286.78      1492739.82      6884237.57
      1492989.79      6884238.54      1493084.82      6884288.28
      1493160.93      6884240.30      1493299.32      6884235.99
      1493360.66      6884143.66      1493441.34      6884101.28
      1493463.35      6884041.19      1493548.94      6884035.61
      1493615.50      6883989.22      1493803.53      6883984.45
      1494006.55      6883841.75      1494196.69      6883834.90
      1494260.87      6883739.57      1494399.91      6883783.37
      1494401.63      6883689.38      1494309.77      6883632.36
      1494307.95      6883590.01      1494596.86      6883244.06
      1494665.69      6883078.02      1494753.36      6883026.17
      1494753.76      6882848.50      1494704.60      6882763.00
      1494753.76      6882677.50      1494755.00      6882438.00

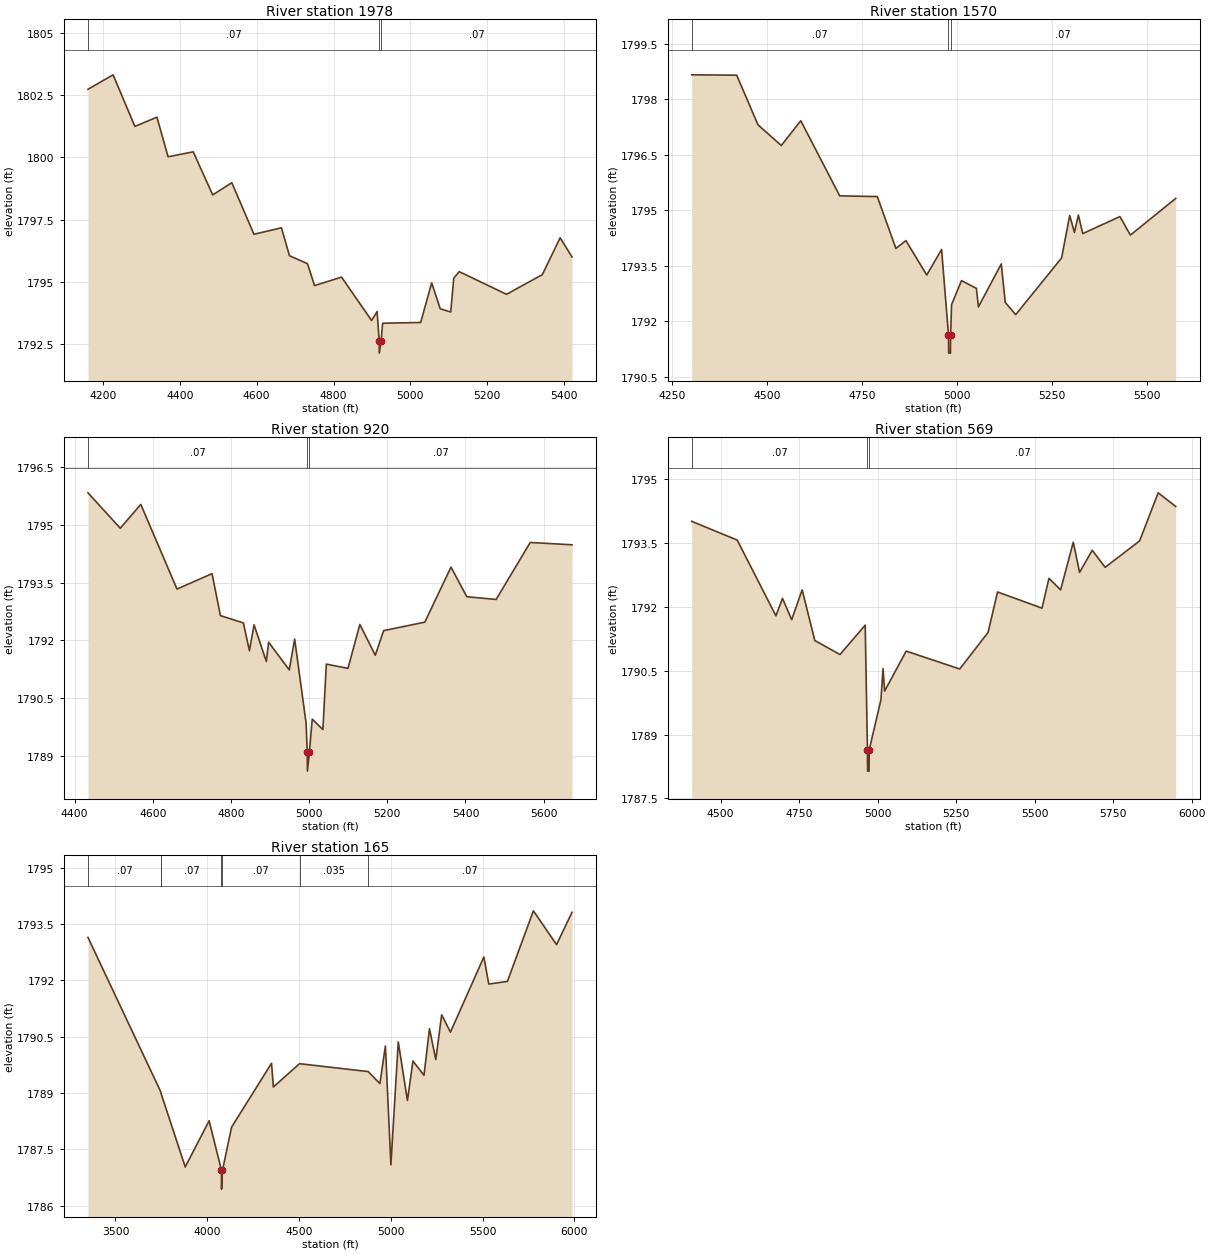
Type RM Length L Ch R = 1,1978,408,408,408
BEGIN DESCRIPTION:
Mapping XS d5fccae3
END DESCRIPTION:
XS GIS Cut Line= 4
      1494762.19      6884371.29      1494293.40      6884044.87
      1494019.10      6883711.54      1493798.48      6883580.55
#Sta/Elev= 30
  4161.1 1802.73  4226.4 1803.31  4283.1 1801.24  4340.5 1801.61  4369.5 1800.02
  4435.0 1800.22  4485.6 1798.49  4535.4 1798.98  4592.9 1796.91  4664.5 1797.17
  4685.4 1796.05  4732.3 1795.73  4750.6 1794.85  4820.9 1795.19  4899.1 1793.45
  4913.4 1793.81  4918.8 1792.64  4919.2 1792.14  4923.8 1792.64  4927.8 1793.34
  5026.8 1793.37  5055.5 1794.96  5077.7 1793.92  5105.0 1793.79  5112.9 1795.15
  5127.2 1795.41  5250.2 1794.50  5343.3 1795.29  5389.8 1796.77  5420.6 1796.00
#Mann=3,-1,0
  4161.1    0.07       0  4918.8    0.07       0  4923.8    0.07       0
Bank Sta=4918.8,4923.8
Exp/Cntr=0.3,0.1

Type RM Length L Ch R = 1,1570,650,650,650
BEGIN DESCRIPTION:
Mapping XS f3d616d1
END DESCRIPTION:
XS GIS Cut Line= 4
      1495085.06      6883888.62      1494519.10      6883763.62
      1494147.57      6883649.04      1493880.25      6883503.23
#Sta/Elev= 30
  4302.0 1798.66  4420.3 1798.65  4476.2 1797.31  4537.6 1796.75  4588.8 1797.42
  4691.2 1795.39  4790.1 1795.37  4838.9 1793.97  4865.3 1794.18  4920.1 1793.25
  4959.1 1793.94  4977.3 1791.64  4977.8 1791.14  4982.4 1791.14  4982.8 1791.64
  4985.4 1792.45  5011.5 1793.10  5050.7 1792.89  5056.0 1792.39  5116.1 1793.55
  5126.6 1792.51  5154.0 1792.18  5274.7 1793.71  5296.1 1794.86  5308.5 1794.40
  5318.9 1794.87  5330.4 1794.37  5428.1 1794.83  5455.7 1794.33  5574.9 1795.32
#Mann=3,-1,0
  4302.0    0.07       0  4977.3    0.07       0  4982.8    0.07       0
Bank Sta=4977.3,4982.8
Exp/Cntr=0.3,0.1

Type RM Length L Ch R = 1,920,351,351,351
BEGIN DESCRIPTION:
Mapping XS 7c2155a2
END DESCRIPTION:
XS GIS Cut Line= 3
      1495081.63      6883534.48      1494522.57      6883208.07
      1493939.58      6883110.90
#Sta/Elev= 30
  4434.2 1795.83  4516.8 1794.91  4569.3 1795.53  4661.9 1793.33  4751.6 1793.73
  4773.1 1792.64  4831.8 1792.45  4847.2 1791.73  4859.1 1792.40  4890.5 1791.45
  4896.3 1791.95  4949.2 1791.23  4963.0 1792.03  4992.2 1789.85  4995.2 1789.10
  4995.6 1788.60  5000.8 1789.10  5007.9 1789.95  5035.2 1789.68  5044.0 1791.38
  5099.4 1791.27  5129.8 1792.41  5169.3 1791.61  5190.6 1792.25  5296.0 1792.47
  5363.0 1793.90  5403.5 1793.13  5478.5 1793.06  5565.7 1794.54  5672.6 1794.48
#Mann=3,-1,0
  4434.2    0.07       0  4995.2    0.07       0  5000.8    0.07       0
Bank Sta=4995.2,5000.8
Exp/Cntr=0.3,0.1

Type RM Length L Ch R = 1,569,404,404,404
BEGIN DESCRIPTION:
Mapping XS fe2cda78
END DESCRIPTION:
XS GIS Cut Line= 4
      1495289.93      6883183.76      1495008.68      6882996.26
      1494237.85      6882930.29      1493810.78      6882978.90
#Sta/Elev= 30
  4407.8 1794.01  4552.7 1793.57  4675.9 1791.79  4696.9 1792.20  4726.2 1791.70
  4759.6 1792.40  4799.7 1791.21  4880.0 1790.88  4960.3 1791.57  4967.5 1788.64
  4968.0 1788.14  4972.7 1788.14  4973.1 1788.64  5010.5 1789.82  5017.1 1790.55
  5022.1 1790.02  5090.8 1790.96  5261.4 1790.54  5351.7 1791.40  5381.8 1792.35
  5523.4 1791.97  5545.5 1792.67  5582.7 1792.40  5623.0 1793.52  5643.1 1792.81
  5683.4 1793.33  5724.5 1792.93  5834.3 1793.55  5893.4 1794.68  5949.3 1794.36
#Mann=3,-1,0
  4407.8    0.07       0  4967.5    0.07       0  4973.1    0.07       0
Bank Sta=4967.5,4973.1
Exp/Cntr=0.3,0.1

Type RM Length L Ch R = 1,165,0,0,0
BEGIN DESCRIPTION:
NC Unknown Stream 66 1.0
END DESCRIPTION:
XS GIS Cut Line= 6
      1496121.88      6883046.92      1495911.36      6882600.72
      1495147.92      6882606.80      1494824.65      6882600.43
      1494519.10      6882610.85      1493804.86      6882840.71
#Sta/Elev= 30
  3350.3 1793.14  3746.8 1789.03  3749.5 1788.97  3880.0 1787.03  4010.0 1788.26
  4077.2 1786.94  4077.7 1786.44  4082.8 1786.94  4132.3 1788.09  4350.0 1789.79
  4360.0 1789.16  4502.6 1789.78  4876.3 1789.57  4940.1 1789.25  4970.1 1790.25
  5000.1 1787.09  5040.2 1790.36  5090.2 1788.80  5120.2 1789.85  5180.3 1789.47
  5210.3 1790.71  5244.5 1789.89  5276.6 1791.08  5324.5 1790.62  5506.4 1792.62
  5533.2 1791.90  5634.7 1791.97  5776.3 1793.85  5902.3 1792.95  5986.5 1793.81
#Mann=7,-1,0
  3350.3    0.07       0  3746.8   0.035       0  3749.5    0.07       0
  4077.2    0.07       0  4082.8    0.07       0  4502.6   0.035       0
  4876.3    0.07       0
Bank Sta=4077.2,4082.8
Exp/Cntr=0.3,0.1

Chan Stop Cuts=-1