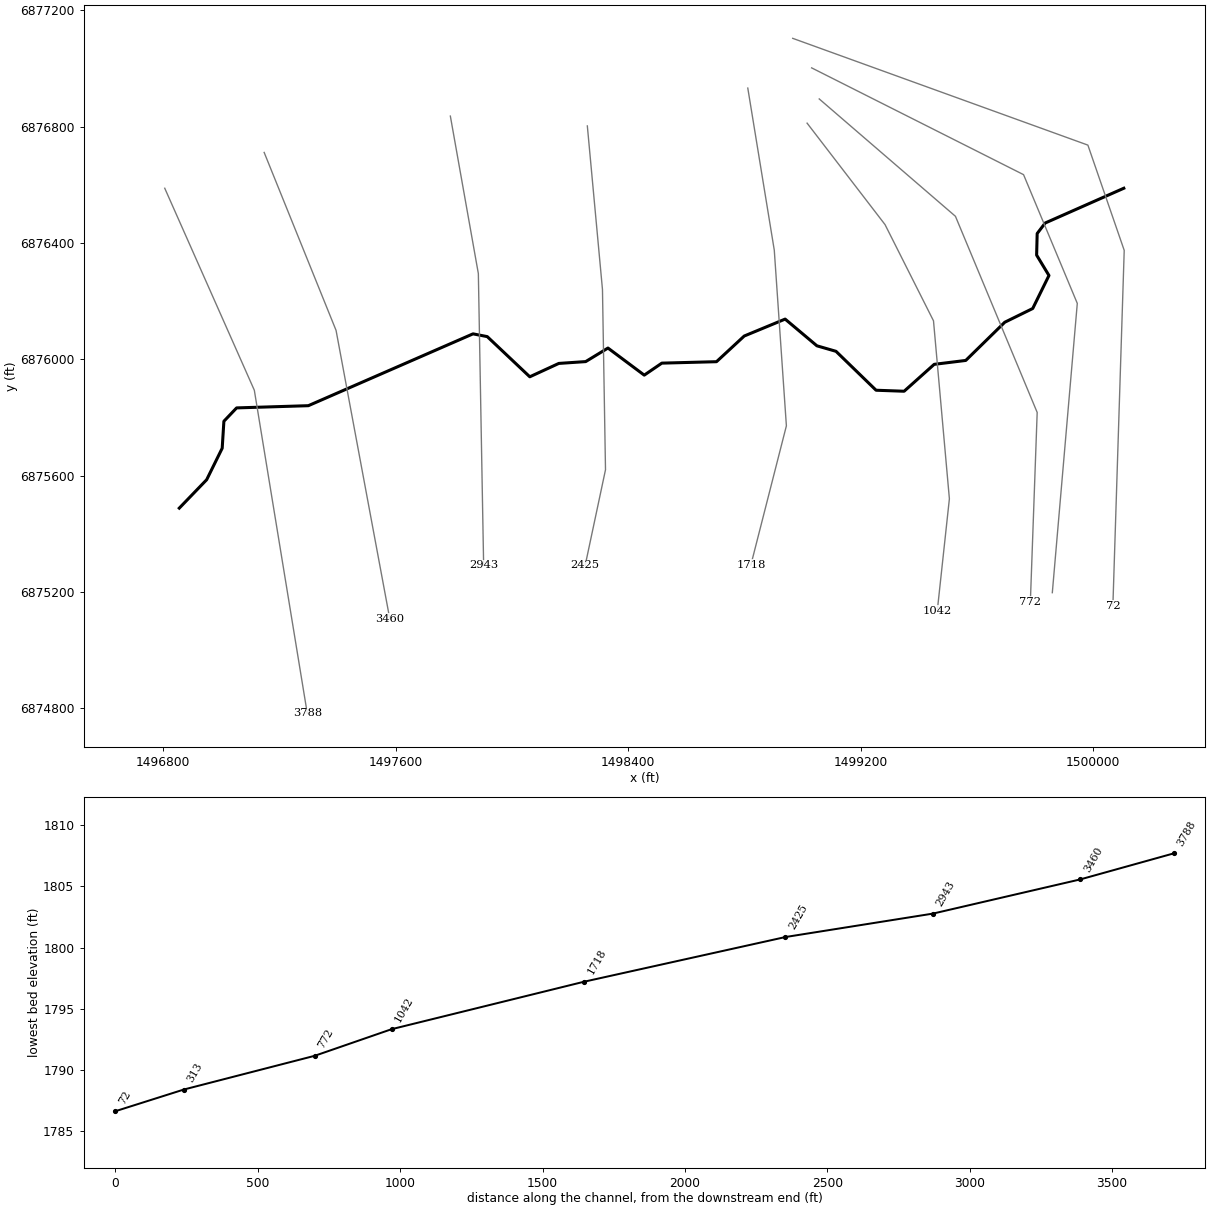
--- NC Unknown Stream 68.prj (project) ---

Proj Title=NC Unknown Stream 68 Base Level Engineering
Current Plan=p01
Default Exp/Contr=0.3,0.1
English Units
Geom File=g01
Flow File=f01
Plan File=p01
Y Axis Title=Elevation
X Axis Title(PF)=Main Channel Distance
X Axis Title(XS)=Station
BEGIN DESCRIPTION:
NC Unknown Stream 68
END DESCRIPTION:
DSS Export Rating Curves= 0
DSS Export Rating Curve Sorted= 0
DSS Export Volume Flow Curves= 0
DXF OffsetX= 0
DXF OffsetY= 0
DXF ScaleX= 1
DXF ScaleY= 10

--- NC Unknown Stream 68.p01 (plan) ---

Plan Title=Multiple Run
Short Identifier=Multiple
Geom File=g01
Flow File=f01
Subcritical Flow
K Sum by GR= 0
Std Step Tol= 0.01
Critical Tol= 0.01
Num of Std Step Trials= 20
Max Error Tol= 0.3
Flow Tol Ratio= 0.001
Split Flow NTrial= 30
Split Flow Tol= 0.02
Split Flow Ratio= 0.02
Log Output Level= 0
Friction Slope Method= 1
Unsteady Friction Slope Method= 2
Unsteady Bridges Friction Slope Method= 1
Parabolic Critical Depth
Global Vel Dist=  1 , 1 , 1
Global Log Level= 0
CheckData=True
Encroach Param= -1, 0, 0, 0
BEGIN DESCRIPTION:
Multiple Run
END DESCRIPTION:

--- NC Unknown Stream 68.f01 (steady flow) ---

Flow Title=Multiple
Program Version=4.10
Number of Profiles= 7
Profile Names=10-year,25-year,50-year,1pct_min,100-year,1pct_plu,500-year
River Rch & RM=NC Unknown Strea,Reach-1         ,3788
     197     267     322     194     386     771     561
River Rch & RM=NC Unknown Strea,Reach-1         ,2943
     254     349     426     258     515    1028     763
Boundary for River Rch & Prof#=NC Unknown Strea,Reach-1         , 1
Up Type= 0
Dn Type= 3
Dn Slope=0.007
Boundary for River Rch & Prof#=NC Unknown Strea,Reach-1         , 2
Up Type= 0
Dn Type= 3
Dn Slope=0.007
Boundary for River Rch & Prof#=NC Unknown Strea,Reach-1         , 3
Up Type= 0
Dn Type= 3
Dn Slope=0.007
Boundary for River Rch & Prof#=NC Unknown Strea,Reach-1         , 4
Up Type= 0
Dn Type= 3
Dn Slope=0.007
Boundary for River Rch & Prof#=NC Unknown Strea,Reach-1         , 5
Up Type= 0
Dn Type= 3
Dn Slope=0.007
Boundary for River Rch & Prof#=NC Unknown Strea,Reach-1         , 6
Up Type= 0
Dn Type= 3
Dn Slope=0.007
Boundary for River Rch & Prof#=NC Unknown Strea,Reach-1         , 7
Up Type= 0
Dn Type= 3
Dn Slope=0.007
DSS Import GetInterval= 0
DSS Import GetPeak= 0
DSS Import FillOption= 0

--- NC Unknown Stream 68.g01 (geometry) ---

Geom Title=Existing Conditions

River Reach=NC Unknown Strea,Reach-1
Reach XY= 30
      1496855.00      6875488.00      1496949.21      6875585.68
      1497002.67      6875693.97      1497008.51      6875786.75
      1497052.26      6875832.66      1497299.06      6875840.26
      1497865.71      6876087.28      1497914.68      6876077.81
      1498061.03      6875939.62      1498160.97      6875985.62
      1498253.42      6875991.89      1498330.04      6876038.49
      1498454.90      6875945.33      1498515.43      6875986.61
      1498703.53      6875991.55      1498798.95      6876079.84
      1498939.66      6876138.05      1499048.96      6876046.18
      1499114.68      6876027.22      1499252.57      6875893.40
      1499349.10      6875889.97      1499452.58      6875982.46
      1499561.17      6875995.86      1499695.34      6876127.21
      1499791.54      6876174.44      1499847.47      6876287.99
      1499805.01      6876358.06      1499806.89      6876432.29
      1499834.41      6876468.42      1500105.00      6876588.00

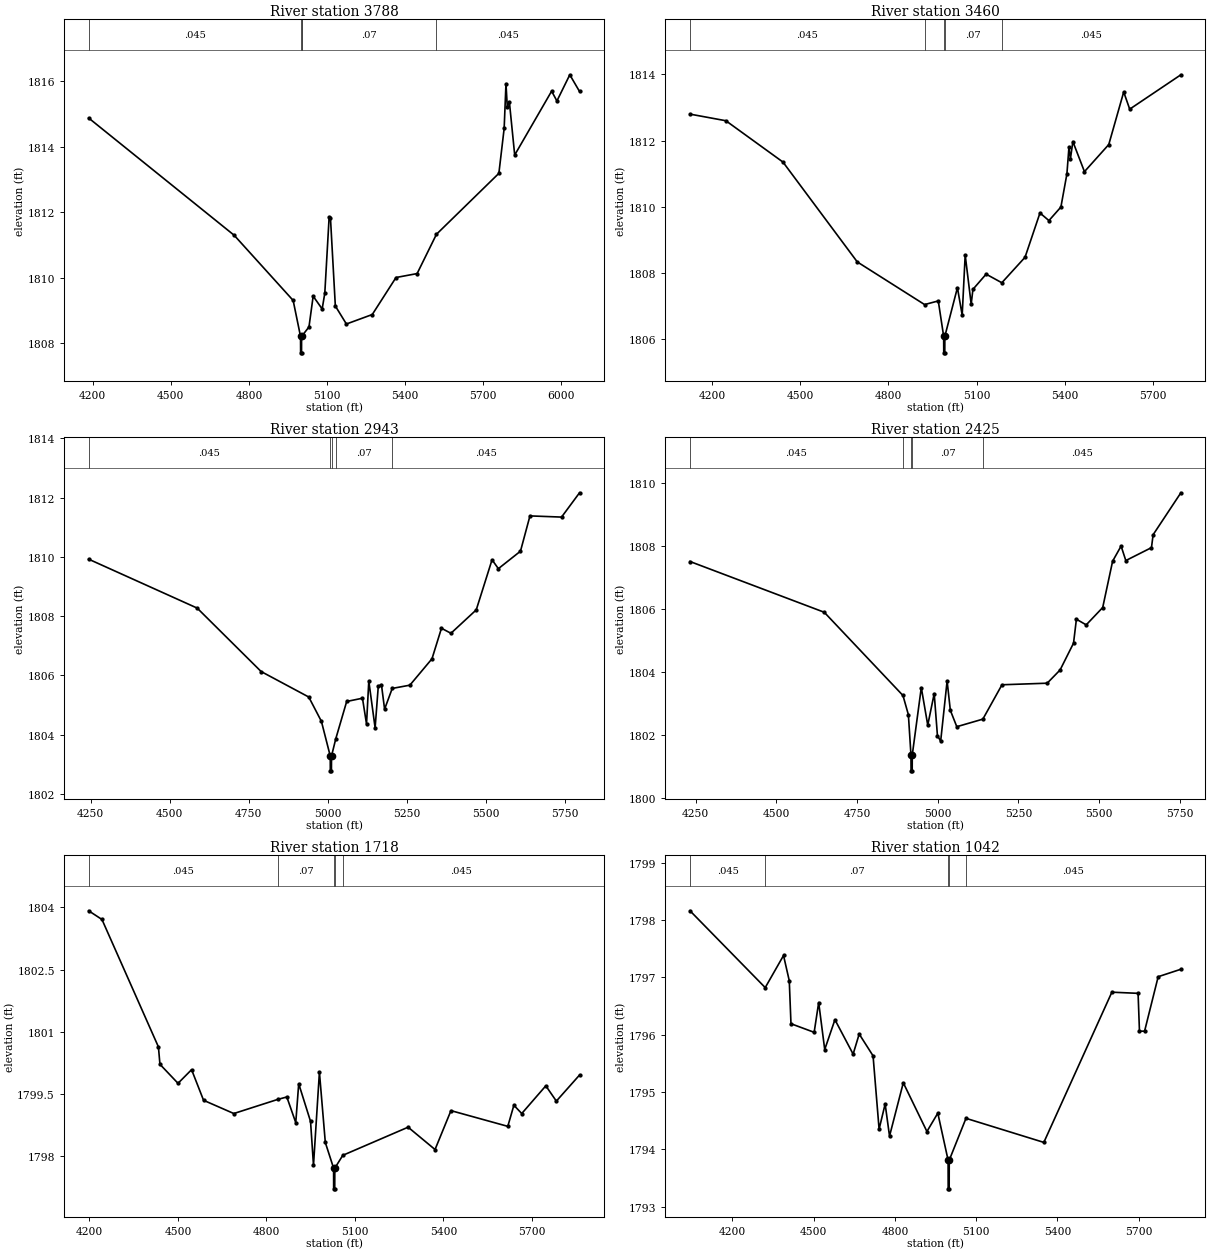
Type RM Length L Ch R = 1,3788,328,328,328
BEGIN DESCRIPTION:
NC Unknown Stream 68 4.0
END DESCRIPTION:
XS GIS Cut Line= 3
      1496804.98      6876588.04      1497113.24      6875893.40
      1497295.40      6874782.20
#Sta/Elev= 30
  4184.2 1814.88  4743.3 1811.30  4969.9 1809.31  4998.3 1808.21  4998.6 1807.71
  5002.1 1807.71  5002.3 1808.21  5004.2 1808.23  5030.7 1808.50  5046.8 1809.44
  5081.4 1809.05  5091.5 1809.53  5108.2 1811.86  5113.2 1811.84  5132.0 1809.14
  5174.5 1808.59  5273.9 1808.88  5365.1 1810.01  5446.2 1810.13  5520.5 1811.33
  5760.3 1813.19  5780.6 1814.56  5787.6 1815.93  5792.7 1815.22  5800.8 1815.36
  5821.1 1813.75  5963.0 1815.70  5983.3 1815.40  6032.8 1816.20  6070.2 1815.69
#Mann=5,-1,0
  4184.2   0.045       0  4998.3   0.045       0  5002.3   0.045       0
  5004.2    0.07       0  5520.5   0.045       0
Bank Sta=4998.3,5002.3
Exp/Cntr=0.3,0.1

Type RM Length L Ch R = 1,3460,517,517,517
BEGIN DESCRIPTION:
Mapping XS 471a8cc2
END DESCRIPTION:
XS GIS Cut Line= 3
      1497147.08      6876711.13      1497394.49      6876099.13
      1497579.39      6875106.92
#Sta/Elev= 30
  4125.3 1812.80  4247.3 1812.60  4441.5 1811.35  4694.2 1808.33  4923.1 1807.04
  4969.7 1807.15  4988.0 1806.08  4988.3 1805.58  4991.8 1805.58  4992.0 1806.08
  5034.8 1807.55  5051.0 1806.72  5061.2 1808.54  5081.6 1807.05  5087.5 1807.50
  5132.4 1807.96  5185.8 1807.70  5264.7 1808.47  5315.5 1809.81  5346.0 1809.58
  5386.7 1809.99  5407.1 1810.99  5414.1 1811.80  5419.1 1811.45  5427.4 1811.97
  5466.8 1811.06  5549.5 1811.88  5600.3 1813.47  5620.7 1812.95  5794.7 1813.99
#Mann=5,-1,0
  4125.3   0.045       0  4923.1    0.07       0  4988.0    0.07       0
  4992.0    0.07       0  5185.8   0.045       0
Bank Sta=4988,4992
Exp/Cntr=0.3,0.1

Type RM Length L Ch R = 1,2943,518,518,518
BEGIN DESCRIPTION:
Mapping XS 8dd593b2
END DESCRIPTION:
XS GIS Cut Line= 3
      1497787.71      6876836.15      1497884.07      6876294.44
      1497902.27      6875291.12
#Sta/Elev= 30
  4243.5 1809.92  4587.0 1808.27  4789.4 1806.13  4940.2 1805.27  4980.2 1804.45
  5008.2 1803.28  5008.4 1802.78  5011.9 1802.78  5012.2 1803.28  5025.9 1803.87
  5060.2 1805.12  5110.2 1805.23  5123.0 1804.36  5130.2 1805.81  5150.2 1804.23
  5160.2 1805.63  5170.2 1805.69  5180.2 1804.86  5204.4 1805.56  5260.2 1805.67
  5330.2 1806.56  5360.2 1807.59  5390.2 1807.42  5470.3 1808.21  5520.3 1809.90
  5540.3 1809.60  5610.3 1810.19  5640.3 1811.38  5740.3 1811.34  5797.2 1812.16
#Mann=5,-1,0
  4243.5   0.045       0  5008.2   0.045       0  5012.2   0.045       0
  5025.9    0.07       0  5204.4   0.045       0
Bank Sta=5008.2,5012.2
Exp/Cntr=0.3,0.1

Type RM Length L Ch R = 1,2425,707,707,707
BEGIN DESCRIPTION:
Mapping XS 085f4b66
END DESCRIPTION:
XS GIS Cut Line= 4
      1498259.07      6876802.28      1498311.15      6876239.75
      1498321.57      6875619.96      1498251.66      6875291.12
#Sta/Elev= 30
  4232.3 1807.50  4648.3 1805.89  4892.2 1803.25  4909.0 1802.64  4917.0 1801.36
  4917.3 1800.86  4920.8 1800.86  4921.0 1801.36  4949.0 1803.50  4969.0 1802.31
  4989.0 1803.31  4999.0 1801.98  5009.0 1801.80  5029.0 1803.71  5039.0 1802.78
  5059.0 1802.26  5139.7 1802.50  5199.0 1803.59  5339.1 1803.64  5379.1 1804.06
  5420.7 1804.91  5429.6 1805.67  5460.0 1805.49  5511.1 1806.04  5541.8 1807.51
  5568.1 1807.99  5582.7 1807.53  5662.2 1807.94  5667.3 1808.35  5753.3 1809.68
#Mann=5,-1,0
  4232.3   0.045       0  4892.2    0.07       0  4917.0    0.07       0
  4921.0    0.07       0  5139.7   0.045       0
Bank Sta=4917,4921
Exp/Cntr=0.3,0.1

Type RM Length L Ch R = 1,1718,676,676,676
BEGIN DESCRIPTION:
Mapping XS b3adffd5
END DESCRIPTION:
XS GIS Cut Line= 4
      1498811.15      6876932.46      1498902.30      6876375.17
      1498943.97      6875771.00      1498821.71      6875292.37
#Sta/Elev= 30
  4197.3 1803.92  4242.4 1803.71  4433.9 1800.63  4439.0 1800.21  4500.3 1799.75
  4546.3 1800.08  4586.9 1799.34  4689.5 1799.02  4837.9 1799.36  4869.2 1799.42
  4899.5 1798.80  4909.5 1799.74  4949.6 1798.83  4959.6 1797.77  4979.7 1800.02
  4999.7 1798.32  5027.8 1797.70  5028.0 1797.20  5031.6 1797.20  5031.9 1797.70
  5059.0 1798.01  5280.4 1798.69  5371.7 1798.15  5425.7 1799.09  5618.4 1798.71
  5639.0 1799.22  5665.7 1799.02  5747.3 1799.69  5783.0 1799.32  5861.6 1799.95
#Mann=5,-1,0
  4197.3   0.045       0  4837.9    0.07       0  5027.8    0.07       0
  5031.9    0.07       0  5059.0   0.045       0
Bank Sta=5027.8,5031.9
Exp/Cntr=0.3,0.1

Type RM Length L Ch R = 1,1042,270,270,270
BEGIN DESCRIPTION:
Mapping XS 17e9b4cf
END DESCRIPTION:
XS GIS Cut Line= 5
      1499015.23      6876811.85      1499283.47      6876462.88
      1499450.14      6876132.15      1499504.82      6875520.17
      1499463.15      6875134.73
#Sta/Elev= 30
  4043.1 1798.16  4320.9 1796.82  4388.5 1797.38  4409.7 1796.94  4416.0 1796.19
  4501.6 1796.04  4518.3 1796.56  4540.6 1795.74  4578.3 1796.26  4645.5 1795.66
  4667.9 1796.01  4719.1 1795.63  4741.4 1794.35  4763.7 1794.79  4779.9 1794.23
  4830.7 1795.16  4918.0 1794.31  4958.2 1794.63  4996.2 1793.81  4996.5 1793.31
  5000.1 1793.31  5000.4 1793.81  5062.2 1794.54  5349.7 1794.12  5600.9 1796.74
  5697.7 1796.72  5702.8 1796.06  5721.7 1796.06  5771.9 1797.01  5855.7 1797.14
#Mann=5,-1,0
  4043.1   0.045       0  4320.9    0.07       0  4996.2    0.07       0
  5000.4    0.07       0  5062.2   0.045       0
Bank Sta=4996.2,5000.4
Exp/Cntr=0.3,0.1

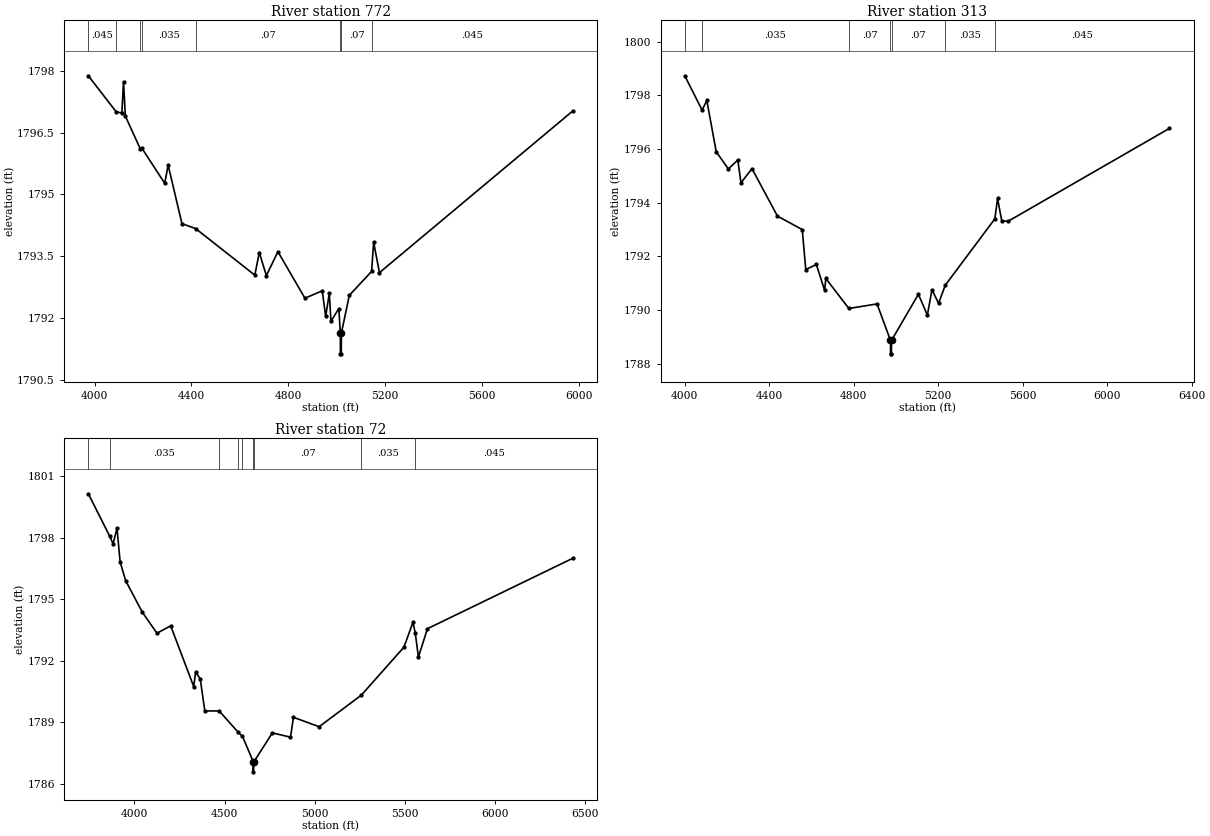
Type RM Length L Ch R = 1,772,459,459,459
BEGIN DESCRIPTION:
Mapping XS db3bca16
END DESCRIPTION:
XS GIS Cut Line= 4
      1499056.94      6876895.15      1499525.66      6876491.53
      1499806.91      6875817.05      1499783.47      6875165.99
#Sta/Elev= 30
  3974.3 1797.88  4089.9 1797.00  4112.9 1796.98  4119.5 1797.74  4127.2 1796.90
  4189.2 1796.10  4195.6 1796.12  4289.6 1795.27  4303.8 1795.71  4360.9 1794.29
  4417.5 1794.17  4661.7 1793.04  4680.0 1793.59  4709.3 1793.03  4756.9 1793.61
  4868.5 1792.48  4939.9 1792.66  4954.2 1792.04  4969.2 1792.60  4975.9 1791.92
  5008.4 1792.23  5014.7 1791.63  5015.0 1791.13  5018.6 1791.13  5018.9 1791.63
  5051.7 1792.55  5143.7 1793.13  5152.2 1793.84  5176.0 1793.10  5975.1 1797.03
#Mann=8,-1,0
  3974.3   0.045       0  4089.9   0.035       0  4189.2    0.07       0
  4195.6   0.035       0  4417.5    0.07       0  5014.7    0.07       0
  5018.9    0.07       0  5143.7   0.045       0
Bank Sta=5014.7,5018.9
Exp/Cntr=0.3,0.1

Type RM Length L Ch R = 1,313,241,241,241
BEGIN DESCRIPTION:
Mapping XS 02749d79
END DESCRIPTION:
XS GIS Cut Line= 4
      1499030.85      6877001.95      1499760.03      6876634.75
      1499944.93      6876192.05      1499858.99      6875197.23
#Sta/Elev= 30
  3999.7 1798.73  4081.7 1797.45  4104.0 1797.81  4148.6 1795.90  4205.9 1795.26
  4250.7 1795.59  4265.8 1794.74  4317.8 1795.27  4438.7 1793.50  4555.9 1793.00
  4572.6 1791.51  4622.8 1791.70  4661.9 1790.73  4667.5 1791.18  4776.6 1790.06
  4910.1 1790.23  4973.7 1788.87  4974.1 1788.37  4978.2 1788.37  4978.5 1788.87
  5106.0 1790.59  5148.2 1789.81  5170.2 1790.76  5201.3 1790.25  5233.3 1790.93
  5467.9 1793.40  5480.6 1794.16  5500.7 1793.32  5530.8 1793.31  6294.4 1796.77
#Mann=7,-1,0
  3999.7   0.045       0  4081.7   0.035       0  4776.6    0.07       0
  4973.7    0.07       0  4978.5    0.07       0  5233.3   0.035       0
  5467.9   0.045       0
Bank Sta=4973.7,4978.5
Exp/Cntr=0.3,0.1

Type RM Length L Ch R = 1,72,0,0,0
BEGIN DESCRIPTION:
NC Unknown Stream 68 1.0
END DESCRIPTION:
XS GIS Cut Line= 4
      1498965.75      6877103.51      1499981.39      6876736.32
      1500106.39      6876374.34      1500067.36      6875151.69
#Sta/Elev= 30
  3745.0 1800.15  3862.9 1798.09  3882.4 1797.71  3903.7 1798.47  3921.3 1796.83
  3952.0 1795.91  4043.9 1794.38  4125.3 1793.35  4201.4 1793.71  4329.0 1790.75
  4339.9 1791.45  4365.2 1791.13  4390.5 1789.56  4470.3 1789.56  4576.6 1788.51
  4599.2 1788.32  4658.7 1787.09  4659.1 1786.59  4663.5 1787.09  4765.0 1788.49
  4865.5 1788.28  4881.7 1789.25  5024.2 1788.79  5258.1 1790.33  5494.4 1792.67
  5544.4 1793.89  5557.3 1793.34  5574.5 1792.19  5624.5 1793.57  6431.2 1797.01
#Mann=9,-1,0
  3745.0   0.045       0  3862.9   0.035       0  4470.3    0.07       0
  4576.6   0.035       0  4599.2    0.07       0  4658.7    0.07       0
  4663.5    0.07       0  5258.1   0.035       0  5557.3   0.045       0
Bank Sta=4658.7,4663.5
Exp/Cntr=0.3,0.1

Chan Stop Cuts=-1