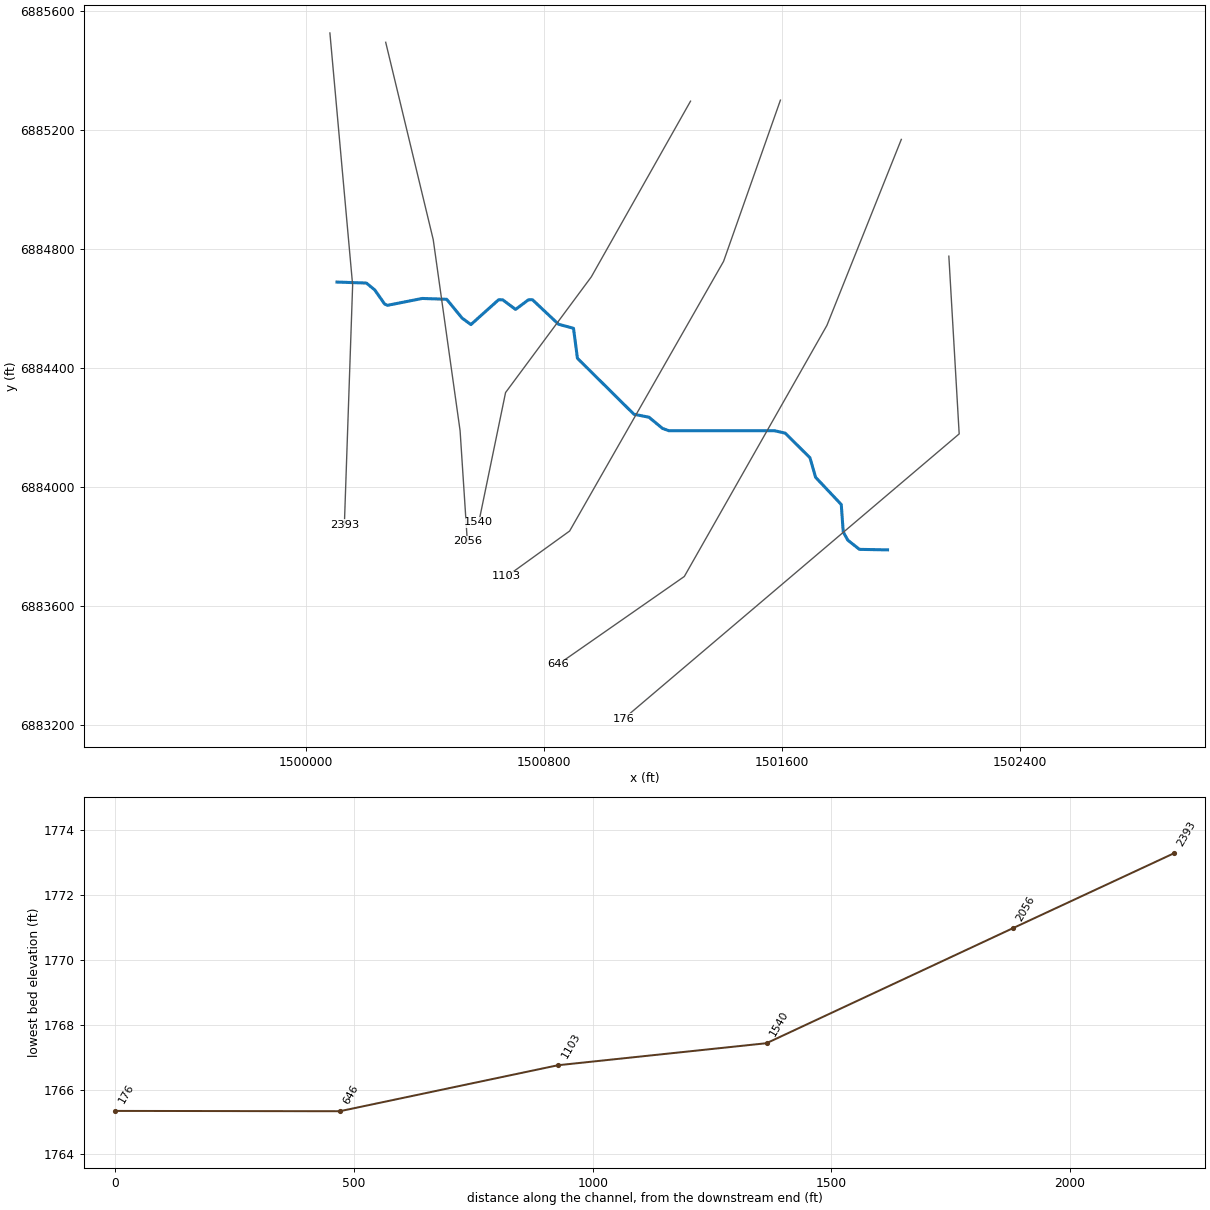
--- NC Unknown Stream 69.prj (project) ---

Proj Title=NC Unknown Stream 69 Base Level Engineering
Current Plan=p01
Default Exp/Contr=0.3,0.1
English Units
Geom File=g01
Flow File=f01
Plan File=p01
BEGIN DESCRIPTION:
NC Unknown Stream 69
END DESCRIPTION:

--- NC Unknown Stream 69.p01 (plan) ---

Plan Title=Multiple Run
Short Identifier=Multiple
Geom File=g01
Flow File=f01
Subcritical Flow
K Sum by GR= 0
Std Step Tol= 0.01
Critical Tol= 0.01
Num of Std Step Trials= 20
Max Error Tol= 0.3
Flow Tol Ratio= 0.001
Split Flow NTrial= 30
Split Flow Tol= 0.02
Split Flow Ratio= 0.02
Log Output Level= 0
Friction Slope Method= 1
Unsteady Friction Slope Method= 2
Unsteady Bridges Friction Slope Method= 1
Parabolic Critical Depth
Global Vel Dist=  1 , 1 , 1
Global Log Level= 0
CheckData=True
Encroach Param= -1, 0, 0, 0
BEGIN DESCRIPTION:
Multiple Run
END DESCRIPTION:

--- NC Unknown Stream 69.f01 (steady flow) ---

Flow Title=Multiple
Number of Profiles=7
Profile Names=10-year,25-year,50-year,1pct_min,100-year,1pct_plu,500-year
River Rch & RM= NC Unknown Strea,Reach-1,2393
     323     455     564     348     694    1385    1064
River Rch & RM= NC Unknown Strea,Reach-1,1540
     340     480     596     368     735    1466    1131
Boundary for River Rch & Prof#=NC Unknown Strea,Reach-1,1
Up Type=0
Dn Type=3
Dn Slope=0.001
Boundary for River Rch & Prof#=NC Unknown Strea,Reach-1,2
Up Type=0
Dn Type=3
Dn Slope=0.001
Boundary for River Rch & Prof#=NC Unknown Strea,Reach-1,3
Up Type=0
Dn Type=3
Dn Slope=0.001
Boundary for River Rch & Prof#=NC Unknown Strea,Reach-1,4
Up Type=0
Dn Type=3
Dn Slope=0.001
Boundary for River Rch & Prof#=NC Unknown Strea,Reach-1,5
Up Type=0
Dn Type=3
Dn Slope=0.001
Boundary for River Rch & Prof#=NC Unknown Strea,Reach-1,6
Up Type=0
Dn Type=3
Dn Slope=0.001
Boundary for River Rch & Prof#=NC Unknown Strea,Reach-1,7
Up Type=0
Dn Type=3
Dn Slope=0.001

--- NC Unknown Stream 69.g01 (geometry) ---

Geom Title=Existing Conditions

River Reach=NC Unknown Strea,Reach-1
Reach XY= 30
      1500105.00      6884688.00      1500203.70      6884684.60
      1500231.89      6884661.51      1500265.07      6884614.08
      1500274.75      6884609.84      1500391.44      6884632.90
      1500473.54      6884630.09      1500525.01      6884567.14
      1500554.95      6884545.07      1500648.10      6884628.56
      1500661.67      6884628.41      1500705.00      6884596.05
      1500748.33      6884628.41      1500761.66      6884628.70
      1500849.30      6884546.34      1500899.74      6884532.53
      1500912.88      6884431.88      1501102.70      6884243.83
      1501153.25      6884233.78      1501198.92      6884196.09
      1501220.21      6884188.51      1501575.18      6884188.43
      1501611.21      6884180.20      1501694.23      6884097.70
      1501713.18      6884031.96      1501799.46      6883940.42
      1501806.09      6883848.32      1501821.24      6883820.79
      1501860.53      6883789.76      1501955.00      6883788.00

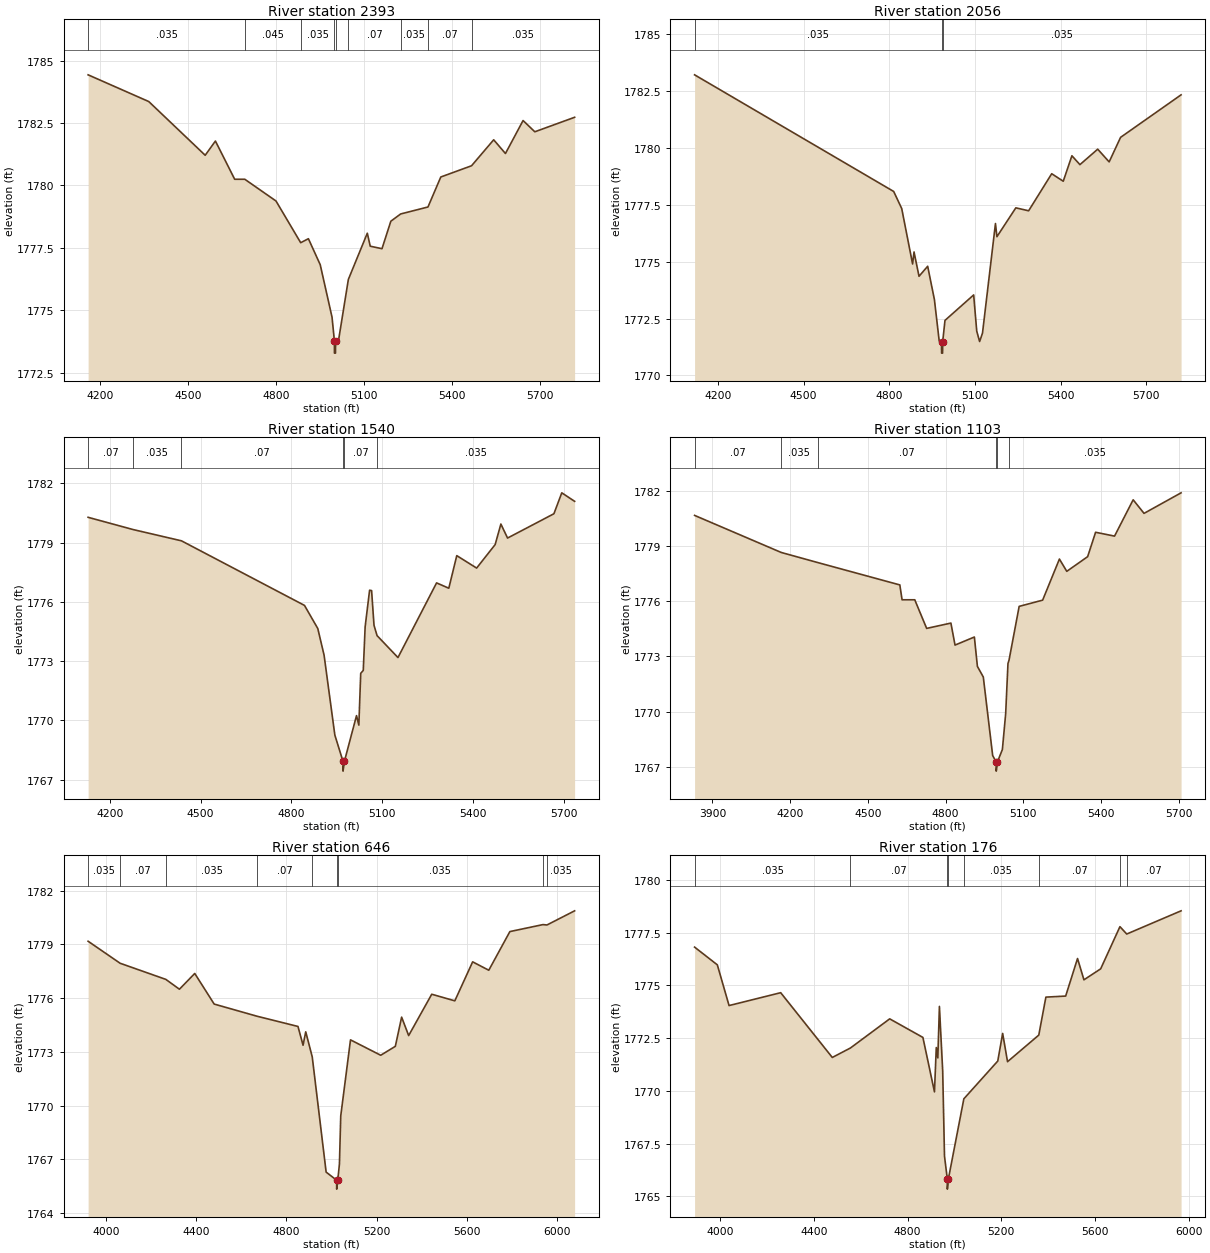
Type RM Length L Ch R = 1,2393,337,337,337
BEGIN DESCRIPTION:
NC Unknown Stream 69 4.0
END DESCRIPTION:
XS GIS Cut Line= 3
      1500081.12      6885525.01      1500157.51      6884677.77
      1500129.74      6883872.62
#Sta/Elev= 30
  4160.3 1784.43  4366.8 1783.36  4558.9 1781.21  4593.7 1781.78  4659.3 1780.25
  4693.7 1780.25  4799.9 1779.38  4884.0 1777.71  4910.3 1777.87  4950.5 1776.83
  4990.7 1774.73  4998.7 1773.79  4999.0 1773.29  5002.5 1773.29  5002.7 1773.79
  5013.4 1773.84  5046.3 1776.24  5110.8 1778.09  5120.8 1777.57  5160.8 1777.47
  5190.9 1778.57  5224.3 1778.86  5317.4 1779.14  5361.0 1780.34  5465.7 1780.79
  5541.1 1781.83  5581.1 1781.28  5641.1 1782.60  5681.1 1782.15  5816.6 1782.73
#Mann=9,-1,0
  4160.3   0.035       0  4693.7   0.045       0  4884.0   0.035       0
  4998.7   0.035       0  5002.7   0.035       0  5046.3    0.07       0
  5224.3   0.035       0  5317.4    0.07       0  5465.7   0.035       0
Bank Sta=4998.7,5002.7
Exp/Cntr=0.3,0.1

Type RM Length L Ch R = 1,2056,516,516,516
BEGIN DESCRIPTION:
Mapping XS 20c8826e
END DESCRIPTION:
XS GIS Cut Line= 4
      1500268.62      6885493.73      1500428.34      6884830.55
      1500518.62      6884188.19      1500542.92      6883816.70
#Sta/Elev= 30
  4118.6 1783.22  4815.6 1778.09  4843.7 1777.34  4881.8 1774.90  4886.8 1775.43
  4904.3 1774.36  4934.6 1774.80  4958.1 1773.34  4975.0 1771.51  4983.1 1771.48
  4983.3 1770.98  4986.8 1770.98  4987.1 1771.48  4995.2 1772.42  5095.6 1773.54
  5106.3 1771.95  5116.4 1771.49  5126.5 1771.86  5171.9 1776.68  5177.0 1776.10
  5243.2 1777.37  5288.0 1777.24  5368.8 1778.87  5409.2 1778.54  5439.5 1779.66
  5467.6 1779.27  5529.8 1779.95  5569.9 1779.39  5609.9 1780.47  5821.7 1782.34
#Mann=3,-1,0
  4118.6   0.035       0  4983.1   0.035       0  4987.1   0.035       0
Bank Sta=4983.1,4987.1
Exp/Cntr=0.3,0.1

Type RM Length L Ch R = 1,1540,437,437,437
BEGIN DESCRIPTION:
Mapping XS 0837e67b
END DESCRIPTION:
XS GIS Cut Line= 4
      1501292.92      6885295.82      1500959.59      6884705.55
      1500671.40      6884316.66      1500581.51      6883881.06
#Sta/Elev= 30
  4128.5 1780.28  4277.2 1779.66  4436.8 1779.09  4843.1 1775.82  4887.0 1774.65
  4907.8 1773.30  4943.3 1769.26  4970.1 1767.93  4970.4 1767.43  4975.0 1767.93
  5014.9 1770.24  5022.6 1769.76  5028.8 1772.38  5037.2 1772.53  5043.4 1774.74
  5058.1 1776.59  5064.7 1776.57  5072.7 1774.81  5082.8 1774.29  5151.8 1773.18
  5279.3 1776.96  5319.7 1776.69  5346.0 1778.34  5411.6 1777.71  5472.8 1778.90
  5491.7 1779.94  5513.7 1779.23  5666.8 1780.46  5692.8 1781.52  5735.2 1781.09
#Mann=6,-1,0
  4128.5    0.07       0  4277.2   0.035       0  4436.8    0.07       0
  4970.1    0.07       0  4975.0    0.07       0  5082.8   0.035       0
Bank Sta=4970.1,4975
Exp/Cntr=0.3,0.1

Type RM Length L Ch R = 1,1103,457,457,457
BEGIN DESCRIPTION:
Mapping XS 35a48c61
END DESCRIPTION:
XS GIS Cut Line= 4
      1501595.00      6885299.29      1501404.04      6884757.63
      1500886.67      6883851.38      1500674.88      6883698.62
#Sta/Elev= 30
  3830.9 1780.69  4165.4 1778.67  4306.3 1778.12  4623.6 1776.90  4632.3 1776.09
  4681.3 1776.09  4727.2 1774.53  4820.9 1774.82  4836.8 1773.62  4911.5 1774.06
  4923.2 1772.46  4946.0 1771.88  4982.2 1767.60  4995.6 1767.25  4996.0 1766.75
  5000.6 1767.25  5019.7 1767.93  5032.4 1769.88  5041.3 1772.62  5045.4 1772.80
  5084.5 1775.73  5175.2 1776.07  5240.0 1778.31  5268.4 1777.64  5349.0 1778.44
  5379.7 1779.77  5452.9 1779.56  5524.8 1781.54  5566.8 1780.80  5709.9 1781.92
#Mann=6,-1,0
  3830.9    0.07       0  4165.4   0.035       0  4306.3    0.07       0
  4995.6    0.07       0  5000.6    0.07       0  5045.4   0.035       0
Bank Sta=4995.6,5000.6
Exp/Cntr=0.3,0.1

Type RM Length L Ch R = 1,646,470,470,470
BEGIN DESCRIPTION:
Mapping XS 76bf5099
END DESCRIPTION:
XS GIS Cut Line= 4
      1502001.26      6885167.35      1501751.26      6884542.36
      1501272.09      6883698.61      1500849.26      6883404.01
#Sta/Elev= 30
  3919.8 1779.18  4061.9 1777.95  4264.5 1777.05  4325.0 1776.50  4393.0 1777.38
  4479.2 1775.67  4669.6 1774.99  4851.0 1774.42  4873.6 1773.37  4885.5 1774.12
  4914.3 1772.72  4976.0 1766.28  5022.5 1765.83  5022.8 1765.33  5027.5 1765.83
  5035.0 1766.73  5040.8 1769.42  5084.1 1773.67  5218.2 1772.81  5283.1 1773.31
  5311.0 1774.94  5342.2 1773.91  5444.6 1776.22  5547.0 1775.85  5626.1 1778.03
  5697.7 1777.56  5791.3 1779.72  5938.0 1780.11  5956.0 1780.09  6078.6 1780.88
#Mann=9,-1,0
  3919.8   0.035       0  4061.9    0.07       0  4264.5   0.035       0
  4669.6    0.07       0  4914.3   0.035       0  5022.5   0.035       0
  5027.5   0.035       0  5938.0    0.07       0  5956.0   0.035       0
Bank Sta=5022.5,5027.5
Exp/Cntr=0.3,0.1

Type RM Length L Ch R = 1,176,0,0,0
BEGIN DESCRIPTION:
NC Unknown Stream 69 1.0
END DESCRIPTION:
XS GIS Cut Line= 3
      1502160.98      6884774.95      1502195.70      6884177.77
      1501068.58      6883220.59
#Sta/Elev= 30
  3891.0 1776.81  3988.1 1775.97  4038.2 1774.04  4258.6 1774.65  4478.9 1771.58
  4556.5 1772.03  4724.0 1773.41  4865.7 1772.53  4915.1 1769.95  4922.8 1772.05
  4929.4 1771.56  4936.2 1774.00  4950.2 1770.94  4957.9 1766.90  4969.7 1765.84
  4970.1 1765.34  4974.8 1765.84  5040.5 1769.62  5185.3 1771.41  5206.2 1772.72
  5227.0 1771.38  5360.4 1772.64  5390.7 1774.44  5475.2 1774.49  5525.8 1776.27
  5553.2 1775.26  5624.6 1775.78  5706.9 1777.78  5735.8 1777.43  5967.9 1778.53
#Mann=8,-1,0
  3891.0   0.035       0  4556.5    0.07       0  4969.7    0.07       0
  4974.8    0.07       0  5040.5   0.035       0  5360.4    0.07       0
  5706.9   0.035       0  5735.8    0.07       0
Bank Sta=4969.7,4974.8
Exp/Cntr=0.3,0.1

Chan Stop Cuts=-1