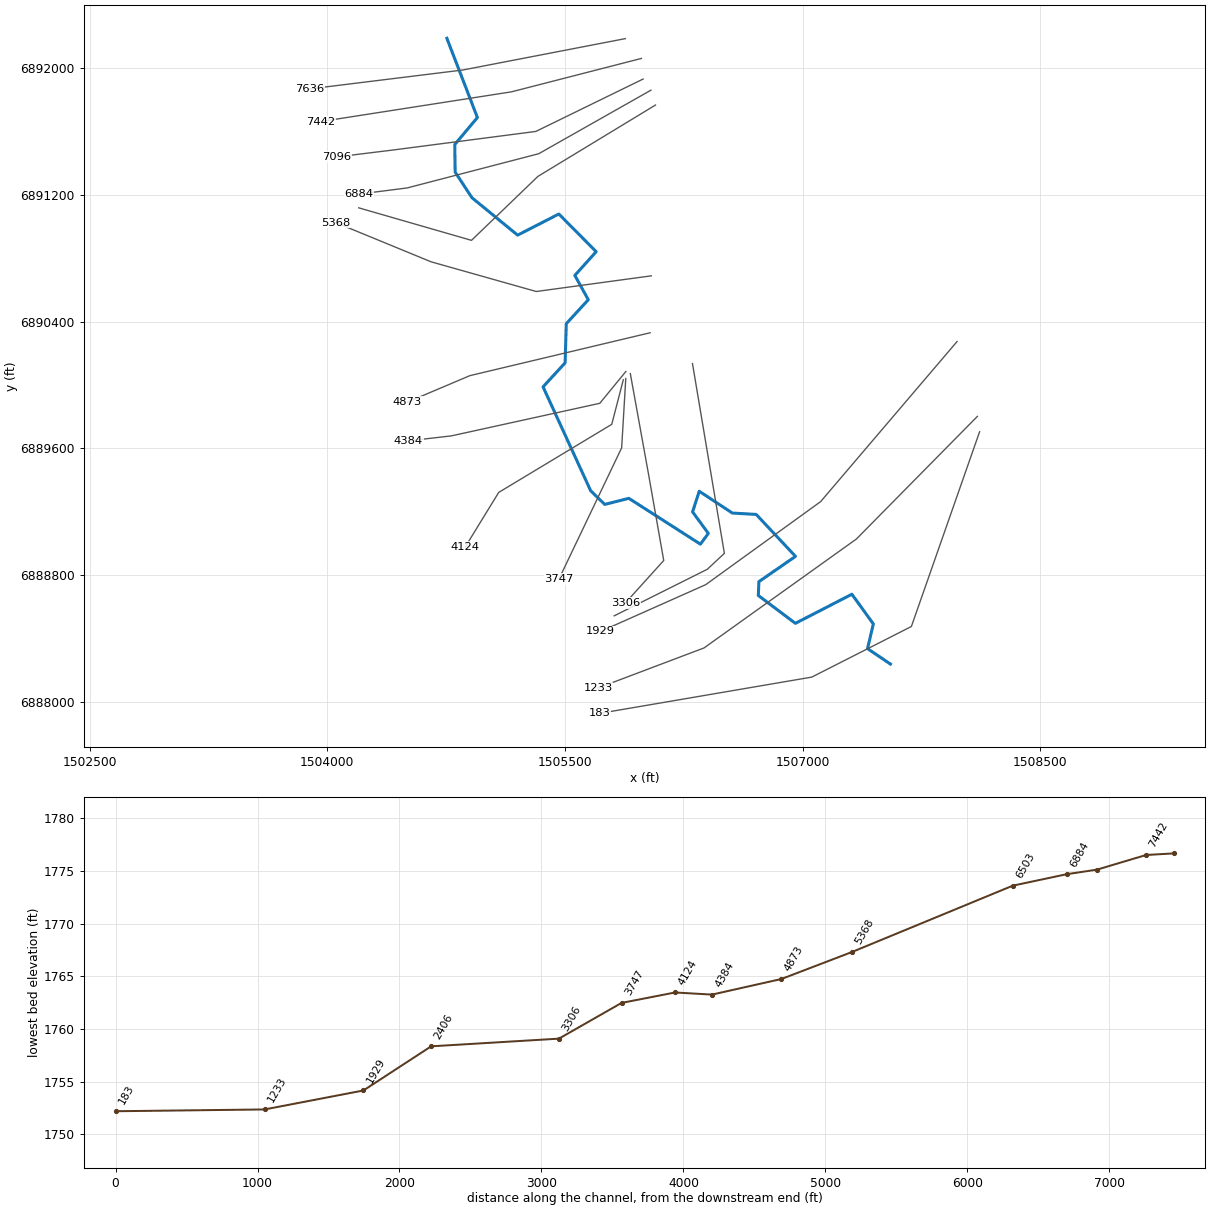
--- NC Unknown Stream 71.prj (project) ---

Proj Title=NC Unknown Stream 71 Base Level Engineering
Current Plan=p01
Default Exp/Contr=0.3,0.1
English Units
Geom File=g01
Flow File=f01
Plan File=p01
BEGIN DESCRIPTION:
NC Unknown Stream 71
END DESCRIPTION:

--- NC Unknown Stream 71.p01 (plan) ---

Plan Title=Multiple Run
Short Identifier=Multiple
Geom File=g01
Flow File=f01
Subcritical Flow
K Sum by GR= 0
Std Step Tol= 0.01
Critical Tol= 0.01
Num of Std Step Trials= 20
Max Error Tol= 0.3
Flow Tol Ratio= 0.001
Split Flow NTrial= 30
Split Flow Tol= 0.02
Split Flow Ratio= 0.02
Log Output Level= 0
Friction Slope Method= 1
Unsteady Friction Slope Method= 2
Unsteady Bridges Friction Slope Method= 1
Parabolic Critical Depth
Global Vel Dist=  1 , 1 , 1
Global Log Level= 0
CheckData=True
Encroach Param= -1, 0, 0, 0
BEGIN DESCRIPTION:
Multiple Run
END DESCRIPTION:

--- NC Unknown Stream 71.f01 (steady flow) ---

Flow Title=Multiple
Number of Profiles=7
Profile Names=10-year,25-year,50-year,1pct_min,100-year,1pct_plu,500-year
River Rch & RM= NC Unknown Strea,Reach-1,7636
     291     407     504     310     619    1234     944
River Rch & RM= NC Unknown Strea,Reach-1,7096
     359     503     623     383     765    1526    1165
Boundary for River Rch & Prof#=NC Unknown Strea,Reach-1,1
Up Type=0
Dn Type=3
Dn Slope=0.001
Boundary for River Rch & Prof#=NC Unknown Strea,Reach-1,2
Up Type=0
Dn Type=3
Dn Slope=0.001
Boundary for River Rch & Prof#=NC Unknown Strea,Reach-1,3
Up Type=0
Dn Type=3
Dn Slope=0.001
Boundary for River Rch & Prof#=NC Unknown Strea,Reach-1,4
Up Type=0
Dn Type=3
Dn Slope=0.001
Boundary for River Rch & Prof#=NC Unknown Strea,Reach-1,5
Up Type=0
Dn Type=3
Dn Slope=0.001
Boundary for River Rch & Prof#=NC Unknown Strea,Reach-1,6
Up Type=0
Dn Type=3
Dn Slope=0.001
Boundary for River Rch & Prof#=NC Unknown Strea,Reach-1,7
Up Type=0
Dn Type=3
Dn Slope=0.001

--- NC Unknown Stream 71.g01 (geometry) ---

Geom Title=Existing Conditions

River Reach=NC Unknown Strea,Reach-1
Reach XY= 30
      1504755.00      6892188.00      1504947.68      6891687.90
      1504804.96      6891518.02      1504807.06      6891343.86
      1504913.15      6891181.93      1505201.67      6890945.61
      1505461.67      6891079.03      1505697.41      6890841.33
      1505562.77      6890691.41      1505647.71      6890537.91
      1505508.54      6890386.54      1505501.46      6890139.46
      1505362.10      6889988.00      1505662.86      6889331.79
      1505751.57      6889245.79      1505903.41      6889284.32
      1506355.28      6888995.01      1506405.59      6889062.81
      1506305.94      6889198.50      1506347.93      6889329.03
      1506556.47      6889191.55      1506707.70      6889182.64
      1506955.55      6888917.87      1506724.40      6888758.12
      1506721.05      6888670.95      1506955.00      6888495.08
      1507311.75      6888678.90      1507446.96      6888491.32
      1507410.38      6888335.56      1507555.00      6888238.00

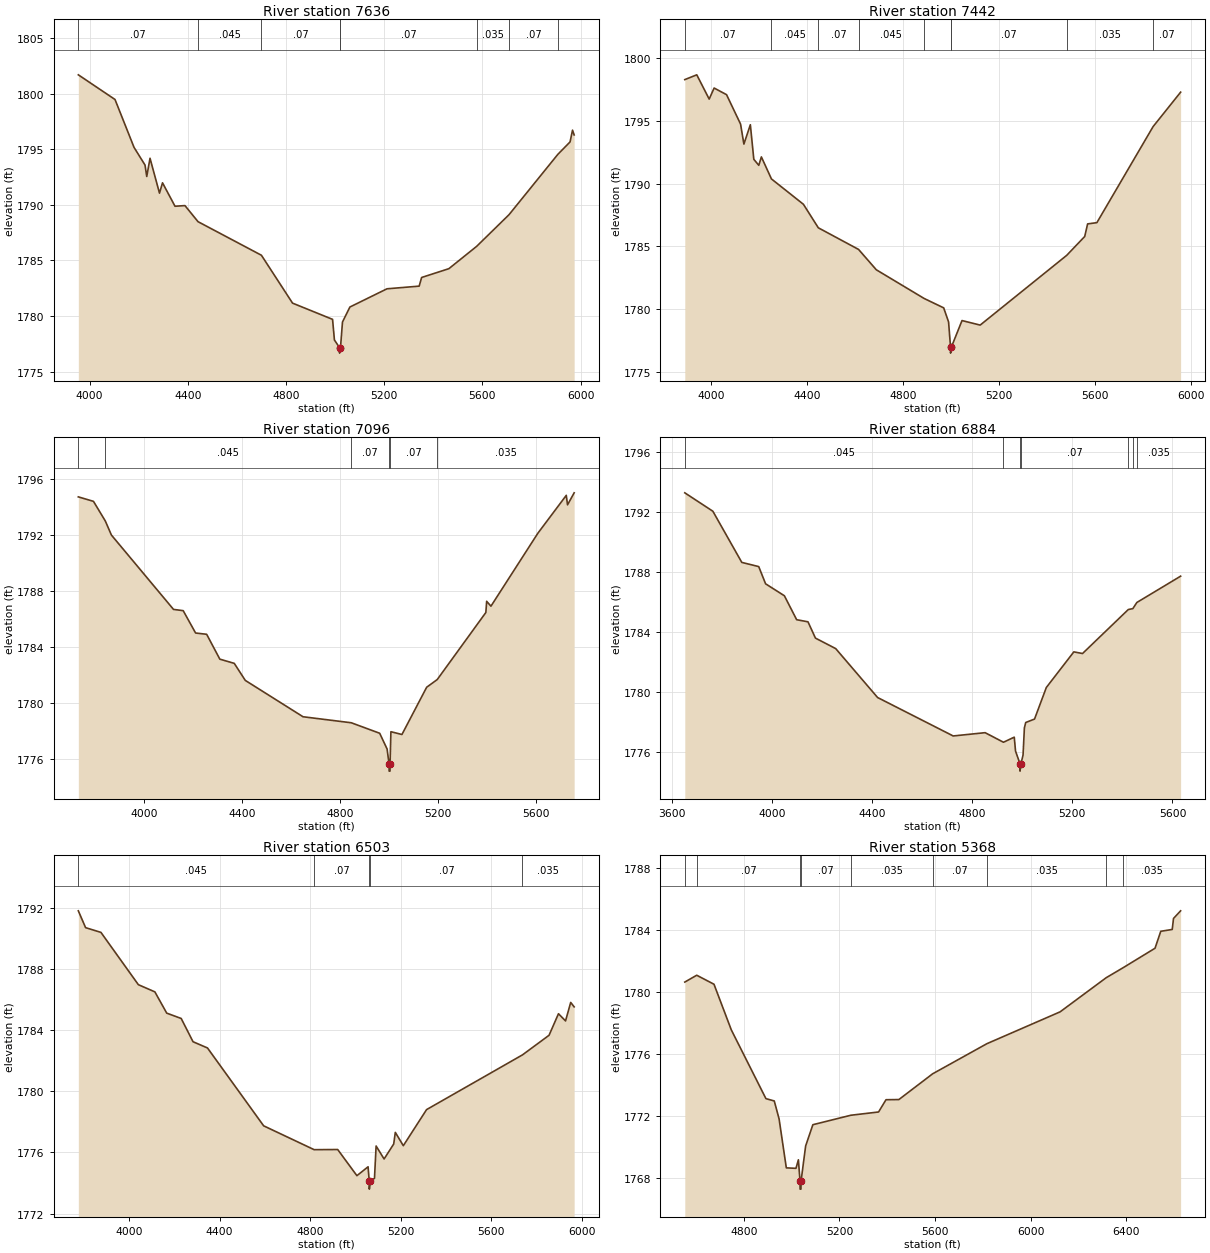
Type RM Length L Ch R = 1,7636,194,194,194
BEGIN DESCRIPTION:
NC Unknown Stream 71 9.0
END DESCRIPTION:
XS GIS Cut Line= 3
      1505881.68      6892186.23      1504855.00      6891988.00
      1503888.47      6891868.72
#Sta/Elev= 30
  3954.4 1801.71  4103.8 1799.49  4181.3 1795.18  4226.0 1793.59  4233.1 1792.56
  4246.4 1794.20  4285.0 1791.06  4297.3 1791.99  4348.2 1789.88  4388.7 1789.94
  4442.0 1788.49  4700.1 1785.47  4826.9 1781.16  4989.9 1779.70  4997.5 1777.84
  5018.2 1777.16  5018.4 1776.66  5022.2 1777.16  5030.3 1779.46  5060.5 1780.81
  5211.6 1782.45  5342.6 1782.69  5352.7 1783.47  5463.5 1784.26  5576.7 1786.27
  5708.6 1789.12  5907.4 1794.55  5957.2 1795.67  5967.3 1796.73  5973.9 1796.30
#Mann=8,-1,0
  3954.4    0.07       0  4442.0   0.045       0  4700.1    0.07       0
  5018.2    0.07       0  5022.2    0.07       0  5576.7   0.035       0
  5708.6    0.07       0  5907.4   0.035       0
Bank Sta=5018.2,5022.2
Exp/Cntr=0.3,0.1

Type RM Length L Ch R = 1,7442,346,346,346
BEGIN DESCRIPTION:
Mapping XS b2e0011e
END DESCRIPTION:
XS GIS Cut Line= 3
      1505983.28      6892061.25      1505162.93      6891850.30
      1503960.58      6891662.92
#Sta/Elev= 30
  3891.9 1798.27  3941.8 1798.65  3993.4 1796.72  4014.0 1797.60  4065.7 1797.07
  4124.1 1794.73  4137.9 1793.14  4164.8 1794.68  4179.2 1791.93  4199.9 1791.45
  4210.7 1792.12  4252.5 1790.37  4385.7 1788.35  4447.7 1786.48  4615.2 1784.76
  4689.1 1783.14  4888.0 1780.86  4969.6 1780.11  4989.9 1778.99  4998.0 1777.01
  4998.2 1776.51  5002.0 1777.01  5045.8 1779.10  5121.4 1778.74  5481.7 1784.29
  5556.6 1785.79  5568.7 1786.79  5607.2 1786.89  5841.2 1794.53  5955.8 1797.27
#Mann=9,-1,0
  3891.9    0.07       0  4252.5   0.045       0  4447.7    0.07       0
  4615.2   0.045       0  4888.0    0.07       0  4998.0    0.07       0
  5002.0    0.07       0  5481.7   0.035       0  5841.2    0.07       0
Bank Sta=4998,5002
Exp/Cntr=0.3,0.1

Type RM Length L Ch R = 1,7096,212,212,212
BEGIN DESCRIPTION:
Mapping XS db473fe7
END DESCRIPTION:
XS GIS Cut Line= 4
      1505993.68      6891931.03      1505316.58      6891600.30
      1504415.54      6891483.11      1504058.12      6891439.08
#Sta/Elev= 30
  3733.3 1794.74  3795.1 1794.42  3843.5 1793.01  3868.2 1792.01  4121.5 1786.69
  4161.0 1786.60  4211.6 1785.00  4256.7 1784.91  4310.5 1783.13  4369.3 1782.83
  4414.3 1781.61  4649.8 1779.01  4846.5 1778.58  4962.4 1777.83  4992.7 1776.70
  5000.7 1775.62  5001.0 1775.12  5004.5 1775.12  5004.7 1775.62  5008.2 1777.94
  5053.2 1777.74  5154.0 1781.12  5197.1 1781.67  5395.5 1786.47  5398.7 1787.27
  5416.2 1786.92  5607.6 1792.14  5723.5 1794.85  5728.6 1794.17  5755.6 1795.03
#Mann=6,-1,0
  3733.3    0.07       0  3843.5   0.045       0  4846.5    0.07       0
  5000.7    0.07       0  5004.7    0.07       0  5197.1   0.035       0
Bank Sta=5000.7,5004.7
Exp/Cntr=0.3,0.1

Type RM Length L Ch R = 1,6884,381,381,381
BEGIN DESCRIPTION:
Mapping XS 2c9e8823
END DESCRIPTION:
XS GIS Cut Line= 4
      1506043.12      6891860.70      1505334.81      6891459.67
      1504504.08      6891243.53      1504198.39      6891204.67
#Sta/Elev= 30
  3652.0 1793.29  3764.1 1792.06  3879.7 1788.64  3947.3 1788.36  3974.7 1787.21
  4049.8 1786.41  4098.8 1784.81  4144.0 1784.67  4173.9 1783.58  4254.7 1782.88
  4422.1 1779.61  4724.1 1777.04  4851.6 1777.26  4924.9 1776.62  4968.0 1776.96
  4973.1 1776.03  4990.7 1775.19  4991.0 1774.69  4994.7 1775.19  5003.1 1775.76
  5008.5 1777.58  5013.7 1777.94  5049.0 1778.17  5096.1 1780.28  5205.9 1782.66
  5240.7 1782.55  5423.5 1785.49  5441.6 1785.55  5457.6 1785.96  5632.5 1787.72
#Mann=7,-1,0
  3652.0   0.045       0  4924.9    0.07       0  4990.7    0.07       0
  4994.7    0.07       0  5423.5   0.035       0  5441.6    0.07       0
  5457.6   0.035       0
Bank Sta=4990.7,4994.7
Exp/Cntr=0.3,0.1

Type RM Length L Ch R = 1,6503,1135,1135,1135
BEGIN DESCRIPTION:
Mapping XS b06bd9f9
END DESCRIPTION:
XS GIS Cut Line= 4
      1506071.80      6891766.97      1505329.60      6891316.44
      1504910.33      6890912.80      1504198.37      6891118.07
#Sta/Elev= 30
  3776.1 1791.80  3808.2 1790.70  3876.0 1790.39  4041.4 1786.97  4114.4 1786.50
  4166.7 1785.11  4230.7 1784.76  4283.0 1783.24  4347.0 1782.83  4595.1 1777.74
  4818.3 1776.18  4922.3 1776.19  5007.2 1774.48  5056.6 1775.06  5061.8 1774.10
  5062.1 1773.60  5065.8 1774.10  5084.9 1774.31  5092.1 1776.42  5127.4 1775.57
  5169.8 1776.55  5177.0 1777.31  5212.3 1776.44  5315.1 1778.80  5739.0 1782.38
  5856.3 1783.66  5898.0 1785.07  5929.2 1784.60  5952.1 1785.81  5967.3 1785.52
#Mann=5,-1,0
  3776.1   0.045       0  4818.3    0.07       0  5061.8    0.07       0
  5065.8    0.07       0  5739.0   0.035       0
Bank Sta=5061.8,5065.8
Exp/Cntr=0.3,0.1

Type RM Length L Ch R = 1,5368,495,495,495
BEGIN DESCRIPTION:
Mapping XS 453b2e08
END DESCRIPTION:
XS GIS Cut Line= 4
      1506045.75      6890688.84      1505319.18      6890589.88
      1504655.12      6890777.38      1504053.60      6891024.76
#Sta/Elev= 30
  4553.1 1780.63  4603.0 1781.07  4675.2 1780.49  4747.6 1777.55  4892.4 1773.12
  4927.3 1772.97  4947.5 1771.81  4977.7 1768.66  5018.1 1768.63  5028.2 1769.18
  5035.1 1767.79  5035.3 1767.29  5038.9 1767.29  5039.2 1767.79  5058.5 1770.07
  5088.7 1771.44  5247.6 1772.05  5363.5 1772.26  5394.6 1773.05  5448.4 1773.06
  5589.7 1774.72  5816.6 1776.66  6122.6 1778.71  6315.5 1780.91  6386.9 1781.56
  6519.8 1782.81  6543.7 1783.90  6591.7 1784.02  6597.1 1784.73  6626.8 1785.22
#Mann=9,-1,0
  4553.1   0.045       0  4603.0    0.07       0  5035.1    0.07       0
  5039.2    0.07       0  5247.6   0.035       0  5589.7    0.07       0
  5816.6   0.035       0  6315.5    0.07       0  6386.9   0.035       0
Bank Sta=5035.1,5039.2
Exp/Cntr=0.3,0.1

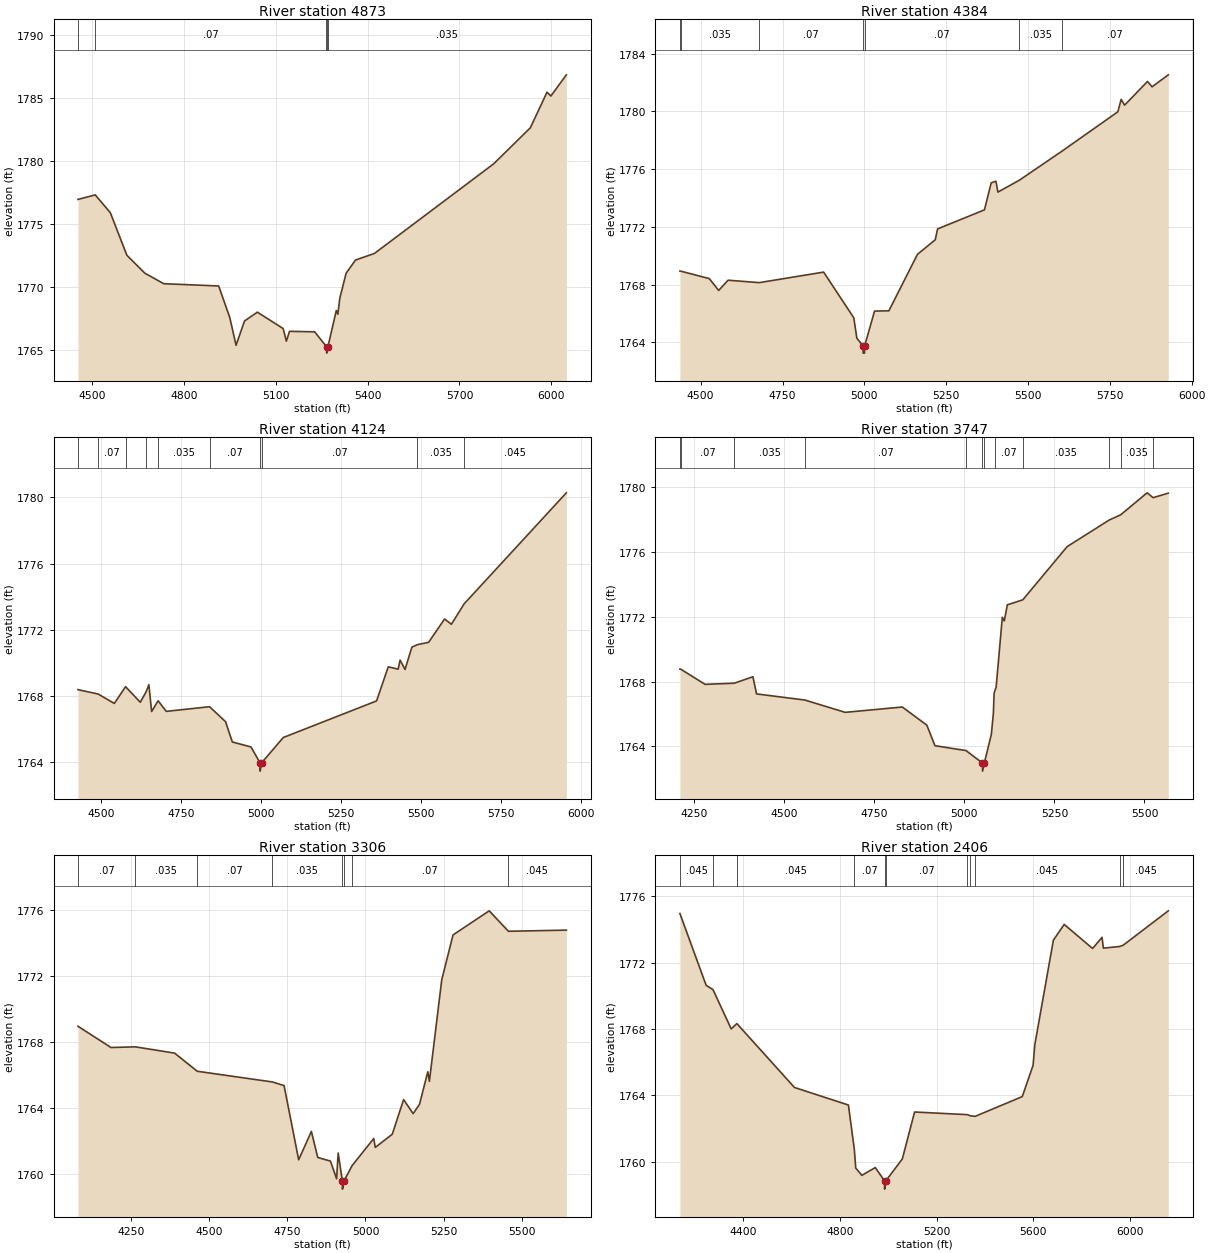
Type RM Length L Ch R = 1,4873,489,489,489
BEGIN DESCRIPTION:
Mapping XS bbc339e7
END DESCRIPTION:
XS GIS Cut Line= 3
      1506037.93      6890329.47      1504899.91      6890058.63
      1504506.68      6889891.96
#Sta/Elev= 30
  4452.5 1776.94  4509.0 1777.30  4558.3 1775.89  4612.4 1772.51  4671.4 1771.08
  4733.1 1770.25  4912.6 1770.07  4948.9 1767.57  4969.5 1765.36  4997.0 1767.29
  5039.1 1767.99  5123.4 1766.69  5133.9 1765.69  5144.2 1766.47  5226.5 1766.43
  5263.9 1765.29  5265.5 1765.24  5265.8 1764.74  5269.7 1765.24  5297.2 1768.12
  5302.3 1767.83  5308.7 1769.10  5329.3 1771.08  5360.1 1772.13  5421.8 1772.65
  5811.5 1779.76  5931.8 1782.63  5986.1 1785.45  5998.9 1785.15  6049.4 1786.83
#Mann=5,-1,0
  4452.5   0.045       0  4509.0    0.07       0  5263.9   0.035       0
  5265.5    0.07       0  5269.7   0.035       0
Bank Sta=5265.5,5269.7
Exp/Cntr=0.3,0.1

Type RM Length L Ch R = 1,4384,260,260,260
BEGIN DESCRIPTION:
Mapping XS 5baaf540
END DESCRIPTION:
XS GIS Cut Line= 4
      1505884.87      6890085.00      1505720.22      6889884.15
      1504782.72      6889678.42      1504511.94      6889647.18
#Sta/Elev= 30
  4436.5 1768.94  4440.0 1768.93  4526.3 1768.42  4555.0 1767.60  4583.7 1768.31
  4678.7 1768.14  4875.6 1768.87  4967.7 1765.71  4977.2 1764.29  4996.0 1763.76
  4996.4 1763.26  5000.5 1763.26  5000.9 1763.76  5031.2 1766.17  5075.0 1766.19
  5162.3 1770.10  5216.7 1771.11  5223.7 1771.86  5367.0 1773.18  5387.5 1775.05
  5402.1 1775.16  5408.0 1774.41  5473.4 1775.23  5604.2 1777.25  5774.5 1779.97
  5784.6 1780.83  5795.1 1780.43  5865.1 1782.07  5879.0 1781.70  5928.6 1782.53
#Mann=7,-1,0
  4436.5    0.07       0  4440.0   0.035       0  4678.7    0.07       0
  4996.0    0.07       0  5000.9    0.07       0  5473.4   0.035       0
  5604.2    0.07       0
Bank Sta=4996,5000.9
Exp/Cntr=0.3,0.1

Type RM Length L Ch R = 1,4124,377,377,377
BEGIN DESCRIPTION:
Mapping XS 44e07c2c
END DESCRIPTION:
XS GIS Cut Line= 4
      1505868.67      6890032.62      1505795.75      6889751.34
      1505082.20      6889321.65      1504871.28      6888977.92
#Sta/Elev= 30
  4428.5 1768.38  4491.2 1768.12  4542.2 1767.55  4577.3 1768.56  4623.4 1767.62
  4641.5 1768.25  4650.2 1768.68  4658.8 1767.06  4679.1 1767.71  4704.6 1767.07
  4839.9 1767.35  4889.8 1766.45  4911.1 1765.22  4969.4 1764.92  4997.7 1763.96
  4998.0 1763.46  5002.6 1763.96  5070.4 1765.49  5362.0 1767.70  5398.6 1769.76
  5429.6 1769.62  5435.5 1770.17  5451.0 1769.60  5472.4 1770.95  5489.8 1771.10
  5524.8 1771.24  5574.6 1772.65  5595.9 1772.33  5635.6 1773.56  5955.3 1780.27
#Mann=10,-1,0
  4428.5   0.035       0  4491.2    0.07       0  4577.3   0.035       0
  4641.5    0.07       0  4679.1   0.035       0  4839.9    0.07       0
  4997.7    0.07       0  5002.6    0.07       0  5489.8   0.035       0
  5635.6   0.045       0
Bank Sta=4997.7,5002.6
Exp/Cntr=0.3,0.1

Type RM Length L Ch R = 1,3747,441,441,441
BEGIN DESCRIPTION:
Mapping XS f5ee357c
END DESCRIPTION:
XS GIS Cut Line= 3
      1505884.29      6890040.42      1505858.25      6889602.90
      1505462.39      6888774.74
#Sta/Elev= 30
  4210.0 1768.77  4212.2 1768.77  4279.9 1767.83  4360.9 1767.90  4412.8 1768.30
  4422.8 1767.24  4557.3 1766.86  4668.9 1766.10  4827.6 1766.43  4895.7 1765.31
  4918.3 1764.04  5004.5 1763.74  5050.1 1762.97  5050.5 1762.47  5055.4 1762.97
  5074.9 1764.75  5080.4 1766.02  5082.6 1767.30  5085.3 1767.47  5088.2 1767.66
  5105.3 1771.97  5110.8 1771.75  5119.2 1772.74  5162.1 1773.05  5285.5 1776.34
  5402.2 1777.98  5433.9 1778.30  5507.4 1779.66  5524.1 1779.36  5566.2 1779.64
#Mann=12,-1,0
  4210.0   0.035       0  4212.2    0.07       0  4360.9   0.035       0
  4557.3    0.07       0  5004.5   0.035       0  5050.1    0.07       0
  5055.4   0.035       0  5085.3    0.07       0  5162.1   0.035       0
  5402.2   0.045       0  5433.9   0.035       0  5524.1   0.045       0
Bank Sta=5050.1,5055.4
Exp/Cntr=0.3,0.1

Type RM Length L Ch R = 1,3306,900,900,900
BEGIN DESCRIPTION:
Mapping XS b8c92327
END DESCRIPTION:
XS GIS Cut Line= 4
      1505912.93      6890071.68      1506027.52      6889438.84
      1506123.87      6888891.97      1505881.70      6888623.75
#Sta/Elev= 30
  4081.7 1768.96  4187.1 1767.67  4264.6 1767.71  4390.3 1767.33  4462.6 1766.23
  4702.9 1765.58  4740.0 1765.36  4786.6 1760.86  4827.2 1762.58  4847.5 1761.00
  4888.1 1760.78  4907.7 1759.71  4912.8 1761.27  4926.1 1759.58  4926.5 1759.08
  4931.4 1759.58  4957.4 1760.51  5026.3 1762.15  5031.3 1761.61  5085.5 1762.41
  5121.7 1764.51  5152.2 1763.66  5172.5 1764.22  5199.0 1766.20  5204.1 1765.62
  5243.5 1771.77  5279.6 1774.50  5395.2 1775.96  5456.4 1774.72  5641.5 1774.79
#Mann=8,-1,0
  4081.7    0.07       0  4264.6   0.035       0  4462.6    0.07       0
  4702.9   0.035       0  4926.1    0.07       0  4931.4   0.035       0
  4957.4    0.07       0  5456.4   0.045       0
Bank Sta=4926.1,4931.4
Exp/Cntr=0.3,0.1

Type RM Length L Ch R = 1,2406,477,477,477
BEGIN DESCRIPTION:
Mapping XS bd0db2f0
END DESCRIPTION:
XS GIS Cut Line= 4
      1506305.30      6890135.01      1506506.68      6888937.10
      1506399.04      6888836.41      1505811.15      6888542.46
#Sta/Elev= 30
  4138.8 1774.97  4247.3 1770.64  4275.6 1770.38  4351.0 1768.01  4374.4 1768.33
  4612.4 1764.48  4835.6 1763.42  4860.1 1760.73  4865.9 1759.62  4891.1 1759.18
  4946.6 1759.65  4984.9 1758.85  4985.3 1758.35  4990.3 1758.85  5058.5 1760.17
  5109.2 1763.00  5327.3 1762.84  5340.3 1762.77  5360.0 1762.74  5554.5 1763.93
  5599.2 1765.82  5606.1 1767.04  5683.1 1773.36  5727.8 1774.31  5845.2 1772.86
  5884.3 1773.53  5889.9 1772.88  5956.8 1772.98  5972.0 1773.06  6158.2 1775.13
#Mann=11,-1,0
  4138.8   0.045       0  4275.6   0.035       0  4374.4   0.045       0
  4860.1    0.07       0  4984.9    0.07       0  4990.3    0.07       0
  5327.3   0.045       0  5340.3    0.07       0  5360.0   0.045       0
  5956.8    0.07       0  5972.0   0.045       0
Bank Sta=4984.9,4990.3
Exp/Cntr=0.3,0.1

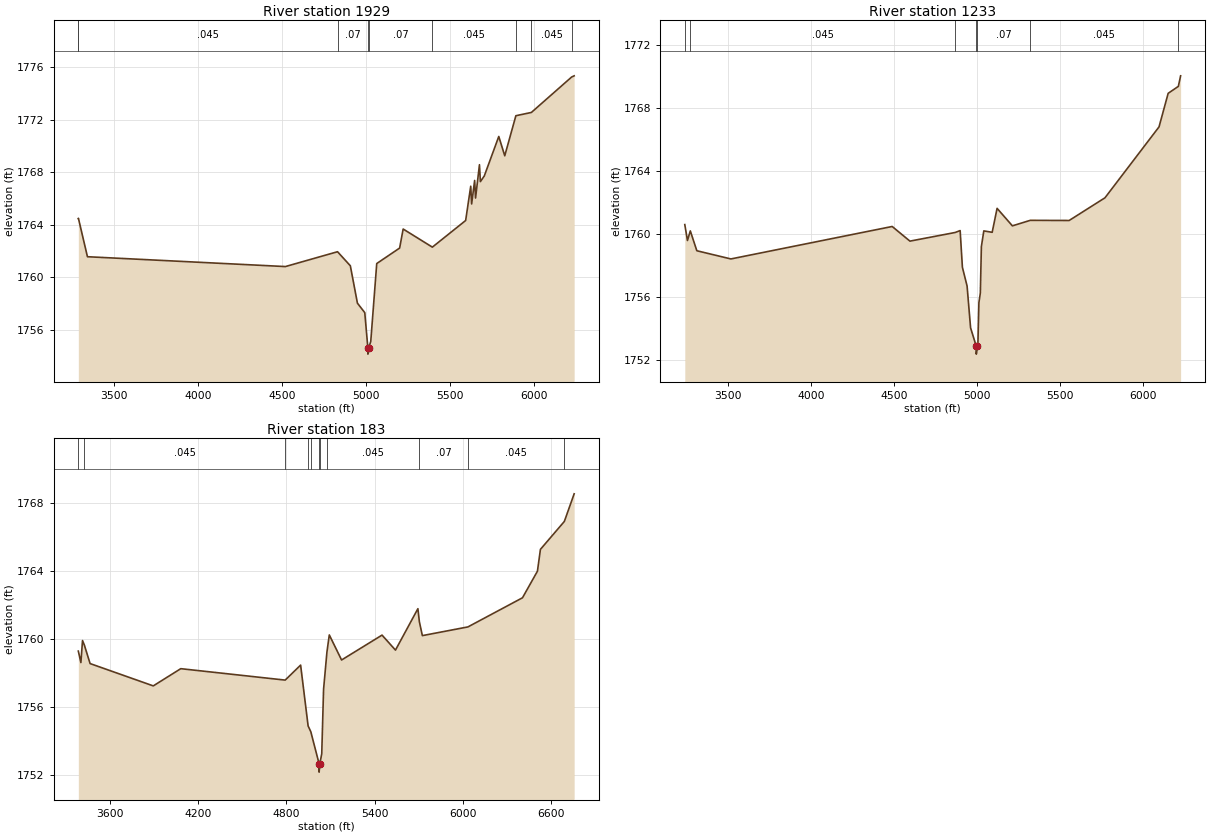
Type RM Length L Ch R = 1,1929,696,696,696
BEGIN DESCRIPTION:
Mapping XS bf3e5fe9
END DESCRIPTION:
XS GIS Cut Line= 4
      1507975.44      6890273.92      1507114.32      6889263.49
      1506388.63      6888739.19      1505725.41      6888444.04
#Sta/Elev= 30
  3288.9 1764.49  3289.4 1764.51  3343.1 1761.58  4520.2 1760.83  4830.4 1761.96
  4906.6 1760.89  4948.8 1758.04  4992.5 1757.32  5010.6 1754.66  5011.0 1754.16
  5016.0 1754.66  5028.0 1755.12  5063.6 1761.06  5199.8 1762.24  5220.7 1763.69
  5394.3 1762.31  5592.4 1764.34  5622.6 1766.95  5628.0 1765.60  5645.8 1767.39
  5651.3 1766.05  5674.5 1768.59  5680.0 1767.30  5703.2 1767.73  5789.4 1770.74
  5824.9 1769.27  5891.1 1772.32  5983.3 1772.57  6222.8 1775.27  6237.7 1775.36
#Mann=9,-1,0
  3288.9   0.035       0  3289.4   0.045       0  4830.4    0.07       0
  5010.6    0.07       0  5016.0    0.07       0  5394.3   0.045       0
  5891.1    0.07       0  5983.3   0.045       0  6222.8    0.07       0
Bank Sta=5010.6,5016
Exp/Cntr=0.3,0.1

Type RM Length L Ch R = 1,1233,1050,1050,1050
BEGIN DESCRIPTION:
Mapping XS deeb8757
END DESCRIPTION:
XS GIS Cut Line= 4
      1508103.88      6889801.66      1507340.02      6889027.38
      1506378.21      6888339.88      1505708.99      6888086.76
#Sta/Elev= 30
  3240.3 1760.58  3256.3 1759.57  3273.5 1760.18  3312.8 1758.92  3517.9 1758.40
  4489.0 1760.46  4595.9 1759.53  4868.6 1760.08  4898.2 1760.20  4911.8 1757.87
  4940.0 1756.68  4961.0 1754.03  4995.2 1752.86  4995.6 1752.36  5000.6 1752.86
  5005.1 1752.99  5011.2 1755.63  5019.8 1756.24  5026.0 1759.18  5040.7 1760.18
  5091.1 1760.09  5120.6 1761.61  5212.8 1760.50  5320.6 1760.85  5554.5 1760.84
  5770.2 1762.28  6095.7 1766.78  6150.7 1768.91  6212.0 1769.35  6225.7 1770.02
#Mann=7,-1,0
  3240.3   0.035       0  3273.5   0.045       0  4868.6    0.07       0
  4995.2    0.07       0  5000.6    0.07       0  5320.6   0.045       0
  6212.0    0.07       0
Bank Sta=4995.2,5000.6
Exp/Cntr=0.3,0.1

Type RM Length L Ch R = 1,183,0,0,0
BEGIN DESCRIPTION:
NC Unknown Stream 71 1.0
END DESCRIPTION:
XS GIS Cut Line= 4
      1508117.78      6889704.43      1507687.24      6888475.30
      1507058.77      6888155.85      1505719.26      6887926.82
#Sta/Elev= 30
  3387.6 1759.29  3405.0 1758.62  3416.0 1759.91  3428.3 1759.65  3467.5 1758.56
  3896.4 1757.25  4083.1 1758.26  4791.9 1757.59  4896.8 1758.47  4947.7 1754.90
  4966.0 1754.56  5022.0 1752.69  5022.4 1752.19  5027.4 1752.69  5040.2 1753.27
  5052.6 1757.05  5075.5 1759.24  5091.5 1760.24  5174.8 1758.77  5449.5 1760.23
  5540.8 1759.35  5693.0 1761.78  5703.1 1761.01  5723.4 1760.20  6032.6 1760.71
  6403.1 1762.42  6504.6 1763.98  6524.9 1765.26  6687.3 1766.90  6753.9 1768.52
#Mann=11,-1,0
  3387.6   0.035       0  3428.3   0.045       0  4791.9    0.07       0
  4947.7   0.045       0  4966.0    0.07       0  5022.0    0.07       0
  5027.4    0.07       0  5075.5   0.045       0  5703.1    0.07       0
  6032.6   0.045       0  6687.3    0.07       0
Bank Sta=5022,5027.4
Exp/Cntr=0.3,0.1

Chan Stop Cuts=-1