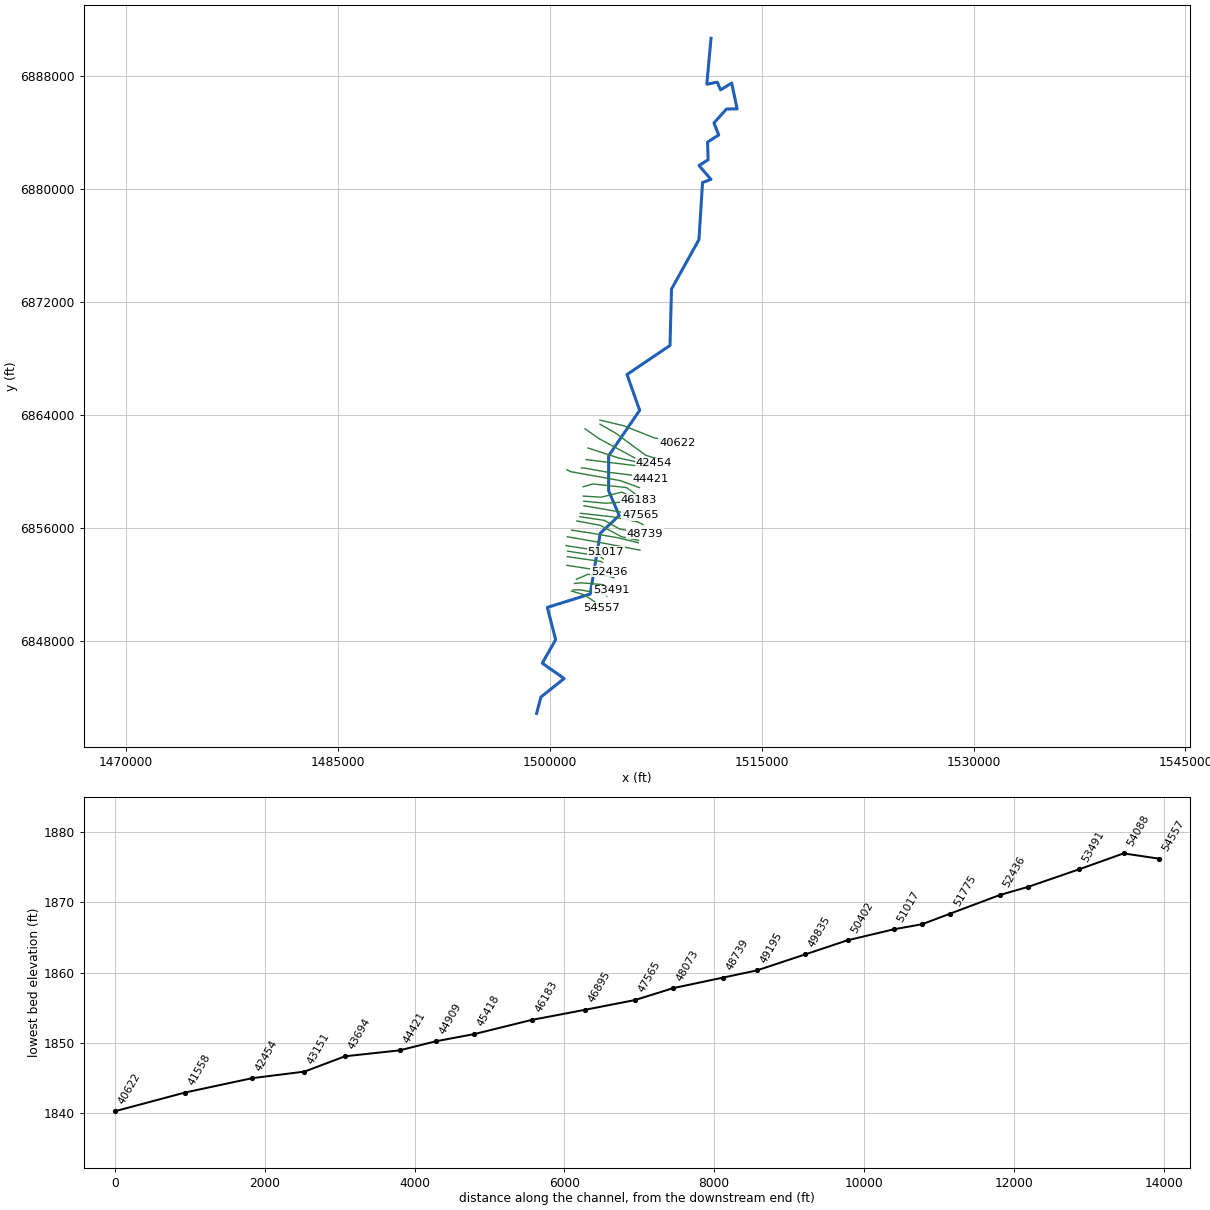
--- NC Unknown Stream 72.prj (project) ---

Proj Title=NC Unknown Stream 72 Base Level Engineering
Current Plan=p01
Default Exp/Contr=0.3,0.1
English Units
Geom File=g01
Flow File=f01
Plan File=p01
Y Axis Title=Elevation
X Axis Title(PF)=Main Channel Distance
X Axis Title(XS)=Station
BEGIN DESCRIPTION:
NC Unknown Stream 72
END DESCRIPTION:
DSS Export Rating Curves= 0
DSS Export Rating Curve Sorted= 0
DSS Export Volume Flow Curves= 0
DXF OffsetX= 0
DXF OffsetY= 0
DXF ScaleX= 1
DXF ScaleY= 10

--- NC Unknown Stream 72.p01 (plan) ---

Plan Title=Multiple Run
Short Identifier=Multiple
Geom File=g01
Flow File=f01
Subcritical Flow
K Sum by GR= 0
Std Step Tol= 0.01
Critical Tol= 0.01
Num of Std Step Trials= 20
Max Error Tol= 0.3
Flow Tol Ratio= 0.001
Split Flow NTrial= 30
Split Flow Tol= 0.02
Split Flow Ratio= 0.02
Log Output Level= 0
Friction Slope Method= 1
Unsteady Friction Slope Method= 2
Unsteady Bridges Friction Slope Method= 1
Parabolic Critical Depth
Global Vel Dist=  1 , 1 , 1
Global Log Level= 0
CheckData=True
Encroach Param= -1, 0, 0, 0
BEGIN DESCRIPTION:
Multiple Run
END DESCRIPTION:

--- NC Unknown Stream 72.f01 (steady flow) ---

Flow Title=Multiple
Program Version=4.10
Number of Profiles= 7
Profile Names=10-year,25-year,50-year,1pct_min,100-year,1pct_plu,500-year
River Rch & RM=NC Unknown Strea,Reach-1         ,54557
     712    1023    1287     801    1599    3191    2501
River Rch & RM=NC Unknown Strea,Reach-1         ,52436
     796    1149    1451     906    1809    3609    2847
River Rch & RM=NC Unknown Strea,Reach-1         ,49195
     796    1149    1451     906    1809    3609    2847
River Rch & RM=NC Unknown Strea,Reach-1         ,47565
     859    1244    1573     984    1964    3919    3100
River Rch & RM=NC Unknown Strea,Reach-1         ,41558
     919    1333    1689    1058    2111    4211    3342
River Rch & RM=NC Unknown Strea,Reach-1         ,38183
     969    1409    1787    1121    2237    4463    3550
River Rch & RM=NC Unknown Strea,Reach-1         ,32178
    1009    1469    1863    1169    2333    4655    3706
River Rch & RM=NC Unknown Strea,Reach-1         ,27364
    1032    1502    1907    1197    2389    4766    3798
River Rch & RM=NC Unknown Strea,Reach-1         ,25856
    1124    1634    2072    1300    2593    5174    4113
River Rch & RM=NC Unknown Strea,Reach-1         ,24150
    1249    1823    2319    1458    2910    5806    4642
River Rch & RM=NC Unknown Strea,Reach-1         ,22808
    1249    1823    2319    1458    2910    5806    4642
River Rch & RM=NC Unknown Strea,Reach-1         ,20255
    1249    1823    2319    1458    2910    5806    4642
River Rch & RM=NC Unknown Strea,Reach-1         ,15011
    1273    1858    2364    1487    2967    5919    4734
River Rch & RM=NC Unknown Strea,Reach-1         ,12789
    1330    1943    2473    1557    3106    6197    4962
River Rch & RM=NC Unknown Strea,Reach-1         ,9147
    1330    1943    2473    1557    3106    6197    4962
River Rch & RM=NC Unknown Strea,Reach-1         ,3884
    1371    2004    2553    1608    3208    6401    5131
Boundary for River Rch & Prof#=NC Unknown Strea,Reach-1         , 1
Up Type= 0
Dn Type= 3
Dn Slope=0.001
Boundary for River Rch & Prof#=NC Unknown Strea,Reach-1         , 2
Up Type= 0
Dn Type= 3
Dn Slope=0.001
Boundary for River Rch & Prof#=NC Unknown Strea,Reach-1         , 3
Up Type= 0
Dn Type= 3
Dn Slope=0.001
Boundary for River Rch & Prof#=NC Unknown Strea,Reach-1         , 4
Up Type= 0
Dn Type= 3
Dn Slope=0.001
Boundary for River Rch & Prof#=NC Unknown Strea,Reach-1         , 5
Up Type= 0
Dn Type= 3
Dn Slope=0.001
Boundary for River Rch & Prof#=NC Unknown Strea,Reach-1         , 6
Up Type= 0
Dn Type= 3
Dn Slope=0.001
Boundary for River Rch & Prof#=NC Unknown Strea,Reach-1         , 7
Up Type= 0
Dn Type= 3
Dn Slope=0.001
DSS Import GetInterval= 0
DSS Import GetPeak= 0
DSS Import FillOption= 0

--- NC Unknown Stream 72.g01 (geometry) ---

Geom Title=Existing Conditions
Program Version=4.10

River Reach=NC Unknown Strea,Reach-1
Reach XY= 30
        1499055.        6842888.      1499365.48       6844047.8
      1501004.51      6845353.22      1499456.96      6846443.89
      1500404.63      6848103.16      1499812.89      6850391.59
      1502851.39       6851339.5      1503558.75      6855636.45
      1504904.59      6856898.63      1504155.52      6858653.89
      1504157.06      6861132.15       1506353.9      6864348.55
      1505457.06      6866882.15      1508501.17      6868939.58
      1508607.26      6872932.06      1510551.47      6876439.47
      1510805.93      6880477.52      1511404.07      6880698.48
      1510556.75       6881681.9      1511201.45      6882089.47
      1511163.16      6883344.05      1511953.21      6883844.11
      1511612.73      6884694.14      1512502.53      6885682.55
      1513253.12      6885693.79      1512868.75       6887524.8
      1512080.09      6887037.67      1511853.53      6887584.46
      1511108.51      6887439.25        1511405.        6890688.

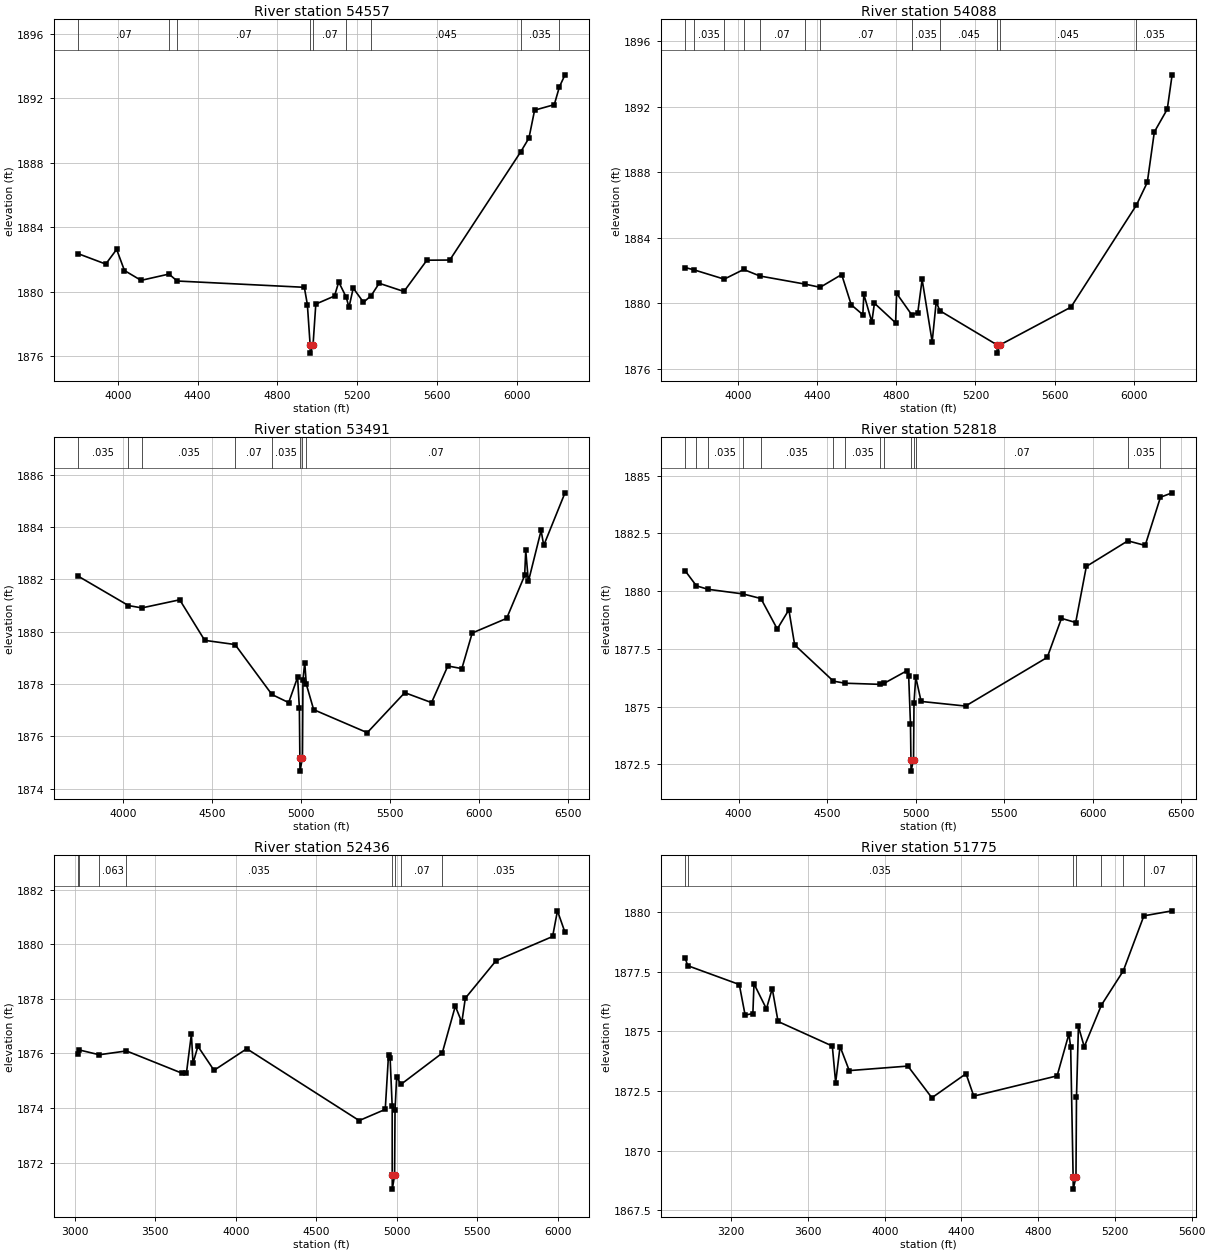
Type RM Length L Ch R = 1 ,54557   ,469,469,469
BEGIN DESCRIPTION:
Mapping XS 2a914a86
END DESCRIPTION:
XS GIS Cut Line= 4
      1501530.88      6851546.56      1502379.88      6851299.16
      1503150.72      6850804.36      1503627.31      6850374.65
#Sta/Elev= 30
  3799.7 1882.37  3939.4 1881.72  3993.9 1882.63  4033.1 1881.32  4116.5 1880.71
  4256.2  1881.1  4297.5 1880.67  4934.9 1880.28  4950.1 1879.21    4964  1876.7
  4964.5  1876.2  4978.5  1876.7  4992.4 1879.24  5086.2 1879.74  5107.3 1880.61
  5144.7 1879.67  5158.8 1879.04    5180 1880.23  5231.5 1879.35  5270.3 1879.77
  5310.1 1880.53  5434.3 1880.02  5549.3 1881.96  5664.1 1881.97  6019.4 1888.67
  6060.9 1889.53  6089.3 1891.26  6187.9  1891.6  6213.8 1892.71  6241.7 1893.45
#Mann= 9 ,-1 , 0
  3799.7     .07       0  4256.2    .035       0  4297.5     .07       0
    4964     .07       0  4978.5     .07       0  5144.7    .035       0
  5270.3    .045       0  6019.4    .035       0  6213.8     .07       0
Bank Sta=4964,4978.5
XS Rating Curve= 0 ,0
Exp/Cntr=0.3,0.1

Type RM Length L Ch R = 1 ,54088   ,597,597,597
BEGIN DESCRIPTION:
Mapping XS 2b401f1d
END DESCRIPTION:
XS GIS Cut Line= 4
      1501648.99      6851626.85      1502110.78      6851640.74
      1503819.12      6851331.71      1504040.69      6851189.76
#Sta/Elev= 30
  3732.4 1882.17  3776.9 1882.03  3930.4 1881.46  4028.7 1882.05    4111 1881.65
  4336.9 1881.16  4415.1 1880.96  4523.9 1881.74  4572.3 1879.89  4630.8 1879.29
  4635.9 1880.53  4676.3 1878.85  4689.4 1879.99  4796.4 1878.79  4801.5 1880.59
  4877.9 1879.28  4908.5 1879.42  4930.4 1881.44  4981.2 1877.63  5001.5 1880.07
    5020 1879.53  5309.3 1877.44  5309.8 1876.94  5323.8 1877.44  5682.4 1879.75
  6013.1 1885.98  6068.1 1887.37  6103.7 1890.45    6169 1891.84  6193.6 1893.94
#Mann= 12 ,-1 , 0
  3732.4     .07       0  3776.9    .035       0  3930.4     .07       0
  4028.7    .035       0    4111     .07       0  4336.9    .035       0
  4415.1     .07       0  4877.9    .035       0    5020    .045       0
  5309.3    .035       0  5323.8    .045       0  6013.1    .035       0
Bank Sta=5309.3,5323.8
XS Rating Curve= 0 ,0
Exp/Cntr=0.3,0.1

Type RM Length L Ch R = 1 ,53491   ,673,673,673
BEGIN DESCRIPTION:
Mapping XS 65d266f2
END DESCRIPTION:
XS GIS Cut Line= 4
      1501735.74      6852085.18      1502204.53      6852133.79
      1503773.98      6852001.85      1504339.99      6851605.99
#Sta/Elev= 30
  3745.5 1882.13  4029.6    1881  4104.8 1880.91  4317.6 1881.22  4458.1 1879.67
  4628.5 1879.51  4835.6  1877.6  4929.8 1877.29    4980 1878.26    4990 1877.07
  4992.7 1875.17  4993.2 1874.67  5007.3 1875.17  5010.1 1878.16  5020.1 1878.82
    5029 1877.99  5070.3 1877.02  5371.3 1876.14  5582.1 1877.67  5732.6 1877.29
  5824.1 1878.69  5902.9 1878.59    5961 1879.95  6154.6 1880.51  6255.8 1882.15
  6261.9 1883.11  6276.7 1881.92  6348.2 1883.87    6363  1883.3  6482.5 1885.31
#Mann= 8 ,-1 , 0
  3745.5    .035       0  4029.6     .07       0  4104.8    .035       0
  4628.5     .07       0  4835.6    .035       0  4992.7    .035       0
  5007.3    .035       0    5029     .07       0
Bank Sta=4992.7,5007.3
XS Rating Curve= 0 ,0
Exp/Cntr=0.3,0.1

Type RM Length L Ch R = 1 ,52818   ,382,382,382
BEGIN DESCRIPTION:
Mapping XS b44010a3
END DESCRIPTION:
XS GIS Cut Line= 4
      1501878.15      6852380.32      1502690.65      6852737.96
      1504128.15      6852616.43      1504530.46      6852491.57
#Sta/Elev= 30
    3697 1880.89  3761.2 1880.23  3826.5 1880.08  4023.4 1879.88  4125.6 1879.68
    4218 1878.36  4283.6 1879.19  4316.3 1877.67    4535  1876.1  4600.7 1876.01
  4799.9 1875.96  4822.8 1876.01  4950.4 1876.55  4960.4 1876.32  4970.5 1874.25
  4973.2  1872.7  4973.7  1872.2  4987.8  1872.7  4990.5 1875.17  5000.4 1876.27
  5030.7 1875.22  5281.6 1875.02  5743.2 1877.13  5823.5 1878.82  5903.8 1878.64
    5964 1881.07  6198.6 1882.18  6296.3 1881.98  6382.7 1884.07  6448.6 1884.26
#Mann= 14 ,-1 , 0
    3697    .035       0  3761.2     .07       0  3826.5    .035       0
  4023.4     .07       0  4125.6    .035       0    4535     .07       0
  4600.7    .035       0  4799.9     .07       0  4822.8    .035       0
  4973.2    .035       0  4987.8    .035       0  5000.4     .07       0
  6198.6    .035       0  6382.7     .07       0
Bank Sta=4973.2,4987.8
XS Rating Curve= 0 ,0
Exp/Cntr=0.3,0.1

Type RM Length L Ch R = 1 ,52436   ,661,661,661
BEGIN DESCRIPTION:
Mapping XS 309bff17
END DESCRIPTION:
XS GIS Cut Line= 3
      1501198.43      6853374.25      1503680.23      6852986.22
      1504191.59      6852931.71
#Sta/Elev= 30
  3019.3 1875.98  3024.5 1876.13    3152 1875.95  3321.1 1876.09  3663.6 1875.28
    3694  1875.3  3724.3  1876.7  3734.4 1875.64  3764.8 1876.26    3865 1875.38
  4068.5 1876.17  4766.8 1873.54  4928.8 1873.95    4949 1875.94  4959.1 1875.82
  4971.9 1874.06    4972 1871.53  4972.5 1871.03  4986.8 1871.53  4989.5 1873.92
  4999.6 1875.13  5027.1 1874.87  5282.7 1876.01    5364 1877.73  5404.5 1877.14
  5426.2 1878.02  5616.5 1879.39  5968.5 1880.28  5998.6 1881.22  6045.5 1880.43
#Mann= 8 ,-1 , 0
  3019.3    .063       0  3024.5    .035       0    3152    .063       0
  3321.1    .035       0    4972    .035       0  4986.8    .035       0
  5027.1     .07       0  5282.7    .035       0
Bank Sta=4972,4986.8
XS Rating Curve= 0 ,0
Exp/Cntr=0.3,0.1

Type RM Length L Ch R = 1 ,51775   ,376,376,376
BEGIN DESCRIPTION:
Mapping XS 3ba48bbe
END DESCRIPTION:
XS GIS Cut Line= 3
      1501234.89      6853983.62      1503638.56      6853642.47
      1503720.91      6853567.84
#Sta/Elev= 30
  2959.3  1878.1  2973.2 1877.76  3242.2 1876.97  3272.5 1875.69  3312.9 1875.75
  3318.8    1877  3383.6 1875.95  3413.9  1876.8  3444.2 1875.42    3727 1874.39
  3744.4 1872.86  3767.4 1874.37  3815.3 1873.36  4120.9 1873.55  4245.9 1872.22
  4423.9 1873.23  4464.3 1872.29  4898.7 1873.14  4960.3  1874.9  4969.4 1874.33
  4982.2 1868.89  4982.7 1868.39    4997 1868.89  4999.7 1872.25  5009.8 1875.21
  5040.1 1874.36  5129.8 1876.11  5243.5 1877.54    5351 1879.85  5498.2 1880.06
#Mann= 7 ,-1 , 0
  2959.3    .063       0  2973.2    .035       0  4982.2    .035       0
    4997    .035       0  5129.8     .07       0  5243.5    .035       0
    5351     .07       0
Bank Sta=4982.2,4997
XS Rating Curve= 0 ,0
Exp/Cntr=0.3,0.1

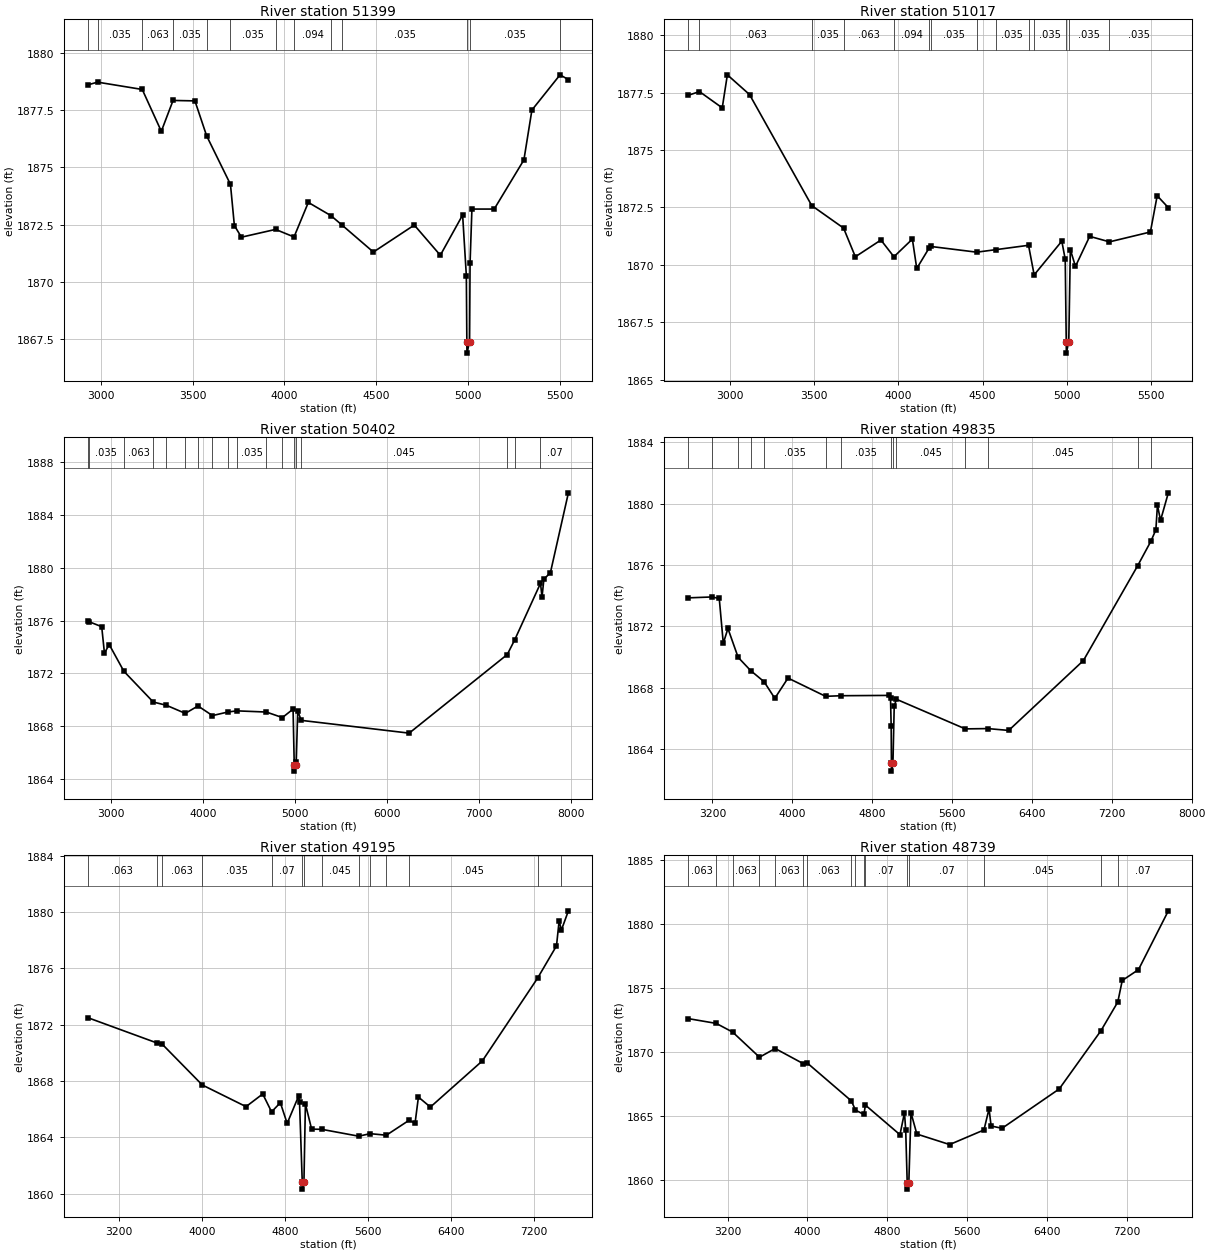
Type RM Length L Ch R = 1 ,51399   ,382,382,382
BEGIN DESCRIPTION:
Mapping XS f6b28cf6
END DESCRIPTION:
XS GIS Cut Line= 3
      1501258.83       6854375.1      1503520.07      6854023.55
      1503780.21      6853824.11
#Sta/Elev= 30
  2929.4 1878.61  2982.4 1878.73  3225.7 1878.41  3329.5 1876.58  3393.4 1877.93
  3512.5 1877.91  3576.3 1876.38  3705.9 1874.26  3727.2 1872.46  3765.5 1871.95
  3951.4 1872.29    4052 1871.96  4129.8 1873.47  4253.3 1872.89  4314.7 1872.47
    4484  1871.3  4706.7 1872.48  4848.4 1871.16  4969.8 1872.92    4990 1870.27
  4992.8 1867.38  4993.3 1866.88  5007.6 1867.38  5010.3 1870.83  5020.4 1873.18
  5141.8 1873.18  5303.4 1875.33    5347 1877.51  5500.2 1879.05  5545.6 1878.84
#Mann= 13 ,-1 , 0
  2929.4    .063       0  2982.4    .035       0  3225.7    .063       0
  3393.4    .035       0  3576.3    .063       0  3705.9    .035       0
  3951.4    .063       0    4052    .094       0  4253.3    .063       0
  4314.7    .035       0  4992.8    .035       0  5007.6    .035       0
  5500.2     .07       0
Bank Sta=4992.8,5007.6
XS Rating Curve= 0 ,0
Exp/Cntr=0.3,0.1

Type RM Length L Ch R = 1 ,51017   ,615,615,615
BEGIN DESCRIPTION:
Mapping XS b677d3ac
END DESCRIPTION:
XS GIS Cut Line= 3
      1501132.94      6854765.73      1503611.22      6854383.79
      1503950.61      6854341.11
#Sta/Elev= 30
    2752 1877.38  2821.3 1877.55  2956.4 1876.84  2986.8 1878.28  3118.3 1877.42
  3487.3 1872.58  3675.9  1871.6  3745.7 1870.35  3897.4 1871.08  3974.5 1870.35
  4083.8 1871.12  4109.9 1869.84  4182.2 1870.72  4192.3  1870.8  4465.6 1870.55
    4579 1870.66  4772.6 1870.85    4806 1869.56  4969.9 1871.03  4990.2 1870.24
  4996.3 1866.65  4996.8 1866.15  5011.2 1866.65  5020.5 1870.66  5050.9 1869.93
  5135.2 1871.24  5252.6    1871  5495.2 1871.43  5535.5 1873.01  5601.6 1872.49
#Mann= 14 ,-1 , 0
    2752    .035       0  2821.3    .063       0  3487.3    .035       0
  3675.9    .063       0  3974.5    .094       0  4182.2    .063       0
  4192.3    .035       0  4465.6    .063       0    4579    .035       0
  4772.6    .063       0    4806    .035       0  4996.3    .045       0
  5011.2    .035       0  5252.6    .035       0
Bank Sta=4996.3,5011.2
XS Rating Curve= 0 ,0
Exp/Cntr=0.3,0.1

Type RM Length L Ch R = 1 ,50402   ,567,567,567
BEGIN DESCRIPTION:
NC Unknown Stream 72 45.0
END DESCRIPTION:
XS GIS Cut Line= 3
       1501236.2      6855395.08      1503460.18      6855004.45
       1506376.8      6854447.17
#Sta/Elev= 30
  2747.4 1875.94  2756.8 1875.93  2898.5 1875.54  2928.3 1873.53  2979.7 1874.19
  3139.7 1872.16  3458.9 1869.83  3602.9 1869.58  3807.4 1868.97    3946 1869.53
  4102.9  1868.8  4269.4 1869.07  4367.4 1869.16  4689.5 1869.07  4863.5 1868.65
  4979.9 1869.29  4992.7 1865.09  4993.2 1864.59  5007.6 1865.09  5014.3 1865.27
  5030.7 1869.17    5068 1868.44    6243 1867.47  7309.8 1873.43  7391.3 1874.55
  7671.3 1878.83  7687.9  1877.8  7708.3 1879.14  7779.2 1879.64  7974.8 1885.69
#Mann= 18 ,-1 , 0
  2747.4    .063       0  2756.8    .035       0  3139.7    .063       0
  3458.9    .035       0  3602.9    .063       0  3807.4    .035       0
    3946    .094       0  4102.9    .035       0  4269.4    .063       0
  4367.4    .035       0  4689.5    .063       0  4863.5    .035       0
  4992.7    .035       0  5007.6    .035       0    5068    .045       0
  7309.8     .07       0  7391.3    .035       0  7671.3     .07       0
Bank Sta=4992.7,5007.6
XS Rating Curve= 0 ,0
Exp/Cntr=0.3,0.1

Type RM Length L Ch R = 1 ,49835   ,640,640,640
BEGIN DESCRIPTION:
NC Unknown Stream 72 44.0
END DESCRIPTION:
XS GIS Cut Line= 4
      1501533.11      6855863.82      1502829.97      6855665.91
      1504866.43      6855311.74      1506261.09      6854973.48
#Sta/Elev= 30
  2952.3 1873.86  3194.2 1873.92  3267.8 1873.82  3308.3  1870.9  3354.6 1871.87
  3456.8 1869.99  3581.7 1869.13    3717  1868.4  3824.3 1867.32  3956.4 1868.64
  4333.1 1867.45  4490.3 1867.49  4969.6 1867.51  4983.2 1867.34  4989.9 1865.51
  4992.6 1863.08  4993.1 1862.58  5007.6 1863.08  5020.4 1866.81  5042.2 1867.26
  5732.4 1865.33  5957.6 1865.35  6167.3 1865.23  6915.5 1869.78  7457.9 1875.94
  7591.6 1877.55  7641.4 1878.29  7657.1 1879.89  7688.3 1878.91  7766.3  1880.7
#Mann= 14 ,-1 , 0
  2952.3    .035       0  3194.2    .063       0  3456.8    .035       0
  3581.7    .063       0    3717    .035       0  4333.1    .063       0
  4490.3    .035       0  4992.6    .035       0  5007.6    .035       0
  5042.2    .045       0  5732.4     .07       0  5957.6    .045       0
  7457.9    .035       0  7591.6     .07       0
Bank Sta=4992.6,5007.6
XS Rating Curve= 0 ,0
Exp/Cntr=0.3,0.1

Type RM Length L Ch R = 1 ,49195   ,456,456,456
BEGIN DESCRIPTION:
Mapping XS ad5eb992
END DESCRIPTION:
XS GIS Cut Line= 4
      1501906.37        6856514.        1503560.      6856205.84
       1505057.4      6855402.89      1506276.97       6855133.8
#Sta/Elev= 30
  2901.9  1872.5  3565.3 1870.71  3615.5 1870.64  4004.4 1867.72  4426.3 1866.18
    4587 1867.08  4672.3 1865.81  4756.8 1866.46  4822.5 1864.99  4932.2 1866.92
  4941.4 1866.51  4967.9 1860.82  4968.4 1860.32  4984.1 1860.82  4998.2 1866.37
  5058.1 1864.58  5154.1 1864.57  5512.1 1864.08  5621.6 1864.26  5778.2 1864.15
    5997 1865.21  6054.6    1865  6087.1 1866.86  6202.4 1866.15    6703 1869.43
  7234.5  1875.3  7417.3  1877.6  7442.9 1879.39  7464.3 1878.72    7532 1880.09
#Mann= 14 ,-1 , 0
  2901.9    .063       0  3565.3    .035       0  3615.5    .063       0
  4004.4    .035       0  4672.3     .07       0  4967.9    .045       0
  4984.1     .07       0  5154.1    .045       0  5512.1     .07       0
  5621.6    .045       0  5778.2     .07       0    5997    .045       0
  7234.5    .035       0  7464.3     .07       0
Bank Sta=4967.9,4984.1
XS Rating Curve= 0 ,0
Exp/Cntr=0.3,0.1

Type RM Length L Ch R = 1 ,48739   ,666,666,666
BEGIN DESCRIPTION:
Mapping XS 051add22
END DESCRIPTION:
XS GIS Cut Line= 4
      1502127.68      6856813.48      1503859.48      6856553.06
      1504927.19      6855945.42      1506728.45      6855598.19
#Sta/Elev= 30
    2801 1872.61  3086.4 1872.23    3251 1871.55  3519.5 1869.59  3676.7 1870.27
  3957.2 1869.09  3999.4 1869.13  4439.8 1866.18  4481.2 1865.46  4565.9 1865.12
  4580.5 1865.85  4926.8 1863.54    4972 1865.26  4984.3 1863.89  4999.3 1859.79
  4999.8 1859.29  5015.5 1859.79  5036.9 1865.26    5096 1863.59  5424.5 1862.77
  5768.1 1863.91  5819.3 1865.56  5839.7 1864.22  5949.3 1864.04    6522 1867.11
  6940.2 1871.66  7108.8  1873.9  7153.4 1875.58  7316.3 1876.43  7615.2 1881.02
#Mann= 16 ,-1 , 0
    2801    .063       0  3086.4    .035       0    3251    .063       0
  3519.5    .035       0  3676.7    .063       0  3957.2    .035       0
  3999.4    .063       0  4439.8    .035       0  4481.2     .07       0
  4565.9    .035       0  4580.5     .07       0  4999.3    .045       0
  5015.5     .07       0  5768.1    .045       0  6940.2    .035       0
  7108.8     .07       0
Bank Sta=4999.3,5015.5
XS Rating Curve= 0 ,0
Exp/Cntr=0.3,0.1

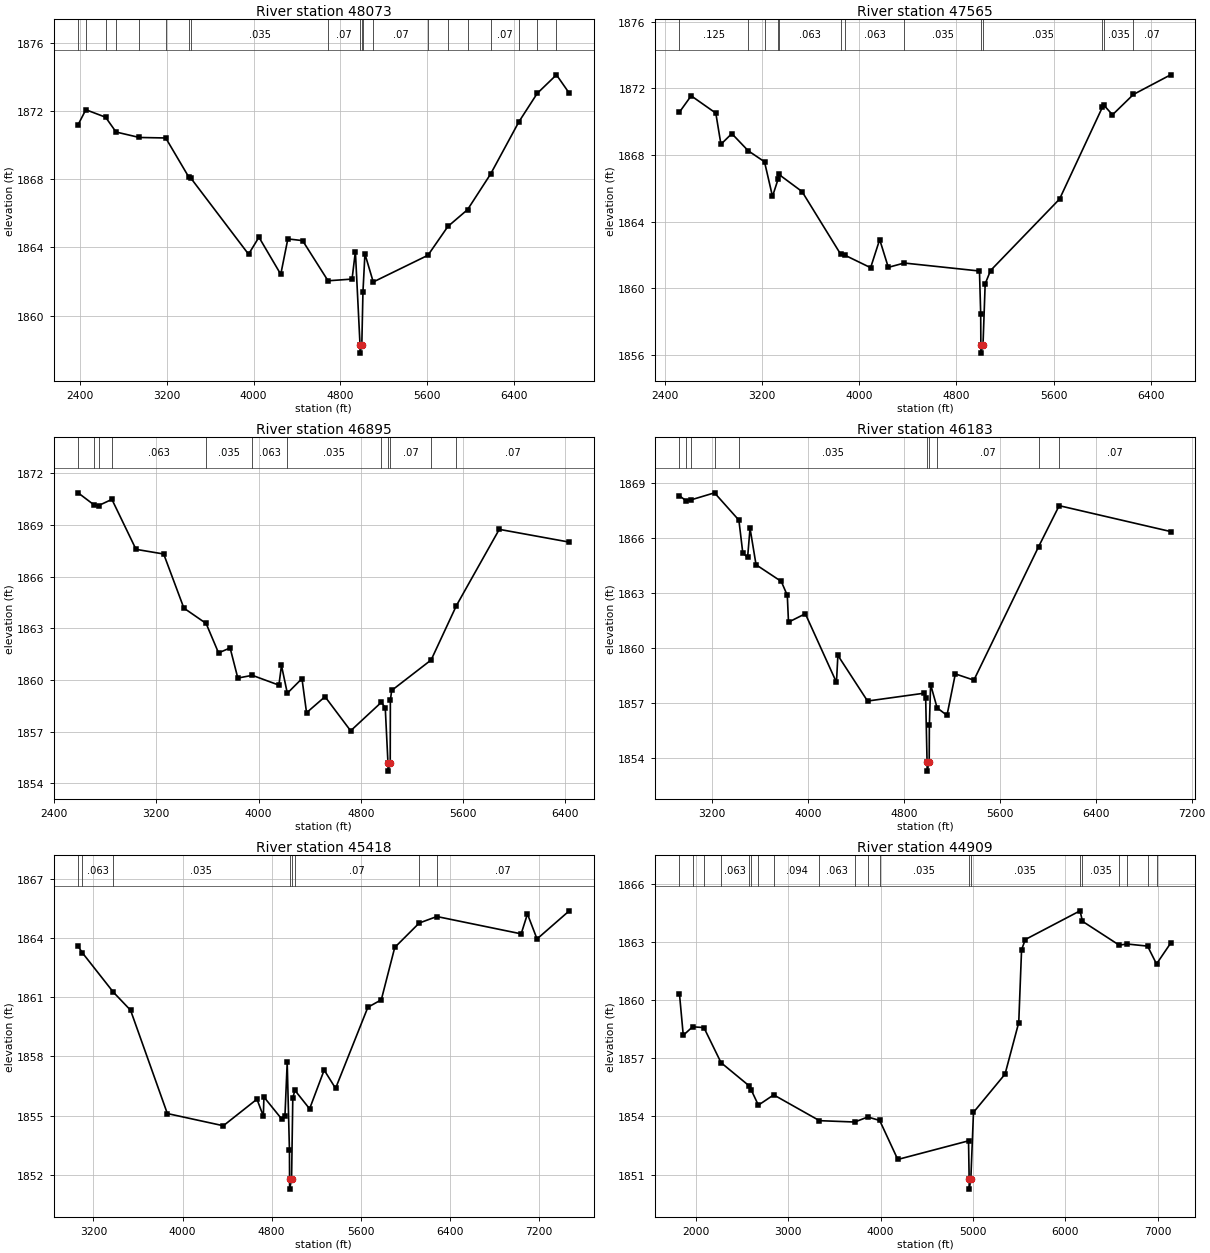
Type RM Length L Ch R = 1 ,48073   ,508,508,508
BEGIN DESCRIPTION:
Mapping XS f22c7c82
END DESCRIPTION:
XS GIS Cut Line= 4
      1502158.14      6857056.53      1504423.72       6856804.8
      1506224.93      6856444.56      1506589.54      6856253.57
#Sta/Elev= 30
  2381.9 1871.21  2453.2 1872.09  2635.3 1871.65  2731.8 1870.78  2946.1 1870.46
  3189.8 1870.43  3401.7 1868.14  3423.8 1868.05  3953.3  1863.6    4049  1864.6
  4250.2 1862.42  4315.5  1864.5  4451.4  1864.4    4686 1862.04  4907.5 1862.14
  4938.1 1863.76  4980.8 1858.29  4981.3 1857.79  4997.4 1858.29  5007.9 1861.39
  5026.1 1863.62  5102.7 1861.97  5607.2 1863.54  5790.7 1865.23  5972.2 1866.22
  6184.5 1868.31  6445.5 1871.38  6614.4 1873.05  6791.7 1874.14  6909.9 1873.06
#Mann= 20 ,-1 , 0
  2381.9    .063       0  2453.2    .035       0  2635.3    .063       0
  2731.8    .035       0  2946.1    .063       0  3189.8    .035       0
  3401.7    .063       0  3423.8    .035       0    4686     .07       0
  4980.8    .045       0  4997.4     .07       0  5007.9    .035       0
  5102.7     .07       0  5607.2    .045       0  5790.7    .045       0
  5972.2    .035       0  6184.5     .07       0  6445.5    .035       0
  6614.4     .07       0  6791.7    .035       0
Bank Sta=4980.8,4997.4
XS Rating Curve= 0 ,0
Exp/Cntr=0.3,0.1

Type RM Length L Ch R = 1 ,47565   ,670,670,670
BEGIN DESCRIPTION:
Mapping XS 0523dd7c
END DESCRIPTION:
XS GIS Cut Line= 3
      1502409.84      6857590.39      1505838.65      6857000.11
      1506398.56      6856917.64
#Sta/Elev= 30
  2518.9 1870.57  2615.5 1871.55  2818.4 1870.51  2860.6 1868.64  2950.3 1869.28
  3085.2 1868.25  3219.4 1867.59  3285.2 1865.51  3330.6 1866.53    3338 1866.83
  3528.7  1865.8  3845.7 1862.05  3881.4 1861.98  4093.4 1861.23    4168 1862.92
    4239 1861.25  4370.2 1861.51  4989.9 1861.03    5000 1858.44  5001.3  1856.6
  5001.8  1856.1    5019  1856.6  5036.8 1860.26  5081.2 1861.06  5649.4 1865.35
  6002.6 1870.87  6011.6 1871.01  6085.4 1870.41  6257.4 1871.63  6564.1 1872.81
#Mann= 13 ,-1 , 0
  2518.9    .125       0  3085.2    .094       0  3219.4    .063       0
  3330.6    .035       0    3338    .063       0  3845.7    .035       0
  3881.4    .063       0  4370.2    .035       0  5001.3     .06       0
    5019    .035       0  6002.6     .07       0  6011.6    .035       0
  6257.4     .07       0
Bank Sta=5001.3,5019
XS Rating Curve= 0 ,0
Exp/Cntr=0.3,0.1

Type RM Length L Ch R = 1 ,46895   ,712,712,712
BEGIN DESCRIPTION:
Mapping XS 86890b71
END DESCRIPTION:
XS GIS Cut Line= 4
      1502401.15      6857915.91      1503959.31      6857768.34
      1505604.27      6857876.85      1506231.85      6857842.22
#Sta/Elev= 30
  2588.5 1870.86  2714.9 1870.15  2748.5 1870.12  2852.9 1870.48  3041.5 1867.58
    3258 1867.31    3416 1864.17  3589.8 1863.28  3687.2 1861.57  3777.6 1861.86
  3837.9 1860.11  3951.2 1860.27  4159.3  1859.7  4179.4 1860.84  4225.2 1859.23
  4339.7 1860.08  4375.6  1858.1  4520.1 1859.03  4720.5 1857.05  4960.1  1858.7
  4991.1  1858.4  5012.3 1855.21  5012.8 1854.71  5030.1 1855.21  5031.2 1858.81
  5041.2 1859.39  5350.1 1861.16  5548.2 1864.32    5883 1868.74  6430.7    1868
#Mann= 12 ,-1 , 0
  2588.5    .125       0  2714.9    .094       0  2748.5    .035       0
  2852.9    .063       0  3589.8    .035       0  3951.2    .063       0
  4225.2    .035       0  4960.1     .07       0  5012.3    .045       0
  5030.1     .07       0  5350.1    .035       0  5548.2     .07       0
Bank Sta=5012.3,5030.1
XS Rating Curve= 0 ,0
Exp/Cntr=0.3,0.1

Type RM Length L Ch R = 1 ,46183   ,765,765,765
BEGIN DESCRIPTION:
Mapping XS b427f99f
END DESCRIPTION:
XS GIS Cut Line= 4
      1502357.78      6858271.81      1503646.81      6858198.03
      1505083.44      6858553.93      1506280.63      6857994.37
#Sta/Elev= 30
  2931.4 1868.28  2984.1 1868.02  3024.9 1868.05  3223.5 1868.44  3426.7 1866.95
  3459.5 1865.15  3499.5 1864.93  3519.6 1866.51  3569.7 1864.52    3780 1863.61
  3830.1 1862.85  3840.1 1861.39  3980.3 1861.85  4239.7 1858.11  4251.6 1859.58
  4498.8 1857.09  4972.7 1857.52    4983 1857.28  4994.7 1853.77  4995.2 1853.27
  5012.5 1853.77  5013.9 1855.76  5024.2 1857.99  5078.4 1856.72  5160.7 1856.31
  5230.3 1858.57  5384.8 1858.23  5923.8  1865.5  6095.6 1867.74  7024.1 1866.33
#Mann= 10 ,-1 , 0
  2931.4    .063       0  2984.1    .125       0  3024.9    .063       0
  3223.5    .094       0  3426.7    .035       0  4994.7    .035       0
  5012.5    .035       0  5078.4     .07       0  5923.8    .035       0
  6095.6     .07       0
Bank Sta=4994.7,5012.5
XS Rating Curve= 0 ,0
Exp/Cntr=0.3,0.1

Type RM Length L Ch R = 1 ,45418   ,509,509,509
BEGIN DESCRIPTION:
Mapping XS 3a6bfb03
END DESCRIPTION:
XS GIS Cut Line= 4
      1502353.45      6858931.55      1503047.85      6859135.53
      1505426.32      6858875.11      1506467.96      6858106.91
#Sta/Elev= 30
  3062.4  1863.6  3100.4 1863.27  3378.5 1861.27  3533.5 1860.35  3863.8  1855.1
  4366.7 1854.48  4668.5 1855.83    4726 1854.97    4731 1855.94  4889.8 1854.83
    4920 1854.99  4940.1  1857.7  4960.3 1853.23  4961.4 1851.76  4961.9 1851.26
  4979.3 1851.76  4990.4  1855.9  5009.3 1856.28  5141.3 1855.34  5272.1 1857.31
  5374.5 1856.38  5664.5  1860.5  5785.2 1860.88  5905.9 1863.54  6125.7 1864.78
    6284 1865.11  7041.2 1864.23  7097.5 1865.24  7183.6 1863.97  7473.1  1865.4
#Mann= 8 ,-1 , 0
  3062.4    .035       0  3100.4    .063       0  3378.5    .035       0
  4961.4    .035       0  4979.3    .035       0  5009.3     .07       0
  6125.7    .035       0    6284     .07       0
Bank Sta=4961.4,4979.3
XS Rating Curve= 0 ,0
Exp/Cntr=0.3,0.1

Type RM Length L Ch R = 1 ,44909   ,488,488,488
BEGIN DESCRIPTION:
Mapping XS 4e26ce8a
END DESCRIPTION:
XS GIS Cut Line= 4
      1501198.93      6860146.79      1501446.29      6860007.92
      1504987.95       6859369.9      1506337.77      6858870.77
#Sta/Elev= 30
  1820.1 1860.33  1861.5 1858.18  1962.4 1858.62  2085.2 1858.58  2270.8 1856.77
  2574.1 1855.58  2598.2 1855.36  2675.2 1854.58  2841.3 1855.11  3337.2 1853.78
  3719.6 1853.71  3860.7 1853.97  3989.7 1853.79  4185.5 1851.78  4952.2 1852.74
  4958.9 1850.75  4959.4 1850.25  4976.9 1850.75  5005.8 1854.21  5347.7 1856.18
  5496.2 1858.84  5526.7 1862.59  5567.2 1863.12  6160.4  1864.6  6186.5 1864.06
  6584.9 1862.83  6668.8 1862.89    6892 1862.78  6988.8 1861.86  7141.6 1862.93
#Mann= 20 ,-1 , 0
  1820.1    .094       0  1962.4    .125       0  2085.2    .094       0
  2270.8    .063       0  2574.1    .094       0  2598.2    .063       0
  2675.2    .125       0  2841.3    .094       0  3337.2    .063       0
  3719.6    .035       0  3860.7    .063       0  3989.7    .035       0
  4958.9    .035       0  4976.9    .035       0  6160.4     .07       0
  6186.5    .035       0  6584.9     .07       0  6668.8    .035       0
    6892    .035       0  6988.8    .063       0
Bank Sta=4958.9,4976.9
XS Rating Curve= 0 ,0
Exp/Cntr=0.3,0.1

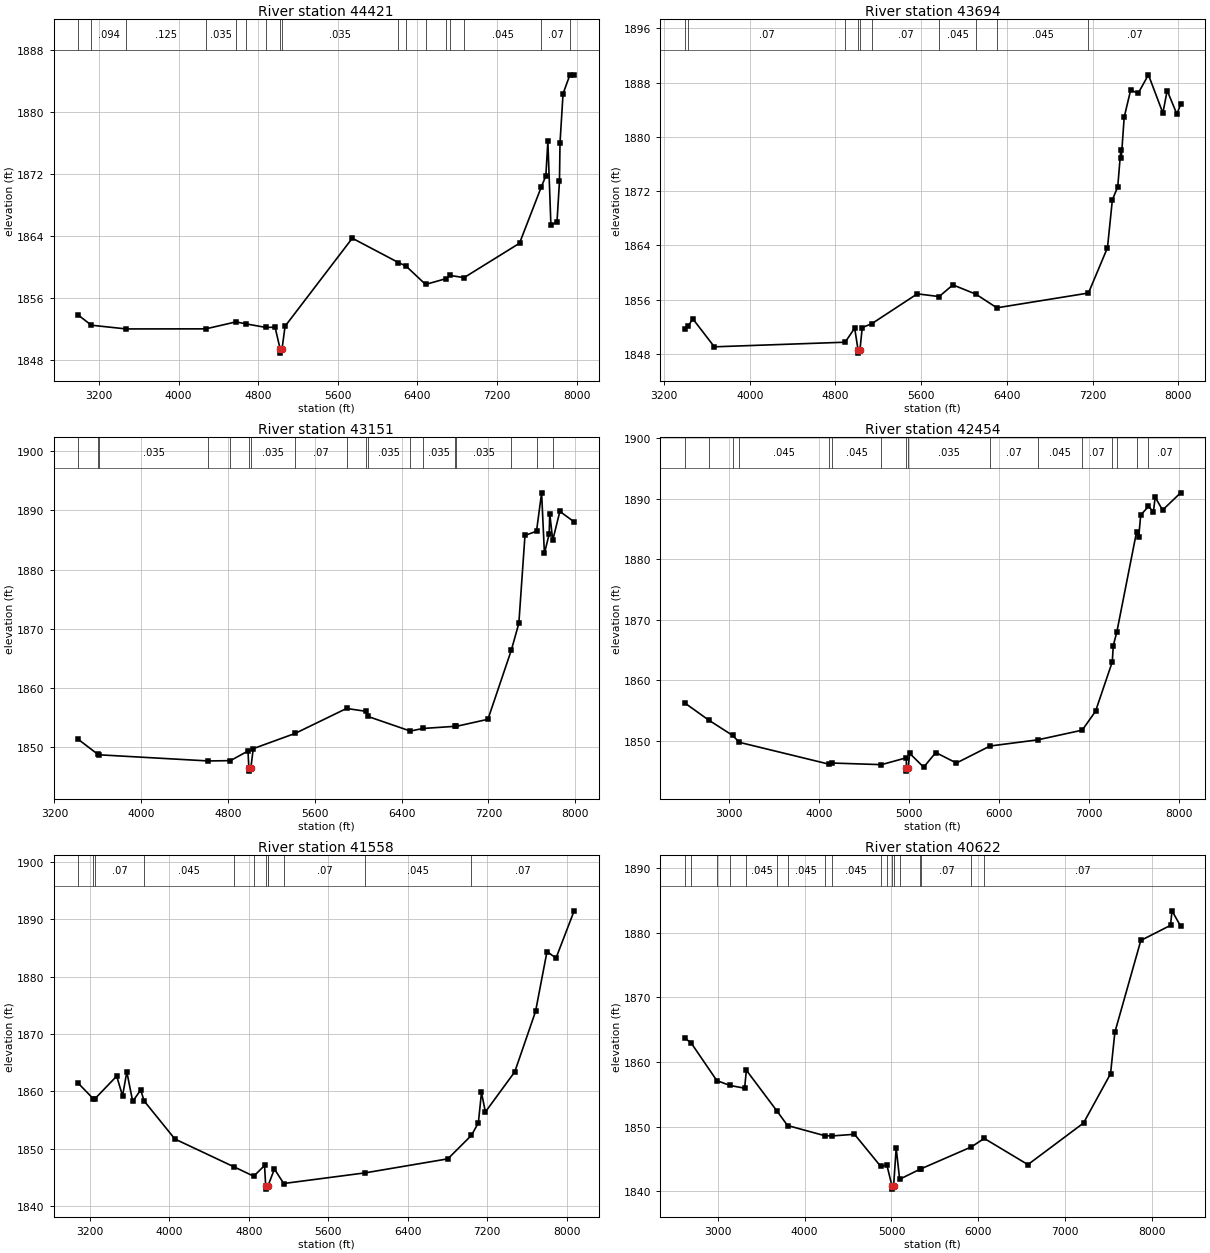
Type RM Length L Ch R = 1 ,44421   ,727,727,727
BEGIN DESCRIPTION:
Mapping XS e6dab1ad
END DESCRIPTION:
XS GIS Cut Line= 5
      1502225.14      6860272.37      1502462.35      6860255.75
      1504030.06       6859974.5      1505837.35      6859750.54
      1507144.68      6859505.74
#Sta/Elev= 30
  2993.2 1853.85    3124 1852.55  3474.5 1852.07  4274.1 1852.08  4577.3 1852.98
  4678.4 1852.72  4880.1 1852.26  4969.8  1852.3  5021.2 1849.45  5021.7 1848.95
  5039.3 1849.45  5070.5 1852.42  5745.7 1863.77  6209.5 1860.63  6286.9 1860.16
  6481.8 1857.81  6686.7 1858.55  6726.3 1858.97  6869.4 1858.69  7425.8 1863.12
  7645.1 1870.39  7690.4  1871.8  7710.7 1876.26  7741.2 1865.49  7802.3 1865.81
  7827.3 1871.11  7832.8 1876.06  7863.3 1882.41  7932.5 1884.84  7974.9 1884.84
#Mann= 17 ,-1 , 0
  2993.2    .035       0    3124    .094       0  3474.5    .125       0
  4274.1    .035       0  4577.3    .094       0  4678.4    .063       0
  4880.1    .035       0  5021.2    .035       0  5039.3    .035       0
  6209.5    .094       0  6286.9    .035       0  6481.8     .07       0
  6686.7    .035       0  6726.3     .07       0  6869.4    .045       0
  7645.1     .07       0  7932.5    .035       0
Bank Sta=5021.2,5039.3
XS Rating Curve= 0 ,0
Exp/Cntr=0.3,0.1

Type RM Length L Ch R = 1 ,43694   ,543,543,543
BEGIN DESCRIPTION:
Mapping XS 2eac07aa
END DESCRIPTION:
XS GIS Cut Line= 3
      1502561.34      6860859.92      1505899.85      6860448.46
       1507160.1      6860349.52
#Sta/Elev= 30
  3394.3 1851.67  3427.3 1852.12  3468.5 1853.18    3670 1849.04  4890.9 1849.72
  4979.9  1851.8  5011.1 1848.61  5011.6 1848.11  5029.3 1848.61  5050.4 1851.87
  5141.6 1852.47  5564.3 1856.85  5768.1 1856.45  5896.8 1858.17  6111.5  1856.8
    6307 1854.79  7161.9 1856.97  7339.4 1863.65  7385.1 1870.71  7435.3 1872.63
  7463.5 1878.05  7468.5 1876.85  7495.5 1882.89  7555.7 1886.89  7625.9 1886.42
  7721.7 1889.14  7856.6 1883.51  7896.7 1886.82    7987 1883.36  8022.2 1884.77
#Mann= 10 ,-1 , 0
  3394.3    .035       0  3427.3     .07       0  4890.9    .035       0
  5011.1    .035       0  5029.3    .035       0  5141.6     .07       0
  5768.1    .045       0  6111.5    .035       0    6307    .045       0
  7161.9     .07       0
Bank Sta=5011.1,5029.3
XS Rating Curve= 0 ,0
Exp/Cntr=0.3,0.1

Type RM Length L Ch R = 1 ,43151   ,697,697,697
BEGIN DESCRIPTION:
Mapping XS 4c337330
END DESCRIPTION:
XS GIS Cut Line= 3
      1502701.94      6861677.63      1504873.81      6860969.29
      1507108.15      6860484.93
#Sta/Elev= 30
  3419.8 1851.29  3602.1 1848.74  3609.2 1848.69  4616.4 1847.65  4821.3  1847.7
  4983.9 1849.33  4991.7 1846.43  4992.2 1845.93  5009.9 1846.43  5032.3 1849.73
  5417.8  1852.3  5892.2 1856.52  6070.2 1856.04  6089.4 1855.17  6480.6  1852.7
  6596.7 1853.14    6891  1853.5  6902.5 1853.49  7195.7 1854.69  7412.1 1866.42
  7480.6 1870.92  7537.1 1885.76  7643.5 1886.47  7690.5 1892.96  7716.3 1882.72
  7760.3 1886.02  7765.4 1889.46  7793.1 1884.95  7858.7 1889.82  7990.5 1888.05
#Mann= 18 ,-1 , 0
  3419.8    .035       0  3602.1    .063       0  3609.2    .035       0
  4616.4     .07       0  4821.3    .035       0  4991.7    .035       0
  5009.9    .035       0  5417.8     .07       0  5892.2    .045       0
  6070.2     .07       0  6089.4    .035       0  6480.6     .07       0
  6596.7    .035       0    6891    .045       0  6902.5    .035       0
  7412.1     .07       0  7643.5    .035       0  7793.1     .07       0
Bank Sta=4991.7,5009.9
XS Rating Curve= 0 ,0
Exp/Cntr=0.3,0.1

Type RM Length L Ch R = 1 ,42454   ,896,896,896
BEGIN DESCRIPTION:
Mapping XS 97d27013
END DESCRIPTION:
XS GIS Cut Line= 4
      1502483.16      6863037.02      1503483.18      6862339.09
      1506332.14      6860802.63      1507361.69      6860594.64
#Sta/Elev= 30
  2512.2 1856.26    2777 1853.44  3043.3  1850.9  3117.7 1849.76  4108.4 1846.17
  4145.6 1846.34  4695.7 1846.07  4972.2  1847.2  4973.6  1845.5  4974.1    1845
  4991.8  1845.5  5010.2 1847.93  5165.3 1845.65  5299.7 1848.07  5528.9 1846.34
  5902.3 1849.15  6432.5 1850.17  6925.8 1851.77  7073.5 1854.88  7260.1 1863.07
    7271 1865.76  7309.5 1867.92  7529.2 1884.51    7553 1883.62  7575.6 1887.32
  7662.1 1888.75  7716.2 1887.86  7736.6 1890.26  7818.2 1888.14  8018.9 1890.99
#Mann= 16 ,-1 , 0
  2512.2    .035       0    2777    .063       0  3043.3     .07       0
  3117.7    .045       0  4108.4     .07       0  4145.6    .045       0
  4695.7    .035       0  4973.6    .035       0  4991.8    .035       0
  5902.3     .07       0  6432.5    .045       0  6925.8     .07       0
  7260.1    .035       0  7309.5     .07       0  7529.2    .035       0
  7662.1     .07       0
Bank Sta=4973.6,4991.8
XS Rating Curve= 0 ,0
Exp/Cntr=0.3,0.1

Type RM Length L Ch R = 1 ,41558   ,936,936,936
BEGIN DESCRIPTION:
Mapping XS ac49c687
END DESCRIPTION:
XS GIS Cut Line= 4
      1503545.65      6863365.14      1504655.06      6862729.71
      1506780.06      6861167.21      1507806.08      6860849.51
#Sta/Elev= 30
  3083.7  1861.4  3232.2 1858.75    3251 1858.72  3469.7 1862.66  3528.6 1859.22
  3571.8  1863.4  3630.8 1858.25  3711.4 1860.25  3745.9 1858.33  4055.3  1851.7
    4646 1846.88  4849.3 1845.21  4957.9 1847.08  4969.5 1843.46    4970 1842.96
  4988.2 1843.46  4992.5 1843.53  5057.2 1846.46  5150.9 1843.94  5971.9  1845.8
  6802.8 1848.24  7040.2 1852.34  7109.7 1854.51  7141.1 1859.81  7180.4 1856.41
  7476.1 1863.41  7685.2 1873.93  7800.6 1884.38  7891.3 1883.24  8073.9 1891.48
#Mann= 12 ,-1 , 0
  3083.7     .07       0  3232.2    .045       0    3251     .07       0
  3745.9    .045       0    4646     .07       0  4849.3    .045       0
  4969.5    .035       0  4988.2    .045       0  4992.5    .035       0
  5150.9     .07       0  5971.9    .045       0  7040.2     .07       0
Bank Sta=4969.5,4988.2
XS Rating Curve= 0 ,0
Exp/Cntr=0.3,0.1

Type RM Length L Ch R = 1 ,40622   ,718,718,718
BEGIN DESCRIPTION:
Mapping XS 863d54dc
END DESCRIPTION:
XS GIS Cut Line= 4
      1503545.24      6863654.63      1505232.75      6863251.85
      1507343.86      6862411.57      1509001.77      6862036.98
#Sta/Elev= 30
  2621.4 1863.68  2691.6 1863.01    2990 1857.12  3140.5 1856.37    3310 1855.94
  3329.9 1858.73  3679.1 1852.46  3803.8 1850.16  4230.1 1848.59  4312.8 1848.54
  4574.4  1848.8  4877.5 1843.81  4946.7 1844.06  5005.9  1840.8  5006.4  1840.3
  5024.6  1840.8  5054.6 1846.66    5094 1841.83  5334.1 1843.42  5343.9 1843.47
  5921.1 1846.85  6067.7 1848.16  6570.5  1844.1  7210.4 1850.54  7521.6 1858.18
  7571.3 1864.61  7870.2 1878.84  8211.9 1881.18    8229 1883.43  8328.2 1881.05
#Mann= 18 ,-1 , 0
  2621.4    .035       0  2691.6     .07       0    2990    .045       0
  3140.5     .07       0  3329.9    .045       0  3679.1     .07       0
  3803.8    .045       0  4230.1     .07       0  4312.8    .045       0
  4877.5     .07       0  4946.7    .035       0  5005.9    .035       0
  5024.6    .035       0    5094     .07       0  5334.1    .094       0
  5343.9     .07       0  5921.1    .094       0  6067.7     .07       0
Bank Sta=5005.9,5024.6
XS Rating Curve= 0 ,0
Exp/Cntr=0.3,0.1