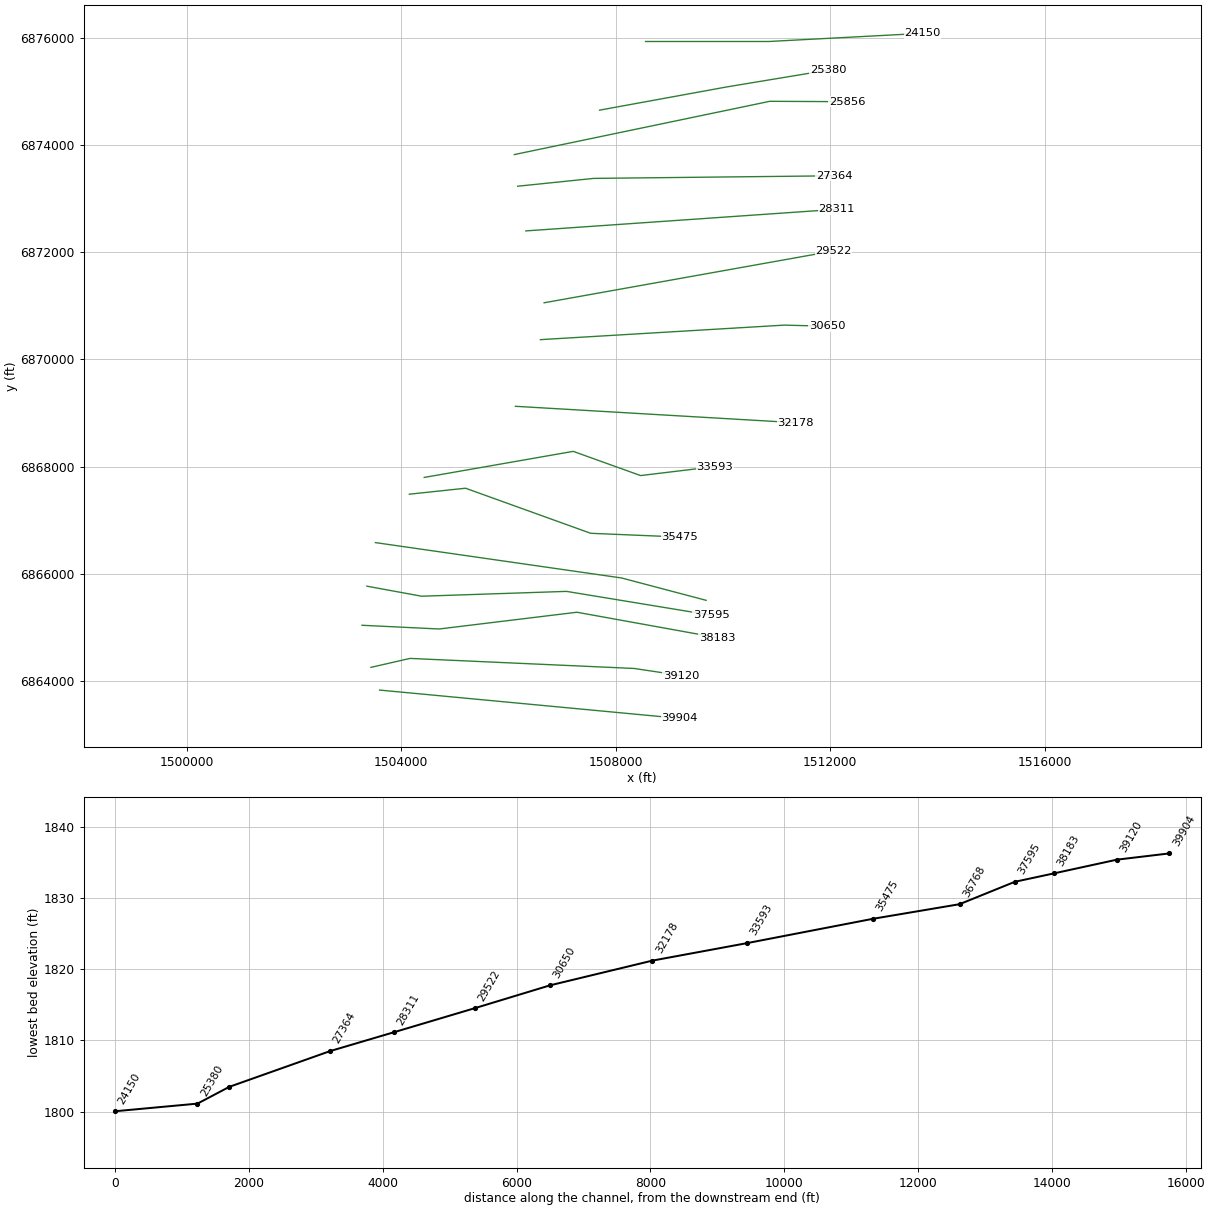
HEC-RAS study NC Unknown Stream 72.prj: NC Unknown Stream 72 Base Level Engineering

--- NC Unknown Stream 72.g01 (geometry) --- (continued)

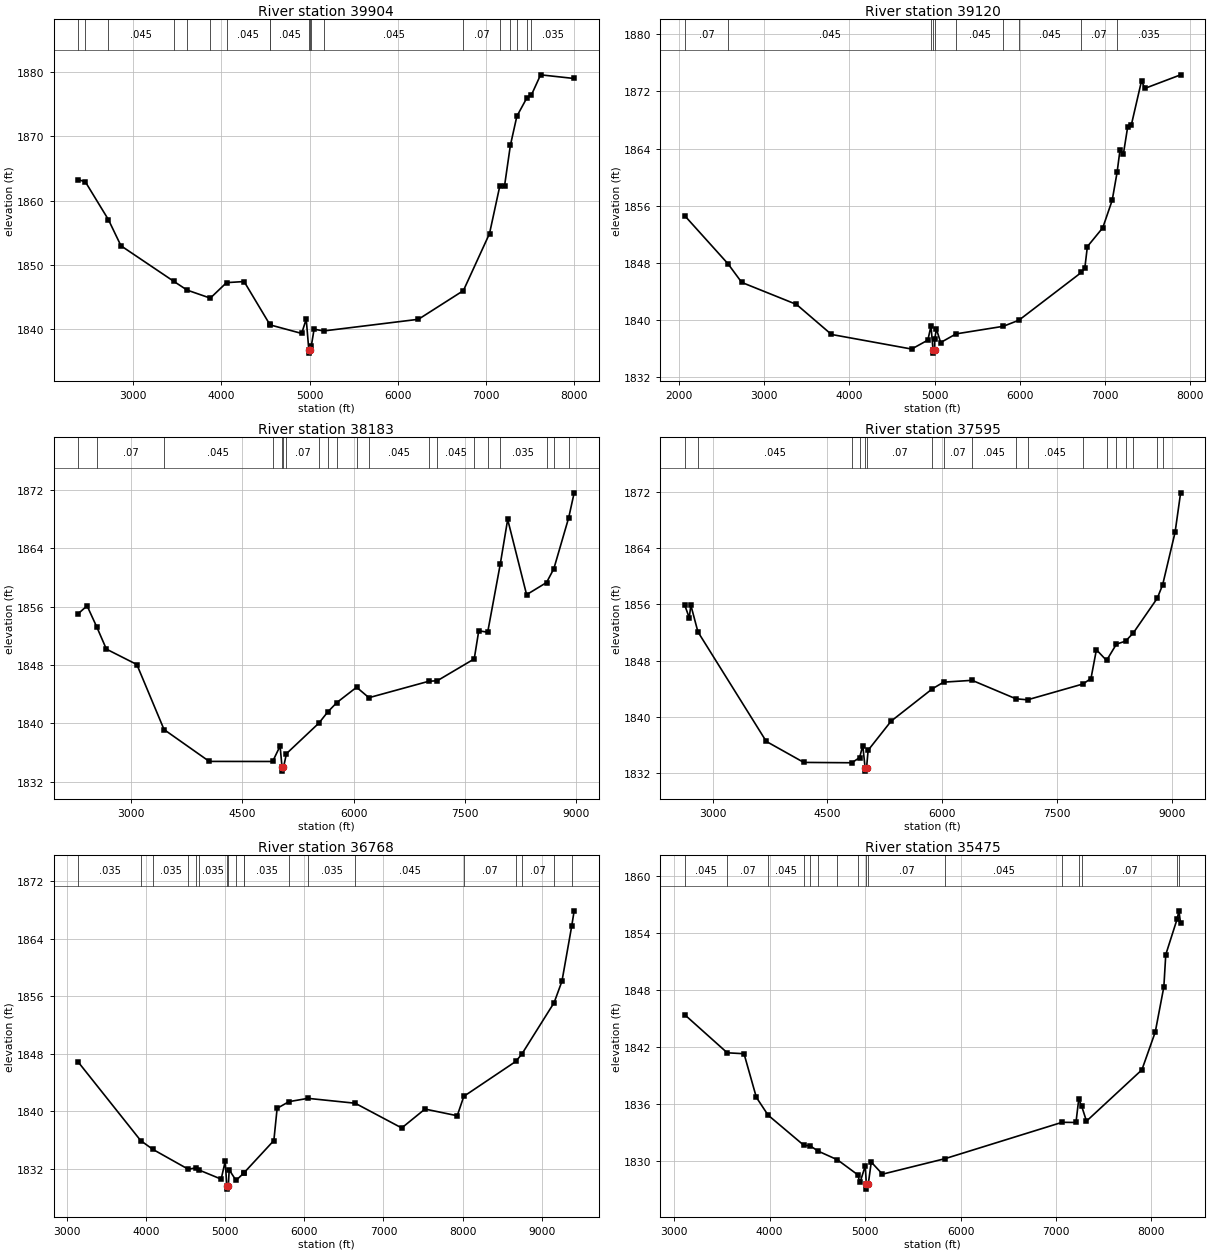
Type RM Length L Ch R = 1 ,39904   ,784,784,784
BEGIN DESCRIPTION:
Mapping XS b78de9a8
END DESCRIPTION:
XS GIS Cut Line= 2
      1503593.85      6863835.18      1509190.53      6863307.45
#Sta/Elev= 30
  2377.2 1863.26  2457.3  1862.9  2717.9 1857.04  2860.5 1852.97  3460.6 1847.43
  3610.5 1846.08  3873.5 1844.83  4057.5 1847.24  4256.6 1847.41  4547.3 1840.75
  4554.2 1840.66  4909.5 1839.34  4960.9 1841.58  4990.5 1836.78    4991 1836.28
  5009.4 1836.78  5018.8 1837.41  5050.2    1840  5159.4 1839.73  6232.8 1841.54
  6742.9    1846  7038.9 1854.86  7156.6 1862.32  7209.7 1862.31  7275.4 1868.57
  7349.1 1873.11  7464.4 1876.01  7513.4  1876.4  7618.3 1879.55  7998.7 1878.98
#Mann= 19 ,-1 , 0
  2377.2    .035       0  2457.3     .07       0  2717.9    .045       0
  3460.6     .07       0  3610.5    .045       0  3873.5     .07       0
  4057.5    .045       0  4547.3     .07       0  4554.2    .045       0
  4990.5    .045       0  5009.4    .045       0  5018.8    .035       0
  5159.4    .045       0  6742.9     .07       0  7156.6    .035       0
  7275.4     .07       0  7349.1    .035       0  7464.4     .07       0
  7513.4    .035       0
Bank Sta=4990.5,5009.4
XS Rating Curve= 0 ,0
Exp/Cntr=0.3,0.1

Type RM Length L Ch R = 1 ,39120   ,937,937,937
BEGIN DESCRIPTION:
Mapping XS e692ed05
END DESCRIPTION:
XS GIS Cut Line= 4
       1503434.1      6864258.78       1504163.3      6864425.46
      1508343.86      6864237.96       1509218.9      6864106.01
#Sta/Elev= 30
  2069.5  1854.6  2575.6  1847.9  2737.2 1845.29  3379.8 1842.21  3790.2 1838.01
  4731.1 1835.97  4921.3 1837.22  4958.1 1839.19  4981.8  1835.9  4982.3  1835.4
    5001  1835.9  5001.4 1837.33  5021.4 1838.78  5071.5 1836.88  5252.1 1838.09
  5806.2 1839.15  5989.3    1840  6723.4 1846.69  6763.2  1847.3  6793.2  1850.3
  6973.4 1852.92  7084.3 1856.77    7142 1860.69  7175.3 1863.76  7215.8 1863.25
  7266.4 1867.06  7307.8 1867.25  7428.2 1873.45  7468.6 1872.42  7887.2 1874.31
#Mann= 10 ,-1 , 0
  2069.5     .07       0  2575.6    .045       0  4958.1     .07       0
  4981.8    .035       0    5001     .07       0  5252.1    .045       0
  5806.2     .07       0  5989.3    .045       0  6723.4     .07       0
    7142    .035       0
Bank Sta=4981.8,5001
XS Rating Curve= 0 ,0
Exp/Cntr=0.3,0.1

Type RM Length L Ch R = 1 ,38183   ,588,588,588
BEGIN DESCRIPTION:
Mapping XS 17a13ef0
END DESCRIPTION:
XS GIS Cut Line= 4
      1503267.43      6865043.52      1504704.97      6864974.07
      1507274.41      6865286.57      1509885.56      6864814.34
#Sta/Elev= 30
    2290 1855.04  2407.7 1856.11  2541.2 1853.15    2668 1850.18  3078.5 1848.07
    3445 1839.17  4054.2 1834.81  4908.5  1834.8  5008.6 1836.92  5035.1 1833.98
  5035.6 1833.48  5054.4 1833.98  5094.2 1835.87  5531.1 1840.05  5649.1 1841.56
  5772.7 1842.86  6039.6 1844.96  6205.7 1843.53  7012.5 1845.78  7126.6 1845.85
  7624.6 1848.84  7685.6 1852.69  7805.8 1852.49  7976.3 1861.86  8075.4 1867.93
  8330.3 1857.63  8598.8 1859.29  8697.3 1861.18  8897.6 1868.17  8971.1 1871.57
#Mann= 20 ,-1 , 0
    2290    .035       0  2541.2     .07       0    3445    .045       0
  4908.5     .07       0  5035.1     .07       0  5054.4     .07       0
  5094.2     .07       0  5531.1    .035       0  5649.1     .07       0
  5772.7    .045       0  6039.6     .07       0  6205.7    .045       0
  7012.5     .07       0  7126.6    .045       0  7624.6    .035       0
  7805.8     .07       0  7976.3    .035       0  8598.8     .07       0
  8697.3    .035       0  8897.6     .07       0
Bank Sta=5035.1,5054.4
XS Rating Curve= 0 ,0
Exp/Cntr=0.3,0.1

Type RM Length L Ch R = 1 ,37595   ,827,827,827
BEGIN DESCRIPTION:
Mapping XS 97c2a74e
END DESCRIPTION:
XS GIS Cut Line= 4
       1503357.7      6865772.69      1504378.58      6865585.18
      1507079.97      6865675.46       1509780.7      6865231.12
#Sta/Elev= 30
    2637 1855.89  2695.5  1854.1  2715.6 1855.91  2808.8  1852.1  3701.4 1836.52
  4191.7 1833.53  4819.2 1833.48  4920.9 1834.22  4962.1 1835.93  4992.4 1832.79
  4992.9 1832.29  5011.8 1832.79  5032.1 1835.26  5332.3  1839.4  5871.9 1844.01
  6018.2 1844.95  6390.7 1845.21  6963.6 1842.58  7114.9 1842.44  7839.3 1844.69
  7943.7 1845.47  8014.6 1849.56  8147.4 1848.04    8276 1850.36  8395.9 1850.79
    8496 1851.94  8809.9 1856.89  8880.4 1858.82  9042.5 1866.28  9114.9 1871.89
#Mann= 18 ,-1 , 0
    2637    .035       0  2808.8    .045       0  4819.2    .035       0
  4920.9     .07       0  4992.4     .07       0  5011.8     .07       0
  5871.9    .035       0  6018.2     .07       0  6390.7    .045       0
  6963.6     .07       0  7114.9    .045       0  7839.3     .07       0
  8147.4    .035       0    8276     .07       0  8395.9    .035       0
    8496     .07       0  8809.9    .035       0  8880.4     .07       0
Bank Sta=4992.4,5011.8
XS Rating Curve= 0 ,0
Exp/Cntr=0.3,0.1

Type RM Length L Ch R = 1 ,36768   ,1293,1293,1293
BEGIN DESCRIPTION:
Mapping XS 1e112ca8
END DESCRIPTION:
XS GIS Cut Line= 3
      1503517.43      6866585.19      1508107.75      6865925.46
      1509684.12      6865508.79
#Sta/Elev= 30
  3143.2  1846.8  3931.7 1835.89  4084.1 1834.68  4534.3  1831.9  4634.7 1832.12
  4662.3 1831.83  4949.1 1830.53  4999.7 1833.01  5020.2 1829.64  5020.7 1829.14
  5039.8 1829.64  5050.2 1831.83  5136.8 1830.35  5237.3  1831.4  5238.4 1831.42
  5614.9  1835.9  5656.3 1840.38  5805.6 1841.31  6046.2 1841.77  6643.3 1841.09
  7231.5 1837.65  7525.3 1840.28    7933 1839.35  8016.4 1842.05  8672.5  1846.9
  8748.7 1847.91  9158.1 1855.09    9257 1858.07  9380.3 1865.74  9411.2 1867.86
#Mann= 19 ,-1 , 0
  3143.2    .035       0  3931.7    .045       0  4084.1    .035       0
  4534.3    .045       0  4634.7     .07       0  4662.3    .035       0
  5020.2    .035       0  5039.8    .035       0  5136.8     .07       0
  5237.3    .045       0  5238.4    .035       0  5805.6    .045       0
  6046.2    .035       0  6643.3    .045       0  8016.4     .07       0
  8672.5    .035       0  8748.7     .07       0  9158.1    .035       0
  9380.3     .07       0
Bank Sta=5020.2,5039.8
XS Rating Curve= 0 ,0
Exp/Cntr=0.3,0.1

Type RM Length L Ch R = 1 ,35475   ,1882,1882,1882
BEGIN DESCRIPTION:
Mapping XS 0eed70c3
END DESCRIPTION:
XS GIS Cut Line= 4
      1504149.45      6867487.96      1505198.02      6867599.07
      1507531.36      6866758.79      1509190.54      6866689.37
#Sta/Elev= 30
  3110.6  1845.4  3555.2 1841.41  3731.2 1841.31  3860.3 1836.73  3983.3 1834.86
  4358.3 1831.69  4423.6 1831.64  4508.1 1831.08  4710.2 1830.17    4921 1828.61
  4946.7 1827.79  5001.5 1829.54  5012.8 1827.59  5013.3 1827.09  5032.6 1827.59
  5064.2 1829.93  5181.7 1828.66  5837.2 1830.29  7064.6 1834.11  7209.2 1834.09
  7238.4 1836.56  7269.9 1835.77  7319.3 1834.23  7899.8 1839.62  8039.9 1843.59
    8130 1848.34    8150 1851.72  8269.1 1855.46  8287.9 1856.32  8305.7 1854.99
#Mann= 16 ,-1 , 0
  3110.6    .045       0  3555.2     .07       0  3983.3    .045       0
  4358.3     .07       0  4423.6    .045       0  4508.1     .07       0
  4710.2    .045       0    4921     .07       0  5012.8     .07       0
  5032.6     .07       0  5837.2    .045       0  7064.6    .035       0
  7238.4    .045       0  7269.9     .07       0  8269.1    .035       0
  8287.9     .07       0
Bank Sta=5012.8,5032.6
XS Rating Curve= 0 ,0
Exp/Cntr=0.3,0.1

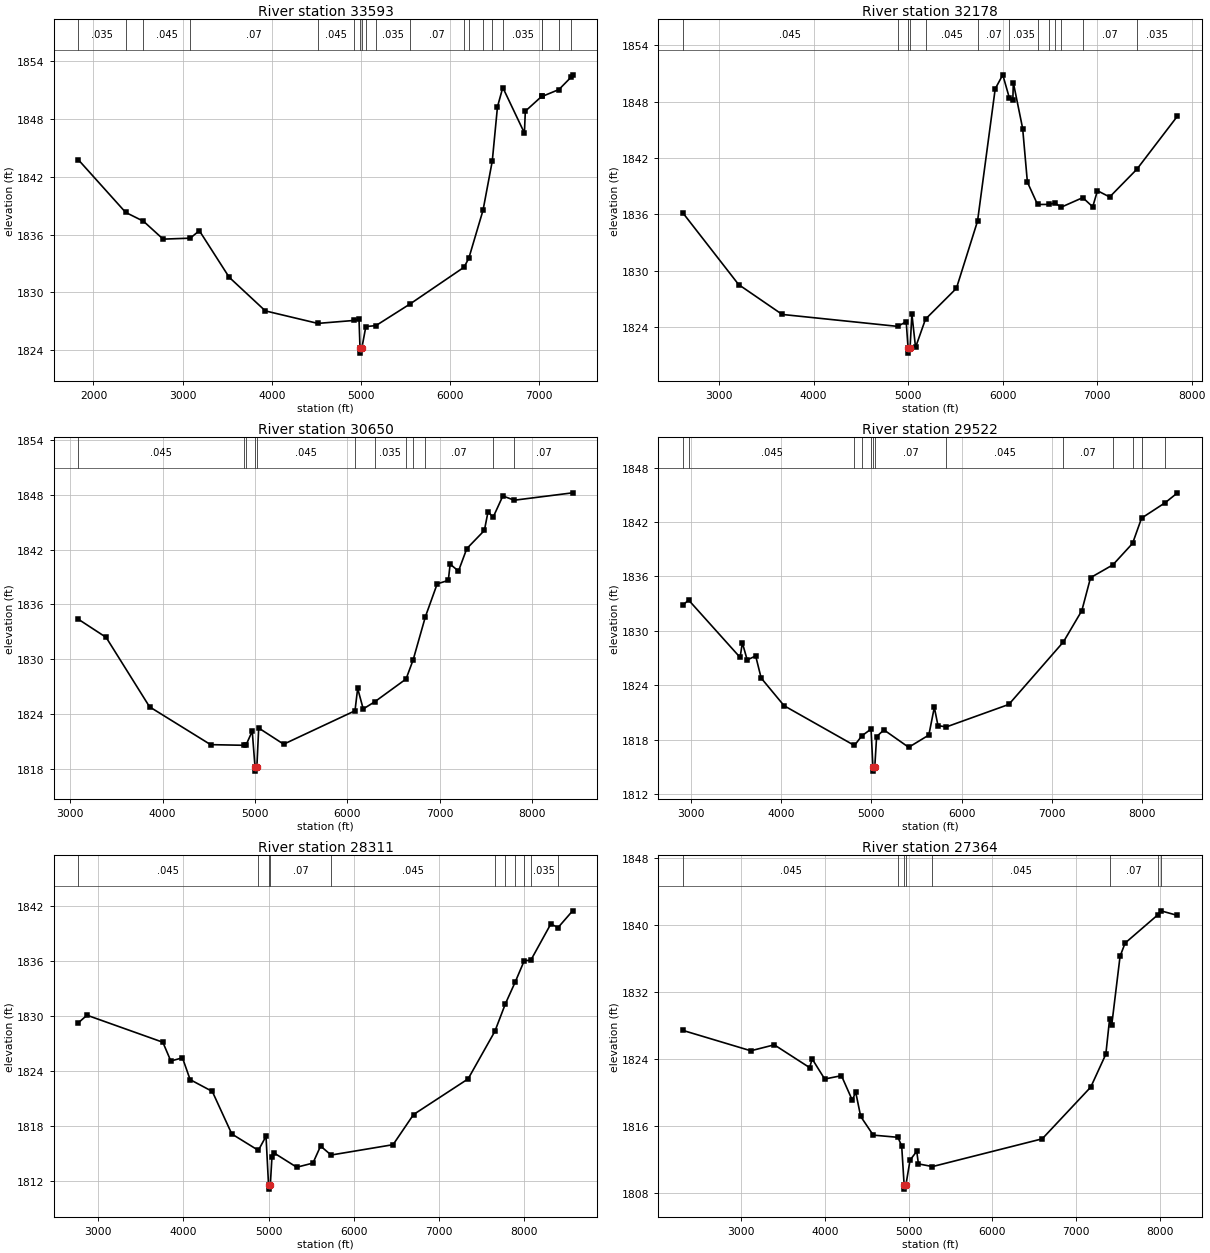
Type RM Length L Ch R = 1 ,33593   ,1415,1415,1415
BEGIN DESCRIPTION:
Mapping XS 703e7148
END DESCRIPTION:
XS GIS Cut Line= 4
      1504427.22      6867800.46      1507204.97      6868286.57
      1508461.91      6867835.18      1509841.91      6868001.61
#Sta/Elev= 30
  1829.1 1843.78  2360.6  1838.3  2560.6 1837.38  2781.1 1835.52  3085.7 1835.62
  3187.2  1836.4  3521.7 1831.56  3927.7 1828.06  4516.6 1826.76  4926.2 1827.07
  4978.5 1827.19  4989.7 1824.17  4990.2 1823.67  5009.7 1824.17    5055 1826.43
  5168.1 1826.53  5555.9 1828.81  6156.5  1832.6  6209.9 1833.53  6369.4 1838.52
  6473.3 1843.64  6531.6 1849.28  6591.3 1851.28  6833.8 1846.55  6843.9 1848.82
  7033.3 1850.41  7034.5 1850.36  7220.7 1851.07  7359.8 1852.38  7374.6  1852.6
#Mann= 20 ,-1 , 0
  1829.1    .035       0  2360.6     .07       0  2560.6    .045       0
  3085.7     .07       0  4516.6    .045       0  4926.2     .07       0
  4989.7     .07       0  5009.7     .07       0    5055    .045       0
  5168.1    .035       0  5555.9     .07       0  6156.5    .035       0
  6209.9     .07       0  6369.4    .035       0  6473.3     .07       0
  6591.3    .035       0  7033.3     .07       0  7034.5    .035       0
  7220.7     .07       0  7359.8    .035       0
Bank Sta=4989.7,5009.7
XS Rating Curve= 0 ,0
Exp/Cntr=0.3,0.1

Type RM Length L Ch R = 1 ,32178   ,1528,1528,1528
BEGIN DESCRIPTION:
Mapping XS 3ec625c8
END DESCRIPTION:
XS GIS Cut Line= 2
      1506128.57      6869126.85      1511350.44      6868821.31
#Sta/Elev= 30
  2619.5 1836.11  3206.9 1828.51  3667.7 1825.33  4888.2 1824.06    4980 1824.55
  4999.8 1821.71  5000.3 1821.21  5020.2 1821.71  5040.1 1825.37  5078.7 1821.82
    5184 1824.83  5510.9 1828.11  5734.6 1835.27  5921.6 1849.36  6001.7 1850.85
  6071.5 1848.38  6108.1 1848.12  6113.1 1850.03  6212.1 1845.13  6262.1 1839.42
  6369.5 1837.04  6487.1 1837.05  6552.2 1837.19  6621.4 1836.76  6848.1 1837.77
  6953.3 1836.79  7003.4 1838.51  7132.6 1837.84  7420.8  1840.8  7850.3 1846.46
#Mann= 13 ,-1 , 0
  2619.5    .045       0  4888.2     .07       0  4999.8     .07       0
  5020.2     .07       0    5184    .045       0  5734.6     .07       0
  6071.5    .035       0  6369.5     .07       0  6487.1    .035       0
  6552.2     .07       0  6621.4    .035       0  6848.1     .07       0
  7420.8    .035       0
Bank Sta=4999.8,5020.2
XS Rating Curve= 0 ,0
Exp/Cntr=0.3,0.1

Type RM Length L Ch R = 1 ,30650   ,1128,1128,1128
BEGIN DESCRIPTION:
Mapping XS 5e61eed4
END DESCRIPTION:
XS GIS Cut Line= 3
      1506593.82       6870369.9      1511142.47      6870640.74
       1511940.5      6870619.92
#Sta/Elev= 30
  3085.8 1834.38  3387.5 1832.39  3858.3 1824.78  4519.5 1820.64  4881.6 1820.57
  4902.4 1820.58  4970.3 1822.12  5000.1 1818.24  5000.6 1817.74  5020.6 1818.24
  5040.4 1822.46  5310.9 1820.69  6083.4 1824.35  6112.3  1826.8  6172.4 1824.55
  6296.7 1825.33  6636.5 1827.83    6714 1829.95  6846.2 1834.66  6973.8 1838.25
  7094.1 1838.63  7114.1 1840.41  7204.3 1839.65  7294.4 1842.11  7484.8  1844.1
  7524.8 1846.17    7579 1845.53    7685 1847.88  7808.5 1847.41  8440.8 1848.22
#Mann= 12 ,-1 , 0
  3085.8    .045       0  4881.6     .07       0  4902.4    .045       0
  5000.1    .045       0  5020.6    .045       0  6083.4     .07       0
  6296.7    .035       0  6636.5     .07       0    6714    .035       0
  6846.2     .07       0    7579    .035       0  7808.5     .07       0
Bank Sta=5000.1,5020.6
XS Rating Curve= 0 ,0
Exp/Cntr=0.3,0.1

Type RM Length L Ch R = 1 ,29522   ,1211,1211,1211
BEGIN DESCRIPTION:
Mapping XS 1e6fb80a
END DESCRIPTION:
XS GIS Cut Line= 2
      1506663.27       6871057.4      1512059.11      6872022.68
#Sta/Elev= 30
  2912.2 1832.86  2972.8  1833.4  3543.8 1827.07  3568.9 1828.68  3622.7 1826.79
  3716.5 1827.23  3777.5 1824.79  4031.4 1821.74  4811.6 1817.35  4893.4 1818.41
  4995.9 1819.16  5016.4 1815.02  5016.9 1814.52  5037.5 1815.02  5057.5 1818.33
  5138.7 1819.07    5413 1817.15  5636.5  1818.5  5697.5 1821.56  5738.1 1819.54
    5831  1819.4  6523.5 1821.88  7128.8 1828.78    7333 1832.23  7429.8 1835.87
    7677 1837.28  7895.5 1839.65  7995.6 1842.44  8258.6 1844.15  8393.7 1845.23
#Mann= 13 ,-1 , 0
  2912.2     .07       0  2972.8    .045       0  4811.6     .07       0
  4893.4    .045       0  4995.9     .07       0  5016.4     .07       0
  5037.5     .07       0    5831    .045       0  7128.8     .07       0
    7677    .035       0  7895.5    .045       0  7995.6    .035       0
  8258.6     .07       0
Bank Sta=5016.4,5037.5
XS Rating Curve= 0 ,0
Exp/Cntr=0.3,0.1

Type RM Length L Ch R = 1 ,28311   ,947,947,947
BEGIN DESCRIPTION:
Mapping XS 03c21316
END DESCRIPTION:
XS GIS Cut Line= 2
      1506323.07      6872397.68       1512120.8       6872800.4
#Sta/Elev= 30
  2763.1 1829.27  2865.3 1830.11  3757.4 1827.16  3851.3 1825.11    3988 1825.46
  4078.2 1823.08  4338.8 1821.79    4568 1817.15  4880.2 1815.36  4970.3  1816.9
  4999.8 1811.63  5000.3 1811.13    5021 1811.63  5040.5 1814.69  5060.6  1815.1
  5331.2 1813.52  5521.7 1813.97  5611.9 1815.83  5735.2 1814.85  6463.9 1815.98
  6704.5 1819.27    7346 1823.16  7660.7 1828.35    7785 1831.37  7898.9 1833.71
  8006.6 1836.07  8083.3 1836.11  8318.4 1840.07  8403.2 1839.67  8574.8  1841.5
#Mann= 11 ,-1 , 0
  2763.1    .045       0  4880.2     .07       0  4999.8     .07       0
    5021     .07       0  5735.2    .045       0  7660.7     .07       0
    7785    .045       0  7898.9    .035       0  8006.6     .07       0
  8083.3    .035       0  8403.2     .07       0
Bank Sta=4999.8,5021
XS Rating Curve= 0 ,0
Exp/Cntr=0.3,0.1

Type RM Length L Ch R = 1 ,27364   ,1508,1508,1508
BEGIN DESCRIPTION:
Mapping XS 5a87e474
END DESCRIPTION:
XS GIS Cut Line= 3
      1506170.26      6873231.02      1507586.91      6873376.85
      1512071.51      6873425.44
#Sta/Elev= 30
  2305.1 1827.42  3114.1    1825  3394.6 1825.71  3817.3 1822.99  3847.3 1824.03
  3997.3 1821.63  4197.4 1822.03  4327.4  1819.1  4367.4 1820.09  4427.4 1817.17
  4577.4 1814.94    4872 1814.68  4917.4 1813.66  4946.7    1809  4947.2  1808.5
    4968    1809  5017.4 1811.96  5097.4 1813.01  5117.4 1811.51  5285.7 1811.19
  6597.5  1814.5  7177.5 1820.67  7357.5 1824.59  7402.4 1828.77  7427.5 1828.03
  7527.5 1836.25  7587.5 1837.84    7981 1841.23  8016.9 1841.69  8214.1 1841.14
#Mann= 8 ,-1 , 0
  2305.1    .045       0    4872     .07       0  4946.7     .07       0
    4968     .07       0  5285.7    .045       0  7402.4     .07       0
    7981    .035       0  8016.9     .07       0
Bank Sta=4946.7,4968
XS Rating Curve= 0 ,0
Exp/Cntr=0.3,0.1

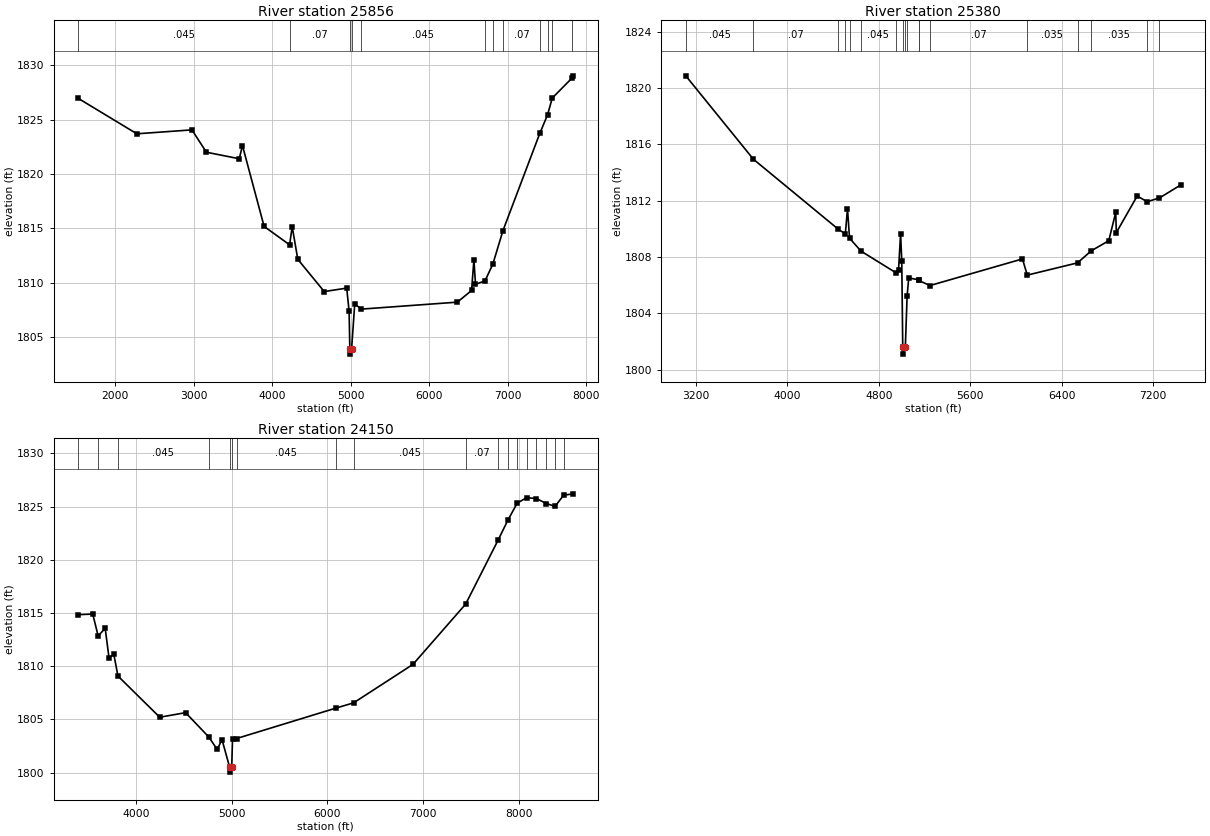
Type RM Length L Ch R = 1 ,25856   ,476,476,476
BEGIN DESCRIPTION:
Mapping XS 2eeb4f64
END DESCRIPTION:
XS GIS Cut Line= 3
       1506107.7      6873821.28      1510871.64      6874814.35
      1512309.18       6874807.4
#Sta/Elev= 30
    1530 1826.94  2275.8 1823.69  2977.8 1824.05  3161.6    1822  3580.4  1821.4
  3621.3 1822.61  3897.1 1815.19    4222  1813.5  4254.6 1815.17  4326.1 1812.17
  4663.2 1809.21  4949.3 1809.53  4979.9  1807.4    4989 1803.97  4989.5 1803.47
  5011.6 1803.97  5051.4 1808.08  5134.6  1807.6  6358.9 1808.24  6539.7 1809.31
  6569.7 1812.14  6589.7 1809.87  6711.2  1810.2  6811.2 1811.74  6939.8 1814.81
  7408.2 1823.72  7507.2 1825.42  7567.4 1826.97  7815.8 1828.78  7833.9 1829.01
#Mann= 12 ,-1 , 0
    1530    .045       0    4222     .07       0    4989     .07       0
  5011.6     .07       0  5134.6    .045       0  6711.2     .07       0
  6811.2    .045       0  6939.8     .07       0  7408.2    .035       0
  7507.2     .07       0  7567.4    .035       0  7815.8     .07       0
Bank Sta=4989,5011.6
XS Rating Curve= 0 ,0
Exp/Cntr=0.3,0.1

Type RM Length L Ch R = 1 ,25380   ,1230,1230,1230
BEGIN DESCRIPTION:
NC Unknown Stream 72 16.0
END DESCRIPTION:
XS GIS Cut Line= 3
       1507696.8      6874649.41      1510074.76      6875083.44
      1511960.09      6875395.93
#Sta/Elev= 30
  3111.5 1820.87  3702.6 1814.95  4446.4 1809.97    4507 1809.65  4525.8 1811.44
  4543.7 1809.34  4644.7 1808.42  4947.1  1806.9  4972.2 1807.08  4990.2 1809.66
  5000.4 1807.74    5009 1801.61  5009.5 1801.11  5031.7 1801.61  5047.2 1805.24
  5061.4 1806.52  5147.3 1806.39  5148.4 1806.34  5247.4 1805.98  6056.1 1807.87
    6098 1806.72  6537.6 1807.59  6658.6 1808.45  6810.8 1809.16  6871.8 1811.17
  6877.1 1809.74  7059.8 1812.34    7146 1811.93  7254.6  1812.2  7439.8 1813.12
#Mann= 18 ,-1 , 0
  3111.5    .045       0  3702.6     .07       0  4446.4    .035       0
    4507     .07       0  4543.7    .035       0  4644.7    .045       0
  4947.1     .07       0    5009     .07       0  5031.7     .07       0
  5047.2    .045       0  5147.3     .07       0  5148.4    .045       0
  5247.4     .07       0    6098    .035       0  6537.6    .045       0
  6658.6    .035       0    7146     .07       0  7254.6    .035       0
Bank Sta=5009,5031.7
XS Rating Curve= 0 ,0
Exp/Cntr=0.3,0.1

Type RM Length L Ch R = 1 ,24150   ,1342,1342,1342
BEGIN DESCRIPTION:
NC Unknown Stream 72 15.0
END DESCRIPTION:
XS GIS Cut Line= 3
      1508553.99       6875929.8      1510854.38       6875929.8
      1513718.96      6876081.71
#Sta/Elev= 30
  3398.9 1814.84  3549.9  1814.9  3606.4 1812.84  3679.9 1813.56  3719.9 1810.78
  3769.9 1811.12  3813.4 1809.07  4249.9  1805.2  4519.9 1805.63  4763.1 1803.33
  4849.9 1802.17  4899.9  1803.1  4978.5 1800.54    4979 1800.04  5001.3 1800.54
  5009.9 1803.12  5052.8  1803.2  6090.2 1806.06  6274.3 1806.55  6894.7 1810.17
  7444.5 1815.83  7785.5 1821.88  7884.5  1823.7  7983.5 1825.33  8082.5 1825.84
  8181.5 1825.76  8288.9 1825.29  8378.5 1825.02  8468.3 1826.07  8567.9  1826.2
#Mann= 18 ,-1 , 0
  3398.9    .045       0  3606.4     .07       0  3813.4    .045       0
  4763.1     .07       0  4978.5     .07       0  5001.3     .07       0
  5052.8    .045       0  6090.2    .035       0  6274.3    .045       0
  7444.5     .07       0  7785.5    .035       0  7884.5     .07       0
  7983.5    .045       0  8082.5    .035       0  8181.5    .045       0
  8288.9     .07       0  8378.5    .045       0  8468.3     .07       0
Bank Sta=4978.5,5001.3
XS Rating Curve= 0 ,0
Exp/Cntr=0.3,0.1