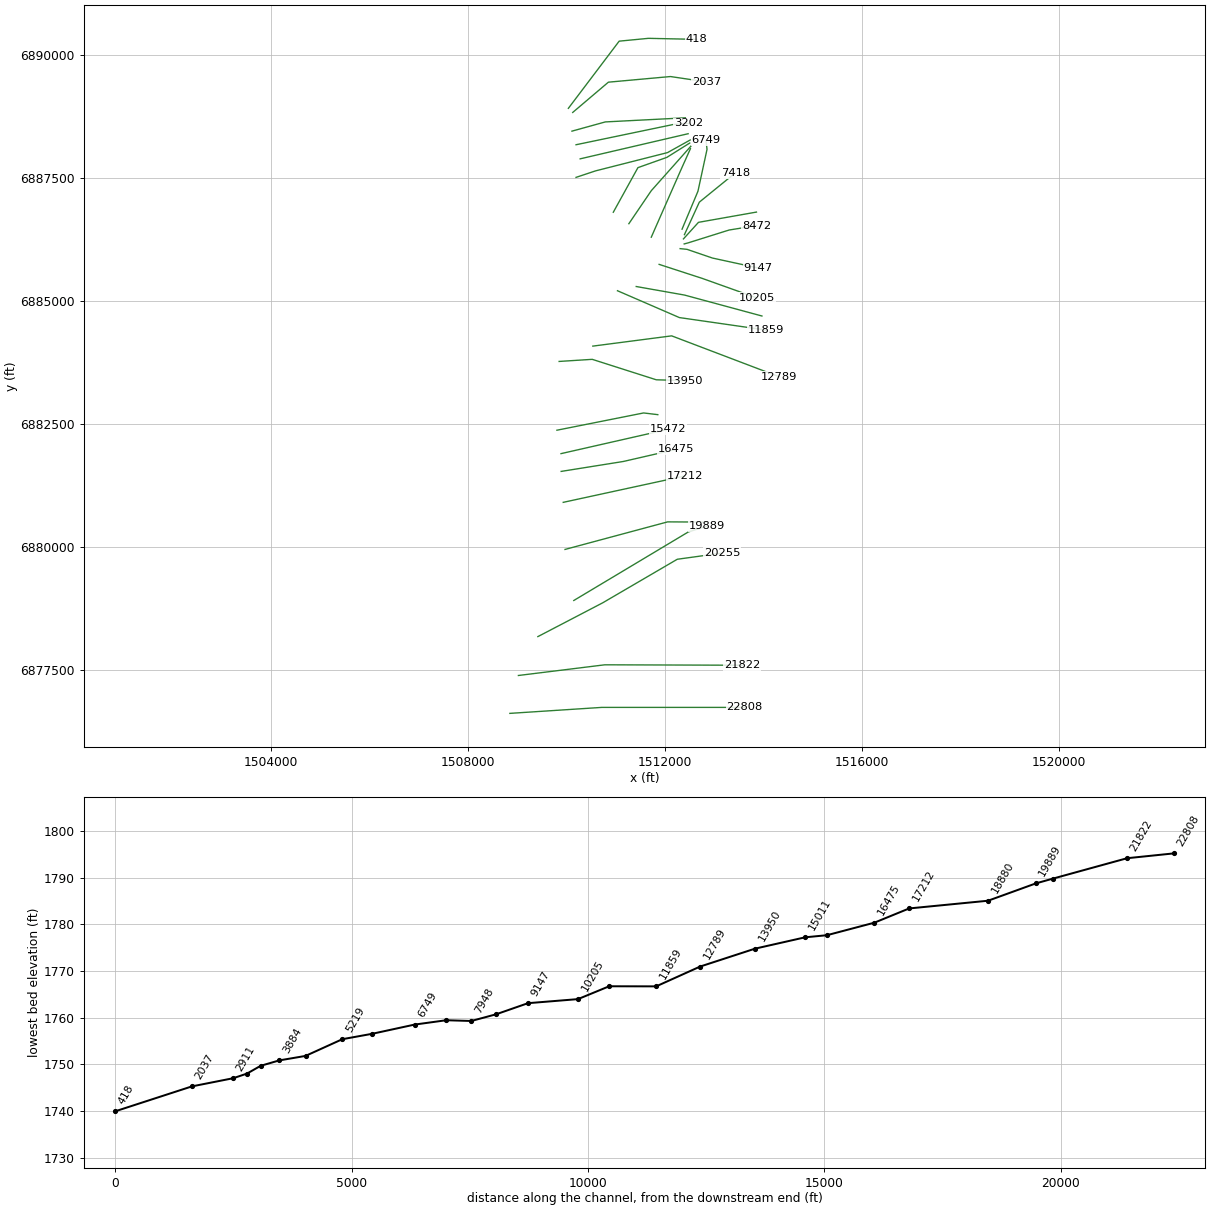
HEC-RAS study NC Unknown Stream 72.prj: NC Unknown Stream 72 Base Level Engineering

--- NC Unknown Stream 72.g01 (geometry) --- (continued)

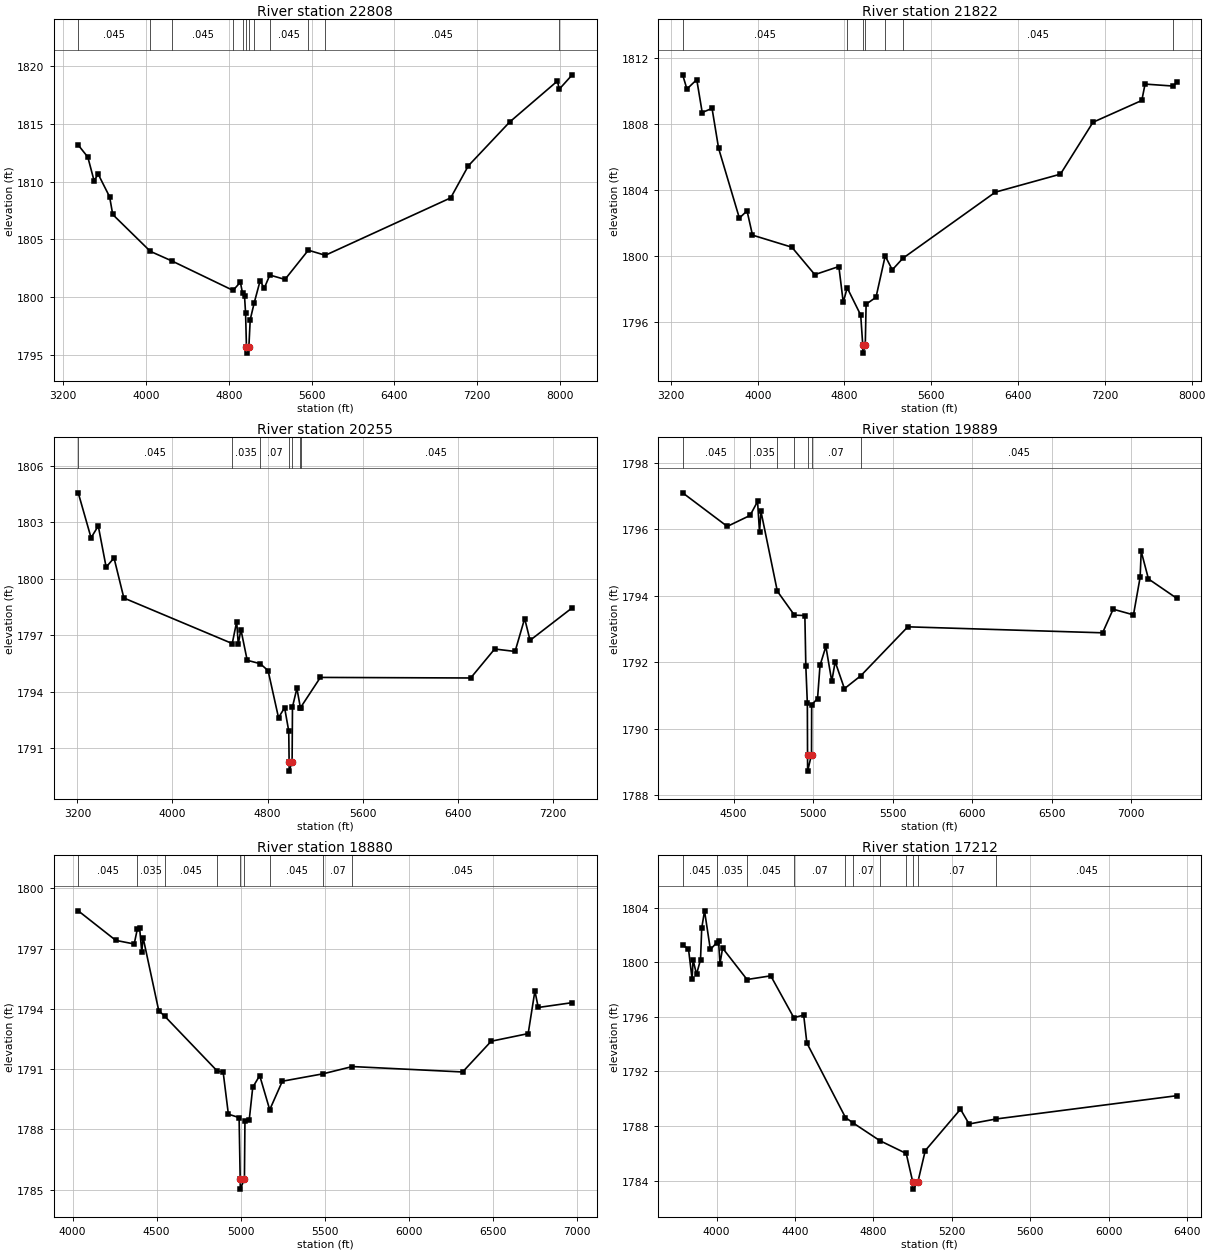
Type RM Length L Ch R = 1 ,22808   ,986,986,986
BEGIN DESCRIPTION:
NC Unknown Stream 72 14.0
END DESCRIPTION:
XS GIS Cut Line= 3
      1508852.66      6876625.11      1510718.97      6876746.64
      1513618.31      6876746.64
#Sta/Elev= 30
  3346.7 1813.17  3439.2 1812.13  3499.4 1810.09  3539.4 1810.65  3649.7 1808.69
  3679.7 1807.16  4042.9 1803.97  4255.5 1803.12  4841.5 1800.59  4912.3  1801.3
  4932.8 1800.35  4952.4 1800.09  4962.5 1798.61    4971 1795.66  4971.5 1795.16
    4994 1795.66  5007.3 1798.06  5045.7 1799.51  5102.7 1801.42  5142.8 1800.78
  5196.4 1801.92    5343 1801.54    5568 1804.07  5732.4 1803.63    6943  1808.6
    7113 1811.37    7513 1815.17    7973 1818.71  7991.5 1818.01  8116.3 1819.25
#Mann= 12 ,-1 , 0
  3346.7    .045       0  4042.9    .035       0  4255.5    .045       0
  4841.5     .07       0  4932.8    .045       0    4971    .045       0
    4994    .045       0  5045.7     .07       0  5196.4    .045       0
    5568    .035       0  5732.4    .045       0  7991.5     .07       0
Bank Sta=4971,4994
XS Rating Curve= 0 ,0
Exp/Cntr=0.3,0.1

Type RM Length L Ch R = 1 ,21822   ,1567,1567,1567
BEGIN DESCRIPTION:
NC Unknown Stream 72 13.0
END DESCRIPTION:
XS GIS Cut Line= 3
      1509026.23      6877394.78      1510779.73       6877611.8
      1513566.14      6877603.12
#Sta/Elev= 30
  3308.4 1810.97  3347.5 1810.11  3438.2 1810.68  3488.5 1808.69  3579.2 1808.94
  3639.7 1806.52  3831.1  1802.3  3901.7 1802.74    3952 1801.27  4314.8 1800.54
  4526.4 1798.88  4748.1 1799.37  4788.4 1797.21  4825.1 1798.08  4949.6 1796.43
  4968.1 1794.63  4968.6 1794.13  4991.6 1794.63  4999.3 1797.09  5090.5 1797.51
  5175.2 1800.01  5240.5 1799.17  5338.2 1799.87  6190.6 1803.87  6790.6 1804.96
  7090.6  1808.1  7540.6 1809.42  7570.6 1810.41  7830.4 1810.29  7861.7 1810.51
#Mann= 7 ,-1 , 0
  3308.4    .045       0  4825.1     .07       0  4968.1     .07       0
  4991.6     .07       0  5175.2    .035       0  5338.2    .045       0
  7830.4     .07       0
Bank Sta=4968.1,4991.6
XS Rating Curve= 0 ,0
Exp/Cntr=0.3,0.1

Type RM Length L Ch R = 1 ,20255   ,366,366,366
BEGIN DESCRIPTION:
Mapping XS faff9db1
END DESCRIPTION:
XS GIS Cut Line= 4
       1509421.2      6878184.71      1510736.33      6878870.48
      1512251.08       6879755.9      1513161.31       6879881.6
#Sta/Elev= 30
  3206.9 1804.56  3314.8 1802.17  3375.5  1802.8  3441.7 1800.61    3508  1801.1
  3590.8 1798.97  4502.8 1796.55  4540.2 1797.72  4553.3 1796.52  4575.8 1797.29
  4628.6 1795.66  4738.2 1795.48  4804.4 1795.11  4892.2 1792.61  4943.4 1793.14
  4978.2  1791.9  4981.4 1790.27  4981.9 1789.77  5006.5 1790.27  5009.6 1793.18
  5046.8 1794.17  5076.9 1793.12    5078 1793.15  5244.3 1794.75  6509.2 1794.72
  6710.9 1796.26  6882.7 1796.13  6963.4 1797.88  7008.6 1796.72  7363.5 1798.45
#Mann= 7 ,-1 , 0
  3206.9    .045       0  4502.8    .035       0  4738.2     .07       0
  4981.4    .045       0  5006.5     .07       0  5076.9     .07       0
    5078    .045       0
Bank Sta=4981.4,5006.5
XS Rating Curve= 0 ,0
Exp/Cntr=0.3,0.1

Type RM Length L Ch R = 1 ,19889   ,1009,1009,1009
BEGIN DESCRIPTION:
Mapping XS 477c46f4
END DESCRIPTION:
XS GIS Cut Line= 3
      1510150.39      6878918.23      1512476.78      6880311.45
      1512854.35      6880428.63
#Sta/Elev= 30
  4179.2  1797.1  4459.7 1796.09  4603.1 1796.42  4650.3 1796.84  4662.5 1795.92
  4671.7 1796.54  4774.7 1794.14  4882.3 1793.42  4947.8 1793.41  4953.9 1791.88
  4963.4 1790.77  4964.6 1789.23  4965.1 1788.73  4989.7 1789.23  4990.6 1790.73
  5027.5 1790.91  5043.1 1791.91    5080 1792.48    5117 1791.43  5138.4 1792.02
  5196.7 1791.21  5299.8  1791.6  5595.3 1793.07  6820.4 1792.89  6886.9  1793.6
  7014.7 1793.43  7056.5 1794.56  7063.3 1795.34  7108.9 1794.51  7286.2 1793.93
#Mann= 7 ,-1 , 0
  4179.2    .045       0  4603.1    .035       0  4774.7    .045       0
  4882.3     .07       0  4964.6     .07       0  4989.7     .07       0
  5299.8    .045       0
Bank Sta=4964.6,4989.7
XS Rating Curve= 0 ,0
Exp/Cntr=0.3,0.1

Type RM Length L Ch R = 1 ,18880   ,1668,1668,1668
BEGIN DESCRIPTION:
Mapping XS 4ae5e97e
END DESCRIPTION:
XS GIS Cut Line= 3
      1509972.47      6879955.56      1512055.77      6880515.45
      1512837.04      6880511.11
#Sta/Elev= 30
  4033.6 1798.88  4256.9 1797.41  4366.4 1797.23  4384.8 1797.96  4398.6 1798.04
  4411.6 1796.83  4419.3 1797.55  4512.5 1793.91  4547.6 1793.64    4859 1790.92
  4895.7 1790.85  4926.7 1788.76  4990.5 1788.59    4997 1785.53  4997.5 1785.03
  5022.2 1785.53  5025.3 1788.43    5051 1788.49  5071.7  1790.1  5113.1 1790.68
  5172.7 1788.98  5247.7  1790.4  5490.5 1790.77  5663.8 1791.13  6320.1 1790.86
  6490.1 1792.39  6710.1 1792.77  6750.1 1794.89  6770.1 1794.07  6972.1 1794.31
#Mann= 9 ,-1 , 0
  4033.6    .045       0  4384.8    .035       0  4547.6    .045       0
    4859     .07       0    4997     .07       0  5022.2     .07       0
  5172.7    .045       0  5490.5     .07       0  5663.8    .045       0
Bank Sta=4997,5022.2
XS Rating Curve= 0 ,0
Exp/Cntr=0.3,0.1

Type RM Length L Ch R = 1 ,17212   ,737,737,737
BEGIN DESCRIPTION:
Mapping XS f6afa40d
END DESCRIPTION:
XS GIS Cut Line= 2
      1509936.03      6880912.16      1512397.82      6881446.88
#Sta/Elev= 30
    3827 1801.23  3856.6 1800.98    3875 1798.77  3880.2 1800.17  3897.6 1799.11
    3918 1800.18  3924.2 1802.49  3938.5 1803.76  3968.2 1800.93    4001 1801.43
  4010.1 1801.52  4017.3 1799.89  4030.6 1801.03  4155.2 1798.73  4276.2    1799
  4393.7 1795.94  4444.2 1796.12  4460.4 1794.08  4657.4 1788.62  4693.8 1788.25
  4832.5 1786.93  4967.1 1785.99  5000.8 1783.88  5001.3 1783.38  5026.1 1783.88
  5064.2  1786.2  5243.8 1789.23  5287.8 1788.15  5426.5 1788.52  6346.2 1790.22
#Mann= 11 ,-1 , 0
    3827    .045       0    4001    .035       0  4155.2    .045       0
  4393.7     .07       0  4657.4    .035       0  4693.8     .07       0
  4832.5    .035       0  4967.1     .07       0  5000.8     .07       0
  5026.1     .07       0  5426.5    .045       0
Bank Sta=5000.8,5026.1
XS Rating Curve= 0 ,0
Exp/Cntr=0.3,0.1

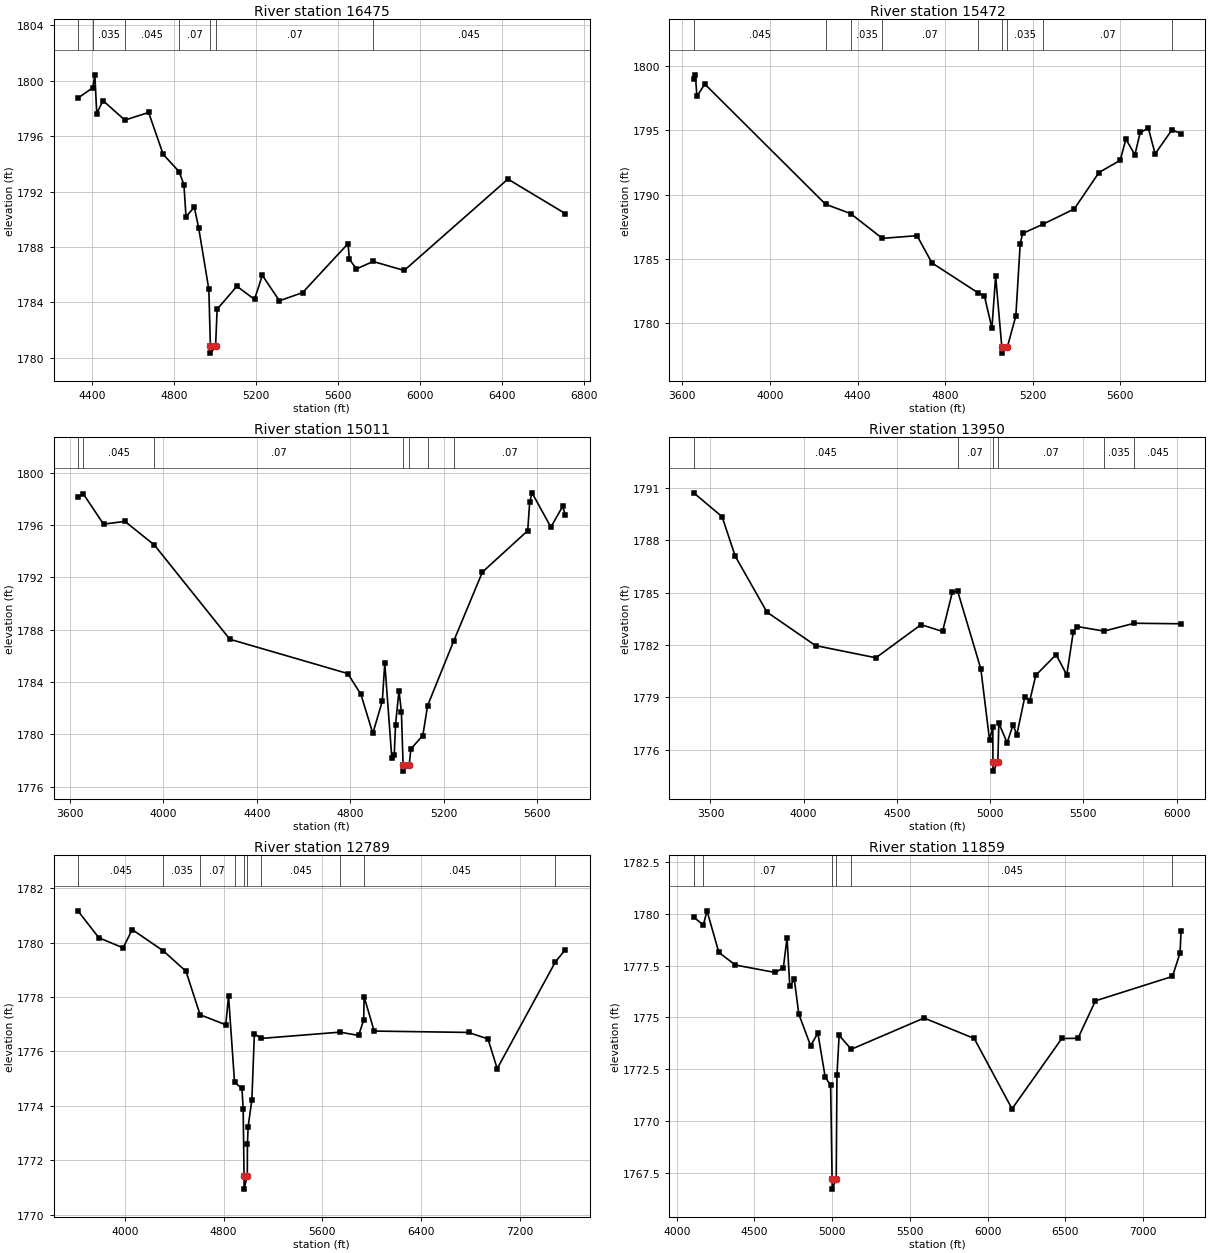
Type RM Length L Ch R = 1 ,16475   ,1003,1003,1003
BEGIN DESCRIPTION:
Mapping XS 78f82efa
END DESCRIPTION:
XS GIS Cut Line= 3
      1509894.29      6881540.62      1511154.73      6881742.01
      1512227.64      6881988.54
#Sta/Elev= 30
  4329.8 1798.75  4402.7  1799.5  4412.4 1800.43  4421.7 1797.63    4452 1798.57
  4558.7 1797.16  4674.8 1797.71  4745.7 1794.69  4823.9 1793.43  4846.9 1792.49
  4857.1 1790.19  4897.6 1790.87  4919.1 1789.36  4968.5 1784.93  4976.1 1780.83
  4976.6 1780.33  5001.4 1780.83    5009  1783.5  5105.3 1785.16  5191.3 1784.21
  5229.5 1785.95  5312.8 1784.11  5425.8  1784.7  5647.6 1788.24    5654 1787.11
  5688.6 1786.41  5769.8 1786.95  5921.4  1786.3  6427.4  1792.9  6707.1 1790.41
#Mann= 7 ,-1 , 0
  4329.8    .045       0  4402.7    .035       0  4558.7    .045       0
  4823.9     .07       0  4976.1     .07       0  5001.4     .07       0
  5769.8    .045       0
Bank Sta=4976.1,5001.4
XS Rating Curve= 0 ,0
Exp/Cntr=0.3,0.1

Type RM Length L Ch R = 1 ,15472   ,461,461,461
BEGIN DESCRIPTION:
Mapping XS 4137f0fa
END DESCRIPTION:
XS GIS Cut Line= 2
      1509890.88      6881901.74      1512060.49      6882394.67
#Sta/Elev= 30
  3652.2 1799.03  3659.7 1799.33  3666.7 1797.66  3702.8 1798.61    4254 1789.25
  4368.5 1788.52  4513.2 1786.59  4671.7  1786.8  4739.7 1784.68  4948.1 1782.37
  4979.3 1782.11  5013.6  1779.6  5030.6 1783.64  5058.7 1778.15  5059.2 1777.65
  5084.5 1778.15  5122.9 1780.55  5142.8 1786.17  5153.6 1786.97  5246.5 1787.69
  5389.5 1788.88  5502.3 1791.72  5599.2 1792.67  5625.4 1794.32  5666.4  1793.1
  5690.5 1794.84  5727.9 1795.17  5758.7 1793.17  5835.4 1795.04  5877.1 1794.75
#Mann= 9 ,-1 , 0
  3652.2    .045       0    4254     .07       0  4368.5    .035       0
  4513.2     .07       0  4948.1    .035       0  5058.7    .035       0
  5084.5    .035       0  5246.5     .07       0  5835.4    .035       0
Bank Sta=5058.7,5084.5
XS Rating Curve= 0 ,0
Exp/Cntr=0.3,0.1

Type RM Length L Ch R = 1 ,15011   ,1061,1061,1061
BEGIN DESCRIPTION:
Mapping XS 72c760dc
END DESCRIPTION:
XS GIS Cut Line= 3
      1509807.55      6882377.43      1511567.92      6882728.12
      1511856.08       6882693.4
#Sta/Elev= 30
  3634.5 1798.12  3657.7 1798.37  3744.1 1796.06  3835.8 1796.27    3962 1794.46
  4284.5 1787.27  4789.1 1784.65  4845.3 1783.07  4896.4 1780.08    4937 1782.55
  4947.5 1785.45  4977.8 1778.18    4988  1778.4  4993.5 1780.76  5008.4 1783.34
  5018.6 1781.74  5025.9  1777.7  5026.4  1777.2  5052.1  1777.7  5059.4  1778.9
  5110.4 1779.92  5130.5 1782.19  5241.7  1787.1  5365.3  1792.4  5559.2 1795.56
  5567.5 1797.73  5577.6 1798.45  5658.2 1795.83  5708.5 1797.41  5719.7 1796.78
#Mann= 7 ,-1 , 0
  3634.5     .07       0  3657.7    .045       0    3962     .07       0
  5025.9     .07       0  5052.1     .07       0  5130.5    .035       0
  5241.7     .07       0
Bank Sta=5025.9,5052.1
XS Rating Curve= 0 ,0
Exp/Cntr=0.3,0.1

Type RM Length L Ch R = 1 ,13950   ,1161,1161,1161
BEGIN DESCRIPTION:
Mapping XS 636e790c
END DESCRIPTION:
XS GIS Cut Line= 4
      1509852.99      6883774.49      1510524.12      6883817.15
      1511824.87      6883401.73      1512400.65      6883384.39
#Sta/Elev= 30
  3410.2 1790.73  3562.5 1789.36  3632.7  1787.1    3803 1783.89  4063.5 1781.97
  4387.5 1781.27  4629.5 1783.17    4745 1782.78  4797.4 1785.03    4826 1785.09
  4950.3 1780.63  4996.9 1776.57  5014.7 1777.28  5015.2 1775.27  5015.7 1774.77
  5041.5 1775.27  5046.8 1777.52  5091.4  1776.4  5122.9 1777.42  5143.4 1776.86
  5186.1 1779.03    5213 1778.82  5245.2 1780.27  5353.8 1781.45  5411.3 1780.29
  5446.1 1782.75  5468.3 1783.06  5610.9  1782.8  5773.4 1783.25  6024.2 1783.22
#Mann= 6 ,-1 , 0
  3410.2    .045       0    4826     .07       0  5015.2     .07       0
  5041.5     .07       0  5610.9    .035       0  5773.4    .045       0
Bank Sta=5015.2,5041.5
XS Rating Curve= 0 ,0
Exp/Cntr=0.3,0.1

Type RM Length L Ch R = 1 ,12789   ,930,930,930
BEGIN DESCRIPTION:
Mapping XS 4550f390
END DESCRIPTION:
XS GIS Cut Line= 3
      1510536.67      6884085.76      1512137.37      6884294.09
      1514320.43       6883463.3
#Sta/Elev= 30
  3619.9 1781.17  3789.7 1780.18  3986.1 1779.81  4060.2 1780.48  4311.6  1779.7
  4495.6 1778.95  4610.1 1777.35  4818.3 1776.98  4840.8 1778.04  4889.5 1774.87
  4949.4 1774.64  4959.4 1773.89  4966.5 1771.44    4967 1770.94  4992.8 1771.44
    4994 1772.59  4999.8 1773.24    5030 1774.23  5050.2 1776.65  5107.5 1776.48
  5743.2 1776.71  5894.9 1776.59  5936.2 1777.15  5939.7 1778.01  6021.2 1776.75
  6785.9  1776.7  6943.5 1776.46  7018.4 1775.37  7489.8 1779.29  7569.9 1779.74
#Mann= 10 ,-1 , 0
  3619.9    .045       0  4311.6    .035       0  4610.1     .07       0
  4889.5    .045       0  4966.5     .07       0  4992.8    .045       0
  5107.5    .045       0  5743.2    .035       0  5939.7    .045       0
  7489.8    .035       0
Bank Sta=4966.5,4992.8
XS Rating Curve= 0 ,0
Exp/Cntr=0.3,0.1

Type RM Length L Ch R = 1 ,11859   ,994,994,994
BEGIN DESCRIPTION:
Mapping XS 3d2dd021
END DESCRIPTION:
XS GIS Cut Line= 3
      1511036.64      6885210.78      1512293.62      6884665.62
      1514041.47       6884413.9
#Sta/Elev= 30
  4108.9 1779.85  4170.9 1779.46  4194.3 1780.15  4270.6 1778.14    4377 1777.53
  4633.4 1777.17  4685.8  1777.4  4709.3 1778.85  4727.3  1776.5  4756.2 1776.84
  4785.1 1775.16    4861 1773.63  4907.9 1774.24  4954.8 1772.12    4990 1771.72
  4999.4  1767.2  4999.9  1766.7  5025.9  1767.2  5030.7  1772.2  5044.5 1774.13
  5123.1 1773.46  5591.5 1774.97    5914 1773.98  6157.3 1770.58  6477.5 1773.98
  6581.7 1773.99  6693.9  1775.8  7189.4 1776.98  7238.4 1778.11  7244.9 1779.18
#Mann= 6 ,-1 , 0
  4108.9    .045       0  4170.9     .07       0  4999.4     .07       0
  5025.9     .07       0  5123.1    .045       0  7189.4    .035       0
Bank Sta=4999.4,5025.9
XS Rating Curve= 0 ,0
Exp/Cntr=0.3,0.1

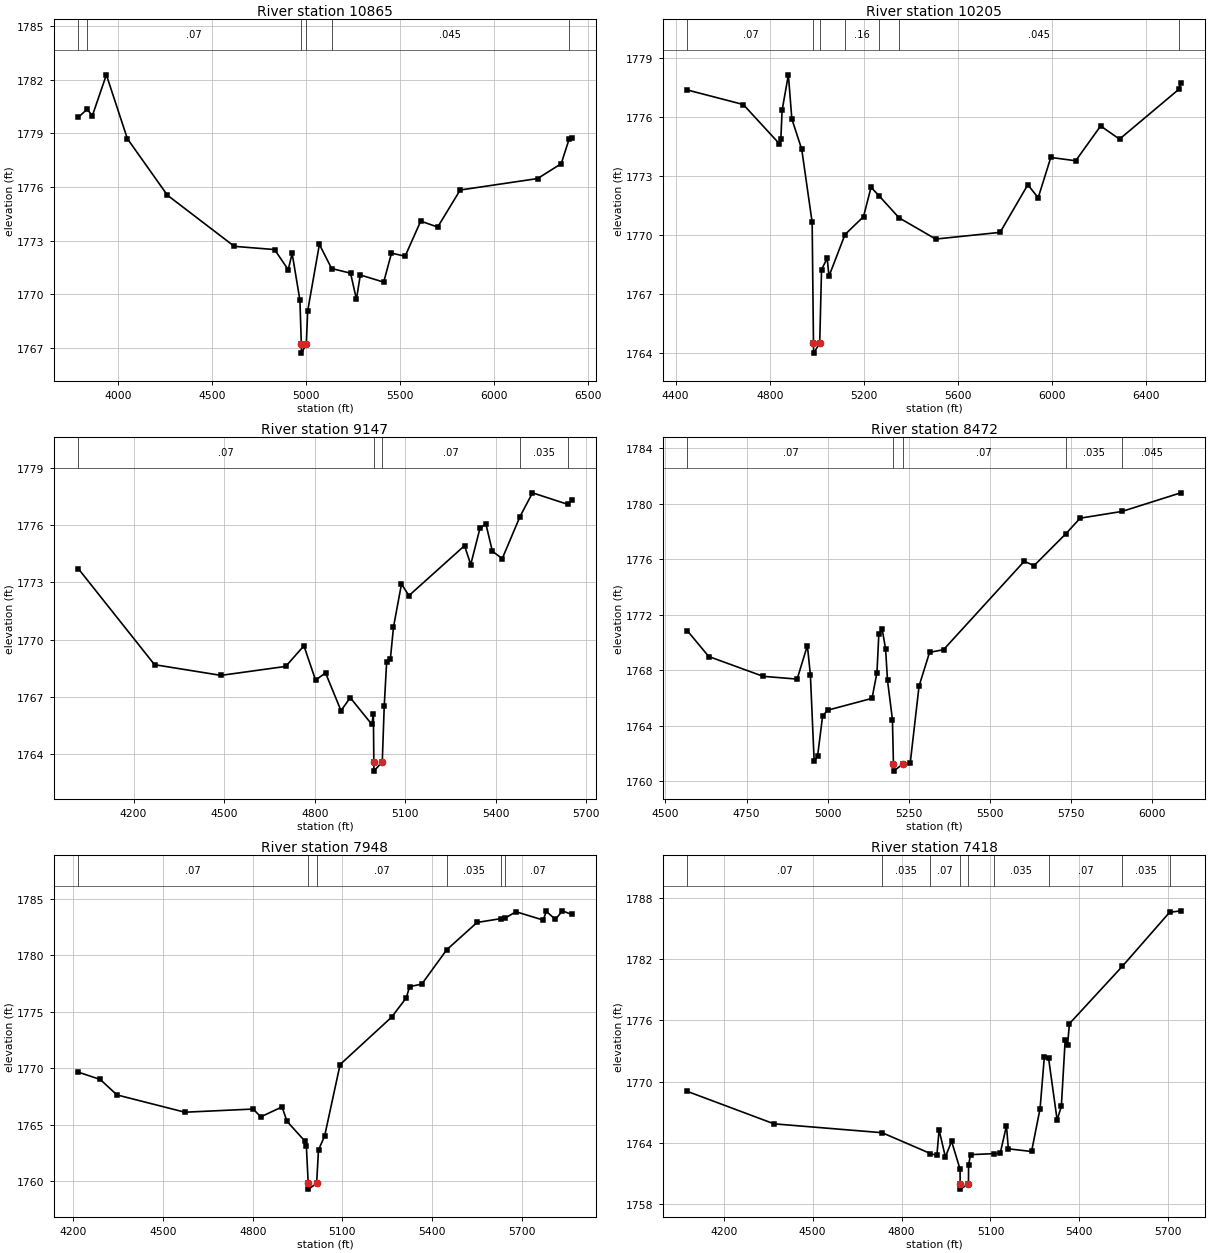
Type RM Length L Ch R = 1 ,10865   ,660,660,660
BEGIN DESCRIPTION:
NC Unknown Stream 72 8.0
END DESCRIPTION:
XS GIS Cut Line= 3
      1511417.55      6885296.48      1512398.44      6885122.87
      1513969.65      6884697.51
#Sta/Elev= 30
  3789.8  1779.9  3836.8 1780.35  3865.2    1780  3939.5 1782.28  4051.2 1778.71
  4264.1 1775.55    4620 1772.69  4834.2 1772.51  4906.7 1771.38  4927.4  1772.3
  4968.8 1769.68  4976.3 1767.22  4976.8 1766.72  5002.8 1767.22  5010.1 1769.08
  5072.4  1772.8  5137.4 1771.45  5238.2 1771.19  5269.3 1769.73    5290 1771.09
  5414.3 1770.69  5455.8 1772.31  5528.3 1772.14  5611.2  1774.1  5701.5 1773.77
  5821.1 1775.84  6232.8 1776.48  6358.3 1777.31  6400.8  1778.7  6413.7 1778.75
#Mann= 6 ,-1 , 0
  3789.8    .045       0  3836.8     .07       0  4976.3     .07       0
  5002.8     .07       0  5137.4    .045       0  6400.8    .035       0
Bank Sta=4976.3,5002.8
XS Rating Curve= 0 ,0
Exp/Cntr=0.3,0.1

Type RM Length L Ch R = 1 ,10205   ,1058,1058,1058
BEGIN DESCRIPTION:
Mapping XS 6d222e33
END DESCRIPTION:
XS GIS Cut Line= 3
      1511882.77      6885746.15      1512757.81      6885461.41
      1513865.41      6885065.59
#Sta/Elev= 30
  4450.1 1777.35  4687.8 1776.61  4841.5 1774.61  4847.4 1774.84  4852.7 1776.31
  4879.4 1778.12  4894.1 1775.88  4936.2 1774.33  4980.4 1770.62    4986 1764.47
  4986.5 1763.97  5012.5 1764.47  5020.3 1768.22  5044.3 1768.79  5051.9 1767.88
    5120    1770  5198.7 1770.91  5230.6  1772.4  5264.7 1771.97  5349.6 1770.85
  5505.4 1769.77  5778.9 1770.11  5896.7 1772.53  5940.8 1771.87  5994.4 1773.92
  6100.1 1773.75  6206.2 1775.52  6286.3 1774.85  6539.1 1777.39  6546.5 1777.71
#Mann= 7 ,-1 , 0
  4450.1     .07       0    4986     .07       0  5012.5     .07       0
    5120     .16       0  5264.7     .07       0  5349.6    .045       0
  6539.1    .035       0
Bank Sta=4986,5012.5
XS Rating Curve= 0 ,0
Exp/Cntr=0.3,0.1

Type RM Length L Ch R = 1 ,9147    ,675,675,675
BEGIN DESCRIPTION:
Mapping XS ced85d42
END DESCRIPTION:
XS GIS Cut Line= 4
      1512308.91      6886066.01      1512448.78      6886051.69
      1512966.14       6885874.6      1513891.62      6885673.56
#Sta/Elev= 30
  4016.6 1773.72  4269.5 1768.68  4489.5 1768.12    4704 1768.59  4764.3 1769.67
  4802.9 1767.87  4835.9 1768.25  4887.1 1766.27  4917.8 1766.95  4989.3 1765.55
  4994.4  1766.1  4995.9  1763.6  4996.4  1763.1  5023.9  1763.6  5030.3  1766.5
  5038.4 1768.84  5050.8    1769    5061 1770.65  5087.5 1772.91  5112.2  1772.3
  5296.4 1774.92  5316.9 1773.93  5347.6 1775.84    5367 1776.07  5388.5 1774.63
  5421.3 1774.24  5479.9 1776.44  5521.5 1777.69  5639.5 1777.08  5651.1 1777.34
#Mann= 5 ,-1 , 0
  4016.6     .07       0  4995.9     .07       0  5023.9     .07       0
  5479.9    .035       0  5639.5    .045       0
Bank Sta=4995.9,5023.9
XS Rating Curve= 0 ,0
Exp/Cntr=0.3,0.1

Type RM Length L Ch R = 1 ,8472    ,524,524,524
BEGIN DESCRIPTION:
Mapping XS 09fcc0e9
END DESCRIPTION:
XS GIS Cut Line= 4
      1512391.34      6886161.51      1512473.09      6886183.63
      1513302.95      6886444.05      1513860.97      6886534.16
#Sta/Elev= 30
  4567.6 1770.85  4633.5 1768.99    4801 1767.56  4905.8 1767.36  4937.3 1769.78
  4946.6 1767.66  4958.2 1761.45  4968.7  1761.8  4984.3 1764.71  5000.2 1765.12
  5136.4 1765.97  5151.6 1767.82  5157.4  1770.6  5167.9 1770.94  5178.3 1769.51
  5184.1 1767.27  5199.3 1764.44  5202.4 1761.22  5202.9 1760.72  5230.5 1761.22
  5254.1  1761.3  5281.3 1766.86  5313.7 1769.29  5356.6 1769.48  5605.2 1775.86
  5635.6 1775.55  5733.6 1777.85  5777.4 1778.97  5906.8 1779.46  6087.3  1780.8
#Mann= 5 ,-1 , 0
  4567.6     .07       0  5202.4     .07       0  5230.5     .07       0
  5733.6    .035       0  5906.8    .045       0
Bank Sta=5202.4,5230.5
XS Rating Curve= 0 ,0
Exp/Cntr=0.3,0.1

Type RM Length L Ch R = 1 ,7948    ,530,530,530
BEGIN DESCRIPTION:
Mapping XS 64c3e9d6
END DESCRIPTION:
XS GIS Cut Line= 3
      1512376.14      6886263.51      1512681.42       6886600.3
      1513858.47      6886808.63
#Sta/Elev= 30
  4216.5 1769.65    4290    1769  4346.1 1767.63  4573.2  1766.1  4801.5 1766.38
    4827 1765.69  4898.1 1766.57  4914.7 1765.29  4973.9 1763.56  4979.4 1763.09
  4985.6 1759.79  4986.1 1759.29  5013.7 1759.79    5020 1762.77  5040.3 1763.97
  5092.2 1770.32  5264.6 1774.52  5313.6 1776.23  5324.6 1777.22  5365.3 1777.44
  5448.7 1780.48  5550.2  1782.9  5629.9 1783.24  5643.2 1783.27  5680.1 1783.85
  5771.5 1783.11  5781.7 1783.89  5812.1 1783.17  5835.8 1783.93  5866.4 1783.61
#Mann= 6 ,-1 , 0
  4216.5     .07       0  4985.6     .07       0  5013.7     .07       0
  5448.7    .035       0  5629.9    .045       0  5643.2     .07       0
Bank Sta=4985.6,5013.7
XS Rating Curve= 0 ,0
Exp/Cntr=0.3,0.1

Type RM Length L Ch R = 1 ,7418    ,669,669,669
BEGIN DESCRIPTION:
Mapping XS a2badfed
END DESCRIPTION:
XS GIS Cut Line= 3
       1512396.7       6886350.3      1512698.78      6887010.02
      1513427.46      6887603.37
#Sta/Elev= 30
    4077 1769.03  4369.6 1765.85  4734.4 1764.98  4897.4 1762.94  4919.2 1762.75
  4926.7 1765.26  4947.9  1762.6  4968.8 1764.14  4997.5  1761.4  4997.8 1759.95
  4998.3 1759.45  5025.9 1759.95  5026.2 1761.79  5032.7 1762.83  5112.5 1762.93
    5133 1762.96    5154 1765.65  5160.5  1763.4  5238.8 1763.14  5267.5 1767.34
  5281.9 1772.41  5296.2 1772.29    5325 1766.24  5339.3 1767.55  5352.2 1774.06
  5360.2 1773.55  5366.6 1775.67  5545.7 1781.31  5704.5 1786.58  5742.3 1786.73
#Mann= 9 ,-1 , 0
    4077     .07       0  4734.4    .035       0  4897.4     .07       0
  4997.8     .07       0  5025.9     .07       0  5112.5    .035       0
  5296.2     .07       0  5545.7    .035       0  5704.5    .045       0
Bank Sta=4997.8,5025.9
XS Rating Curve= 0 ,0
Exp/Cntr=0.3,0.1

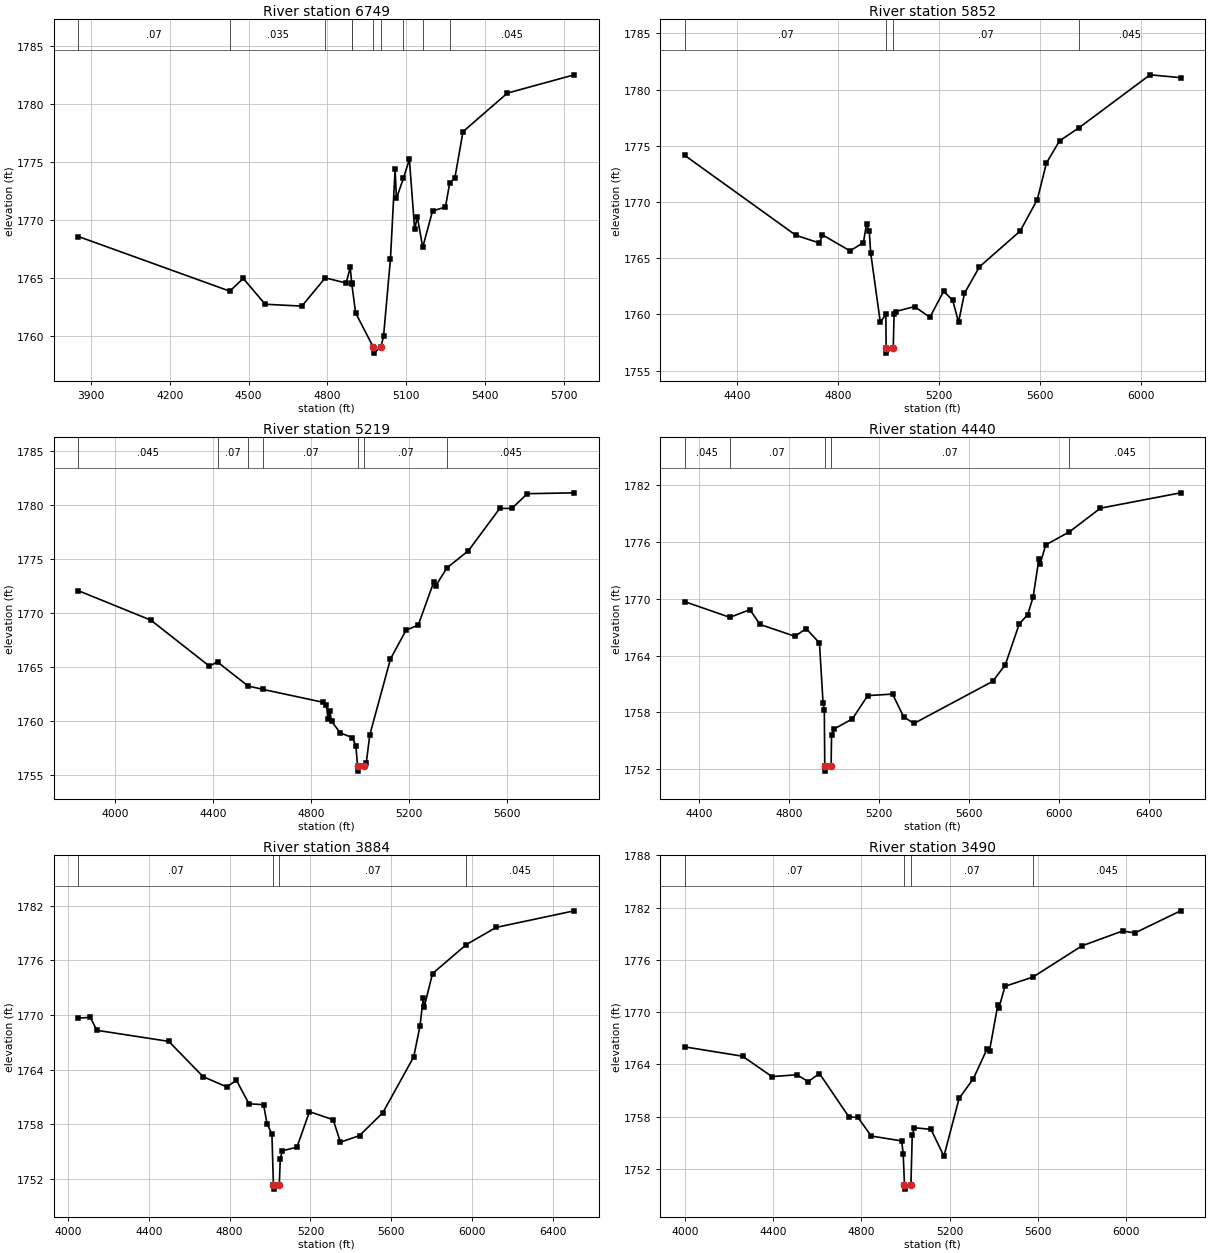
Type RM Length L Ch R = 1 ,6749    ,897,897,897
BEGIN DESCRIPTION:
Mapping XS 326ea755
END DESCRIPTION:
XS GIS Cut Line= 4
      1512348.08      6886461.38      1512671.01      6887232.24
      1512855.03      6888082.94      1512834.42      6888265.03
#Sta/Elev= 30
  3850.9 1768.59  4428.1 1763.87  4479.3 1764.97  4562.8 1762.74  4702.8 1762.58
  4791.8 1765.02  4871.4 1764.57    4887 1765.92  4892.6 1764.59  4892.9 1764.52
  4907.4    1762  4975.2 1759.02  4975.7 1758.52  5003.4 1759.02  5013.9 1759.97
  5040.4 1766.69    5058 1774.38  5063.1 1771.88  5089.6 1773.61  5112.4 1775.25
  5132.5 1769.22  5142.7 1770.27  5163.3 1767.66  5200.6 1770.79  5249.8 1771.14
  5265.9 1773.17    5286 1773.68  5316.7 1777.64  5485.7 1780.97  5740.3 1782.55
#Mann= 10 ,-1 , 0
  3850.9     .07       0  4428.1    .035       0  4791.8     .07       0
  4892.6    .035       0  4892.9     .07       0  4975.2     .07       0
  5003.4     .07       0  5089.6    .045       0  5163.3     .07       0
  5265.9    .045       0
Bank Sta=4975.2,5003.4
XS Rating Curve= 0 ,0
Exp/Cntr=0.3,0.1

Type RM Length L Ch R = 1 ,5852    ,633,633,633
BEGIN DESCRIPTION:
Mapping XS ce68a456
END DESCRIPTION:
XS GIS Cut Line= 3
      1511723.11      6886298.25       1512334.2       6887687.1
      1512518.23      6888096.83
#Sta/Elev= 30
  4192.4 1774.14  4633.1 1767.03  4726.5 1766.35  4738.4 1767.07  4847.6 1765.65
  4900.8 1766.38  4913.2 1768.06  4924.1 1767.38  4929.6 1765.48  4967.8 1759.29
  4989.7 1759.99    4991 1757.05  4991.5 1756.55  5019.2 1757.05  5022.4    1760
  5028.4 1760.25  5103.9 1760.69  5164.5 1759.74  5219.1 1762.06  5254.9 1761.25
  5278.2 1759.31  5301.5 1761.87  5361.1 1764.23  5522.5 1767.41  5590.5 1770.21
  5626.8 1773.47  5678.9 1775.44  5755.2 1776.59  6037.7 1781.31  6158.9 1781.06
#Mann= 4 ,-1 , 0
  4192.4     .07       0    4991     .07       0  5019.2     .07       0
  5755.2    .045       0
Bank Sta=4991,5019.2
XS Rating Curve= 0 ,0
Exp/Cntr=0.3,0.1

Type RM Length L Ch R = 1 ,5219    ,779,779,779
BEGIN DESCRIPTION:
Mapping XS 03f7b57a
END DESCRIPTION:
XS GIS Cut Line= 3
      1511268.21      6886572.49      1511723.09      6887242.66
      1512531.06      6888151.19
#Sta/Elev= 30
  3850.2 1772.08  4146.9 1769.35  4385.1 1765.11  4418.9 1765.48  4543.1 1763.27
  4606.2 1762.94  4849.6 1761.76  4863.8 1761.48  4870.5  1760.2    4878 1760.92
  4884.7    1760  4920.6 1758.92    4970 1758.49  4984.2 1757.73  4990.9 1755.89
  4991.4 1755.39  5019.2 1755.89  5026.8 1756.18    5041 1758.74  5125.5 1765.76
  5189.2 1768.43  5239.2  1768.9  5302.8 1772.92  5309.7  1772.5  5356.4 1774.19
  5444.1 1775.78    5572 1779.69  5621.4 1779.69  5684.9 1781.05    5876 1781.13
#Mann= 7 ,-1 , 0
  3850.2    .045       0  4418.9     .07       0  4543.1    .045       0
  4606.2     .07       0  4990.9     .07       0  5019.2     .07       0
  5356.4    .045       0
Bank Sta=4990.9,5019.2
XS Rating Curve= 0 ,0
Exp/Cntr=0.3,0.1

Type RM Length L Ch R = 1 ,4440    ,556,556,556
BEGIN DESCRIPTION:
Mapping XS 7972355f
END DESCRIPTION:
XS GIS Cut Line= 4
      1510952.27      6886805.19      1511452.26      6887711.41
      1512039.06      6887919.74      1512504.32       6888211.4
#Sta/Elev= 30
  4334.6 1769.69  4535.2 1768.04  4624.4 1768.85    4669 1767.29    4825 1766.04
  4874.6 1766.85  4933.8 1765.34  4949.9 1759.05  4955.6 1758.22  4957.5 1752.31
    4958 1751.81  4985.8 1752.31  4987.7 1755.63  5000.2 1756.27  5080.5 1757.32
  5148.7 1759.78  5259.3 1759.94  5308.6 1757.54  5354.3 1756.84  5704.9 1761.28
  5761.4 1763.05  5823.1 1767.34  5860.6 1768.32  5884.8 1770.16  5910.4 1774.16
  5915.7 1773.65  5941.2 1775.69  6045.7 1777.05  6184.5 1779.56  6541.4 1781.18
#Mann= 5 ,-1 , 0
  4334.6    .045       0  4535.2     .07       0  4957.5     .07       0
  4985.8     .07       0  6045.7    .045       0
Bank Sta=4957.5,4985.8
XS Rating Curve= 0 ,0
Exp/Cntr=0.3,0.1

Type RM Length L Ch R = 1 ,3884    ,394,394,394
BEGIN DESCRIPTION:
Mapping XS 241907b8
END DESCRIPTION:
XS GIS Cut Line= 4
      1510195.28      6887513.48      1510591.14      6887645.44
      1512052.95      6888016.97      1512513.95      6888273.46
#Sta/Elev= 30
  4051.5 1769.66  4111.2 1769.74  4142.8 1768.32    4499  1767.1  4668.8 1763.22
  4785.5  1762.1  4833.9 1762.82  4895.8 1760.23    4968 1760.14  4985.1 1758.05
  5009.3  1756.9  5016.6 1751.35  5017.1 1750.85  5045.8 1751.35  5050.6 1754.21
  5060.9 1755.07  5133.1 1755.46    5195 1759.37  5312.5 1758.48  5348.3 1756.01
  5442.6 1756.74  5558.1 1759.26  5710.9  1765.4  5741.9 1768.81  5757.7 1771.82
  5762.8 1770.88  5803.8 1774.56  5971.3 1777.75  6117.7 1779.63  6504.6 1781.46
#Mann= 4 ,-1 , 0
  4051.5     .07       0  5016.6     .07       0  5045.8     .07       0
  5971.3    .045       0
Bank Sta=5016.6,5045.8
XS Rating Curve= 0 ,0
Exp/Cntr=0.3,0.1

Type RM Length L Ch R = 1 ,3490    ,288,288,288
BEGIN DESCRIPTION:
Mapping XS e9b5d43e
END DESCRIPTION:
XS GIS Cut Line= 2
       1510279.7      6887890.23      1512471.21      6888400.37
#Sta/Elev= 30
  3998.2 1766.01  4260.3 1764.94  4393.8  1762.6  4506.7 1762.81  4558.1 1762.03
  4609.4 1762.95  4742.9 1757.98    4784 1757.91  4844.4 1755.78  4982.5 1755.22
  4989.3 1753.71  4995.2 1750.19  4995.7 1749.69  5024.4 1750.19  5030.4 1755.93
  5040.6 1756.73  5115.4 1756.55  5174.1 1753.47  5243.1  1760.1  5307.6 1762.36
  5369.2 1765.73  5381.2 1765.58  5418.6 1770.81  5423.8  1770.5  5451.3 1772.96
  5577.9 1774.02  5800.4  1777.6  5985.2 1779.31  6040.5 1779.08  6248.3 1781.62
#Mann= 4 ,-1 , 0
  3998.2     .07       0  4995.2     .07       0  5024.4     .07       0
  5577.9    .045       0
Bank Sta=4995.2,5024.4
XS Rating Curve= 0 ,0
Exp/Cntr=0.3,0.1

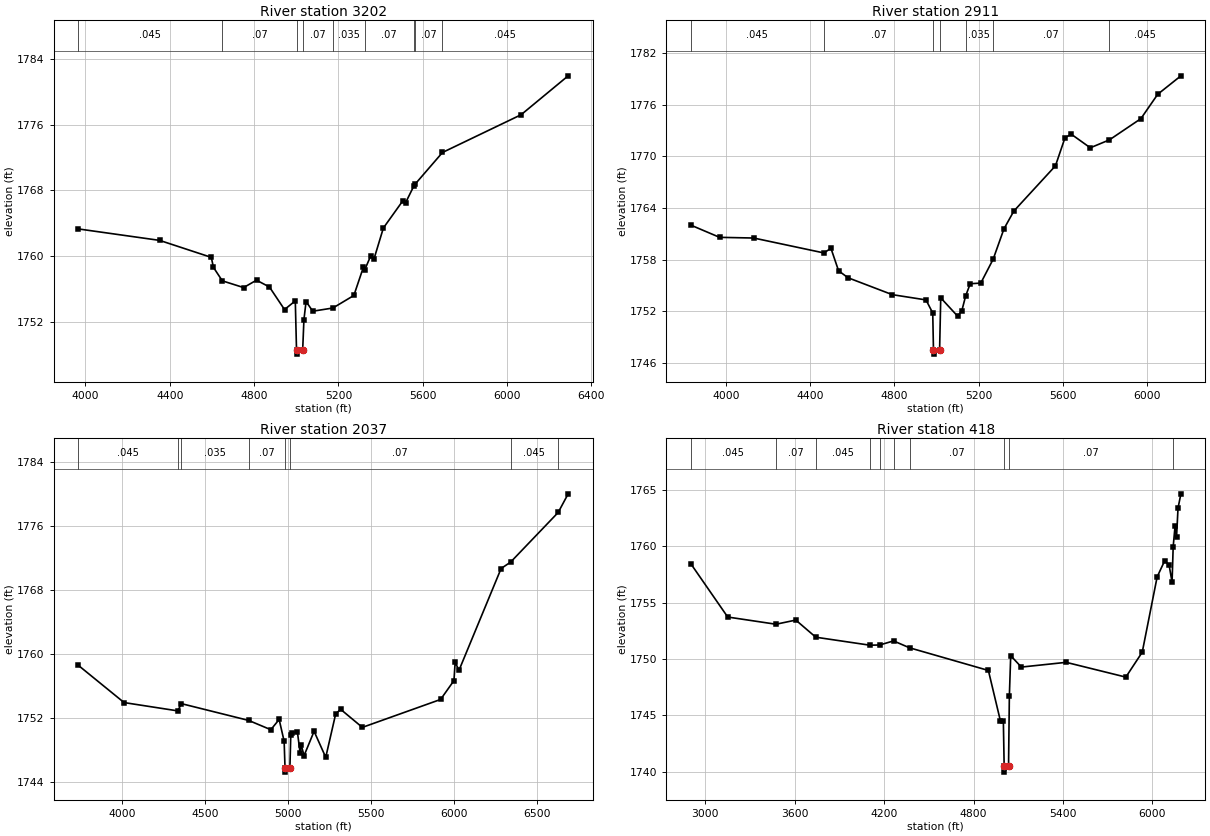
Type RM Length L Ch R = 1 ,3202    ,291,291,291
BEGIN DESCRIPTION:
Mapping XS defd52f4
END DESCRIPTION:
XS GIS Cut Line= 3
      1510196.38      6888176.69      1512170.31      6888588.15
      1512477.64      6888608.98
#Sta/Elev= 30
  3965.1 1763.29  4351.9 1761.89    4597 1759.82  4607.2  1758.6  4649.3 1756.96
  4750.2 1756.14  4811.5 1757.04  4872.8 1756.21  4944.3 1753.46  4995.4 1754.52
  5001.2 1748.53  5001.7 1748.03  5030.4 1748.53  5036.3 1752.22  5046.5 1754.44
  5078.2 1753.26  5173.8 1753.65  5273.2 1755.18  5318.2 1758.61  5324.4 1758.29
  5352.9 1759.99  5368.2 1759.59  5413.1  1763.4  5506.1 1766.74  5518.3 1766.47
  5557.7 1768.52  5562.6 1768.71  5693.4  1772.6  6066.3  1777.2  6289.5 1781.94
#Mann= 9 ,-1 , 0
  3965.1    .045       0  4649.3     .07       0  5001.2     .07       0
  5030.4     .07       0  5173.8    .035       0  5324.4     .07       0
  5557.7    .045       0  5562.6     .07       0  5693.4    .045       0
Bank Sta=5001.2,5030.4
XS Rating Curve= 0 ,0
Exp/Cntr=0.3,0.1

Type RM Length L Ch R = 1 ,2911    ,874,874,874
BEGIN DESCRIPTION:
Mapping XS 21a3094d
END DESCRIPTION:
XS GIS Cut Line= 3
      1510113.01      6888452.73       1510790.1      6888640.23
      1512415.09      6888723.56
#Sta/Elev= 30
  3831.9 1762.01  3968.9 1760.59  4131.2 1760.51  4464.7 1758.78  4498.1 1759.32
  4534.4 1756.71  4579.4  1755.9  4789.7 1753.94  4949.9 1753.33    4982 1751.81
  4985.4 1747.54  4985.9 1747.04  5014.6 1747.54    5020 1753.57  5100.1 1751.45
  5120.1 1752.06  5138.5  1753.8  5160.2 1755.21  5210.3 1755.28  5269.3 1758.06
  5320.4 1761.57  5367.5 1763.64  5565.3 1768.89  5610.8 1772.16  5640.8 1772.55
  5730.9 1770.98  5821.8  1771.9  5971.3 1774.36  6051.4 1777.19  6161.6 1779.33
#Mann= 7 ,-1 , 0
  3831.9    .045       0  4464.7     .07       0  4985.4     .07       0
  5014.6     .07       0  5138.5    .035       0  5269.3     .07       0
  5821.8    .045       0
Bank Sta=4985.4,5014.6
XS Rating Curve= 0 ,0
Exp/Cntr=0.3,0.1

Type RM Length L Ch R = 1 ,2037    ,1619,1619,1619
BEGIN DESCRIPTION:
Mapping XS 29a2bd6f
END DESCRIPTION:
XS GIS Cut Line= 4
      1510128.61      6888832.91       1510852.6      6889447.52
      1512113.02       6889562.1      1512846.53      6889452.86
#Sta/Elev= 30
  3734.1 1758.66  4011.9 1753.98  4336.4 1752.94  4356.8 1753.85  4763.4 1751.75
  4897.1 1750.59  4947.3 1751.87  4977.4 1749.15  4982.8 1745.79  4983.3 1745.29
  5012.1 1745.79  5017.6 1749.95  5027.6 1750.23  5057.7 1750.28  5074.2 1747.62
  5079.2 1748.73  5097.9 1747.36  5158.1 1750.39  5228.4 1747.14  5288.7 1752.59
  5318.8 1753.13  5449.3 1750.88  5921.3 1754.37    6002 1756.73  6009.1 1759.02
  6032.3 1758.01  6286.4 1770.73  6343.8 1771.53  6630.6 1777.73    6691 1780.06
#Mann= 8 ,-1 , 0
  3734.1    .045       0  4336.4     .07       0  4356.8    .035       0
  4763.4     .07       0  4982.8     .07       0  5012.1     .07       0
  6343.8    .045       0  6630.6    .035       0
Bank Sta=4982.8,5012.1
XS Rating Curve= 0 ,0
Exp/Cntr=0.3,0.1

Type RM Length L Ch R = 1 ,418     ,0,0,0
BEGIN DESCRIPTION:
NC Unknown Stream 72 1.0
END DESCRIPTION:
XS GIS Cut Line= 4
      1510040.11      6888916.28      1511071.35      6890280.85
       1511665.1      6890338.15      1512644.26      6890317.31
#Sta/Elev= 30
  2904.2 1758.46  3151.8 1753.73  3475.3 1753.09  3608.3 1753.46  3742.3 1751.94
  4105.5 1751.23  4170.7 1751.25  4263.8 1751.61    4371    1751  4899.6 1748.99
    4980 1744.53    5000  1744.5  5005.4 1740.47  5005.9 1739.97  5034.8 1740.47
  5040.2  1746.7  5049.3  1750.3  5120.6 1749.29  5421.1 1749.71  5821.2  1748.4
  5931.2 1750.61  6031.2 1757.29  6081.2 1758.71  6111.2 1758.36  6131.2 1756.81
  6138.7 1759.97  6151.2 1761.79  6161.2 1760.83  6171.2  1763.4  6190.5 1764.66
#Mann= 10 ,-1 , 0
  2904.2    .045       0  3475.3     .07       0  3742.3    .045       0
  4105.5    .035       0  4170.7    .045       0  4263.8    .035       0
    4371     .07       0  5005.4     .07       0  5034.8     .07       0
  6138.7    .035       0
Bank Sta=5005.4,5034.8
XS Rating Curve= 0 ,0
Exp/Cntr=0.3,0.1

Chan Stop Cuts=-1
Use User Specified Reach Order=0
Composite Channel Slope=5