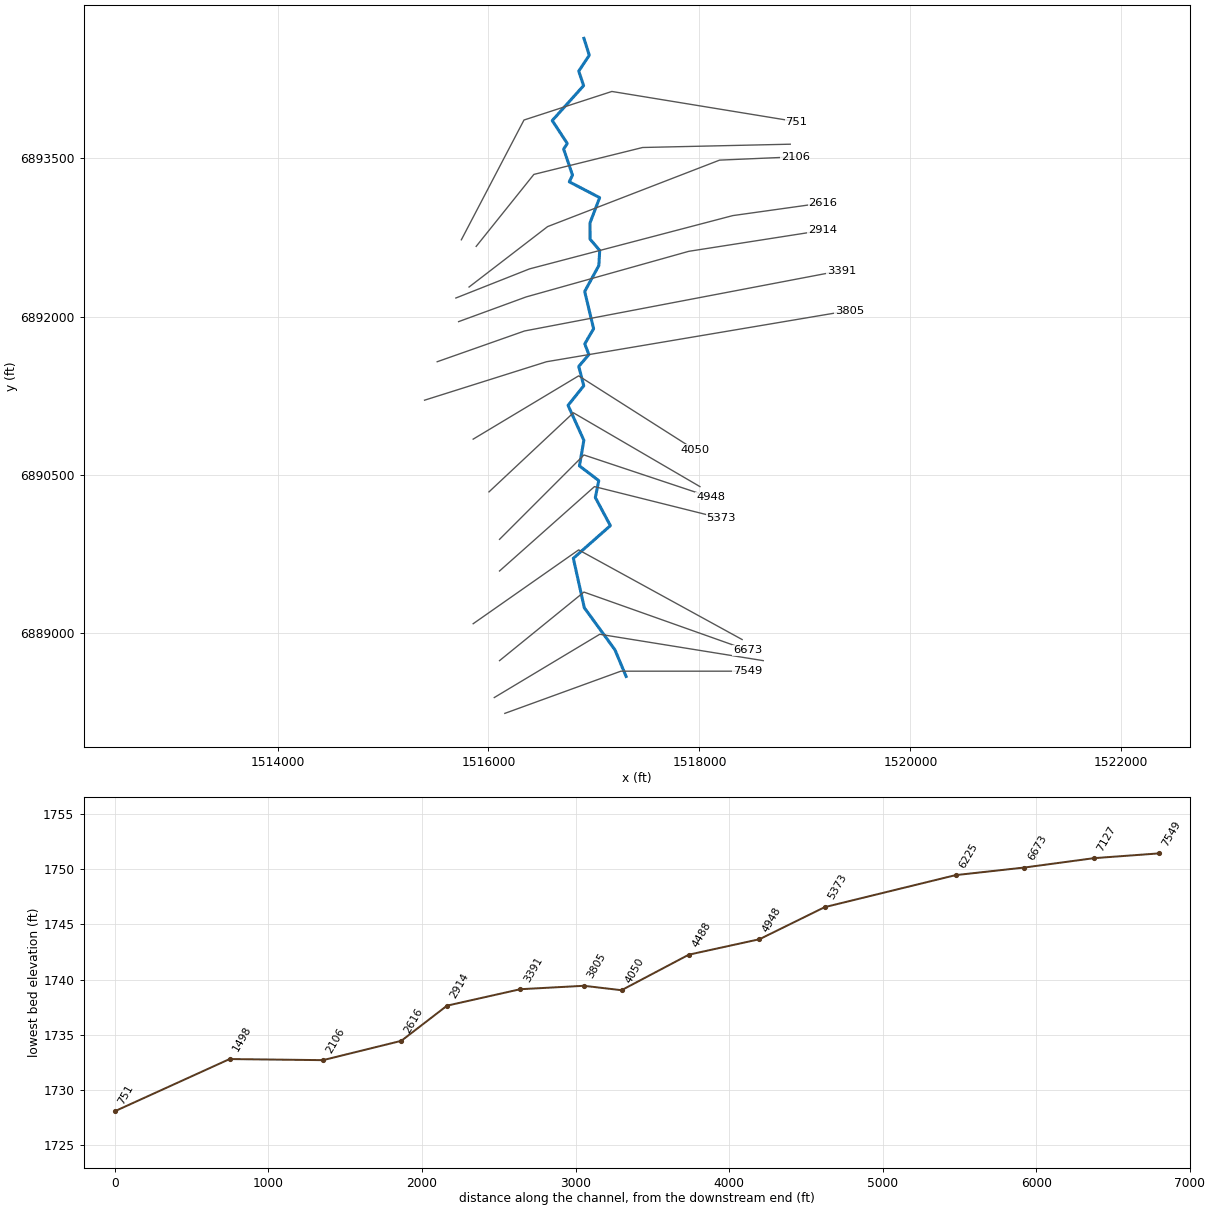
--- NC Unknown Stream 76.prj (project) ---

Proj Title=NC Unknown Stream 76 Base Level Engineering
Current Plan=p01
Default Exp/Contr=0.3,0.1
English Units
Geom File=g01
Flow File=f01
Plan File=p01
BEGIN DESCRIPTION:
NC Unknown Stream 76
END DESCRIPTION:

--- NC Unknown Stream 76.p01 (plan) ---

Plan Title=Multiple Run
Short Identifier=Multiple
Geom File=g01
Flow File=f01
Subcritical Flow
K Sum by GR= 0
Std Step Tol= 0.01
Critical Tol= 0.01
Num of Std Step Trials= 20
Max Error Tol= 0.3
Flow Tol Ratio= 0.001
Split Flow NTrial= 30
Split Flow Tol= 0.02
Split Flow Ratio= 0.02
Log Output Level= 0
Friction Slope Method= 1
Unsteady Friction Slope Method= 2
Unsteady Bridges Friction Slope Method= 1
Parabolic Critical Depth
Global Vel Dist=  1 , 1 , 1
Global Log Level= 0
CheckData=True
Encroach Param= -1, 0, 0, 0
BEGIN DESCRIPTION:
Multiple Run
END DESCRIPTION:

--- NC Unknown Stream 76.f01 (steady flow) ---

Flow Title=Multiple
Number of Profiles=7
Profile Names=10-year,25-year,50-year,1pct_min,100-year,1pct_plu,500-year
River Rch & RM= NC Unknown Strea,Reach-1,7549
     339     475     588     362     722    1440    1104
River Rch & RM= NC Unknown Strea,Reach-1,751
     342     479     593     365     728    1453    1113
Boundary for River Rch & Prof#=NC Unknown Strea,Reach-1,1
Up Type=0
Dn Type=3
Dn Slope=0.001
Boundary for River Rch & Prof#=NC Unknown Strea,Reach-1,2
Up Type=0
Dn Type=3
Dn Slope=0.001
Boundary for River Rch & Prof#=NC Unknown Strea,Reach-1,3
Up Type=0
Dn Type=3
Dn Slope=0.001
Boundary for River Rch & Prof#=NC Unknown Strea,Reach-1,4
Up Type=0
Dn Type=3
Dn Slope=0.001
Boundary for River Rch & Prof#=NC Unknown Strea,Reach-1,5
Up Type=0
Dn Type=3
Dn Slope=0.001
Boundary for River Rch & Prof#=NC Unknown Strea,Reach-1,6
Up Type=0
Dn Type=3
Dn Slope=0.001
Boundary for River Rch & Prof#=NC Unknown Strea,Reach-1,7
Up Type=0
Dn Type=3
Dn Slope=0.001

--- NC Unknown Stream 76.g01 (geometry) ---

Geom Title=Existing Conditions

River Reach=NC Unknown Strea,Reach-1
Reach XY= 30
      1517305.00      6888588.00      1517199.17      6888840.30
      1516908.75      6889239.55      1516804.64      6889708.21
      1517155.67      6890017.92      1517013.00      6890284.67
      1517045.72      6890444.68      1516862.72      6890584.34
      1516904.20      6890827.30      1516754.64      6891158.21
      1516903.38      6891344.03      1516855.94      6891527.52
      1516951.83      6891639.65      1516913.07      6891741.31
      1516996.77      6891884.77      1516912.36      6892238.08
      1517046.73      6892484.78      1517054.34      6892627.36
      1516962.83      6892734.60      1516962.56      6892888.00
      1517054.14      6893127.69      1516766.10      6893277.68
      1516796.71      6893341.21      1516712.81      6893588.10
      1516746.99      6893641.33      1516604.60      6893858.27
      1516901.86      6894189.64      1516855.61      6894327.37
      1516955.83      6894477.92      1516905.00      6894638.00

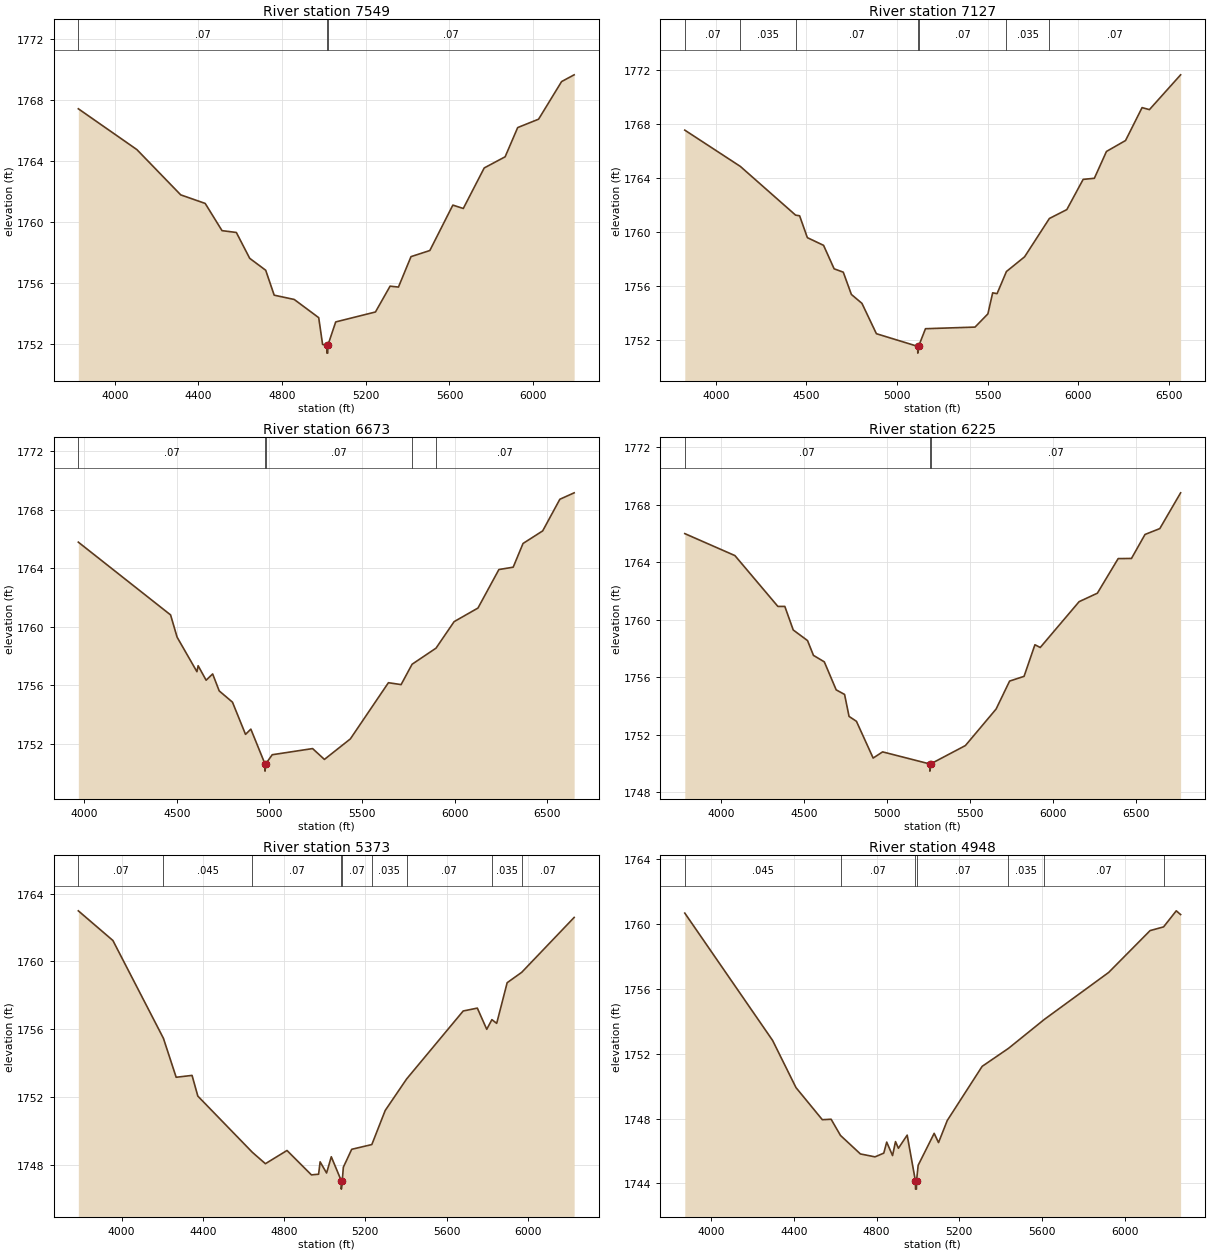
Type RM Length L Ch R = 1,7549,422,422,422
BEGIN DESCRIPTION:
NC Unknown Stream 76 15.0
END DESCRIPTION:
XS GIS Cut Line= 3
      1516155.01      6888238.00      1517255.00      6888638.00
      1518455.04      6888638.00
#Sta/Elev= 30
  3825.5 1767.41  4105.5 1764.74  4315.0 1761.78  4432.0 1761.22  4512.5 1759.44
  4581.0 1759.32  4644.8 1757.63  4721.3 1756.85  4761.9 1755.22  4857.6 1754.94
  4974.7 1753.75  4993.3 1752.00  5013.8 1751.93  5014.1 1751.43  5017.9 1751.43
  5018.2 1751.93  5056.0 1753.47  5246.0 1754.12  5316.0 1755.81  5356.0 1755.75
  5416.0 1757.74  5506.0 1758.14  5616.0 1761.11  5666.0 1760.89  5766.0 1763.54
  5866.0 1764.27  5926.0 1766.18  6026.0 1766.73  6136.0 1769.19  6196.0 1769.63
#Mann=3,-1,0
  3825.5    0.07       0  5013.8    0.07       0  5018.2    0.07       0
Bank Sta=5013.8,5018.2
Exp/Cntr=0.3,0.1

Type RM Length L Ch R = 1,7127,454,454,454
BEGIN DESCRIPTION:
NC Unknown Stream 76 14.0
END DESCRIPTION:
XS GIS Cut Line= 3
      1516055.01      6888388.01      1517055.00      6888988.00
      1518604.99      6888738.00
#Sta/Elev= 30
  3828.6 1767.53  4135.2 1764.84  4440.0 1761.23  4462.2 1761.18  4505.0 1759.56
  4594.4 1758.99  4652.7 1757.25  4703.2 1757.00  4747.9 1755.35  4806.2 1754.69
  4885.9 1752.44  5114.1 1751.50  5114.4 1751.00  5118.6 1751.50  5156.8 1752.81
  5430.3 1752.93  5501.2 1753.91  5527.6 1755.47  5551.9 1755.41  5603.6 1757.05
  5703.8 1758.14  5840.5 1760.98  5936.8 1761.64  6026.9 1763.88  6088.7 1763.96
  6155.6 1765.95  6260.9 1766.76  6352.1 1769.20  6392.6 1769.05  6564.8 1771.63
#Mann=7,-1,0
  3828.6    0.07       0  4135.2   0.035       0  4440.0    0.07       0
  5114.1    0.07       0  5118.6    0.07       0  5603.6   0.035       0
  5840.5    0.07       0
Bank Sta=5114.1,5118.6
Exp/Cntr=0.3,0.1

Type RM Length L Ch R = 1,6673,448,448,448
BEGIN DESCRIPTION:
NC Unknown Stream 76 13.0
END DESCRIPTION:
XS GIS Cut Line= 3
      1516105.00      6888738.00      1516905.00      6889388.00
      1518455.03      6888837.99
#Sta/Elev= 30
  3968.8 1765.79  4466.6 1760.82  4501.8 1759.30  4608.8 1756.94  4615.3 1757.35
  4658.4 1756.36  4693.6 1756.79  4729.0 1755.63  4800.6 1754.86  4871.0 1752.66
  4899.7 1753.02  4975.7 1750.65  4976.1 1750.15  4980.3 1750.65  5015.0 1751.27
  5233.0 1751.69  5296.7 1750.95  5436.6 1752.35  5642.0 1756.19  5710.5 1756.06
  5769.7 1757.45  5898.9 1758.55  5996.5 1760.36  6125.3 1761.29  6238.2 1763.92
  6315.3 1764.08  6368.4 1765.70  6474.5 1766.56  6567.1 1768.72  6644.3 1769.16
#Mann=5,-1,0
  3968.8    0.07       0  4975.7    0.07       0  4980.3    0.07       0
  5769.7   0.035       0  5898.9    0.07       0
Bank Sta=4975.7,4980.3
Exp/Cntr=0.3,0.1

Type RM Length L Ch R = 1,6225,852,852,852
BEGIN DESCRIPTION:
NC Unknown Stream 76 12.0
END DESCRIPTION:
XS GIS Cut Line= 3
      1515855.03      6889088.02      1516855.00      6889788.00
      1518405.01      6888937.99
#Sta/Elev= 30
  3782.3 1766.00  4084.4 1764.47  4343.3 1760.93  4385.2 1760.93  4435.8 1759.29
  4522.1 1758.55  4557.8 1757.52  4623.2 1757.07  4694.7 1755.12  4745.3 1754.80
  4772.3 1753.27  4816.8 1752.93  4917.5 1750.37  4974.6 1750.80  5258.9 1749.96
  5259.2 1749.46  5263.5 1749.96  5473.5 1751.24  5658.4 1753.78  5739.9 1755.73
  5827.1 1756.06  5892.5 1758.26  5924.7 1758.07  6158.8 1761.26  6268.9 1761.85
  6394.3 1764.26  6474.5 1764.27  6556.0 1765.94  6645.2 1766.35  6770.7 1768.84
#Mann=3,-1,0
  3782.3    0.07       0  5258.9    0.07       0  5263.5    0.07       0
Bank Sta=5258.9,5263.5
Exp/Cntr=0.3,0.1

Type RM Length L Ch R = 1,5373,425,425,425
BEGIN DESCRIPTION:
NC Unknown Stream 76 11.0
END DESCRIPTION:
XS GIS Cut Line= 3
      1516104.98      6889587.98      1517005.00      6890388.00
      1518204.98      6890088.01
#Sta/Elev= 30
  3787.2 1762.98  3957.4 1761.23  4206.1 1755.46  4268.9 1753.16  4347.1 1753.27
  4375.5 1752.05  4644.2 1748.73  4708.3 1748.06  4814.5 1748.84  4934.9 1747.40
  4970.1 1747.44  4977.6 1748.17  5009.4 1747.51  5032.6 1748.47  5081.6 1747.06
  5082.0 1746.56  5086.7 1747.06  5091.9 1747.85  5133.1 1748.91  5232.2 1749.19
  5298.0 1751.20  5403.5 1753.06  5682.0 1757.07  5751.6 1757.24  5798.0 1755.99
  5823.3 1756.56  5846.9 1756.34  5898.5 1758.74  5970.0 1759.35  6228.3 1762.59
#Mann=9,-1,0
  3787.2    0.07       0  4206.1   0.045       0  4644.2    0.07       0
  5081.6    0.07       0  5086.7    0.07       0  5232.2   0.035       0
  5403.5    0.07       0  5823.3   0.035       0  5970.0    0.07       0
Bank Sta=5081.6,5086.7
Exp/Cntr=0.3,0.1

Type RM Length L Ch R = 1,4948,460,460,460
BEGIN DESCRIPTION:
NC Unknown Stream 76 10.0
END DESCRIPTION:
XS GIS Cut Line= 3
      1516104.98      6889887.98      1516905.00      6890688.00
      1518104.99      6890288.00
#Sta/Elev= 30
  3873.0 1760.67  4297.3 1752.82  4410.4 1749.91  4537.7 1747.93  4580.1 1747.96
  4625.5 1746.96  4721.6 1745.82  4792.3 1745.64  4834.7 1745.87  4848.8 1746.55
  4877.1 1745.72  4891.3 1746.58  4905.4 1746.17  4947.8 1746.98  4987.7 1744.15
  4988.1 1743.65  4992.4 1743.65  4992.8 1744.15  5000.9 1745.12  5078.2 1747.09
  5099.3 1746.52  5141.4 1747.88  5310.1 1751.22  5437.4 1752.33  5610.2 1754.11
  5921.5 1757.01  6121.7 1759.59  6187.0 1759.82  6248.2 1760.81  6269.3 1760.58
#Mann=7,-1,0
  3873.0   0.045       0  4625.5    0.07       0  4987.7    0.07       0
  4992.8    0.07       0  5437.4   0.035       0  5610.2    0.07       0
  6187.0   0.035       0
Bank Sta=4987.7,4992.8
Exp/Cntr=0.3,0.1

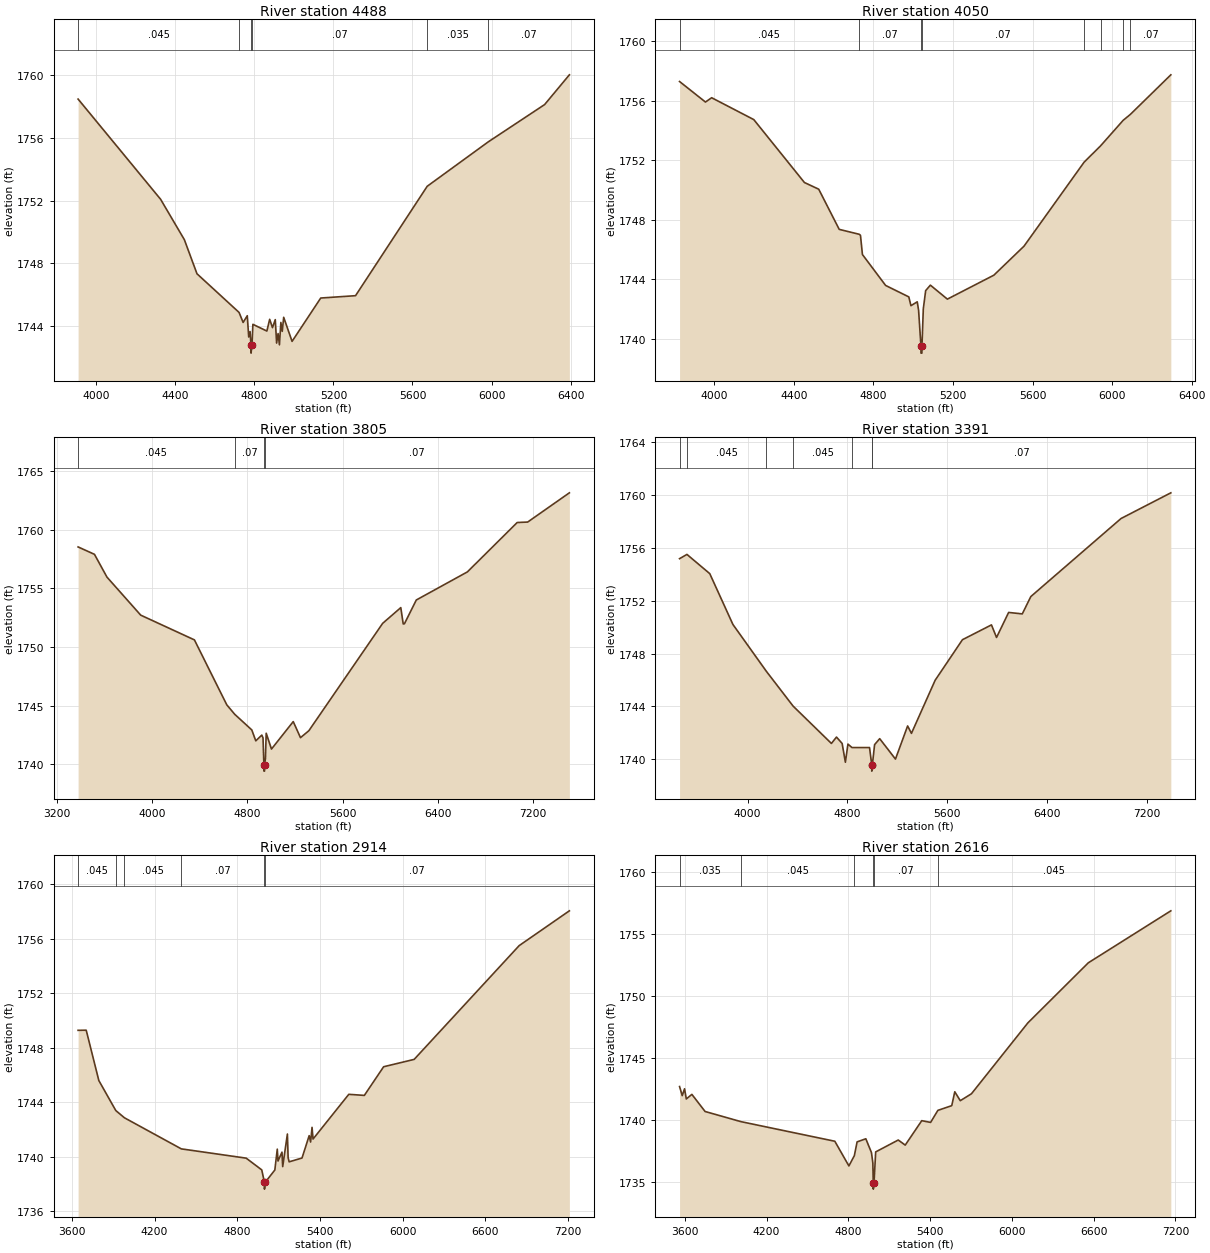
Type RM Length L Ch R = 1,4488,438,438,438
BEGIN DESCRIPTION:
NC Unknown Stream 76 9.0
END DESCRIPTION:
XS GIS Cut Line= 3
      1516004.99      6890337.99      1516805.00      6891088.00
      1518004.97      6890388.02
#Sta/Elev= 30
  3908.0 1758.48  4325.4 1752.08  4445.6 1749.50  4509.5 1747.32  4722.5 1744.85
  4743.0 1744.21  4764.0 1744.64  4771.3 1743.28  4778.2 1743.63  4782.7 1742.75
  4783.1 1742.25  4787.8 1742.75  4792.4 1744.09  4863.2 1743.66  4877.3 1744.41
  4891.5 1743.88  4905.7 1744.39  4912.5 1742.89  4919.8 1743.50  4926.7 1742.78
  4934.0 1744.21  4940.9 1743.64  4948.2 1744.54  4990.7 1743.00  5135.7 1745.77
  5311.8 1745.92  5674.5 1752.91  5983.7 1755.75  6268.6 1758.13  6393.8 1760.03
#Mann=6,-1,0
  3908.0   0.045       0  4722.5    0.07       0  4782.7    0.07       0
  4787.8    0.07       0  5674.5   0.035       0  5983.7    0.07       0
Bank Sta=4782.7,4787.8
Exp/Cntr=0.3,0.1

Type RM Length L Ch R = 1,4050,245,245,245
BEGIN DESCRIPTION:
NC Unknown Stream 76 8.0
END DESCRIPTION:
XS GIS Cut Line= 3
      1515854.99      6890838.00      1516855.00      6891438.00
      1517954.97      6890738.02
#Sta/Elev= 30
  3825.3 1757.29  3955.5 1755.91  3986.6 1756.20  4198.5 1754.73  4453.1 1750.50
  4525.0 1750.05  4628.0 1747.35  4728.7 1747.02  4734.9 1746.95  4744.7 1745.66
  4861.3 1743.58  4977.9 1742.81  4988.6 1742.22  5020.3 1742.48  5027.1 1741.91
  5038.8 1739.53  5039.2 1739.03  5043.7 1739.03  5044.1 1739.53  5050.8 1742.01
  5062.6 1743.23  5086.3 1743.60  5171.8 1742.66  5405.5 1744.27  5557.1 1746.22
  5859.4 1751.87  5941.7 1752.96  6055.6 1754.68  6091.8 1755.08  6295.3 1757.74
#Mann=8,-1,0
  3825.3   0.045       0  4728.7    0.07       0  5038.8    0.07       0
  5044.1    0.07       0  5859.4   0.035       0  5941.7    0.07       0
  6055.6   0.035       0  6091.8    0.07       0
Bank Sta=5038.8,5044.1
Exp/Cntr=0.3,0.1

Type RM Length L Ch R = 1,3805,414,414,414
BEGIN DESCRIPTION:
Mapping XS 9d8a28ff
END DESCRIPTION:
XS GIS Cut Line= 3
      1515394.01      6891207.25      1516550.28      6891571.84
      1519420.00      6892056.20
#Sta/Elev= 30
  3380.4 1758.53  3517.7 1757.90  3622.6 1755.96  3905.7 1752.72  4356.6 1750.61
  4628.0 1745.08  4694.9 1744.27  4838.0 1742.94  4871.4 1742.01  4922.1 1742.50
  4932.2 1742.26  4939.7 1739.93  4940.1 1739.43  4944.7 1739.43  4945.1 1739.93
  4952.5 1740.51  4958.9 1742.66  5003.2 1741.31  5185.8 1743.65  5246.6 1742.28
  5316.7 1742.87  5936.2 1752.02  6088.4 1753.36  6108.7 1751.97  6118.8 1751.98
  6218.6 1754.01  6646.9 1756.40  7065.1 1760.61  7153.2 1760.65  7503.1 1763.14
#Mann=4,-1,0
  3380.4   0.045       0  4694.9    0.07       0  4939.7    0.07       0
  4945.1    0.07       0
Bank Sta=4939.7,4945.1
Exp/Cntr=0.3,0.1

Type RM Length L Ch R = 1,3391,477,477,477
BEGIN DESCRIPTION:
Mapping XS e7de9dec
END DESCRIPTION:
XS GIS Cut Line= 3
      1515513.84      6891571.85      1516341.95      6891863.51
      1519347.16      6892436.42
#Sta/Elev= 30
  3454.8 1755.16  3514.0 1755.48  3696.8 1754.03  3882.6 1750.19  4150.1 1746.66
  4364.7 1744.03  4671.8 1741.21  4712.5 1741.69  4757.8 1741.21  4783.8 1739.79
  4804.2 1741.16  4836.4 1740.90  4977.2 1740.90  4994.8 1739.62  4995.3 1739.12
  5000.3 1739.62  5017.9 1741.12  5058.7 1741.57  5185.2 1740.03  5282.6 1742.53
  5313.2 1741.97  5503.2 1745.98  5721.9 1749.04  5954.5 1750.16  5995.2 1749.21
  6092.1 1751.10  6201.5 1750.99  6270.1 1752.30  6992.9 1758.19  7392.1 1760.13
#Mann=7,-1,0
  3454.8   0.035       0  3514.0   0.045       0  4150.1    0.07       0
  4364.7   0.045       0  4836.4    0.07       0  4994.8    0.07       0
  5000.3    0.07       0
Bank Sta=4994.8,5000.3
Exp/Cntr=0.3,0.1

Type RM Length L Ch R = 1,2914,298,298,298
BEGIN DESCRIPTION:
Mapping XS 5c73626f
END DESCRIPTION:
XS GIS Cut Line= 4
      1515716.91      6891952.04      1516357.57      6892186.42
      1517899.24      6892618.72      1519164.84      6892816.63
#Sta/Elev= 30
  3645.2 1749.27  3704.0 1749.28  3795.6 1745.59  3918.7 1743.39  3981.3 1742.86
  4394.1 1740.58  4864.8 1739.90  4977.6 1739.04  4997.0 1738.13  4997.4 1737.63
  5002.5 1738.13  5072.5 1739.03  5090.3 1740.56  5095.5 1739.69  5124.4 1740.34
  5129.6 1739.28  5163.7 1741.67  5168.9 1739.94  5176.3 1739.63  5269.8 1739.91
  5321.7 1741.55  5332.1 1741.08  5342.5 1742.16  5349.7 1741.30  5609.2 1744.58
  5721.9 1744.50  5861.8 1746.60  6083.4 1747.14  6845.3 1755.48  7209.5 1758.03
#Mann=6,-1,0
  3645.2   0.045       0  3918.7   0.035       0  3981.3   0.045       0
  4394.1    0.07       0  4997.0    0.07       0  5002.5    0.07       0
Bank Sta=4997,5002.5
Exp/Cntr=0.3,0.1

Type RM Length L Ch R = 1,2616,510,510,510
BEGIN DESCRIPTION:
Mapping XS 8b1773e7
END DESCRIPTION:
XS GIS Cut Line= 4
      1515690.95      6892176.02      1516388.82      6892452.05
      1518315.91      6892957.26      1519170.06      6893077.05
#Sta/Elev= 30
  3561.4 1742.71  3581.1 1741.98  3598.0 1742.53  3610.9 1741.71  3651.8 1742.08
  3748.7 1740.70  4012.3 1739.88  4700.8 1738.30  4804.1 1736.31  4844.1 1737.14
  4864.3 1738.25  4928.2 1738.50  4969.6 1737.39  4979.9 1736.54  4982.8 1734.94
  4983.2 1734.44  4988.3 1734.94  5000.6 1737.44  5166.0 1738.40  5217.5 1737.99
  5338.7 1739.96  5403.7 1739.82  5457.0 1740.79  5558.8 1741.17  5581.1 1742.29
  5621.5 1741.57  5703.5 1742.13  6117.1 1747.84  6561.1 1752.69  7166.6 1756.88
#Mann=6,-1,0
  3561.4   0.035       0  4012.3   0.045       0  4844.1    0.07       0
  4982.8    0.07       0  4988.3    0.07       0  5457.0   0.045       0
Bank Sta=4982.8,4988.3
Exp/Cntr=0.3,0.1

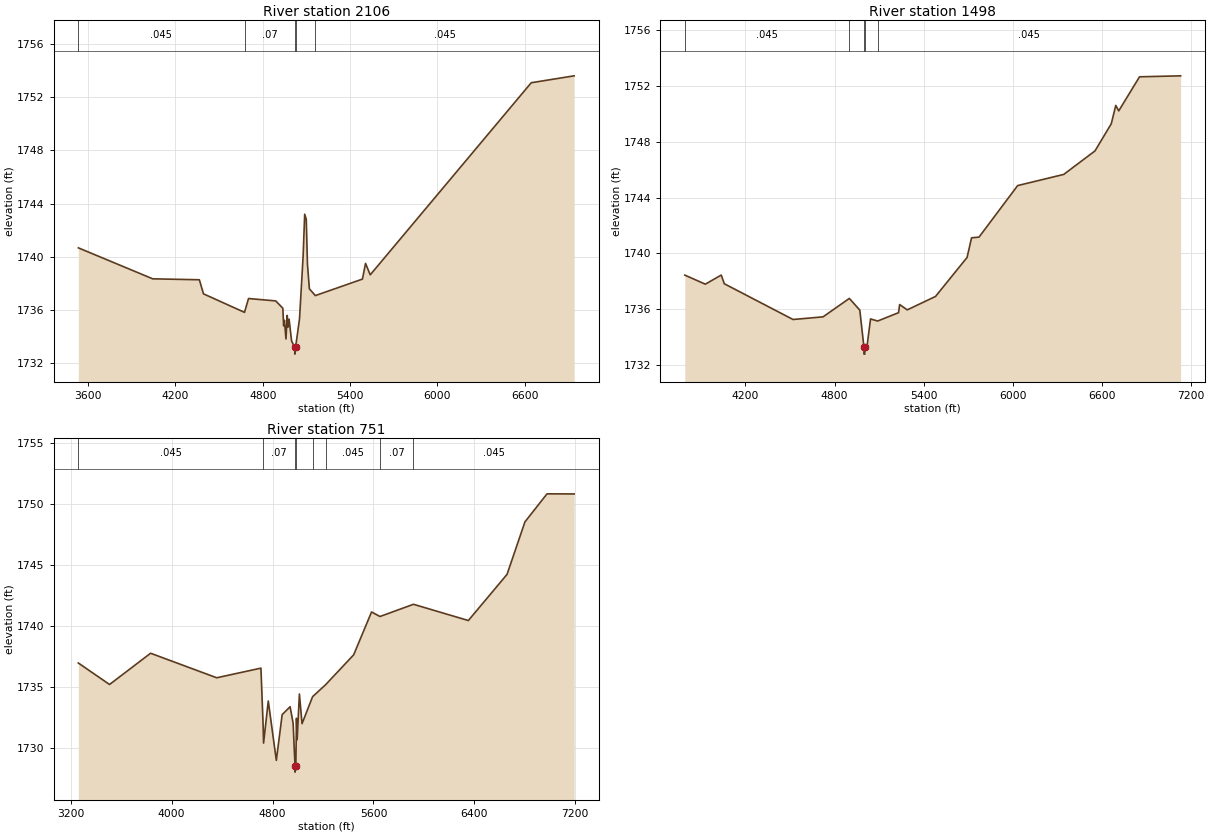
Type RM Length L Ch R = 1,2106,608,608,608
BEGIN DESCRIPTION:
Mapping XS a885e536
END DESCRIPTION:
XS GIS Cut Line= 4
      1515815.94      6892280.20      1516560.70      6892853.09
      1518190.91      6893483.30      1518909.64      6893514.55
#Sta/Elev= 30
  3533.0 1740.68  4044.4 1738.35  4364.5 1738.28  4393.2 1737.22  4674.9 1735.83
  4702.4 1736.87  4889.2 1736.69  4938.2 1736.14  4943.7 1734.81  4949.1 1735.23
  4959.7 1733.83  4968.3 1735.60  4973.7 1734.72  4981.1 1735.32  4998.2 1733.68
  5020.0 1733.19  5020.5 1732.69  5025.6 1733.19  5052.8 1735.35  5077.4 1740.02
  5088.3 1743.21  5099.1 1742.82  5107.3 1739.46  5120.5 1737.60  5161.4 1737.09
  5485.0 1738.33  5506.5 1739.51  5538.6 1738.65  6644.9 1753.09  6939.8 1753.61
#Mann=5,-1,0
  3533.0   0.045       0  4674.9    0.07       0  5020.0    0.07       0
  5025.6    0.07       0  5161.4   0.045       0
Bank Sta=5020,5025.6
Exp/Cntr=0.3,0.1

Type RM Length L Ch R = 1,1498,747,747,747
BEGIN DESCRIPTION:
Mapping XS 0fca8652
END DESCRIPTION:
XS GIS Cut Line= 4
      1515883.59      6892665.56      1516430.49      6893347.88
      1517461.74      6893603.09      1518861.38      6893634.31
#Sta/Elev= 30
  3791.6 1738.45  3929.5 1737.80  4036.8 1738.45  4057.6 1737.83  4520.1 1735.27
  4722.2 1735.46  4899.1 1736.78  4969.4 1735.94  4997.1 1733.29  4997.6 1732.79
  5003.0 1732.79  5003.5 1733.29  5018.1 1733.37  5041.6 1735.31  5089.6 1735.16
  5230.3 1735.76  5237.3 1736.34  5288.8 1735.96  5478.8 1736.92  5691.1 1739.71
  5721.5 1741.12  5771.7 1741.17  6031.7 1744.86  6341.8 1745.66  6551.9 1747.34
  6661.9 1749.29  6691.9 1750.60  6711.9 1750.21  6851.9 1752.65  7128.4 1752.72
#Mann=5,-1,0
  3791.6   0.045       0  4899.1    0.07       0  4997.1    0.07       0
  5003.5    0.07       0  5089.6   0.045       0
Bank Sta=4997.1,5003.5
Exp/Cntr=0.3,0.1

Type RM Length L Ch R = 1,751,0,0,0
BEGIN DESCRIPTION:
NC Unknown Stream 76 1.0
END DESCRIPTION:
XS GIS Cut Line= 4
      1515743.00      6892728.11      1516336.74      6893863.51
      1517170.07      6894134.34      1518920.07      6893847.88
#Sta/Elev= 30
  3260.1 1737.00  3507.6 1735.24  3833.1 1737.80  4357.2 1735.79  4707.8 1736.58
  4725.0 1731.92  4728.7 1730.44  4765.9 1733.89  4829.8 1729.02  4876.0 1732.77
  4939.1 1733.42  4962.9 1732.06  4977.9 1728.56  4978.4 1728.06  4984.5 1728.56
  4989.5 1732.47  4994.8 1730.71  5012.7 1734.46  5033.7 1732.03  5117.2 1734.24
  5220.3 1735.22  5442.9 1737.67  5584.7 1741.18  5651.6 1740.81  5917.0 1741.81
  6352.1 1740.48  6658.8 1744.26  6800.7 1748.56  6975.8 1750.86  7190.9 1750.85
#Mann=8,-1,0
  3260.1   0.045       0  4725.0    0.07       0  4977.9    0.07       0
  4984.5    0.07       0  5117.2   0.035       0  5220.3   0.045       0
  5651.6    0.07       0  5917.0   0.045       0
Bank Sta=4977.9,4984.5
Exp/Cntr=0.3,0.1

Chan Stop Cuts=-1