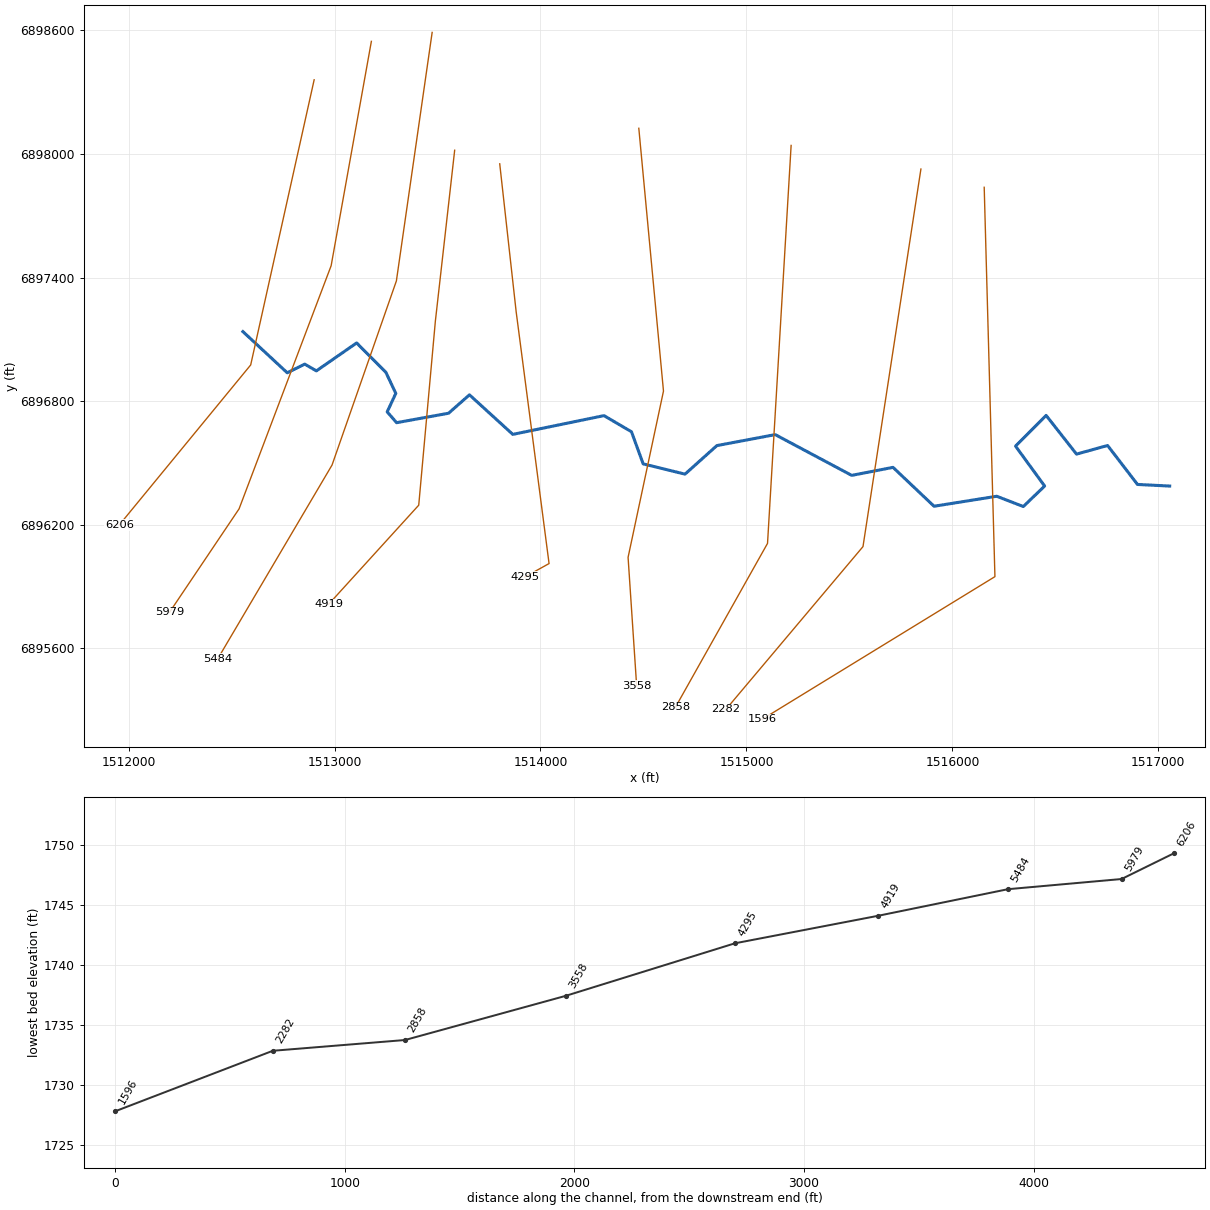
--- NC Unknown Stream 77.prj (project) ---

Proj Title=NC Unknown Stream 77 Base Level Engineering
Current Plan=p01
Default Exp/Contr=0.3,0.1
English Units
Geom File=g01
Flow File=f01
Plan File=p01
BEGIN DESCRIPTION:
NC Unknown Stream 77
END DESCRIPTION:

--- NC Unknown Stream 77.p01 (plan) ---

Plan Title=Multiple Run
Short Identifier=Multiple
Geom File=g01
Flow File=f01
Subcritical Flow
K Sum by GR= 0
Std Step Tol= 0.01
Critical Tol= 0.01
Num of Std Step Trials= 20
Max Error Tol= 0.3
Flow Tol Ratio= 0.001
Split Flow NTrial= 30
Split Flow Tol= 0.02
Split Flow Ratio= 0.02
Log Output Level= 0
Friction Slope Method= 1
Unsteady Friction Slope Method= 2
Unsteady Bridges Friction Slope Method= 1
Parabolic Critical Depth
Global Vel Dist=  1 , 1 , 1
Global Log Level= 0
CheckData=True
Encroach Param= -1, 0, 0, 0
BEGIN DESCRIPTION:
Multiple Run
END DESCRIPTION:

--- NC Unknown Stream 77.f01 (steady flow) ---

Flow Title=Multiple
Number of Profiles=7
Profile Names=10-year,25-year,50-year,1pct_min,100-year,1pct_plu,500-year
River Rch & RM= NC Unknown Strea,Reach-1,6206
     223     306     373     226     452     902     673
Boundary for River Rch & Prof#=NC Unknown Strea,Reach-1,1
Up Type=0
Dn Type=3
Dn Slope=0.001
Boundary for River Rch & Prof#=NC Unknown Strea,Reach-1,2
Up Type=0
Dn Type=3
Dn Slope=0.001
Boundary for River Rch & Prof#=NC Unknown Strea,Reach-1,3
Up Type=0
Dn Type=3
Dn Slope=0.001
Boundary for River Rch & Prof#=NC Unknown Strea,Reach-1,4
Up Type=0
Dn Type=3
Dn Slope=0.001
Boundary for River Rch & Prof#=NC Unknown Strea,Reach-1,5
Up Type=0
Dn Type=3
Dn Slope=0.001
Boundary for River Rch & Prof#=NC Unknown Strea,Reach-1,6
Up Type=0
Dn Type=3
Dn Slope=0.001
Boundary for River Rch & Prof#=NC Unknown Strea,Reach-1,7
Up Type=0
Dn Type=3
Dn Slope=0.001

--- NC Unknown Stream 77.g01 (geometry) ---

Geom Title=Existing Conditions

River Reach=NC Unknown Strea,Reach-1
Reach XY= 30
      1512555.00      6897138.00      1512770.36      6896938.01
      1512855.09      6896980.16      1512911.67      6896947.30
      1513107.29      6897082.94      1513249.19      6896940.29
      1513297.44      6896838.00      1513255.64      6896748.31
      1513301.26      6896695.69      1513553.54      6896741.56
      1513655.01      6896830.92      1513865.48      6896638.93
      1514308.32      6896729.96      1514441.74      6896651.66
      1514498.48      6896495.68      1514701.79      6896445.87
      1514856.47      6896584.46      1515139.78      6896637.75
      1515511.13      6896439.86      1515711.67      6896478.71
      1515910.89      6896289.96      1516215.19      6896338.45
      1516344.39      6896288.60      1516447.93      6896387.99
      1516306.58      6896581.95      1516455.21      6896731.02
      1516602.69      6896543.09      1516753.58      6896584.96
      1516898.78      6896395.78      1517055.00      6896388.00

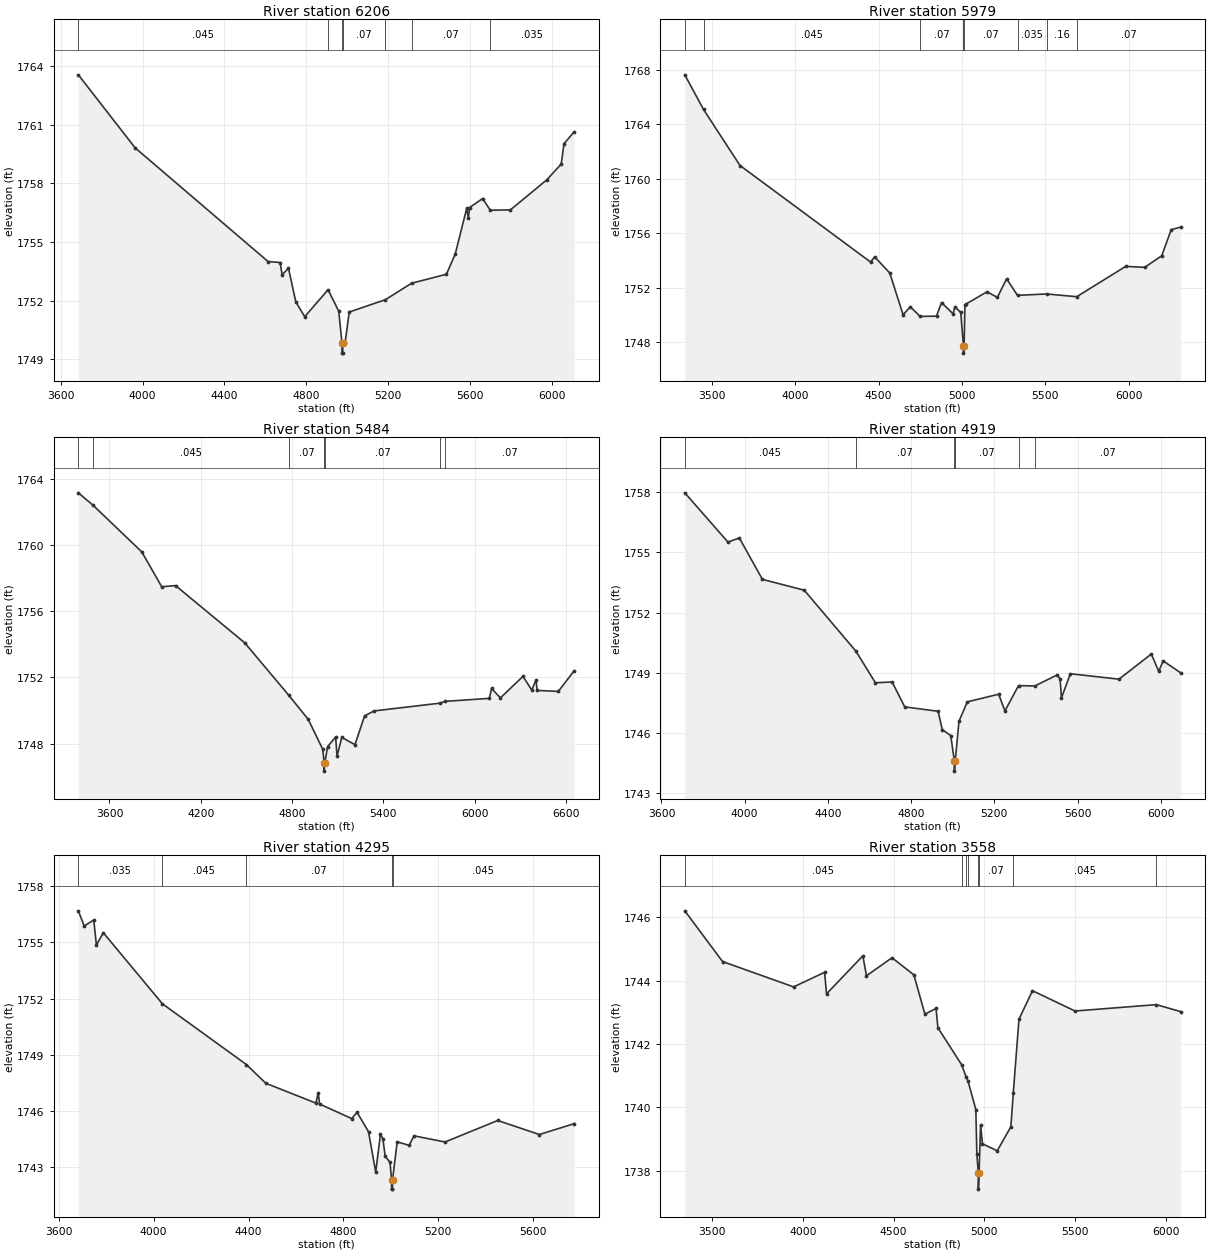
Type RM Length L Ch R = 1,6206,227,227,227
BEGIN DESCRIPTION:
NC Unknown Stream 77 3.0
END DESCRIPTION:
XS GIS Cut Line= 3
      1512900.98      6898360.67      1512592.82      6896976.09
      1511954.78      6896199.16
#Sta/Elev= 30
  3685.5 1763.54  3963.0 1759.81  4613.0 1754.00  4671.7 1753.95  4682.0 1753.32
  4712.7 1753.66  4748.6 1751.94  4792.1 1751.18  4906.2 1752.56  4958.6 1751.46
  4974.4 1749.82  4974.6 1749.32  4978.1 1749.32  4978.4 1749.82  4989.3 1749.82
  5009.8 1751.42  5186.5 1752.05  5314.3 1752.89  5484.9 1753.35  5527.9 1754.38
  5583.9 1756.71  5591.8 1756.23  5598.3 1756.76  5662.1 1757.22  5699.4 1756.62
  5797.7 1756.64  5975.0 1758.17  6046.1 1758.98  6059.7 1760.02  6109.3 1760.63
#Mann=7,-1,0
  3685.5   0.045       0  4906.2    0.07       0  4974.4    0.07       0
  4978.4    0.07       0  5186.5   0.035       0  5314.3    0.07       0
  5699.4   0.035       0
Bank Sta=4974.4,4978.4
Exp/Cntr=0.3,0.1

Type RM Length L Ch R = 1,5979,495,495,495
BEGIN DESCRIPTION:
Mapping XS 62267282
END DESCRIPTION:
XS GIS Cut Line= 4
      1513178.76      6898547.29      1512983.44      6897457.87
      1512536.39      6896277.31      1512198.95      6895775.47
#Sta/Elev= 30
  3337.2 1767.65  3449.7 1765.10  3668.4 1760.98  4451.5 1753.88  4475.9 1754.26
  4566.7 1753.07  4646.5 1750.00  4689.8 1750.59  4748.6 1749.88  4846.9 1749.90
  4877.1 1750.90  4946.4 1750.07  4956.9 1750.59  4992.4 1750.17  5008.6 1747.68
  5008.8 1747.18  5012.6 1747.68  5017.2 1750.69  5022.5 1750.78  5149.6 1751.69
  5212.3 1751.28  5267.2 1752.65  5332.7 1751.43  5508.4 1751.53  5688.0 1751.33
  5981.6 1753.56  6095.7 1753.49  6197.6 1754.34  6254.6 1756.26  6311.1 1756.45
#Mann=8,-1,0
  3337.2   0.035       0  3449.7   0.045       0  4748.6    0.07       0
  5008.6    0.07       0  5012.6    0.07       0  5332.7   0.035       0
  5508.4    0.16       0  5688.0    0.07       0
Bank Sta=5008.6,5012.6
Exp/Cntr=0.3,0.1

Type RM Length L Ch R = 1,5484,565,565,565
BEGIN DESCRIPTION:
Mapping XS 44d722ca
END DESCRIPTION:
XS GIS Cut Line= 4
      1513473.90      6898590.72      1513300.28      6897384.08
      1512987.78      6896489.98      1512432.22      6895548.13
#Sta/Elev= 30
  3395.4 1763.16  3493.2 1762.40  3812.4 1759.59  3943.7 1757.48  4034.6 1757.55
  4489.3 1754.09  4777.7 1750.93  4906.9 1749.46  5002.3 1747.65  5011.7 1746.83
  5011.9 1746.33  5015.8 1746.83  5034.0 1747.81  5087.0 1748.39  5096.3 1747.23
  5127.3 1748.37  5214.1 1747.93  5277.2 1749.67  5339.3 1749.97  5772.7 1750.44
  5808.0 1750.55  6098.0 1750.73  6111.9 1751.33  6170.4 1750.76  6318.6 1752.06
  6376.6 1751.23  6404.6 1751.85  6411.4 1751.21  6550.8 1751.15  6655.1 1752.40
#Mann=7,-1,0
  3395.4   0.035       0  3493.2   0.045       0  4777.7    0.07       0
  5011.7    0.07       0  5015.8    0.07       0  5772.7    0.16       0
  5808.0    0.07       0
Bank Sta=5011.7,5015.8
Exp/Cntr=0.3,0.1

Type RM Length L Ch R = 1,4919,624,624,624
BEGIN DESCRIPTION:
Mapping XS 1b2d4259
END DESCRIPTION:
XS GIS Cut Line= 4
      1513583.27      6898018.62      1513489.52      6897188.77
      1513408.75      6896295.11      1512970.86      6895813.57
#Sta/Elev= 30
  3712.3 1757.97  3919.4 1755.52  3974.6 1755.72  4085.3 1753.66  4286.5 1753.12
  4535.1 1750.08  4628.5 1748.51  4708.9 1748.55  4769.2 1747.31  4929.8 1747.09
  4949.8 1746.18  4990.7 1745.88  5008.0 1744.61  5008.3 1744.11  5012.1 1744.61
  5030.2 1746.59  5070.3 1747.56  5220.9 1747.94  5251.1 1747.11  5316.6 1748.37
  5394.8 1748.35  5502.0 1748.90  5516.2 1748.71  5522.9 1747.76  5565.5 1748.96
  5799.3 1748.69  5954.7 1749.94  5990.5 1749.08  6011.5 1749.60  6095.6 1749.01
#Mann=6,-1,0
  3712.3   0.045       0  4535.1    0.07       0  5008.0    0.07       0
  5012.1    0.07       0  5316.6   0.045       0  5394.8    0.07       0
Bank Sta=5008,5012.1
Exp/Cntr=0.3,0.1

Type RM Length L Ch R = 1,4295,737,737,737
BEGIN DESCRIPTION:
Mapping XS f9e46efe
END DESCRIPTION:
XS GIS Cut Line= 4
      1513802.02      6897952.66      1513881.88      6897233.91
      1514041.60      6896011.68      1513924.00      6895946.41
#Sta/Elev= 30
  3682.6 1756.69  3707.4 1755.88  3747.7 1756.20  3758.8 1754.86  3787.9 1755.52
  4037.0 1751.72  4391.2 1748.47  4472.9 1747.47  4684.0 1746.41  4694.1 1746.95
  4699.6 1746.36  4835.3 1745.58  4857.4 1745.92  4905.9 1744.88  4936.3 1742.72
  4956.3 1744.75  4966.4 1744.51  4976.5 1743.56  4996.7 1743.24  5003.1 1742.31
  5003.4 1741.81  5007.0 1741.81  5007.3 1742.31  5026.9 1744.34  5077.3 1744.15
  5097.5 1744.66  5228.6 1744.33  5450.5 1745.48  5626.5 1744.73  5772.9 1745.31
#Mann=5,-1,0
  3682.6   0.035       0  4037.0   0.045       0  4391.2    0.07       0
  5003.1    0.07       0  5007.3   0.045       0
Bank Sta=5003.1,5007.3
Exp/Cntr=0.3,0.1

Type RM Length L Ch R = 1,3558,700,700,700
BEGIN DESCRIPTION:
Mapping XS 6d75104f
END DESCRIPTION:
XS GIS Cut Line= 4
      1514477.37      6898125.21      1514597.16      6896849.18
      1514425.28      6896041.89      1514466.95      6895416.91
#Sta/Elev= 30
  3349.4 1746.20  3557.5 1744.60  3949.2 1743.80  4120.0 1744.26  4130.8 1743.58
  4330.9 1744.78  4351.0 1744.15  4491.6 1744.72  4612.1 1744.18  4673.1 1742.94
  4734.5 1743.12  4744.7 1742.51  4875.0 1741.35  4899.8 1740.97  4910.7 1740.83
  4953.9 1739.93  4959.4 1738.54  4967.5 1737.92  4967.8 1737.42  4971.7 1737.92
  4979.9 1739.45  4990.1 1738.85  5071.9 1738.63  5147.1 1739.39  5160.3 1740.45
  5191.6 1742.78  5266.1 1743.68  5500.4 1743.04  5949.0 1743.24  6082.8 1743.02
#Mann=8,-1,0
  3349.4   0.045       0  4875.0    0.07       0  4899.8   0.045       0
  4910.7    0.07       0  4967.5    0.07       0  4971.7    0.07       0
  5160.3   0.045       0  5949.0   0.035       0
Bank Sta=4967.5,4971.7
Exp/Cntr=0.3,0.1

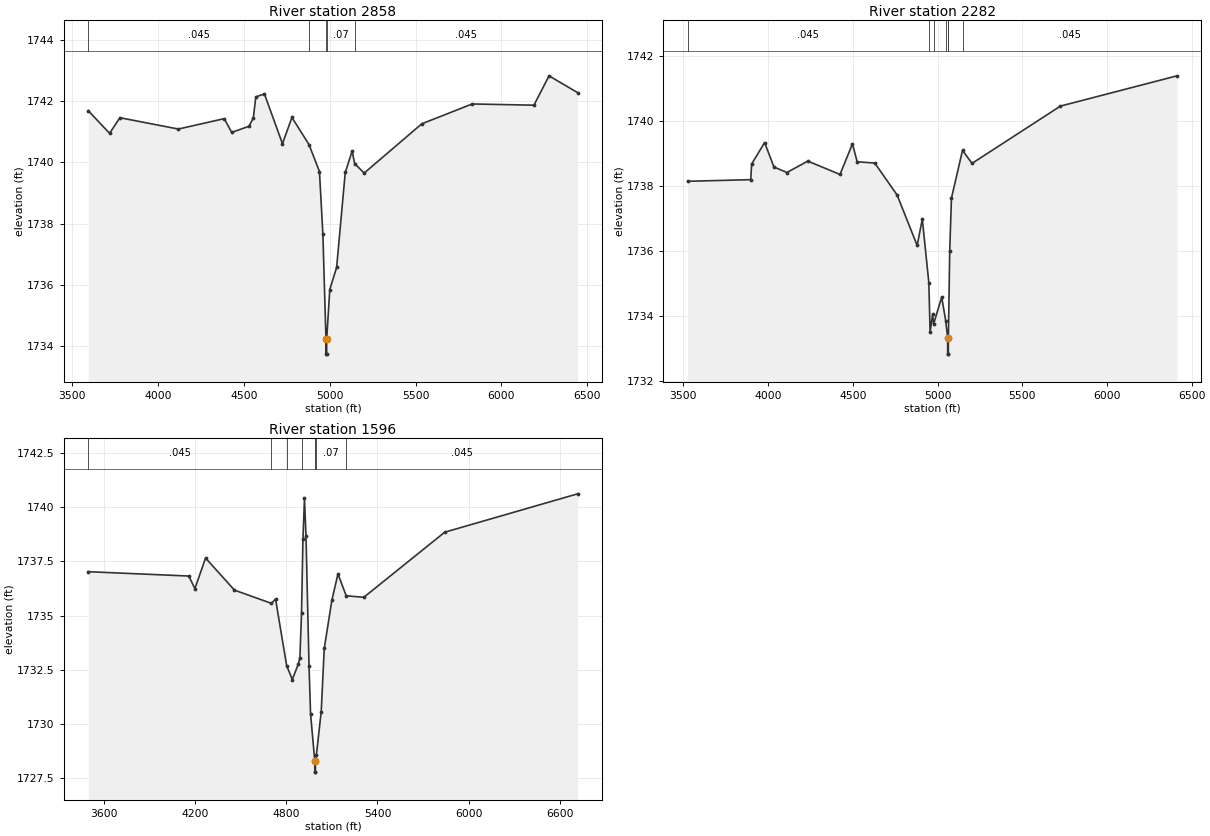
Type RM Length L Ch R = 1,2858,576,576,576
BEGIN DESCRIPTION:
Mapping XS cd1d5d24
END DESCRIPTION:
XS GIS Cut Line= 3
      1515216.95      6898041.91      1515102.36      6896109.60
      1514654.52      6895312.85
#Sta/Elev= 30
  3593.9 1741.69  3718.0 1740.95  3778.1 1741.46  4118.7 1741.09  4385.6 1741.43
  4429.3 1740.98  4529.5 1741.18  4555.2 1741.45  4569.5 1742.14  4619.6 1742.24
  4724.8 1740.61  4779.9 1741.47  4879.5 1740.58  4940.2 1739.70  4960.2 1737.65
  4978.1 1734.23  4978.4 1733.73  4982.1 1733.73  4982.4 1734.23  5000.3 1735.84
  5040.3 1736.57  5090.4 1739.67  5130.5 1740.37  5145.3 1739.96  5200.6 1739.65
  5535.8 1741.26  5829.7 1741.91  6189.3 1741.87  6277.1 1742.83  6443.6 1742.28
#Mann=5,-1,0
  3593.9   0.045       0  4879.5    0.07       0  4978.1    0.07       0
  4982.4    0.07       0  5145.3   0.045       0
Bank Sta=4978.1,4982.4
Exp/Cntr=0.3,0.1

Type RM Length L Ch R = 1,2282,686,686,686
BEGIN DESCRIPTION:
Mapping XS fe9d2287
END DESCRIPTION:
XS GIS Cut Line= 3
      1515847.15      6897927.27      1515565.91      6896093.98
      1514899.90      6895303.09
#Sta/Elev= 30
  3524.9 1738.14  3897.6 1738.19  3902.7 1738.67  3979.4 1739.33  4034.4 1738.58
  4110.9 1738.41  4234.5 1738.76  4424.4 1738.35  4497.9 1739.29  4525.7 1738.74
  4629.6 1738.70  4761.3 1737.72  4879.8 1736.17  4910.2 1736.98  4948.7 1735.03
  4956.3 1733.50  4970.9 1734.05  4977.2 1733.76  5024.7 1734.58  5048.2 1733.86
  5059.8 1733.33  5060.0 1732.83  5063.8 1732.83  5064.1 1733.33  5072.1 1736.01
  5082.2 1737.62  5147.6 1739.09  5203.6 1738.69  5725.6 1740.45  6413.6 1741.38
#Mann=7,-1,0
  3524.9   0.045       0  4948.7    0.07       0  4977.2   0.045       0
  5048.2    0.07       0  5059.8   0.045       0  5064.1    0.07       0
  5147.6   0.045       0
Bank Sta=5059.8,5064.1
Exp/Cntr=0.3,0.1

Type RM Length L Ch R = 1,1596,0,0,0
BEGIN DESCRIPTION:
NC Unknown Stream 77 1.0
END DESCRIPTION:
XS GIS Cut Line= 3
      1516154.45      6897838.76      1516206.53      6895948.14
      1515076.35      6895255.45
#Sta/Elev= 30
  3499.0 1737.02  4160.0 1736.82  4200.0 1736.24  4270.1 1737.65  4460.1 1736.17
  4703.3 1735.56  4730.2 1735.76  4803.1 1732.69  4840.3 1732.05  4880.3 1732.77
  4890.3 1733.06  4900.9 1735.12  4910.3 1738.53  4920.3 1740.40  4930.3 1738.66
  4950.3 1732.68  4960.3 1730.47  4988.1 1728.28  4988.4 1727.78  4992.2 1727.78
  4992.5 1728.28  4998.8 1728.58  5030.3 1730.57  5050.3 1733.48  5100.4 1735.70
  5140.4 1736.92  5194.5 1735.91  5310.4 1735.84  5842.0 1738.84  6715.9 1740.61
#Mann=8,-1,0
  3499.0   0.045       0  4703.3    0.07       0  4803.1   0.045       0
  4900.9    0.16       0  4988.1    0.07       0  4992.5    0.16       0
  4998.8    0.07       0  5194.5   0.045       0
Bank Sta=4988.1,4992.5
Exp/Cntr=0.3,0.1

Chan Stop Cuts=-1