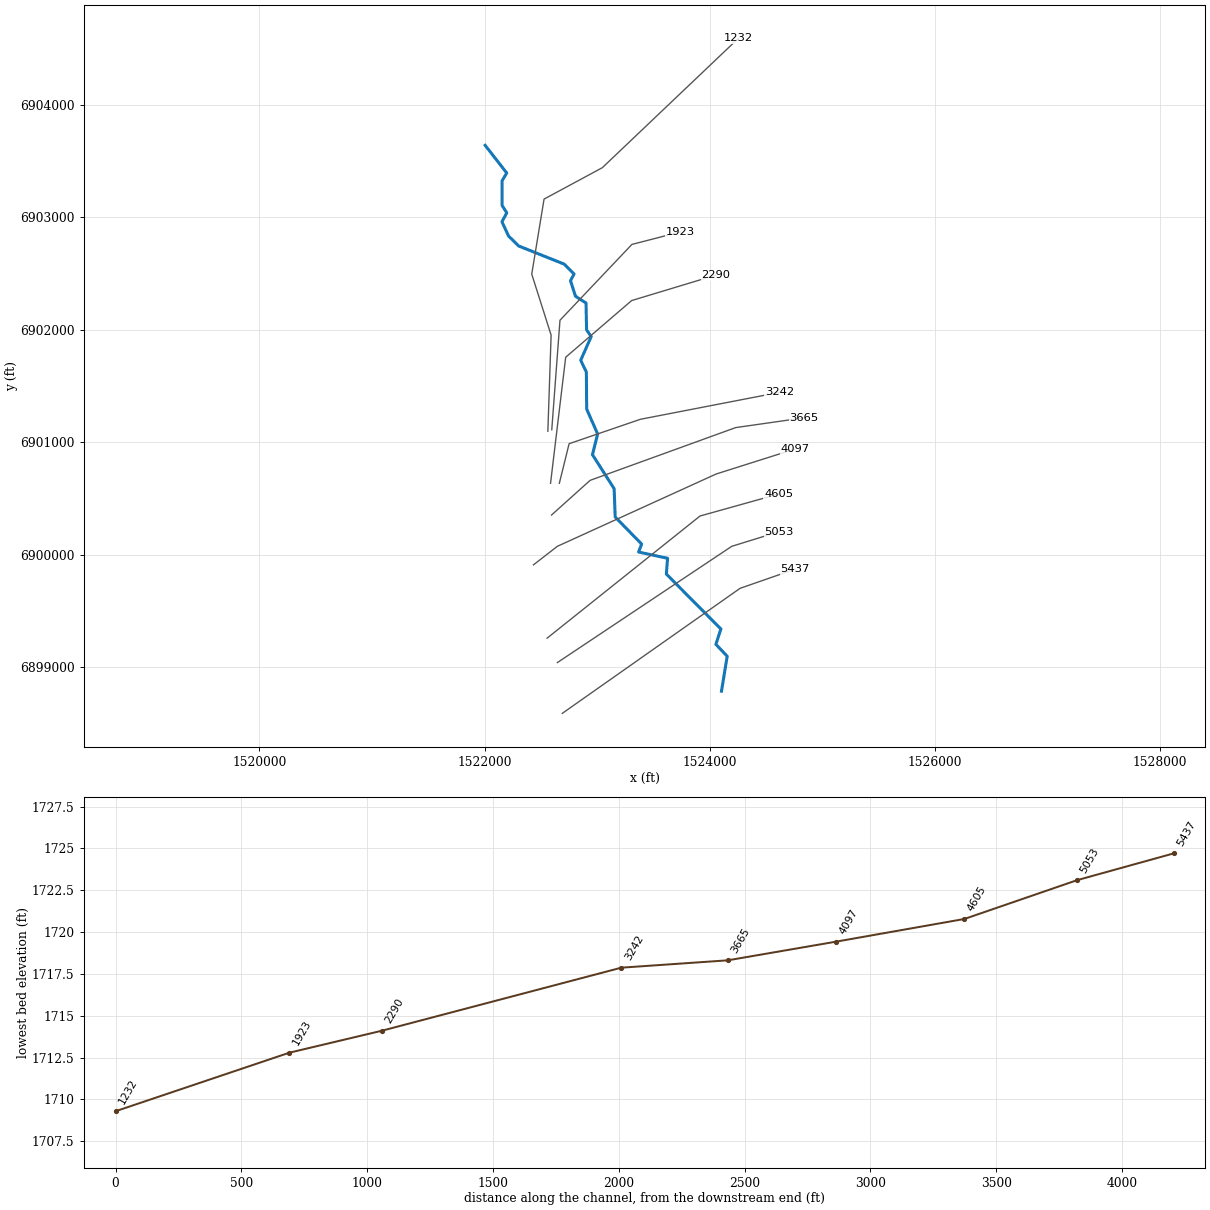
--- NC Unknown Stream 78.prj (project) ---

Proj Title=NC Unknown Stream 78 Base Level Engineering
Current Plan=p01
Default Exp/Contr=0.3,0.1
English Units
Geom File=g01
Flow File=f01
Plan File=p01
Y Axis Title=Elevation
X Axis Title(PF)=Main Channel Distance
X Axis Title(XS)=Station
BEGIN DESCRIPTION:
NC Unknown Stream 78
END DESCRIPTION:
DSS Export Rating Curves= 0
DSS Export Rating Curve Sorted= 0
DSS Export Volume Flow Curves= 0
DXF OffsetX= 0
DXF OffsetY= 0
DXF ScaleX= 1
DXF ScaleY= 10

--- NC Unknown Stream 78.p01 (plan) ---

Plan Title=Multiple Run
Short Identifier=Multiple
Geom File=g01
Flow File=f01
Subcritical Flow
K Sum by GR= 0
Std Step Tol= 0.01
Critical Tol= 0.01
Num of Std Step Trials= 20
Max Error Tol= 0.3
Flow Tol Ratio= 0.001
Split Flow NTrial= 30
Split Flow Tol= 0.02
Split Flow Ratio= 0.02
Log Output Level= 0
Friction Slope Method= 1
Unsteady Friction Slope Method= 2
Unsteady Bridges Friction Slope Method= 1
Parabolic Critical Depth
Global Vel Dist=  1 , 1 , 1
Global Log Level= 0
CheckData=True
Encroach Param= -1, 0, 0, 0
BEGIN DESCRIPTION:
Multiple Run
END DESCRIPTION:

--- NC Unknown Stream 78.f01 (steady flow) ---

Flow Title=Multiple
Program Version=4.10
Number of Profiles= 7
Profile Names=10-year,25-year,50-year,1pct_min,100-year,1pct_plu,500-year
River Rch & RM=NC Unknown Strea,Reach-1         ,5437
     315     439     541     332     662    1321    1006
River Rch & RM=NC Unknown Strea,Reach-1         ,1232
     324     452     558     342     683    1364    1040
Boundary for River Rch & Prof#=NC Unknown Strea,Reach-1         , 1
Up Type= 0
Dn Type= 3
Dn Slope=0.01
Boundary for River Rch & Prof#=NC Unknown Strea,Reach-1         , 2
Up Type= 0
Dn Type= 3
Dn Slope=0.01
Boundary for River Rch & Prof#=NC Unknown Strea,Reach-1         , 3
Up Type= 0
Dn Type= 3
Dn Slope=0.01
Boundary for River Rch & Prof#=NC Unknown Strea,Reach-1         , 4
Up Type= 0
Dn Type= 3
Dn Slope=0.01
Boundary for River Rch & Prof#=NC Unknown Strea,Reach-1         , 5
Up Type= 0
Dn Type= 3
Dn Slope=0.01
Boundary for River Rch & Prof#=NC Unknown Strea,Reach-1         , 6
Up Type= 0
Dn Type= 3
Dn Slope=0.01
Boundary for River Rch & Prof#=NC Unknown Strea,Reach-1         , 7
Up Type= 0
Dn Type= 3
Dn Slope=0.01
DSS Import GetInterval= 0
DSS Import GetPeak= 0
DSS Import FillOption= 0

--- NC Unknown Stream 78.g01 (geometry) ---

Geom Title=Existing Conditions

River Reach=NC Unknown Strea,Reach-1
Reach XY= 30
      1524105.00      6898788.00      1524155.84      6899098.12
      1524055.25      6899204.02      1524099.91      6899340.30
      1523615.21      6899828.32      1523626.10      6899968.41
      1523368.47      6900024.24      1523395.69      6900094.66
      1523160.46      6900335.55      1523151.45      6900586.53
      1522958.47      6900889.50      1523004.91      6901072.61
      1522907.26      6901293.94      1522904.48      6901622.78
      1522854.22      6901727.95      1522947.47      6901937.99
      1522906.38      6901998.44      1522901.52      6902236.74
      1522808.19      6902296.35      1522763.28      6902434.78
      1522795.71      6902494.69      1522707.33      6902582.17
      1522302.56      6902743.52      1522213.13      6902831.93
      1522154.78      6902958.20      1522197.41      6903037.99
      1522155.66      6903103.16      1522155.66      6903322.84
      1522197.21      6903391.42      1522005.00      6903638.00

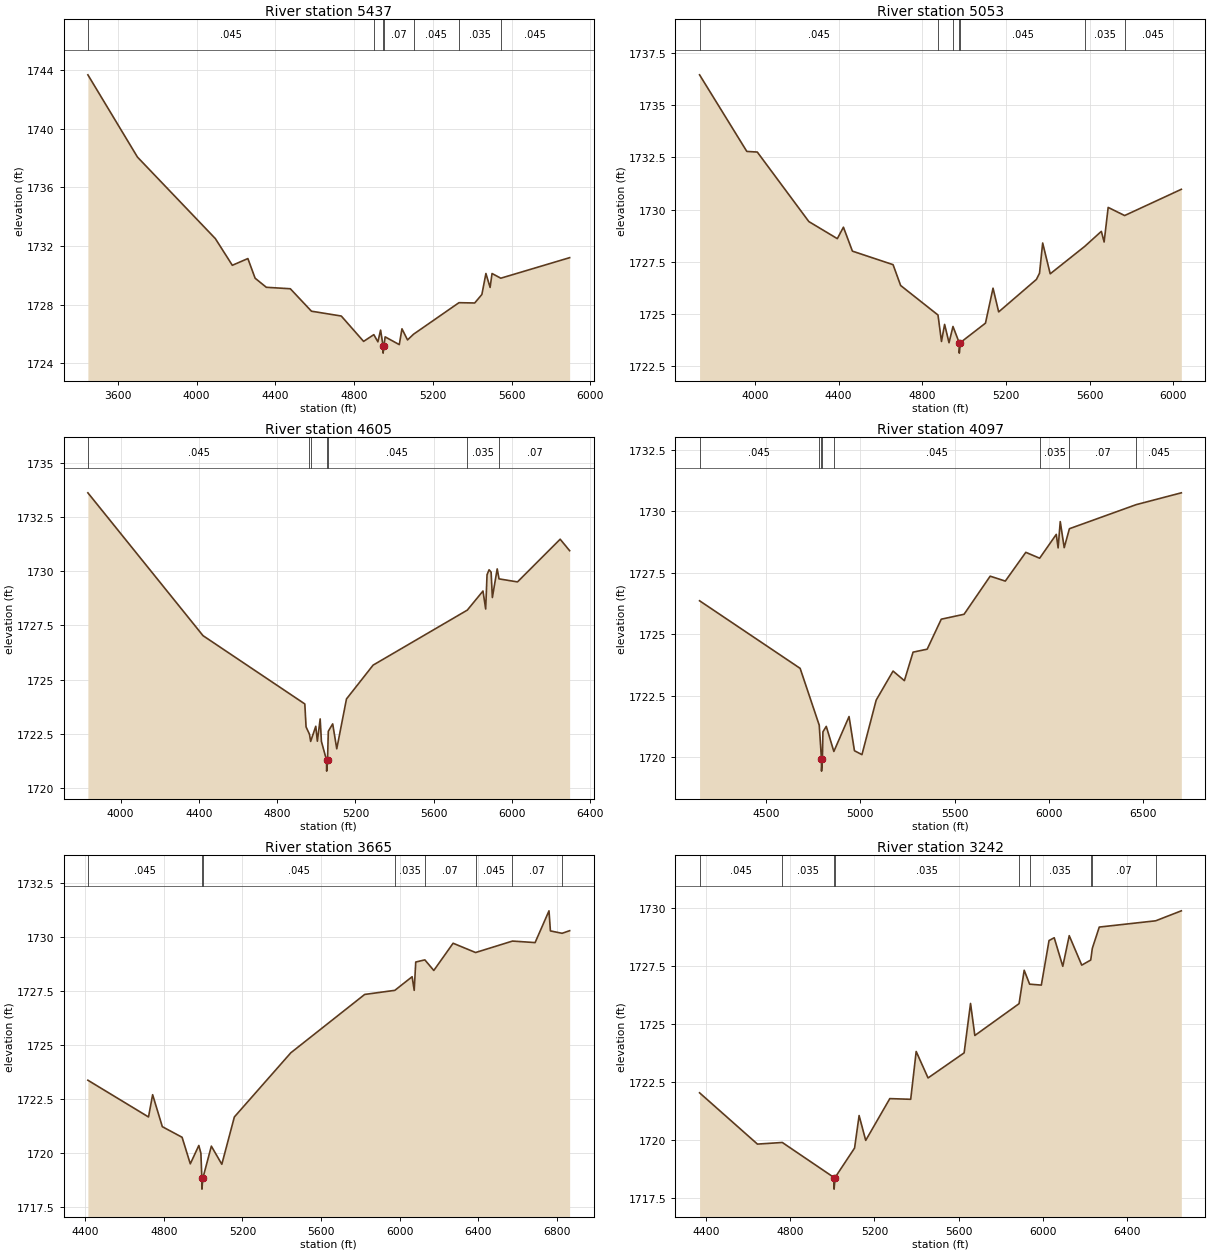
Type RM Length L Ch R = 1,5437,384,384,384
BEGIN DESCRIPTION:
Mapping XS 7cf85c07
END DESCRIPTION:
XS GIS Cut Line= 3
      1522690.48      6898590.68      1524270.33      6899701.79
      1524756.46      6899871.06
#Sta/Elev= 30
  3448.3 1743.68  3700.1 1738.07  4095.6 1732.51  4181.8 1730.69  4260.7 1731.15
  4297.4 1729.81  4354.3 1729.19  4476.3 1729.09  4583.5 1727.56  4735.0 1727.23
  4848.3 1725.50  4900.2 1725.96  4920.9 1725.47  4934.6 1726.27  4947.1 1725.20
  4947.4 1724.70  4951.7 1725.20  4957.6 1725.81  5029.5 1725.28  5043.1 1726.36
  5071.3 1725.60  5101.9 1725.99  5332.6 1728.14  5412.5 1728.12  5448.9 1728.70
  5469.4 1730.13  5490.6 1729.18  5500.5 1730.13  5544.9 1729.81  5894.5 1731.21
#Mann=7,-1,0
  3448.3   0.045       0  4900.2    0.07       0  4947.1    0.07       0
  4951.7    0.07       0  5101.9   0.045       0  5332.6   0.035       0
  5544.9   0.045       0
Bank Sta=4947.1,4951.7
Exp/Cntr=0.3,0.1

Type RM Length L Ch R = 1,5053,448,448,448
BEGIN DESCRIPTION:
Mapping XS 1d107a2c
END DESCRIPTION:
XS GIS Cut Line= 3
      1522647.07      6899042.07      1524196.55      6900075.05
      1524617.53      6900205.25
#Sta/Elev= 30
  3735.3 1736.47  3961.2 1732.79  4011.3 1732.76  4257.7 1729.42  4393.8 1728.60
  4423.0 1729.15  4465.9 1728.00  4660.3 1727.35  4696.4 1726.35  4875.1 1724.93
  4891.7 1723.66  4906.7 1724.48  4927.7 1723.60  4946.7 1724.38  4976.5 1723.60
  4976.8 1723.10  4981.2 1723.60  5102.0 1724.54  5138.1 1726.22  5165.1 1725.08
  5345.4 1726.64  5360.4 1726.94  5375.4 1728.39  5411.5 1726.91  5576.7 1728.23
  5655.9 1728.95  5669.2 1728.44  5688.5 1730.10  5767.3 1729.71  6038.2 1730.97
#Mann=7,-1,0
  3735.3   0.045       0  4875.1    0.07       0  4946.7   0.045       0
  4976.5   0.045       0  4981.2   0.045       0  5576.7   0.035       0
  5767.3   0.045       0
Bank Sta=4976.5,4981.2
Exp/Cntr=0.3,0.1

Type RM Length L Ch R = 1,4605,508,508,508
BEGIN DESCRIPTION:
Mapping XS a49454b7
END DESCRIPTION:
XS GIS Cut Line= 3
      1522555.90      6899259.06      1523914.43      6900344.15
      1524611.62      6900539.02
#Sta/Elev= 30
  3832.5 1733.62  4421.1 1727.03  4941.4 1723.88  4947.8 1722.82  4965.3 1722.48
  4971.3 1722.15  4997.4 1722.85  5005.5 1722.16  5019.9 1723.19  5026.3 1722.15
  5052.7 1721.28  5053.0 1720.78  5057.5 1721.28  5061.5 1722.62  5083.9 1722.96
  5104.7 1721.81  5154.4 1724.11  5290.4 1725.67  5772.2 1728.21  5852.1 1729.09
  5865.9 1728.26  5872.9 1729.84  5883.3 1730.07  5893.7 1729.96  5900.1 1728.79
  5924.8 1730.11  5934.2 1729.65  6028.6 1729.51  6246.7 1731.48  6295.1 1730.95
#Mann=7,-1,0
  3832.5   0.045       0  4965.3    0.07       0  4971.3   0.045       0
  5052.7   0.045       0  5057.5   0.045       0  5772.2   0.035       0
  5934.2    0.07       0
Bank Sta=5052.7,5057.5
Exp/Cntr=0.3,0.1

Type RM Length L Ch R = 1,4097,432,432,432
BEGIN DESCRIPTION:
Mapping XS 36f32d73
END DESCRIPTION:
XS GIS Cut Line= 4
      1522434.39      6899910.12      1522647.07      6900075.05
      1524057.66      6900717.41      1524756.43      6900938.76
#Sta/Elev= 30
  4149.3 1726.36  4682.1 1723.61  4783.2 1721.30  4795.0 1719.93  4795.4 1719.43
  4799.9 1719.93  4802.9 1721.03  4820.5 1721.25  4860.7 1720.23  4941.2 1721.65
  4969.8 1720.26  5009.5 1720.10  5085.0 1722.32  5174.3 1723.50  5234.3 1723.11
  5280.4 1724.27  5355.1 1724.39  5429.7 1725.61  5550.5 1725.81  5688.8 1727.36
  5769.0 1727.16  5877.6 1728.33  5950.9 1728.09  6039.0 1729.06  6048.7 1728.51
  6060.0 1729.58  6081.0 1728.52  6108.5 1729.29  6462.6 1730.27  6701.4 1730.75
#Mann=8,-1,0
  4149.3   0.045       0  4783.2    0.07       0  4795.0   0.045       0
  4799.9    0.07       0  4860.7   0.045       0  5950.9   0.035       0
  6108.5    0.07       0  6462.6   0.045       0
Bank Sta=4795,4799.9
Exp/Cntr=0.3,0.1

Type RM Length L Ch R = 1,3665,423,423,423
BEGIN DESCRIPTION:
Mapping XS 007962ac
END DESCRIPTION:
XS GIS Cut Line= 4
      1522595.01      6900352.85      1522937.87      6900660.99
      1524231.27      6901129.74      1524838.90      6901216.54
#Sta/Elev= 30
  4413.9 1723.35  4722.3 1721.65  4743.3 1722.68  4792.6 1721.20  4893.1 1720.71
  4934.9 1719.48  4978.2 1720.33  4988.8 1719.97  4993.7 1718.81  4994.1 1718.31
  4998.6 1718.81  5042.0 1720.30  5095.2 1719.46  5159.0 1721.65  5446.2 1724.62
  5821.9 1727.32  5975.3 1727.51  6063.1 1728.14  6073.8 1727.51  6081.6 1728.82
  6127.9 1728.92  6173.5 1728.43  6271.6 1729.69  6386.0 1729.26  6573.6 1729.79
  6688.7 1729.72  6759.4 1731.19  6766.6 1730.26  6826.0 1730.15  6864.4 1730.27
#Mann=8,-1,0
  4413.9   0.045       0  4993.7   0.045       0  4998.6   0.045       0
  5975.3   0.035       0  6127.9    0.07       0  6386.0   0.045       0
  6573.6    0.07       0  6826.0   0.045       0
Bank Sta=4993.7,4998.6
Exp/Cntr=0.3,0.1

Type RM Length L Ch R = 1,3242,952,952,952
BEGIN DESCRIPTION:
Mapping XS 4880efee
END DESCRIPTION:
XS GIS Cut Line= 4
      1522664.44      6900634.99      1522751.24      6900986.51
      1523384.92      6901203.53      1524617.53      6901442.23
#Sta/Elev= 30
  4369.9 1722.02  4644.7 1719.81  4762.7 1719.88  5008.3 1718.37  5008.7 1717.87
  5013.3 1718.37  5105.9 1719.64  5127.4 1721.04  5158.8 1719.97  5273.2 1721.77
  5372.4 1721.74  5398.4 1723.80  5454.8 1722.66  5626.0 1723.74  5656.5 1725.87
  5676.9 1724.49  5886.9 1725.86  5911.2 1727.30  5937.0 1726.70  5992.6 1726.66
  6029.2 1728.58  6053.8 1728.70  6094.5 1727.47  6125.1 1728.79  6184.5 1727.52
  6227.2 1727.74  6234.6 1728.24  6267.7 1729.16  6535.6 1729.43  6657.3 1729.86
#Mann=9,-1,0
  4369.9   0.045       0  4762.7   0.035       0  5008.3   0.035       0
  5013.3   0.035       0  5886.9   0.045       0  5937.0   0.035       0
  6227.2   0.045       0  6234.6    0.07       0  6535.6   0.035       0
Bank Sta=5008.3,5013.3
Exp/Cntr=0.3,0.1

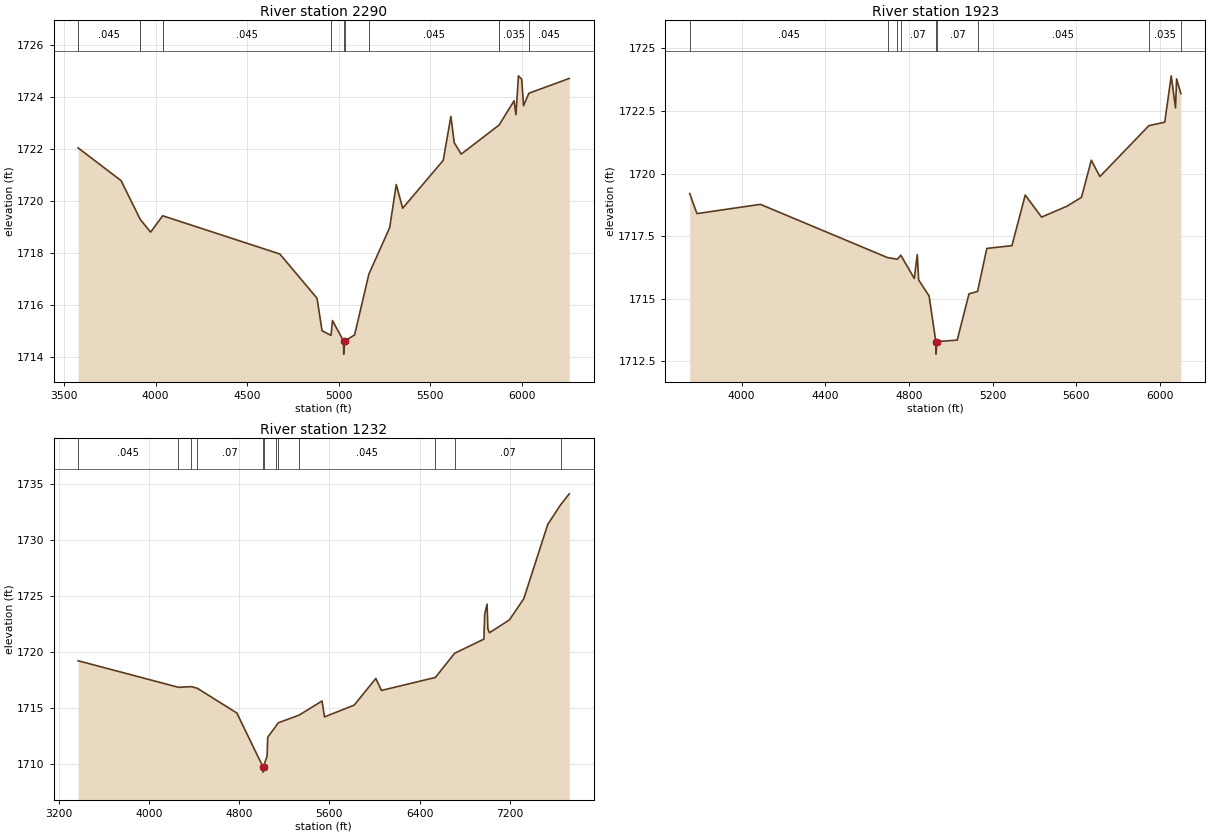
Type RM Length L Ch R = 1,2290,367,367,367
BEGIN DESCRIPTION:
Mapping XS c853ce47
END DESCRIPTION:
XS GIS Cut Line= 4
      1522586.31      6900634.95      1522720.85      6901754.74
      1523306.79      6902258.21      1524053.35      6902483.92
#Sta/Elev= 30
  3577.6 1722.03  3812.3 1720.77  3916.7 1719.28  3973.5 1718.79  4039.0 1719.42
  4678.5 1717.95  4881.3 1716.25  4908.8 1715.00  4957.9 1714.82  4965.8 1715.39
  5026.5 1714.60  5027.0 1714.10  5032.5 1714.60  5086.5 1714.84  5164.6 1717.18
  5277.8 1718.96  5313.7 1720.62  5348.8 1719.71  5570.1 1721.55  5611.9 1723.24
  5630.2 1722.23  5668.3 1721.79  5875.2 1722.91  5956.7 1723.84  5967.1 1723.31
  5980.5 1724.80  5998.5 1724.67  6008.3 1723.65  6037.5 1724.13  6257.9 1724.70
#Mann=9,-1,0
  3577.6   0.045       0  3916.7   0.035       0  4039.0   0.045       0
  4957.9    0.07       0  5026.5    0.07       0  5032.5    0.07       0
  5164.6   0.045       0  5875.2   0.035       0  6037.5   0.045       0
Bank Sta=5026.5,5032.5
Exp/Cntr=0.3,0.1

Type RM Length L Ch R = 1,1923,691,691,691
BEGIN DESCRIPTION:
Mapping XS 2fa54b4e
END DESCRIPTION:
XS GIS Cut Line= 4
      1522597.20      6901111.16      1522670.12      6902083.39
      1523309.01      6902757.00      1523739.55      6902868.11
#Sta/Elev= 30
  3751.9 1719.20  3786.6 1718.40  4089.7 1718.77  4698.7 1716.64  4745.3 1716.58
  4761.0 1716.74  4825.6 1715.81  4839.8 1716.76  4846.6 1715.75  4896.4 1715.11
  4928.6 1713.29  4929.1 1712.79  4934.6 1713.29  5030.7 1713.35  5087.3 1715.20
  5128.1 1715.29  5172.3 1717.01  5292.4 1717.12  5355.9 1719.14  5434.0 1718.26
  5554.1 1718.69  5624.9 1719.05  5671.8 1720.53  5713.1 1719.88  5947.0 1721.91
  6022.9 1722.05  6053.9 1723.90  6074.4 1722.62  6079.6 1723.78  6099.9 1723.19
#Mann=9,-1,0
  3751.9   0.045       0  4698.7    0.07       0  4745.3   0.045       0
  4761.0    0.07       0  4928.6    0.07       0  4934.6    0.07       0
  5128.1   0.045       0  5947.0   0.035       0  6099.9    0.07       0
Bank Sta=4928.6,4934.6
Exp/Cntr=0.3,0.1

Type RM Length L Ch R = 1,1232,0,0,0
BEGIN DESCRIPTION:
NC Unknown Stream 78 1.0
END DESCRIPTION:
XS GIS Cut Line= 6
      1522562.48      6901097.31      1522591.34      6901951.42
      1522419.25      6902493.11      1522528.63      6903159.78
      1523046.37      6903438.77      1524255.03      6904588.03
#Sta/Elev= 30
  3373.0 1719.23  4263.0 1716.86  4376.2 1716.92  4430.7 1716.77  4780.1 1714.57
  5010.6 1709.79  5011.1 1709.29  5016.8 1709.79  5048.4 1710.72  5054.3 1712.41
  5130.7 1713.45  5147.0 1713.69  5332.8 1714.38  5535.6 1715.64  5557.6 1714.22
  5820.4 1715.27  6012.7 1717.65  6062.2 1716.58  6540.5 1717.74  6711.2 1719.90
  6970.5 1721.16  6977.8 1723.39  6998.8 1724.28  7006.1 1722.07  7020.2 1721.73
  7197.0 1722.88  7324.4 1724.77  7536.4 1731.39  7649.9 1733.14  7727.5 1734.13
#Mann=12,-1,0
  3373.0   0.045       0  4263.0    0.07       0  4376.2   0.045       0
  4430.7    0.07       0  5010.6    0.07       0  5016.8    0.07       0
  5130.7   0.045       0  5147.0    0.07       0  5332.8   0.045       0
  6540.5   0.035       0  6711.2    0.07       0  7649.9   0.045       0
Bank Sta=5010.6,5016.8
Exp/Cntr=0.3,0.1

Chan Stop Cuts=-1