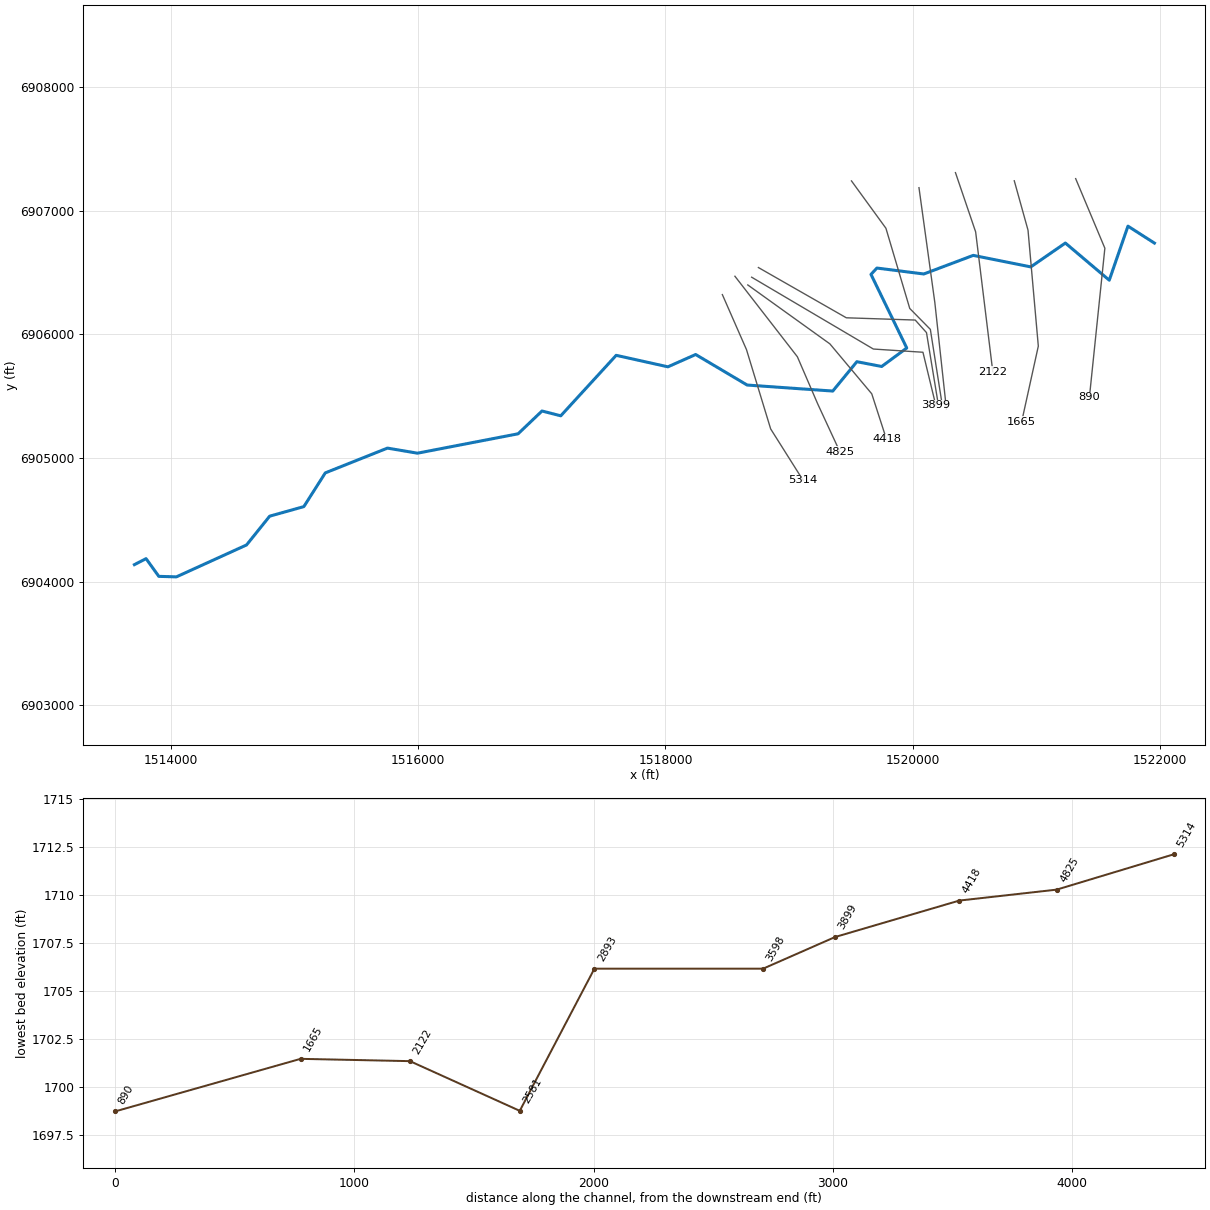
--- NC Unknown Stream 79.prj (project) ---

Proj Title=NC Unknown Stream 79 Base Level Engineering
Current Plan=p01
Default Exp/Contr=0.3,0.1
English Units
Geom File=g01
Flow File=f01
Plan File=p01
BEGIN DESCRIPTION:
NC Unknown Stream 79
END DESCRIPTION:

--- NC Unknown Stream 79.p01 (plan) ---

Plan Title=Multiple Run
Short Identifier=Multiple
Geom File=g01
Flow File=f01
Subcritical Flow
K Sum by GR= 0
Std Step Tol= 0.01
Critical Tol= 0.01
Num of Std Step Trials= 20
Max Error Tol= 0.3
Flow Tol Ratio= 0.001
Split Flow NTrial= 30
Split Flow Tol= 0.02
Split Flow Ratio= 0.02
Log Output Level= 0
Friction Slope Method= 1
Unsteady Friction Slope Method= 2
Unsteady Bridges Friction Slope Method= 1
Parabolic Critical Depth
Global Vel Dist=  1 , 1 , 1
Global Log Level= 0
CheckData=True
Encroach Param= -1, 0, 0, 0
BEGIN DESCRIPTION:
Multiple Run
END DESCRIPTION:

--- NC Unknown Stream 79.f01 (steady flow) ---

Flow Title=Multiple
Number of Profiles=7
Profile Names=10-year,25-year,50-year,1pct_min,100-year,1pct_plu,500-year
River Rch & RM= NC Unknown Strea,Reach-1,5314
     824    1193    1508     945    1885    3760    2982
Boundary for River Rch & Prof#=NC Unknown Strea,Reach-1,1
Up Type=0
Dn Type=3
Dn Slope=0.001
Boundary for River Rch & Prof#=NC Unknown Strea,Reach-1,2
Up Type=0
Dn Type=3
Dn Slope=0.001
Boundary for River Rch & Prof#=NC Unknown Strea,Reach-1,3
Up Type=0
Dn Type=3
Dn Slope=0.001
Boundary for River Rch & Prof#=NC Unknown Strea,Reach-1,4
Up Type=0
Dn Type=3
Dn Slope=0.001
Boundary for River Rch & Prof#=NC Unknown Strea,Reach-1,5
Up Type=0
Dn Type=3
Dn Slope=0.001
Boundary for River Rch & Prof#=NC Unknown Strea,Reach-1,6
Up Type=0
Dn Type=3
Dn Slope=0.001
Boundary for River Rch & Prof#=NC Unknown Strea,Reach-1,7
Up Type=0
Dn Type=3
Dn Slope=0.001

--- NC Unknown Stream 79.g01 (geometry) ---

Geom Title=Existing Conditions

River Reach=NC Unknown Strea,Reach-1
Reach XY= 30
      1513705.00      6904138.00      1513799.23      6904186.54
      1513902.30      6904043.35      1514044.50      6904039.19
      1514611.95      6904297.19      1514798.94      6904529.86
      1515075.39      6904607.21      1515248.89      6904879.95
      1515751.59      6905080.19      1515994.49      6905039.22
      1516808.34      6905195.99      1517001.58      6905380.20
      1517153.50      6905341.46      1517601.67      6905830.39
      1518020.20      6905737.51      1518244.52      6905837.07
      1518660.97      6905590.15      1519353.55      6905541.53
      1519548.24      6905778.88      1519749.07      6905740.23
      1519951.91      6905889.64      1519662.50      6906484.88
      1519710.48      6906536.03      1520089.59      6906488.13
      1520489.80      6906638.49      1520955.10      6906545.32
      1521234.82      6906738.30      1521589.78      6906437.83
      1521741.01      6906874.90      1521955.00      6906738.00

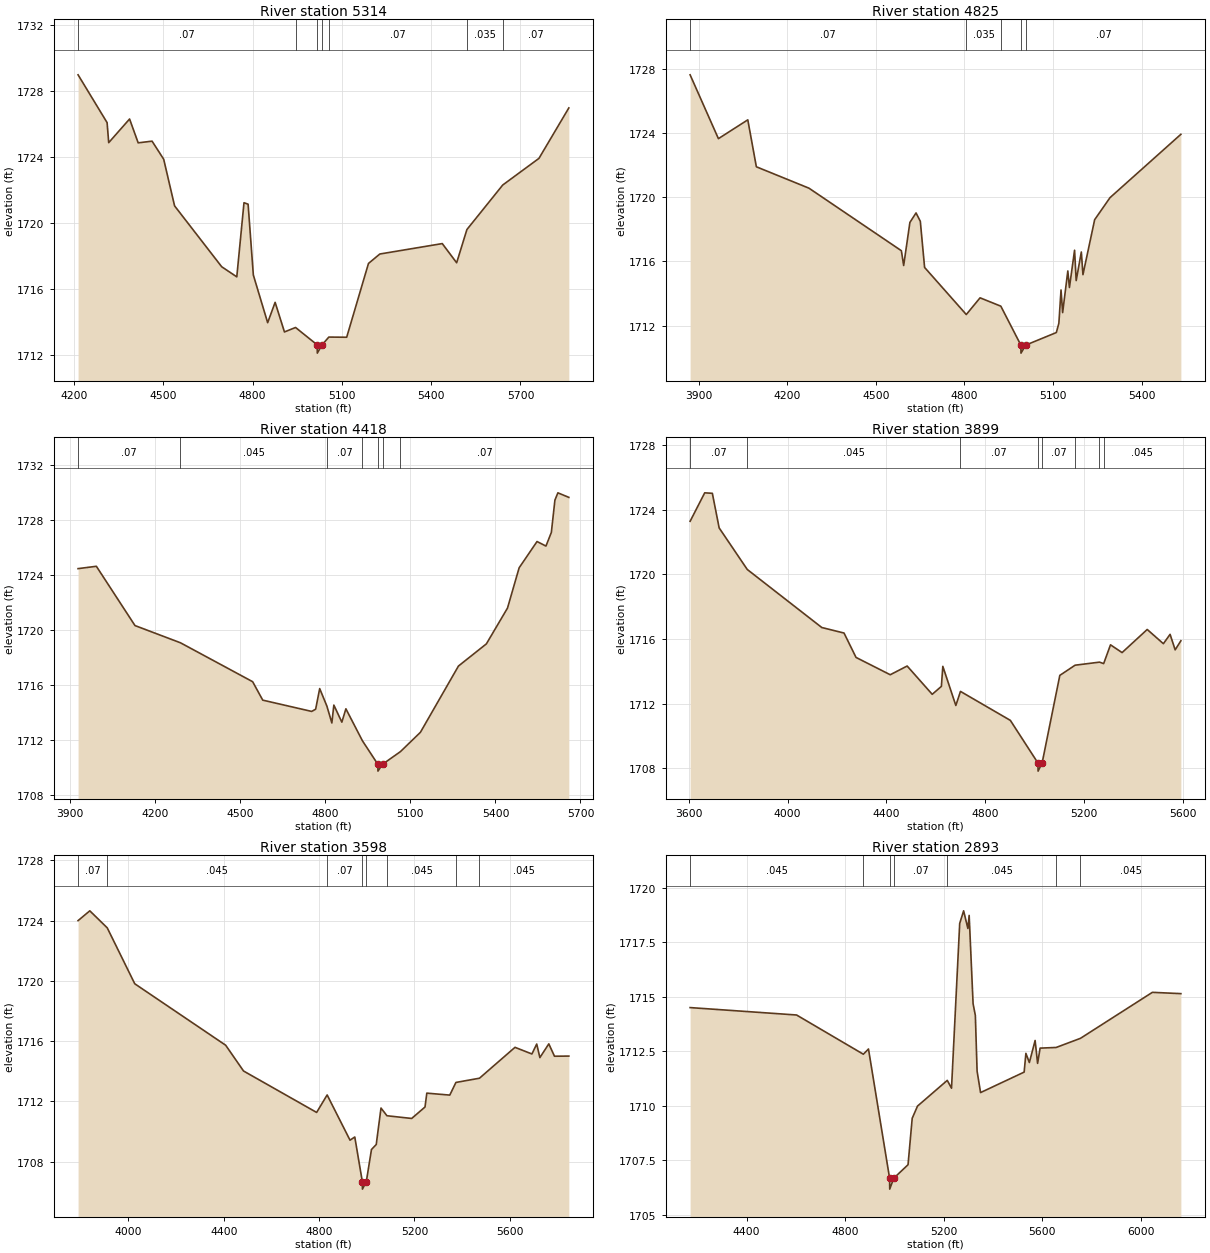
Type RM Length L Ch R = 1,5314,489,489,489
BEGIN DESCRIPTION:
Mapping XS 3c2cf6db
END DESCRIPTION:
XS GIS Cut Line= 4
      1518460.45      6906321.38      1518655.75      6905876.09
      1518851.06      6905235.47      1519114.08      6904818.81
#Sta/Elev= 30
  4213.7 1728.96  4311.2 1726.07  4316.6 1724.86  4386.7 1726.29  4415.6 1724.85
  4462.3 1724.95  4501.3 1723.86  4537.9 1721.04  4696.2 1717.36  4746.9 1716.75
  4771.1 1721.23  4784.9 1721.14  4802.5 1716.86  4850.6 1713.98  4875.7 1715.21
  4907.0 1713.42  4944.3 1713.69  5016.9 1712.64  5017.4 1712.14  5033.5 1712.64
  5056.1 1713.11  5116.1 1713.10  5189.3 1717.56  5227.4 1718.13  5437.2 1718.76
  5485.5 1717.60  5520.0 1719.61  5640.3 1722.30  5762.0 1723.91  5862.4 1726.96
#Mann=7,-1,0
  4213.7    0.07       0  4944.3   0.035       0  5016.9   0.035       0
  5033.5   0.035       0  5056.1    0.07       0  5520.0   0.035       0
  5640.3    0.07       0
Bank Sta=5016.9,5033.5
Exp/Cntr=0.3,0.1

Type RM Length L Ch R = 1,4825,407,407,407
BEGIN DESCRIPTION:
Mapping XS c3f47448
END DESCRIPTION:
XS GIS Cut Line= 4
      1518562.01      6906469.84      1519067.21      6905818.80
      1519231.27      6905438.59      1519409.92      6905052.81
#Sta/Elev= 30
  3870.1 1727.61  3966.0 1723.64  4065.6 1724.81  4094.6 1721.89  4272.9 1720.56
  4586.1 1716.67  4593.9 1715.75  4615.0 1718.43  4635.8 1719.02  4650.3 1718.50
  4664.8 1715.63  4806.1 1712.70  4852.8 1713.74  4923.2 1713.22  4991.0 1710.80
  4991.5 1710.30  5007.7 1710.80  5111.3 1711.58  5119.9 1712.16  5127.2 1714.23
  5132.7 1712.82  5150.2 1715.41  5155.7 1714.38  5173.1 1716.70  5178.6 1714.81
  5196.0 1716.59  5201.5 1715.18  5241.2 1718.60  5293.2 1719.97  5533.4 1723.91
#Mann=5,-1,0
  3870.1    0.07       0  4806.1   0.035       0  4923.2    0.07       0
  4991.0    0.07       0  5007.7    0.07       0
Bank Sta=4991,5007.7
Exp/Cntr=0.3,0.1

Type RM Length L Ch R = 1,4418,519,519,519
BEGIN DESCRIPTION:
Mapping XS 593734da
END DESCRIPTION:
XS GIS Cut Line= 4
      1518666.16      6906399.54      1519330.23      6905922.97
      1519668.77      6905519.32      1519788.01      6905151.25
#Sta/Elev= 30
  3927.8 1724.45  3992.3 1724.62  4128.6 1720.31  4288.9 1719.06  4543.6 1716.23
  4579.2 1714.89  4751.7 1714.07  4765.8 1714.23  4780.1 1715.73  4805.4 1714.46
  4823.0 1713.23  4830.0 1714.53  4858.2 1713.29  4872.5 1714.26  4930.7 1711.94
  4985.1 1710.23  4985.6 1709.73  5001.8 1710.23  5065.0 1711.15  5135.3 1712.55
  5269.6 1717.37  5368.0 1718.98  5442.5 1721.58  5483.6 1724.51  5546.7 1726.42
  5578.2 1726.09  5597.2 1727.08  5609.8 1729.43  5620.3 1729.96  5658.9 1729.63
#Mann=7,-1,0
  3927.8    0.07       0  4288.9   0.045       0  4805.4    0.07       0
  4930.7   0.035       0  4985.1   0.035       0  5001.8   0.035       0
  5065.0    0.07       0
Bank Sta=4985.1,5001.8
Exp/Cntr=0.3,0.1

Type RM Length L Ch R = 1,3899,301,301,301
BEGIN DESCRIPTION:
Mapping XS ce077cac
END DESCRIPTION:
XS GIS Cut Line= 4
      1518697.45      6906462.01      1519681.79      6905881.30
      1520082.83      6905855.26      1520187.00      6905425.56
#Sta/Elev= 30
  3605.6 1723.28  3664.7 1725.04  3695.6 1725.01  3723.2 1722.87  3837.0 1720.30
  4138.8 1716.71  4228.7 1716.37  4277.4 1714.86  4415.9 1713.79  4484.3 1714.33
  4585.8 1712.58  4622.9 1713.07  4628.7 1714.31  4681.4 1711.89  4700.2 1712.76
  4902.0 1710.97  5013.9 1708.33  5014.4 1707.83  5030.7 1708.33  5102.4 1713.75
  5164.2 1714.38  5263.0 1714.57  5279.9 1714.48  5307.6 1715.64  5354.5 1715.16
  5456.2 1716.59  5521.7 1715.71  5548.8 1716.29  5569.4 1715.33  5592.5 1715.89
#Mann=8,-1,0
  3605.6    0.07       0  3837.0   0.045       0  4700.2    0.07       0
  5013.9    0.07       0  5030.7    0.07       0  5164.2   0.035       0
  5263.0    0.07       0  5279.9   0.045       0
Bank Sta=5013.9,5030.7
Exp/Cntr=0.3,0.1

Type RM Length L Ch R = 1,3598,705,705,705
BEGIN DESCRIPTION:
Mapping XS c6323bf5
END DESCRIPTION:
XS GIS Cut Line= 5
      1518752.10      6906540.16      1519463.04      6906133.91
      1520020.33      6906115.68      1520111.48      6906014.12
      1520200.01      6905475.12
#Sta/Elev= 30
  3788.9 1724.00  3838.1 1724.65  3911.3 1723.52  4026.7 1719.81  4408.2 1715.73
  4483.1 1714.02  4789.8 1711.27  4833.9 1712.43  4929.9 1709.43  4949.9 1709.64
  4981.5 1706.68  4982.0 1706.18  4998.3 1706.68  5019.9 1708.81  5039.9 1709.14
  5059.9 1711.56  5084.9 1711.05  5188.6 1710.87  5244.6 1711.63  5252.1 1712.55
  5348.5 1712.42  5374.2 1713.26  5473.0 1713.54  5622.1 1715.59  5693.1 1715.15
  5713.3 1715.81  5726.5 1714.91  5764.0 1715.82  5787.8 1715.00  5848.0 1715.01
#Mann=8,-1,0
  3788.9    0.07       0  3911.3   0.045       0  4833.9    0.07       0
  4981.5    0.07       0  4998.3    0.07       0  5084.9   0.045       0
  5374.2   0.035       0  5473.0   0.045       0
Bank Sta=4981.5,4998.3
Exp/Cntr=0.3,0.1

Type RM Length L Ch R = 1,2893,312,312,312
BEGIN DESCRIPTION:
Mapping XS 1644c287
END DESCRIPTION:
XS GIS Cut Line= 5
      1519504.71      6907240.68      1519783.35      6906857.87
      1519976.06      6906209.43      1520142.73      6906040.16
      1520236.48      6905443.78
#Sta/Elev= 30
  4171.2 1714.51  4603.1 1714.17  4874.1 1712.37  4894.9 1712.61  4980.6 1706.68
  4981.1 1706.18  4997.4 1706.68  5055.4 1707.30  5072.3 1709.43  5093.8 1709.99
  5214.6 1711.17  5231.8 1710.81  5265.0 1718.37  5280.9 1718.95  5298.2 1718.14
  5303.4 1718.74  5319.3 1714.69  5328.5 1714.15  5335.6 1711.59  5349.7 1710.61
  5526.5 1711.55  5533.6 1712.41  5547.7 1711.99  5571.0 1713.00  5581.1 1711.95
  5591.3 1712.65  5656.4 1712.68  5755.1 1713.10  6046.8 1715.21  6162.4 1715.15
#Mann=7,-1,0
  4171.2   0.045       0  4874.1    0.07       0  4980.6    0.07       0
  4997.4    0.07       0  5214.6   0.045       0  5656.4   0.035       0
  5755.1   0.045       0
Bank Sta=4980.6,4997.4
Exp/Cntr=0.3,0.1

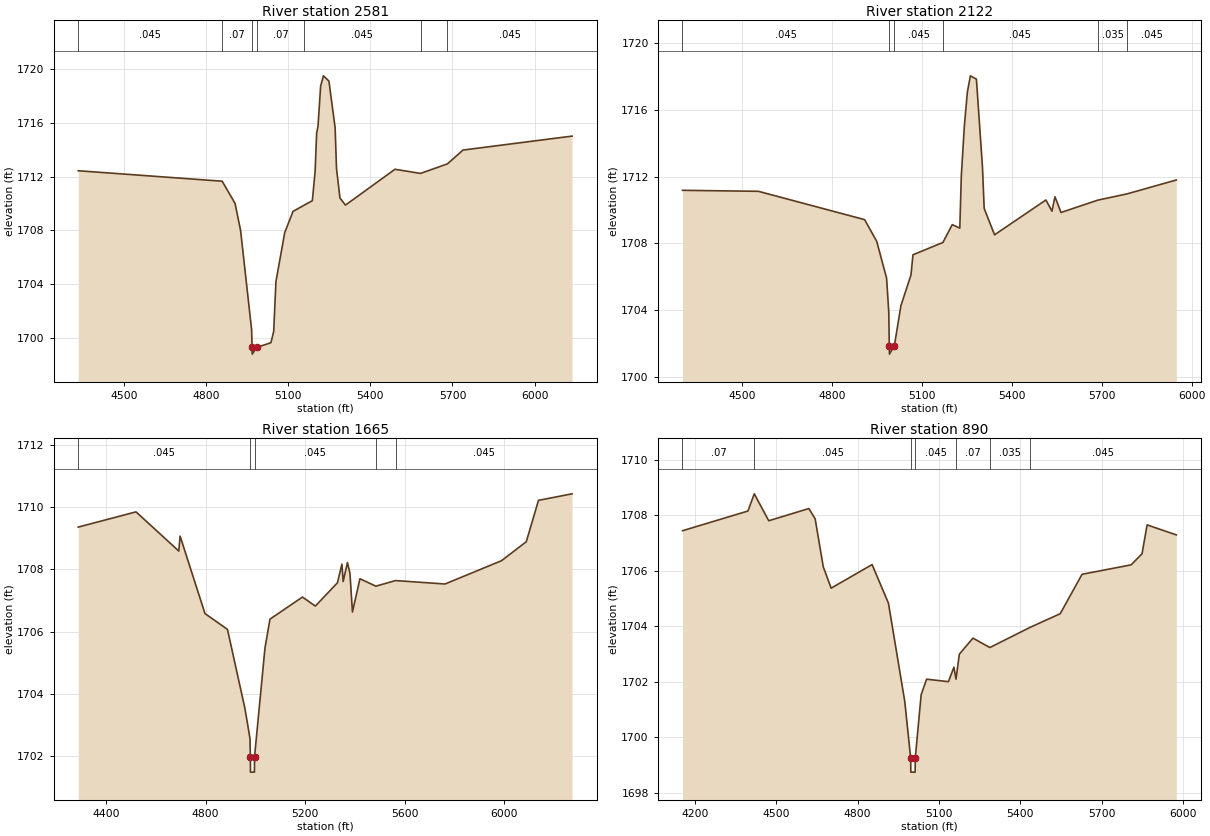
Type RM Length L Ch R = 1,2581,459,459,459
BEGIN DESCRIPTION:
Mapping XS f2611e3f
END DESCRIPTION:
XS GIS Cut Line= 3
      1520050.72      6907185.96      1520179.19      6906255.43
      1520272.93      6905394.37
#Sta/Elev= 30
  4331.8 1712.43  4858.1 1711.65  4905.1 1710.00  4925.3 1708.00  4965.7 1700.59
  4967.4 1699.27  4967.9 1698.77  4984.2 1699.27  5036.4 1699.62  5046.5 1700.47
  5054.6 1704.17  5086.9 1707.83  5117.1 1709.40  5157.5 1709.86  5187.8 1710.20
  5197.9 1712.39  5203.5 1715.23  5208.5 1715.75  5218.1 1718.74  5228.2 1719.50
  5248.4 1719.11  5271.1 1715.62  5276.1 1712.59  5288.7 1710.40  5308.8 1709.87
  5489.9 1712.54  5583.3 1712.23  5681.5 1712.94  5738.5 1713.97  6137.3 1715.01
#Mann=7,-1,0
  4331.8   0.045       0  4858.1    0.07       0  4967.4    0.07       0
  4984.2    0.07       0  5157.5   0.045       0  5583.3   0.035       0
  5681.5   0.045       0
Bank Sta=4967.4,4984.2
Exp/Cntr=0.3,0.1

Type RM Length L Ch R = 1,2122,457,457,457
BEGIN DESCRIPTION:
Mapping XS c644b185
END DESCRIPTION:
XS GIS Cut Line= 3
      1520345.84      6907307.55      1520509.05      6906828.35
      1520647.94      6905696.37
#Sta/Elev= 30
  4302.2 1711.19  4555.3 1711.13  4909.5 1709.43  4949.8 1708.13  4982.8 1705.92
  4990.1 1703.86  4991.8 1701.86  4992.3 1701.36  5008.7 1701.86  5030.4 1704.26
  5064.1 1706.11  5070.7 1707.32  5170.6 1708.06  5201.7 1709.13  5226.9 1708.92
  5231.9 1712.03  5242.0 1715.03  5252.1 1717.08  5262.2 1718.06  5282.3 1717.86
  5302.5 1712.58  5308.2 1710.10  5342.8 1708.52  5514.0 1710.61  5534.2 1709.94
  5544.3 1710.80  5564.4 1709.86  5687.2 1710.60  5785.5 1710.98  5948.9 1711.81
#Mann=6,-1,0
  4302.2   0.045       0  4991.8    0.07       0  5008.7   0.045       0
  5170.6   0.045       0  5687.2   0.035       0  5785.5   0.045       0
Bank Sta=4991.8,5008.7
Exp/Cntr=0.3,0.1

Type RM Length L Ch R = 1,1665,775,775,775
BEGIN DESCRIPTION:
Mapping XS d800b305
END DESCRIPTION:
XS GIS Cut Line= 4
      1520821.54      6907241.58      1520932.66      6906842.24
      1521015.99      6905904.74      1520880.89      6905291.56
#Sta/Elev= 30
  4288.1 1709.36  4520.2 1709.85  4692.1 1708.59  4697.3 1709.07  4797.2 1706.58
  4887.6 1706.07  4957.9 1703.52  4977.9 1702.57  4979.5 1701.98  4980.0 1701.48
  4995.9 1701.48  4996.4 1701.98  5038.2 1705.47  5058.3 1706.40  5188.8 1707.11
  5240.6 1706.82  5329.3 1707.57  5347.3 1708.17  5352.3 1707.61  5369.5 1708.22
  5379.5 1707.88  5389.6 1706.63  5419.7 1707.70  5483.4 1707.46  5562.7 1707.64
  5761.4 1707.53  5988.6 1708.28  6087.9 1708.89  6136.8 1710.22  6271.7 1710.43
#Mann=5,-1,0
  4288.1   0.045       0  4979.5   0.045       0  4996.4   0.045       0
  5483.4   0.035       0  5562.7   0.045       0
Bank Sta=4979.5,4996.4
Exp/Cntr=0.3,0.1

Type RM Length L Ch R = 1,890,0,0,0
BEGIN DESCRIPTION:
NC Unknown Stream 79 1.0
END DESCRIPTION:
XS GIS Cut Line= 3
      1521318.06      6907258.94      1521554.19      6906696.41
      1521429.26      6905492.25
#Sta/Elev= 30
  4154.6 1707.44  4395.9 1708.15  4419.2 1708.77  4472.6 1707.80  4620.6 1708.24
  4643.7 1707.87  4673.6 1706.14  4702.7 1705.37  4853.6 1706.22  4913.9 1704.83
  4974.2 1701.28  4995.9 1699.24  4996.4 1698.74  5012.3 1698.74  5012.8 1699.24
  5034.5 1701.53  5054.6 1702.09  5135.1 1702.00  5155.2 1702.52  5163.0 1702.09
  5175.3 1702.99  5225.5 1703.57  5287.8 1703.23  5436.7 1703.96  5547.3 1704.45
  5627.7 1705.87  5808.7 1706.21  5848.9 1706.61  5867.6 1707.65  5975.3 1707.29
#Mann=7,-1,0
  4154.6    0.07       0  4419.2   0.045       0  4995.9   0.045       0
  5012.8   0.045       0  5163.0    0.07       0  5287.8   0.035       0
  5436.7   0.045       0
Bank Sta=4995.9,5012.8
Exp/Cntr=0.3,0.1

Chan Stop Cuts=-1