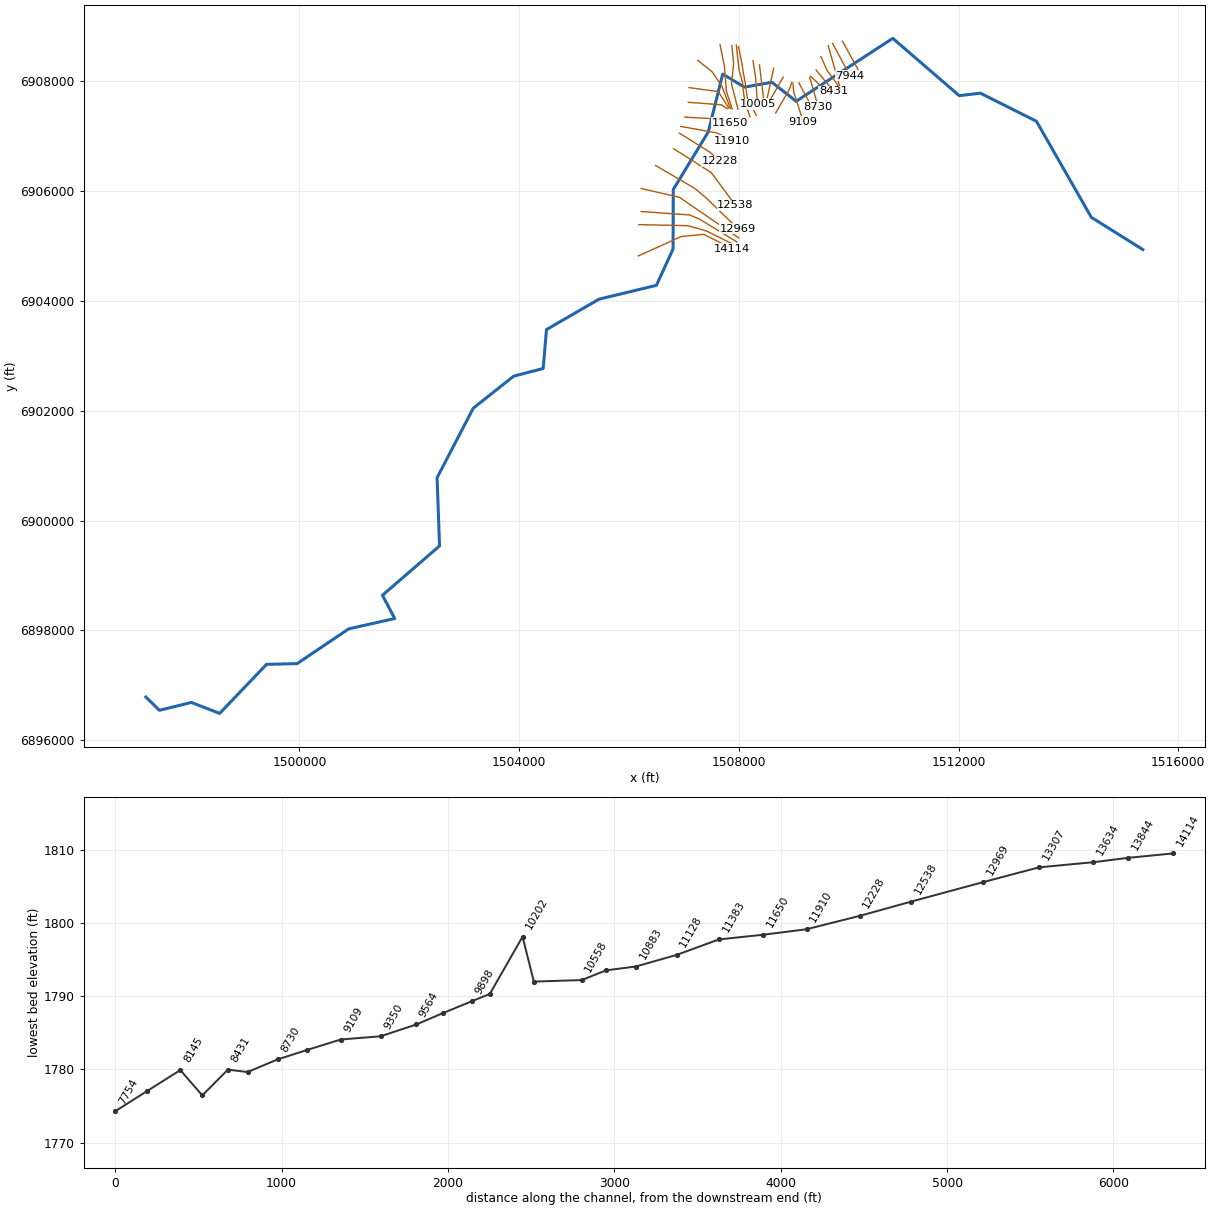
--- NC Unknown Stream 82.prj (project) ---

Proj Title=NC Unknown Stream 82 Base Level Engineering
Current Plan=p01
Default Exp/Contr=0.3,0.1
English Units
Geom File=g01
Flow File=f01
Plan File=p01
BEGIN DESCRIPTION:
NC Unknown Stream 82
END DESCRIPTION:

--- NC Unknown Stream 82.p01 (plan) ---

Plan Title=Multiple Run
Short Identifier=Multiple
Geom File=g01
Flow File=f01
Subcritical Flow
K Sum by GR= 0
Std Step Tol= 0.01
Critical Tol= 0.01
Num of Std Step Trials= 20
Max Error Tol= 0.3
Flow Tol Ratio= 0.001
Split Flow NTrial= 30
Split Flow Tol= 0.02
Split Flow Ratio= 0.02
Log Output Level= 0
Friction Slope Method= 1
Unsteady Friction Slope Method= 2
Unsteady Bridges Friction Slope Method= 1
Parabolic Critical Depth
Global Vel Dist=  1 , 1 , 1
Global Log Level= 0
CheckData=True
Encroach Param= -1, 0, 0, 0
BEGIN DESCRIPTION:
Multiple Run
END DESCRIPTION:

--- NC Unknown Stream 82.f01 (steady flow) ---

Flow Title=Multiple
Number of Profiles=7
Profile Names=10-year,25-year,50-year,1pct_min,100-year,1pct_plu,500-year
River Rch & RM= NC Unknown Strea,Reach-1,14114
     399     551     674     408     815    1626    1207
River Rch & RM= NC Unknown Strea,Reach-1,10005
     643     916    1147     711    1419    2831    2199
Boundary for River Rch & Prof#=NC Unknown Strea,Reach-1,1
Up Type=0
Dn Type=3
Dn Slope=0.001
Boundary for River Rch & Prof#=NC Unknown Strea,Reach-1,2
Up Type=0
Dn Type=3
Dn Slope=0.001
Boundary for River Rch & Prof#=NC Unknown Strea,Reach-1,3
Up Type=0
Dn Type=3
Dn Slope=0.001
Boundary for River Rch & Prof#=NC Unknown Strea,Reach-1,4
Up Type=0
Dn Type=3
Dn Slope=0.001
Boundary for River Rch & Prof#=NC Unknown Strea,Reach-1,5
Up Type=0
Dn Type=3
Dn Slope=0.001
Boundary for River Rch & Prof#=NC Unknown Strea,Reach-1,6
Up Type=0
Dn Type=3
Dn Slope=0.001
Boundary for River Rch & Prof#=NC Unknown Strea,Reach-1,7
Up Type=0
Dn Type=3
Dn Slope=0.001

--- NC Unknown Stream 82.g01 (geometry) ---

Geom Title=Existing Conditions

River Reach=NC Unknown Strea,Reach-1
Reach XY= 30
      1497205.00      6896788.00      1497451.58      6896545.79
      1498034.80      6896688.37      1498548.97      6896489.62
      1499402.30      6897382.64      1499958.42      6897395.79
      1500897.95      6898028.82      1501735.99      6898217.52
      1501512.69      6898641.67      1502551.85      6899539.63
      1502507.25      6900782.07      1503165.51      6902047.81
      1503902.45      6902632.27      1504438.79      6902771.33
      1504498.81      6903480.14      1505456.47      6904034.45
      1506499.88      6904285.71      1506803.80      6904948.50
      1506807.24      6906032.07      1507445.42      6907081.45
      1507706.47      6908134.47      1508101.33      6907895.69
      1508603.53      6907984.47      1509044.52      6907638.93
      1510803.37      6908784.88      1512013.34      6907740.98
      1512399.33      6907786.02      1513418.36      6907274.60
      1514418.48      6905524.44      1515355.00      6904938.00

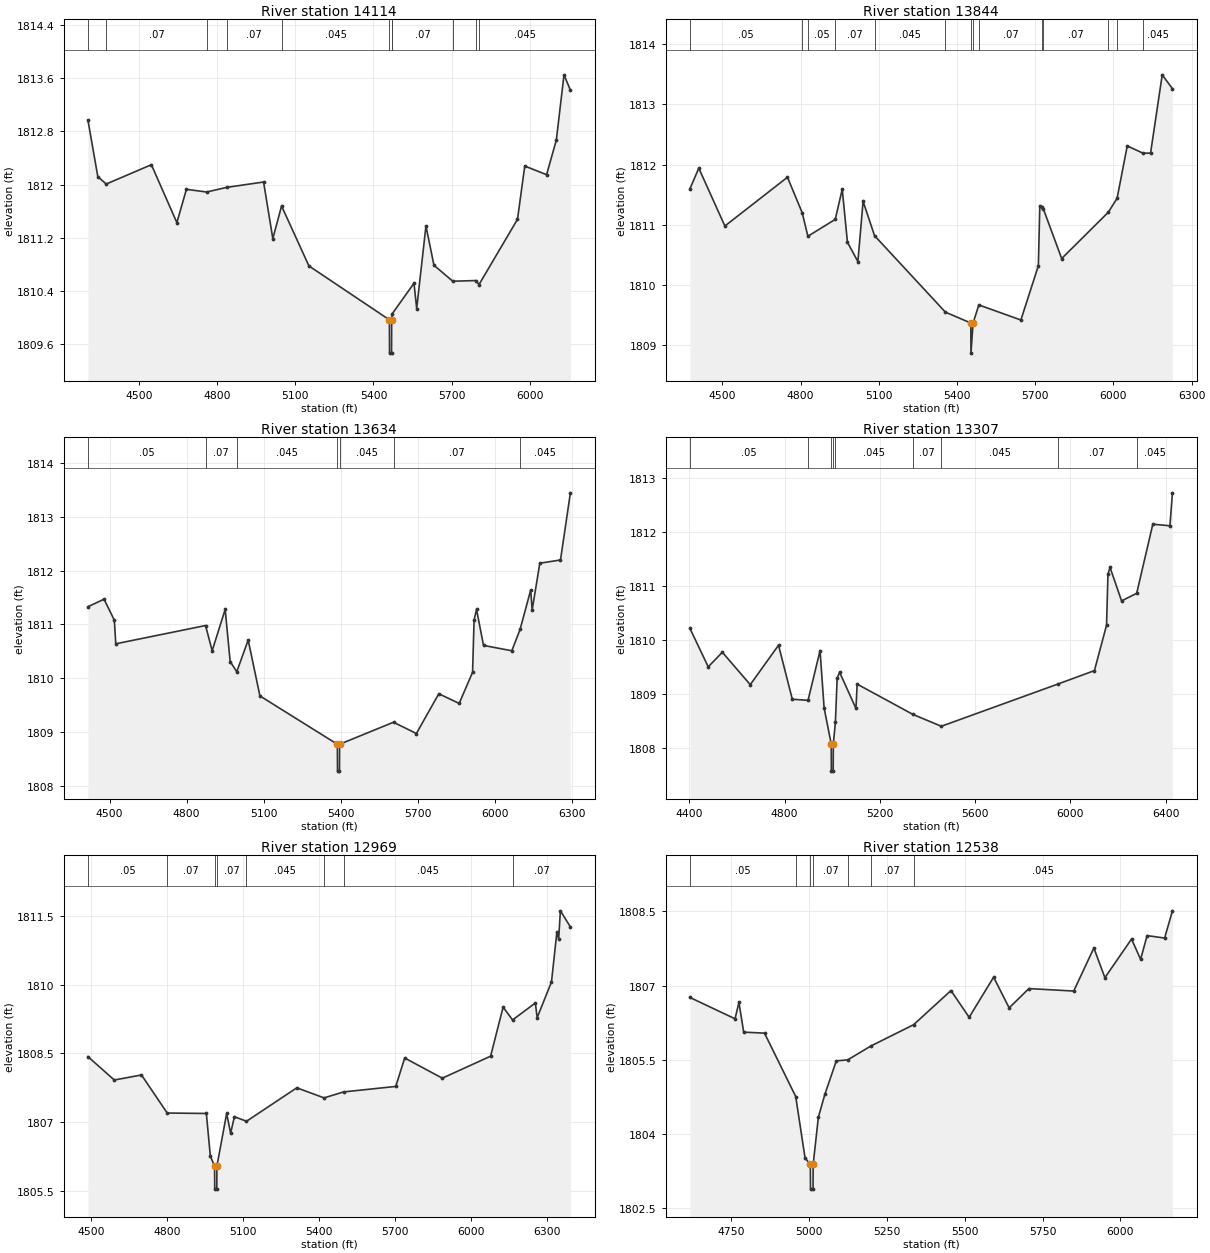
Type RM Length L Ch R = 1,14114,270,270,270
BEGIN DESCRIPTION:
Mapping XS 0dc0460e
END DESCRIPTION:
XS GIS Cut Line= 4
      1506170.33      6904821.31      1506951.58      6905175.04
      1507362.60      6905214.28      1507883.27      6904952.64
#Sta/Elev= 30
  4303.3 1812.97  4341.4 1812.12  4373.8 1812.01  4547.1 1812.30  4645.0 1811.43
  4681.6 1811.93  4759.6 1811.89  4836.9 1811.96  4978.0 1812.04  5013.5 1811.19
  5047.1 1811.68  5152.1 1810.78  5461.3 1809.97  5461.8 1809.47  5469.5 1809.47
  5470.0 1809.97  5472.0 1810.06  5555.7 1810.52  5566.1 1810.14  5601.7 1811.38
  5632.4 1810.79  5704.7 1810.55  5793.0 1810.56  5805.5 1810.50  5953.3 1811.48
  5981.2 1812.28  6065.0 1812.15  6102.5 1812.67  6131.9 1813.65  6156.5 1813.42
#Mann=11,-1,0
  4303.3    0.05       0  4373.8    0.07       0  4759.6   0.045       0
  4836.9    0.07       0  5047.1   0.045       0  5461.3    0.07       0
  5470.0   0.045       0  5472.0    0.07       0  5704.7   0.045       0
  5793.0    0.07       0  5805.5   0.045       0
Bank Sta=5461.3,5470
Exp/Cntr=0.3,0.1

Type RM Length L Ch R = 1,13844,210,210,210
BEGIN DESCRIPTION:
Mapping XS af937314
END DESCRIPTION:
XS GIS Cut Line= 4
      1506181.15      6905392.05      1507075.27      6905372.52
      1507415.64      6905274.10      1507953.61      6905004.71
#Sta/Elev= 30
  4376.0 1811.60  4409.9 1811.94  4509.9 1810.98  4749.9 1811.79  4806.5 1811.20
  4828.2 1810.81  4933.1 1811.09  4960.0 1811.59  4980.0 1810.71  5020.0 1810.39
  5040.0 1811.39  5083.8 1810.82  5355.7 1809.55  5453.1 1809.37  5453.6 1808.87
  5461.8 1809.37  5483.8 1809.67  5645.1 1809.42  5712.1 1810.32  5717.7 1811.32
  5725.9 1811.29  5731.6 1811.26  5801.5 1810.44  5980.6 1811.21  6014.0 1811.44
  6053.0 1812.31  6112.8 1812.19  6142.4 1812.19  6187.1 1813.49  6226.3 1813.26
#Mann=14,-1,0
  4376.0    0.05       0  4806.5    0.07       0  4828.2    0.05       0
  4933.1    0.07       0  5083.8   0.045       0  5355.7    0.07       0
  5453.1    0.07       0  5461.8    0.07       0  5483.8    0.07       0
  5725.9   0.045       0  5731.6    0.07       0  5980.6   0.045       0
  6014.0    0.07       0  6112.8   0.045       0
Bank Sta=5453.1,5461.8
Exp/Cntr=0.3,0.1

Type RM Length L Ch R = 1,13634,327,327,327
BEGIN DESCRIPTION:
Mapping XS c0a89388
END DESCRIPTION:
XS GIS Cut Line= 4
      1506222.38      6905630.77      1507103.49      6905567.83
      1507280.92      6905494.89      1507966.59      6905075.04
#Sta/Elev= 30
  4415.9 1811.33  4478.7 1811.47  4518.8 1811.08  4524.4 1810.64  4874.1 1810.98
  4899.8 1810.51  4950.5 1811.28  4969.9 1810.31  4995.7 1810.12  5040.1 1810.71
  5085.8 1809.67  5387.5 1808.77  5388.0 1808.27  5395.7 1808.27  5396.2 1808.77
  5606.1 1809.18  5695.2 1808.97  5782.6 1809.71  5861.9 1809.53  5914.1 1810.11
  5919.9 1811.08  5929.5 1811.28  5956.7 1810.61  6066.9 1810.51  6099.3 1810.91
  6140.4 1811.64  6146.2 1811.27  6176.0 1812.14  6256.5 1812.20  6295.1 1813.45
#Mann=7,-1,0
  4415.9    0.05       0  4874.1    0.07       0  4995.7   0.045       0
  5387.5   0.045       0  5396.2   0.045       0  5606.1    0.07       0
  6099.3   0.045       0
Bank Sta=5387.5,5396.2
Exp/Cntr=0.3,0.1

Type RM Length L Ch R = 1,13307,338,338,338
BEGIN DESCRIPTION:
Mapping XS 6d01c12a
END DESCRIPTION:
XS GIS Cut Line= 4
      1506222.45      6906049.60      1506921.19      6905889.01
      1507253.58      6905659.06      1508001.57      6905148.97
#Sta/Elev= 30
  4402.3 1810.21  4479.1 1809.50  4538.3 1809.77  4655.6 1809.17  4774.3 1809.90
  4832.2 1808.90  4898.3 1808.88  4948.7 1809.80  4965.8 1808.74  4995.7 1808.07
  4996.2 1807.57  5003.9 1807.57  5004.4 1808.07  5013.2 1808.48  5020.6 1809.29
  5030.8 1809.40  5099.5 1808.73  5104.6 1809.18  5338.6 1808.62  5458.1 1808.40
  5946.9 1809.18  6101.1 1809.43  6152.0 1810.27  6158.0 1811.22  6166.7 1811.34
  6215.1 1810.72  6278.6 1810.86  6346.4 1812.14  6418.2 1812.11  6428.8 1812.72
#Mann=9,-1,0
  4402.3    0.05       0  4898.3    0.07       0  4995.7    0.07       0
  5004.4    0.07       0  5013.2   0.045       0  5338.6    0.07       0
  5458.1   0.045       0  5946.9    0.07       0  6278.6   0.045       0
Bank Sta=4995.7,5004.4
Exp/Cntr=0.3,0.1

Type RM Length L Ch R = 1,12969,431,431,431
BEGIN DESCRIPTION:
Mapping XS 818b7a7a
END DESCRIPTION:
XS GIS Cut Line= 4
      1506485.03      6906468.42      1507198.97      6906051.77
      1507398.54      6905884.46      1507987.44      6905314.63
#Sta/Elev= 30
  4487.6 1808.43  4591.8 1807.92  4699.3 1808.03  4800.8 1807.20  4955.6 1807.19
  4971.3 1806.26  4988.2 1806.04  4988.7 1805.54  4996.8 1805.54  4997.3 1806.04
  5035.8 1807.19  5051.5 1806.76  5066.5 1807.12  5114.2 1807.02  5313.0 1807.75
  5420.7 1807.53  5497.8 1807.66  5704.0 1807.78  5739.3 1808.40  5888.0 1807.96
  6078.8 1808.44  6128.2 1809.51  6165.6 1809.23  6255.6 1809.60  6262.8 1809.28
  6319.4 1810.06  6340.5 1811.14  6347.7 1811.00  6354.6 1811.61  6394.1 1811.26
#Mann=8,-1,0
  4487.6    0.05       0  4800.8    0.07       0  4988.2    0.07       0
  4997.3    0.07       0  5114.2   0.045       0  5420.7    0.07       0
  5497.8   0.045       0  6165.6    0.07       0
Bank Sta=4988.2,4997.3
Exp/Cntr=0.3,0.1

Type RM Length L Ch R = 1,12538,310,310,310
BEGIN DESCRIPTION:
Mapping XS ba7a44c2
END DESCRIPTION:
XS GIS Cut Line= 3
      1506812.69      6906774.43      1507496.57      6906341.17
      1507937.96      6905746.93
#Sta/Elev= 30
  4617.1 1806.76  4761.9 1806.33  4774.4 1806.66  4789.7 1806.06  4856.6 1806.04
  4956.8 1804.76  4986.8 1803.52  5003.8 1803.39  5004.3 1802.89  5012.4 1802.89
  5012.9 1803.39  5029.5 1804.34  5050.7 1804.81  5087.2 1805.48  5123.7 1805.50
  5198.2 1805.78  5335.4 1806.21  5455.5 1806.90  5513.9 1806.36  5592.5 1807.17
  5642.4 1806.55  5705.8 1806.94  5849.8 1806.89  5914.5 1807.76  5949.9 1807.16
  6035.5 1807.94  6064.7 1807.53  6085.5 1808.01  6141.8 1807.96  6166.9 1808.51
#Mann=7,-1,0
  4617.1    0.05       0  4956.8    0.07       0  5003.8    0.07       0
  5012.9    0.07       0  5123.7   0.045       0  5198.2    0.07       0
  5335.4   0.045       0
Bank Sta=5003.8,5012.9
Exp/Cntr=0.3,0.1

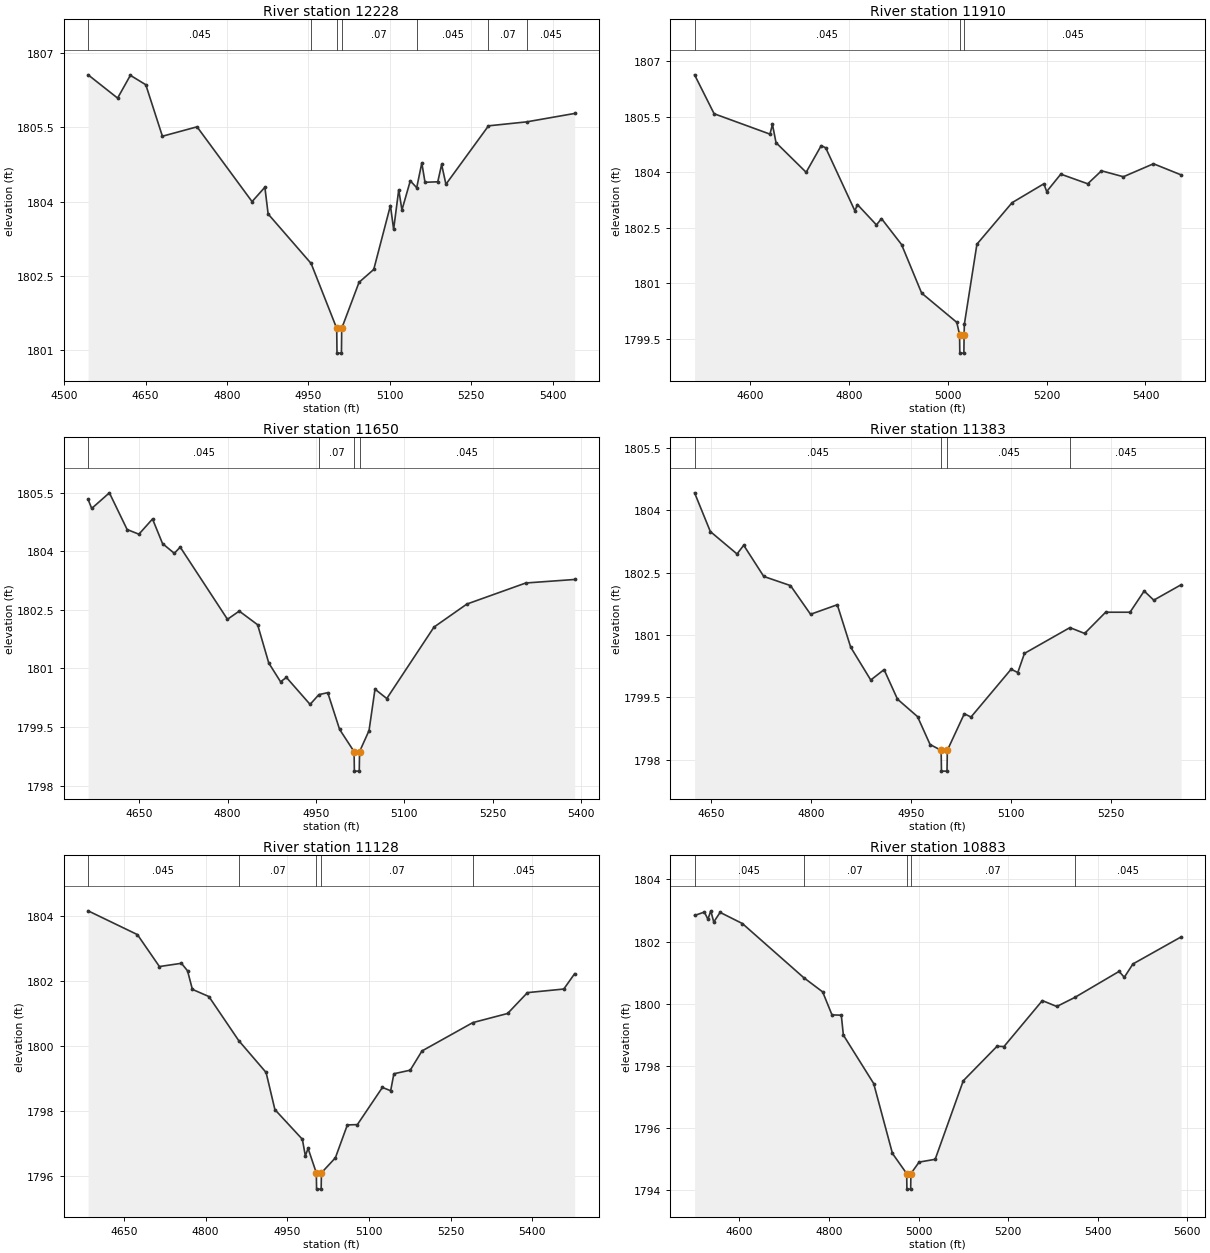
Type RM Length L Ch R = 1,12228,318,318,318
BEGIN DESCRIPTION:
Mapping XS 1a27ad3a
END DESCRIPTION:
XS GIS Cut Line= 3
      1506919.01      6907058.73      1507474.58      6906711.50
      1507650.15      6906546.77
#Sta/Elev= 30
  4544.3 1806.56  4598.6 1806.09  4622.1 1806.55  4650.5 1806.36  4681.1 1805.32
  4744.9 1805.51  4846.2 1804.00  4869.8 1804.29  4875.8 1803.75  4955.0 1802.75
  5002.1 1801.44  5002.6 1800.94  5010.8 1800.94  5011.3 1801.44  5043.2 1802.37
  5070.3 1802.63  5101.0 1803.92  5106.9 1803.44  5116.3 1804.24  5122.2 1803.83
  5137.6 1804.42  5149.4 1804.28  5158.8 1804.78  5164.7 1804.39  5188.2 1804.40
  5195.3 1804.75  5203.2 1804.35  5281.6 1805.53  5351.8 1805.61  5440.2 1805.78
#Mann=7,-1,0
  4544.3   0.045       0  4955.0    0.07       0  5002.1    0.07       0
  5011.3    0.07       0  5149.4   0.045       0  5281.6    0.07       0
  5351.8   0.045       0
Bank Sta=5002.1,5011.3
Exp/Cntr=0.3,0.1

Type RM Length L Ch R = 1,11910,260,260,260
BEGIN DESCRIPTION:
Mapping XS f55ce1c0
END DESCRIPTION:
XS GIS Cut Line= 3
      1506942.88      6907180.25      1507600.45      6907063.06
      1507881.31      6906918.31
#Sta/Elev= 30
  4488.1 1806.63  4527.6 1805.58  4640.5 1805.03  4645.6 1805.29  4652.8 1804.80
  4713.7 1804.00  4744.2 1804.72  4753.3 1804.66  4812.3 1802.96  4817.4 1803.13
  4855.9 1802.58  4866.1 1802.75  4906.7 1802.05  4947.3 1800.74  5018.4 1799.95
  5024.0 1799.62  5024.5 1799.12  5032.7 1799.12  5033.2 1799.62  5033.7 1799.90
  5059.1 1802.06  5130.2 1803.18  5194.5 1803.69  5200.2 1803.48  5228.7 1803.95
  5283.2 1803.69  5311.0 1804.04  5355.3 1803.88  5416.2 1804.23  5472.0 1803.93
#Mann=3,-1,0
  4488.1   0.045       0  5024.0   0.045       0  5033.2   0.045       0
Bank Sta=5024,5033.2
Exp/Cntr=0.3,0.1

Type RM Length L Ch R = 1,11650,267,267,267
BEGIN DESCRIPTION:
Mapping XS 36eedeb8
END DESCRIPTION:
XS GIS Cut Line= 3
      1507018.93      6907349.09      1507661.32      6907312.63
      1507833.17      6907251.87
#Sta/Elev= 30
  4563.2 1805.33  4569.3 1805.10  4599.3 1805.50  4629.4 1804.56  4649.4 1804.44
  4672.5 1804.83  4689.5 1804.20  4709.5 1803.95  4719.5 1804.11  4799.7 1802.26
  4819.7 1802.47  4850.9 1802.12  4869.8 1801.14  4889.8 1800.66  4899.8 1800.77
  4939.9 1800.08  4954.9 1800.33  4969.9 1800.38  4990.0 1799.44  5014.6 1798.87
  5015.1 1798.37  5023.4 1798.37  5023.9 1798.87  5040.0 1799.41  5050.1 1800.47
  5070.1 1800.23  5150.2 1802.06  5206.0 1802.65  5306.0 1803.19  5388.9 1803.28
#Mann=4,-1,0
  4563.2   0.045       0  4954.9    0.07       0  5014.6    0.07       0
  5023.9   0.045       0
Bank Sta=5014.6,5023.9
Exp/Cntr=0.3,0.1

Type RM Length L Ch R = 1,11383,255,255,255
BEGIN DESCRIPTION:
Mapping XS 1d75929c
END DESCRIPTION:
XS GIS Cut Line= 3
      1507081.47      6907619.92      1507678.68      6907574.78
      1507789.75      6907505.36
#Sta/Elev= 30
  4625.5 1804.42  4649.1 1803.49  4689.2 1802.95  4699.2 1803.16  4729.3 1802.41
  4769.4 1802.19  4799.5 1801.50  4839.6 1801.73  4859.7 1800.71  4889.8 1799.92
  4909.8 1800.17  4929.9 1799.46  4960.0 1799.04  4978.8 1798.37  4995.4 1798.23
  4995.9 1797.73  5004.2 1797.73  5004.7 1798.23  5030.2 1799.11  5040.2 1799.03
  5100.4 1800.18  5110.4 1800.10  5120.4 1800.56  5188.6 1801.18  5210.7 1801.04
  5242.2 1801.55  5278.8 1801.55  5300.0 1802.06  5314.4 1801.84  5355.4 1802.21
#Mann=4,-1,0
  4625.5   0.045       0  4995.4    0.07       0  5004.7   0.045       0
  5188.6   0.045       0
Bank Sta=4995.4,5004.7
Exp/Cntr=0.3,0.1

Type RM Length L Ch R = 1,11128,245,245,245
BEGIN DESCRIPTION:
Mapping XS 376cfe95
END DESCRIPTION:
XS GIS Cut Line= 3
      1507095.33      6907887.28      1507626.60      6907814.36
      1507819.31      6907514.01
#Sta/Elev= 30
  4584.4 1804.15  4674.9 1803.42  4715.3 1802.44  4755.7 1802.54  4766.9 1802.31
  4775.8 1801.74  4806.1 1801.52  4860.8 1800.17  4911.1 1799.19  4927.3 1798.05
  4977.7 1797.14  4983.2 1796.63  4988.2 1796.86  5003.3 1796.11  5003.8 1795.61
  5012.2 1795.61  5012.7 1796.11  5038.3 1796.57  5060.3 1797.58  5078.7 1797.59
  5124.6 1798.73  5139.8 1798.63  5145.7 1799.15  5175.7 1799.26  5197.3 1799.85
  5290.6 1800.72  5354.5 1801.00  5390.9 1801.64  5457.6 1801.75  5477.5 1802.22
#Mann=5,-1,0
  4584.4   0.045       0  4860.8    0.07       0  5003.3    0.07       0
  5012.7    0.07       0  5290.6   0.045       0
Bank Sta=5003.3,5012.7
Exp/Cntr=0.3,0.1

Type RM Length L Ch R = 1,10883,180,180,180
BEGIN DESCRIPTION:
Mapping XS 9bbbc8c8
END DESCRIPTION:
XS GIS Cut Line= 4
      1507251.59      6908385.55      1507512.01      6908177.21
      1507689.10      6907920.26      1507847.08      6907508.81
#Sta/Elev= 30
  4499.8 1802.84  4521.6 1802.95  4529.6 1802.72  4536.0 1802.99  4542.6 1802.63
  4556.8 1802.94  4606.6 1802.58  4743.4 1800.84  4785.8 1800.38  4806.6 1799.64
  4827.4 1799.63  4832.0 1798.99  4899.7 1797.43  4941.6 1795.18  4973.4 1794.53
  4973.9 1794.03  4982.3 1794.03  4982.8 1794.53  5001.1 1794.90  5037.0 1794.99
  5099.8 1797.52  5175.2 1798.63  5190.6 1798.62  5276.3 1800.10  5308.5 1799.91
  5348.6 1800.20  5447.7 1801.04  5459.3 1800.85  5478.6 1801.28  5586.1 1802.15
#Mann=5,-1,0
  4499.8   0.045       0  4743.4    0.07       0  4973.4    0.07       0
  4982.8    0.07       0  5348.6   0.045       0
Bank Sta=4973.4,4982.8
Exp/Cntr=0.3,0.1

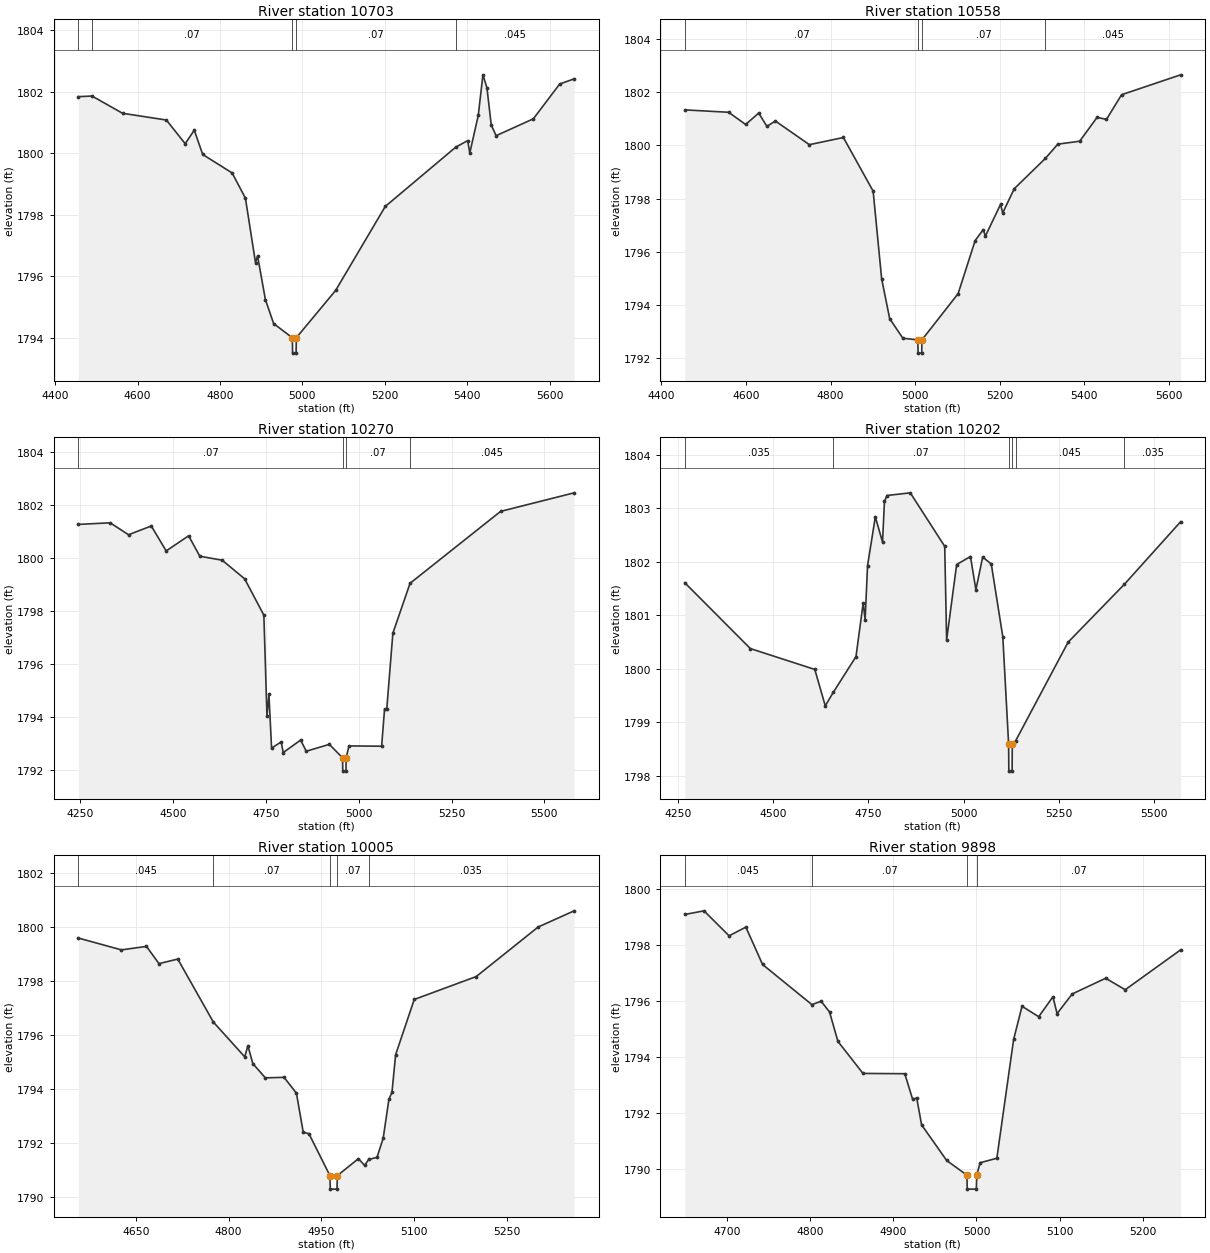
Type RM Length L Ch R = 1,10703,145,145,145
BEGIN DESCRIPTION:
Mapping XS 7d6cecb7
END DESCRIPTION:
XS GIS Cut Line= 4
      1507657.84      6908673.78      1507737.71      6908279.64
      1507774.17      6907821.31      1507880.03      6907496.77
#Sta/Elev= 30
  4456.3 1801.84  4489.6 1801.86  4563.5 1801.30  4670.0 1801.08  4715.6 1800.31
  4737.7 1800.75  4758.1 1799.96  4829.5 1799.36  4861.8 1798.54  4886.3 1796.44
  4891.3 1796.66  4910.3 1795.24  4930.3 1794.46  4975.7 1794.00  4976.2 1793.50
  4984.8 1793.50  4985.3 1794.00  5080.8 1795.54  5201.2 1798.27  5372.4 1800.20
  5401.1 1800.41  5406.3 1800.01  5426.9 1801.23  5438.2 1802.55  5447.9 1802.13
  5458.4 1800.92  5470.1 1800.57  5560.6 1801.12  5624.4 1802.25  5659.6 1802.42
#Mann=5,-1,0
  4456.3   0.045       0  4489.6    0.07       0  4975.7    0.07       0
  4985.3    0.07       0  5372.4   0.045       0
Bank Sta=4975.7,4985.3
Exp/Cntr=0.3,0.1

Type RM Length L Ch R = 1,10558,288,288,288
BEGIN DESCRIPTION:
Mapping XS 5e565788
END DESCRIPTION:
XS GIS Cut Line= 4
      1507873.12      6908651.21      1507906.11      6908319.57
      1507867.92      6907953.25      1507984.24      6907496.62
#Sta/Elev= 30
  4455.2 1801.34  4558.9 1801.25  4599.1 1800.79  4630.0 1801.22  4649.4 1800.72
  4669.5 1800.92  4749.9 1800.03  4830.3 1800.30  4900.7 1798.28  4920.8 1794.98
  4939.8 1793.48  4971.0 1792.74  5006.5 1792.68  5007.0 1792.18  5015.6 1792.18
  5016.1 1792.68  5101.7 1794.42  5142.0 1796.42  5161.1 1796.83  5166.3 1796.59
  5202.0 1797.78  5207.2 1797.46  5234.4 1798.37  5307.9 1799.51  5337.6 1800.05
  5389.2 1800.16  5430.5 1801.06  5452.5 1800.98  5488.3 1801.91  5628.0 1802.66
#Mann=4,-1,0
  4455.2    0.07       0  5006.5    0.07       0  5016.1    0.07       0
  5307.9   0.045       0
Bank Sta=5006.5,5016.1
Exp/Cntr=0.3,0.1

Type RM Length L Ch R = 1,10270,68,68,68
BEGIN DESCRIPTION:
Mapping XS 78bb05eb
END DESCRIPTION:
XS GIS Cut Line= 6
      1507954.73      6908663.29      1508005.07      6908206.72
      1508065.83      6907991.44      1508079.72      6907847.35
      1508107.50      6907647.69      1508201.26      6907356.00
#Sta/Elev= 30
  4244.3 1801.27  4330.1 1801.33  4379.5 1800.88  4440.8 1801.21  4481.0 1800.27
  4541.4 1800.84  4571.6 1800.07  4631.9 1799.92  4692.3 1799.22  4744.1 1797.85
  4752.5 1794.05  4757.8 1794.86  4764.9 1792.84  4790.9 1793.07  4796.2 1792.67
  4843.2 1793.14  4858.4 1792.72  4920.6 1792.98  4956.2 1792.47  4956.7 1791.97
  4965.3 1791.97  4965.8 1792.47  4973.4 1792.92  5061.4 1792.91  5069.3 1794.31
  5075.3 1794.32  5091.7 1797.17  5138.0 1799.05  5381.8 1801.76  5580.1 1802.46
#Mann=4,-1,0
  4244.3    0.07       0  4956.2    0.07       0  4965.8    0.07       0
  5138.0   0.045       0
Bank Sta=4956.2,4965.8
Exp/Cntr=0.3,0.1

Type RM Length L Ch R = 1,10202,197,197,197
BEGIN DESCRIPTION:
Mapping XS d806708a
END DESCRIPTION:
XS GIS Cut Line= 6
      1507996.39      6908630.31      1508062.36      6908295.26
      1508077.99      6908175.47      1508110.97      6908012.28
      1508157.85      6907684.15      1508319.79      6907382.66
#Sta/Elev= 30
  4267.6 1801.61  4439.8 1800.38  4609.1 1799.99  4636.6 1799.31  4657.5 1799.56
  4717.3 1800.23  4736.2 1801.23  4741.3 1800.92  4747.7 1801.93  4768.1 1802.84
  4787.0 1802.37  4792.1 1803.13  4798.7 1803.24  4859.9 1803.29  4950.4 1802.29
  4955.4 1800.54  4981.7 1801.95  5018.0 1802.10  5032.3 1801.48  5050.1 1802.09
  5072.7 1801.96  5103.0 1800.60  5118.3 1798.59  5118.8 1798.09  5127.4 1798.09
  5127.9 1798.59  5136.9 1798.66  5274.6 1800.50  5422.2 1801.58  5570.1 1802.75
#Mann=6,-1,0
  4267.6   0.035       0  4657.5    0.07       0  5118.3    0.07       0
  5127.9    0.07       0  5136.9   0.045       0  5422.2   0.035       0
Bank Sta=5118.3,5127.9
Exp/Cntr=0.3,0.1

Type RM Length L Ch R = 1,10005,107,107,107
BEGIN DESCRIPTION:
Mapping XS 0b07b992
END DESCRIPTION:
XS GIS Cut Line= 3
      1508258.54      6908376.89      1508307.15      6908062.63
      1508340.14      6907579.95
#Sta/Elev= 30
  4557.0 1799.60  4626.7 1799.16  4667.2 1799.29  4687.4 1798.65  4717.8 1798.82
  4775.4 1796.48  4826.1 1795.19  4831.2 1795.60  4839.2 1794.94  4859.4 1794.41
  4889.7 1794.43  4909.7 1793.84  4920.7 1792.39  4929.8 1792.34  4963.9 1790.78
  4964.4 1790.28  4975.3 1790.28  4975.8 1790.78  5009.9 1791.41  5020.0 1791.16
  5026.4 1791.38  5040.0 1791.46  5050.0 1792.17  5059.2 1793.61  5064.2 1793.88
  5070.1 1795.27  5100.2 1797.32  5200.4 1798.17  5300.6 1800.01  5358.8 1800.61
#Mann=5,-1,0
  4557.0   0.045       0  4775.4    0.07       0  4963.9    0.07       0
  4975.8    0.07       0  5026.4   0.035       0
Bank Sta=4963.9,4975.8
Exp/Cntr=0.3,0.1

Type RM Length L Ch R = 1,9898,174,174,174
BEGIN DESCRIPTION:
Mapping XS c8435021
END DESCRIPTION:
XS GIS Cut Line= 2
      1508376.59      6908300.93      1508448.21      6907708.44
#Sta/Elev= 30
  4648.9 1799.08  4672.0 1799.21  4702.2 1798.32  4722.4 1798.63  4742.5 1797.30
  4801.9 1795.87  4813.0 1795.99  4823.1 1795.61  4833.2 1794.56  4863.4 1793.42
  4913.7 1793.41  4923.0 1792.51  4928.1 1792.54  4933.9 1791.59  4964.1 1790.32
  4988.4 1789.80  4988.9 1789.30  4999.8 1789.30  5000.3 1789.80  5004.4 1790.24
  5024.5 1790.40  5044.7 1794.63  5054.8 1795.81  5074.9 1795.44  5092.0 1796.15
  5097.0 1795.55  5115.2 1796.25  5155.5 1796.81  5179.0 1796.40  5245.7 1797.82
#Mann=4,-1,0
  4648.9   0.045       0  4801.9    0.07       0  4988.4    0.07       0
  5000.3    0.07       0
Bank Sta=4988.4,5000.3
Exp/Cntr=0.3,0.1

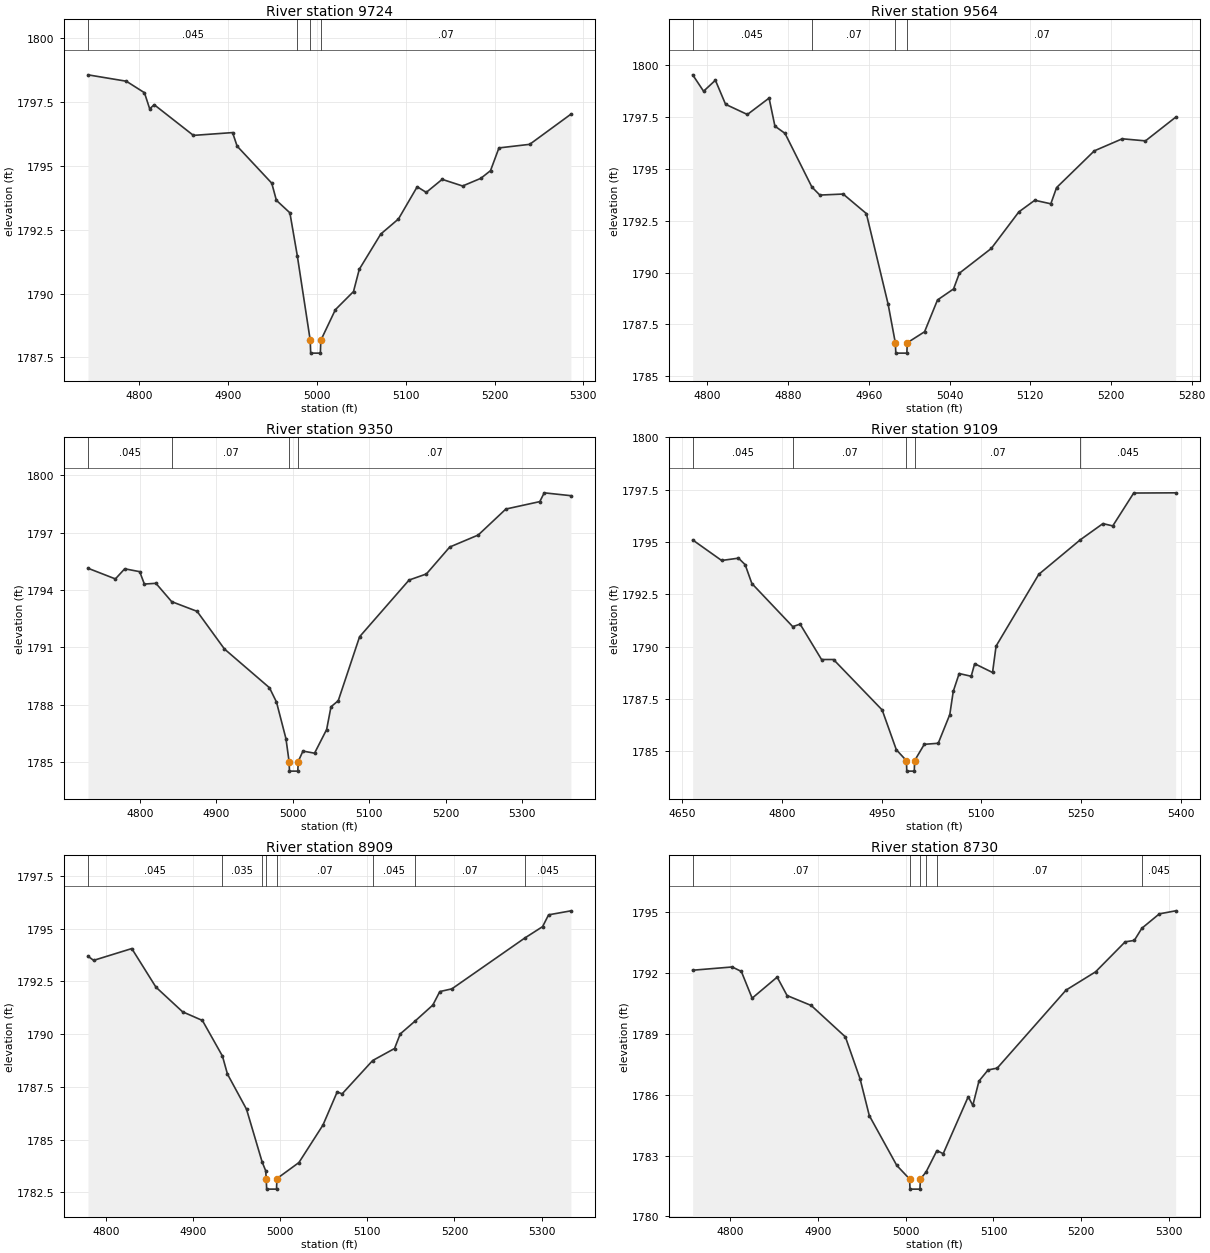
Type RM Length L Ch R = 1,9724,160,160,160
BEGIN DESCRIPTION:
Mapping XS 50bf7869
END DESCRIPTION:
XS GIS Cut Line= 2
      1508634.85      6908240.18      1508519.92      6907708.87
#Sta/Elev= 30
  4742.3 1798.56  4785.5 1798.31  4805.9 1797.86  4811.8 1797.23  4816.9 1797.39
  4861.0 1796.19  4905.1 1796.30  4910.2 1795.77  4949.2 1794.32  4954.4 1793.65
  4969.6 1793.16  4977.9 1791.49  4992.5 1788.17  4993.0 1787.67  5003.9 1787.67
  5004.4 1788.17  5020.8 1789.37  5041.2 1790.08  5047.7 1790.95  5071.9 1792.33
  5091.8 1792.92  5112.9 1794.18  5123.1 1793.96  5141.0 1794.47  5164.0 1794.21
  5184.5 1794.51  5195.4 1794.81  5204.9 1795.70  5239.5 1795.84  5285.9 1797.02
#Mann=4,-1,0
  4742.3   0.045       0  4977.9    0.07       0  4992.5    0.07       0
  5004.4    0.07       0
Bank Sta=4992.5,5004.4
Exp/Cntr=0.3,0.1

Type RM Length L Ch R = 1,9564,214,214,214
BEGIN DESCRIPTION:
Mapping XS 4ca405f8
END DESCRIPTION:
XS GIS Cut Line= 2
      1508808.44      6908077.35      1508570.52      6907662.08
#Sta/Elev= 30
  4785.5 1799.52  4796.3 1798.73  4808.0 1799.26  4818.1 1798.10  4839.7 1797.61
  4861.2 1798.40  4867.0 1797.05  4877.0 1796.70  4903.6 1794.12  4911.5 1793.73
  4934.6 1793.78  4957.6 1792.84  4979.2 1788.47  4986.3 1786.62  4986.8 1786.12
  4997.7 1786.12  4998.2 1786.62  5015.3 1787.15  5028.1 1788.68  5044.0 1789.21
  5049.8 1789.97  5081.4 1791.16  5108.7 1792.92  5124.5 1793.48  5140.4 1793.31
  5146.1 1794.09  5183.5 1795.86  5211.2 1796.44  5234.2 1796.34  5264.1 1797.48
#Mann=4,-1,0
  4785.5   0.045       0  4903.6    0.07       0  4986.3    0.07       0
  4998.2    0.07       0
Bank Sta=4986.3,4998.2
Exp/Cntr=0.3,0.1

Type RM Length L Ch R = 1,9350,241,241,241
BEGIN DESCRIPTION:
Mapping XS 5d8472cd
END DESCRIPTION:
XS GIS Cut Line= 3
      1508964.70      6907981.87      1508921.30      6907858.20
      1508671.75      6907424.19
#Sta/Elev= 30
  4732.3 1795.14  4768.2 1794.58  4780.4 1795.11  4800.0 1794.96  4806.1 1794.31
  4821.2 1794.35  4841.8 1793.39  4875.1 1792.88  4910.8 1790.91  4969.7 1788.88
  4978.9 1788.13  4991.3 1786.21  4995.4 1785.01  4995.9 1784.51  5006.8 1784.51
  5007.3 1785.01  5013.5 1785.56  5028.7 1785.45  5044.5 1786.69  5050.2 1787.88
  5059.7 1788.20  5087.6 1791.55  5152.3 1794.52  5175.0 1794.84  5205.5 1796.25
  5242.8 1796.88  5278.9 1798.24  5323.3 1798.63  5329.1 1799.09  5364.0 1798.94
#Mann=4,-1,0
  4732.3   0.045       0  4841.8    0.07       0  4995.4    0.07       0
  5007.3    0.07       0
Bank Sta=4995.4,5007.3
Exp/Cntr=0.3,0.1

Type RM Length L Ch R = 1,9109,200,200,200
BEGIN DESCRIPTION:
Mapping XS 59aa0cbe
END DESCRIPTION:
XS GIS Cut Line= 3
      1508986.41      6907966.68      1508999.43      6907810.46
      1509173.04      6907267.92
#Sta/Elev= 30
  4665.8 1795.10  4709.3 1794.12  4734.7 1794.23  4744.7 1793.92  4754.8 1793.02
  4816.3 1790.96  4827.4 1791.08  4859.6 1789.39  4877.6 1789.39  4950.8 1786.98
  4972.1 1785.08  4987.3 1784.56  4987.8 1784.06  4999.1 1784.06  4999.6 1784.56
  5014.1 1785.34  5035.1 1785.39  5052.5 1786.76  5057.7 1787.87  5066.6 1788.72
  5084.7 1788.59  5089.9 1789.19  5116.8 1788.77  5122.1 1790.03  5186.4 1793.46
  5248.9 1795.11  5282.8 1795.88  5297.6 1795.77  5329.1 1797.34  5392.2 1797.35
#Mann=5,-1,0
  4665.8   0.045       0  4816.3    0.07       0  4987.3    0.07       0
  4999.6    0.07       0  5248.9   0.045       0
Bank Sta=4987.3,4999.6
Exp/Cntr=0.3,0.1

Type RM Length L Ch R = 1,8909,179,179,179
BEGIN DESCRIPTION:
Mapping XS 5985b18d
END DESCRIPTION:
XS GIS Cut Line= 2
      1509094.24      6907973.69      1509355.96      6907485.41
#Sta/Elev= 30
  4779.6 1793.70  4786.1 1793.50  4829.9 1794.06  4857.6 1792.23  4888.2 1791.06
  4910.9 1790.65  4933.9 1788.96  4939.6 1788.11  4961.5 1786.44  4979.4 1783.94
  4983.5 1783.52  4984.1 1783.15  4984.6 1782.65  4995.9 1782.65  4996.4 1783.15
  5021.6 1783.91  5049.2 1785.69  5065.5 1787.26  5071.2 1787.17  5106.2 1788.75
  5131.3 1789.32  5137.8 1790.01  5155.1 1790.63  5175.2 1791.38  5183.2 1792.02
  5197.1 1792.15  5280.7 1794.56  5301.1 1795.10  5308.0 1795.66  5333.6 1795.85
#Mann=8,-1,0
  4779.6   0.045       0  4933.9   0.035       0  4979.4    0.07       0
  4984.1    0.07       0  4996.4    0.07       0  5106.2   0.045       0
  5155.1    0.07       0  5280.7   0.045       0
Bank Sta=4984.1,4996.4
Exp/Cntr=0.3,0.1

Type RM Length L Ch R = 1,8730,181,181,181
BEGIN DESCRIPTION:
Mapping XS 044f7b3b
END DESCRIPTION:
XS GIS Cut Line= 2
      1509292.19      6908071.28      1509444.49      6907542.78
#Sta/Elev= 30
  4757.5 1792.15  4802.5 1792.31  4812.9 1792.09  4825.2 1790.77  4853.7 1791.81
  4865.0 1790.90  4892.5 1790.41  4931.4 1788.86  4948.2 1786.78  4958.6 1784.98
  4989.9 1782.52  5004.5 1781.85  5005.0 1781.35  5016.3 1781.35  5016.8 1781.85
  5023.2 1782.19  5035.6 1783.25  5042.8 1783.10  5071.3 1785.91  5076.5 1785.48
  5083.5 1786.68  5093.9 1787.23  5104.3 1787.32  5182.7 1791.17  5216.3 1792.07
  5250.0 1793.55  5260.4 1793.62  5269.0 1794.22  5288.9 1794.93  5307.5 1795.08
#Mann=6,-1,0
  4757.5    0.07       0  5004.5    0.07       0  5016.8    0.07       0
  5023.2   0.035       0  5035.6    0.07       0  5269.0   0.045       0
Bank Sta=5004.5,5016.8
Exp/Cntr=0.3,0.1

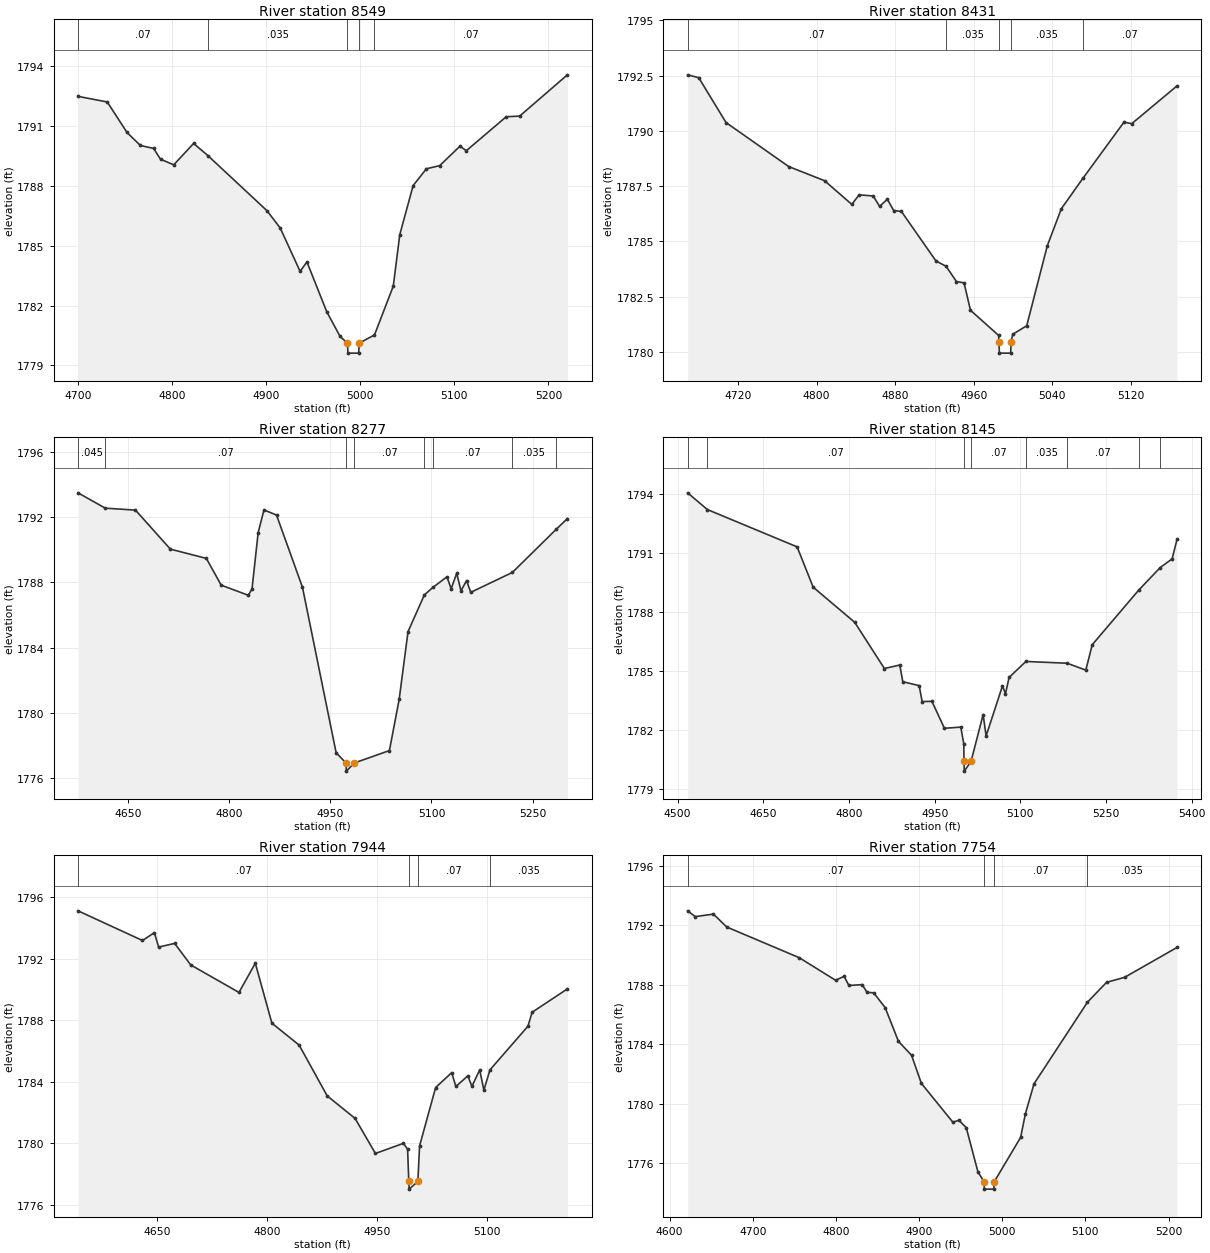
Type RM Length L Ch R = 1,8549,118,118,118
BEGIN DESCRIPTION:
Mapping XS 6bb86704
END DESCRIPTION:
XS GIS Cut Line= 2
      1509307.83      6908094.72      1509684.10      6907735.37
#Sta/Elev= 30
  4699.9 1792.49  4731.0 1792.21  4752.0 1790.68  4766.2 1790.03  4780.3 1789.88
  4787.6 1789.34  4801.7 1789.06  4822.8 1790.13  4838.0 1789.52  4900.8 1786.76
  4914.9 1785.89  4936.0 1783.72  4943.3 1784.19  4964.3 1781.70  4978.5 1780.46
  4986.4 1780.12  4986.9 1779.62  4998.3 1779.62  4998.8 1780.12  5015.1 1780.53
  5035.1 1782.98  5042.0 1785.56  5056.2 1788.02  5070.3 1788.86  5084.5 1789.02
  5105.9 1789.99  5112.8 1789.77  5155.2 1791.47  5169.4 1791.50  5220.2 1793.57
#Mann=5,-1,0
  4699.9    0.07       0  4838.0   0.035       0  4986.4   0.035       0
  4998.8   0.035       0  5015.1    0.07       0
Bank Sta=4986.4,4998.8
Exp/Cntr=0.3,0.1

Type RM Length L Ch R = 1,8431,154,154,154
BEGIN DESCRIPTION:
Mapping XS ae362f71
END DESCRIPTION:
XS GIS Cut Line= 2
      1509408.05      6908206.74      1509725.58      6907822.84
#Sta/Elev= 30
  4668.8 1792.54  4680.1 1792.41  4707.9 1790.38  4771.7 1788.39  4808.2 1787.75
  4835.9 1786.68  4843.4 1787.11  4857.7 1787.06  4864.2 1786.59  4872.1 1786.91
  4878.6 1786.40  4886.4 1786.36  4921.6 1784.12  4931.9 1783.88  4942.4 1783.19
  4950.2 1783.13  4956.7 1781.89  4985.4 1780.75  4985.7 1780.45  4986.2 1779.95
  4997.6 1779.95  4998.1 1780.45  4999.7 1780.80  5014.0 1781.19  5034.9 1784.80
  5049.2 1786.48  5071.2 1787.86  5113.0 1790.40  5120.9 1790.33  5167.0 1792.04
#Mann=5,-1,0
  4668.8    0.07       0  4931.9   0.035       0  4985.7   0.035       0
  4998.1   0.035       0  5071.2    0.07       0
Bank Sta=4985.7,4998.1
Exp/Cntr=0.3,0.1

Type RM Length L Ch R = 1,8277,132,132,132
BEGIN DESCRIPTION:
Mapping XS c286e7bf
END DESCRIPTION:
XS GIS Cut Line= 4
      1509495.32      6908451.48      1509616.40      6908183.28
      1509793.48      6907950.21      1509844.96      6907821.50
#Sta/Elev= 30
  4575.9 1793.49  4616.3 1792.55  4661.1 1792.43  4712.8 1790.04  4766.2 1789.47
  4788.2 1787.83  4828.4 1787.21  4833.9 1787.60  4843.0 1791.05  4851.6 1792.44
  4870.2 1792.13  4908.7 1787.70  4958.6 1777.56  4973.2 1776.93  4973.7 1776.43
  4985.6 1776.93  5037.6 1777.69  5052.1 1780.83  5065.2 1784.98  5089.4 1787.23
  5102.0 1787.69  5122.9 1788.34  5129.2 1787.61  5137.4 1788.56  5143.7 1787.48
  5152.0 1788.11  5158.2 1787.39  5219.9 1788.61  5284.8 1791.25  5301.5 1791.91
#Mann=8,-1,0
  4575.9   0.045       0  4616.3    0.07       0  4973.2    0.07       0
  4985.6    0.07       0  5089.4   0.035       0  5102.0    0.07       0
  5219.9   0.035       0  5284.8    0.07       0
Bank Sta=4973.2,4985.6
Exp/Cntr=0.3,0.1

Type RM Length L Ch R = 1,8145,201,201,201
BEGIN DESCRIPTION:
Mapping XS 47ed097a
END DESCRIPTION:
XS GIS Cut Line= 2
      1509628.13      6908649.39      1509862.50      6907825.17
#Sta/Elev= 30
  4517.5 1794.05  4552.0 1793.20  4709.2 1791.30  4737.3 1789.25  4810.1 1787.46
  4862.0 1785.11  4889.0 1785.29  4894.2 1784.44  4922.9 1784.24  4928.1 1783.43
  4945.2 1783.44  4967.1 1782.07  4995.8 1782.13  5001.0 1781.28  5001.4 1780.39
  5001.9 1779.89  5013.8 1780.39  5034.9 1782.77  5040.1 1781.68  5068.8 1784.23
  5074.0 1783.83  5080.4 1784.66  5109.8 1785.47  5181.9 1785.38  5214.7 1785.03
  5225.9 1786.32  5307.0 1789.09  5345.0 1790.25  5365.8 1790.69  5374.4 1791.68
#Mann=8,-1,0
  4517.5   0.045       0  4552.0    0.07       0  5001.4    0.07       0
  5013.8    0.07       0  5109.8   0.035       0  5181.9    0.07       0
  5307.0   0.035       0  5345.0    0.07       0
Bank Sta=5001.4,5013.8
Exp/Cntr=0.3,0.1

Type RM Length L Ch R = 1,7944,190,190,190
BEGIN DESCRIPTION:
Mapping XS ec669c36
END DESCRIPTION:
XS GIS Cut Line= 2
      1509708.83      6908691.13      1510023.84      6908102.75
#Sta/Elev= 30
  4542.2 1795.12  4630.1 1793.19  4646.4 1793.70  4652.1 1792.76  4674.0 1793.00
  4695.9 1791.60  4761.7 1789.81  4784.0 1791.71  4806.6 1787.81  4843.8 1786.38
  4882.0 1783.08  4920.1 1781.61  4947.8 1779.33  4986.0 1779.99  4991.7 1779.61
  4993.3 1777.51  4993.8 1777.01  5005.7 1777.51  5008.0 1779.82  5029.9 1783.62
  5051.8 1784.59  5057.5 1783.69  5073.8 1784.38  5079.4 1783.70  5090.0 1784.77
  5095.7 1783.45  5104.0 1784.77  5155.8 1787.61  5161.5 1788.52  5209.6 1790.04
#Mann=4,-1,0
  4542.2    0.07       0  4993.3    0.07       0  5005.7    0.07       0
  5104.0   0.035       0
Bank Sta=4993.3,5005.7
Exp/Cntr=0.3,0.1

Type RM Length L Ch R = 1,7754,121,121,121
BEGIN DESCRIPTION:
Mapping XS ffacf71a
END DESCRIPTION:
XS GIS Cut Line= 2
      1509887.24      6908734.04      1510170.55      6908218.11
#Sta/Elev= 30
  4621.6 1792.98  4630.8 1792.59  4652.6 1792.76  4668.7 1791.89  4755.8 1789.83
  4799.6 1788.31  4809.8 1788.58  4815.5 1787.96  4831.6 1788.02  4837.3 1787.50
  4845.3 1787.47  4859.1 1786.48  4875.2 1784.20  4890.9 1783.27  4902.7 1781.38
  4940.6 1778.77  4947.9 1778.90  4956.7 1778.40  4970.7 1775.44  4978.0 1774.77
  4978.5 1774.27  4989.9 1774.27  4990.4 1774.77  5022.1 1777.75  5027.8 1779.33
  5038.2 1781.35  5102.5 1786.84  5125.4 1788.17  5147.2 1788.51  5210.2 1790.52
#Mann=4,-1,0
  4621.6    0.07       0  4978.0    0.07       0  4990.4    0.07       0
  5102.5   0.035       0
Bank Sta=4978,4990.4
Exp/Cntr=0.3,0.1