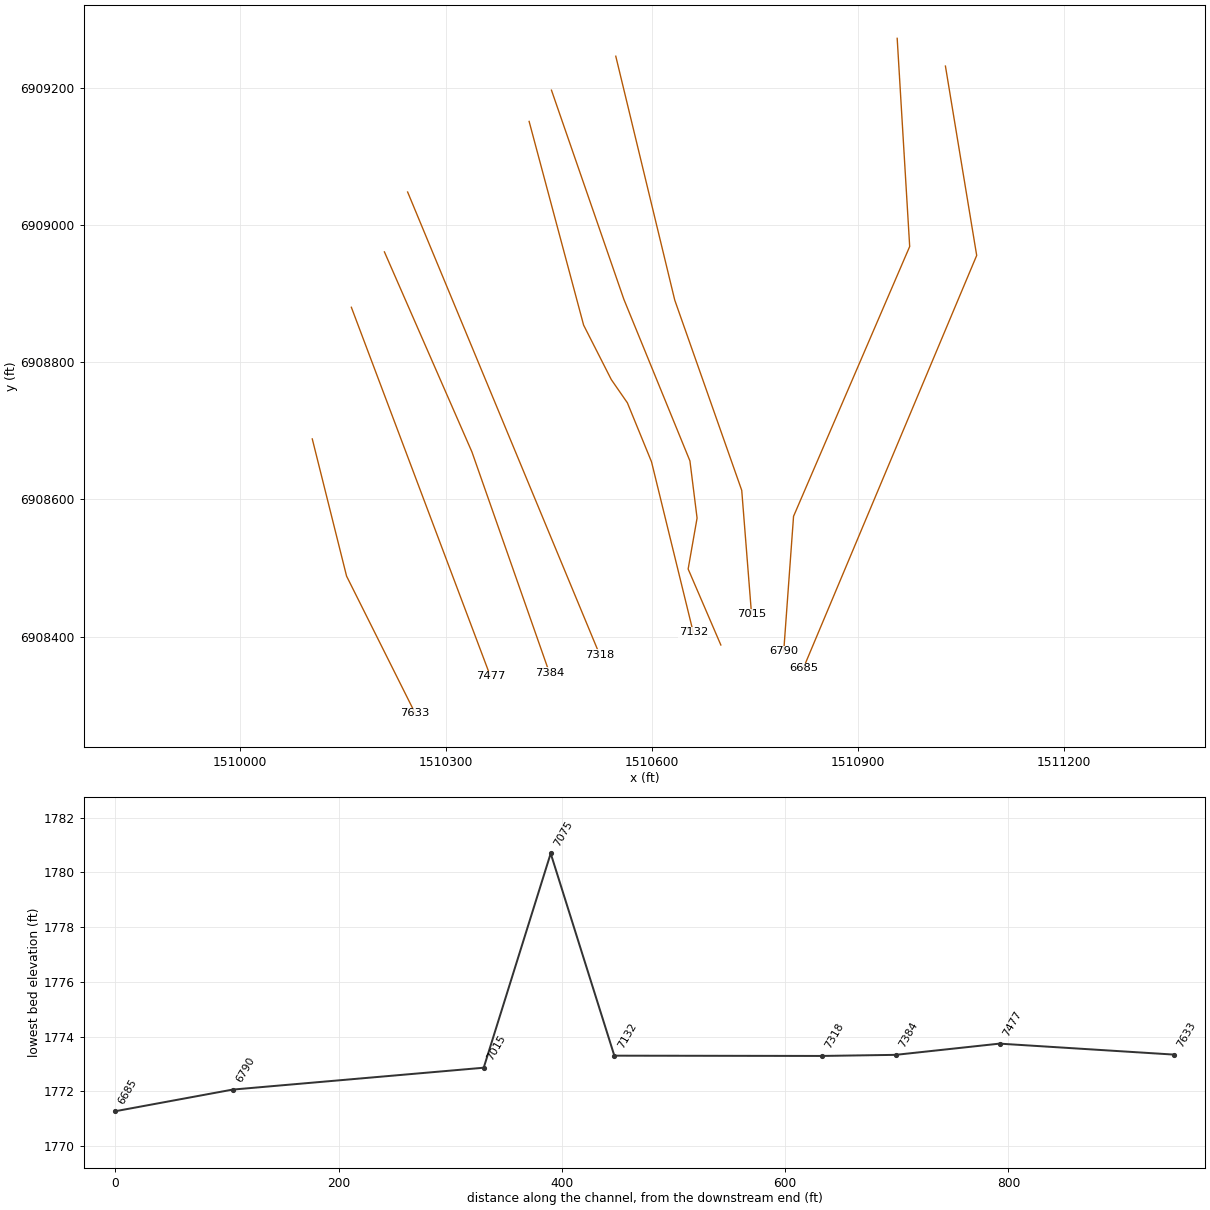
HEC-RAS study NC Unknown Stream 82.prj: NC Unknown Stream 82 Base Level Engineering

--- NC Unknown Stream 82.g01 (geometry) --- (continued)

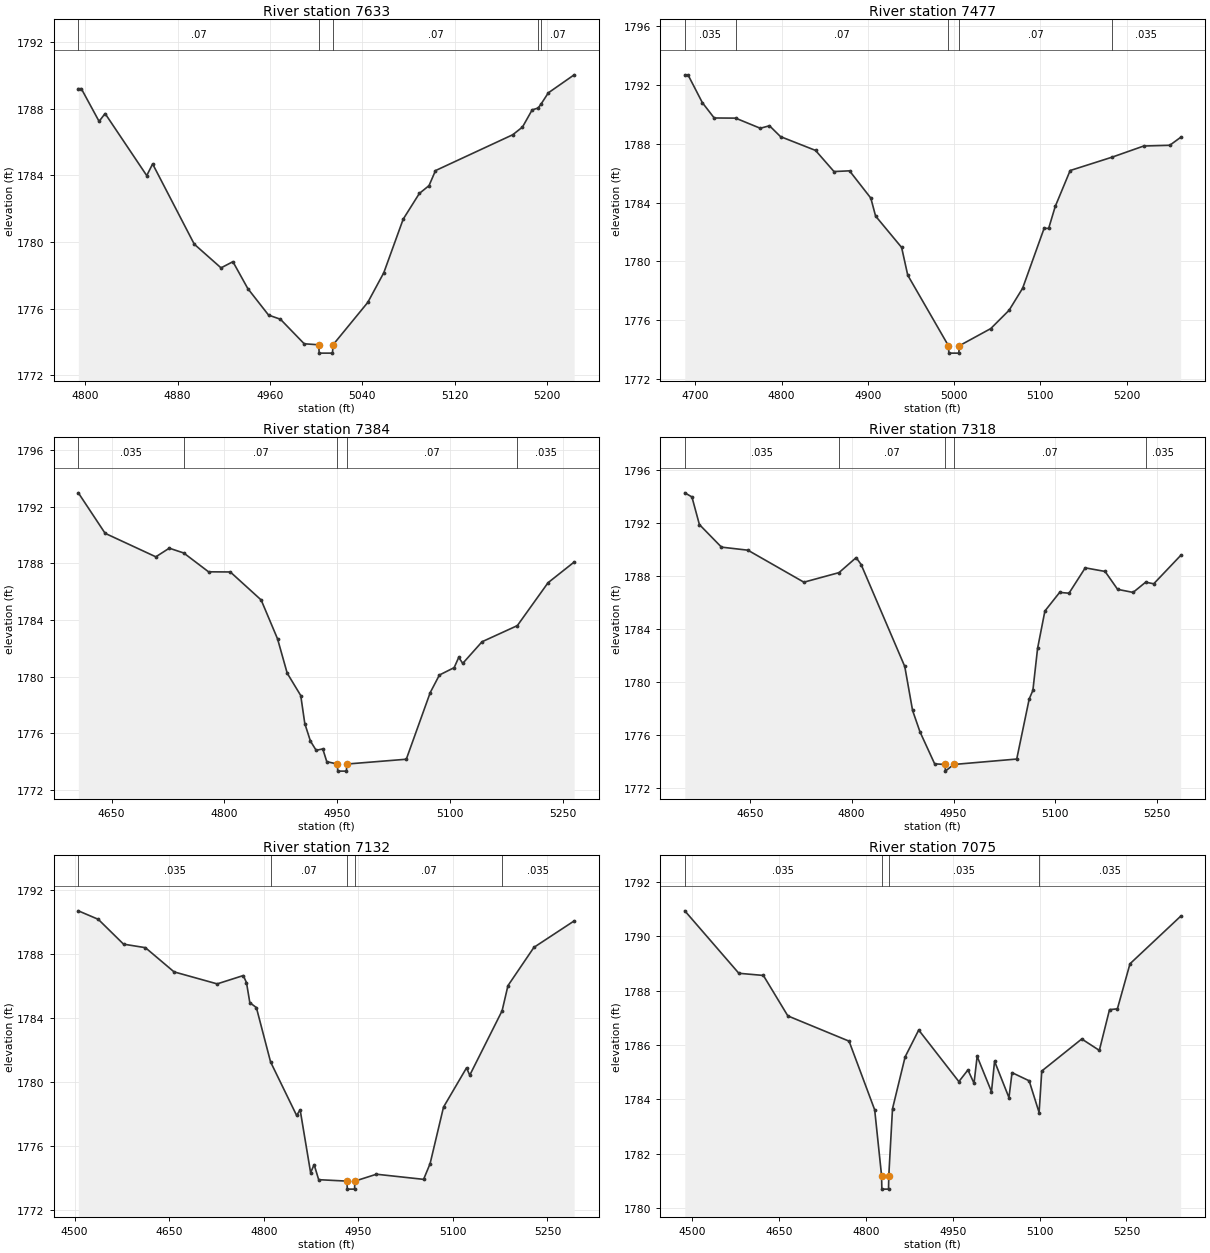
Type RM Length L Ch R = 1,7633,156,156,156
BEGIN DESCRIPTION:
NC Unknown Stream 79 18.0
END DESCRIPTION:
XS GIS Cut Line= 3
      1510105.00      6908687.99      1510155.00      6908488.00
      1510255.02      6908287.96
#Sta/Elev= 30
  4793.9 1789.19  4796.5 1789.19  4811.9 1787.23  4817.1 1787.70  4853.2 1783.98
  4858.3 1784.68  4894.4 1779.87  4917.6 1778.45  4927.9 1778.82  4940.8 1777.21
  4958.8 1775.62  4969.1 1775.37  4989.7 1773.90  5002.2 1773.84  5002.7 1773.34
  5014.2 1773.34  5014.7 1773.84  5044.8 1776.38  5058.7 1778.16  5075.5 1781.37
  5089.5 1782.91  5097.9 1783.38  5103.5 1784.28  5170.5 1786.43  5178.9 1786.89
  5187.3 1787.92  5192.5 1788.03  5195.3 1788.30  5201.3 1788.94  5223.7 1790.02
#Mann=5,-1,0
  4793.9    0.07       0  5002.2    0.07       0  5014.7    0.07       0
  5192.5   0.035       0  5195.3    0.07       0
Bank Sta=5002.2,5014.7
Exp/Cntr=0.3,0.1

Type RM Length L Ch R = 1,7477,93,93,93
BEGIN DESCRIPTION:
Mapping XS 6368d8aa
END DESCRIPTION:
XS GIS Cut Line= 2
      1510161.98      6908879.87      1510364.70      6908341.90
#Sta/Elev= 30
  4687.7 1792.70  4691.4 1792.70  4708.1 1790.80  4721.8 1789.76  4746.6 1789.75
  4775.2 1789.06  4785.9 1789.23  4798.7 1788.49  4839.3 1787.55  4860.7 1786.11
  4878.7 1786.16  4903.4 1784.30  4908.9 1783.08  4939.1 1780.94  4946.2 1779.05
  4993.4 1774.24  4993.9 1773.74  5005.4 1773.74  5005.9 1774.24  5042.4 1775.41
  5063.7 1776.66  5079.4 1778.16  5104.3 1782.24  5109.6 1782.24  5117.2 1783.73
  5134.5 1786.18  5183.1 1787.09  5219.8 1787.85  5250.0 1787.90  5262.6 1788.44
#Mann=5,-1,0
  4687.7   0.035       0  4746.6    0.07       0  4993.4    0.07       0
  5005.9    0.07       0  5183.1   0.035       0
Bank Sta=4993.4,5005.9
Exp/Cntr=0.3,0.1

Type RM Length L Ch R = 1,7384,66,66,66
BEGIN DESCRIPTION:
Mapping XS aa69faed
END DESCRIPTION:
XS GIS Cut Line= 3
      1510210.15      6908960.61      1510337.75      6908668.96
      1510450.52      6908347.51
#Sta/Elev= 30
  4605.9 1792.99  4641.5 1790.13  4708.9 1788.47  4726.8 1789.08  4746.0 1788.74
  4779.0 1787.41  4807.9 1787.40  4848.9 1785.42  4870.7 1782.67  4883.5 1780.25
  4901.5 1778.67  4906.9 1776.69  4914.4 1775.45  4922.0 1774.80  4930.8 1774.90
  4936.1 1774.00  4950.2 1773.83  4950.7 1773.33  4962.2 1773.33  4962.7 1773.83
  5041.8 1774.17  5073.6 1778.88  5085.8 1780.12  5105.4 1780.64  5111.5 1781.37
  5116.8 1780.94  5142.5 1782.47  5189.4 1783.61  5230.2 1786.64  5264.9 1788.10
#Mann=5,-1,0
  4605.9   0.035       0  4746.0    0.07       0  4950.2    0.07       0
  4962.7    0.07       0  5189.4   0.035       0
Bank Sta=4950.2,4962.7
Exp/Cntr=0.3,0.1

Type RM Length L Ch R = 1,7318,186,186,186
BEGIN DESCRIPTION:
Mapping XS fba1117d
END DESCRIPTION:
XS GIS Cut Line= 2
      1510243.99      6909047.89      1510523.95      6908373.39
#Sta/Elev= 30
  4554.2 1794.25  4564.7 1793.94  4575.7 1791.86  4608.2 1790.16  4647.1 1789.93
  4729.6 1787.52  4781.3 1788.24  4806.6 1789.37  4813.9 1788.85  4878.2 1781.17
  4889.7 1777.86  4900.6 1776.25  4922.2 1773.84  4937.6 1773.79  4938.1 1773.29
  4950.1 1773.79  5043.1 1774.20  5061.5 1778.73  5066.9 1779.37  5073.8 1782.53
  5084.6 1785.35  5106.3 1786.75  5120.1 1786.69  5144.0 1788.60  5173.2 1788.33
  5191.7 1786.98  5214.5 1786.75  5233.0 1787.52  5244.9 1787.40  5284.5 1789.53
#Mann=5,-1,0
  4554.2   0.035       0  4781.3    0.07       0  4937.6    0.07       0
  4950.1    0.07       0  5233.0   0.035       0
Bank Sta=4937.6,4950.1
Exp/Cntr=0.3,0.1

Type RM Length L Ch R = 1,7132,57,57,57
BEGIN DESCRIPTION:
Mapping XS d3a161a3
END DESCRIPTION:
XS GIS Cut Line= 6
      1510421.08      6909150.76      1510500.51      6908853.86
      1510540.88      6908774.43      1510564.31      6908740.58
      1510599.47      6908654.64      1510660.32      6908406.05
#Sta/Elev= 30
  4505.9 1790.67  4537.5 1790.14  4577.6 1788.59  4612.3 1788.37  4657.7 1786.86
  4726.1 1786.11  4767.5 1786.63  4772.6 1786.19  4777.9 1784.94  4788.3 1784.63
  4810.8 1781.24  4852.1 1777.90  4857.7 1778.25  4874.3 1774.33  4879.9 1774.83
  4887.1 1773.89  4932.0 1773.80  4932.5 1773.30  4944.0 1773.30  4944.5 1773.80
  4978.7 1774.23  5053.5 1773.91  5063.8 1774.89  5085.1 1778.42  5121.6 1780.87
  5126.7 1780.41  5178.0 1784.43  5187.3 1786.00  5228.5 1788.39  5292.3 1790.04
#Mann=5,-1,0
  4505.9   0.035       0  4810.8    0.07       0  4932.0    0.07       0
  4944.5    0.07       0  5178.0   0.035       0
Bank Sta=4932,4944.5
Exp/Cntr=0.3,0.1

Type RM Length L Ch R = 1,7075,60,60,60
BEGIN DESCRIPTION:
Mapping XS d18a1546
END DESCRIPTION:
XS GIS Cut Line= 6
      1510453.64      6909196.30      1510559.11      6908891.62
      1510655.46      6908655.94      1510665.88      6908572.61
      1510652.86      6908498.39      1510700.51      6908387.64
#Sta/Elev= 30
  4486.7 1790.94  4580.1 1788.64  4622.5 1788.56  4664.8 1787.07  4770.6 1786.14
  4814.9 1783.61  4826.8 1781.19  4827.3 1780.69  4838.8 1780.69  4839.3 1781.19
  4845.7 1783.65  4867.5 1785.56  4891.0 1786.55  4960.4 1784.65  4976.1 1785.08
  4986.6 1784.59  4992.0 1785.58  5016.8 1784.28  5022.1 1785.40  5047.0 1784.06
  5052.3 1784.98  5081.9 1784.68  5099.1 1783.51  5103.7 1785.04  5172.8 1786.22
  5203.2 1785.80  5220.8 1787.30  5234.4 1787.33  5256.2 1788.99  5343.7 1790.74
#Mann=4,-1,0
  4486.7   0.035       0  4826.8    0.07       0  4839.3   0.035       0
  5099.1   0.035       0
Bank Sta=4826.8,4839.3
Exp/Cntr=0.3,0.1

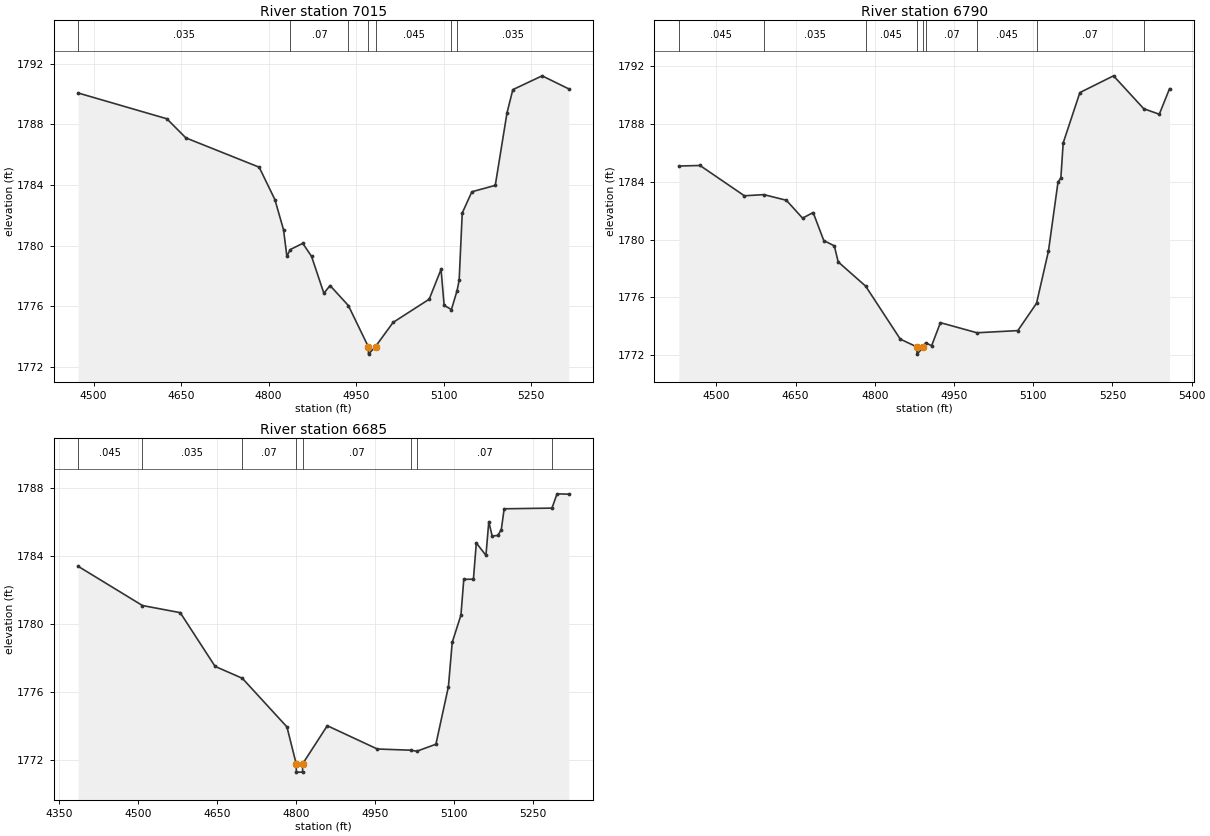
Type RM Length L Ch R = 1,7015,225,225,225
BEGIN DESCRIPTION:
Mapping XS 5dab03f4
END DESCRIPTION:
XS GIS Cut Line= 4
      1510547.38      6909245.81      1510633.33      6908890.32
      1510730.98      6908612.97      1510745.26      6908432.51
#Sta/Elev= 30
  4473.5 1790.07  4625.6 1788.37  4658.2 1787.11  4783.8 1785.18  4810.8 1783.04
  4825.6 1781.05  4831.3 1779.31  4837.1 1779.75  4858.5 1780.16  4873.5 1779.31
  4894.7 1776.87  4905.3 1777.38  4936.7 1776.06  4970.7 1773.36  4971.2 1772.86
  4983.2 1773.36  5013.3 1774.95  5075.2 1776.48  5095.5 1778.45  5100.8 1776.07
  5113.3 1775.80  5122.9 1777.04  5126.5 1777.72  5131.8 1782.16  5148.3 1783.56
  5188.4 1783.98  5208.5 1788.76  5218.5 1790.29  5268.7 1791.20  5314.3 1790.34
#Mann=7,-1,0
  4473.5   0.035       0  4837.1    0.07       0  4936.7   0.045       0
  4970.7   0.045       0  4983.2   0.045       0  5113.3    0.07       0
  5122.9   0.035       0
Bank Sta=4970.7,4983.2
Exp/Cntr=0.3,0.1

Type RM Length L Ch R = 1,6790,105,105,105
BEGIN DESCRIPTION:
Mapping XS aa0c5bce
END DESCRIPTION:
XS GIS Cut Line= 4
      1510957.54      6909271.87      1510975.77      6908968.44
      1510806.50      6908575.21      1510792.18      6908378.62
#Sta/Elev= 30
  4428.9 1785.09  4468.9 1785.13  4553.0 1783.03  4589.8 1783.11  4632.4 1782.72
  4663.2 1781.48  4683.2 1781.87  4703.3 1779.93  4723.3 1779.56  4730.6 1778.45
  4782.6 1776.77  4848.2 1773.10  4879.5 1772.56  4880.0 1772.06  4892.1 1772.56
  4896.3 1772.85  4907.5 1772.64  4924.2 1774.24  4993.4 1773.54  5070.8 1773.69
  5106.2 1775.58  5128.8 1779.20  5146.9 1783.98  5152.3 1784.27  5156.7 1786.69
  5188.3 1790.18  5252.0 1791.34  5309.3 1789.06  5338.7 1788.68  5358.1 1790.45
#Mann=9,-1,0
  4428.9   0.045       0  4589.8   0.035       0  4782.6   0.045       0
  4879.5   0.045       0  4892.1   0.045       0  4896.3    0.07       0
  4993.4   0.045       0  5106.2    0.07       0  5309.3   0.035       0
Bank Sta=4879.5,4892.1
Exp/Cntr=0.3,0.1

Type RM Length L Ch R = 1,6685,0,0,0
BEGIN DESCRIPTION:
NC Unknown Stream 79 16.0
END DESCRIPTION:
XS GIS Cut Line= 3
      1511027.86      6909231.43      1511073.43      6908955.42
      1510820.82      6908353.85
#Sta/Elev= 30
  4386.5 1783.38  4508.8 1781.07  4580.6 1780.65  4646.8 1777.49  4698.6 1776.79
  4783.3 1773.93  4800.8 1771.77  4801.3 1771.27  4812.9 1771.27  4813.4 1771.77
  4860.0 1774.00  4955.0 1772.63  5018.6 1772.56  5030.0 1772.50  5066.3 1772.91
  5090.1 1776.30  5097.3 1778.90  5113.9 1780.51  5119.3 1782.61  5137.6 1782.62
  5143.1 1784.75  5161.4 1784.02  5166.8 1786.00  5173.2 1785.16  5184.0 1785.19
  5190.6 1785.54  5196.0 1786.76  5286.8 1786.80  5296.5 1787.64  5318.7 1787.62
#Mann=8,-1,0
  4386.5   0.045       0  4508.8   0.035       0  4698.6    0.07       0
  4800.8    0.07       0  4813.4    0.07       0  5018.6   0.045       0
  5030.0    0.07       0  5286.8   0.035       0
Bank Sta=4800.8,4813.4
Exp/Cntr=0.3,0.1

Chan Stop Cuts=-1