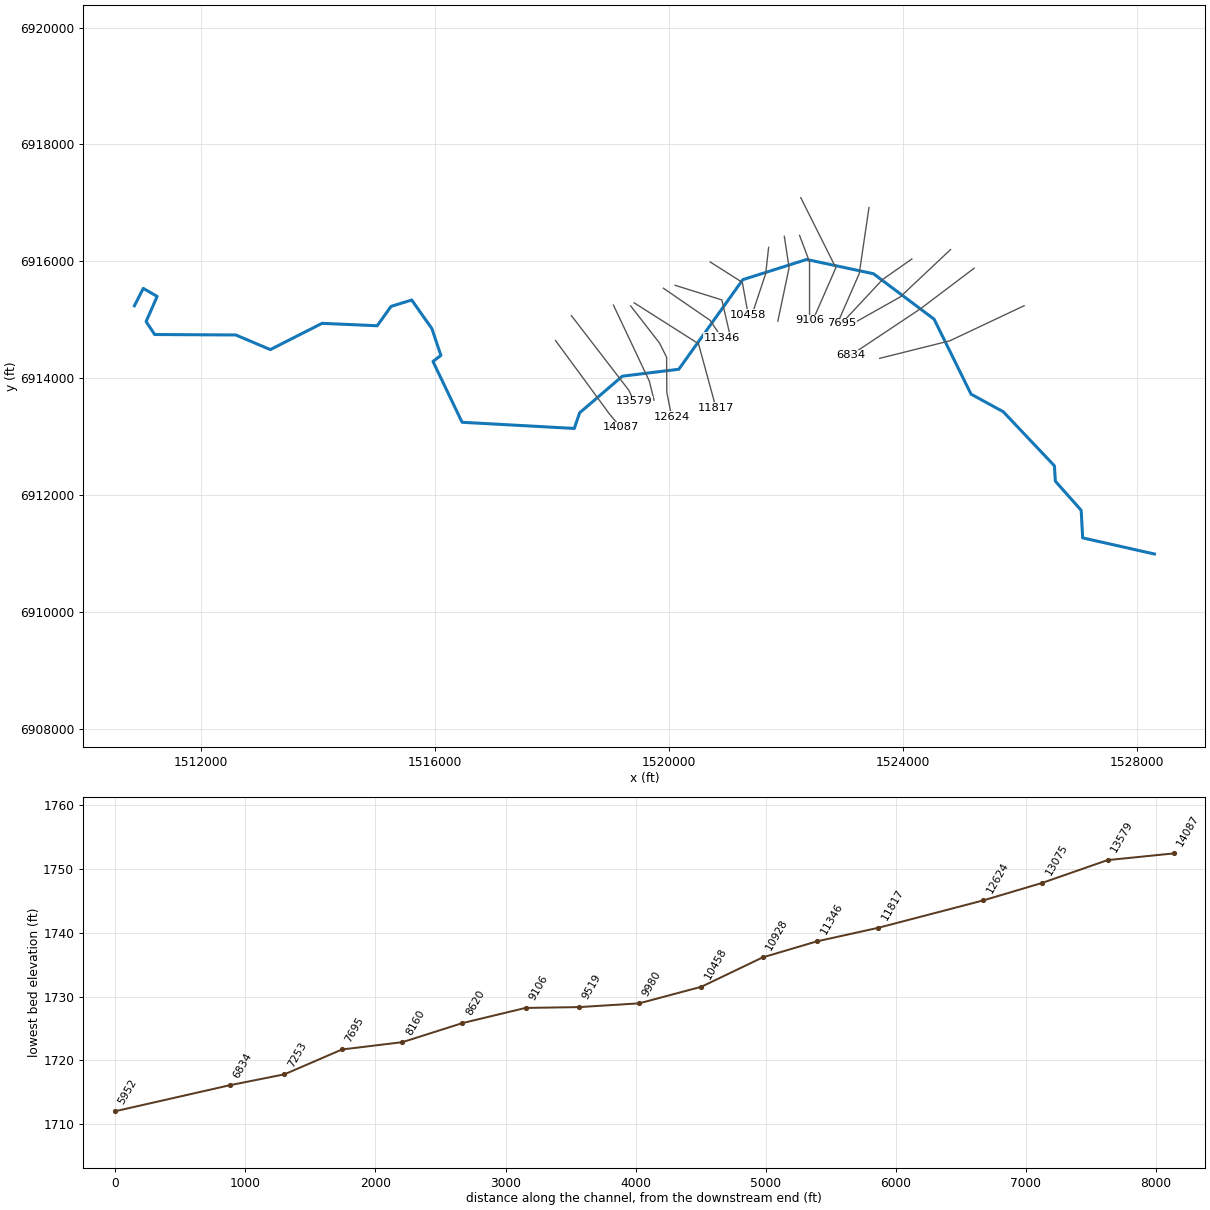
--- NC Unknown Stream 84.prj (project) ---

Proj Title=NC Unknown Stream 84 Base Level Engineering
Current Plan=p01
Default Exp/Contr=0.3,0.1
English Units
Geom File=g01
Flow File=f01
Plan File=p01
BEGIN DESCRIPTION:
NC Unknown Stream 84
END DESCRIPTION:

--- NC Unknown Stream 84.p01 (plan) ---

Plan Title=Multiple Run
Short Identifier=Multiple
Geom File=g01
Flow File=f01
Subcritical Flow
K Sum by GR= 0
Std Step Tol= 0.01
Critical Tol= 0.01
Num of Std Step Trials= 20
Max Error Tol= 0.3
Flow Tol Ratio= 0.001
Split Flow NTrial= 30
Split Flow Tol= 0.02
Split Flow Ratio= 0.02
Log Output Level= 0
Friction Slope Method= 1
Unsteady Friction Slope Method= 2
Unsteady Bridges Friction Slope Method= 1
Parabolic Critical Depth
Global Vel Dist=  1 , 1 , 1
Global Log Level= 0
CheckData=True
Encroach Param= -1, 0, 0, 0
BEGIN DESCRIPTION:
Multiple Run
END DESCRIPTION:

--- NC Unknown Stream 84.f01 (steady flow) ---

Flow Title=Multiple
Number of Profiles=7
Profile Names=10-year,25-year,50-year,1pct_min,100-year,1pct_plu,500-year
River Rch & RM= NC Unknown Strea,Reach-1,14087
     360     495     605     367     732    1461    1087
River Rch & RM= NC Unknown Strea,Reach-1,13075
     393     544     668     407     811    1619    1214
River Rch & RM= NC Unknown Strea,Reach-1,9980
     497     699     867     533    1064    2122    1625
River Rch & RM= NC Unknown Strea,Reach-1,6834
     593     844    1056     655    1307    2607    2030
Boundary for River Rch & Prof#=NC Unknown Strea,Reach-1,1
Up Type=0
Dn Type=3
Dn Slope=0.001
Boundary for River Rch & Prof#=NC Unknown Strea,Reach-1,2
Up Type=0
Dn Type=3
Dn Slope=0.001
Boundary for River Rch & Prof#=NC Unknown Strea,Reach-1,3
Up Type=0
Dn Type=3
Dn Slope=0.001
Boundary for River Rch & Prof#=NC Unknown Strea,Reach-1,4
Up Type=0
Dn Type=3
Dn Slope=0.001
Boundary for River Rch & Prof#=NC Unknown Strea,Reach-1,5
Up Type=0
Dn Type=3
Dn Slope=0.001
Boundary for River Rch & Prof#=NC Unknown Strea,Reach-1,6
Up Type=0
Dn Type=3
Dn Slope=0.001
Boundary for River Rch & Prof#=NC Unknown Strea,Reach-1,7
Up Type=0
Dn Type=3
Dn Slope=0.001

--- NC Unknown Stream 84.g01 (geometry) ---

Geom Title=Existing Conditions

River Reach=NC Unknown Strea,Reach-1
Reach XY= 30
      1510855.00      6915238.00      1511006.42      6915534.96
      1511244.05      6915398.02      1511054.90      6914967.90
      1511201.58      6914745.79      1512589.78      6914737.76
      1513180.00      6914487.58      1514065.68      6914937.25
      1515008.41      6914895.82      1515245.30      6915227.26
      1515598.97      6915336.39      1515945.42      6914844.55
      1516098.00      6914387.78      1515962.51      6914284.85
      1516460.47      6913243.25      1518380.22      6913137.67
      1518471.41      6913404.80      1519202.70      6914032.17
      1520168.21      6914151.14      1521263.35      6915684.81
      1522354.99      6916030.47      1523498.88      6915786.16
      1524535.77      6915008.57      1525168.23      6913724.33
      1525718.22      6913424.38      1526594.25      6912497.70
      1526609.99      6912235.45      1527051.86      6911736.36
      1527077.72      6911264.10      1528305.00      6910988.00

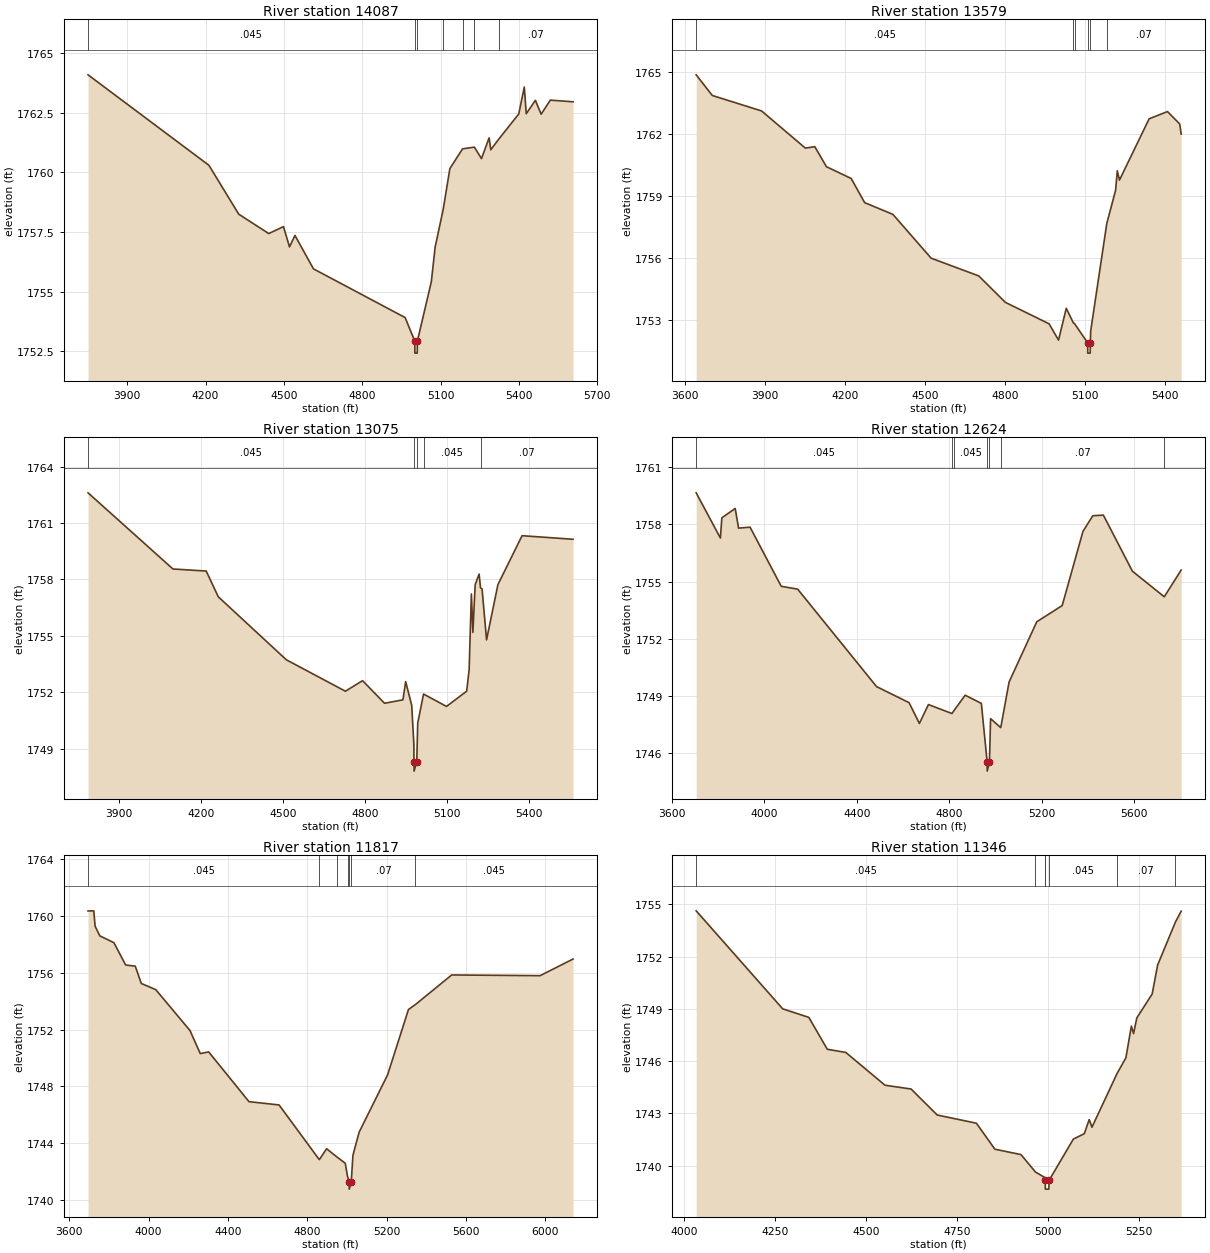
Type RM Length L Ch R = 1,14087,508,508,508
BEGIN DESCRIPTION:
Mapping XS 8f434f65
END DESCRIPTION:
XS GIS Cut Line= 3
      1518060.51      6914641.42      1518987.60      6913377.51
      1519175.08      6913155.31
#Sta/Elev= 30
  3749.5 1764.09  4212.6 1760.30  4327.0 1758.25  4441.9 1757.44  4498.3 1757.73
  4521.4 1756.88  4542.3 1757.36  4613.3 1755.96  4964.4 1753.92  5001.4 1752.93
  5001.9 1752.43  5010.8 1752.43  5011.3 1752.93  5064.8 1755.42  5079.4 1756.87
  5110.6 1758.47  5135.8 1760.16  5184.5 1760.99  5229.7 1761.06  5257.0 1760.58
  5286.3 1761.45  5292.5 1760.95  5324.2 1761.41  5399.8 1762.45  5421.0 1763.58
  5428.4 1762.46  5463.5 1763.02  5485.6 1762.44  5520.7 1763.03  5607.7 1762.96
#Mann=7,-1,0
  3749.5   0.045       0  5001.4   0.045       0  5011.3   0.045       0
  5110.6   0.045       0  5184.5    0.07       0  5229.7   0.045       0
  5324.2    0.07       0
Bank Sta=5001.4,5011.3
Exp/Cntr=0.3,0.1

Type RM Length L Ch R = 1,13579,504,504,504
BEGIN DESCRIPTION:
Mapping XS 62e0bbd5
END DESCRIPTION:
XS GIS Cut Line= 3
      1518331.36      6915068.47      1519313.99      6913790.71
      1519400.41      6913604.05
#Sta/Elev= 30
  3642.4 1764.86  3702.8 1763.86  3887.6 1763.11  4051.6 1761.31  4087.0 1761.38
  4130.5 1760.41  4223.3 1759.84  4273.7 1758.67  4379.7 1758.10  4522.9 1755.98
  4701.4 1755.12  4801.1 1753.84  4965.1 1752.80  5000.4 1752.01  5029.4 1753.55
  5056.2 1752.84  5060.3 1752.81  5109.5 1751.88  5110.0 1751.38  5119.1 1751.38
  5119.6 1751.88  5120.9 1752.45  5181.3 1757.66  5214.3 1759.27  5220.6 1760.21
  5228.8 1759.76  5340.0 1762.73  5408.7 1763.08  5454.6 1762.48  5460.0 1761.99
#Mann=6,-1,0
  3642.4   0.045       0  5056.2    0.07       0  5060.3   0.045       0
  5109.5   0.045       0  5119.6   0.045       0  5181.3    0.07       0
Bank Sta=5109.5,5119.6
Exp/Cntr=0.3,0.1

Type RM Length L Ch R = 1,13075,451,451,451
BEGIN DESCRIPTION:
Mapping XS f8d07117
END DESCRIPTION:
XS GIS Cut Line= 3
      1519050.12      6915249.01      1519664.68      6913946.96
      1519744.25      6913621.75
#Sta/Elev= 30
  3786.7 1762.60  4097.4 1758.55  4219.1 1758.44  4263.3 1757.07  4512.4 1753.72
  4728.4 1752.05  4791.2 1752.61  4871.5 1751.41  4938.9 1751.59  4948.9 1752.56
  4971.0 1751.30  4978.9 1749.22  4979.3 1748.30  4979.8 1747.80  4989.5 1748.30
  4993.1 1750.36  5014.3 1751.90  5098.3 1751.24  5172.1 1752.05  5181.1 1753.18
  5189.4 1757.22  5194.9 1755.18  5203.2 1757.71  5217.7 1758.28  5222.8 1757.55
  5228.5 1757.49  5244.9 1754.78  5286.5 1757.72  5374.9 1760.32  5561.3 1760.13
#Mann=5,-1,0
  3786.7   0.045       0  4979.3    0.07       0  4989.5   0.045       0
  5014.3   0.045       0  5222.8    0.07       0
Bank Sta=4979.3,4989.5
Exp/Cntr=0.3,0.1

Type RM Length L Ch R = 1,12624,807,807,807
BEGIN DESCRIPTION:
Mapping XS 42d88f20
END DESCRIPTION:
XS GIS Cut Line= 5
      1519345.26      6915235.13      1519838.29      6914599.73
      1519959.82      6914356.68      1519963.29      6913752.51
      1520046.26      6913341.16
#Sta/Elev= 30
  3704.6 1759.66  3809.4 1757.29  3815.7 1758.35  3873.6 1758.84  3888.1 1757.81
  3937.9 1757.86  4072.8 1754.76  4144.0 1754.61  4485.7 1749.50  4626.3 1748.66
  4671.0 1747.57  4710.2 1748.56  4812.0 1748.09  4820.6 1748.24  4869.3 1749.05
  4939.3 1748.62  4964.2 1745.57  4964.7 1745.07  4974.4 1745.57  4979.3 1747.82
  5023.3 1747.35  5059.3 1749.74  5179.3 1752.90  5289.3 1753.75  5379.3 1757.64
  5421.9 1758.46  5467.6 1758.49  5593.4 1755.55  5731.2 1754.21  5804.4 1755.61
#Mann=7,-1,0
  3704.6   0.045       0  4812.0    0.07       0  4820.6   0.045       0
  4964.2   0.045       0  4974.4   0.045       0  5023.3    0.07       0
  5731.2   0.045       0
Bank Sta=4964.2,4974.4
Exp/Cntr=0.3,0.1

Type RM Length L Ch R = 1,11817,471,471,471
BEGIN DESCRIPTION:
NC Unknown Stream 84 14.0
END DESCRIPTION:
XS GIS Cut Line= 3
      1519405.01      6915288.00      1520505.00      6914588.00
      1520805.00      6913488.01
#Sta/Elev= 30
  3694.9 1760.34  3723.7 1760.35  3730.5 1759.27  3754.2 1758.59  3825.3 1758.11
  3884.5 1756.54  3932.8 1756.46  3963.3 1755.24  4036.1 1754.81  4208.8 1751.93
  4260.5 1750.31  4302.8 1750.43  4506.0 1746.93  4657.5 1746.70  4860.4 1742.85
  4897.1 1743.62  4947.3 1743.06  4991.1 1742.60  5002.5 1741.68  5010.8 1741.28
  5011.3 1740.78  5021.2 1741.28  5029.8 1743.16  5060.9 1744.78  5204.3 1748.81
  5309.7 1753.41  5344.8 1753.76  5527.4 1755.84  5973.1 1755.79  6138.9 1756.96
#Mann=7,-1,0
  3694.9   0.045       0  4860.4    0.07       0  4947.3   0.045       0
  5002.5    0.07       0  5010.8   0.045       0  5021.2    0.07       0
  5344.8   0.045       0
Bank Sta=5010.8,5021.2
Exp/Cntr=0.3,0.1

Type RM Length L Ch R = 1,11346,418,418,418
BEGIN DESCRIPTION:
NC Unknown Stream 84 13.0
END DESCRIPTION:
XS GIS Cut Line= 3
      1519904.96      6915538.03      1520705.00      6914988.00
      1520904.99      6914688.02
#Sta/Elev= 30
  4033.8 1754.62  4271.3 1749.00  4343.0 1748.51  4393.8 1746.68  4444.5 1746.50
  4552.1 1744.62  4623.8 1744.40  4695.5 1742.91  4803.1 1742.44  4853.8 1740.95
  4925.5 1740.64  4965.3 1739.64  4991.1 1739.32  4991.9 1739.16  4992.4 1738.66
  5002.0 1738.66  5002.5 1739.16  5069.3 1741.53  5099.3 1741.84  5112.8 1742.65
  5120.3 1742.21  5189.0 1745.28  5213.5 1746.19  5228.5 1748.01  5234.5 1747.58
  5243.5 1748.48  5285.6 1749.85  5300.6 1751.51  5349.5 1753.98  5365.2 1754.60
#Mann=7,-1,0
  4033.8   0.045       0  4965.3    0.16       0  4991.1   0.045       0
  4991.9   0.045       0  5002.5   0.045       0  5189.0    0.07       0
  5349.5   0.045       0
Bank Sta=4991.9,5002.5
Exp/Cntr=0.3,0.1

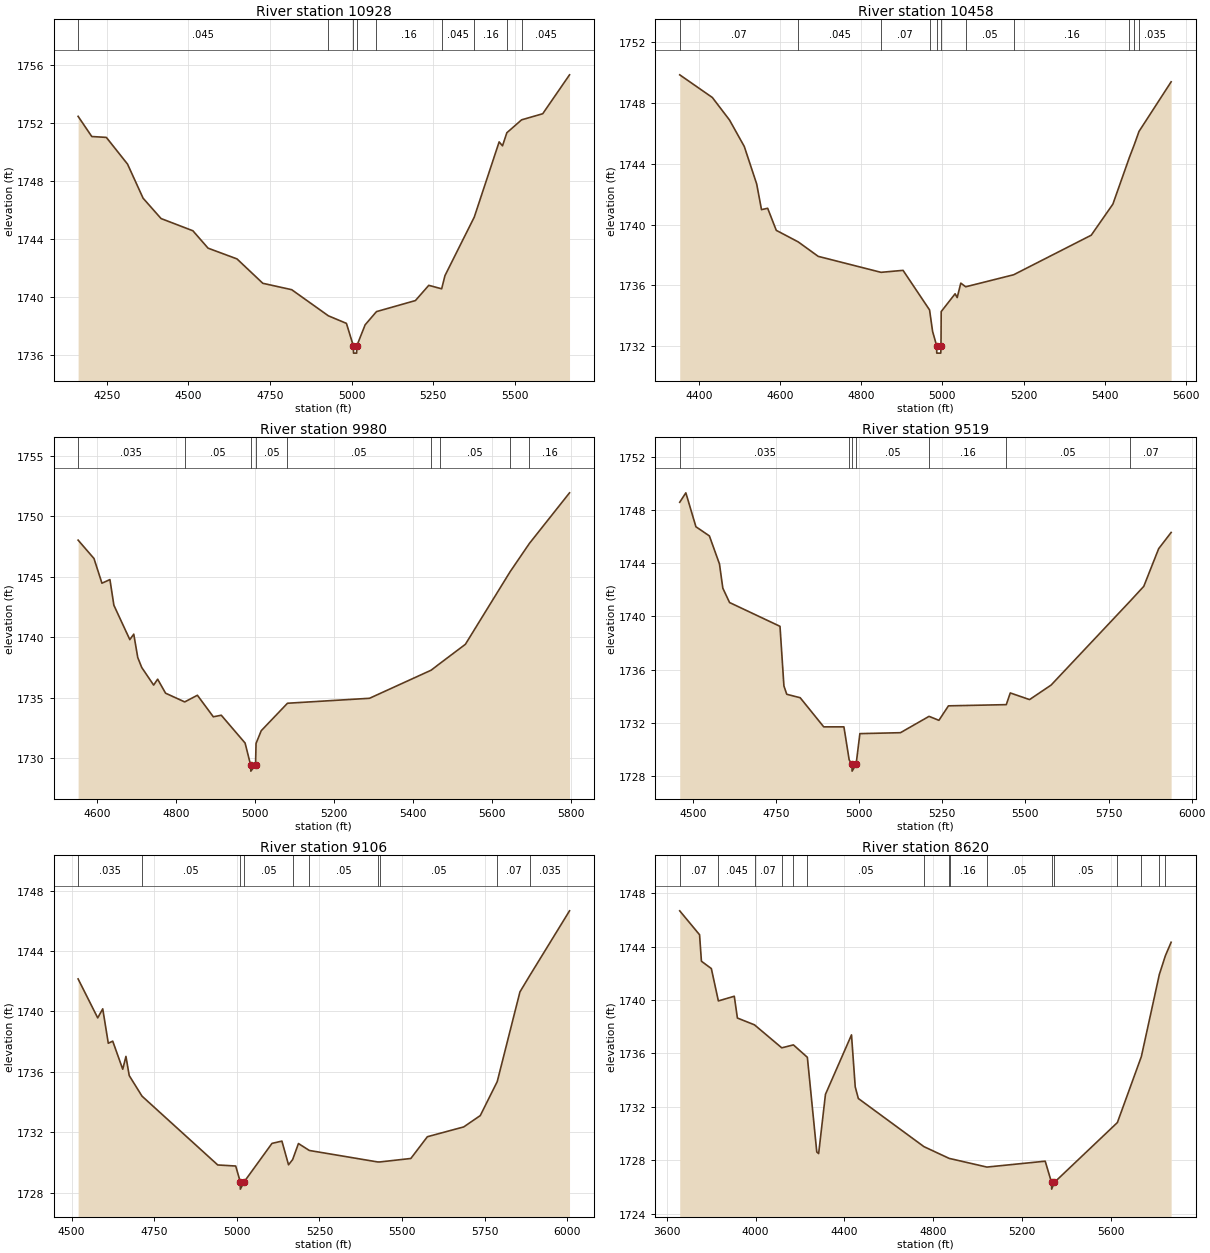
Type RM Length L Ch R = 1,10928,470,470,470
BEGIN DESCRIPTION:
NC Unknown Stream 84 12.0
END DESCRIPTION:
XS GIS Cut Line= 3
      1520104.98      6915588.01      1520905.00      6915338.00
      1521055.01      6914687.96
#Sta/Elev= 30
  4162.1 1752.45  4204.0 1751.06  4248.6 1751.00  4313.5 1749.16  4361.2 1746.81
  4416.2 1745.41  4513.6 1744.57  4560.2 1743.37  4648.8 1742.63  4727.9 1740.95
  4816.4 1740.51  4928.7 1738.71  4984.0 1738.19  5005.2 1736.64  5005.7 1736.14
  5015.3 1736.14  5015.8 1736.64  5041.3 1738.09  5076.1 1739.00  5195.3 1739.76
  5236.3 1740.81  5275.7 1740.57  5285.9 1741.48  5375.6 1745.51  5451.8 1750.69
  5462.1 1750.42  5475.4 1751.32  5520.6 1752.21  5585.3 1752.63  5667.4 1755.31
#Mann=9,-1,0
  4162.1   0.045       0  4928.7    0.07       0  5005.2    0.07       0
  5015.8    0.07       0  5076.1    0.16       0  5275.7   0.045       0
  5375.6    0.16       0  5475.4    0.07       0  5520.6   0.045       0
Bank Sta=5005.2,5015.8
Exp/Cntr=0.3,0.1

Type RM Length L Ch R = 1,10458,478,478,478
BEGIN DESCRIPTION:
NC Unknown Stream 84 11.0
END DESCRIPTION:
XS GIS Cut Line= 3
      1520705.02      6915987.99      1521255.00      6915638.00
      1521355.00      6915088.01
#Sta/Elev= 30
  4352.7 1749.84  4433.1 1748.35  4475.4 1746.87  4511.8 1745.13  4542.3 1742.67
  4554.2 1740.98  4569.4 1741.07  4590.6 1739.62  4644.7 1738.86  4693.9 1737.91
  4848.7 1736.86  4903.0 1736.99  4968.3 1734.39  4975.8 1732.98  4985.6 1732.05
  4986.1 1731.55  4996.0 1731.55  4996.5 1732.05  4997.0 1734.28  5031.3 1735.45
  5036.4 1735.20  5045.3 1736.15  5057.4 1735.91  5175.5 1736.70  5366.7 1739.30
  5420.0 1741.34  5460.7 1744.41  5472.5 1745.23  5484.4 1746.12  5563.6 1749.38
#Mann=11,-1,0
  4352.7    0.07       0  4644.7   0.045       0  4848.7    0.07       0
  4968.3    0.16       0  4985.6    0.07       0  4996.5    0.16       0
  5057.4    0.05       0  5175.5    0.16       0  5460.7    0.05       0
  5472.5    0.16       0  5484.4   0.035       0
Bank Sta=4985.6,4996.5
Exp/Cntr=0.3,0.1

Type RM Length L Ch R = 1,9980,461,461,461
BEGIN DESCRIPTION:
NC Unknown Stream 84 10.0
END DESCRIPTION:
XS GIS Cut Line= 3
      1521705.00      6916237.96      1521655.00      6915788.00
      1521405.00      6915038.00
#Sta/Elev= 30
  4552.1 1748.04  4592.3 1746.52  4612.4 1744.48  4632.6 1744.78  4642.6 1742.66
  4682.9 1739.82  4692.9 1740.27  4703.0 1738.34  4713.0 1737.52  4743.2 1736.06
  4753.3 1736.55  4773.4 1735.39  4821.8 1734.67  4853.9 1735.22  4894.2 1733.44
  4914.3 1733.57  4974.6 1731.27  4988.6 1729.45  4989.1 1728.95  5001.0 1729.45
  5002.3 1731.24  5015.4 1732.29  5081.8 1734.56  5289.4 1734.97  5445.2 1737.29
  5466.8 1737.83  5531.9 1739.43  5644.9 1745.42  5693.7 1747.76  5795.4 1751.95
#Mann=9,-1,0
  4552.1   0.035       0  4821.8    0.05       0  4988.6    0.07       0
  5001.0    0.05       0  5081.8    0.05       0  5445.2    0.16       0
  5466.8    0.05       0  5644.9   0.035       0  5693.7    0.16       0
Bank Sta=4988.6,5001
Exp/Cntr=0.3,0.1

Type RM Length L Ch R = 1,9519,413,413,413
BEGIN DESCRIPTION:
NC Unknown Stream 84 9.0
END DESCRIPTION:
XS GIS Cut Line= 3
      1521973.70      6916426.17      1522055.00      6915888.00
      1521862.60      6914974.72
#Sta/Elev= 30
  4460.7 1748.58  4479.1 1749.29  4509.4 1746.74  4549.9 1746.05  4580.2 1743.94
  4590.3 1742.12  4610.5 1741.04  4762.2 1739.25  4774.0 1734.77  4782.5 1734.14
  4822.9 1733.88  4893.7 1731.69  4954.4 1731.69  4970.2 1729.21  4978.5 1728.86
  4979.0 1728.36  4991.0 1728.86  5002.4 1731.18  5124.4 1731.25  5210.4 1732.48
  5240.0 1732.18  5268.7 1733.27  5442.6 1733.36  5454.6 1734.24  5512.6 1733.74
  5577.3 1734.83  5815.6 1741.16  5856.1 1742.26  5900.8 1745.09  5938.3 1746.31
#Mann=7,-1,0
  4460.7   0.035       0  4970.2    0.05       0  4978.5    0.05       0
  4991.0    0.05       0  5210.4    0.16       0  5442.6    0.05       0
  5815.6    0.07       0
Bank Sta=4978.5,4991
Exp/Cntr=0.3,0.1

Type RM Length L Ch R = 1,9106,486,486,486
BEGIN DESCRIPTION:
NC Unknown Stream 84 8.0
END DESCRIPTION:
XS GIS Cut Line= 3
      1522234.12      6916443.50      1522405.00      6915988.00
      1522405.00      6914988.00
#Sta/Elev= 30
  4519.9 1742.15  4579.2 1739.57  4594.4 1740.17  4611.2 1737.89  4624.6 1738.03
  4654.9 1736.17  4664.6 1737.02  4674.5 1735.75  4713.1 1734.39  4942.3 1729.83
  4996.6 1729.76  5010.2 1728.73  5010.7 1728.23  5022.7 1728.73  5106.4 1731.26
  5136.4 1731.41  5156.4 1729.84  5168.9 1730.19  5186.4 1731.25  5219.4 1730.79
  5426.1 1730.03  5432.8 1730.03  5526.4 1730.26  5576.4 1731.70  5686.4 1732.35
  5736.4 1733.10  5787.7 1735.35  5856.4 1741.29  5885.5 1742.35  6006.4 1746.66
#Mann=10,-1,0
  4519.9   0.035       0  4713.1    0.05       0  5010.2    0.05       0
  5022.7    0.05       0  5168.9    0.16       0  5219.4    0.05       0
  5426.1    0.16       0  5432.8    0.05       0  5787.7    0.07       0
  5885.5   0.035       0
Bank Sta=5010.2,5022.7
Exp/Cntr=0.3,0.1

Type RM Length L Ch R = 1,8620,460,460,460
BEGIN DESCRIPTION:
NC Unknown Stream 84 7.0
END DESCRIPTION:
XS GIS Cut Line= 3
      1522255.01      6917087.98      1522855.00      6915888.00
      1522505.01      6915088.03
#Sta/Elev= 30
  3658.3 1746.67  3747.7 1744.88  3756.1 1742.90  3800.8 1742.35  3832.5 1739.93
  3904.2 1740.28  3918.2 1738.65  3995.3 1738.14  4118.2 1736.42  4170.7 1736.64
  4233.6 1735.71  4276.0 1728.63  4284.4 1728.51  4315.1 1732.94  4432.5 1737.39
  4449.3 1733.50  4463.3 1732.63  4758.8 1729.03  4873.9 1728.14  4875.3 1728.14
  5042.7 1727.50  5305.5 1727.94  5334.0 1726.35  5334.5 1725.85  5346.5 1726.35
  5630.8 1730.83  5738.9 1735.77  5819.9 1741.91  5847.1 1743.31  5873.1 1744.32
#Mann=16,-1,0
  3658.3    0.07       0  3832.5   0.045       0  3995.3    0.07       0
  4118.2    0.05       0  4170.7    0.07       0  4233.6    0.05       0
  4758.8    0.16       0  4873.9    0.05       0  4875.3    0.16       0
  5042.7    0.05       0  5334.0    0.07       0  5346.5    0.05       0
  5630.8    0.07       0  5738.9    0.05       0  5819.9    0.07       0
  5847.1   0.035       0
Bank Sta=5334,5346.5
Exp/Cntr=0.3,0.1

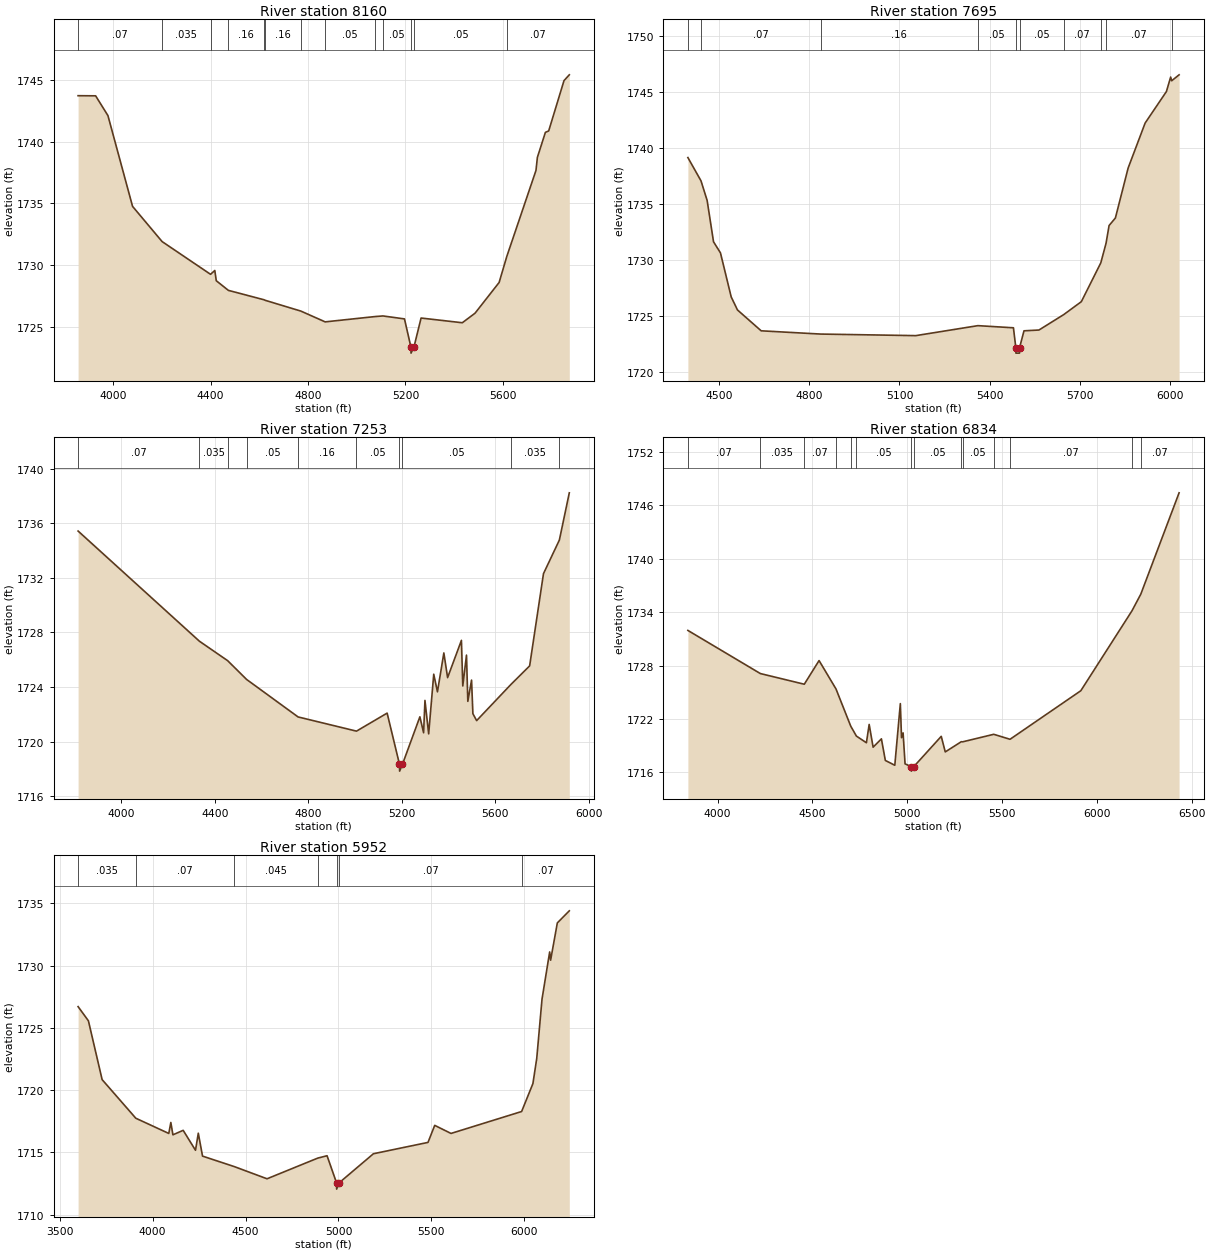
Type RM Length L Ch R = 1,8160,465,465,465
BEGIN DESCRIPTION:
NC Unknown Stream 84 6.0
END DESCRIPTION:
XS GIS Cut Line= 3
      1523421.63      6916919.21      1523255.00      6915788.00
      1522905.01      6914988.03
#Sta/Elev= 30
  3856.2 1743.71  3928.2 1743.70  3978.7 1742.10  4079.8 1734.75  4201.1 1731.90
  4400.0 1729.25  4417.4 1729.56  4423.5 1728.73  4473.2 1727.95  4619.5 1727.19
  4625.3 1727.14  4771.2 1726.27  4870.6 1725.40  5075.4 1725.83  5107.7 1725.88
  5196.1 1725.64  5222.5 1723.37  5223.0 1722.87  5235.1 1723.37  5264.3 1725.71
  5433.5 1725.33  5485.7 1726.10  5584.7 1728.59  5616.1 1730.69  5736.0 1737.66
  5741.8 1738.72  5774.6 1740.74  5788.2 1740.86  5851.0 1744.93  5872.8 1745.40
#Mann=13,-1,0
  3856.2    0.07       0  4201.1   0.035       0  4400.0    0.07       0
  4473.2    0.16       0  4619.5    0.05       0  4625.3    0.16       0
  4771.2    0.12       0  4870.6    0.05       0  5075.4    0.16       0
  5107.7    0.05       0  5222.5    0.05       0  5235.1    0.05       0
  5616.1    0.07       0
Bank Sta=5222.5,5235.1
Exp/Cntr=0.3,0.1

Type RM Length L Ch R = 1,7695,442,442,442
BEGIN DESCRIPTION:
NC Unknown Stream 84 5.0
END DESCRIPTION:
XS GIS Cut Line= 3
      1524155.00      6916038.00      1523655.00      6915688.00
      1522955.03      6914938.03
#Sta/Elev= 30
  4395.3 1739.16  4438.9 1737.09  4459.4 1735.34  4480.7 1731.65  4503.8 1730.66
  4539.6 1726.73  4560.5 1725.57  4639.4 1723.71  4837.6 1723.42  5154.4 1723.28
  5361.3 1724.17  5479.7 1723.98  5487.6 1722.22  5488.1 1721.72  5499.8 1721.72
  5500.3 1722.22  5514.9 1723.71  5564.7 1723.78  5647.4 1725.16  5705.9 1726.31
  5770.7 1729.77  5788.2 1731.52  5798.3 1733.10  5819.3 1733.77  5861.8 1738.23
  5918.4 1742.24  5989.3 1745.05  6003.4 1746.34  6006.8 1746.01  6031.5 1746.54
#Mann=10,-1,0
  4395.3   0.035       0  4438.9    0.07       0  4837.6    0.16       0
  5361.3    0.05       0  5487.6    0.07       0  5500.3    0.05       0
  5647.4    0.07       0  5770.7   0.035       0  5788.2    0.07       0
  6006.8   0.035       0
Bank Sta=5487.6,5500.3
Exp/Cntr=0.3,0.1

Type RM Length L Ch R = 1,7253,419,419,419
BEGIN DESCRIPTION:
NC Unknown Stream 84 4.0
END DESCRIPTION:
XS GIS Cut Line= 3
      1524817.47      6916200.44      1523955.00      6915388.00
      1523155.04      6914938.02
#Sta/Elev= 30
  3815.1 1735.42  4334.3 1727.35  4455.5 1725.92  4536.2 1724.55  4756.8 1721.80
  5006.8 1720.76  5138.0 1722.08  5190.9 1718.33  5191.4 1717.83  5203.6 1718.33
  5278.2 1721.81  5294.1 1720.64  5299.9 1723.01  5315.8 1720.56  5337.5 1724.93
  5353.4 1723.64  5380.8 1726.49  5396.8 1724.68  5456.0 1727.41  5461.8 1724.07
  5477.7 1726.33  5483.4 1722.94  5499.4 1724.50  5505.1 1722.04  5521.1 1721.53
  5667.9 1724.18  5748.0 1725.54  5807.3 1732.30  5875.3 1734.76  5917.8 1738.22
#Mann=10,-1,0
  3815.1    0.07       0  4334.3   0.035       0  4455.5    0.07       0
  4536.2    0.05       0  4756.8    0.16       0  5006.8    0.05       0
  5190.9    0.07       0  5203.6    0.05       0  5667.9   0.035       0
  5875.3    0.07       0
Bank Sta=5190.9,5203.6
Exp/Cntr=0.3,0.1

Type RM Length L Ch R = 1,6834,882,882,882
BEGIN DESCRIPTION:
NC Unknown Stream 84 3.0
END DESCRIPTION:
XS GIS Cut Line= 3
      1525221.08      6915880.97      1524305.00      6915188.00
      1523104.98      6914387.99
#Sta/Elev= 30
  3843.0 1731.95  4225.2 1727.10  4457.0 1725.90  4534.9 1728.56  4624.2 1725.37
  4701.9 1721.19  4731.9 1720.07  4784.6 1719.32  4799.2 1721.38  4820.0 1718.82
  4863.7 1719.76  4884.5 1717.33  4934.4 1716.79  4963.6 1723.72  4969.8 1719.89
  4978.1 1720.43  4988.5 1716.95  5021.2 1716.63  5021.7 1716.13  5034.3 1716.63
  5179.4 1720.04  5200.5 1718.29  5285.3 1719.44  5291.5 1719.42  5456.3 1720.27
  5542.2 1719.71  5915.6 1725.17  6185.3 1734.15  6232.0 1736.03  6433.9 1747.42
#Mann=14,-1,0
  3843.0    0.07       0  4225.2   0.035       0  4457.0    0.07       0
  4624.2   0.035       0  4701.9    0.07       0  4731.9    0.05       0
  5021.2    0.05       0  5034.3    0.05       0  5285.3    0.16       0
  5291.5    0.05       0  5456.3   0.045       0  5542.2    0.07       0
  6185.3   0.035       0  6232.0    0.07       0
Bank Sta=5021.2,5034.3
Exp/Cntr=0.3,0.1

Type RM Length L Ch R = 1,5952,0,0,0
BEGIN DESCRIPTION:
NC Unknown Stream 84 2.0
END DESCRIPTION:
XS GIS Cut Line= 3
      1526076.15      6915238.63      1524805.00      6914638.00
      1523605.04      6914338.01
#Sta/Elev= 30
  3599.0 1726.70  3654.5 1725.56  3728.3 1720.84  3909.6 1717.74  4086.9 1716.52
  4098.0 1717.40  4109.1 1716.41  4164.3 1716.77  4230.7 1715.17  4245.7 1716.54
  4268.5 1714.70  4439.1 1713.86  4615.5 1712.88  4888.4 1714.54  4938.5 1714.73
  4989.6 1712.55  4990.1 1712.05  5003.0 1712.55  5187.9 1714.89  5481.6 1715.80
  5517.7 1717.17  5605.3 1716.52  5985.3 1718.28  6046.0 1720.52  6066.6 1722.54
  6095.0 1727.30  6136.2 1731.09  6141.3 1730.43  6177.4 1733.42  6241.8 1734.39
#Mann=7,-1,0
  3599.0   0.035       0  3909.6    0.07       0  4439.1   0.045       0
  4888.4    0.07       0  4989.6   0.045       0  5003.0    0.07       0
  5985.3    0.07       0
Bank Sta=4989.6,5003
Exp/Cntr=0.3,0.1

Chan Stop Cuts=-1