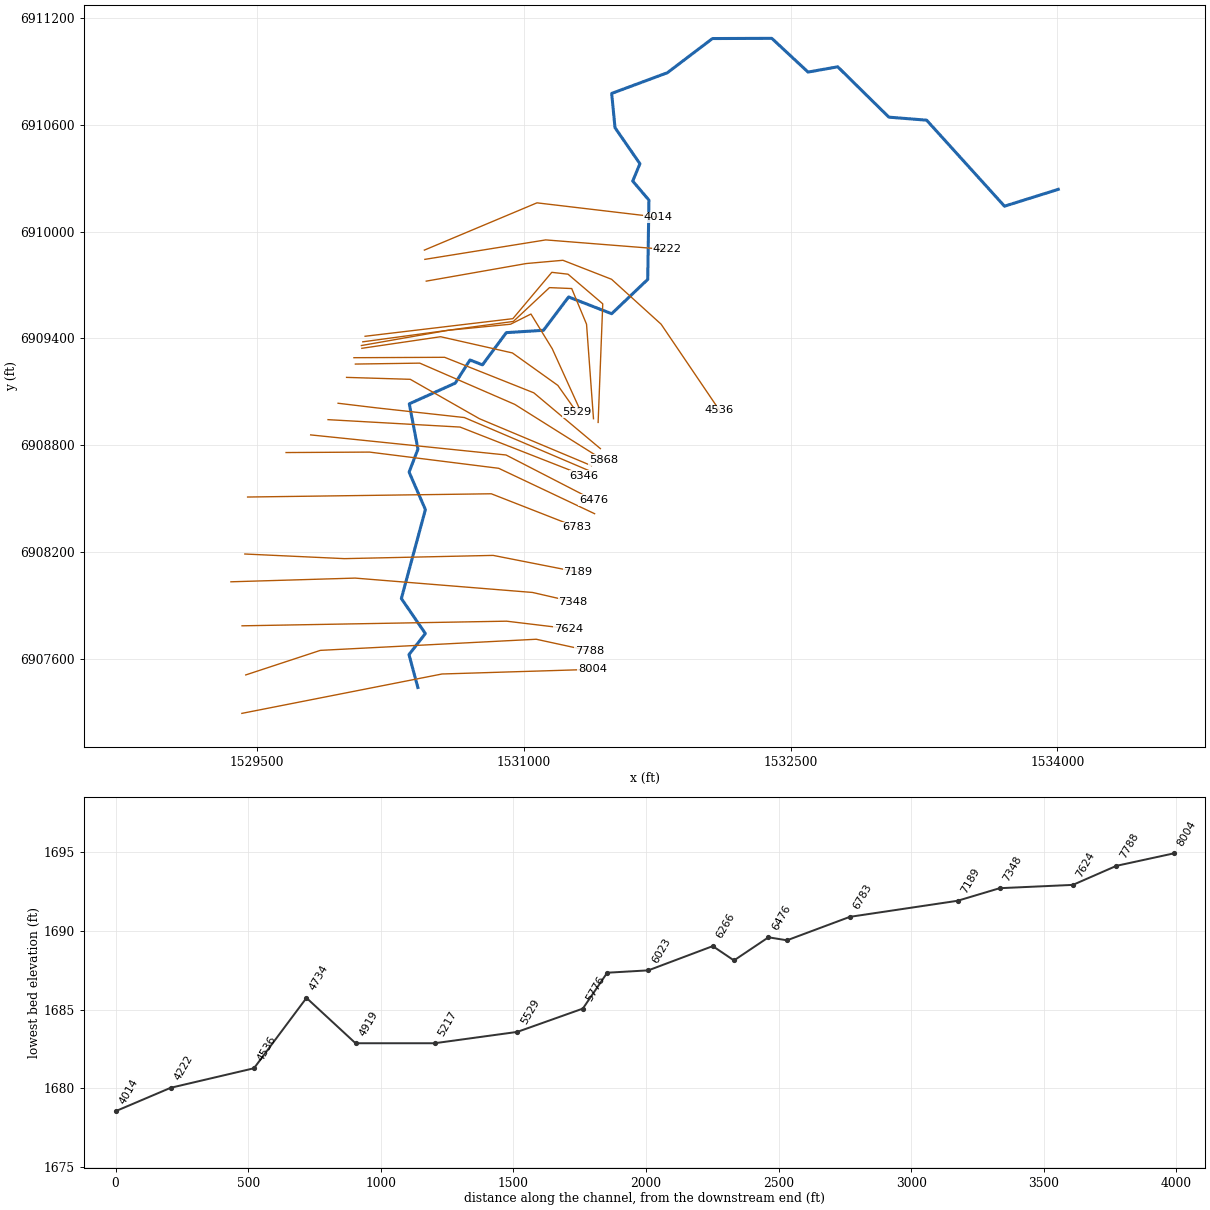
--- NC Unknown Stream 85.prj (project) ---

Proj Title=NC Unknown Stream 85 Base Level Engineering
Current Plan=p01
Default Exp/Contr=0.3,0.1
English Units
Geom File=g01
Flow File=f01
Plan File=p01
Y Axis Title=Elevation
X Axis Title(PF)=Main Channel Distance
X Axis Title(XS)=Station
BEGIN DESCRIPTION:
NC Unknown Stream 85
END DESCRIPTION:
DSS Export Rating Curves= 0
DSS Export Rating Curve Sorted= 0
DSS Export Volume Flow Curves= 0
DXF OffsetX= 0
DXF OffsetY= 0
DXF ScaleX= 1
DXF ScaleY= 10

--- NC Unknown Stream 85.p01 (plan) ---

Plan Title=Multiple Run
Short Identifier=Multiple
Geom File=g01
Flow File=f01
Subcritical Flow
K Sum by GR= 0
Std Step Tol= 0.01
Critical Tol= 0.01
Num of Std Step Trials= 20
Max Error Tol= 0.3
Flow Tol Ratio= 0.001
Split Flow NTrial= 30
Split Flow Tol= 0.02
Split Flow Ratio= 0.02
Log Output Level= 0
Friction Slope Method= 1
Unsteady Friction Slope Method= 2
Unsteady Bridges Friction Slope Method= 1
Parabolic Critical Depth
Global Vel Dist=  1 , 1 , 1
Global Log Level= 0
CheckData=True
Encroach Param= -1, 0, 0, 0
BEGIN DESCRIPTION:
Multiple Run
END DESCRIPTION:

--- NC Unknown Stream 85.f01 (steady flow) ---

Flow Title=Multiple
Number of Profiles=7
Profile Names=10-year,25-year,50-year,1pct_min,100-year,1pct_plu,500-year
River Rch & RM= NC Unknown Strea,Reach-1,8004
     211     289     353     215     428     855     639
River Rch & RM= NC Unknown Strea,Reach-1,6546
     285     395     485     297     592    1181     893
Boundary for River Rch & Prof#=NC Unknown Strea,Reach-1,1
Up Type=0
Dn Type=3
Dn Slope=0.007
Boundary for River Rch & Prof#=NC Unknown Strea,Reach-1,2
Up Type=0
Dn Type=3
Dn Slope=0.007
Boundary for River Rch & Prof#=NC Unknown Strea,Reach-1,3
Up Type=0
Dn Type=3
Dn Slope=0.007
Boundary for River Rch & Prof#=NC Unknown Strea,Reach-1,4
Up Type=0
Dn Type=3
Dn Slope=0.007
Boundary for River Rch & Prof#=NC Unknown Strea,Reach-1,5
Up Type=0
Dn Type=3
Dn Slope=0.007
Boundary for River Rch & Prof#=NC Unknown Strea,Reach-1,6
Up Type=0
Dn Type=3
Dn Slope=0.007
Boundary for River Rch & Prof#=NC Unknown Strea,Reach-1,7
Up Type=0
Dn Type=3
Dn Slope=0.007

--- NC Unknown Stream 85.g01 (geometry) ---

Geom Title=Existing Conditions

River Reach=NC Unknown Strea,Reach-1
Reach XY= 30
      1530405.00      6907438.00      1530355.25      6907622.79
      1530447.16      6907741.23      1530312.30      6907937.92
      1530447.44      6908438.00      1530355.77      6908648.69
      1530405.50      6908777.83      1530356.96      6909032.50
      1530615.00      6909148.65      1530698.05      6909278.81
      1530768.36      6909251.64      1530902.30      6909432.64
      1531111.21      6909445.80      1531252.46      6909633.04
      1531494.52      6909538.93      1531697.19      6909731.81
      1531703.95      6910177.56      1531612.84      6910284.60
      1531653.33      6910381.95      1531513.25      6910584.77
      1531494.57      6910777.22      1531807.45      6910893.47
      1532060.93      6911085.76      1532394.57      6911086.95
      1532598.33      6910897.29      1532765.32      6910926.90
      1533052.71      6910643.84      1533265.05      6910626.89
      1533702.55      6910143.45      1534005.00      6910238.00

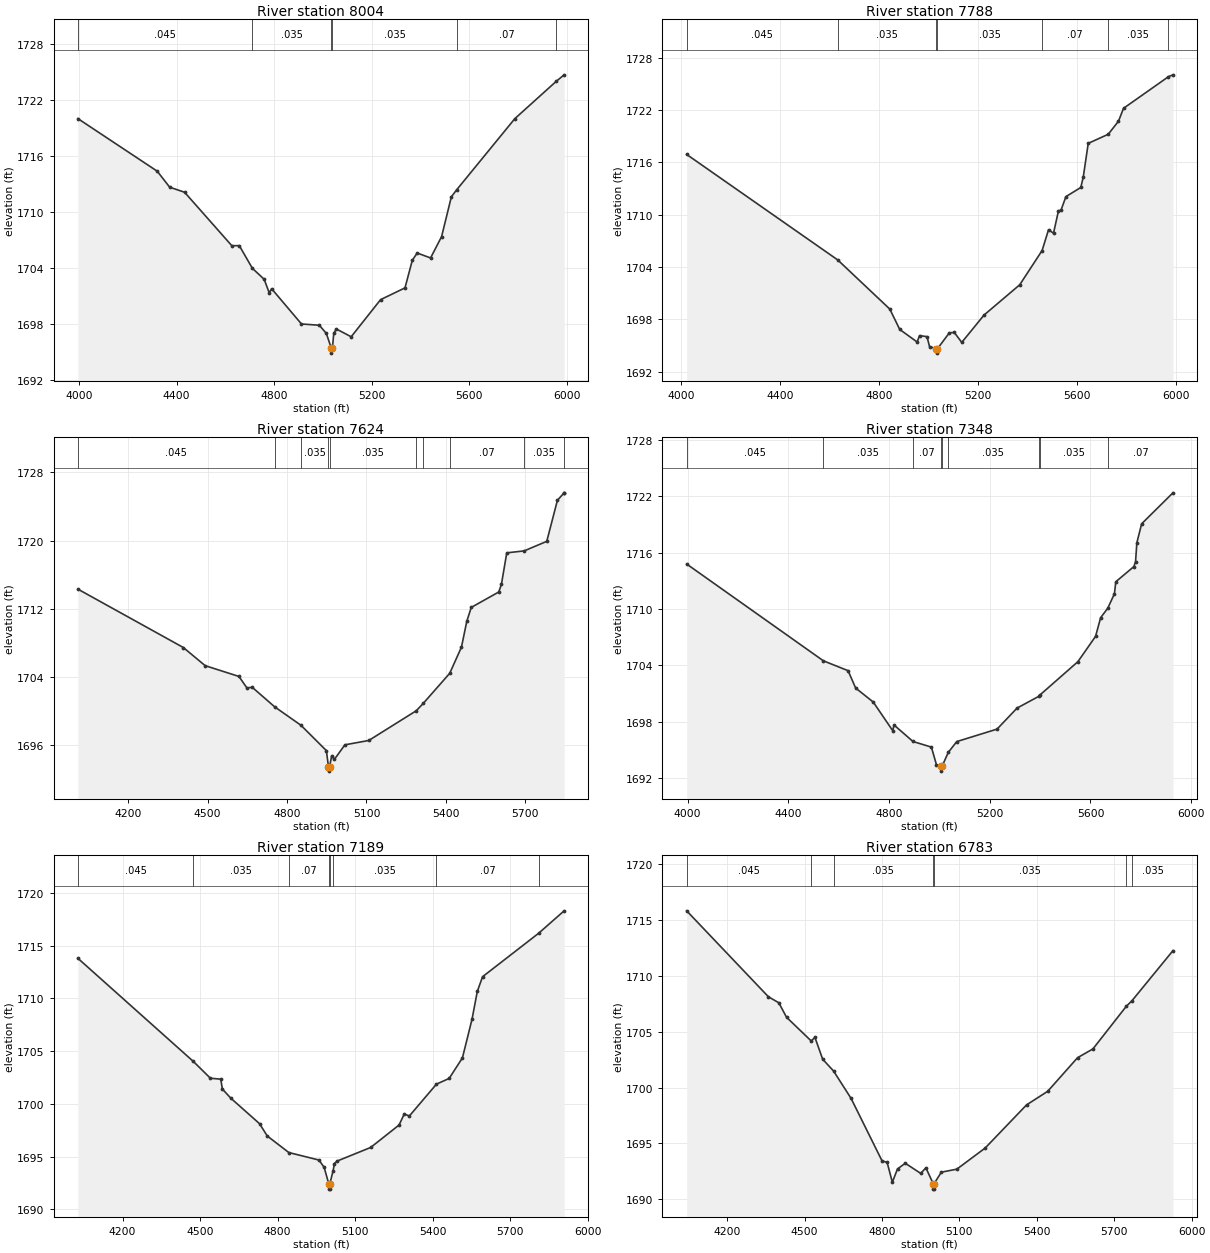
Type RM Length L Ch R = 1,8004,216,216,216
BEGIN DESCRIPTION:
NC Unknown Stream 85 8.0
END DESCRIPTION:
XS GIS Cut Line= 3
      1529415.69      6907292.43      1530540.73      6907513.80
      1531387.12      6907539.84
#Sta/Elev= 30
  3995.4 1720.01  4320.8 1714.38  4371.8 1712.67  4432.9 1712.13  4626.6 1706.41
  4657.2 1706.42  4710.9 1703.99  4759.1 1702.82  4779.9 1701.37  4789.7 1701.81
  4912.0 1698.04  4985.4 1697.90  5013.9 1697.03  5034.8 1695.42  5035.1 1694.92
  5038.8 1695.42  5044.4 1697.02  5054.6 1697.51  5115.8 1696.67  5236.3 1700.64
  5336.4 1701.90  5366.4 1704.85  5386.4 1705.63  5441.3 1705.10  5486.4 1707.38
  5526.5 1711.64  5547.9 1712.38  5786.6 1720.00  5957.1 1724.01  5988.8 1724.69
#Mann=6,-1,0
  3995.4   0.045       0  4710.9   0.035       0  5034.8   0.035       0
  5038.8   0.035       0  5547.9    0.07       0  5957.1   0.035       0
Bank Sta=5034.8,5038.8
Exp/Cntr=0.3,0.1

Type RM Length L Ch R = 1,7788,164,164,164
BEGIN DESCRIPTION:
Mapping XS ecd5017a
END DESCRIPTION:
XS GIS Cut Line= 4
      1529437.56      6907508.57      1529856.88      6907646.61
      1531070.42      6907709.11      1531369.92      6907644.00
#Sta/Elev= 30
  4024.0 1716.92  4633.8 1704.82  4844.1 1699.18  4884.1 1696.85  4954.2 1695.41
  4964.2 1696.14  4994.3 1696.02  5004.3 1694.89  5032.3 1694.63  5032.6 1694.13
  5036.3 1694.63  5084.4 1696.46  5104.4 1696.50  5134.5 1695.36  5224.6 1698.50
  5368.6 1701.97  5458.9 1705.90  5484.9 1708.29  5504.9 1707.88  5525.0 1710.46
  5535.0 1710.51  5555.0 1712.08  5615.1 1713.13  5625.1 1714.33  5645.1 1718.19
  5725.8 1719.23  5767.2 1720.73  5787.6 1722.21  5969.1 1725.84  5987.1 1726.05
#Mann=7,-1,0
  4024.0   0.045       0  4633.8   0.035       0  5032.3   0.035       0
  5036.3   0.035       0  5458.9    0.07       0  5725.8   0.035       0
  5969.1    0.07       0
Bank Sta=5032.3,5036.3
Exp/Cntr=0.3,0.1

Type RM Length L Ch R = 1,7624,276,276,276
BEGIN DESCRIPTION:
Mapping XS 2537a430
END DESCRIPTION:
XS GIS Cut Line= 3
      1529416.82      6907784.63      1530903.75      6907810.67
      1531250.10      6907769.01
#Sta/Elev= 30
  4010.3 1714.30  4408.5 1707.44  4490.9 1705.31  4618.6 1704.04  4648.6 1702.69
  4668.6 1702.77  4753.5 1700.47  4852.5 1698.31  4948.6 1695.33  4956.6 1693.42
  4956.9 1692.92  4960.6 1693.42  4968.6 1694.73  4978.6 1694.29  5018.6 1696.01
  5108.6 1696.52  5287.9 1700.01  5314.2 1700.87  5414.3 1704.41  5458.7 1707.49
  5478.7 1710.51  5495.6 1712.15  5599.4 1713.96  5609.5 1714.86  5629.7 1718.56
  5695.5 1718.79  5780.7 1719.91  5821.0 1724.74  5846.1 1725.60  5846.3 1725.61
#Mann=10,-1,0
  4010.3   0.045       0  4753.5    0.07       0  4852.5   0.035       0
  4956.6   0.035       0  4960.6   0.035       0  5287.9    0.07       0
  5314.2   0.035       0  5414.3    0.07       0  5695.5   0.035       0
  5846.1    0.07       0
Bank Sta=4956.6,4960.6
Exp/Cntr=0.3,0.1

Type RM Length L Ch R = 1,7348,159,159,159
BEGIN DESCRIPTION:
Mapping XS 7bf4483e
END DESCRIPTION:
XS GIS Cut Line= 4
      1529354.24      6908032.03      1530052.19      6908052.86
      1531049.59      6907972.13      1531276.15      6907920.05
#Sta/Elev= 30
  3996.1 1714.79  4539.1 1704.47  4637.1 1703.42  4667.2 1701.57  4737.3 1700.07
  4814.6 1697.02  4819.6 1697.63  4895.0 1695.87  4968.1 1695.27  4988.1 1693.40
  5006.2 1693.21  5006.4 1692.71  5010.2 1693.21  5035.2 1694.71  5068.9 1695.86
  5228.9 1697.19  5308.3 1699.43  5393.7 1700.67  5398.1 1700.80  5550.0 1704.38
  5620.2 1707.08  5640.3 1709.07  5668.4 1710.07  5695.0 1711.61  5700.6 1712.90
  5772.4 1714.52  5779.0 1715.04  5784.1 1717.05  5803.2 1719.08  5927.5 1722.38
#Mann=9,-1,0
  3996.1   0.045       0  4539.1   0.035       0  4895.0    0.07       0
  5006.2    0.07       0  5010.2    0.07       0  5035.2   0.035       0
  5393.7    0.07       0  5398.1   0.035       0  5668.4    0.07       0
Bank Sta=5006.2,5010.2
Exp/Cntr=0.3,0.1

Type RM Length L Ch R = 1,7189,406,406,406
BEGIN DESCRIPTION:
Mapping XS e8caadb0
END DESCRIPTION:
XS GIS Cut Line= 4
      1529432.45      6908188.27      1529992.30      6908162.23
      1530828.23      6908180.46      1531304.81      6908086.71
#Sta/Elev= 30
  4027.1 1713.81  4473.8 1704.03  4540.2 1702.43  4580.3 1702.34  4586.4 1701.41
  4619.0 1700.54  4730.3 1698.12  4760.3 1696.95  4843.8 1695.38  4960.3 1694.67
  4980.4 1693.98  4998.4 1692.41  4998.6 1691.91  5002.1 1691.91  5002.4 1692.41
  5015.0 1693.64  5020.4 1694.34  5030.4 1694.57  5160.4 1695.86  5270.4 1697.99
  5290.4 1699.03  5310.4 1698.85  5415.2 1701.87  5464.3 1702.41  5515.7 1704.36
  5552.9 1708.03  5573.3 1710.67  5593.7 1712.06  5810.6 1716.18  5909.4 1718.31
#Mann=8,-1,0
  4027.1   0.045       0  4473.8   0.035       0  4843.8    0.07       0
  4998.4    0.07       0  5002.4    0.07       0  5015.0   0.035       0
  5415.2    0.07       0  5810.6   0.035       0
Bank Sta=4998.4,5002.4
Exp/Cntr=0.3,0.1

Type RM Length L Ch R = 1,6783,237,237,237
BEGIN DESCRIPTION:
Mapping XS f0c5de9b
END DESCRIPTION:
XS GIS Cut Line= 3
      1529448.02      6908508.59      1530817.82      6908526.82
      1531297.02      6908339.30
#Sta/Elev= 30
  4043.0 1715.84  4360.0 1708.13  4400.0 1707.60  4430.0 1706.30  4525.8 1704.17
  4540.0 1704.50  4570.0 1702.54  4612.2 1701.48  4680.0 1699.03  4800.0 1693.43
  4820.0 1693.28  4840.0 1691.51  4860.1 1692.70  4890.1 1693.21  4950.1 1692.30
  4970.1 1692.80  4998.1 1691.39  4998.3 1690.89  5001.8 1690.89  5002.1 1691.39
  5030.1 1692.41  5090.1 1692.68  5200.1 1694.58  5360.1 1698.44  5442.1 1699.66
  5557.7 1702.67  5617.4 1703.46  5746.7 1707.28  5768.7 1707.78  5927.5 1712.27
#Mann=7,-1,0
  4043.0   0.045       0  4525.8    0.07       0  4612.2   0.035       0
  4998.1   0.035       0  5002.1   0.035       0  5746.7    0.07       0
  5768.7   0.035       0
Bank Sta=4998.1,5002.1
Exp/Cntr=0.3,0.1

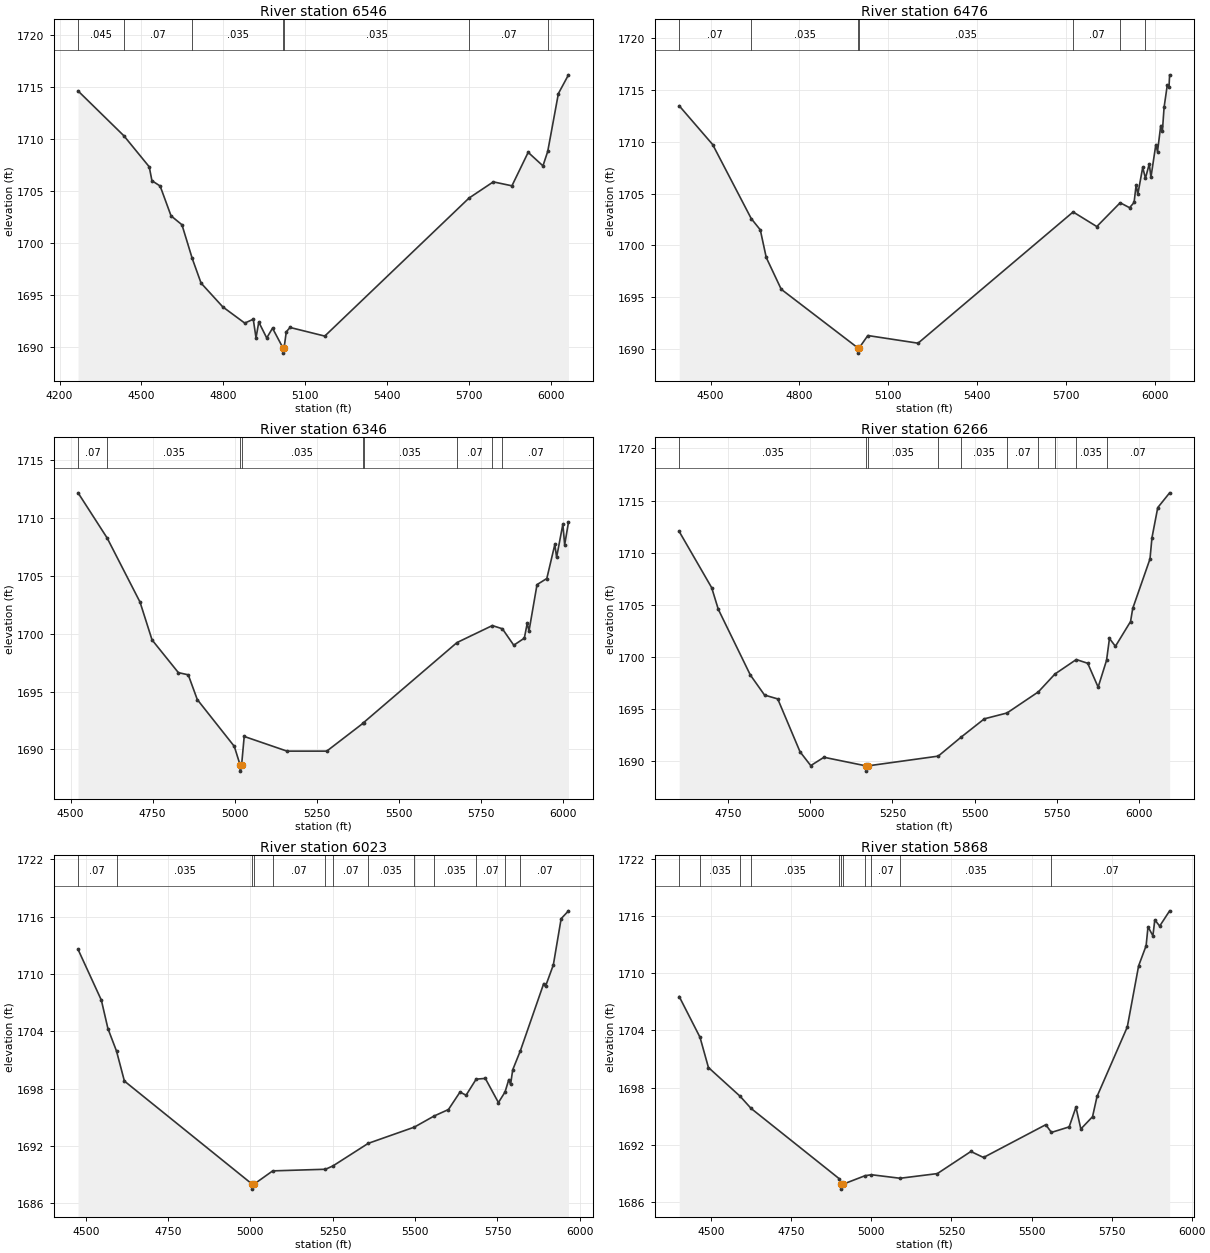
Type RM Length L Ch R = 1,6546,70,70,70
BEGIN DESCRIPTION:
Mapping XS dcf77656
END DESCRIPTION:
XS GIS Cut Line= 4
      1529664.22      6908758.59      1530132.92      6908761.19
      1530859.48      6908670.05      1531398.55      6908414.83
#Sta/Elev= 30
  4268.0 1714.63  4436.1 1710.31  4528.8 1707.33  4538.8 1705.99  4568.8 1705.48
  4608.8 1702.61  4648.8 1701.75  4686.4 1698.51  4718.8 1696.14  4798.4 1693.85
  4878.9 1692.29  4910.1 1692.66  4920.2 1690.87  4930.3 1692.39  4959.4 1690.86
  4980.7 1691.80  5019.0 1689.90  5019.3 1689.40  5023.1 1689.90  5031.1 1691.45
  5044.9 1691.87  5172.2 1691.04  5700.8 1704.32  5789.8 1705.88  5858.1 1705.50
  5917.6 1708.72  5971.8 1707.42  5989.3 1708.81  6028.4 1714.38  6065.4 1716.18
#Mann=7,-1,0
  4268.0   0.045       0  4436.1    0.07       0  4686.4   0.035       0
  5019.0   0.035       0  5023.1   0.035       0  5700.8    0.07       0
  5989.3   0.035       0
Bank Sta=5019,5023.1
Exp/Cntr=0.3,0.1

Type RM Length L Ch R = 1,6476,130,130,130
BEGIN DESCRIPTION:
Mapping XS 756342e0
END DESCRIPTION:
XS GIS Cut Line= 3
      1529802.52      6908857.75      1530900.63      6908744.90
      1531391.65      6908491.81
#Sta/Elev= 30
  4393.9 1713.49  4507.0 1709.74  4637.2 1702.59  4667.8 1701.50  4687.9 1698.83
  4738.5 1695.76  4997.5 1690.09  4997.8 1689.59  5001.6 1690.09  5031.0 1691.29
  5200.6 1690.55  5724.3 1703.23  5804.2 1701.82  5883.2 1704.12  5915.0 1703.64
  5930.2 1704.15  5937.2 1705.86  5942.8 1704.94  5959.3 1707.53  5968.6 1706.49
  5981.5 1707.88  5987.1 1706.58  6003.6 1709.73  6009.3 1709.06  6020.2 1711.58
  6025.8 1711.05  6031.5 1713.34  6042.3 1715.49  6048.0 1715.27  6050.2 1716.48
#Mann=7,-1,0
  4393.9    0.07       0  4637.2   0.035       0  4997.5   0.035       0
  5001.6   0.035       0  5724.3    0.07       0  5883.2   0.035       0
  5968.6    0.07       0
Bank Sta=4997.5,5001.6
Exp/Cntr=0.3,0.1

Type RM Length L Ch R = 1,6346,80,80,80
BEGIN DESCRIPTION:
Mapping XS 8a0487fe
END DESCRIPTION:
XS GIS Cut Line= 3
      1529900.13      6908943.48      1530642.30      6908901.82
      1531340.12      6908628.42
#Sta/Elev= 30
  4523.0 1712.19  4611.6 1708.28  4711.6 1702.74  4748.2 1699.47  4828.3 1696.64
  4858.4 1696.45  4885.9 1694.31  4998.6 1690.26  5016.6 1688.62  5016.8 1688.12
  5020.7 1688.62  5028.7 1691.12  5158.9 1689.85  5280.0 1689.85  5390.0 1692.25
  5392.2 1692.32  5676.4 1699.24  5784.0 1700.71  5814.6 1700.43  5849.2 1699.01
  5881.4 1699.62  5890.2 1700.91  5895.6 1700.24  5920.0 1704.25  5949.8 1704.78
  5974.3 1707.73  5979.6 1706.61  5998.7 1709.48  6004.1 1707.69  6015.8 1709.65
#Mann=9,-1,0
  4523.0    0.07       0  4611.6   0.035       0  5016.6   0.035       0
  5020.7   0.035       0  5390.0    0.07       0  5392.2   0.035       0
  5676.4    0.07       0  5784.0   0.035       0  5814.6    0.07       0
Bank Sta=5016.6,5020.7
Exp/Cntr=0.3,0.1

Type RM Length L Ch R = 1,6266,243,243,243
BEGIN DESCRIPTION:
Mapping XS 171c40d9
END DESCRIPTION:
XS GIS Cut Line= 4
      1529956.60      6909035.70      1530173.63      6909009.65
      1530666.25      6908955.40      1531384.61      6908649.39
#Sta/Elev= 30
  4599.8 1712.03  4698.9 1706.63  4719.0 1704.56  4816.6 1698.26  4860.0 1696.33
  4900.2 1695.96  4968.1 1690.89  5000.8 1689.56  5041.1 1690.36  5169.8 1689.53
  5170.1 1689.03  5173.9 1689.53  5389.4 1690.47  5459.5 1692.30  5530.0 1694.05
  5599.1 1694.61  5694.8 1696.64  5745.2 1698.35  5810.3 1699.74  5845.2 1699.38
  5876.9 1697.09  5902.5 1699.66  5911.4 1701.76  5929.6 1701.01  5975.7 1703.39
  5982.3 1704.64  6035.0 1709.40  6040.9 1711.42  6058.6 1714.32  6094.8 1715.74
#Mann=10,-1,0
  4599.8   0.035       0  5169.8   0.035       0  5173.9   0.035       0
  5389.4    0.07       0  5459.5   0.035       0  5599.1    0.07       0
  5694.8   0.035       0  5745.2    0.07       0  5810.3   0.035       0
  5902.5    0.07       0
Bank Sta=5169.8,5173.9
Exp/Cntr=0.3,0.1

Type RM Length L Ch R = 1,6023,155,155,155
BEGIN DESCRIPTION:
Mapping XS 26d138ef
END DESCRIPTION:
XS GIS Cut Line= 4
      1530004.32      6909181.10      1530362.43      6909170.24
      1530750.89      6908948.89      1531381.17      6908684.65
#Sta/Elev= 30
  4476.8 1712.58  4547.5 1707.27  4567.5 1704.29  4593.5 1701.94  4617.5 1698.80
  5006.1 1687.99  5006.3 1687.49  5010.2 1687.99  5067.7 1689.40  5227.9 1689.57
  5250.6 1689.92  5357.6 1692.28  5497.6 1693.98  5558.0 1695.15  5601.1 1695.82
  5636.3 1697.65  5654.7 1697.32  5685.3 1699.00  5713.1 1699.08  5752.9 1696.55
  5773.0 1697.66  5784.4 1698.96  5789.8 1698.45  5796.3 1699.98  5819.7 1701.99
  5890.4 1709.01  5895.8 1708.71  5919.6 1710.96  5943.3 1715.80  5965.6 1716.62
#Mann=13,-1,0
  4476.8    0.07       0  4593.5   0.035       0  5006.1   0.035       0
  5010.2   0.035       0  5067.7    0.07       0  5227.9   0.035       0
  5250.6    0.07       0  5357.6   0.035       0  5497.6    0.07       0
  5558.0   0.035       0  5685.3    0.07       0  5773.0   0.035       0
  5819.7    0.07       0
Bank Sta=5006.1,5010.2
Exp/Cntr=0.3,0.1

Type RM Length L Ch R = 1,5868,92,92,92
BEGIN DESCRIPTION:
Mapping XS 63c935ce
END DESCRIPTION:
XS GIS Cut Line= 4
      1530053.75      6909255.98      1530415.73      6909261.19
      1530949.59      6909029.42      1531446.96      6908716.94
#Sta/Elev= 30
  4399.8 1707.55  4464.8 1703.27  4491.1 1700.10  4590.1 1697.08  4624.2 1695.81
  4900.0 1688.42  4906.0 1687.84  4906.3 1687.34  4910.1 1687.84  4980.3 1688.75
  5000.2 1688.85  5089.6 1688.48  5205.9 1688.97  5310.6 1691.29  5350.1 1690.66
  5544.5 1694.10  5562.1 1693.29  5617.5 1693.87  5638.7 1695.94  5654.0 1693.65
  5690.5 1694.94  5704.5 1697.06  5799.0 1704.35  5834.4 1710.77  5857.8 1712.88
  5863.7 1714.87  5879.0 1713.92  5884.9 1715.59  5900.2 1714.94  5931.2 1716.54
#Mann=11,-1,0
  4399.8    0.07       0  4464.8   0.035       0  4590.1    0.07       0
  4624.2   0.035       0  4900.0    0.07       0  4906.0   0.035       0
  4910.1    0.07       0  4980.3   0.035       0  5000.2    0.07       0
  5089.6   0.035       0  5562.1    0.07       0
Bank Sta=4906,4910.1
Exp/Cntr=0.3,0.1

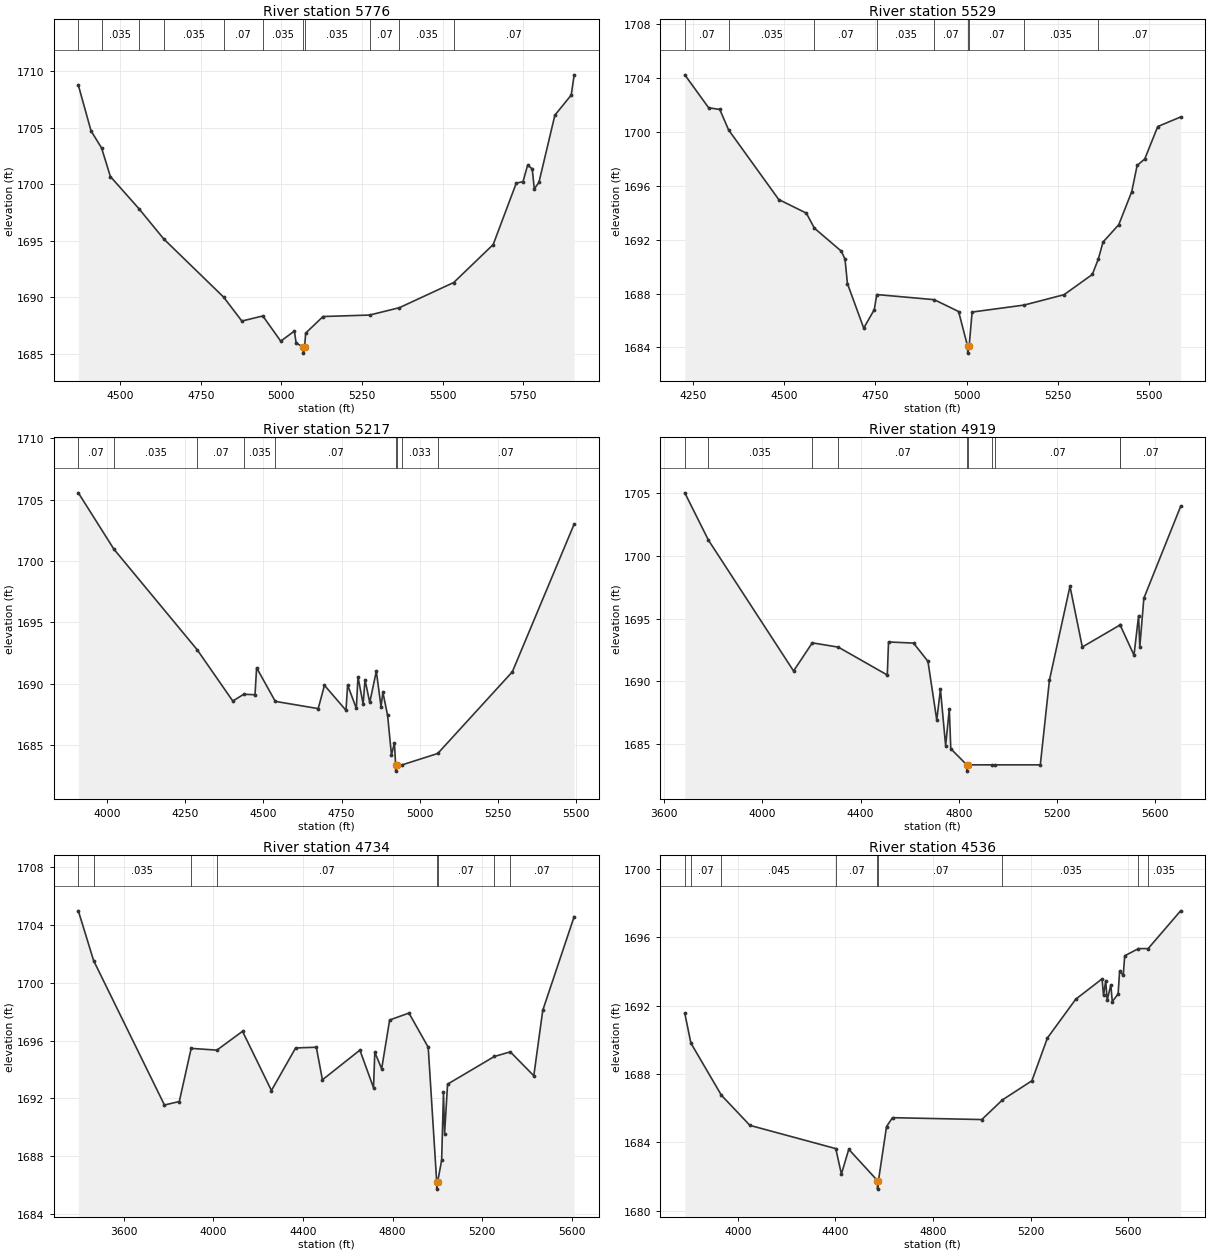
Type RM Length L Ch R = 1,5776,247,247,247
BEGIN DESCRIPTION:
Mapping XS 824dc66a
END DESCRIPTION:
XS GIS Cut Line= 4
      1530045.59      6909291.77      1530555.57      6909293.94
      1531056.88      6909094.29      1531431.12      6908780.61
#Sta/Elev= 30
  4370.3 1708.78  4409.7 1704.73  4442.5 1703.21  4469.7 1700.69  4558.1 1697.85
  4635.1 1695.17  4820.9 1690.02  4877.5 1687.90  4942.6 1688.35  4998.1 1686.12
  5040.4 1687.01  5045.8 1685.98  5068.0 1685.56  5068.2 1685.06  5072.1 1685.56
  5075.4 1686.83  5129.3 1688.30  5273.9 1688.43  5365.9 1689.08  5534.7 1691.31
  5657.1 1694.67  5728.7 1700.11  5749.5 1700.23  5763.8 1701.69  5778.1 1701.37
  5784.6 1699.60  5798.9 1700.17  5848.4 1706.12  5899.1 1707.90  5908.2 1709.69
#Mann=11,-1,0
  4370.3    0.07       0  4442.5   0.035       0  4558.1    0.07       0
  4635.1   0.035       0  4820.9    0.07       0  4942.6   0.035       0
  5068.0   0.035       0  5072.1   0.035       0  5273.9    0.07       0
  5365.9   0.035       0  5534.7    0.07       0
Bank Sta=5068,5072.1
Exp/Cntr=0.3,0.1

Type RM Length L Ch R = 1,5529,312,312,312
BEGIN DESCRIPTION:
Mapping XS 40695924
END DESCRIPTION:
XS GIS Cut Line= 5
      1530090.17      6909344.52      1530532.92      6909409.63
      1530936.57      6909318.48      1531191.77      6909136.19
      1531298.53      6908985.17
#Sta/Elev= 30
  4227.2 1704.25  4292.7 1701.80  4323.1 1701.68  4347.3 1700.16  4484.8 1694.99
  4560.5 1693.98  4582.7 1692.86  4656.6 1691.15  4666.7 1690.55  4673.2 1688.75
  4717.9 1685.44  4746.9 1686.81  4753.7 1687.93  4911.4 1687.55  4978.2 1686.67
  5002.9 1684.08  5003.1 1683.58  5007.0 1684.08  5015.2 1686.63  5157.9 1687.15
  5267.4 1687.92  5344.8 1689.42  5361.3 1690.56  5374.3 1691.83  5417.4 1693.12
  5453.0 1695.57  5467.8 1697.52  5488.7 1698.00  5524.4 1700.41  5587.1 1701.12
#Mann=9,-1,0
  4227.2    0.07       0  4347.3   0.035       0  4582.7    0.07       0
  4753.7   0.035       0  4911.4    0.07       0  5002.9    0.07       0
  5007.0    0.07       0  5157.9   0.035       0  5361.3    0.07       0
Bank Sta=5002.9,5007
Exp/Cntr=0.3,0.1

Type RM Length L Ch R = 1,5217,298,298,298
BEGIN DESCRIPTION:
Mapping XS 9d4496c3
END DESCRIPTION:
XS GIS Cut Line= 6
      1530087.58      6909360.15      1530577.19      6909446.09
      1530926.15      6909479.94      1531040.73      6909537.23
      1531160.52      6909341.92      1531316.77      6908998.17
#Sta/Elev= 30
  3909.2 1705.56  4022.7 1700.97  4288.9 1692.76  4402.6 1688.58  4437.7 1689.13
  4473.6 1689.09  4478.7 1691.29  4538.4 1688.55  4675.4 1687.96  4695.5 1689.86
  4764.2 1687.82  4769.4 1689.88  4797.3 1687.98  4802.5 1690.56  4819.0 1688.32
  4825.0 1690.31  4840.1 1688.46  4861.1 1691.01  4876.1 1688.12  4882.1 1689.29
  4897.2 1687.40  4909.5 1684.18  4919.0 1685.16  4922.8 1683.36  4923.1 1682.86
  4927.0 1683.36  4942.2 1683.36  5057.4 1684.30  5295.6 1690.96  5493.1 1703.01
#Mann=9,-1,0
  3909.2    0.07       0  4022.7   0.035       0  4288.9    0.07       0
  4437.7   0.035       0  4538.4    0.07       0  4922.8   0.033       0
  4927.0    0.07       0  4942.2   0.033       0  5057.4    0.07       0
Bank Sta=4922.8,4927
Exp/Cntr=0.3,0.1

Type RM Length L Ch R = 1,4919,185,185,185
BEGIN DESCRIPTION:
Mapping XS 8bbeb8b1
END DESCRIPTION:
XS GIS Cut Line= 6
      1530095.43      6909380.99      1530941.77      6909495.57
      1531144.90      6909685.67      1531269.90      6909680.46
      1531353.23      6909479.94      1531392.29      6908948.73
#Sta/Elev= 30
  3684.6 1705.01  3780.7 1701.25  4127.5 1690.83  4203.7 1693.07  4309.5 1692.73
  4509.1 1690.51  4514.1 1693.14  4616.0 1693.05  4674.6 1691.60  4710.5 1686.93
  4725.5 1689.37  4746.6 1684.88  4761.6 1687.81  4767.6 1684.64  4832.7 1683.36
  4833.0 1682.86  4836.9 1683.36  4937.2 1683.36  4947.5 1683.36  5132.1 1683.36
  5169.2 1690.09  5252.9 1697.57  5303.1 1692.74  5456.6 1694.49  5457.1 1694.49
  5513.6 1692.09  5532.2 1695.23  5537.2 1692.75  5553.7 1696.62  5703.4 1703.93
#Mann=10,-1,0
  3684.6    0.07       0  3780.7   0.035       0  4203.7   0.045       0
  4309.5    0.07       0  4832.7    0.07       0  4836.9    0.07       0
  4937.2   0.033       0  4947.5    0.07       0  5456.6   0.035       0
  5457.1    0.07       0
Bank Sta=4832.7,4836.9
Exp/Cntr=0.3,0.1

Type RM Length L Ch R = 1,4734,198,198,198
BEGIN DESCRIPTION:
Mapping XS acb927fd
END DESCRIPTION:
XS GIS Cut Line= 6
      1530108.48      6909412.24      1530939.17      6909511.19
      1531157.92      6909771.61      1531249.07      6909761.19
      1531444.38      6909594.53      1531418.34      6908927.89
#Sta/Elev= 30
  3397.9 1704.96  3466.2 1701.52  3782.2 1691.55  3848.4 1691.79  3901.4 1695.46
  4016.3 1695.34  4130.6 1696.64  4259.6 1692.55  4367.5 1695.49  4459.9 1695.54
  4487.1 1693.29  4654.4 1695.34  4715.2 1692.74  4720.9 1695.19  4751.5 1694.05
  4787.1 1697.42  4873.2 1697.90  4959.2 1695.54  4997.1 1686.24  4997.4 1685.74
  5001.3 1686.24  5019.2 1687.74  5027.3 1692.42  5032.3 1689.58  5045.6 1692.99
  5254.2 1694.90  5325.5 1695.22  5430.4 1693.57  5470.4 1698.09  5610.5 1704.56
#Mann=8,-1,0
  3397.9    0.07       0  3466.2   0.035       0  3901.4   0.045       0
  4016.3    0.07       0  4997.1    0.07       0  5001.3    0.07       0
  5254.2   0.035       0  5325.5    0.07       0
Bank Sta=4997.1,5001.3
Exp/Cntr=0.3,0.1

Type RM Length L Ch R = 1,4536,314,314,314
BEGIN DESCRIPTION:
Mapping XS b9a477c1
END DESCRIPTION:
XS GIS Cut Line= 6
      1530452.17      6909722.13      1531014.69      6909821.09
      1531220.42      6909839.32      1531493.86      6909732.55
      1531772.50      6909479.94      1532100.30      6908996.06
#Sta/Elev= 30
  3783.1 1691.55  3808.2 1689.81  3933.2 1686.76  4050.0 1685.00  4401.8 1683.64
  4424.8 1682.15  4455.0 1683.60  4572.5 1681.77  4572.8 1681.27  4576.7 1681.77
  4609.8 1684.93  4634.3 1685.45  5000.1 1685.34  5084.7 1686.49  5205.5 1687.61
  5269.0 1690.11  5385.1 1692.38  5493.0 1693.57  5499.0 1692.60  5507.9 1693.47
  5513.9 1692.32  5528.9 1693.22  5534.9 1692.24  5558.8 1692.69  5564.8 1694.01
  5579.8 1693.79  5585.8 1694.92  5642.1 1695.34  5681.7 1695.34  5814.9 1697.55
#Mann=9,-1,0
  3783.1   0.045       0  3808.2    0.07       0  3933.2   0.045       0
  4401.8    0.07       0  4572.5    0.07       0  4576.7    0.07       0
  5084.7   0.035       0  5642.1    0.07       0  5681.7   0.035       0
Bank Sta=4572.5,4576.7
Exp/Cntr=0.3,0.1

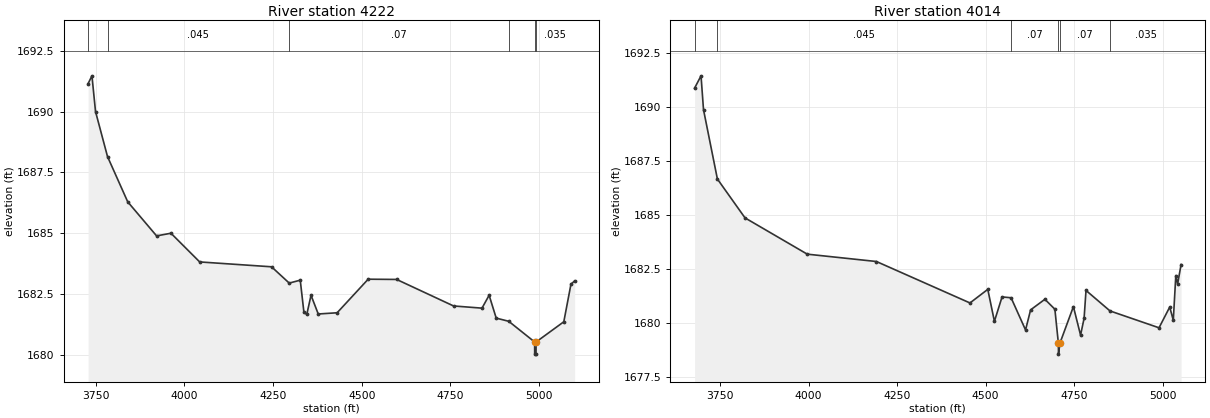
Type RM Length L Ch R = 1,4222,208,208,208
BEGIN DESCRIPTION:
Mapping XS 6a1f2da7
END DESCRIPTION:
XS GIS Cut Line= 3
      1530444.35      6909844.52      1531124.07      6909953.90
      1531805.38      6909899.98
#Sta/Elev= 30
  3728.5 1691.15  3739.3 1691.47  3749.4 1690.00  3783.2 1688.15  3840.2 1686.29
  3921.6 1684.89  3962.1 1685.00  4043.1 1683.82  4245.7 1683.62  4295.6 1682.95
  4326.7 1683.07  4336.9 1681.77  4345.1 1681.66  4357.1 1682.45  4377.4 1681.68
  4430.7 1681.73  4518.2 1683.11  4598.5 1683.10  4759.0 1682.01  4839.2 1681.92
  4859.3 1682.45  4879.3 1681.51  4914.6 1681.38  4987.6 1680.53  4987.8 1680.03
  4991.5 1680.03  4991.8 1680.53  5069.9 1681.36  5090.0 1682.90  5100.4 1683.04
#Mann=6,-1,0
  3728.5    0.07       0  3783.2   0.045       0  4295.6    0.07       0
  4914.6   0.035       0  4987.6   0.035       0  4991.8   0.035       0
Bank Sta=4987.6,4991.8
Exp/Cntr=0.3,0.1

Type RM Length L Ch R = 1,4014,0,0,0
BEGIN DESCRIPTION:
Mapping XS cb891d4f
END DESCRIPTION:
XS GIS Cut Line= 3
      1530441.73      6909896.59      1531074.59      6910162.23
      1531756.88      6910081.51
#Sta/Elev= 30
  3678.4 1690.86  3696.6 1691.43  3703.6 1689.86  3742.8 1686.65  3820.8 1684.85
  3996.5 1683.17  4191.7 1682.83  4455.8 1680.91  4506.1 1681.54  4524.8 1680.06
  4546.4 1681.19  4571.9 1681.15  4612.7 1679.66  4627.0 1680.59  4667.3 1681.08
  4695.5 1680.62  4705.4 1679.04  4705.7 1678.54  4709.6 1679.04  4747.8 1680.74
  4768.0 1679.42  4778.0 1680.20  4783.4 1681.49  4851.2 1680.54  4989.5 1679.76
  5019.7 1680.72  5029.8 1680.11  5036.9 1682.18  5042.0 1681.79  5051.8 1682.69
#Mann=6,-1,0
  3678.4    0.07       0  3742.8   0.045       0  4571.9    0.07       0
  4705.4   0.035       0  4709.6    0.07       0  4851.2   0.035       0
Bank Sta=4705.4,4709.6
Exp/Cntr=0.3,0.1

Chan Stop Cuts=-1