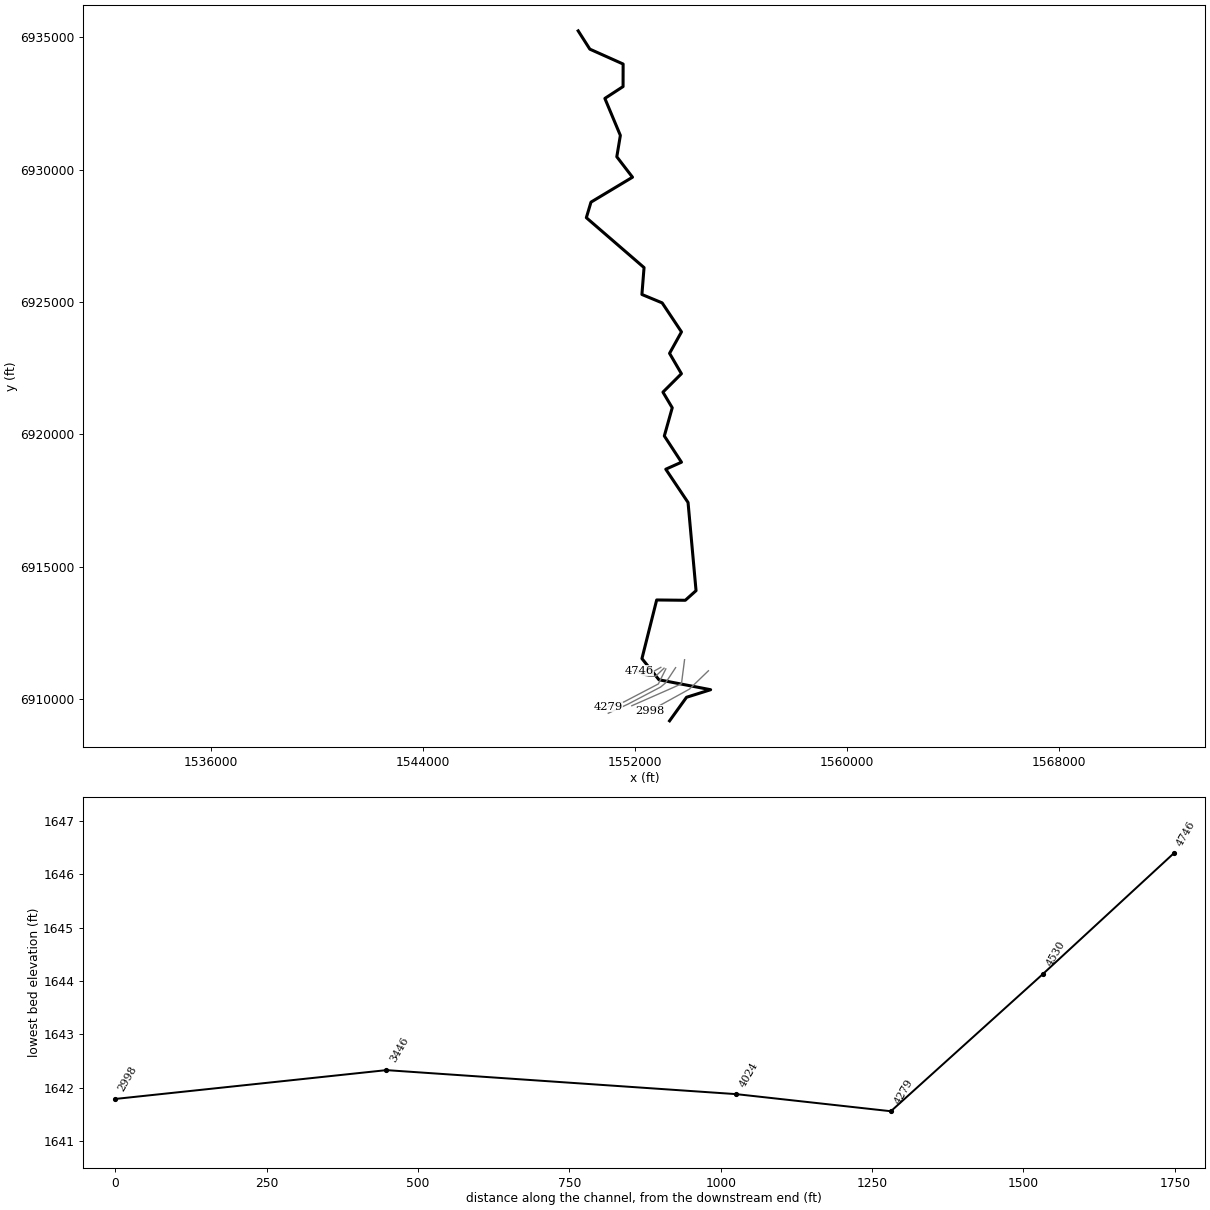
--- NC Unknown Stream 88.prj (project) ---

Proj Title=NC Unknown Stream 88 Base Level Engineering
Current Plan=p01
Default Exp/Contr=0.3,0.1
English Units
Geom File=g01
Flow File=f01
Plan File=p01
BEGIN DESCRIPTION:
NC Unknown Stream 88
END DESCRIPTION:

--- NC Unknown Stream 88.p01 (plan) ---

Plan Title=Multiple Run
Short Identifier=Multiple
Geom File=g01
Flow File=f01
Subcritical Flow
K Sum by GR= 0
Std Step Tol= 0.01
Critical Tol= 0.01
Num of Std Step Trials= 20
Max Error Tol= 0.3
Flow Tol Ratio= 0.001
Split Flow NTrial= 30
Split Flow Tol= 0.02
Split Flow Ratio= 0.02
Log Output Level= 0
Friction Slope Method= 1
Unsteady Friction Slope Method= 2
Unsteady Bridges Friction Slope Method= 1
Parabolic Critical Depth
Global Vel Dist=  1 , 1 , 1
Global Log Level= 0
CheckData=True
Encroach Param= -1, 0, 0, 0
BEGIN DESCRIPTION:
Multiple Run
END DESCRIPTION:

--- NC Unknown Stream 88.f01 (steady flow) ---

Flow Title=Multiple
Number of Profiles=7
Profile Names=10-year,25-year,50-year,1pct_min,100-year,1pct_plu,500-year
River Rch & RM= NC Unknown Strea,Reach-1,4746
     620     883    1105     686    1368    2730    2128
River Rch & RM= NC Unknown Strea,Reach-1,4279
    1011    1468    1862    1169    2332    4653    3712
Boundary for River Rch & Prof#=NC Unknown Strea,Reach-1,1
Up Type=0
Dn Type=3
Dn Slope=0.001
Boundary for River Rch & Prof#=NC Unknown Strea,Reach-1,2
Up Type=0
Dn Type=3
Dn Slope=0.001
Boundary for River Rch & Prof#=NC Unknown Strea,Reach-1,3
Up Type=0
Dn Type=3
Dn Slope=0.001
Boundary for River Rch & Prof#=NC Unknown Strea,Reach-1,4
Up Type=0
Dn Type=3
Dn Slope=0.001
Boundary for River Rch & Prof#=NC Unknown Strea,Reach-1,5
Up Type=0
Dn Type=3
Dn Slope=0.001
Boundary for River Rch & Prof#=NC Unknown Strea,Reach-1,6
Up Type=0
Dn Type=3
Dn Slope=0.001
Boundary for River Rch & Prof#=NC Unknown Strea,Reach-1,7
Up Type=0
Dn Type=3
Dn Slope=0.001

--- NC Unknown Stream 88.g01 (geometry) ---

Geom Title=Existing Conditions

River Reach=NC Unknown Strea,Reach-1
Reach XY= 30
      1549855.00      6935238.00      1550294.82      6934548.32
      1551551.55      6933986.52      1551549.31      6933135.43
      1550862.06      6932688.00      1551447.00      6931291.33
      1551312.84      6930484.73      1551905.51      6929713.04
      1550337.78      6928771.79      1550162.60      6928184.66
      1552341.38      6926301.22      1552260.80      6925285.71
      1553025.16      6924968.40      1553754.76      6923872.78
      1553304.49      6923063.03      1553752.86      6922293.97
      1553054.45      6921598.19      1553405.60      6921008.05
      1553107.24      6919943.93      1553754.62      6918953.15
      1553162.07      6918688.00      1554002.74      6917432.06
      1554304.69      6914103.02      1553898.95      6913739.58
      1552818.40      6913751.36      1552262.10      6911538.00
      1552905.00      6910738.00      1554855.75      6910362.80
      1553945.21      6910077.48      1553305.00      6909188.00

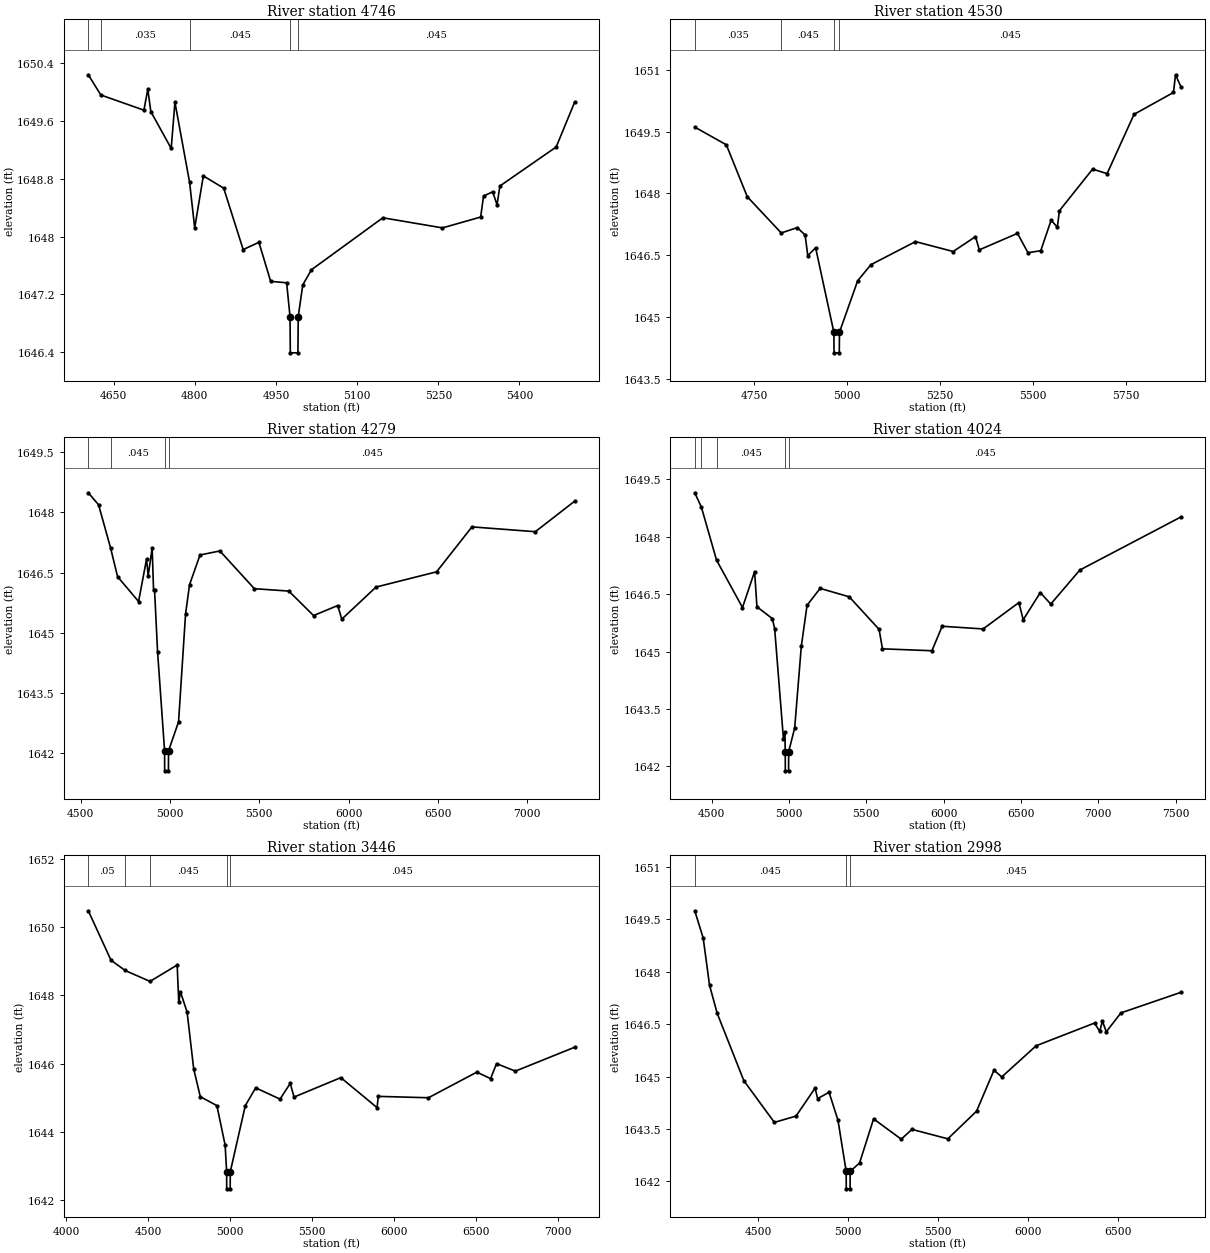
Type RM Length L Ch R = 1,4746,216,216,216
BEGIN DESCRIPTION:
Mapping XS 67cfced8
END DESCRIPTION:
XS GIS Cut Line= 4
      1552974.67      6911207.39      1552603.15      6910999.06
      1552323.64      6911014.69      1552143.11      6911082.39
#Sta/Elev= 30
  4603.2 1650.24  4626.4 1649.96  4706.0 1649.75  4713.1 1650.04  4718.8 1649.73
  4756.4 1649.22  4763.3 1649.86  4790.4 1648.75  4799.8 1648.12  4815.8 1648.84
  4853.4 1648.67  4889.4 1647.82  4918.5 1647.92  4940.2 1647.38  4969.7 1647.36
  4976.0 1646.89  4976.5 1646.39  4990.6 1646.39  4991.1 1646.89  4999.5 1647.33
  5015.5 1647.54  5147.5 1648.26  5257.7 1648.12  5328.2 1648.27  5333.6 1648.56
  5350.4 1648.62  5358.5 1648.44  5363.8 1648.70  5467.8 1649.24  5501.9 1649.86
#Mann=5,-1,0
  4603.2    0.05       0  4626.4   0.035       0  4790.4   0.045       0
  4976.0   0.045       0  4991.1   0.045       0
Bank Sta=4976,4991.1
Exp/Cntr=0.3,0.1

Type RM Length L Ch R = 1,4530,251,251,251
BEGIN DESCRIPTION:
Mapping XS ec8b825b
END DESCRIPTION:
XS GIS Cut Line= 5
      1553096.48      6911176.54      1552778.54      6910871.63
      1552523.55      6910870.55      1552324.85      6910917.00
      1551959.08      6911100.97
#Sta/Elev= 30
  4589.8 1649.61  4674.8 1649.18  4731.1 1647.92  4822.6 1647.04  4865.7 1647.17
  4886.8 1646.99  4894.0 1646.49  4915.1 1646.68  4964.2 1644.63  4964.7 1644.13
  4978.8 1644.13  4979.3 1644.63  5028.3 1645.88  5063.9 1646.27  5183.9 1646.83
  5285.3 1646.59  5345.4 1646.95  5355.7 1646.63  5458.4 1647.03  5486.7 1646.56
  5521.1 1646.61  5549.0 1647.35  5565.7 1647.18  5571.3 1647.58  5660.6 1648.59
  5699.6 1648.48  5772.2 1649.92  5878.2 1650.45  5883.8 1650.88  5898.8 1650.58
#Mann=4,-1,0
  4589.8   0.035       0  4822.6   0.045       0  4964.2   0.045       0
  4979.3   0.045       0
Bank Sta=4964.2,4979.3
Exp/Cntr=0.3,0.1

Type RM Length L Ch R = 1,4279,255,255,255
BEGIN DESCRIPTION:
Mapping XS 96f7fe28
END DESCRIPTION:
XS GIS Cut Line= 4
      1553163.75      6911148.34      1552881.63      6910580.83
      1551587.09      6909904.19      1550984.23      6909722.55
#Sta/Elev= 30
  4541.8 1648.49  4599.4 1648.19  4666.3 1647.12  4705.8 1646.40  4823.4 1645.78
  4868.2 1646.84  4877.2 1646.42  4899.5 1647.11  4907.4 1646.06  4913.0 1646.06
  4929.8 1644.53  4969.1 1642.06  4969.6 1641.56  4990.7 1641.56  4991.2 1642.06
  5047.4 1642.78  5086.6 1645.47  5109.0 1646.20  5167.6 1646.94  5278.9 1647.04
  5471.9 1646.10  5665.0 1646.04  5803.6 1645.43  5939.0 1645.68  5961.6 1645.34
  6153.4 1646.14  6492.7 1646.52  6690.7 1647.64  7045.8 1647.52  7265.9 1648.28
#Mann=4,-1,0
  4541.8   0.035       0  4666.3   0.045       0  4969.1   0.045       0
  4991.2   0.045       0
Bank Sta=4969.1,4991.2
Exp/Cntr=0.3,0.1

Type RM Length L Ch R = 1,4024,578,578,578
BEGIN DESCRIPTION:
Mapping XS f9a748dc
END DESCRIPTION:
XS GIS Cut Line= 5
      1553532.76      6911195.90      1553152.55      6910617.77
      1552967.65      6910464.12      1551732.27      6909816.90
      1550990.61      6909474.72
#Sta/Elev= 30
  4391.6 1649.15  4434.8 1648.77  4532.3 1647.39  4700.1 1646.15  4778.4 1647.09
  4793.5 1646.17  4892.9 1645.86  4908.0 1645.60  4965.2 1642.70  4974.3 1642.89
  4976.5 1642.38  4977.0 1641.88  4998.1 1641.88  4998.6 1642.38  5037.5 1643.00
  5080.4 1645.14  5117.6 1646.21  5202.2 1646.65  5390.0 1646.43  5583.0 1645.58
  5605.0 1645.07  5924.7 1645.02  5990.9 1645.66  6255.6 1645.59  6487.0 1646.28
  6514.7 1645.83  6625.2 1646.54  6692.9 1646.24  6880.8 1647.13  7535.4 1648.52
#Mann=5,-1,0
  4391.6   0.045       0  4434.8   0.035       0  4532.3   0.045       0
  4976.5   0.045       0  4998.6   0.045       0
Bank Sta=4976.5,4998.6
Exp/Cntr=0.3,0.1

Type RM Length L Ch R = 1,3446,448,448,448
BEGIN DESCRIPTION:
Mapping XS c7b6e4f0
END DESCRIPTION:
XS GIS Cut Line= 4
      1553871.30      6911495.40      1553754.11      6910589.12
      1553462.44      6910453.71      1551879.19      6909757.39
#Sta/Elev= 30
  4135.1 1650.48  4273.6 1649.03  4359.8 1648.73  4511.4 1648.41  4677.0 1648.89
  4686.5 1647.80  4697.1 1648.10  4737.5 1647.51  4777.8 1645.84  4818.1 1645.03
  4919.0 1644.77  4969.4 1643.61  4978.5 1642.83  4979.0 1642.33  5000.2 1642.33
  5000.7 1642.83  5092.4 1644.77  5155.6 1645.29  5304.0 1644.96  5366.3 1645.42
  5389.5 1645.02  5674.7 1645.59  5895.7 1644.71  5903.0 1645.04  6208.9 1645.00
  6503.8 1645.75  6587.6 1645.56  6624.0 1646.00  6738.6 1645.78  7100.1 1646.48
#Mann=5,-1,0
  4135.1    0.05       0  4359.8   0.035       0  4511.4   0.045       0
  4978.5   0.045       0  5000.7   0.045       0
Bank Sta=4978.5,5000.7
Exp/Cntr=0.3,0.1

Type RM Length L Ch R = 1,2998,0,0,0
BEGIN DESCRIPTION:
NC Unknown Stream 88 1.0
END DESCRIPTION:
XS GIS Cut Line= 3
      1554771.56      6911077.71      1554051.06      6910383.25
      1552558.88      6909560.23
#Sta/Elev= 30
  4147.1 1649.74  4194.0 1648.96  4229.3 1647.61  4271.7 1646.81  4420.2 1644.88
  4589.9 1643.69  4710.3 1643.87  4816.3 1644.67  4830.5 1644.37  4894.0 1644.55
  4943.7 1643.75  4989.2 1642.29  4989.7 1641.79  5010.9 1641.79  5011.4 1642.29
  5063.8 1642.53  5141.6 1643.79  5295.4 1643.21  5355.0 1643.49  5554.4 1643.22
  5714.3 1644.01  5811.1 1645.18  5854.7 1644.99  6045.5 1645.88  6370.5 1646.53
  6399.5 1646.29  6414.0 1646.59  6435.8 1646.28  6517.2 1646.82  6851.9 1647.41
#Mann=3,-1,0
  4147.1   0.045       0  4989.2   0.045       0  5011.4   0.045       0
Bank Sta=4989.2,5011.4
Exp/Cntr=0.3,0.1

Chan Stop Cuts=-1