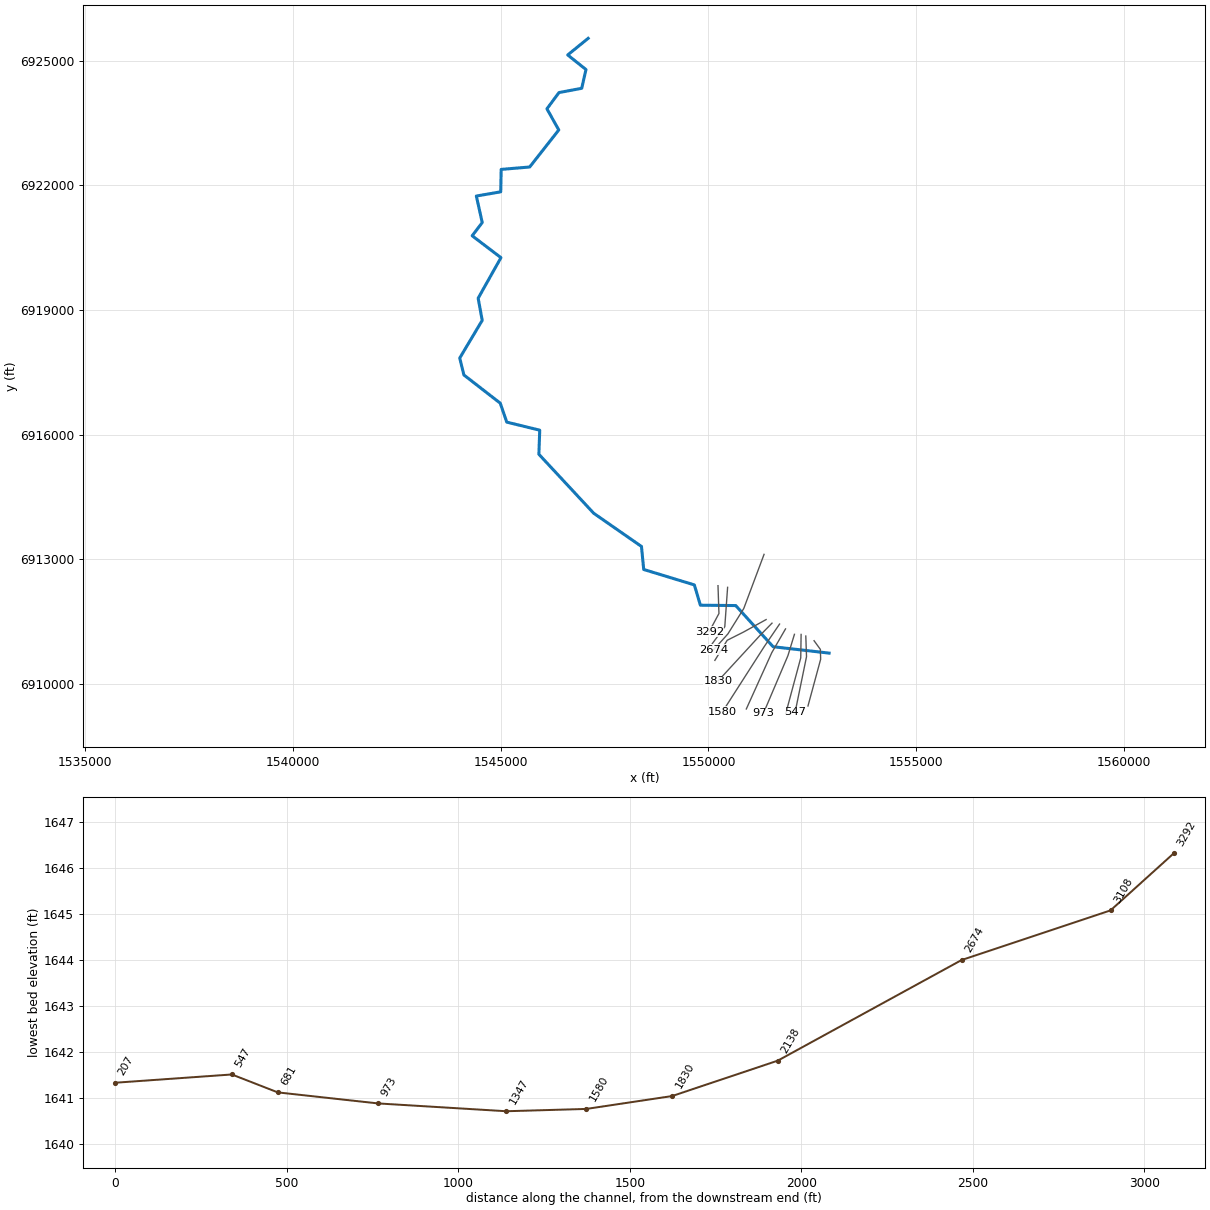
--- NC Unknown Stream 90.prj (project) ---

Proj Title=NC Unknown Stream 90 Base Level Engineering
Current Plan=p01
Default Exp/Contr=0.3,0.1
English Units
Geom File=g01
Flow File=f01
Plan File=p01
BEGIN DESCRIPTION:
NC Unknown Stream 90
END DESCRIPTION:

--- NC Unknown Stream 90.p01 (plan) ---

Plan Title=Multiple Run
Short Identifier=Multiple
Geom File=g01
Flow File=f01
Subcritical Flow
K Sum by GR= 0
Std Step Tol= 0.01
Critical Tol= 0.01
Num of Std Step Trials= 20
Max Error Tol= 0.3
Flow Tol Ratio= 0.001
Split Flow NTrial= 30
Split Flow Tol= 0.02
Split Flow Ratio= 0.02
Log Output Level= 0
Friction Slope Method= 1
Unsteady Friction Slope Method= 2
Unsteady Bridges Friction Slope Method= 1
Parabolic Critical Depth
Global Vel Dist=  1 , 1 , 1
Global Log Level= 0
CheckData=True
Encroach Param= -1, 0, 0, 0
BEGIN DESCRIPTION:
Multiple Run
END DESCRIPTION:

--- NC Unknown Stream 90.f01 (steady flow) ---

Flow Title=Multiple
Number of Profiles=7
Profile Names=10-year,25-year,50-year,1pct_min,100-year,1pct_plu,500-year
River Rch & RM= NC Unknown Strea,Reach-1,3292
     476     670     832     513    1024    2042    1570
River Rch & RM= NC Unknown Strea,Reach-1,2138
     545     772     962     595    1187    2368    1832
Boundary for River Rch & Prof#=NC Unknown Strea,Reach-1,1
Up Type=0
Dn Type=3
Dn Slope=0.001
Boundary for River Rch & Prof#=NC Unknown Strea,Reach-1,2
Up Type=0
Dn Type=3
Dn Slope=0.001
Boundary for River Rch & Prof#=NC Unknown Strea,Reach-1,3
Up Type=0
Dn Type=3
Dn Slope=0.001
Boundary for River Rch & Prof#=NC Unknown Strea,Reach-1,4
Up Type=0
Dn Type=3
Dn Slope=0.001
Boundary for River Rch & Prof#=NC Unknown Strea,Reach-1,5
Up Type=0
Dn Type=3
Dn Slope=0.001
Boundary for River Rch & Prof#=NC Unknown Strea,Reach-1,6
Up Type=0
Dn Type=3
Dn Slope=0.001
Boundary for River Rch & Prof#=NC Unknown Strea,Reach-1,7
Up Type=0
Dn Type=3
Dn Slope=0.001

--- NC Unknown Stream 90.g01 (geometry) ---

Geom Title=Existing Conditions

River Reach=NC Unknown Strea,Reach-1
Reach XY= 30
      1547105.00      6925538.00      1546612.07      6925138.00
      1547051.93      6924786.57      1546949.88      6924335.17
      1546402.54      6924232.48      1546112.41      6923841.40
      1546397.24      6923331.83      1545696.90      6922440.47
      1545010.44      6922382.83      1545000.00      6921842.99
      1544413.00      6921741.35      1544554.52      6921103.20
      1544312.58      6920784.65      1545005.48      6920258.16
      1544456.62      6919281.97      1544554.07      6918748.48
      1544013.04      6917841.32      1544112.82      6917434.59
      1544988.61      6916754.79      1545145.29      6916298.75
      1545938.80      6916104.72      1545918.53      6915524.62
      1547238.33      6914104.65      1548388.35      6913305.53
      1548441.62      6912751.54      1549661.07      6912379.87
      1549806.22      6911891.43      1550657.45      6911882.54
      1551556.58      6910891.83      1552905.00      6910738.00

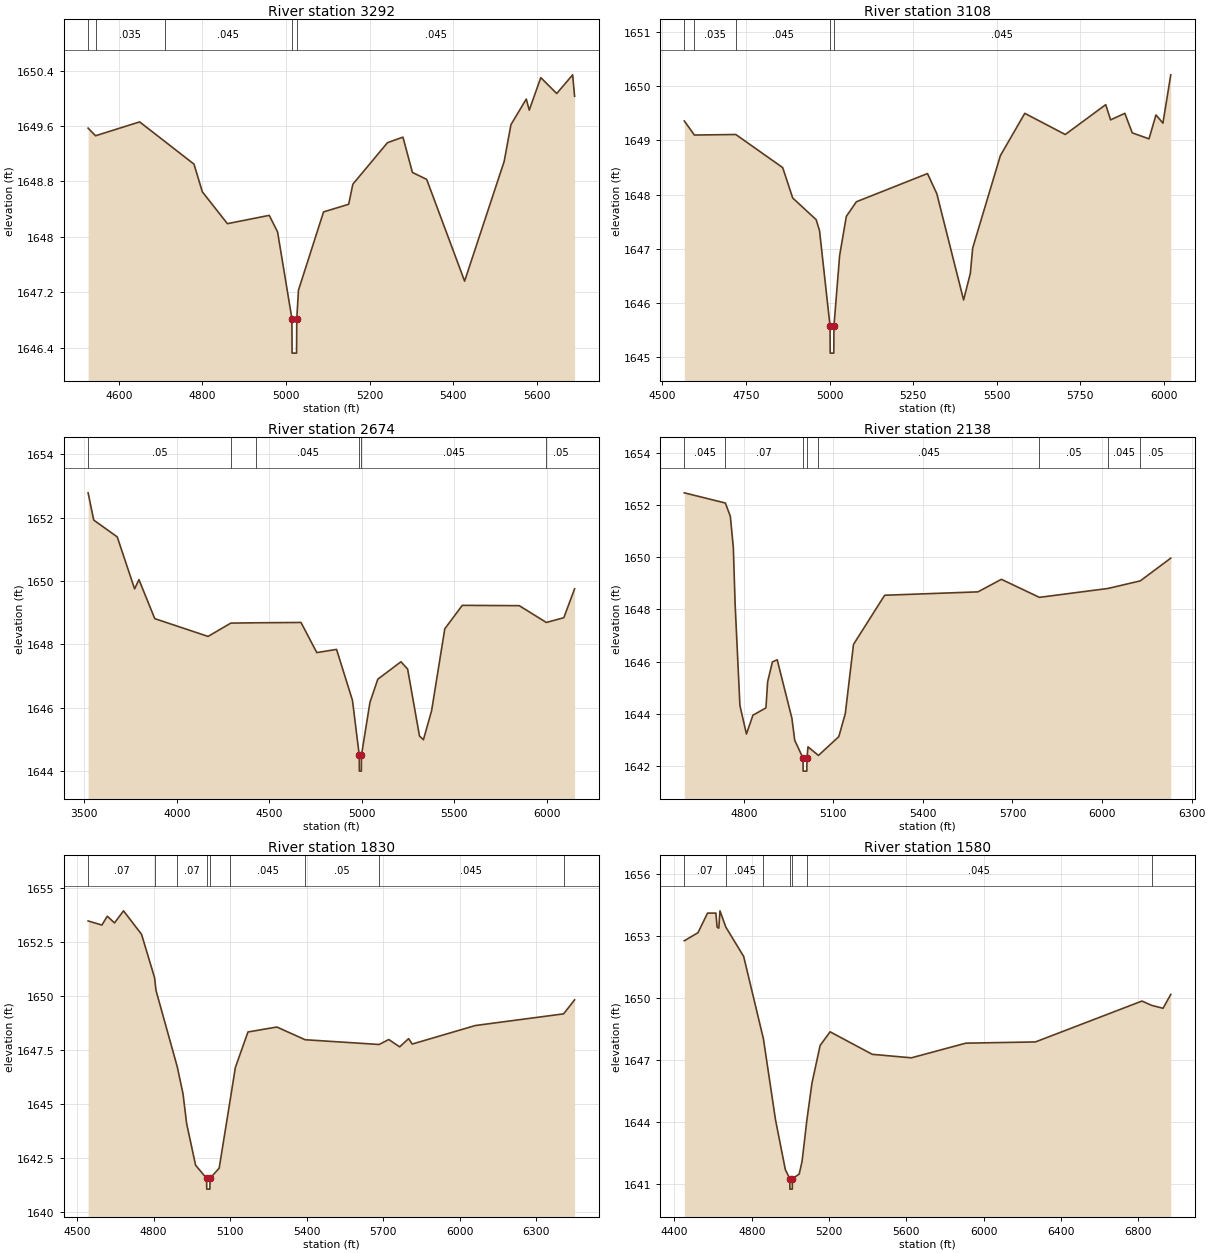
Type RM Length L Ch R = 1,3292,184,184,184
BEGIN DESCRIPTION:
NC Unknown Stream 90 3.0
END DESCRIPTION:
XS GIS Cut Line= 3
      1550230.55      6912361.23      1550253.12      6911691.17
      1550019.36      6911256.13
#Sta/Elev= 30
  4526.5 1649.57  4544.3 1649.46  4649.8 1649.66  4709.6 1649.38  4779.9 1649.05
  4799.9 1648.65  4859.9 1648.19  4960.0 1648.31  4980.0 1648.07  5014.2 1646.82
  5014.7 1646.32  5025.4 1646.32  5025.9 1646.82  5030.0 1647.23  5090.0 1648.36
  5150.1 1648.47  5160.1 1648.76  5243.0 1649.36  5280.0 1649.44  5302.7 1648.93
  5336.8 1648.83  5427.6 1647.36  5522.3 1649.09  5538.5 1649.62  5575.2 1649.99
  5582.3 1649.83  5609.9 1650.30  5648.1 1650.07  5686.2 1650.34  5690.8 1650.03
#Mann=5,-1,0
  4526.5    0.05       0  4544.3   0.035       0  4709.6   0.045       0
  5014.2   0.045       0  5025.9   0.045       0
Bank Sta=5014.2,5025.9
Exp/Cntr=0.3,0.1

Type RM Length L Ch R = 1,3108,434,434,434
BEGIN DESCRIPTION:
Mapping XS 88ad763f
END DESCRIPTION:
XS GIS Cut Line= 3
      1550461.64      6912321.61      1550393.94      6911373.70
      1550093.61      6910967.48
#Sta/Elev= 30
  4565.3 1649.36  4595.6 1649.10  4719.5 1649.11  4859.7 1648.50  4889.7 1647.94
  4959.9 1647.54  4969.9 1647.34  5001.4 1645.58  5001.9 1645.08  5012.6 1645.08
  5013.1 1645.58  5030.1 1646.88  5050.1 1647.60  5080.2 1647.87  5293.0 1648.39
  5320.8 1648.02  5401.0 1646.06  5421.1 1646.55  5428.3 1647.02  5511.0 1648.72
  5584.1 1649.50  5705.2 1649.11  5826.2 1649.66  5840.8 1649.38  5883.4 1649.50
  5905.6 1649.14  5955.7 1649.03  5976.5 1649.47  5997.4 1649.32  6020.8 1650.21
#Mann=5,-1,0
  4565.3    0.05       0  4595.6   0.035       0  4719.5   0.045       0
  5001.4   0.045       0  5013.1   0.045       0
Bank Sta=5001.4,5013.1
Exp/Cntr=0.3,0.1

Type RM Length L Ch R = 1,2674,536,536,536
BEGIN DESCRIPTION:
Mapping XS 37d8ca7e
END DESCRIPTION:
XS GIS Cut Line= 4
      1551339.18      6913115.37      1550850.53      6911811.20
      1550468.59      6911200.09      1550123.89      6910816.73
#Sta/Elev= 30
  3521.1 1652.78  3551.5 1651.92  3678.5 1651.39  3772.3 1649.75  3795.9 1650.04
  3881.4 1648.81  4169.3 1648.25  4292.4 1648.67  4428.0 1648.68  4671.6 1648.69
  4757.0 1647.74  4863.8 1647.84  4949.8 1646.23  4986.4 1644.50  4986.9 1644.00
  4997.7 1644.00  4998.2 1644.50  5044.2 1646.17  5086.6 1646.90  5211.6 1647.45
  5247.8 1647.22  5311.8 1645.11  5333.1 1644.99  5377.5 1645.91  5448.6 1648.49
  5543.0 1649.23  5851.2 1649.22  5997.4 1648.69  6091.9 1648.84  6150.0 1649.75
#Mann=6,-1,0
  3521.1    0.05       0  4292.4   0.035       0  4428.0   0.045       0
  4986.4   0.045       0  4998.2   0.045       0  5997.4    0.05       0
Bank Sta=4986.4,4998.2
Exp/Cntr=0.3,0.1

Type RM Length L Ch R = 1,2138,308,308,308
BEGIN DESCRIPTION:
Mapping XS 35a181fb
END DESCRIPTION:
XS GIS Cut Line= 4
      1551388.69      6911545.55      1550845.33      6911245.23
      1550451.58      6911046.76      1550155.15      6910563.27
#Sta/Elev= 30
  4601.1 1652.46  4738.6 1652.07  4755.3 1651.56  4765.3 1650.37  4771.4 1648.18
  4787.4 1644.32  4809.2 1643.23  4830.9 1643.95  4874.5 1644.23  4880.2 1645.23
  4896.2 1645.99  4912.3 1646.07  4961.5 1643.83  4970.9 1642.99  4998.6 1642.31
  4999.1 1641.81  5011.4 1641.81  5011.9 1642.31  5015.4 1642.74  5050.3 1642.41
  5118.5 1643.13  5140.2 1644.01  5167.7 1646.66  5272.0 1648.54  5584.3 1648.67
  5662.9 1649.15  5790.1 1648.46  6019.7 1648.80  6127.9 1649.09  6230.0 1649.96
#Mann=8,-1,0
  4601.1   0.045       0  4738.6    0.07       0  4998.6    0.07       0
  5011.9    0.07       0  5050.3   0.045       0  5790.1    0.05       0
  6019.7   0.045       0  6127.9    0.05       0
Bank Sta=4998.6,5011.9
Exp/Cntr=0.3,0.1

Type RM Length L Ch R = 1,1830,250,250,250
BEGIN DESCRIPTION:
NC Unknown Stream 90 2.0
END DESCRIPTION:
XS GIS Cut Line= 3
      1551530.19      6911459.17      1551241.59      6911164.06
      1550229.01      6910064.29
#Sta/Elev= 30
  4542.9 1653.48  4596.9 1653.29  4618.1 1653.70  4646.4 1653.39  4681.8 1653.95
  4752.5 1652.86  4803.5 1650.85  4809.1 1650.26  4892.6 1646.71  4915.1 1645.46
  4929.3 1644.08  4964.4 1642.15  5007.6 1641.54  5008.1 1641.04  5020.4 1641.04
  5020.9 1641.54  5056.8 1642.01  5100.4 1645.20  5120.3 1646.68  5169.7 1648.33
  5283.1 1648.56  5394.0 1647.97  5684.1 1647.75  5722.0 1647.98  5764.6 1647.64
  5799.7 1648.02  5813.9 1647.77  6061.7 1648.63  6407.5 1649.17  6450.6 1649.82
#Mann=9,-1,0
  4542.9    0.07       0  4803.5   0.045       0  4892.6    0.07       0
  5007.6    0.07       0  5020.9    0.07       0  5100.4   0.045       0
  5394.0    0.05       0  5684.1   0.045       0  6407.5    0.05       0
Bank Sta=5007.6,5020.9
Exp/Cntr=0.3,0.1

Type RM Length L Ch R = 1,1580,233,233,233
BEGIN DESCRIPTION:
Mapping XS 17449ff1
END DESCRIPTION:
XS GIS Cut Line= 3
      1551712.53      6911437.52      1551343.59      6910894.97
      1550339.59      6909327.80
#Sta/Elev= 30
  4451.0 1652.79  4521.8 1653.18  4571.4 1654.13  4614.6 1654.13  4620.7 1653.45
  4629.6 1653.40  4635.6 1654.24  4666.1 1653.45  4758.3 1652.03  4860.5 1648.04
  4923.0 1644.12  4973.8 1641.71  4997.0 1641.26  4997.5 1640.76  5009.9 1640.76
  5010.4 1641.26  5045.7 1641.49  5060.6 1642.11  5085.3 1644.10  5111.6 1645.89
  5153.9 1647.72  5205.5 1648.38  5423.6 1647.29  5626.1 1647.12  5908.0 1647.83
  6268.2 1647.89  6819.4 1649.87  6869.5 1649.66  6928.5 1649.52  6968.3 1650.19
#Mann=7,-1,0
  4451.0    0.07       0  4666.1   0.045       0  4860.5    0.07       0
  4997.0    0.07       0  5010.4    0.07       0  5085.3   0.045       0
  6869.5    0.05       0
Bank Sta=4997,5010.4
Exp/Cntr=0.3,0.1

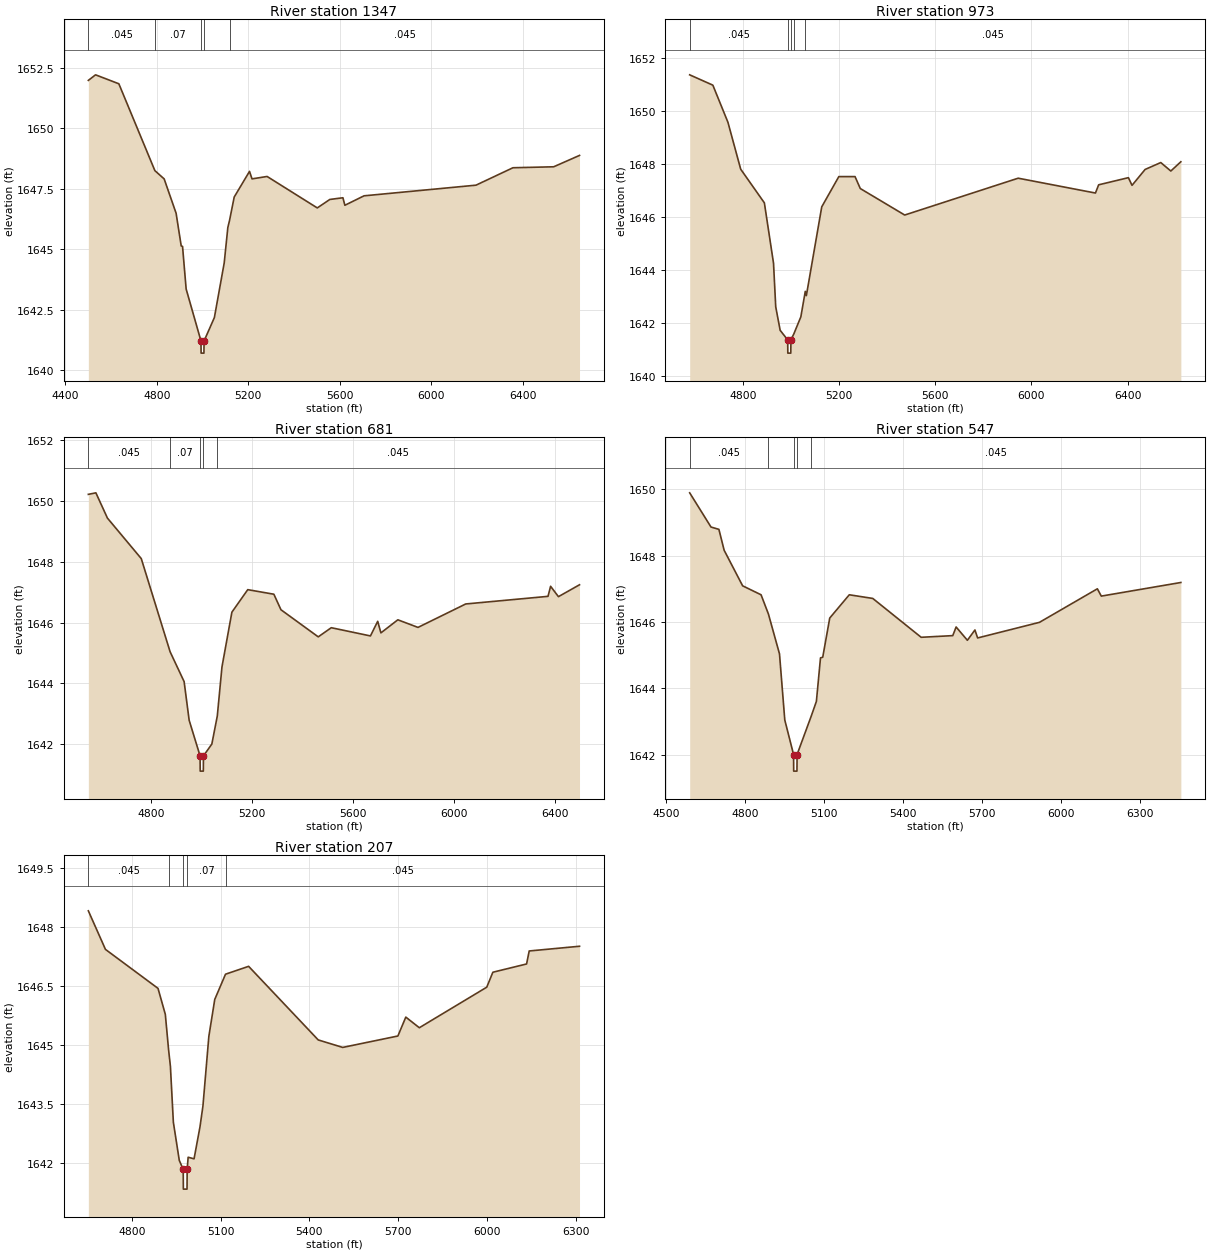
Type RM Length L Ch R = 1,1347,374,374,374
BEGIN DESCRIPTION:
Mapping XS b507a926
END DESCRIPTION:
XS GIS Cut Line= 3
      1551855.73      6911320.30      1551525.88      6910749.57
      1550912.11      6909393.17
#Sta/Elev= 30
  4500.7 1651.98  4532.2 1652.21  4634.1 1651.84  4791.7 1648.25  4832.2 1647.91
  4884.5 1646.49  4906.8 1645.14  4912.6 1645.12  4928.4 1643.36  4993.3 1641.21
  4993.8 1640.71  5006.2 1640.71  5006.7 1641.21  5051.9 1642.18  5094.9 1644.44
  5110.7 1645.90  5118.1 1646.19  5138.6 1647.16  5205.5 1648.22  5216.5 1647.91
  5282.4 1648.01  5501.9 1646.71  5556.8 1647.06  5614.0 1647.13  5622.6 1646.82
  5706.4 1647.21  6195.9 1647.65  6357.6 1648.37  6535.8 1648.41  6648.7 1648.88
#Mann=5,-1,0
  4500.7   0.045       0  4791.7    0.07       0  4993.3    0.07       0
  5006.7    0.07       0  5118.1   0.045       0
Bank Sta=4993.3,5006.7
Exp/Cntr=0.3,0.1

Type RM Length L Ch R = 1,973,292,292,292
BEGIN DESCRIPTION:
Mapping XS af7f7f3a
END DESCRIPTION:
XS GIS Cut Line= 3
      1552070.59      6911190.13      1551914.34      6910677.95
      1551325.18      6909291.19
#Sta/Elev= 30
  4579.2 1651.38  4675.5 1650.99  4738.2 1649.59  4791.3 1647.82  4889.7 1646.55
  4927.8 1644.27  4936.9 1642.63  4955.4 1641.74  4986.7 1641.38  4987.2 1640.88
  4999.6 1640.88  5000.1 1641.38  5012.0 1641.60  5041.4 1642.25  5059.8 1643.21
  5064.3 1643.05  5128.3 1646.40  5199.3 1647.54  5266.7 1647.54  5288.5 1647.09
  5473.2 1646.09  5945.0 1647.48  6266.3 1646.92  6279.6 1647.23  6403.3 1647.50
  6418.4 1647.21  6472.8 1647.81  6537.9 1648.07  6579.7 1647.75  6621.4 1648.10
#Mann=5,-1,0
  4579.2   0.045       0  4986.7   0.045       0  5000.1   0.045       0
  5012.0    0.07       0  5059.8   0.045       0
Bank Sta=4986.7,5000.1
Exp/Cntr=0.3,0.1

Type RM Length L Ch R = 1,681,134,134,134
BEGIN DESCRIPTION:
Mapping XS bee2ae3e
END DESCRIPTION:
XS GIS Cut Line= 3
      1552231.18      6911187.89      1552222.50      6910623.70
      1551862.62      6909287.26
#Sta/Elev= 30
  4550.0 1650.21  4579.9 1650.26  4625.7 1649.43  4759.9 1648.10  4874.3 1645.04
  4929.9 1644.06  4949.9 1642.79  4993.2 1641.62  4993.7 1641.12  5006.1 1641.12
  5006.6 1641.62  5039.9 1642.01  5061.5 1642.93  5080.0 1644.54  5119.4 1646.34
  5182.3 1647.08  5285.9 1646.93  5314.0 1646.42  5461.9 1645.53  5513.7 1645.83
  5669.0 1645.56  5697.8 1646.04  5710.5 1645.66  5777.7 1646.09  5857.6 1645.84
  6047.0 1646.61  6373.3 1646.86  6383.6 1647.19  6414.7 1646.85  6498.3 1647.24
#Mann=5,-1,0
  4550.0   0.045       0  4874.3    0.07       0  4993.2    0.07       0
  5006.6    0.07       0  5061.5   0.045       0
Bank Sta=4993.2,5006.6
Exp/Cntr=0.3,0.1

Type RM Length L Ch R = 1,547,340,340,340
BEGIN DESCRIPTION:
Mapping XS 809a649c
END DESCRIPTION:
XS GIS Cut Line= 3
      1552344.03      6911148.84      1552361.39      6910651.91
      1552086.34      6909312.08
#Sta/Elev= 30
  4588.9 1649.89  4669.8 1648.86  4699.8 1648.79  4719.8 1648.16  4789.9 1647.09
  4859.9 1646.82  4887.9 1646.24  4929.9 1645.04  4950.0 1643.05  4983.3 1642.01
  4983.8 1641.51  4996.2 1641.51  4996.7 1642.01  5050.6 1643.17  5070.0 1643.61
  5085.6 1644.92  5094.1 1644.94  5120.7 1646.12  5194.9 1646.82  5284.1 1646.71
  5467.8 1645.54  5587.8 1645.59  5600.6 1645.85  5643.3 1645.45  5672.0 1645.76
  5682.2 1645.52  5917.0 1645.99  6136.9 1647.00  6151.8 1646.78  6453.9 1647.19
#Mann=5,-1,0
  4588.9   0.045       0  4887.9    0.07       0  4983.3    0.07       0
  4996.7    0.07       0  5050.6   0.045       0
Bank Sta=4983.3,4996.7
Exp/Cntr=0.3,0.1

Type RM Length L Ch R = 1,207,0,0,0
BEGIN DESCRIPTION:
NC Unknown Stream 90 1.0
END DESCRIPTION:
XS GIS Cut Line= 4
      1552543.23      6911036.04      1552695.15      6910827.26
      1552701.66      6910590.28      1552396.48      6909465.21
#Sta/Elev= 30
  4652.5 1648.40  4710.4 1647.42  4888.1 1646.43  4912.8 1645.77  4924.0 1644.86
  4930.0 1644.45  4940.0 1643.03  4960.0 1642.06  4973.3 1641.83  4973.8 1641.33
  4986.2 1641.33  4986.7 1641.83  4990.0 1642.14  5010.0 1642.10  5030.0 1642.91
  5040.0 1643.44  5060.0 1645.21  5080.0 1646.15  5116.4 1646.79  5194.5 1646.99
  5429.9 1645.12  5512.8 1644.93  5699.3 1645.22  5726.1 1645.70  5771.8 1645.43
  5999.8 1646.46  6020.5 1646.84  6134.5 1647.05  6143.4 1647.38  6313.5 1647.50
#Mann=5,-1,0
  4652.5   0.045       0  4924.0    0.07       0  4973.3    0.07       0
  4986.7    0.07       0  5116.4   0.045       0
Bank Sta=4973.3,4986.7
Exp/Cntr=0.3,0.1

Chan Stop Cuts=-1