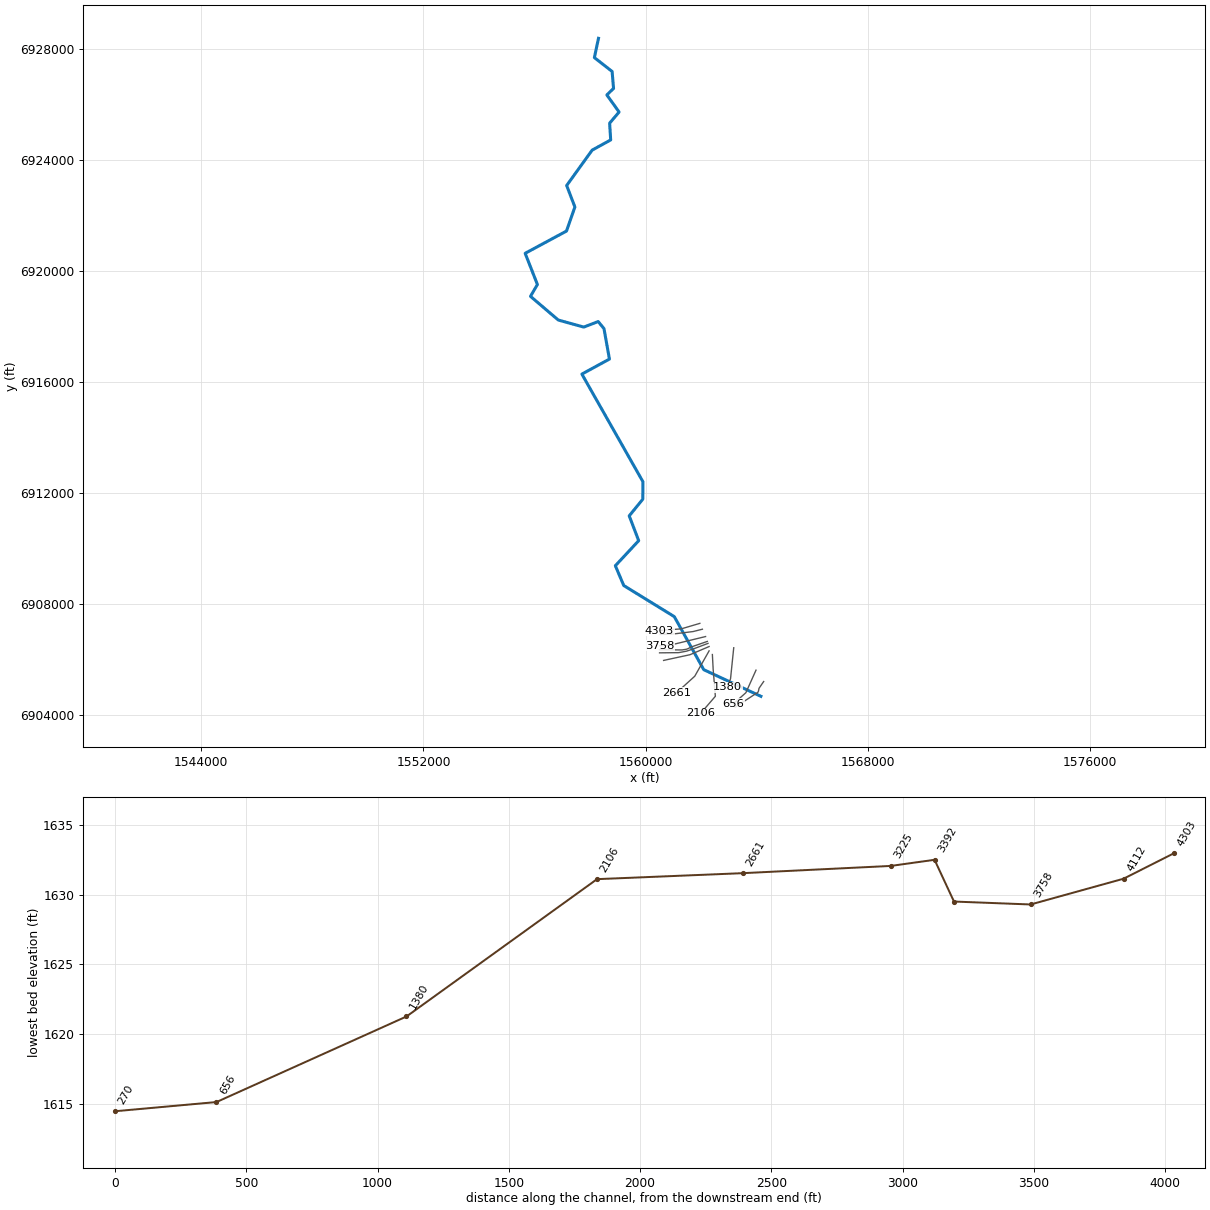
--- NC Unknown Stream 91.prj (project) ---

Proj Title=NC Unknown Stream 91 Base Level Engineering
Current Plan=p01
Default Exp/Contr=0.3,0.1
English Units
Geom File=g01
Flow File=f01
Plan File=p01
BEGIN DESCRIPTION:
NC Unknown Stream 91
END DESCRIPTION:

--- NC Unknown Stream 91.p01 (plan) ---

Plan Title=Multiple Run
Short Identifier=Multiple
Geom File=g01
Flow File=f01
Subcritical Flow
K Sum by GR= 0
Std Step Tol= 0.01
Critical Tol= 0.01
Num of Std Step Trials= 20
Max Error Tol= 0.3
Flow Tol Ratio= 0.001
Split Flow NTrial= 30
Split Flow Tol= 0.02
Split Flow Ratio= 0.02
Log Output Level= 0
Friction Slope Method= 1
Unsteady Friction Slope Method= 2
Unsteady Bridges Friction Slope Method= 1
Parabolic Critical Depth
Global Vel Dist=  1 , 1 , 1
Global Log Level= 0
CheckData=True
Encroach Param= -1, 0, 0, 0
BEGIN DESCRIPTION:
Multiple Run
END DESCRIPTION:

--- NC Unknown Stream 91.f01 (steady flow) ---

Flow Title=Multiple
Number of Profiles=7
Profile Names=10-year,25-year,50-year,1pct_min,100-year,1pct_plu,500-year
River Rch & RM= NC Unknown Strea,Reach-1,4303
     449     627     775     475     949    1893    1440
River Rch & RM= NC Unknown Strea,Reach-1,1380
     447     625     772     473     943    1882    1430
Boundary for River Rch & Prof#=NC Unknown Strea,Reach-1,1
Up Type=0
Dn Type=3
Dn Slope=0.001
Boundary for River Rch & Prof#=NC Unknown Strea,Reach-1,2
Up Type=0
Dn Type=3
Dn Slope=0.001
Boundary for River Rch & Prof#=NC Unknown Strea,Reach-1,3
Up Type=0
Dn Type=3
Dn Slope=0.001
Boundary for River Rch & Prof#=NC Unknown Strea,Reach-1,4
Up Type=0
Dn Type=3
Dn Slope=0.001
Boundary for River Rch & Prof#=NC Unknown Strea,Reach-1,5
Up Type=0
Dn Type=3
Dn Slope=0.001
Boundary for River Rch & Prof#=NC Unknown Strea,Reach-1,6
Up Type=0
Dn Type=3
Dn Slope=0.001
Boundary for River Rch & Prof#=NC Unknown Strea,Reach-1,7
Up Type=0
Dn Type=3
Dn Slope=0.001

--- NC Unknown Stream 91.g01 (geometry) ---

Geom Title=Existing Conditions

River Reach=NC Unknown Strea,Reach-1
Reach XY= 30
      1558305.00      6928388.00      1558156.80      6927694.11
      1558796.04      6927194.68      1558847.52      6926584.42
      1558605.72      6926348.71      1559047.41      6925734.67
      1558706.61      6925331.98      1558744.05      6924728.00
      1558077.72      6924362.15      1557158.51      6923086.75
      1557455.50      6922312.97      1557152.08      6921445.92
      1555663.88      6920644.53      1556104.97      6919522.58
      1555856.59      6919094.05      1556856.55      6918241.75
      1557775.16      6917987.53      1558294.52      6918187.07
      1558502.75      6917932.07      1558699.31      6916835.43
      1557706.78      6916294.09      1559905.29      6912417.83
      1559901.54      6911789.50      1559412.02      6911187.79
      1559753.20      6910294.11      1558912.61      6909391.33
      1559216.11      6908677.68      1561035.60      6907558.65
      1562095.21      6905648.52      1564155.00      6904688.00

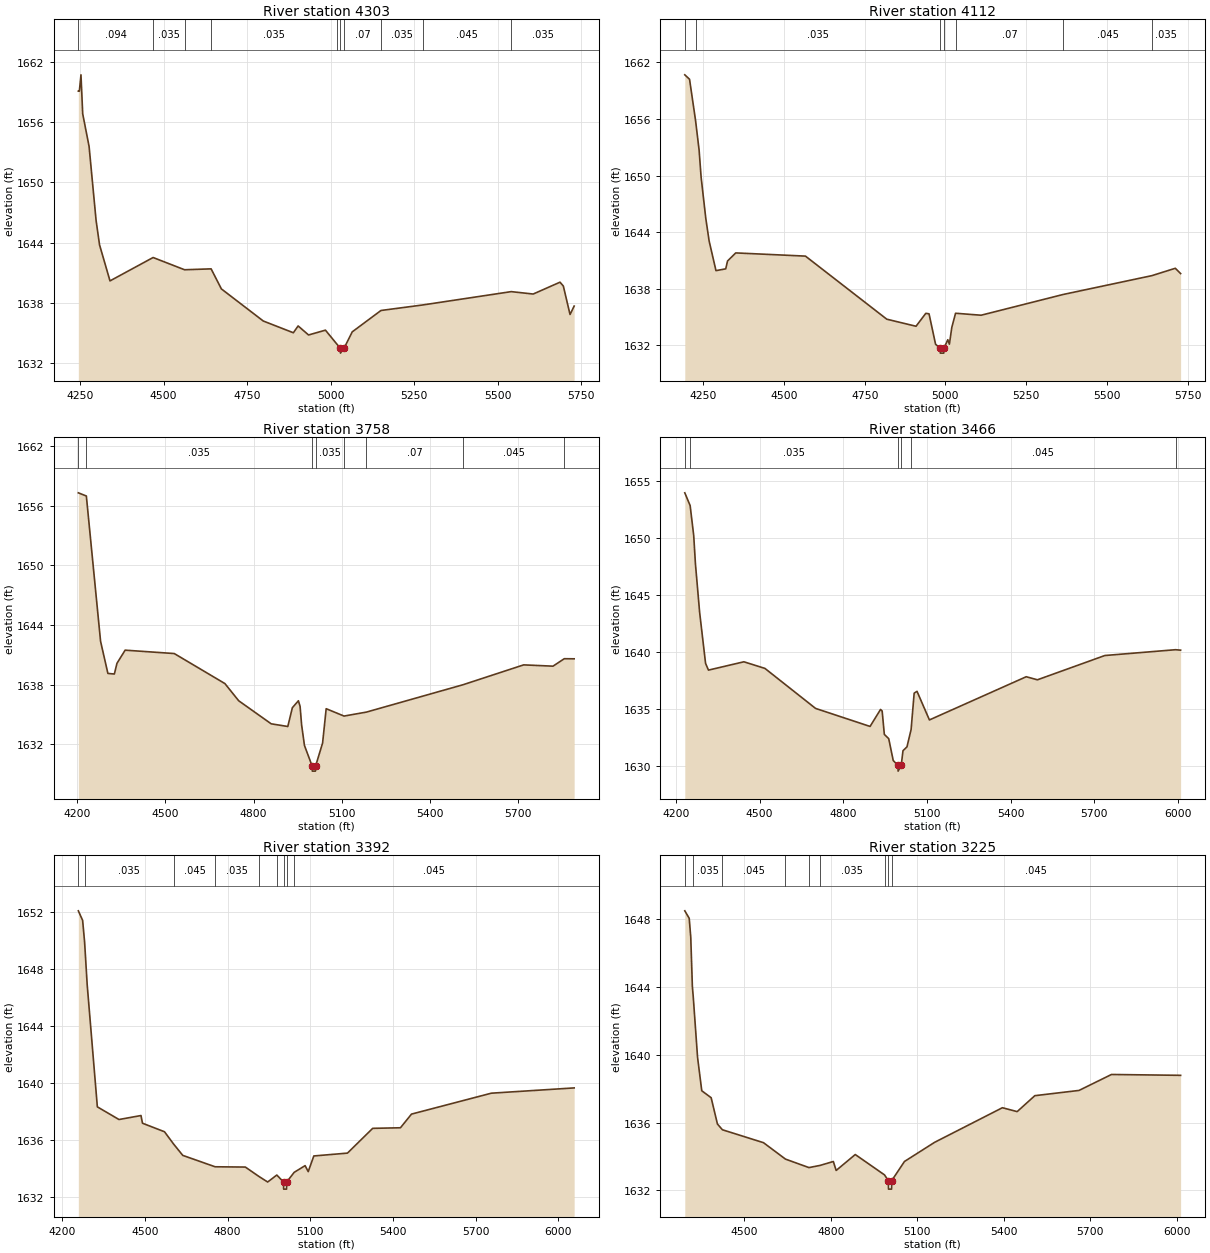
Type RM Length L Ch R = 1,4303,191,191,191
BEGIN DESCRIPTION:
NC Unknown Stream 91 7.0
END DESCRIPTION:
XS GIS Cut Line= 3
      1561955.88      6907315.72      1561285.74      6907117.80
      1560502.72      6907058.77
#Sta/Elev= 30
  4244.9 1659.09  4248.0 1659.09  4252.8 1660.72  4258.0 1656.83  4277.1 1653.58
  4298.0 1646.22  4308.4 1643.77  4339.7 1640.18  4468.7 1642.51  4562.9 1641.29
  4642.3 1641.38  4673.1 1639.38  4798.5 1636.18  4888.5 1635.01  4902.7 1635.69
  4934.0 1634.79  4984.5 1635.27  5019.9 1633.83  5029.0 1633.48  5029.5 1632.98
  5040.4 1633.48  5064.7 1635.10  5150.7 1637.23  5275.6 1637.78  5540.5 1639.11
  5606.3 1638.87  5686.5 1640.05  5696.5 1639.67  5716.6 1636.83  5728.9 1637.67
#Mann=10,-1,0
  4244.9   0.094       0  4468.7   0.035       0  4562.9   0.094       0
  4642.3   0.035       0  5019.9    0.07       0  5029.0   0.035       0
  5040.4    0.07       0  5150.7   0.035       0  5275.6   0.045       0
  5540.5   0.035       0
Bank Sta=5029,5040.4
Exp/Cntr=0.3,0.1

Type RM Length L Ch R = 1,4112,354,354,354
BEGIN DESCRIPTION:
Mapping XS cf0f0af1
END DESCRIPTION:
XS GIS Cut Line= 4
      1562047.94      6907105.66      1561712.82      6907020.58
      1560936.78      6906925.10      1560528.51      6906916.45
#Sta/Elev= 30
  4192.7 1660.68  4207.4 1660.21  4225.9 1655.87  4237.0 1652.70  4243.2 1649.84
  4257.6 1645.49  4268.0 1643.07  4289.3 1639.91  4319.5 1640.10  4325.1 1640.93
  4350.5 1641.79  4566.5 1641.45  4818.4 1634.76  4909.0 1634.01  4939.3 1635.38
  4949.3 1635.33  4969.5 1632.11  4983.9 1631.66  4984.4 1631.16  4994.9 1631.16
  4995.4 1631.66  5007.4 1632.58  5012.4 1632.11  5019.9 1633.90  5031.5 1635.39
  5110.6 1635.18  5364.7 1637.38  5639.8 1639.38  5712.2 1640.16  5728.7 1639.60
#Mann=7,-1,0
  4192.7   0.094       0  4225.9   0.035       0  4983.9   0.035       0
  4995.4   0.035       0  5031.5    0.07       0  5364.7   0.045       0
  5639.8   0.035       0
Bank Sta=4983.9,4995.4
Exp/Cntr=0.3,0.1

Type RM Length L Ch R = 1,3758,292,292,292
BEGIN DESCRIPTION:
Mapping XS 36357ea6
END DESCRIPTION:
XS GIS Cut Line= 3
      1562162.78      6906841.04      1560874.57      6906528.54
      1560513.45      6906509.44
#Sta/Elev= 30
  4203.8 1657.31  4231.1 1656.99  4279.5 1642.37  4304.4 1639.14  4326.4 1639.08
  4335.3 1640.16  4363.1 1641.48  4530.2 1641.14  4702.5 1638.12  4749.5 1636.39
  4860.1 1634.07  4916.6 1633.80  4932.1 1635.69  4952.7 1636.39  4958.4 1635.82
  4963.6 1633.96  4973.3 1631.89  4999.6 1629.81  5000.1 1629.31  5010.6 1629.31
  5011.1 1629.81  5035.0 1632.14  5047.2 1635.59  5107.9 1634.85  5184.2 1635.25
  5512.7 1638.00  5719.2 1640.00  5819.0 1639.87  5857.4 1640.62  5891.0 1640.61
#Mann=8,-1,0
  4203.8   0.094       0  4231.1   0.035       0  4999.6   0.035       0
  5011.1   0.035       0  5107.9   0.045       0  5184.2    0.07       0
  5512.7   0.045       0  5857.4    0.07       0
Bank Sta=4999.6,5011.1
Exp/Cntr=0.3,0.1

Type RM Length L Ch R = 1,3466,74,74,74
BEGIN DESCRIPTION:
Mapping XS 83610f86
END DESCRIPTION:
XS GIS Cut Line= 6
      1562225.26      6906665.69      1561628.04      6906459.10
      1561541.24      6906410.48      1561480.47      6906386.18
      1561315.54      6906358.40      1560501.31      6906365.35
#Sta/Elev= 30
  4231.6 1653.93  4250.8 1652.81  4263.6 1650.18  4269.7 1647.72  4284.8 1643.45
  4306.1 1638.97  4316.5 1638.38  4443.5 1639.11  4519.0 1638.53  4700.7 1635.02
  4896.1 1633.44  4933.7 1634.93  4939.5 1634.79  4947.3 1632.74  4963.0 1632.37
  4979.2 1630.45  4996.3 1630.02  4996.8 1629.52  5007.8 1630.02  5014.2 1631.31
  5028.5 1631.65  5043.3 1633.17  5054.3 1636.36  5064.5 1636.52  5109.0 1634.01
  5456.3 1637.80  5496.3 1637.53  5738.2 1639.66  5991.9 1640.17  6010.0 1640.13
#Mann=6,-1,0
  4231.6   0.094       0  4250.8   0.035       0  4996.3   0.035       0
  5007.8   0.035       0  5043.3   0.045       0  5991.9    0.07       0
Bank Sta=4996.3,5007.8
Exp/Cntr=0.3,0.1

Type RM Length L Ch R = 1,3392,167,167,167
BEGIN DESCRIPTION:
Mapping XS 2ba06fe0
END DESCRIPTION:
XS GIS Cut Line= 5
      1562249.60      6906594.52      1561725.27      6906396.60
      1561471.79      6906313.26      1561194.02      6906261.18
      1560504.73      6906254.23
#Sta/Elev= 30
  4258.2 1652.07  4273.8 1651.40  4281.0 1649.87  4290.3 1646.89  4327.2 1638.30
  4405.7 1637.41  4485.6 1637.69  4491.0 1637.15  4570.9 1636.55  4605.0 1635.66
  4637.2 1634.89  4754.6 1634.09  4864.2 1634.07  4913.6 1633.41  4945.2 1633.02
  4978.5 1633.51  5002.7 1633.02  5003.2 1632.52  5013.7 1632.52  5014.2 1633.02
  5041.5 1633.70  5081.1 1634.17  5092.4 1633.75  5112.7 1634.85  5234.8 1635.05
  5326.4 1636.79  5427.1 1636.83  5467.1 1637.79  5757.1 1639.26  6057.4 1639.63
#Mann=9,-1,0
  4258.2   0.094       0  4281.0   0.035       0  4605.0   0.045       0
  4754.6   0.035       0  4913.6   0.045       0  4978.5   0.035       0
  5002.7   0.035       0  5014.2   0.035       0  5041.5   0.045       0
Bank Sta=5002.7,5014.2
Exp/Cntr=0.3,0.1

Type RM Length L Ch R = 1,3225,564,564,564
BEGIN DESCRIPTION:
Mapping XS 93894266
END DESCRIPTION:
XS GIS Cut Line= 3
      1562289.18      6906481.07      1561598.24      6906185.95
      1560650.36      6905981.09
#Sta/Elev= 30
  4293.0 1648.49  4308.3 1648.05  4313.7 1646.94  4319.3 1644.02  4322.4 1643.41
  4337.3 1639.85  4351.9 1637.88  4384.5 1637.47  4406.3 1635.92  4423.6 1635.58
  4566.0 1634.82  4642.5 1633.85  4724.0 1633.35  4763.0 1633.48  4808.6 1633.71
  4818.4 1633.18  4884.7 1634.12  4986.2 1632.92  4999.6 1632.58  5000.1 1632.08
  5010.7 1632.08  5011.2 1632.58  5055.5 1633.71  5160.2 1634.84  5395.5 1636.88
  5446.7 1636.65  5508.0 1637.59  5661.5 1637.90  5774.0 1638.84  6014.1 1638.79
#Mann=9,-1,0
  4293.0   0.094       0  4322.4   0.035       0  4423.6   0.045       0
  4642.5   0.035       0  4724.0   0.045       0  4763.0   0.035       0
  4986.2   0.045       0  4999.6   0.045       0  5011.2   0.045       0
Bank Sta=4999.6,5011.2
Exp/Cntr=0.3,0.1

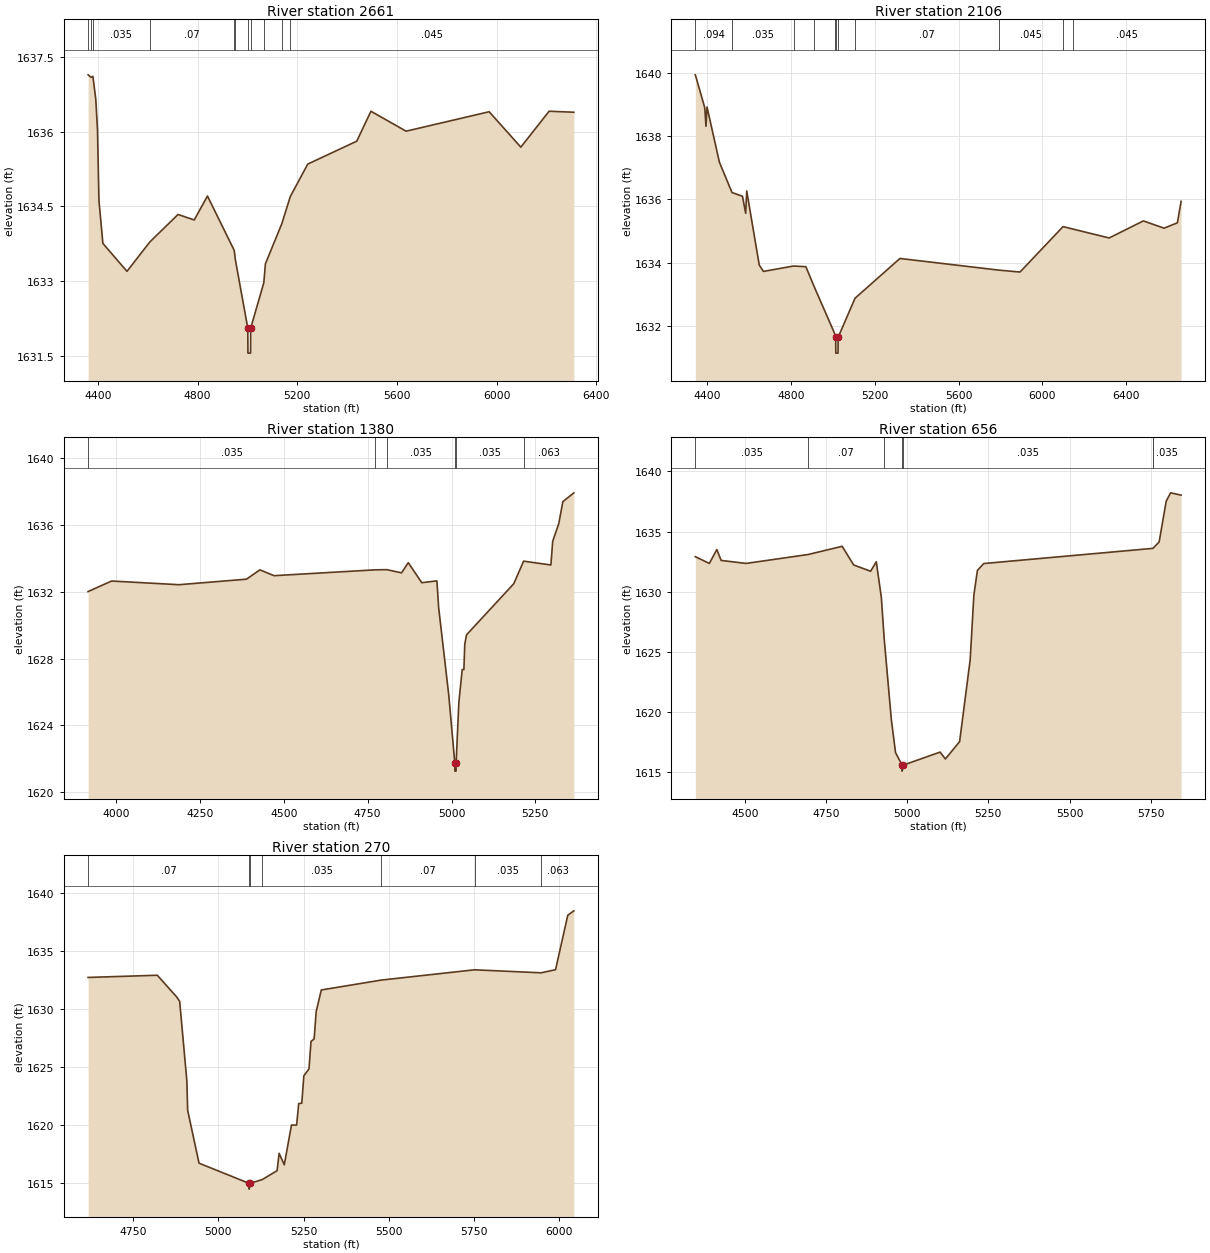
Type RM Length L Ch R = 1,2661,555,555,555
BEGIN DESCRIPTION:
Mapping XS 0c363f44
END DESCRIPTION:
XS GIS Cut Line= 3
      1562289.23      6906324.86      1561771.85      6905411.64
      1561105.18      6904807.47
#Sta/Elev= 30
  4360.9 1637.14  4373.2 1637.09  4380.3 1637.11  4391.8 1636.65  4398.7 1636.04
  4404.5 1634.62  4420.3 1633.76  4517.0 1633.20  4608.9 1633.79  4721.9 1634.34
  4786.8 1634.23  4840.0 1634.71  4947.3 1633.62  4951.7 1633.44  5001.8 1632.06
  5002.3 1631.56  5012.9 1631.56  5013.4 1632.06  5066.0 1632.97  5072.5 1633.35
  5138.7 1634.16  5172.4 1634.70  5242.3 1635.35  5439.1 1635.81  5495.9 1636.41
  5637.1 1636.01  5970.3 1636.40  6097.4 1635.69  6210.9 1636.41  6310.2 1636.39
#Mann=11,-1,0
  4360.9   0.094       0  4373.2   0.045       0  4380.3   0.035       0
  4608.9    0.07       0  4947.3   0.045       0  4951.7    0.07       0
  5001.8    0.07       0  5013.4    0.07       0  5066.0   0.045       0
  5138.7    0.07       0  5172.4   0.045       0
Bank Sta=5001.8,5013.4
Exp/Cntr=0.3,0.1

Type RM Length L Ch R = 1,2106,726,726,726
BEGIN DESCRIPTION:
NC Unknown Stream 91 6.0
END DESCRIPTION:
XS GIS Cut Line= 4
      1562407.27      6906192.88      1562435.05      6905668.59
      1562514.91      6904689.42      1561984.73      6904073.67
#Sta/Elev= 30
  4342.5 1639.95  4387.4 1638.91  4393.3 1638.32  4398.3 1638.93  4457.5 1637.18
  4517.6 1636.22  4567.7 1636.10  4582.9 1635.56  4587.9 1636.27  4647.8 1633.92
  4667.8 1633.72  4811.3 1633.89  4870.3 1633.87  4909.2 1633.25  5007.2 1631.76
  5012.8 1631.63  5013.3 1631.13  5023.9 1631.13  5024.4 1631.63  5105.2 1632.87
  5319.6 1634.13  5792.4 1633.76  5893.1 1633.70  6098.6 1635.14  6146.6 1635.06
  6318.8 1634.78  6482.2 1635.32  6581.0 1635.09  6644.6 1635.26  6662.5 1635.94
#Mann=11,-1,0
  4342.5   0.094       0  4517.6   0.035       0  4811.3   0.045       0
  4909.2    0.07       0  5007.2   0.045       0  5012.8    0.07       0
  5024.4   0.045       0  5105.2    0.07       0  5792.4   0.045       0
  6098.6    0.07       0  6146.6   0.045       0
Bank Sta=5012.8,5024.4
Exp/Cntr=0.3,0.1

Type RM Length L Ch R = 1,1380,724,724,724
BEGIN DESCRIPTION:
NC Unknown Stream 91 5.0
END DESCRIPTION:
XS GIS Cut Line= 3
      1563176.37      6906437.69      1563061.78      6905323.10
      1562947.21      6905015.83
#Sta/Elev= 30
  3916.4 1632.01  3986.5 1632.64  4187.5 1632.42  4388.6 1632.75  4428.8 1633.31
  4470.8 1632.96  4772.6 1633.31  4807.2 1633.32  4851.0 1633.13  4871.1 1633.74
  4911.3 1632.54  4956.5 1632.65  4961.6 1631.06  4991.7 1625.83  5009.8 1621.76
  5010.1 1621.26  5013.6 1621.26  5013.8 1621.76  5021.9 1625.38  5031.9 1627.34
  5036.9 1627.34  5039.5 1628.85  5044.8 1629.42  5185.7 1632.48  5215.0 1633.83
  5296.3 1633.60  5301.7 1635.02  5319.8 1636.08  5332.0 1637.39  5364.8 1637.92
#Mann=6,-1,0
  3916.4   0.035       0  4772.6    0.07       0  4807.2   0.035       0
  5009.8   0.035       0  5013.8   0.035       0  5215.0   0.063       0
Bank Sta=5009.8,5013.8
Exp/Cntr=0.3,0.1

Type RM Length L Ch R = 1,656,386,386,386
BEGIN DESCRIPTION:
NC Unknown Stream 91 4.0
END DESCRIPTION:
XS GIS Cut Line= 3
      1563978.46      6905630.42      1563613.87      6904817.89
      1563160.73      6904416.84
#Sta/Elev= 30
  4347.9 1632.91  4391.0 1632.35  4414.1 1633.50  4427.3 1632.60  4504.0 1632.35
  4695.2 1633.09  4799.9 1633.77  4835.5 1632.22  4887.6 1631.70  4905.0 1632.49
  4920.5 1629.55  4929.3 1626.11  4951.4 1619.38  4964.3 1616.65  4984.3 1615.61
  4984.5 1615.11  4988.3 1615.61  5101.4 1616.69  5117.8 1616.12  5161.6 1617.56
  5194.1 1624.35  5205.5 1629.73  5216.4 1631.77  5235.7 1632.34  5756.6 1633.60
  5757.4 1633.62  5775.9 1634.13  5797.6 1637.51  5811.2 1638.21  5843.6 1638.02
#Mann=7,-1,0
  4347.9   0.035       0  4695.2    0.07       0  4929.3   0.035       0
  4984.3   0.035       0  4988.3   0.035       0  5756.6   0.063       0
  5757.4   0.035       0
Bank Sta=4984.3,4988.3
Exp/Cntr=0.3,0.1

Type RM Length L Ch R = 1,270,0,0,0
BEGIN DESCRIPTION:
NC Unknown Stream 91 1.0
END DESCRIPTION:
XS GIS Cut Line= 6
      1564254.80      6905220.55      1564088.16      6904979.05
      1564066.02      6904870.97      1564037.81      6904821.28
      1563963.16      6904778.53      1563230.09      6904298.06
#Sta/Elev= 30
  4618.7 1632.72  4821.5 1632.91  4878.3 1631.04  4887.1 1630.65  4908.1 1623.81
  4910.5 1621.25  4943.8 1616.69  5090.4 1614.95  5090.7 1614.45  5094.4 1614.95
  5129.3 1615.28  5172.5 1616.04  5178.5 1617.54  5193.6 1616.55  5214.7 1619.98
  5229.8 1619.98  5235.8 1621.83  5244.9 1621.87  5250.9 1624.23  5266.0 1624.83
  5271.9 1627.20  5281.1 1627.41  5287.0 1629.77  5302.1 1631.64  5477.2 1632.49
  5751.2 1633.38  5946.3 1633.12  5988.4 1633.39  6024.3 1638.09  6042.1 1638.47
#Mann=7,-1,0
  4618.7    0.07       0  5090.4    0.07       0  5094.4    0.07       0
  5129.3   0.035       0  5477.2    0.07       0  5751.2   0.035       0
  5946.3   0.063       0
Bank Sta=5090.4,5094.4
Exp/Cntr=0.3,0.1

Chan Stop Cuts=-1