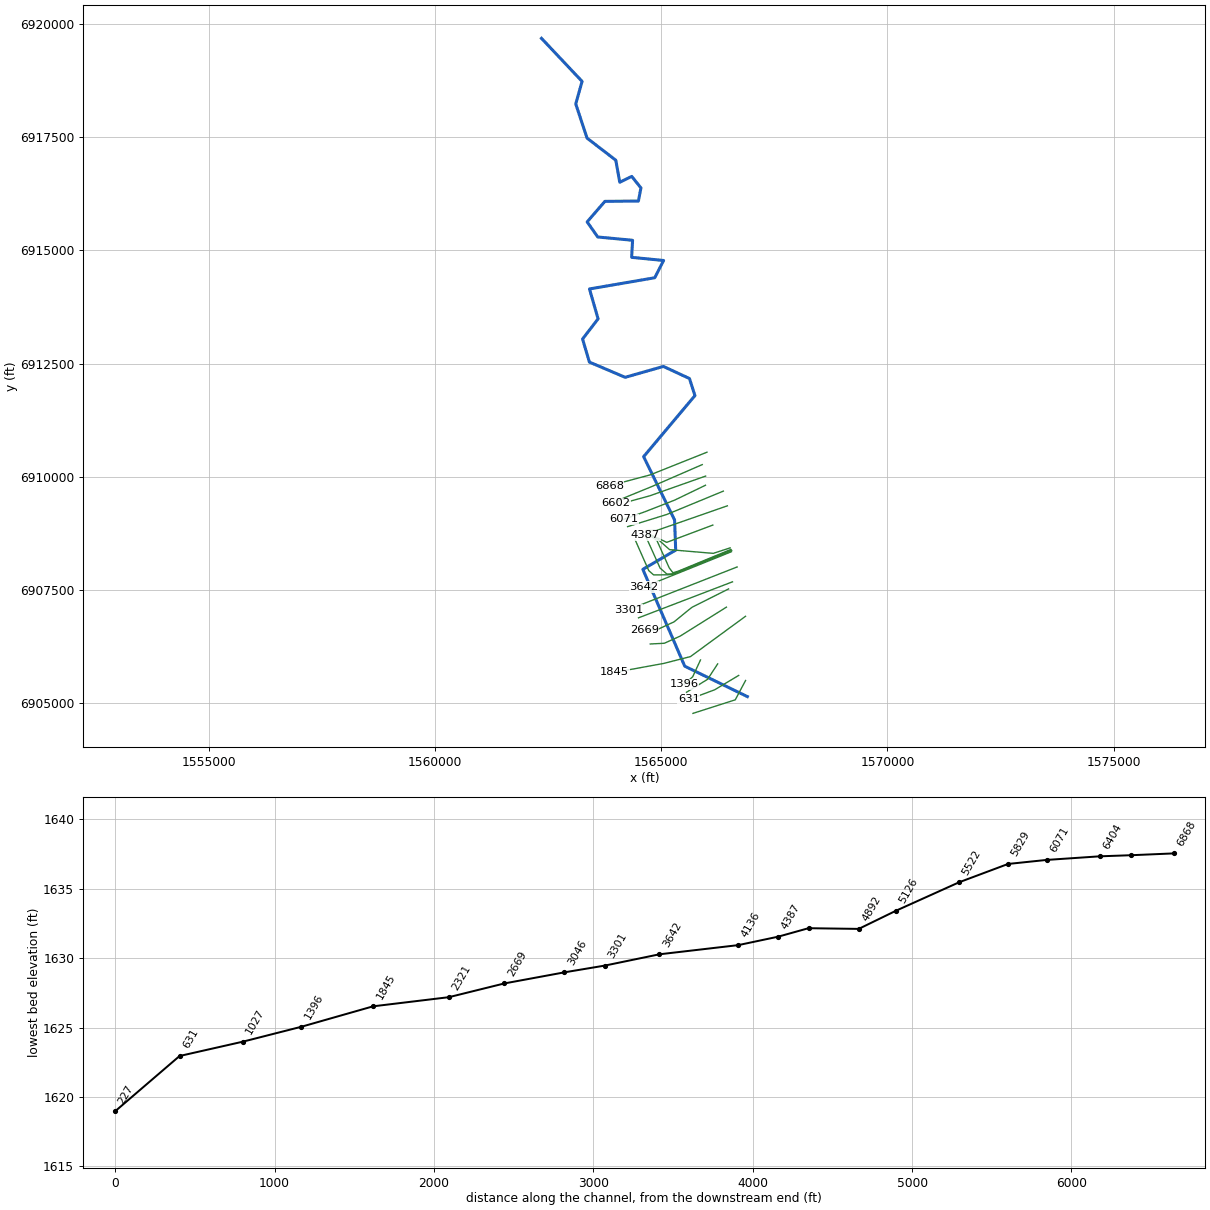
--- NC Unknown Stream 92.prj (project) ---

Proj Title=NC Unknown Stream 92 Base Level Engineering
Current Plan=p01
Default Exp/Contr=0.3,0.1
English Units
Geom File=g01
Flow File=f01
Plan File=p01
Y Axis Title=Elevation
X Axis Title(PF)=Main Channel Distance
X Axis Title(XS)=Station
BEGIN DESCRIPTION:
NC Unknown Stream 92
END DESCRIPTION:
DSS Export Rating Curves= 0
DSS Export Rating Curve Sorted= 0
DSS Export Volume Flow Curves= 0
DXF OffsetX= 0
DXF OffsetY= 0
DXF ScaleX= 1
DXF ScaleY= 10

--- NC Unknown Stream 92.p01 (plan) ---

Plan Title=Multiple Run
Short Identifier=Multiple
Geom File=g01
Flow File=f01
Subcritical Flow
K Sum by GR= 0
Std Step Tol= 0.01
Critical Tol= 0.01
Num of Std Step Trials= 20
Max Error Tol= 0.3
Flow Tol Ratio= 0.001
Split Flow NTrial= 30
Split Flow Tol= 0.02
Split Flow Ratio= 0.02
Log Output Level= 0
Friction Slope Method= 1
Unsteady Friction Slope Method= 2
Unsteady Bridges Friction Slope Method= 1
Parabolic Critical Depth
Global Vel Dist=  1 , 1 , 1
Global Log Level= 0
CheckData=True
Encroach Param= -1, 0, 0, 0
BEGIN DESCRIPTION:
Multiple Run
END DESCRIPTION:

--- NC Unknown Stream 92.f01 (steady flow) ---

Flow Title=Multiple
Number of Profiles=7
Profile Names=10-year,25-year,50-year,1pct_min,100-year,1pct_plu,500-year
River Rch & RM= NC Unknown Strea,Reach-1,6868
     357     494     605     368     735    1467    1100
River Rch & RM= NC Unknown Strea,Reach-1,4136
     407     567     699     427     853    1701    1287
River Rch & RM= NC Unknown Strea,Reach-1,1845
     414     577     712     436     869    1735    1315
Boundary for River Rch & Prof#=NC Unknown Strea,Reach-1,1
Up Type=0
Dn Type=3
Dn Slope=0.001
Boundary for River Rch & Prof#=NC Unknown Strea,Reach-1,2
Up Type=0
Dn Type=3
Dn Slope=0.001
Boundary for River Rch & Prof#=NC Unknown Strea,Reach-1,3
Up Type=0
Dn Type=3
Dn Slope=0.001
Boundary for River Rch & Prof#=NC Unknown Strea,Reach-1,4
Up Type=0
Dn Type=3
Dn Slope=0.001
Boundary for River Rch & Prof#=NC Unknown Strea,Reach-1,5
Up Type=0
Dn Type=3
Dn Slope=0.001
Boundary for River Rch & Prof#=NC Unknown Strea,Reach-1,6
Up Type=0
Dn Type=3
Dn Slope=0.001
Boundary for River Rch & Prof#=NC Unknown Strea,Reach-1,7
Up Type=0
Dn Type=3
Dn Slope=0.001

--- NC Unknown Stream 92.g01 (geometry) ---

Geom Title=Existing Conditions
Program Version=4.10

River Reach=NC Unknown Strea,Reach-1
Reach XY= 30
        1562355.        6919688.      1563251.96      6918736.58
       1563112.2       6918237.7      1563362.48      6917481.94
      1563997.51      6916994.07      1564084.96      6916507.19
      1564349.56      6916636.35      1564552.95      6916382.14
      1564496.85      6916091.38      1563756.73      6916084.69
      1563363.84      6915631.05      1563598.25       6915297.1
      1564368.37      6915224.37      1564347.95      6914847.17
      1565054.13      6914777.67      1564858.23      6914396.23
      1563415.78      6914148.43      1563605.85      6913488.01
      1563262.76      6913041.38      1563414.15      6912531.27
       1564204.7       6912195.2      1565049.14      6912435.94
      1565625.59      6912168.79      1565746.92       6911791.3
      1564612.58      6910441.32      1565296.96      6909041.32
      1565321.36      6908376.22      1564595.51        6907951.
      1565521.21      6905810.11        1566905.        6905138.

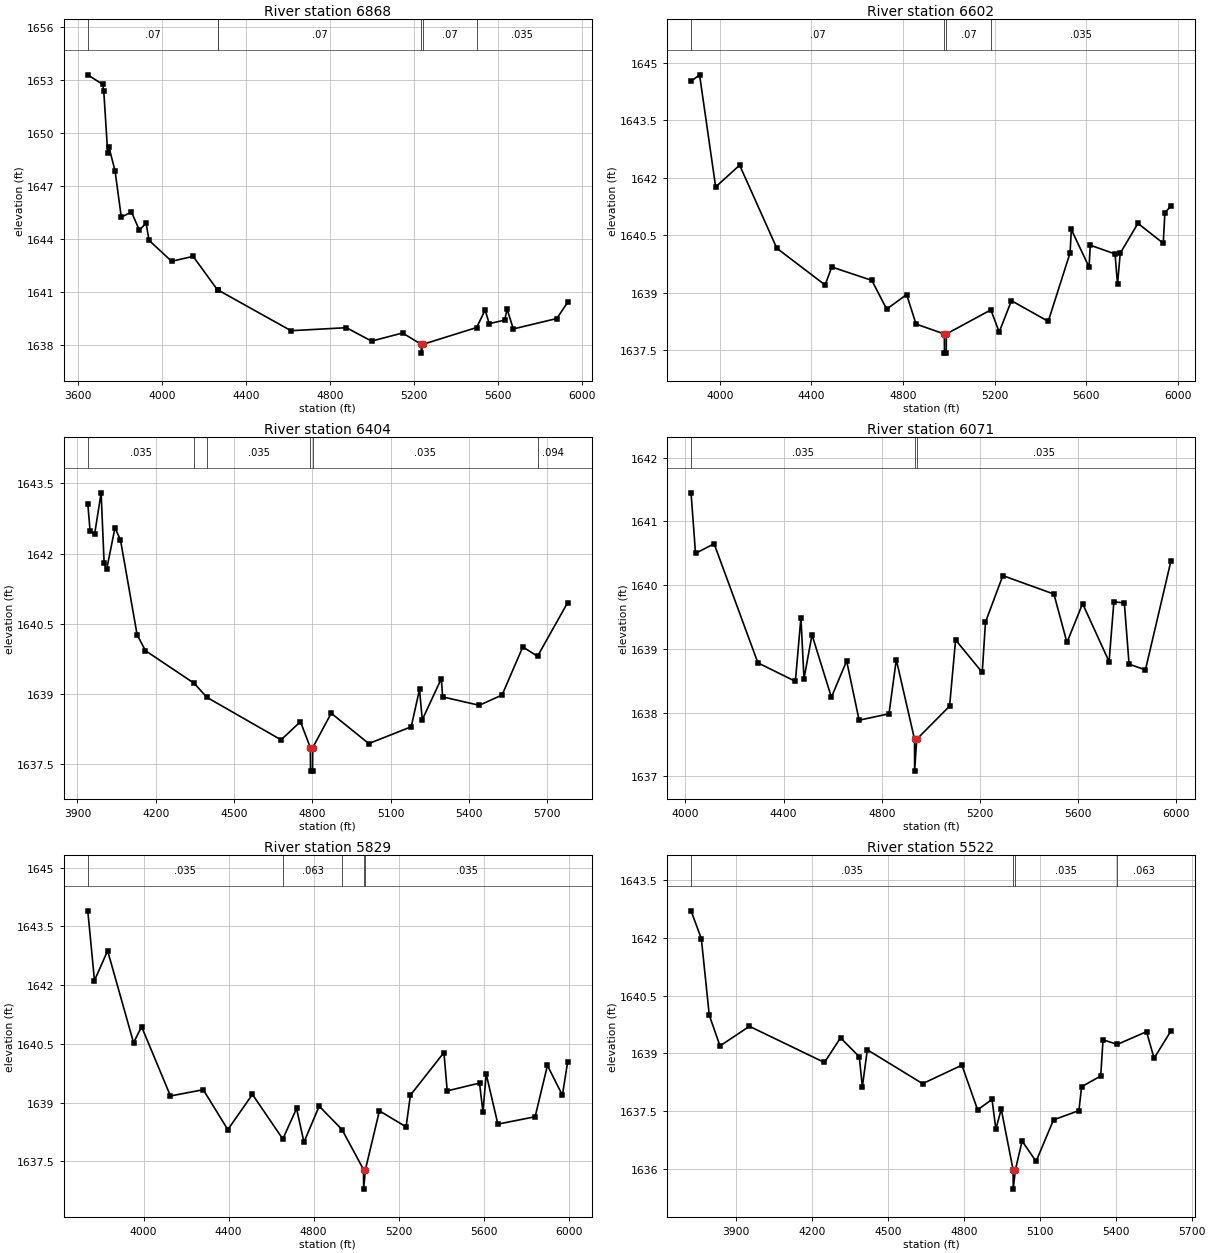
Type RM Length L Ch R = 1 ,6868    ,266,266,266
BEGIN DESCRIPTION:
NC Unknown Stream 92 8.0
END DESCRIPTION:
XS GIS Cut Line= 3
      1566013.14      6910540.19        1564755.        6910038.
      1563854.92      6909797.57
#Sta/Elev= 30
  3645.6 1653.31  3716.3 1652.77  3721.6 1652.41  3740.5 1648.88  3745.9 1649.24
  3775.5 1647.87  3805.2 1645.25  3853.7 1645.54  3891.2 1644.52  3923.5 1644.91
  3937.2 1643.94    4045 1642.75  4147.4 1643.03  4264.3 1641.12  4268.3 1641.11
  4613.6 1638.82  4877.7 1638.99  4997.6 1638.23  5145.2 1638.69  5234.2 1638.05
  5234.7 1637.55  5242.5 1638.05  5498.2    1639  5538.5 1639.99  5558.1 1639.22
  5631.6 1639.42  5643.4 1640.03    5673 1638.92  5880.1 1639.51  5931.9 1640.43
#Mann= 6 ,-1 , 0
  3645.6     .07       0  4264.3    .035       0  4268.3     .07       0
  5234.2     .07       0  5242.5     .07       0  5498.2    .035       0
Bank Sta=5234.2,5242.5
XS Rating Curve= 0 ,0
Exp/Cntr=0.3,0.1

Type RM Length L Ch R = 1 ,6602    ,198,198,198
BEGIN DESCRIPTION:
Mapping XS aef397ee
END DESCRIPTION:
XS GIS Cut Line= 4
      1565908.53      6910265.88       1564790.5      6909779.78
      1564070.01      6909484.64      1564002.28      6909413.44
#Sta/Elev= 30
  3874.1 1644.52  3911.3 1644.69  3981.6 1641.76  4086.3 1642.33  4248.7 1640.16
  4459.7  1639.2  4488.6 1639.67  4663.7 1639.32  4728.5 1638.57  4815.7 1638.95
  4856.7 1638.18  4980.4 1637.92  4980.9 1637.42  4988.7 1637.42  4989.2 1637.92
  5183.5 1638.55    5220 1637.97  5273.4 1638.79  5434.2 1638.25  5529.6 1640.04
    5535 1640.65  5612.4 1639.67  5617.9 1640.24    5726 1640.01  5736.8 1639.22
  5748.6 1640.03    5826 1640.81  5936.5 1640.29  5943.7 1641.09  5970.1 1641.26
#Mann= 4 ,-1 , 0
  3874.1     .07       0  4980.4     .07       0  4989.2     .07       0
  5183.5    .035       0
Bank Sta=4980.4,4989.2
XS Rating Curve= 0 ,0
Exp/Cntr=0.3,0.1

Type RM Length L Ch R = 1 ,6404    ,333,333,333
BEGIN DESCRIPTION:
Mapping XS d945bb34
END DESCRIPTION:
XS GIS Cut Line= 3
      1565983.17      6910012.41      1564750.57      6909576.66
      1564238.35      6909436.49
#Sta/Elev= 30
  3939.8 1643.07  3948.5 1642.49  3966.2 1642.42  3990.9  1643.3  4002.4 1641.79
  4012.1 1641.66  4043.9 1642.55  4065.1 1642.29  4128.8 1640.26  4160.6 1639.92
  4347.5 1639.22  4396.1 1638.92  4680.3 1638.01  4754.6  1638.4  4792.5 1637.84
    4793 1637.34  4800.9 1637.34  4801.4 1637.84  4872.3 1638.58  5016.3 1637.93
  5178.8 1638.29  5210.6 1639.09  5221.2 1638.44  5294.1 1639.32  5299.2 1638.93
  5439.5 1638.75  5526.9 1638.97  5606.3    1640  5662.7  1639.8  5778.2 1640.95
#Mann= 6 ,-1 , 0
  3939.8    .035       0  4347.5     .07       0  4396.1    .035       0
  4792.5    .035       0  4801.4    .035       0  5662.7    .094       0
Bank Sta=4792.5,4801.4
XS Rating Curve= 0 ,0
Exp/Cntr=0.3,0.1

Type RM Length L Ch R = 1 ,6071    ,242,242,242
BEGIN DESCRIPTION:
Mapping XS 4df22cd2
END DESCRIPTION:
XS GIS Cut Line= 4
      1565979.73       6909809.3      1565299.18      6909481.17
      1564637.72      6909222.49       1564176.2      6909056.28
#Sta/Elev= 30
  4022.8 1641.45    4041  1640.5  4116.9 1640.65  4295.3 1638.78  4448.1 1638.49
  4470.7 1639.49  4483.2 1638.53  4515.9 1639.22  4594.9 1638.24  4657.1 1638.81
  4707.9 1637.88  4829.7 1637.98  4859.5 1638.83  4933.8 1637.58  4934.3 1637.08
  4942.7 1637.58  5076.7  1638.1  5101.2 1639.14  5209.8 1638.63  5223.1 1639.42
  5293.9 1640.15  5502.1 1639.86  5555.2  1639.1    5619 1639.71  5726.9  1638.8
  5746.5 1639.74  5789.1 1639.72  5808.4 1638.76  5875.1 1638.67  5979.1 1640.38
#Mann= 3 ,-1 , 0
  4022.8    .035       0  4933.8    .035       0  4942.7    .035       0
Bank Sta=4933.8,4942.7
XS Rating Curve= 0 ,0
Exp/Cntr=0.3,0.1

Type RM Length L Ch R = 1 ,5829    ,307,307,307
BEGIN DESCRIPTION:
Mapping XS 234f21e6
END DESCRIPTION:
XS GIS Cut Line= 3
      1566374.14      6909679.56      1565123.83      6909163.46
      1564258.83      6908894.78
#Sta/Elev= 30
  3737.2  1643.9  3768.7 1642.12  3830.6 1642.88  3952.6 1640.53  3990.4 1640.94
  4126.2 1639.17  4280.6 1639.33  4396.2 1638.31  4512.1 1639.21    4655 1638.07
  4719.7 1638.85  4754.5 1637.99  4826.2 1638.91  4933.9 1638.31  5034.8 1637.29
  5035.3 1636.79  5043.8 1637.29  5109.6 1638.79  5235.2 1638.38  5255.4 1639.19
  5413.2 1640.28  5428.7  1639.3  5580.8  1639.5  5596.8 1638.76  5612.2 1639.73
  5667.1 1638.45  5842.5 1638.64  5900.3 1639.95  5970.7 1639.19  5995.6 1640.04
#Mann= 5 ,-1 , 0
  3737.2    .035       0    4655    .063       0  4933.9    .035       0
  5034.8    .035       0  5043.8    .035       0
Bank Sta=5034.8,5043.8
XS Rating Curve= 0 ,0
Exp/Cntr=0.3,0.1

Type RM Length L Ch R = 1 ,5522    ,396,396,396
BEGIN DESCRIPTION:
Mapping XS db194d7a
END DESCRIPTION:
XS GIS Cut Line= 3
      1566462.98      6909354.73      1564892.93      6908807.56
      1564658.41      6908805.43
#Sta/Elev= 30
  3720.9  1642.7  3761.5 1641.98  3792.9 1639.99  3835.3 1639.19  3951.7  1639.7
  4248.3 1638.76  4311.8  1639.4  4385.9 1638.91  4398.2 1638.13  4417.7 1639.09
  4636.3 1638.21  4791.7 1638.69  4853.8 1637.53  4910.7  1637.8    4926 1637.03
  4947.2 1637.55  4994.1 1635.97  4994.6 1635.47  5003.1 1635.97  5029.7 1636.72
  5084.9 1636.19    5154 1637.27  5254.3 1637.51  5264.9 1638.13  5340.5 1638.41
  5349.6 1639.35  5406.1 1639.23  5521.5 1639.56  5551.5 1638.87  5618.1 1639.58
#Mann= 4 ,-1 , 0
  3720.9    .035       0  4994.1    .035       0  5003.1    .035       0
  5406.1    .063       0
Bank Sta=4994.1,5003.1
XS Rating Curve= 0 ,0
Exp/Cntr=0.3,0.1

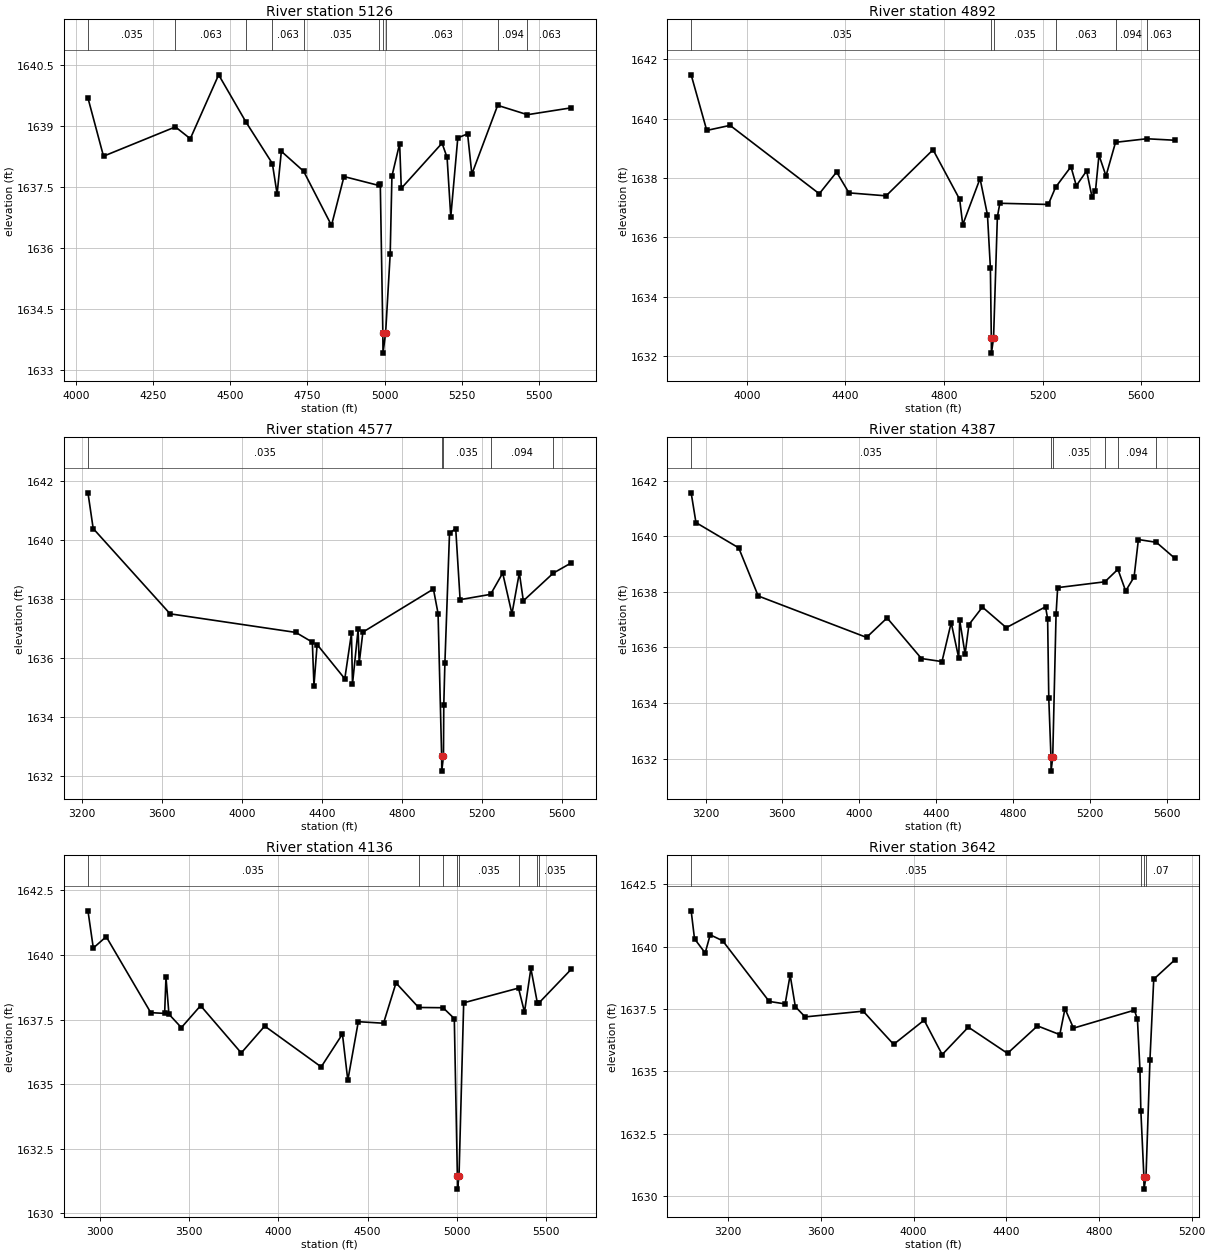
Type RM Length L Ch R = 1 ,5126    ,234,234,234
BEGIN DESCRIPTION:
Mapping XS de9471ba
END DESCRIPTION:
XS GIS Cut Line= 3
      1566141.21       6908929.1      1565123.83      6908547.14
       1564691.1      6908752.72
#Sta/Elev= 30
  4039.3 1639.69  4089.6 1638.26  4322.4 1638.98  4370.7 1638.69  4462.5 1640.26
  4550.9  1639.1  4636.4 1638.08  4651.8 1637.33  4665.5 1638.38  4737.7 1637.89
  4827.9 1636.56  4868.4 1637.76  4981.6 1637.54  4985.9 1637.58  4994.2 1633.92
  4994.7 1633.42  5003.2 1633.92    5018 1635.86  5023.6 1637.77  5048.6 1638.57
  5053.9 1637.47  5185.9 1638.58  5202.2 1638.23  5214.2 1636.77  5236.9 1638.71
  5268.6 1638.81  5282.4 1637.82    5366 1639.51  5462.4 1639.28  5605.1 1639.45
#Mann= 10 ,-1 , 0
  4039.3    .035       0  4322.4    .063       0  4550.9    .035       0
  4636.4    .063       0  4737.7    .035       0  4981.6    .063       0
  4994.2    .035       0  5003.2    .063       0    5366    .094       0
  5462.4    .063       0
Bank Sta=4994.2,5003.2
XS Rating Curve= 0 ,0
Exp/Cntr=0.3,0.1

Type RM Length L Ch R = 1 ,4892    ,315,315,315
BEGIN DESCRIPTION:
Mapping XS b3879da4
END DESCRIPTION:
XS GIS Cut Line= 5
      1566525.16      6908425.36      1566151.61      6908304.09
      1565186.33      6908385.69      1564937.39      6908607.54
      1564704.46      6908737.82
#Sta/Elev= 30
    3774 1641.47  3837.3  1639.6  3931.9 1639.77  4293.8 1637.47  4364.1  1638.2
  4414.2  1637.5  4564.8  1637.4  4755.4 1638.95  4863.5 1637.28  4875.9 1636.43
  4946.1 1637.98  4976.2 1636.76  4988.1 1634.97  4991.8 1632.61  4992.3 1632.11
  5000.9 1632.61  5016.4 1636.69  5026.4 1637.15    5223 1637.11  5252.7 1637.69
  5314.9 1638.38  5336.7 1637.74  5378.5 1638.24  5400.2 1637.37  5414.4 1637.56
  5428.6 1638.77  5457.1 1638.07  5495.8  1639.2  5622.5 1639.32  5735.8 1639.27
#Mann= 6 ,-1 , 0
    3774    .035       0  4991.8    .045       0  5000.9    .035       0
  5252.7    .063       0  5495.8    .094       0  5622.5    .063       0
Bank Sta=4991.8,5000.9
XS Rating Curve= 0 ,0
Exp/Cntr=0.3,0.1

Type RM Length L Ch R = 1 ,4577    ,190,190,190
BEGIN DESCRIPTION:
Mapping XS a44a9802
END DESCRIPTION:
XS GIS Cut Line= 6
      1566539.13      6908389.62      1565375.12       6907909.4
      1565259.25      6907875.27      1565177.65      6907984.64
      1564905.82      6908589.48      1564711.42      6908725.32
#Sta/Elev= 30
  3231.4 1641.59  3257.5 1640.38  3641.8 1637.49  4270.2 1636.86  4352.8 1636.53
  4360.9 1635.06  4376.7 1636.45    4515 1635.29  4548.3 1636.83  4553.5 1635.11
  4581.7 1636.97  4586.9 1635.81  4605.4 1636.87    4958 1638.33  4981.2  1637.5
  4999.1 1632.66  4999.6 1632.16  5008.2 1632.66  5009.8 1634.41  5015.3 1635.81
  5038.4 1640.22  5069.4 1640.38  5091.4 1637.97  5243.7 1638.15  5304.2 1638.87
  5350.5 1637.49  5387.4 1638.88  5407.4 1637.93  5557.2 1638.87  5648.1 1639.22
#Mann= 5 ,-1 , 0
  3231.4    .035       0  4999.1    .035       0  5008.2    .035       0
  5243.7    .094       0  5557.2    .063       0
Bank Sta=4999.1,5008.2
XS Rating Curve= 0 ,0
Exp/Cntr=0.3,0.1

Type RM Length L Ch R = 1 ,4387    ,251,251,251
BEGIN DESCRIPTION:
Mapping XS 99afcec7
END DESCRIPTION:
XS GIS Cut Line= 5
      1566548.18      6908377.06      1565266.89       6907853.6
      1565127.31      6907845.76      1564976.26      6907979.44
      1564650.12      6908700.62
#Sta/Elev= 30
  3125.3 1641.56  3150.3 1640.49  3372.9 1639.58  3474.4 1637.85  4038.3 1636.36
  4145.2 1637.06  4324.1  1635.6    4431 1635.49    4479 1636.89  4518.2 1635.62
  4523.2 1636.98  4551.4 1635.76  4571.4 1636.82  4641.5 1637.45  4765.8 1636.71
  4970.1 1637.46    4981 1637.03    4987 1634.17  4998.4 1632.05  4998.9 1631.55
  5007.5 1632.05  5024.9 1637.19  5033.2 1638.15    5279 1638.36  5346.9 1638.81
  5387.1 1638.03    5431 1638.53  5453.5 1639.88    5547 1639.78  5642.4 1639.21
#Mann= 6 ,-1 , 0
  3125.3    .035       0  4998.4    .035       0  5007.5    .035       0
    5279    .063       0  5346.9    .094       0    5547    .063       0
Bank Sta=4998.4,5007.5
XS Rating Curve= 0 ,0
Exp/Cntr=0.3,0.1

Type RM Length L Ch R = 1 ,4136    ,494,494,494
BEGIN DESCRIPTION:
Mapping XS a501ab98
END DESCRIPTION:
XS GIS Cut Line= 6
      1566560.68      6908362.97      1565269.03      6907842.14
      1565142.93      6907830.13       1564833.9      6907828.39
      1564726.26      6907922.14      1564427.01       6908599.1
#Sta/Elev= 30
  2932.4 1641.71  2962.3 1640.27  3034.7 1640.71  3284.4 1637.77  3362.3 1637.74
  3369.8 1639.14  3386.4 1637.71  3456.1 1637.19  3563.9 1638.04  3791.9 1636.21
  3923.4 1637.25  4240.2 1635.67  4359.3 1636.94  4389.4 1635.15  4448.2 1637.42
  4589.7 1637.36  4659.7 1638.92  4786.4 1637.97  4923.6 1637.96  4986.5 1637.54
  5003.8 1631.44  5004.3 1630.94  5012.9 1631.44  5039.2 1638.15  5346.6 1638.72
  5380.1 1637.79    5416 1639.48  5452.4 1638.14    5459 1638.13  5643.7 1639.46
#Mann= 8 ,-1 , 0
  2932.4    .035       0  4786.4     .07       0  4923.6    .035       0
  5003.8    .035       0  5012.9    .035       0  5346.6    .094       0
  5452.4    .063       0    5459    .035       0
Bank Sta=5003.8,5012.9
XS Rating Curve= 0 ,0
Exp/Cntr=0.3,0.1

Type RM Length L Ch R = 1 ,3642    ,341,341,341
BEGIN DESCRIPTION:
Mapping XS e778cd0b
END DESCRIPTION:
XS GIS Cut Line= 2
      1566551.16      6908339.33      1564615.94      6907559.33
#Sta/Elev= 30
    3040 1641.43  3054.5 1640.31  3100.5 1639.74  3122.1 1640.47    3176 1640.23
  3376.7  1637.8  3445.6  1637.7  3467.1 1638.86  3489.5 1637.59  3531.8 1637.18
  3782.2 1637.41  3913.7 1636.08  4045.3 1637.05  4123.2 1635.67    4236 1636.77
  4405.1 1635.72  4534.5 1636.82  4630.7 1636.47  4653.1 1637.51  4689.8 1636.73
  4952.9 1637.45  4965.8 1637.08  4976.6 1635.07  4980.5 1633.42  4993.6 1630.78
  4994.1 1630.28  5002.7 1630.78  5019.7 1635.45  5036.1 1638.69  5126.5 1639.46
#Mann= 4 ,-1 , 0
    3040    .035       0  4980.5     .07       0  4993.6     .05       0
  5002.7     .07       0
Bank Sta=4993.6,5002.7
XS Rating Curve= 0 ,0
Exp/Cntr=0.3,0.1

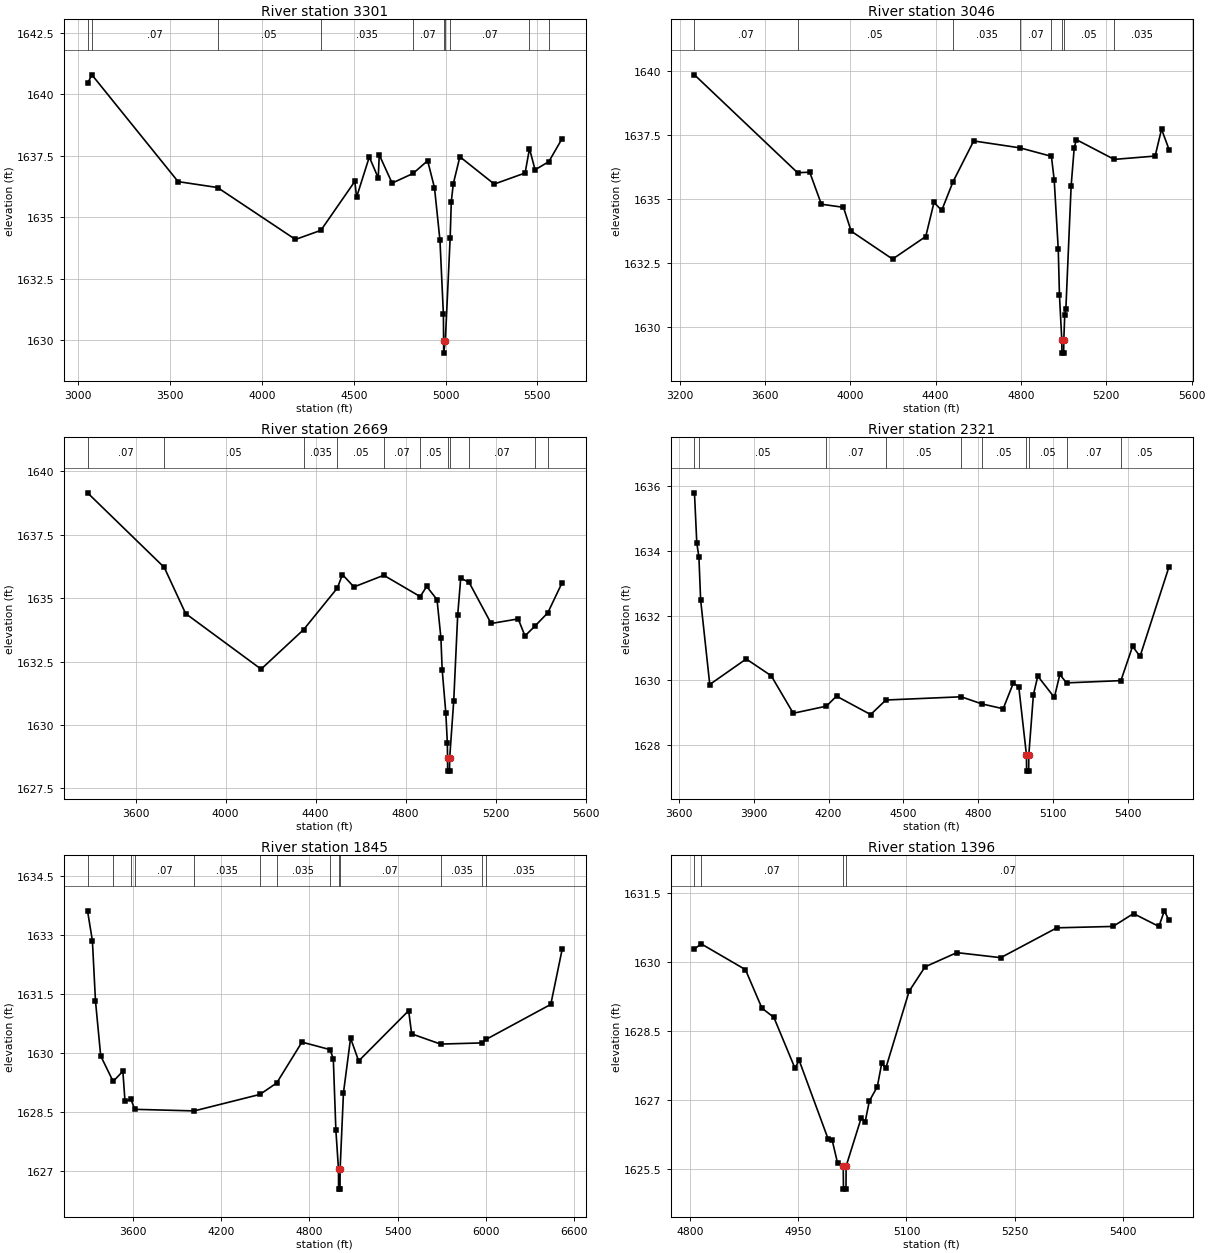
Type RM Length L Ch R = 1 ,3301    ,255,255,255
BEGIN DESCRIPTION:
Mapping XS f94a6d2e
END DESCRIPTION:
XS GIS Cut Line= 2
      1566678.79       6908003.4      1564273.17      6907058.88
#Sta/Elev= 30
  3050.5 1640.43  3074.4 1640.78  3543.7 1636.44  3758.3  1636.2  4182.6 1634.09
  4321.1 1634.46    4506 1636.45  4515.6 1635.81  4584.7 1637.44  4633.5 1636.59
  4638.9 1637.53    4709 1636.38  4822.7 1636.77  4902.4 1637.29  4939.8 1636.19
  4969.6 1634.05  4988.3 1631.04  4989.4 1629.97  4989.9 1629.47  4998.7 1629.97
  5025.1 1634.15  5031.3 1635.63  5042.1 1636.35    5078 1637.45  5265.1 1636.34
  5433.1 1636.79    5457 1637.78  5487.4 1636.92  5562.2 1637.25  5634.9 1638.19
#Mann= 10 ,-1 , 0
  3050.5    .035       0  3074.4     .07       0  3758.3     .05       0
  4321.1    .035       0  4822.7     .07       0  4989.4     .05       0
  4998.7     .07       0  5025.1     .07       0    5457    .063       0
  5562.2    .035       0
Bank Sta=4989.4,4998.7
XS Rating Curve= 0 ,0
Exp/Cntr=0.3,0.1

Type RM Length L Ch R = 1 ,3046    ,377,377,377
BEGIN DESCRIPTION:
Mapping XS 7a6447a9
END DESCRIPTION:
XS GIS Cut Line= 2
      1566577.19      6907675.26      1564499.88      6906879.24
#Sta/Elev= 30
  3269.6 1639.84  3752.8 1636.02  3809.8 1636.04  3864.5 1634.79    3968 1634.67
    4004 1633.74  4198.2 1632.65  4353.6 1633.53  4392.4 1634.86  4428.5 1634.55
  4481.6 1635.67  4578.4 1637.26  4795.5 1636.99  4942.6 1636.66  4955.7 1635.74
  4974.7 1633.04  4980.3 1631.25  4991.4 1629.48  4991.9 1628.98  5000.2 1628.98
  5000.7 1629.48    5005 1630.46  5010.4 1630.71  5035.1 1635.51  5049.6    1637
  5059.8 1637.31  5236.9 1636.54  5428.8 1636.67  5458.8 1637.72  5494.2 1636.92
#Mann= 8 ,-1 , 0
  3269.6     .07       0  3752.8     .05       0  4481.6    .035       0
  4795.5     .07       0  4942.6     .05       0  4991.4     .05       0
  5000.7     .05       0  5236.9    .035       0
Bank Sta=4991.4,5000.7
XS Rating Curve= 0 ,0
Exp/Cntr=0.3,0.1

Type RM Length L Ch R = 1 ,2669    ,348,348,348
BEGIN DESCRIPTION:
Mapping XS d95b85a5
END DESCRIPTION:
XS GIS Cut Line= 6
      1566490.92      6907517.83      1565684.83      6907114.06
      1565601.26      6907048.45      1565286.16      6906790.63
      1564913.76      6906618.76      1564629.98      6906603.14
#Sta/Elev= 30
  3386.2 1639.15  3727.2 1636.21  3822.3 1634.39  4157.6  1632.2  4346.8 1633.76
  4496.7  1635.4    4519 1635.93    4570 1635.44  4702.8  1635.9  4864.6 1635.06
  4893.5 1635.46  4939.4 1634.94  4956.6 1633.44  4962.3 1632.18  4978.6 1630.46
  4985.3 1629.28  4986.1 1628.68  4986.6 1628.18    4995 1628.18  4995.5 1628.68
  5013.7 1630.96  5031.2 1634.32  5044.7 1635.79  5081.9 1635.62  5179.9    1634
  5300.2 1634.18  5330.2 1633.51    5375  1633.9  5431.6 1634.42  5495.5 1635.61
#Mann= 11 ,-1 , 0
  3386.2     .07       0  3727.2     .05       0  4346.8    .035       0
  4496.7     .05       0  4702.8     .07       0  4864.6     .05       0
  4986.1     .05       0  4995.5     .05       0  5081.9     .07       0
    5375    .035       0  5431.6     .05       0
Bank Sta=4986.1,4995.5
XS Rating Curve= 0 ,0
Exp/Cntr=0.3,0.1

Type RM Length L Ch R = 1 ,2321    ,476,476,476
BEGIN DESCRIPTION:
Mapping XS fe4992c1
END DESCRIPTION:
XS GIS Cut Line= 4
      1566442.19      6907115.35      1565421.58      6906475.53
      1565070.01      6906316.68      1564758.78      6906301.11
#Sta/Elev= 30
  3662.7  1635.8  3672.1 1634.24  3680.5 1633.82  3687.4 1632.49    3724 1629.87
  3870.1 1630.66  3970.3 1630.14  4058.6 1628.98  4191.5  1629.2  4231.9 1629.51
  4368.6 1628.94  4429.9 1629.39  4731.8 1629.49  4814.1 1629.27  4899.8 1629.12
  4940.3 1629.91  4962.3  1629.8  4993.1 1627.69  4993.6 1627.19    5002 1627.19
  5002.5 1627.69  5020.9 1629.55  5038.5 1630.13  5104.9 1629.47  5126.9 1630.18
  5153.6 1629.92  5371.7 1629.99  5418.3 1631.05  5448.3 1630.74  5564.7 1633.52
#Mann= 10 ,-1 , 0
  3662.7    .063       0  3680.5     .05       0  4191.5     .07       0
  4429.9     .05       0  4731.8     .07       0  4814.1     .05       0
  4993.1     .05       0  5002.5     .05       0  5153.6     .07       0
  5371.7     .05       0
Bank Sta=4993.1,5002.5
XS Rating Curve= 0 ,0
Exp/Cntr=0.3,0.1

Type RM Length L Ch R = 1 ,1845    ,449,449,449
BEGIN DESCRIPTION:
Mapping XS f25c3e1e
END DESCRIPTION:
XS GIS Cut Line= 4
      1566865.41      6906913.56      1565648.14      6906022.41
      1565056.99      6905871.36      1563969.08      6905672.37
#Sta/Elev= 30
  3292.5 1633.61  3325.6 1632.85  3346.5 1631.32    3382 1629.92  3466.5 1629.27
  3532.6 1629.53  3547.2 1628.76  3586.8 1628.82  3613.6 1628.56  4017.5 1628.52
  4464.4 1628.94  4577.7 1629.23  4749.3 1630.27  4939.5 1630.08  4962.3 1629.85
  4979.8 1628.03  4997.7 1627.03  4998.2 1626.53    5008 1626.53  5008.5 1627.03
  5031.4 1628.98  5079.7 1630.37  5134.6 1629.79  5474.3 1631.07  5494.6 1630.48
  5690.8 1630.22  5975.4 1630.25  6000.9 1630.34    6440 1631.23  6517.2 1632.63
#Mann= 13 ,-1 , 0
  3292.5     .05       0  3466.5     .07       0  3586.8    .035       0
  3613.6     .07       0  4017.5    .035       0  4464.4     .07       0
  4577.7    .035       0  4939.5     .07       0  4997.7     .07       0
  5008.5     .07       0  5690.8    .035       0  5975.4     .07       0
  6000.9    .035       0
Bank Sta=4997.7,5008.5
XS Rating Curve= 0 ,0
Exp/Cntr=0.3,0.1

Type RM Length L Ch R = 1 ,1396    ,369,369,369
BEGIN DESCRIPTION:
Mapping XS 1cc7aefb
END DESCRIPTION:
XS GIS Cut Line= 3
       1565869.3      6905947.84      1565697.62      6905577.09
      1565511.56      6905411.71
#Sta/Elev= 30
  4806.3 1630.29  4815.7  1630.4  4876.9 1629.84  4899.8    1629  4916.3  1628.8
  4945.6 1627.69  4951.2 1627.87  4991.5 1626.15    4997 1626.13  5004.5 1625.63
  5012.4 1625.56  5012.7 1625.06  5016.2 1625.06  5016.4 1625.56  5037.3 1626.61
  5042.8 1626.53  5048.6 1626.98  5059.6 1627.29  5065.7  1627.8  5071.3 1627.69
  5103.7 1629.37  5125.7  1629.9  5169.8 1630.21  5230.6  1630.1  5308.3 1630.75
  5386.1 1630.78  5414.5 1631.06  5449.7 1630.78  5457.2 1631.12  5463.8 1630.91
#Mann= 4 ,-1 , 0
  4806.3    .035       0  4815.7     .07       0  5012.4     .07       0
  5016.4     .07       0
Bank Sta=5012.4,5016.4
XS Rating Curve= 0 ,0
Exp/Cntr=0.3,0.1

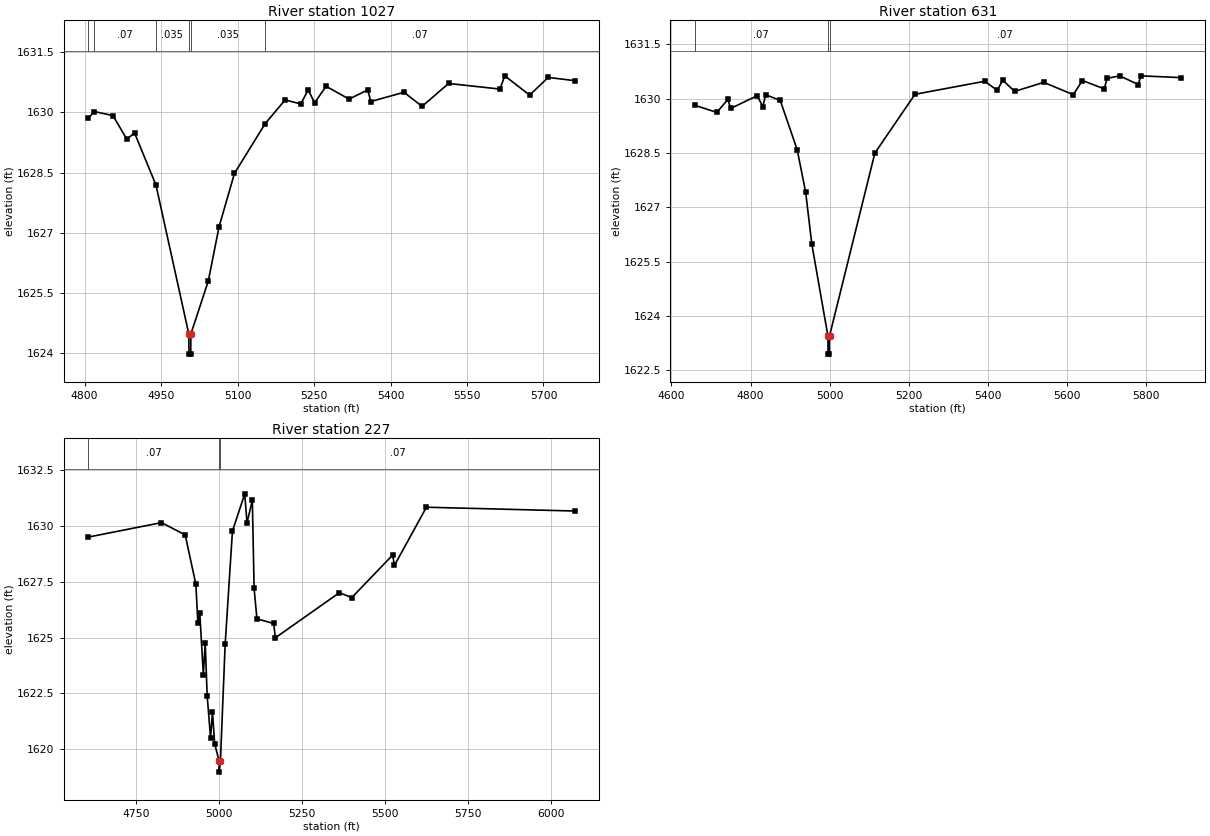
Type RM Length L Ch R = 1 ,1027    ,396,396,396
BEGIN DESCRIPTION:
Mapping XS 719032a8
END DESCRIPTION:
XS GIS Cut Line= 3
      1566248.99      6905860.44      1566025.74       6905519.8
      1565559.77      6905233.45
#Sta/Elev= 30
  4806.9 1629.85    4819 1630.02  4855.7 1629.92  4882.8 1629.33  4897.9 1629.49
    4940 1628.19  5004.4 1624.48  5004.7 1623.98  5008.2 1623.98  5008.4 1624.48
  5042.6  1625.8  5063.7 1627.15  5093.9 1628.48  5154.2 1629.72  5193.3 1630.31
    5224 1630.21  5238.5 1630.56  5251.2 1630.24  5273.7 1630.65  5318.7 1630.33
  5355.4 1630.56  5361.3 1630.27  5426.3  1630.5  5461.9 1630.15    5514 1630.72
  5614.6 1630.58  5624.1 1630.91  5672.8 1630.43  5709.3 1630.87  5761.1 1630.79
#Mann= 6 ,-1 , 0
  4806.9    .035       0    4819     .07       0    4940    .035       0
  5004.4    .045       0  5008.4    .035       0  5154.2     .07       0
Bank Sta=5004.4,5008.4
XS Rating Curve= 0 ,0
Exp/Cntr=0.3,0.1

Type RM Length L Ch R = 1 ,631     ,404,404,404
BEGIN DESCRIPTION:
Mapping XS 88a00f91
END DESCRIPTION:
XS GIS Cut Line= 3
      1566713.24      6905605.74      1566181.99      6905288.03
      1565609.57      6905074.67
#Sta/Elev= 30
  4658.4 1629.82  4714.6 1629.62  4742.7 1629.98  4749.6 1629.73  4816.6 1630.08
  4831.1 1629.78    4838 1630.11    4875 1629.95  4917.8 1628.59  4939.2 1627.42
  4954.7 1625.99  4995.5 1623.45  4995.8 1622.95  4999.3 1622.95  4999.5 1623.45
  5114.2  1628.5  5215.6 1630.12  5391.6 1630.48  5423.6 1630.23  5437.3 1630.51
  5467.6  1630.2    5541 1630.45  5615.7 1630.11  5638.9  1630.5  5694.2 1630.27
  5701.1 1630.56  5733.1 1630.63  5779.8 1630.39  5786.5 1630.63  5888.3 1630.58
#Mann= 3 ,-1 , 0
  4658.4     .07       0  4995.5     .07       0  4999.5     .07       0
Bank Sta=4995.5,4999.5
XS Rating Curve= 0 ,0
Exp/Cntr=0.3,0.1

Type RM Length L Ch R = 1 ,227     ,0,0,0
BEGIN DESCRIPTION:
NC Unknown Stream 92 1.0
END DESCRIPTION:
XS GIS Cut Line= 3
      1566866.02      6905494.62      1566637.72      6905066.68
      1565702.85       6904767.2
#Sta/Elev= 30
    4605  1629.5  4826.2 1630.15  4897.7  1629.6  4929.9 1627.38    4936 1625.63
  4941.7 1626.09  4952.3 1623.34    4958 1624.76  4963.9  1622.4  4974.2 1620.49
  4979.9 1621.67  4986.5 1620.24  4999.9 1619.47  5000.1 1618.97  5003.9 1619.47
  5018.2 1624.71  5040.1 1629.77  5077.2 1631.44    5084 1630.14  5100.1 1631.15
  5105.4 1627.21  5113.9 1625.84  5164.4 1625.63  5169.6 1624.99  5362.5 1627.01
  5399.9 1626.79  5523.2  1628.7  5528.4 1628.23  5624.9 1630.84  6071.7 1630.67
#Mann= 3 ,-1 , 0
    4605     .07       0  4999.9     .07       0  5003.9     .07       0
Bank Sta=4999.9,5003.9
XS Rating Curve= 0 ,0
Exp/Cntr=0.3,0.1

Chan Stop Cuts=-1
Use User Specified Reach Order=0
Composite Channel Slope=5