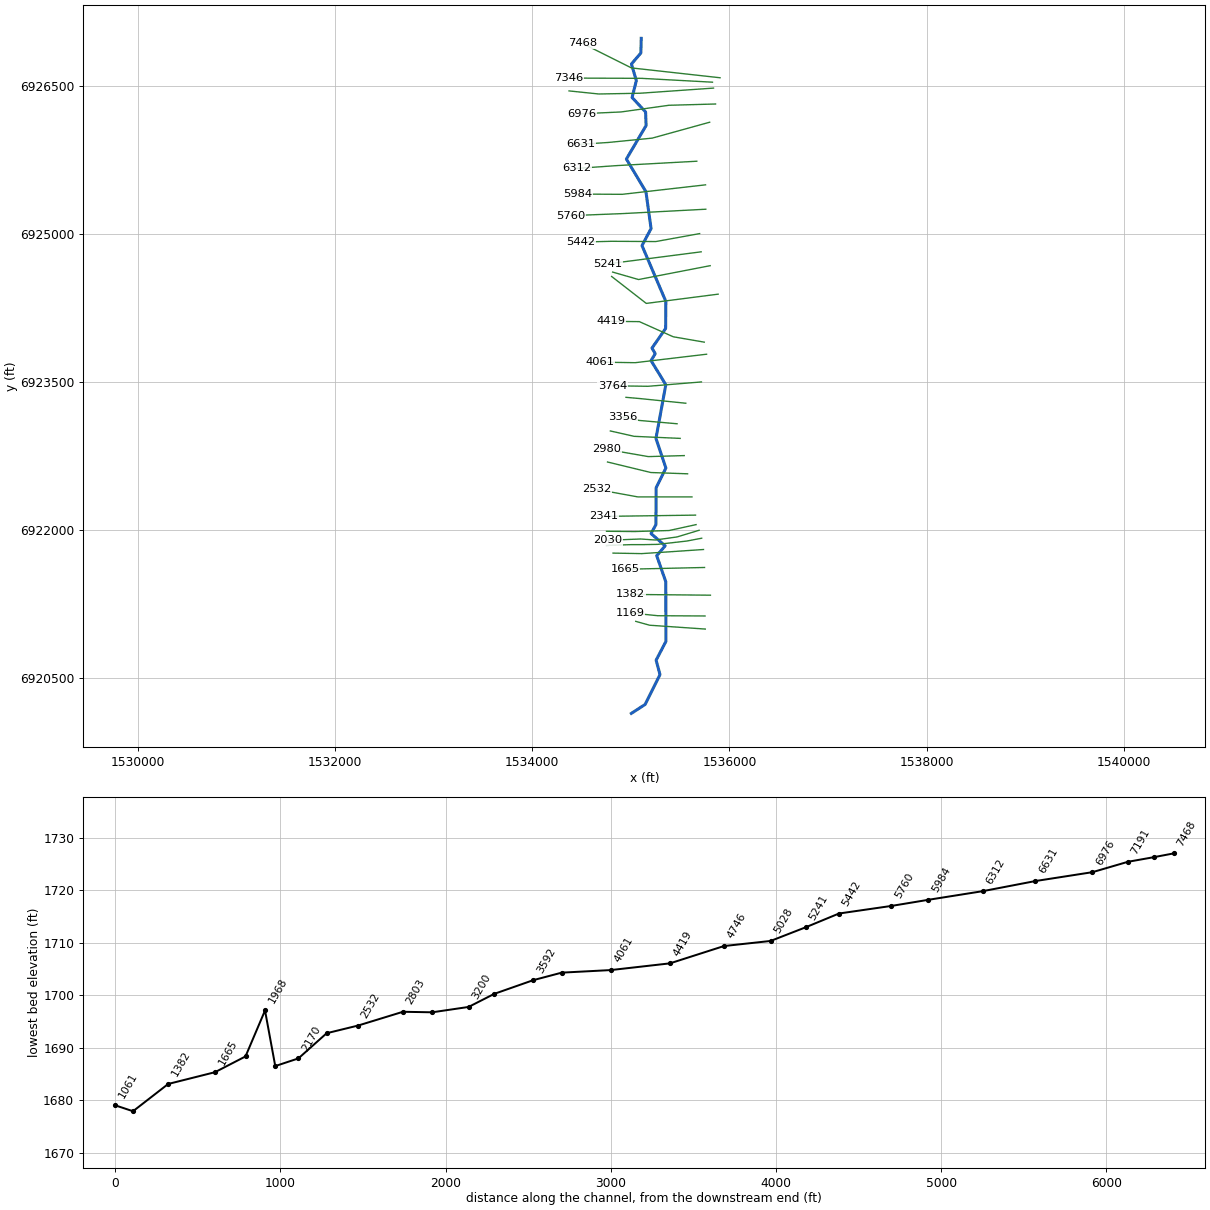
--- NC Unknown Stream 99.prj (project) ---

Proj Title=NC Unknown Stream 99 Base Level Engineering
Current Plan=p01
Default Exp/Contr=0.3,0.1
English Units
Geom File=g01
Flow File=f01
Plan File=p01
BEGIN DESCRIPTION:
NC Unknown Stream 99
END DESCRIPTION:

--- NC Unknown Stream 99.p01 (plan) ---

Plan Title=Multiple Run
Short Identifier=Multiple
Geom File=g01
Flow File=f01
Subcritical Flow
K Sum by GR= 0
Std Step Tol= 0.01
Critical Tol= 0.01
Num of Std Step Trials= 20
Max Error Tol= 0.3
Flow Tol Ratio= 0.001
Split Flow NTrial= 30
Split Flow Tol= 0.02
Split Flow Ratio= 0.02
Log Output Level= 0
Friction Slope Method= 1
Unsteady Friction Slope Method= 2
Unsteady Bridges Friction Slope Method= 1
Parabolic Critical Depth
Global Vel Dist=  1 , 1 , 1
Global Log Level= 0
CheckData=True
Encroach Param= -1, 0, 0, 0
BEGIN DESCRIPTION:
Multiple Run
END DESCRIPTION:

--- NC Unknown Stream 99.f01 (steady flow) ---

Flow Title=Multiple
Number of Profiles=7
Profile Names=10-year,25-year,50-year,1pct_min,100-year,1pct_plu,500-year
River Rch & RM= NC Unknown Strea,Reach-1,7468
     216     297     363     221     441     880     660
River Rch & RM= NC Unknown Strea,Reach-1,6631
     293     409     505     311     620    1238     947
Boundary for River Rch & Prof#=NC Unknown Strea,Reach-1,1
Up Type=0
Dn Type=3
Dn Slope=0.001
Boundary for River Rch & Prof#=NC Unknown Strea,Reach-1,2
Up Type=0
Dn Type=3
Dn Slope=0.001
Boundary for River Rch & Prof#=NC Unknown Strea,Reach-1,3
Up Type=0
Dn Type=3
Dn Slope=0.001
Boundary for River Rch & Prof#=NC Unknown Strea,Reach-1,4
Up Type=0
Dn Type=3
Dn Slope=0.001
Boundary for River Rch & Prof#=NC Unknown Strea,Reach-1,5
Up Type=0
Dn Type=3
Dn Slope=0.001
Boundary for River Rch & Prof#=NC Unknown Strea,Reach-1,6
Up Type=0
Dn Type=3
Dn Slope=0.001
Boundary for River Rch & Prof#=NC Unknown Strea,Reach-1,7
Up Type=0
Dn Type=3
Dn Slope=0.001

--- NC Unknown Stream 99.g01 (geometry) ---

Geom Title=Existing Conditions

River Reach=NC Unknown Strea,Reach-1
Reach XY= 30
      1535105.00      6926988.00      1535101.49      6926839.45
      1535005.94      6926727.52      1535055.39      6926558.13
      1535012.32      6926387.90      1535149.55      6926240.45
      1535154.51      6926103.22      1534954.58      6925763.00
      1535152.75      6925432.07      1535204.94      6925058.03
      1535113.06      6924884.71      1535354.94      6924317.97
      1535352.76      6924043.93      1535214.31      6923844.66
      1535247.16      6923788.09      1535204.82      6923717.87
      1535354.63      6923472.83      1535254.54      6922927.81
      1535355.50      6922627.83      1535256.20      6922427.50
      1535254.46      6922053.20      1535204.47      6921962.88
      1535347.91      6921838.01      1535262.34      6921738.10
      1535354.48      6921472.78      1535355.36      6920867.85
      1535256.09      6920677.45      1535295.58      6920531.38
      1535144.25      6920228.30      1535005.00      6920138.00

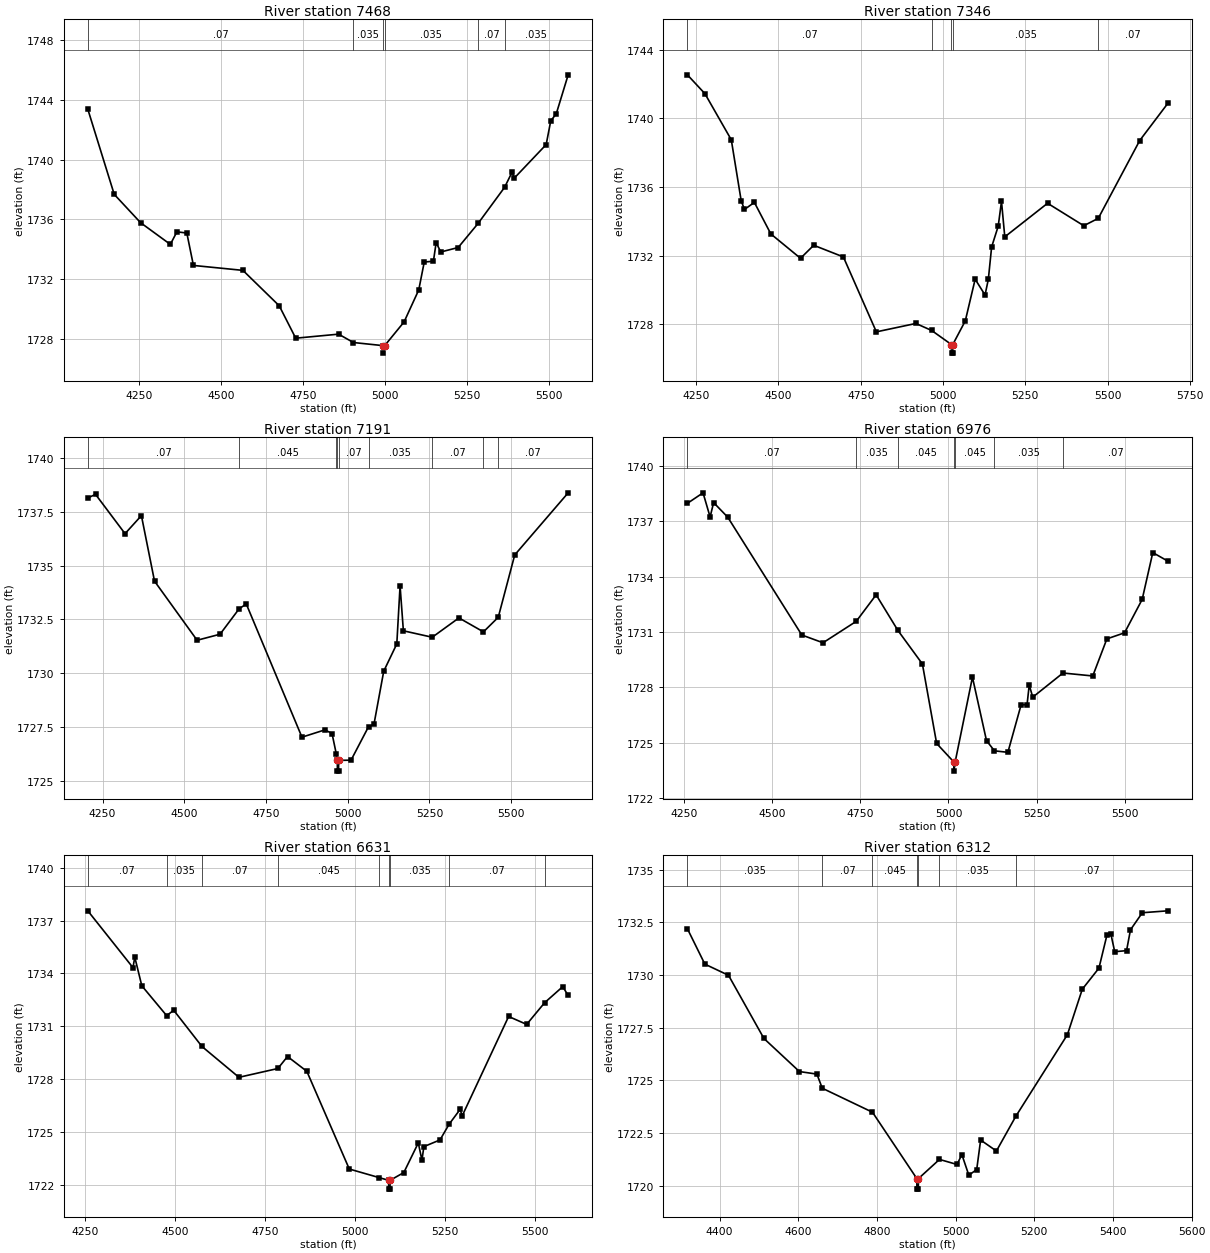
Type RM Length L Ch R = 1,7468,122,122,122
BEGIN DESCRIPTION:
NC Unknown Stream 99 16.0
END DESCRIPTION:
XS GIS Cut Line= 3
      1535905.05      6926587.99      1535005.00      6926688.00
      1534505.00      6926938.00
#Sta/Elev= 30
  4093.5 1743.37  4174.0 1737.67  4254.5 1735.77  4345.1 1734.32  4365.2 1735.16
  4395.4 1735.08  4415.5 1732.91  4566.4 1732.58  4677.1 1730.21  4727.4 1728.04
  4858.2 1728.31  4903.3 1727.75  4994.6 1727.54  4994.8 1727.04  4998.6 1727.54
  5057.8 1729.13  5102.5 1731.27  5119.3 1733.14  5147.2 1733.19  5155.6 1734.44
  5169.6 1733.81  5222.7 1734.11  5283.4 1735.72  5364.3 1738.14  5387.6 1739.18
  5393.2 1738.74  5491.0 1741.00  5505.0 1742.59  5521.8 1743.06  5558.1 1745.67
#Mann=6,-1,0
  4093.5    0.07       0  4903.3   0.035       0  4994.6   0.035       0
  4998.6   0.035       0  5283.4    0.07       0  5364.3   0.035       0
Bank Sta=4994.6,4998.6
Exp/Cntr=0.3,0.1

Type RM Length L Ch R = 1,7346,155,155,155
BEGIN DESCRIPTION:
Mapping XS ceaa8651
END DESCRIPTION:
XS GIS Cut Line= 3
      1535828.21      6926543.02      1535106.82      6926582.08
      1534369.87      6926584.69
#Sta/Elev= 30
  4223.4 1742.54  4276.7 1741.44  4356.8 1738.75  4386.9 1735.19  4396.9 1734.69
  4426.9 1735.10  4477.0 1733.26  4567.1 1731.84  4607.2 1732.60  4697.3 1731.92
  4797.5 1727.55  4917.6 1728.04  4965.6 1727.63  5025.7 1726.81  5025.9 1726.31
  5029.4 1726.31  5029.7 1726.81  5067.7 1728.19  5097.7 1730.62  5127.7 1729.70
  5137.7 1730.61  5147.7 1732.50  5167.7 1733.71  5177.7 1735.16  5187.7 1733.09
  5317.7 1735.05  5427.7 1733.74  5471.7 1734.17  5597.7 1738.71  5682.8 1740.87
#Mann=5,-1,0
  4223.4    0.07       0  4965.6   0.035       0  5025.7   0.035       0
  5029.7   0.035       0  5471.7    0.07       0
Bank Sta=5025.7,5029.7
Exp/Cntr=0.3,0.1

Type RM Length L Ch R = 1,7191,215,215,215
BEGIN DESCRIPTION:
Mapping XS 15e2ba40
END DESCRIPTION:
XS GIS Cut Line= 4
      1535838.59      6926483.13      1535096.40      6926431.04
      1534674.53      6926423.23      1534372.40      6926454.48
#Sta/Elev= 30
  4204.8 1738.15  4228.4 1738.32  4318.7 1736.49  4368.8 1737.33  4408.9 1734.28
  4539.2 1731.53  4609.4 1731.81  4667.6 1732.99  4689.6 1733.22  4860.0 1727.02
  4930.2 1727.36  4952.0 1727.19  4964.8 1726.26  4968.2 1725.94  4968.5 1725.44
  4972.0 1725.44  4972.2 1725.94  5010.2 1725.95  5063.8 1727.51  5080.2 1727.61
  5110.2 1730.09  5150.2 1731.36  5160.2 1734.06  5170.3 1731.97  5258.6 1731.67
  5340.3 1732.57  5415.3 1731.92  5460.6 1732.60  5511.0 1735.50  5674.5 1738.39
#Mann=9,-1,0
  4204.8    0.07       0  4667.6   0.045       0  4964.8    0.07       0
  4968.2    0.07       0  4972.2    0.07       0  5063.8   0.035       0
  5258.6    0.07       0  5415.3   0.035       0  5460.6    0.07       0
Bank Sta=4968.2,4972.2
Exp/Cntr=0.3,0.1

Type RM Length L Ch R = 1,6976,345,345,345
BEGIN DESCRIPTION:
Mapping XS a7f2109e
END DESCRIPTION:
XS GIS Cut Line= 4
      1535859.41      6926321.67      1535385.47      6926308.65
      1534901.09      6926240.94      1534502.61      6926222.71
#Sta/Elev= 30
  4259.7 1737.98  4304.1 1738.55  4324.1 1737.24  4334.1 1738.02  4374.1 1737.23
  4584.2 1730.84  4644.3 1730.42  4738.4 1731.58  4794.9 1733.02  4856.6 1731.09
  4926.1 1729.27  4966.5 1724.96  5015.0 1723.96  5015.3 1723.46  5019.0 1723.96
  5068.0 1728.55  5107.9 1725.11  5130.5 1724.56  5168.5 1724.48  5205.9 1727.05
  5222.9 1727.07  5229.0 1728.13  5239.0 1727.47  5324.7 1728.78  5409.2 1728.62
  5449.2 1730.63  5499.3 1730.96  5549.3 1732.77  5579.4 1735.31  5621.8 1734.85
#Mann=7,-1,0
  4259.7    0.07       0  4738.4   0.035       0  4856.6   0.045       0
  5015.0   0.045       0  5019.0   0.045       0  5130.5   0.035       0
  5324.7    0.07       0
Bank Sta=5015,5019
Exp/Cntr=0.3,0.1

Type RM Length L Ch R = 1,6631,319,319,319
BEGIN DESCRIPTION:
Mapping XS f9343eb0
END DESCRIPTION:
XS GIS Cut Line= 4
      1535799.57      6926136.78      1535216.20      6925975.31
      1534768.28      6925931.04      1534489.97      6925913.00
#Sta/Elev= 30
  4257.1 1737.55  4382.5 1734.33  4387.6 1734.92  4407.1 1733.30  4476.0 1731.61
  4495.8 1731.91  4574.1 1729.86  4676.9 1728.11  4785.1 1728.61  4811.8 1729.29
  4865.5 1728.45  4983.4 1722.91  5066.9 1722.42  5092.7 1722.27  5093.0 1721.77
  5096.5 1721.77  5096.8 1722.27  5134.9 1722.71  5175.1 1724.39  5185.2 1723.41
  5190.6 1724.18  5235.4 1724.56  5261.0 1725.46  5291.6 1726.30  5296.7 1725.91
  5426.0 1731.56  5476.1 1731.11  5526.0 1732.34  5576.3 1733.25  5591.4 1732.75
#Mann=9,-1,0
  4257.1    0.07       0  4476.0   0.035       0  4574.1    0.07       0
  4785.1   0.045       0  5066.9   0.035       0  5092.7   0.045       0
  5096.8   0.035       0  5261.0    0.07       0  5526.0   0.035       0
Bank Sta=5092.7,5096.8
Exp/Cntr=0.3,0.1

Type RM Length L Ch R = 1,6312,328,328,328
BEGIN DESCRIPTION:
Mapping XS 10dfb474
END DESCRIPTION:
XS GIS Cut Line= 3
      1535669.33      6925740.94      1534859.42      6925696.67
      1534450.55      6925668.02
#Sta/Elev= 30
  4318.2 1732.20  4362.6 1730.52  4422.7 1729.99  4512.8 1726.99  4603.0 1725.42
  4647.4 1725.30  4661.0 1724.63  4788.7 1723.49  4901.4 1720.34  4901.6 1719.84
  4905.2 1719.84  4905.5 1720.34  4959.0 1721.25  5003.6 1721.01  5015.9 1721.48
  5033.6 1720.50  5053.6 1720.77  5063.6 1722.17  5103.7 1721.65  5153.1 1723.30
  5284.1 1727.17  5322.0 1729.33  5364.3 1730.33  5384.4 1731.88  5394.4 1731.97
  5404.4 1731.11  5434.5 1731.16  5444.5 1732.15  5474.6 1732.96  5539.2 1733.05
#Mann=7,-1,0
  4318.2   0.035       0  4661.0    0.07       0  4788.7   0.045       0
  4901.4   0.035       0  4905.5   0.045       0  4959.0   0.035       0
  5153.1    0.07       0
Bank Sta=4901.4,4905.5
Exp/Cntr=0.3,0.1

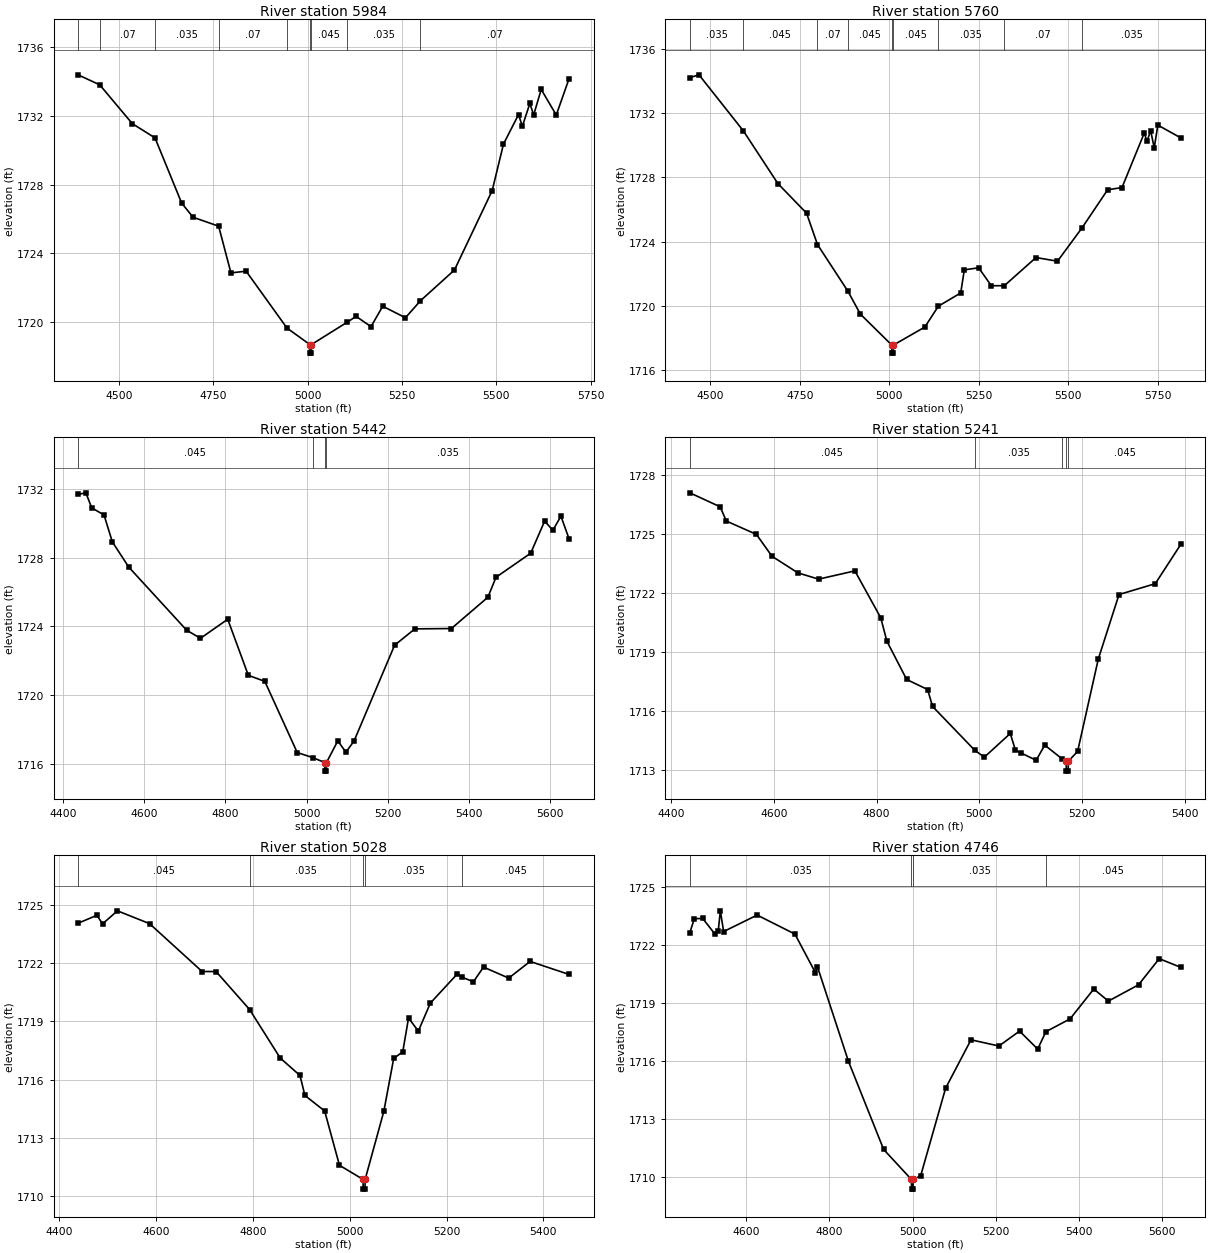
Type RM Length L Ch R = 1,5984,224,224,224
BEGIN DESCRIPTION:
Mapping XS e4018e6a
END DESCRIPTION:
XS GIS Cut Line= 3
      1535757.81      6925501.35      1534911.51      6925405.00
      1534460.99      6925407.60
#Sta/Elev= 30
  4390.9 1734.40  4448.2 1733.82  4534.6 1731.56  4594.9 1730.73  4665.5 1726.94
  4695.7 1726.11  4763.7 1725.59  4796.3 1722.87  4836.6 1722.97  4944.9 1719.66
  5005.6 1718.70  5005.9 1718.20  5009.5 1718.20  5009.8 1718.70  5104.7 1720.00
  5128.4 1720.34  5167.8 1719.74  5198.9 1720.93  5259.2 1720.26  5299.0 1721.25
  5389.2 1723.04  5489.2 1727.66  5519.2 1730.37  5559.2 1732.09  5569.2 1731.40
  5589.2 1732.74  5599.2 1732.06  5619.2 1733.55  5659.2 1732.06  5693.2 1734.18
#Mann=9,-1,0
  4390.9   0.035       0  4448.2    0.07       0  4594.9   0.035       0
  4763.7    0.07       0  4944.9   0.045       0  5005.6   0.045       0
  5009.8   0.045       0  5104.7   0.035       0  5299.0    0.07       0
Bank Sta=5005.6,5009.8
Exp/Cntr=0.3,0.1

Type RM Length L Ch R = 1,5760,318,318,318
BEGIN DESCRIPTION:
Mapping XS 12df7734
END DESCRIPTION:
XS GIS Cut Line= 3
      1535760.43      6925253.96      1534919.32      6925209.69
      1534390.70      6925188.86
#Sta/Elev= 30
  4443.0 1734.24  4468.5 1734.41  4592.4 1730.91  4688.8 1727.62  4768.9 1725.77
  4799.4 1723.81  4884.3 1720.90  4919.1 1719.47  5007.1 1717.53  5007.4 1717.03
  5011.1 1717.03  5011.3 1717.53  5099.3 1718.66  5137.0 1719.96  5199.5 1720.79
  5209.5 1722.23  5249.5 1722.36  5284.9 1721.24  5321.2 1721.24  5409.7 1723.00
  5469.7 1722.77  5538.5 1724.86  5609.8 1727.23  5649.9 1727.37  5712.0 1730.77
  5719.9 1730.26  5729.9 1730.93  5739.9 1729.85  5750.0 1731.27  5814.3 1730.47
#Mann=9,-1,0
  4443.0   0.035       0  4592.4   0.045       0  4799.4    0.07       0
  4884.3   0.045       0  5007.1   0.045       0  5011.3   0.045       0
  5137.0   0.035       0  5321.2    0.07       0  5538.5   0.035       0
Bank Sta=5007.1,5011.3
Exp/Cntr=0.3,0.1

Type RM Length L Ch R = 1,5442,201,201,201
BEGIN DESCRIPTION:
Mapping XS 948ea401
END DESCRIPTION:
XS GIS Cut Line= 4
      1535698.00      6925006.57      1535252.65      6924925.83
      1534804.74      6924928.44      1534494.87      6924920.63
#Sta/Elev= 30
  4436.7 1731.67  4455.9 1731.76  4470.2 1730.89  4500.7 1730.47  4521.1 1728.91
  4561.7 1727.44  4704.0 1723.78  4738.3 1723.30  4805.6 1724.41  4856.4 1721.15
  4897.0 1720.80  4977.0 1716.66  5014.9 1716.37  5044.9 1716.08  5045.1 1715.58
  5048.8 1715.58  5049.1 1716.08  5077.0 1717.34  5097.0 1716.68  5117.0 1717.33
  5217.0 1722.90  5267.0 1723.85  5357.0 1723.87  5447.0 1725.69  5467.0 1726.85
  5552.5 1728.25  5587.0 1730.12  5607.1 1729.58  5627.1 1730.40  5647.2 1729.08
#Mann=4,-1,0
  4436.7   0.045       0  5014.9   0.035       0  5044.9   0.045       0
  5049.1   0.035       0
Bank Sta=5044.9,5049.1
Exp/Cntr=0.3,0.1

Type RM Length L Ch R = 1,5241,213,213,213
BEGIN DESCRIPTION:
Mapping XS 33ee08bc
END DESCRIPTION:
XS GIS Cut Line= 2
      1535713.56      6924821.66      1534765.63      6924699.27
#Sta/Elev= 30
  4436.6 1727.08  4495.6 1726.37  4507.5 1725.65  4566.2 1724.97  4596.5 1723.86
  4646.9 1723.02  4687.2 1722.70  4757.8 1723.12  4808.2 1720.74  4820.0 1719.56
  4858.6 1717.61  4899.4 1717.10  4909.1 1716.24  4991.5 1714.01  5009.9 1713.67
  5060.3 1714.87  5070.4 1714.02  5080.5 1713.89  5110.7 1713.51  5127.4 1714.28
  5161.8 1713.57  5169.1 1713.46  5169.4 1712.96  5173.1 1712.96  5173.3 1713.46
  5191.4 1713.96  5231.7 1718.65  5272.0 1721.92  5342.6 1722.47  5392.4 1724.47
#Mann=5,-1,0
  4436.6   0.045       0  4991.5   0.035       0  5161.8   0.045       0
  5169.1   0.035       0  5173.3   0.045       0
Bank Sta=5169.1,5173.3
Exp/Cntr=0.3,0.1

Type RM Length L Ch R = 1,5028,282,282,282
BEGIN DESCRIPTION:
Mapping XS 14449bdf
END DESCRIPTION:
XS GIS Cut Line= 3
      1535804.72      6924681.04      1535078.17      6924540.42
      1534815.14      6924615.94
#Sta/Elev= 30
  4439.3 1724.06  4478.1 1724.47  4489.9 1724.03  4520.5 1724.70  4586.8 1724.04
  4695.4 1721.57  4724.2 1721.57  4793.4 1719.61  4856.6 1717.11  4897.4 1716.21
  4907.6 1715.18  4948.3 1714.38  4978.9 1711.58  5027.7 1710.85  5027.9 1710.35
  5031.6 1710.35  5031.9 1710.85  5070.5 1714.36  5090.9 1717.09  5109.6 1717.43
  5121.5 1719.17  5141.8 1718.50  5166.5 1719.94  5222.0 1721.44  5232.8 1721.27
  5255.5 1721.04  5276.3 1721.80  5328.3 1721.23  5372.5 1722.09  5453.0 1721.42
#Mann=5,-1,0
  4439.3   0.045       0  4793.4   0.035       0  5027.7   0.035       0
  5031.9   0.035       0  5232.8   0.045       0
Bank Sta=5027.7,5031.9
Exp/Cntr=0.3,0.1

Type RM Length L Ch R = 1,4746,327,327,327
BEGIN DESCRIPTION:
Mapping XS 80e073d4
END DESCRIPTION:
XS GIS Cut Line= 3
      1535885.49      6924391.98      1535156.30      6924298.23
      1534804.72      6924571.68
#Sta/Elev= 30
  4464.5 1722.62  4475.1 1723.34  4495.2 1723.36  4525.5 1722.53  4532.7 1722.71
  4537.8 1723.75  4545.7 1722.68  4626.3 1723.53  4717.1 1722.55  4766.3 1720.56
  4771.3 1720.86  4845.8 1715.98  4930.4 1711.43  4997.2 1709.88  4997.5 1709.38
  5001.2 1709.38  5001.5 1709.88  5019.5 1710.07  5079.4 1714.59  5140.5 1717.09
  5207.6 1716.77  5257.3 1717.54  5300.8 1716.61  5320.6 1717.51  5378.7 1718.17
  5435.6 1719.71  5470.9 1719.09  5543.3 1719.93  5593.1 1721.28  5645.1 1720.83
#Mann=4,-1,0
  4464.5   0.035       0  4997.2   0.035       0  5001.5   0.035       0
  5320.6   0.045       0
Bank Sta=4997.2,5001.5
Exp/Cntr=0.3,0.1

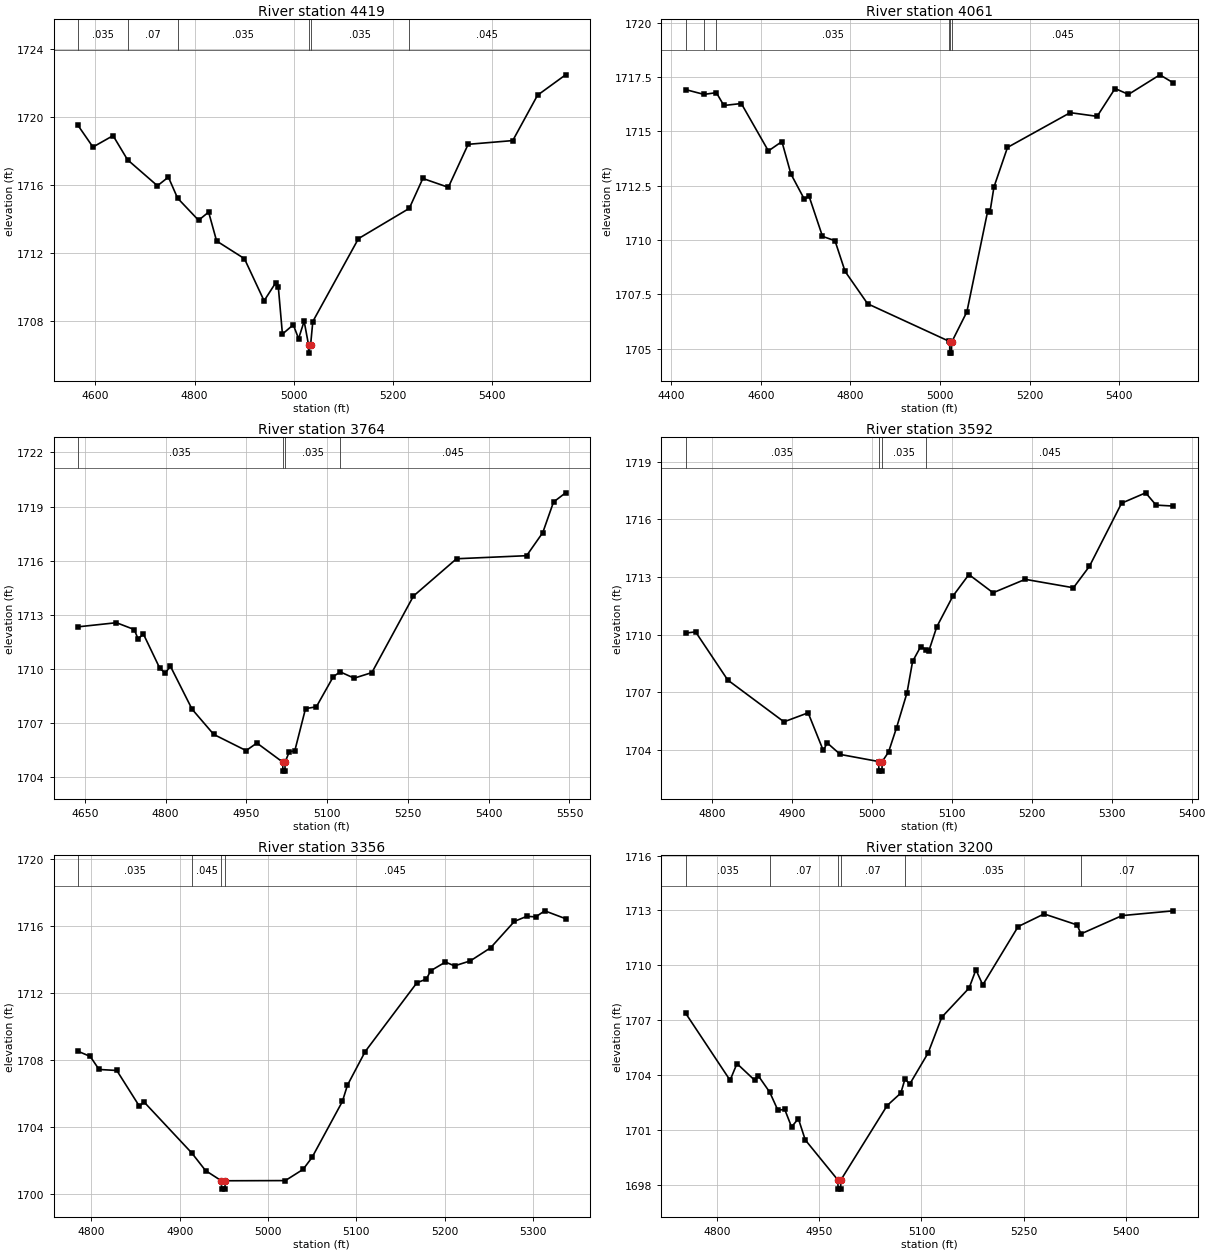
Type RM Length L Ch R = 1,4419,358,358,358
BEGIN DESCRIPTION:
Mapping XS 226ace03
END DESCRIPTION:
XS GIS Cut Line= 4
      1535744.83      6923905.00      1535429.74      6923959.69
      1535085.99      6924113.33      1534798.43      6924115.92
#Sta/Elev= 30
  4564.7 1719.49  4595.0 1718.21  4635.6 1718.88  4664.8 1717.46  4725.1 1715.93
  4747.2 1716.44  4765.8 1715.20  4808.1 1713.90  4828.4 1714.38  4844.5 1712.68
  4900.6 1711.64  4940.3 1709.16  4963.5 1710.21  4969.0 1709.97  4977.3 1707.20
  4999.2 1707.75  5009.9 1706.93  5021.1 1707.96  5029.9 1706.58  5030.2 1706.08
  5034.2 1706.58  5038.6 1707.94  5130.7 1712.82  5233.2 1714.60  5260.6 1716.36
  5312.0 1715.84  5352.0 1718.37  5442.0 1718.59  5492.0 1721.26  5548.6 1722.46
#Mann=6,-1,0
  4564.7   0.035       0  4664.8    0.07       0  4765.8   0.035       0
  5029.9   0.035       0  5034.2   0.035       0  5233.2   0.045       0
Bank Sta=5029.9,5034.2
Exp/Cntr=0.3,0.1

Type RM Length L Ch R = 1,4061,297,297,297
BEGIN DESCRIPTION:
Mapping XS 54b4948f
END DESCRIPTION:
XS GIS Cut Line= 3
      1535768.30      6923782.61      1535044.32      6923696.67
      1534684.92      6923701.88
#Sta/Elev= 30
  4432.5 1716.92  4473.2 1716.70  4501.0 1716.78  4517.7 1716.19  4556.7 1716.28
  4617.1 1714.10  4647.3 1714.53  4667.4 1713.04  4697.6 1711.87  4707.7 1712.03
  4737.9 1710.17  4765.8 1709.97  4788.3 1708.56  4838.6 1707.07  5021.0 1705.34
  5021.8 1705.30  5022.1 1704.80  5025.8 1704.80  5026.1 1705.30  5060.2 1706.70
  5106.7 1711.34  5111.7 1711.29  5120.6 1712.44  5150.8 1714.26  5290.9 1715.86
  5350.9 1715.69  5390.9 1716.97  5420.9 1716.70  5490.9 1717.60  5521.0 1717.23
#Mann=6,-1,0
  4432.5   0.035       0  4473.2    0.07       0  4501.0   0.035       0
  5021.0   0.045       0  5021.8   0.035       0  5026.1   0.045       0
Bank Sta=5021.8,5026.1
Exp/Cntr=0.3,0.1

Type RM Length L Ch R = 1,3764,172,172,172
BEGIN DESCRIPTION:
Mapping XS ceddb0b6
END DESCRIPTION:
XS GIS Cut Line= 3
      1535716.22      6923501.36      1535174.53      6923457.08
      1534812.56      6923462.29
#Sta/Elev= 30
  4637.3 1712.32  4708.8 1712.55  4741.9 1712.17  4748.9 1711.65  4758.9 1711.92
  4789.0 1710.04  4799.1 1709.75  4809.1 1710.13  4849.2 1707.75  4889.4 1706.35
  4949.6 1705.45  4969.6 1705.87  5017.6 1704.81  5017.9 1704.31  5021.7 1704.31
  5022.0 1704.81  5029.8 1705.39  5039.9 1705.43  5059.9 1707.78  5080.0 1707.88
  5111.6 1709.56  5124.3 1709.82  5150.2 1709.47  5183.1 1709.78  5260.3 1714.03
  5340.3 1716.10  5470.4 1716.27  5500.4 1717.55  5520.4 1719.25  5542.8 1719.76
#Mann=4,-1,0
  4637.3   0.035       0  5017.6   0.035       0  5022.0   0.035       0
  5124.3   0.045       0
Bank Sta=5017.6,5022
Exp/Cntr=0.3,0.1

Type RM Length L Ch R = 1,3592,236,236,236
BEGIN DESCRIPTION:
Mapping XS e7ec7d92
END DESCRIPTION:
XS GIS Cut Line= 3
      1535557.29      6923285.21      1535096.40      6923332.08
      1534950.55      6923345.11
#Sta/Elev= 30
  4767.4 1710.08  4779.8 1710.14  4820.0 1707.63  4890.3 1705.45  4920.5 1705.92
  4939.4 1703.96  4944.4 1704.35  4960.7 1703.75  5008.7 1703.38  5009.0 1702.88
  5012.8 1702.88  5013.1 1703.38  5021.0 1703.87  5031.0 1705.14  5044.1 1706.96
  5051.1 1708.60  5061.2 1709.37  5068.1 1709.21  5071.3 1709.13  5081.3 1710.40
  5101.4 1712.00  5121.5 1713.13  5151.7 1712.18  5191.9 1712.88  5252.2 1712.44
  5272.2 1713.56  5312.4 1716.85  5342.5 1717.39  5355.5 1716.75  5377.1 1716.70
#Mann=4,-1,0
  4767.4   0.035       0  5008.7   0.035       0  5013.1   0.035       0
  5068.1   0.045       0
Bank Sta=5008.7,5013.1
Exp/Cntr=0.3,0.1

Type RM Length L Ch R = 1,3356,156,156,156
BEGIN DESCRIPTION:
Mapping XS 245aa8e3
END DESCRIPTION:
XS GIS Cut Line= 3
      1535468.84      6923076.87      1535083.38      6923110.73
      1534921.93      6923144.58
#Sta/Elev= 30
  4784.9 1708.51  4798.8 1708.20  4808.8 1707.42  4828.9 1707.36  4854.5 1705.22
  4859.5 1705.49  4913.9 1702.42  4929.3 1701.38  4947.2 1700.77  4947.5 1700.27
  4951.3 1700.27  4951.6 1700.77  5019.6 1700.78  5039.7 1701.45  5049.8 1702.16
  5084.2 1705.51  5089.9 1706.48  5110.0 1708.49  5168.5 1712.60  5179.1 1712.82
  5184.2 1713.32  5200.8 1713.84  5211.1 1713.61  5229.0 1713.91  5251.9 1714.69
  5278.9 1716.27  5292.8 1716.57  5303.0 1716.54  5313.2 1716.90  5336.8 1716.43
#Mann=4,-1,0
  4784.9   0.035       0  4913.9   0.045       0  4947.2   0.045       0
  4951.6   0.045       0
Bank Sta=4947.2,4951.6
Exp/Cntr=0.3,0.1

Type RM Length L Ch R = 1,3200,220,220,220
BEGIN DESCRIPTION:
Mapping XS b7f9b0cc
END DESCRIPTION:
XS GIS Cut Line= 3
      1535500.08      6922928.44      1535033.90      6922949.27
      1534791.74      6923003.95
#Sta/Elev= 30
  4754.3 1707.38  4819.4 1703.72  4829.5 1704.63  4855.5 1703.72  4860.5 1703.98
  4877.5 1703.07  4889.5 1702.08  4899.5 1702.13  4909.5 1701.17  4919.5 1701.62
  4929.6 1700.46  4977.4 1698.27  4977.7 1697.77  4981.5 1697.77  4981.8 1698.27
  5049.7 1702.34  5069.7 1703.02  5075.9 1703.80  5082.6 1703.50  5109.7 1705.21
  5129.8 1707.17  5169.8 1708.76  5179.8 1709.76  5189.8 1708.93  5241.7 1712.12
  5279.7 1712.81  5328.1 1712.21  5333.8 1711.72  5394.1 1712.72  5469.2 1712.98
#Mann=6,-1,0
  4754.3   0.035       0  4877.5    0.07       0  4977.4    0.07       0
  4981.8    0.07       0  5075.9   0.035       0  5333.8    0.07       0
Bank Sta=4977.4,4981.8
Exp/Cntr=0.3,0.1

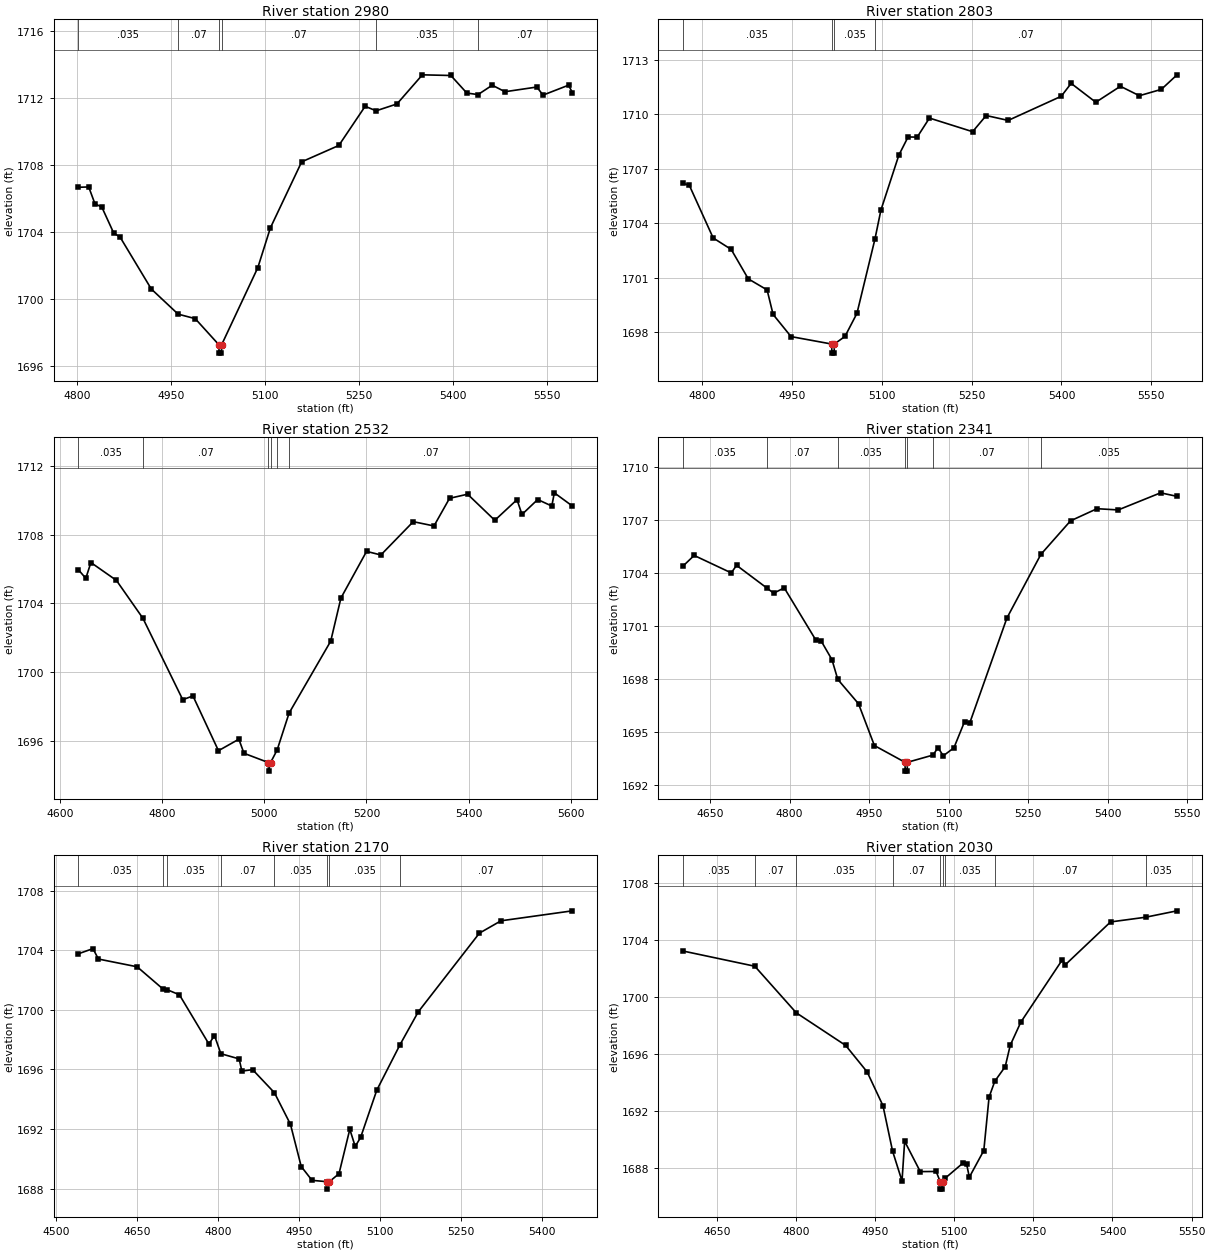
Type RM Length L Ch R = 1,2980,177,177,177
BEGIN DESCRIPTION:
Mapping XS 38d77eb7
END DESCRIPTION:
XS GIS Cut Line= 3
      1535541.70      6922753.96      1535177.13      6922743.54
      1534758.92      6922816.27
#Sta/Elev= 30
  4801.9 1706.66  4818.6 1706.68  4828.6 1705.67  4839.5 1705.48  4858.6 1703.92
  4868.6 1703.69  4918.6 1700.58  4961.4 1699.08  4988.7 1698.81  5026.5 1697.25
  5026.8 1696.75  5030.6 1696.75  5030.9 1697.25  5088.7 1701.86  5108.7 1704.23
  5158.7 1708.18  5218.1 1709.16  5260.1 1711.50  5277.6 1711.23  5310.9 1711.64
  5351.5 1713.38  5397.0 1713.34  5422.5 1712.29  5440.4 1712.20  5463.1 1712.76
  5483.4 1712.37  5534.2 1712.65  5544.3 1712.17  5584.9 1712.76  5591.1 1712.32
#Mann=6,-1,0
  4801.9   0.035       0  4961.4    0.07       0  5026.5    0.07       0
  5030.9    0.07       0  5277.6   0.035       0  5440.4    0.07       0
Bank Sta=5026.5,5030.9
Exp/Cntr=0.3,0.1

Type RM Length L Ch R = 1,2803,271,271,271
BEGIN DESCRIPTION:
Mapping XS 440f28ad
END DESCRIPTION:
XS GIS Cut Line= 3
      1535575.61      6922569.06      1535203.17      6922582.08
      1534763.10      6922688.85
#Sta/Elev= 30
  4767.5 1706.19  4778.1 1706.10  4818.1 1703.19  4848.2 1702.56  4876.7 1700.94
  4908.2 1700.33  4918.2 1698.98  4948.2 1697.76  5016.1 1697.35  5016.4 1696.85
  5020.2 1696.85  5020.5 1697.35  5038.3 1697.77  5058.3 1699.04  5088.3 1703.12
  5098.3 1704.72  5128.3 1707.75  5143.7 1708.75  5158.9 1708.74  5179.4 1709.79
  5251.5 1709.04  5274.2 1709.93  5310.9 1709.66  5399.6 1710.99  5416.1 1711.70
  5457.3 1710.66  5498.4 1711.54  5530.1 1711.02  5566.8 1711.37  5593.0 1712.17
#Mann=4,-1,0
  4767.5   0.035       0  5016.1   0.035       0  5020.5   0.035       0
  5088.3    0.07       0
Bank Sta=5016.1,5020.5
Exp/Cntr=0.3,0.1

Type RM Length L Ch R = 1,2532,191,191,191
BEGIN DESCRIPTION:
Mapping XS c08ccc17
END DESCRIPTION:
XS GIS Cut Line= 3
      1535619.82      6922334.69      1535070.36      6922334.69
      1534658.12      6922409.88
#Sta/Elev= 30
  4635.1 1705.97  4649.9 1705.46  4659.9 1706.38  4709.9 1705.34  4761.9 1703.13
  4839.9 1698.39  4859.9 1698.61  4909.9 1695.42  4949.9 1696.09  4959.9 1695.27
  5007.7 1694.73  5008.0 1694.23  5012.1 1694.73  5025.0 1695.47  5048.3 1697.61
  5129.9 1701.80  5149.9 1704.31  5200.2 1707.03  5228.2 1706.82  5291.7 1708.76
  5332.3 1708.51  5362.8 1710.12  5398.2 1710.36  5451.5 1708.84  5495.0 1710.04
  5504.8 1709.18  5535.6 1710.05  5563.2 1709.67  5568.2 1710.44  5603.6 1709.67
#Mann=6,-1,0
  4635.1   0.035       0  4761.9    0.07       0  5007.7    0.07       0
  5012.1    0.07       0  5025.0   0.035       0  5048.3    0.07       0
Bank Sta=5007.7,5012.1
Exp/Cntr=0.3,0.1

Type RM Length L Ch R = 1,2341,171,171,171
BEGIN DESCRIPTION:
Mapping XS a9b89a77
END DESCRIPTION:
XS GIS Cut Line= 2
      1535656.32      6922149.79      1534724.01      6922136.77
#Sta/Elev= 30
  4598.7 1704.38  4620.0 1704.99  4690.0 1704.00  4700.0 1704.43  4756.8 1703.15
  4770.0 1702.85  4790.0 1703.15  4850.0 1700.17  4860.0 1700.12  4880.0 1699.08
  4891.0 1697.96  4930.1 1696.58  4960.1 1694.21  5017.9 1693.26  5018.2 1692.76
  5022.0 1692.76  5022.3 1693.26  5070.6 1693.67  5080.1 1694.09  5090.1 1693.63
  5110.1 1694.08  5130.1 1695.56  5140.1 1695.50  5210.1 1701.44  5274.2 1705.05
  5330.1 1706.95  5380.1 1707.64  5420.1 1707.57  5500.1 1708.54  5531.1 1708.34
#Mann=7,-1,0
  4598.7   0.035       0  4756.8    0.07       0  4891.0   0.035       0
  5017.9   0.035       0  5022.3   0.035       0  5070.6    0.07       0
  5274.2   0.035       0
Bank Sta=5017.9,5022.3
Exp/Cntr=0.3,0.1

Type RM Length L Ch R = 1,2170,140,140,140
BEGIN DESCRIPTION:
Mapping XS 7b7355b6
END DESCRIPTION:
XS GIS Cut Line= 4
      1535661.54      6922053.44      1535388.07      6921993.54
      1535036.51      6921983.13      1534752.69      6921985.73
#Sta/Elev= 30
  4541.3 1703.77  4568.5 1704.12  4578.7 1703.42  4650.4 1702.90  4698.8 1701.39
  4706.0 1701.36  4728.7 1701.02  4783.4 1697.71  4793.7 1698.28  4805.5 1697.06
  4839.4 1696.71  4844.4 1695.89  4864.3 1695.99  4904.7 1694.44  4934.4 1692.32
  4954.4 1689.48  4974.4 1688.55  5002.2 1688.46  5002.5 1687.96  5006.6 1688.46
  5024.4 1689.00  5044.4 1691.98  5054.4 1690.83  5064.4 1691.43  5094.4 1694.61
  5137.5 1697.67  5171.2 1699.87  5284.5 1705.16  5324.5 1705.99  5456.8 1706.66
#Mann=8,-1,0
  4541.3   0.035       0  4698.8    0.07       0  4706.0   0.035       0
  4805.5    0.07       0  4904.7   0.035       0  5002.2   0.035       0
  5006.6   0.035       0  5137.5    0.07       0
Bank Sta=5002.2,5006.6
Exp/Cntr=0.3,0.1

Type RM Length L Ch R = 1,2030,62,62,62
BEGIN DESCRIPTION:
Mapping XS 25bacf18
END DESCRIPTION:
XS GIS Cut Line= 5
      1535692.79      6921996.16      1535468.80      6921928.44
      1535247.45      6921897.19      1535099.01      6921907.60
      1534769.11      6921894.62
#Sta/Elev= 30
  4585.8 1703.22  4722.1 1702.15  4800.7 1698.88  4894.3 1696.59  4935.0 1694.73
  4965.0 1692.36  4983.2 1689.17  5001.1 1687.07  5006.1 1689.86  5035.7 1687.73
  5065.8 1687.74  5073.7 1687.00  5074.0 1686.50  5077.8 1686.50  5078.1 1687.00
  5082.7 1687.26  5116.0 1688.31  5123.7 1688.23  5128.7 1687.34  5156.1 1689.21
  5166.1 1692.96  5177.0 1694.08  5196.7 1695.10  5206.2 1696.60  5226.2 1698.22
  5305.2 1702.62  5310.2 1702.24  5396.3 1705.26  5462.6 1705.59  5522.3 1706.04
#Mann=9,-1,0
  4585.8   0.035       0  4722.1    0.07       0  4800.7   0.035       0
  4983.2    0.07       0  5073.7    0.07       0  5078.1    0.07       0
  5082.7   0.035       0  5177.0    0.07       0  5462.6   0.035       0
Bank Sta=5073.7,5078.1
Exp/Cntr=0.3,0.1

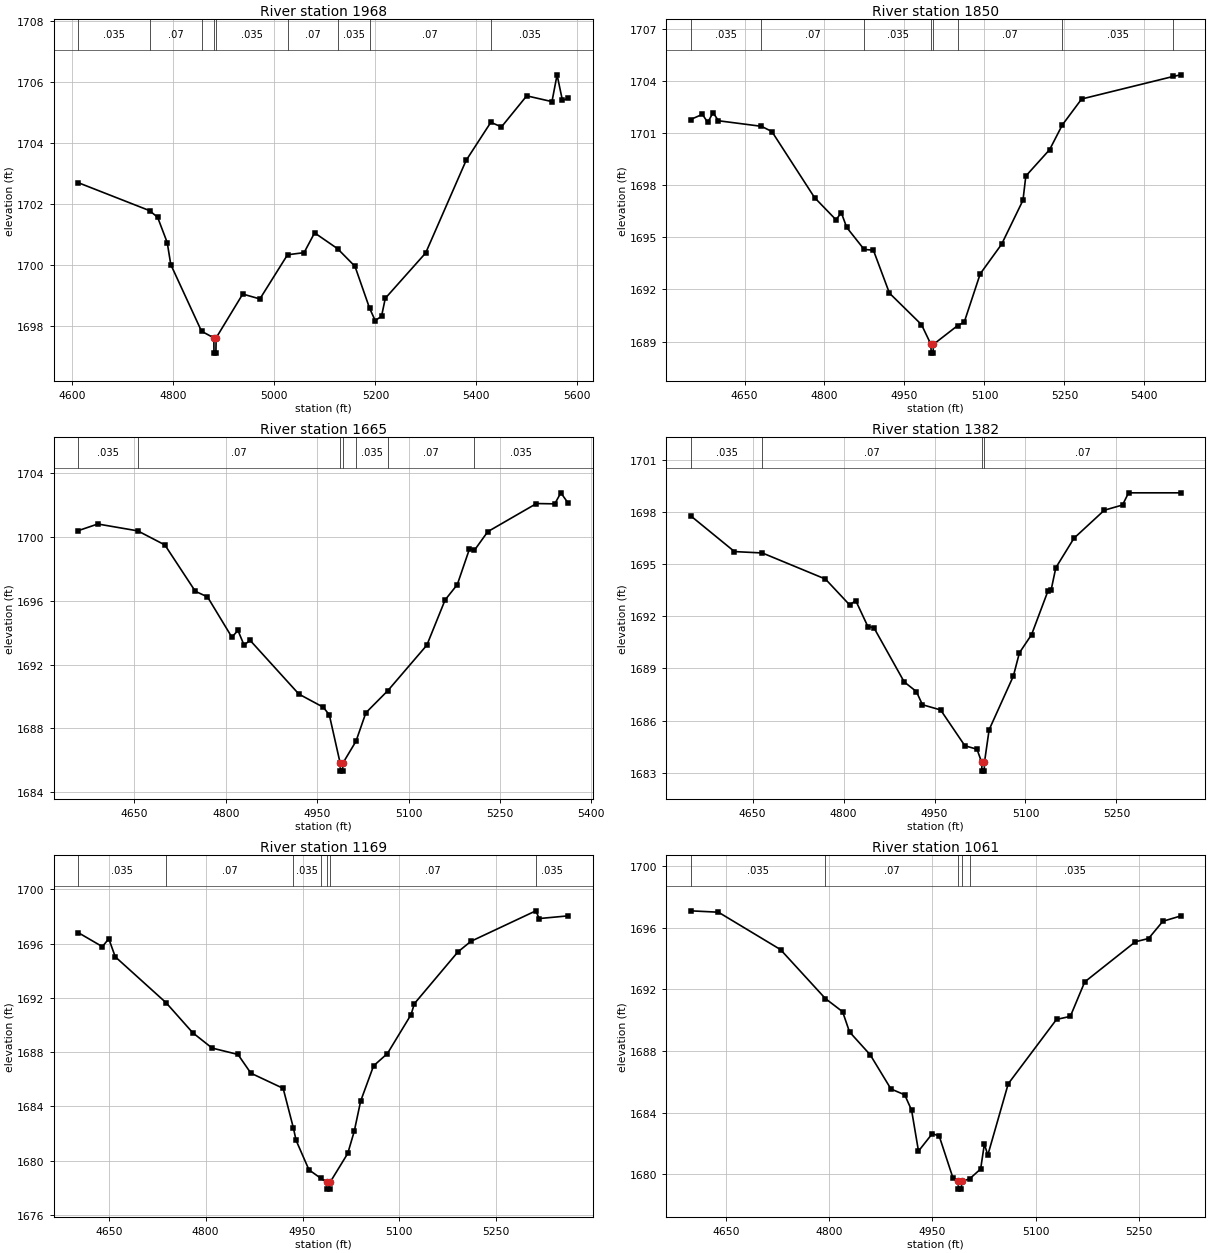
Type RM Length L Ch R = 1,1968,118,118,118
BEGIN DESCRIPTION:
Mapping XS 2d82ed0b
END DESCRIPTION:
XS GIS Cut Line= 6
      1535718.80      6921915.42      1535567.76      6921886.77
      1535270.88      6921852.92      1535122.45      6921850.31
      1535005.26      6921850.31      1534752.66      6921842.50
#Sta/Elev= 30
  4611.2 1702.70  4752.8 1701.78  4768.8 1701.56  4787.8 1700.73  4794.8 1700.01
  4855.7 1697.82  4880.1 1697.60  4880.4 1697.10  4884.2 1697.10  4884.6 1697.60
  4937.3 1699.04  4971.3 1698.88  5026.0 1700.33  5058.8 1700.40  5079.6 1701.05
  5125.1 1700.53  5159.6 1699.95  5188.4 1698.58  5199.6 1698.17  5212.2 1698.31
  5219.6 1698.90  5299.6 1700.39  5379.7 1703.43  5428.6 1704.68  5449.7 1704.53
  5499.7 1705.55  5549.7 1705.36  5559.8 1706.24  5570.4 1705.40  5582.1 1705.47
#Mann=9,-1,0
  4611.2   0.035       0  4752.8    0.07       0  4855.7   0.035       0
  4880.1   0.035       0  4884.6   0.035       0  5026.0    0.07       0
  5125.1   0.035       0  5188.4    0.07       0  5428.6   0.035       0
Bank Sta=4880.1,4884.6
Exp/Cntr=0.3,0.1

Type RM Length L Ch R = 1,1850,185,185,185
BEGIN DESCRIPTION:
Mapping XS 8bb2ad58
END DESCRIPTION:
XS GIS Cut Line= 4
      1535737.02      6921800.83      1535351.61      6921774.79
      1535109.42      6921759.17      1534818.85      6921764.36
#Sta/Elev= 30
  4548.9 1701.77  4571.0 1702.07  4581.0 1701.60  4591.0 1702.17  4601.0 1701.70
  4681.7 1701.38  4701.3 1701.08  4781.4 1697.28  4821.5 1696.01  4831.6 1696.41
  4841.6 1695.57  4874.4 1694.30  4891.7 1694.26  4921.8 1691.79  4981.9 1689.98
  4999.7 1688.84  5000.0 1688.34  5003.8 1688.34  5004.2 1688.84  5049.6 1689.92
  5062.1 1690.12  5092.1 1692.90  5132.2 1694.60  5172.3 1697.13  5177.6 1698.52
  5222.3 1700.04  5246.1 1701.46  5282.3 1702.95  5454.5 1704.25  5468.5 1704.34
#Mann=8,-1,0
  4548.9   0.035       0  4681.7    0.07       0  4874.4   0.035       0
  4999.7   0.035       0  5004.2   0.035       0  5049.6    0.07       0
  5246.1   0.035       0  5454.5    0.07       0
Bank Sta=4999.7,5004.2
Exp/Cntr=0.3,0.1

Type RM Length L Ch R = 1,1665,283,283,283
BEGIN DESCRIPTION:
Mapping XS 65271ddf
END DESCRIPTION:
XS GIS Cut Line= 2
      1535747.42      6921618.54      1534942.73      6921600.31
#Sta/Elev= 30
  4557.4 1700.37  4589.8 1700.79  4655.4 1700.36  4699.9 1699.48  4749.9 1696.58
  4769.9 1696.23  4809.9 1693.71  4819.9 1694.13  4829.9 1693.22  4839.9 1693.51
  4919.9 1690.15  4959.9 1689.33  4969.9 1688.85  4987.7 1685.83  4988.0 1685.33
  4991.8 1685.33  4992.2 1685.83  5013.7 1687.20  5029.9 1688.98  5066.1 1690.37
  5130.0 1693.21  5160.0 1696.04  5180.0 1697.00  5200.0 1699.23  5208.2 1699.15
  5230.0 1700.31  5310.0 1702.07  5340.0 1702.05  5350.0 1702.74  5362.3 1702.08
#Mann=7,-1,0
  4557.4   0.035       0  4655.4    0.07       0  4987.7    0.07       0
  4992.2    0.07       0  5013.7   0.035       0  5066.1    0.07       0
  5208.2   0.035       0
Bank Sta=4987.7,4992.2
Exp/Cntr=0.3,0.1

Type RM Length L Ch R = 1,1382,213,213,213
BEGIN DESCRIPTION:
Mapping XS 4b9fca36
END DESCRIPTION:
XS GIS Cut Line= 2
      1535807.31      6921337.29      1534998.74      6921345.09
#Sta/Elev= 30
  4547.7 1697.78  4620.0 1695.72  4666.0 1695.64  4770.0 1694.14  4810.0 1692.65
  4820.0 1692.90  4840.0 1691.41  4850.0 1691.34  4900.0 1688.22  4920.0 1687.67
  4930.0 1686.91  4960.0 1686.61  5000.0 1684.55  5020.0 1684.35  5027.8 1683.59
  5028.1 1683.09  5032.0 1683.09  5032.3 1683.59  5040.0 1685.47  5080.0 1688.56
  5090.0 1689.90  5110.0 1690.94  5137.2 1693.47  5142.2 1693.50  5150.0 1694.79
  5180.0 1696.49  5230.0 1698.10  5260.0 1698.40  5270.0 1699.10  5356.3 1699.10
#Mann=4,-1,0
  4547.7   0.035       0  4666.0    0.07       0  5027.8    0.07       0
  5032.3    0.07       0
Bank Sta=5027.8,5032.3
Exp/Cntr=0.3,0.1

Type RM Length L Ch R = 1,1169,108,108,108
BEGIN DESCRIPTION:
Mapping XS 7b3fd1ed
END DESCRIPTION:
XS GIS Cut Line= 3
      1535752.60      6921126.36      1535273.49      6921128.96
      1534994.88      6921157.60
#Sta/Elev= 30
  4602.4 1696.81  4640.0 1695.77  4650.0 1696.35  4660.0 1695.02  4738.8 1691.63
  4780.0 1689.42  4810.0 1688.29  4850.0 1687.82  4870.0 1686.44  4920.0 1685.32
  4935.9 1682.39  4940.0 1681.49  4960.0 1679.31  4978.3 1678.69  4987.5 1678.39
  4987.9 1677.89  4992.2 1677.89  4992.6 1678.39  5020.0 1680.52  5030.0 1682.14
  5040.0 1684.38  5060.0 1686.98  5081.5 1687.89  5118.1 1690.76  5123.1 1691.56
  5190.6 1695.38  5210.7 1696.16  5311.3 1698.41  5316.4 1697.84  5361.6 1698.04
#Mann=7,-1,0
  4602.4   0.035       0  4738.8    0.07       0  4935.9   0.035       0
  4978.3    0.07       0  4987.5    0.07       0  4992.6    0.07       0
  5311.3   0.035       0
Bank Sta=4987.5,4992.6
Exp/Cntr=0.3,0.1

Type RM Length L Ch R = 1,1061,233,233,233
BEGIN DESCRIPTION:
Mapping XS a7ab4471
END DESCRIPTION:
XS GIS Cut Line= 3
      1535755.26      6920993.54      1535190.15      6921032.60
      1535049.72      6921071.61
#Sta/Elev= 30
  4598.8 1697.11  4639.2 1697.02  4729.4 1694.59  4794.5 1691.41  4819.6 1690.55
  4829.6 1689.24  4859.7 1687.75  4889.8 1685.53  4909.8 1685.15  4919.8 1684.15
  4929.8 1681.49  4949.9 1682.63  4959.9 1682.47  4980.0 1679.73  4987.4 1679.52
  4987.8 1679.02  4992.1 1679.02  4992.5 1679.52  5004.1 1679.69  5020.1 1680.33
  5025.5 1681.95  5030.5 1681.23  5060.2 1685.87  5130.3 1690.05  5150.4 1690.25
  5171.3 1692.49  5244.9 1695.10  5264.0 1695.31  5284.8 1696.43  5311.0 1696.78
#Mann=5,-1,0
  4598.8   0.035       0  4794.5    0.07       0  4987.4    0.07       0
  4992.5    0.07       0  5004.1   0.035       0
Bank Sta=4987.4,4992.5
Exp/Cntr=0.3,0.1