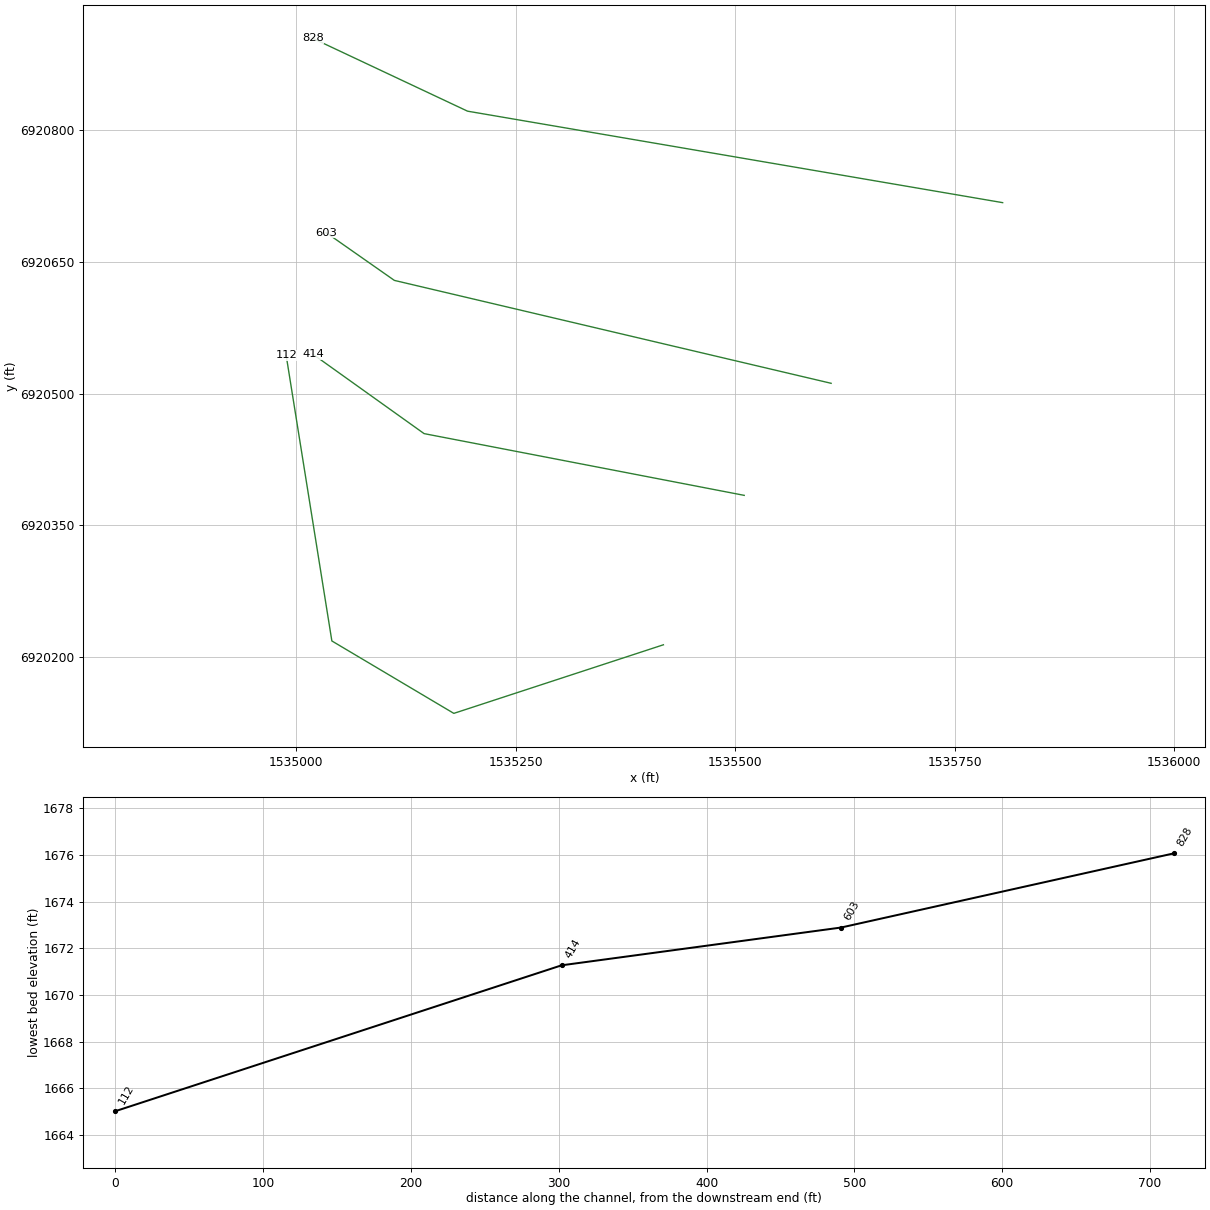
HEC-RAS study NC Unknown Stream 99.prj: NC Unknown Stream 99 Base Level Engineering

--- NC Unknown Stream 99.g01 (geometry) --- (continued)

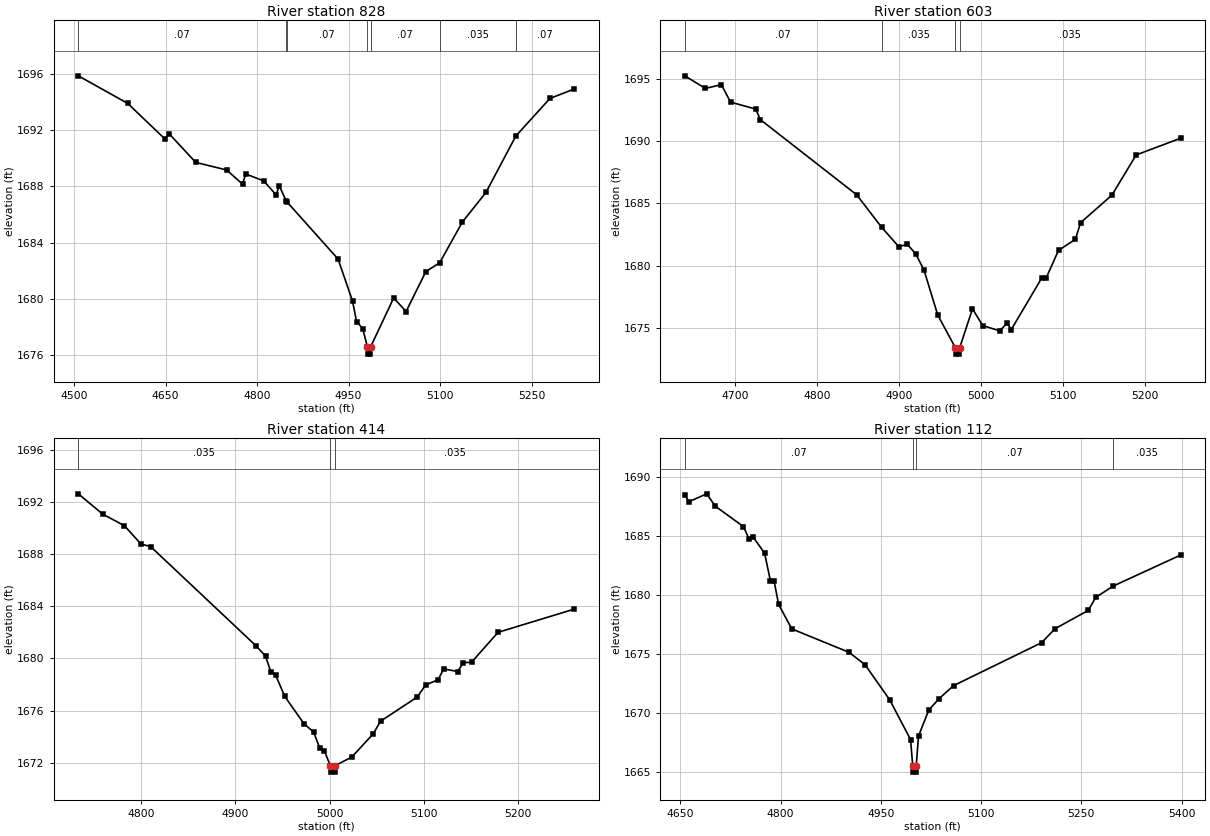
Type RM Length L Ch R = 1,828,225,225,225
BEGIN DESCRIPTION:
Mapping XS d26b4742
END DESCRIPTION:
XS GIS Cut Line= 3
      1535804.72      6920717.50      1535195.36      6920821.67
      1535019.10      6920904.61
#Sta/Elev= 30
  4506.9 1695.87  4587.8 1693.91  4648.6 1691.39  4656.0 1691.74  4699.4 1689.71
  4750.1 1689.17  4776.2 1688.16  4781.3 1688.89  4811.0 1688.39  4831.2 1687.40
  4836.3 1688.05  4847.5 1686.99  4848.8 1686.91  4932.7 1682.84  4956.5 1679.85
  4963.1 1678.39  4973.3 1677.88  4980.9 1676.57  4981.3 1676.07  4985.6 1676.07
  4986.0 1676.57  5024.0 1680.07  5044.3 1679.10  5076.7 1681.94  5099.4 1682.57
  5136.5 1685.46  5175.2 1687.57  5224.3 1691.59  5280.2 1694.26  5319.9 1694.93
#Mann=7,-1,0
  4506.9    0.07       0  4847.5   0.035       0  4848.8    0.07       0
  4980.9    0.07       0  4986.0    0.07       0  5099.4   0.035       0
  5224.3    0.07       0
Bank Sta=4980.9,4986
Exp/Cntr=0.3,0.1

Type RM Length L Ch R = 1,603,189,189,189
BEGIN DESCRIPTION:
Mapping XS e3cac338
END DESCRIPTION:
XS GIS Cut Line= 3
      1535609.41      6920511.77      1535112.03      6920628.96
      1535034.37      6920683.32
#Sta/Elev= 30
  4638.1 1695.23  4663.2 1694.22  4682.8 1694.52  4694.0 1693.12  4724.8 1692.56
  4730.3 1691.72  4848.1 1685.68  4878.5 1683.08  4899.5 1681.52  4910.0 1681.70
  4920.0 1680.96  4930.3 1679.65  4947.2 1676.02  4968.8 1673.39  4969.2 1672.89
  4973.5 1672.89  4973.9 1673.39  4989.6 1676.52  5002.2 1675.18  5022.8 1674.76
  5031.9 1675.37  5037.0 1674.86  5074.1 1678.99  5079.4 1678.97  5094.7 1681.22
  5115.2 1682.10  5121.7 1683.44  5160.0 1685.66  5189.6 1688.88  5243.9 1690.22
#Mann=4,-1,0
  4638.1    0.07       0  4878.5   0.035       0  4968.8   0.035       0
  4973.9   0.035       0
Bank Sta=4968.8,4973.9
Exp/Cntr=0.3,0.1

Type RM Length L Ch R = 1,414,302,302,302
BEGIN DESCRIPTION:
Mapping XS 5e3a42d1
END DESCRIPTION:
XS GIS Cut Line= 3
      1535510.44      6920384.17      1535145.88      6920454.48
      1535019.16      6920544.99
#Sta/Elev= 30
  4733.0 1692.65  4758.9 1691.09  4782.0 1690.20  4799.6 1688.79  4809.8 1688.60
  4921.9 1680.97  4932.0 1680.18  4937.6 1678.96  4942.7 1678.72  4952.4 1677.09
  4972.8 1674.99  4983.0 1674.36  4989.4 1673.15  4994.5 1672.91  5000.8 1671.77
  5001.2 1671.27  5005.5 1671.27  5005.9 1671.77  5023.7 1672.43  5046.4 1674.21
  5054.2 1675.18  5093.2 1677.04  5102.2 1677.97  5115.2 1678.36  5121.4 1679.20
  5136.1 1679.00  5142.3 1679.68  5150.9 1679.71  5179.1 1682.01  5260.0 1683.79
#Mann=3,-1,0
  4733.0   0.035       0  5000.8   0.035       0  5005.9   0.035       0
Bank Sta=5000.8,5005.9
Exp/Cntr=0.3,0.1

Type RM Length L Ch R = 1,112,0,0,0
BEGIN DESCRIPTION:
NC Unknown Stream 99 1.0
END DESCRIPTION:
XS GIS Cut Line= 4
      1535418.43      6920214.02      1535179.74      6920135.90
      1535040.85      6920218.37      1534988.83      6920543.46
#Sta/Elev= 30
  4656.7 1688.52  4662.8 1687.93  4689.4 1688.60  4702.4 1687.55  4744.5 1685.82
  4753.1 1684.74  4758.4 1684.98  4776.1 1683.57  4784.9 1681.20  4790.2 1681.24
  4797.1 1679.22  4816.8 1677.15  4902.3 1675.17  4926.3 1674.12  4963.3 1671.14
  4994.5 1667.77  4997.8 1665.51  4998.1 1665.01  5002.5 1665.01  5002.9 1665.51
  5006.4 1668.06  5021.8 1670.28  5037.4 1671.25  5058.8 1672.34  5190.5 1675.98
  5210.8 1677.17  5260.5 1678.72  5271.5 1679.82  5297.7 1680.78  5398.6 1683.41
#Mann=4,-1,0
  4656.7    0.07       0  4997.8    0.07       0  5002.9    0.07       0
  5297.7   0.035       0
Bank Sta=4997.8,5002.9
Exp/Cntr=0.3,0.1

Chan Stop Cuts=-1