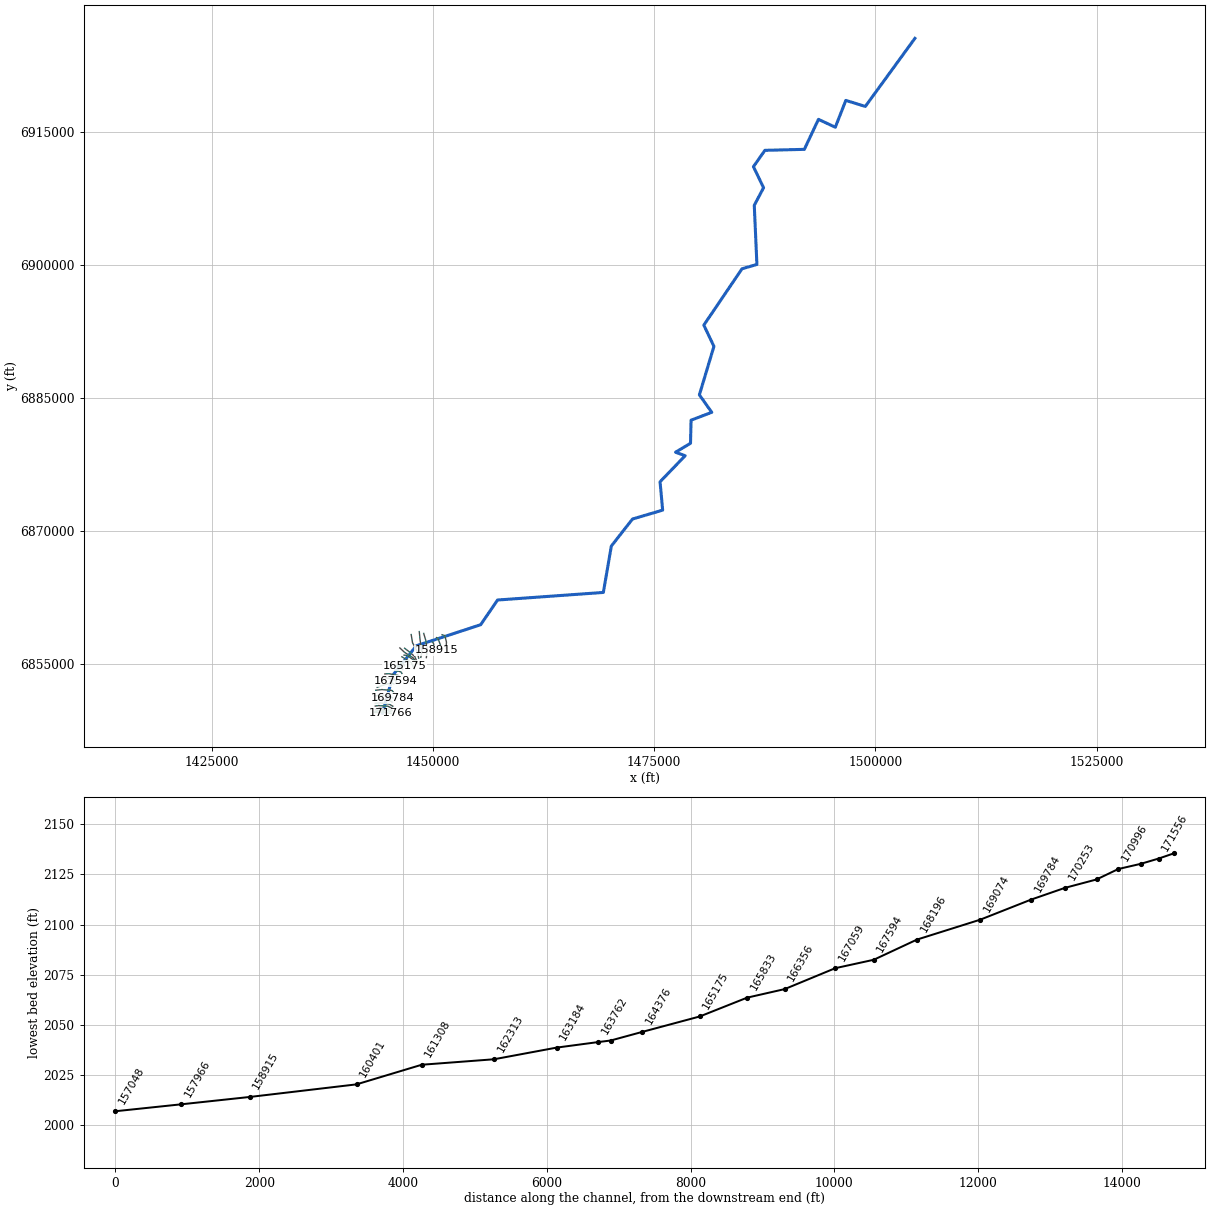
--- Noodle Creek.prj (project) ---

Proj Title=Noodle Creek Base Level Engineering
Current Plan=p01
Default Exp/Contr=0.3,0.1
English Units
Geom File=g01
Flow File=f01
Plan File=p01
Y Axis Title=Elevation
X Axis Title(PF)=Main Channel Distance
X Axis Title(XS)=Station
BEGIN DESCRIPTION:
Noodle Creek
END DESCRIPTION:
DSS Export Rating Curves= 0
DSS Export Rating Curve Sorted= 0
DSS Export Volume Flow Curves= 0
DXF OffsetX= 0
DXF OffsetY= 0
DXF ScaleX= 1
DXF ScaleY= 10

--- Noodle Creek.p01 (plan) ---

Plan Title=Multiple Run
Short Identifier=Multiple
Geom File=g01
Flow File=f01
Subcritical Flow
K Sum by GR= 0
Std Step Tol= 0.01
Critical Tol= 0.01
Num of Std Step Trials= 20
Max Error Tol= 0.3
Flow Tol Ratio= 0.001
Split Flow NTrial= 30
Split Flow Tol= 0.02
Split Flow Ratio= 0.02
Log Output Level= 0
Friction Slope Method= 1
Unsteady Friction Slope Method= 2
Unsteady Bridges Friction Slope Method= 1
Parabolic Critical Depth
Global Vel Dist=  1 , 1 , 1
Global Log Level= 0
CheckData=True
Encroach Param= -1, 0, 0, 0
BEGIN DESCRIPTION:
Multiple Run
END DESCRIPTION:

--- Noodle Creek.f01 (steady flow) ---

Flow Title=Multiple
Program Version=4.10
Number of Profiles= 7
Profile Names=10-year,25-year,50-year,1pct_min,100-year,1pct_plu,500-year
River Rch & RM=Noodle Creek,Reach-1         ,171766
     531     787    1012     647    1291    2576    2130
River Rch & RM=Noodle Creek,Reach-1         ,161308
     616     915    1177     752    1501    2995    2474
River Rch & RM=Noodle Creek,Reach-1         ,155670
     672     988    1265     803    1602    3197    2605
River Rch & RM=Noodle Creek,Reach-1         ,146743
     974    1445    1857    1183    2360    4708    3859
River Rch & RM=Noodle Creek,Reach-1         ,140602
    2198    3343    4374    2828    5643   11259    9511
River Rch & RM=Noodle Creek,Reach-1         ,131780
    2198    3343    4374    2828    5643   11259    9511
River Rch & RM=Noodle Creek,Reach-1         ,128889
    2198    3343    4374    2828    5643   11259    9511
River Rch & RM=Noodle Creek,Reach-1         ,123451
    2198    3343    4374    2828    5643   11259    9511
River Rch & RM=Noodle Creek,Reach-1         ,121501
    2200    3334    4351    2806    5598   11170    9384
River Rch & RM=Noodle Creek,Reach-1         ,119091
    2200    3334    4351    2806    5598   11170    9384
River Rch & RM=Noodle Creek,Reach-1         ,116742
    2308    3496    4561    2939    5865   11701    9818
River Rch & RM=Noodle Creek,Reach-1         ,111608
    2308    3496    4561    2939    5865   11701    9818
River Rch & RM=Noodle Creek,Reach-1         ,108762
    2265    3419    4449    2860    5705   11384    9501
River Rch & RM=Noodle Creek,Reach-1         ,103396
    3072    4662    6089    3925    7832   15627   13116
River Rch & RM=Noodle Creek,Reach-1         ,99604
    3072    4662    6089    3925    7832   15627   13116
River Rch & RM=Noodle Creek,Reach-1         ,89484
    3045    4612    6014    3871    7724   15411   12896
River Rch & RM=Noodle Creek,Reach-1         ,84844
    2995    4525    5890    3784    7551   15066   12560
River Rch & RM=Noodle Creek,Reach-1         ,80082
    3099    4676    6083    3904    7790   15543   12933
River Rch & RM=Noodle Creek,Reach-1         ,78120
    3099    4676    6083    3904    7790   15543   12933
River Rch & RM=Noodle Creek,Reach-1         ,74021
    3160    4763    6191    3971    7922   15807   13130
River Rch & RM=Noodle Creek,Reach-1         ,68361
    3185    4800    6239    4001    7983   15929   13228
River Rch & RM=Noodle Creek,Reach-1         ,65857
    3163    4758    6177    3956    7893   15748   13044
River Rch & RM=Noodle Creek,Reach-1         ,59909
    3166    4759    6176    3953    7888   15738   13023
River Rch & RM=Noodle Creek,Reach-1         ,54204
    3153    4734    6137    3925    7832   15626   12906
River Rch & RM=Noodle Creek,Reach-1         ,53118
    3136    4701    6088    3890    7761   15485   12761
River Rch & RM=Noodle Creek,Reach-1         ,45319
    3125    4682    6062    3871    7723   15410   12689
River Rch & RM=Noodle Creek,Reach-1         ,42726
    3309    4961    6425    4105    8190   16340   13463
River Rch & RM=Noodle Creek,Reach-1         ,41834
    3309    4961    6425    4105    8190   16340   13463
River Rch & RM=Noodle Creek,Reach-1         ,36147
    3335    5001    6477    4137    8255   16472   13571
River Rch & RM=Noodle Creek,Reach-1         ,34917
    3329    4988    6458    4124    8228   16416   13513
River Rch & RM=Noodle Creek,Reach-1         ,29263
    3567    5325    6879    4382    8744   17446   14288
River Rch & RM=Noodle Creek,Reach-1         ,19054
    3576    5335    6890    4388    8754   17467   14294
River Rch & RM=Noodle Creek,Reach-1         ,13981
    3726    5563    7187    4579    9137   18230   14930
River Rch & RM=Noodle Creek,Reach-1         ,9100
    3721    5551    7168    4564    9106   18170   14861
River Rch & RM=Noodle Creek,Reach-1         ,5281
    3737    5573    7195    4580    9139   18235   14909
Boundary for River Rch & Prof#=Noodle Creek,Reach-1         , 1
Up Type= 0
Dn Type= 3
Dn Slope=0.001
Boundary for River Rch & Prof#=Noodle Creek,Reach-1         , 2
Up Type= 0
Dn Type= 3
Dn Slope=0.001
Boundary for River Rch & Prof#=Noodle Creek,Reach-1         , 3
Up Type= 0
Dn Type= 3
Dn Slope=0.001
Boundary for River Rch & Prof#=Noodle Creek,Reach-1         , 4
Up Type= 0
Dn Type= 3
Dn Slope=0.001
Boundary for River Rch & Prof#=Noodle Creek,Reach-1         , 5
Up Type= 0
Dn Type= 3
Dn Slope=0.001
Boundary for River Rch & Prof#=Noodle Creek,Reach-1         , 6
Up Type= 0
Dn Type= 3
Dn Slope=0.001
Boundary for River Rch & Prof#=Noodle Creek,Reach-1         , 7
Up Type= 0
Dn Type= 3
Dn Slope=0.001
DSS Import GetInterval= 0
DSS Import GetPeak= 0
DSS Import FillOption= 0

--- Noodle Creek.g01 (geometry) ---

Geom Title=Existing Conditions
Program Version=4.10

River Reach=Noodle Creek    ,Reach-1
Reach XY= 30
        1444305.        6849388.      1445510.83       6853740.3
       1448131.6      6857015.56      1455396.69      6859390.97
      1457302.29      6862182.72        1469255.        6863038.
      1470158.06       6868279.7      1472548.83      6871330.14
        1475955.        6872338.      1475660.47      6875540.45
      1478499.63      6878485.62      1477405.55      6878877.36
      1479101.87      6879889.61      1479165.75      6882497.68
      1481501.55      6883389.25      1480105.06      6885358.03
      1481747.93      6890837.99        1480605.        6893238.
      1484918.36      6899601.35      1486602.93      6900093.86
      1486305.32      6906772.98       1487355.2      6908763.08
      1486210.82      6911140.32      1487506.48      6912984.55
      1491961.21       6913095.8      1493556.56      6916484.58
      1495461.21      6915595.81      1496648.32      6918629.06
      1498849.38      6917943.62        1504455.        6925638.

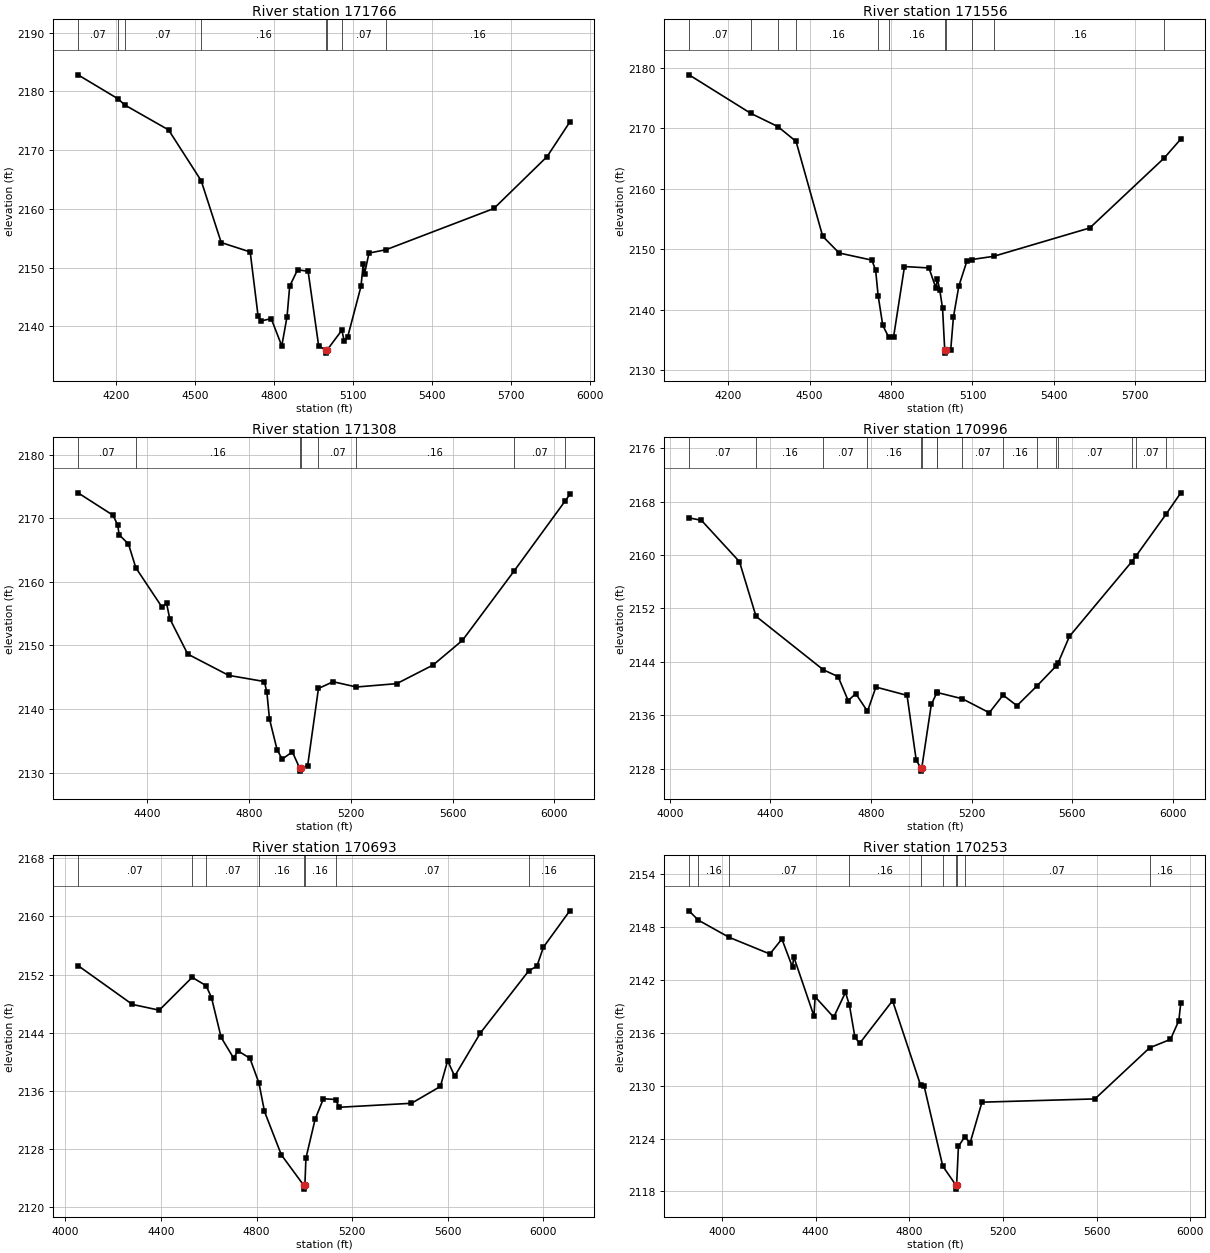
Type RM Length L Ch R = 1 ,171766  ,210,210,210
BEGIN DESCRIPTION:
Noodle Creek 112.0
END DESCRIPTION:
XS GIS Cut Line= 3
      1443421.23      6849485.47      1444413.46      6849495.89
      1445280.34      6849376.14
#Sta/Elev= 30
  4056.7 2182.81  4208.2 2178.74  4234.2 2177.68  4400.5 2173.44  4524.4 2164.79
  4600.5 2154.26  4710.5 2152.66  4740.5 2141.76  4750.5 2140.91  4790.5  2141.3
  4830.5 2136.66  4850.5 2141.66  4860.5 2146.83  4890.5 2149.63  4930.5 2149.37
  4970.5 2136.69  4997.9 2135.94  4998.2 2135.44  5002.1 2135.94  5058.6 2139.34
  5067.9 2137.43  5080.8 2138.21  5131.3 2146.81  5139.8 2150.67  5144.8 2148.95
  5161.6 2152.47  5226.3 2153.04    5636 2160.06  5837.9 2168.89  5924.1 2174.77
#Mann= 8 ,-1 , 0
  4056.7     .07       0  4208.2     .16       0  4234.2     .07       0
  4524.4     .16       0  4997.9     .07       0  5002.1     .16       0
  5058.6     .07       0  5226.3     .16       0
Bank Sta=4997.9,5002.1
XS Rating Curve= 0 ,0
Exp/Cntr=0.3,0.1

Type RM Length L Ch R = 1 ,171556  ,248,248,248
BEGIN DESCRIPTION:
Mapping XS 91f2ec69
END DESCRIPTION:
XS GIS Cut Line= 4
      1443468.11      6849618.28      1444061.89      6849706.82
      1444936.89      6849667.76      1445257.24      6849568.79
#Sta/Elev= 30
  4056.1 2178.86  4283.5 2172.49  4383.1 2170.31  4450.3 2167.85  4548.4 2152.17
    4609 2149.41  4729.6 2148.23  4743.4 2146.56  4752.6 2142.36  4769.7 2137.45
  4791.2 2135.52  4809.7 2135.59  4849.7 2147.17  4939.8 2146.94  4965.6 2143.59
  4970.6 2145.19  4979.9 2143.22  4989.9 2140.27  4997.9 2133.36  4998.2 2132.86
  5002.1 2133.36  5019.9 2133.36  5029.9  2138.8  5049.9 2143.95    5080 2148.13
  5097.5 2148.33  5178.1 2148.86  5532.3 2153.55  5806.6 2165.12  5867.6 2168.25
#Mann= 11 ,-1 , 0
  4056.1     .07       0  4283.5     .16       0  4383.1     .07       0
  4450.3     .16       0  4752.6     .07       0  4791.2     .16       0
  4997.9     .07       0  5002.1     .16       0  5097.5     .07       0
  5178.1     .16       0  5806.6     .07       0
Bank Sta=4997.9,5002.1
XS Rating Curve= 0 ,0
Exp/Cntr=0.3,0.1

Type RM Length L Ch R = 1 ,171308  ,312,312,312
BEGIN DESCRIPTION:
Mapping XS ee8ceca7
END DESCRIPTION:
XS GIS Cut Line= 4
      1443489.01      6849857.87      1443996.79      6849938.59
      1444874.39      6849899.53      1445377.81      6849702.32
#Sta/Elev= 30
  4126.9 2174.01  4264.6 2170.48  4283.4  2168.9  4288.4 2167.42  4325.4 2165.95
  4354.1 2162.23    4457 2156.04  4475.1 2156.62  4487.4 2154.24  4558.2 2148.65
  4719.3  2145.3  4859.5 2144.33  4869.5 2142.61  4879.5 2138.47  4909.5 2133.61
  4929.6 2132.13  4969.6 2133.27  4997.9 2130.74  4998.2 2130.24  5002.2 2130.74
  5029.7  2131.1  5072.2 2143.24  5129.8  2144.3  5221.4 2143.47    5380    2144
  5522.5 2146.92  5638.3 2150.81  5841.6 2161.73  6041.9 2172.72  6060.2 2173.75
#Mann= 8 ,-1 , 0
  4126.9     .07       0  4354.1     .16       0  4997.9     .07       0
  5002.2     .16       0  5072.2     .07       0  5221.4     .16       0
  5841.6     .07       0  6041.9     .16       0
Bank Sta=4997.9,5002.2
XS Rating Curve= 0 ,0
Exp/Cntr=0.3,0.1

Type RM Length L Ch R = 1 ,170996  ,303,303,303
BEGIN DESCRIPTION:
Mapping XS 242d3412
END DESCRIPTION:
XS GIS Cut Line= 4
      1443486.38      6850201.62      1443869.19       6850256.3
      1444916.06      6850183.39      1445381.09      6849949.57
#Sta/Elev= 30
  4076.2 2165.56  4125.3  2165.2  4276.8    2159  4342.6 2150.83  4610.2 2142.83
  4669.2  2141.8  4709.3 2138.21  4739.4 2139.26  4786.1 2136.61  4819.6 2140.24
  4943.5    2139    4980 2129.31  4997.9 2128.16  4998.2 2127.66  5002.2 2128.16
  5040.1 2137.64  5062.5 2139.43  5064.1 2139.42  5163.5 2138.49  5270.7  2136.4
  5325.7 2139.04  5380.9 2137.45  5461.8 2140.46  5537.8 2143.44  5544.6 2143.86
  5589.5 2147.82  5837.7 2159.01  5855.9 2159.93  5974.4 2166.13  6032.8 2169.31
#Mann= 16 ,-1 , 0
  4076.2     .07       0  4342.6     .16       0  4610.2     .07       0
  4786.1     .16       0  4997.9     .07       0  5002.2     .16       0
  5062.5     .07       0  5064.1     .16       0  5163.5     .07       0
  5325.7     .16       0  5461.8     .07       0  5537.8     .16       0
  5544.6     .07       0  5837.7     .16       0  5855.9     .07       0
  5974.4     .16       0
Bank Sta=4997.9,5002.2
XS Rating Curve= 0 ,0
Exp/Cntr=0.3,0.1

Type RM Length L Ch R = 1 ,170693  ,440,440,440
BEGIN DESCRIPTION:
Mapping XS 22374499
END DESCRIPTION:
XS GIS Cut Line= 4
      1443488.11      6850514.98      1444061.03      6850562.73
      1445037.59      6850432.52      1445470.84      6850185.57
#Sta/Elev= 30
  4052.4 2153.23  4280.1 2147.88  4392.6 2147.09  4530.2 2151.61  4588.5 2150.47
  4611.2 2148.83  4651.5 2143.35  4703.9 2140.49  4722.1 2141.49    4772 2140.47
  4809.8 2137.07  4833.1 2133.14  4903.7 2127.17  4997.9 2122.95  4998.2 2122.45
  5002.2 2122.95  5006.6 2126.71  5044.9 2132.05  5079.7  2134.9  5130.6 2134.79
  5145.8 2133.72  5448.5 2134.27  5569.5 2136.59  5599.8 2140.13  5629.3    2138
  5737.3 2143.97  5939.5 2152.51  5973.6 2153.15  6000.9 2155.77  6111.2 2160.77
#Mann= 8 ,-1 , 0
  4052.4     .07       0  4530.2     .16       0  4588.5     .07       0
  4809.8     .16       0  4997.9     .07       0  5002.2     .16       0
  5130.6     .07       0  5939.5     .16       0
Bank Sta=4997.9,5002.2
XS Rating Curve= 0 ,0
Exp/Cntr=0.3,0.1

Type RM Length L Ch R = 1 ,170253  ,469,469,469
BEGIN DESCRIPTION:
Mapping XS 87f06072
END DESCRIPTION:
XS GIS Cut Line= 4
      1443370.95      6850875.23      1444169.53      6850962.03
      1445076.65      6850875.23      1445389.13      6850649.55
#Sta/Elev= 30
  3859.6 2149.85  3898.6  2148.8  4030.2 2146.85  4204.9 2144.95    4256 2146.65
  4301.5 2143.44  4306.5 2144.65    4393 2137.91    4398 2140.09  4477.3 2137.77
  4527.6  2140.6  4544.7 2139.11  4567.8 2135.52  4587.9  2134.8  4728.6 2139.65
  4848.4 2130.05  4863.5 2129.95    4943 2120.87  4997.9 2118.76  4998.2 2118.26
  5002.2 2118.76  5009.9 2123.11    5036 2124.16  5060.2 2123.54  5110.4 2128.13
  5592.8  2128.5  5826.3  2134.3  5915.4 2135.26    5951 2137.38  5959.6 2139.44
#Mann= 10 ,-1 , 0
  3859.6     .07       0  3898.6     .16       0  4030.2     .07       0
  4544.7     .16       0  4848.4     .07       0    4943     .16       0
  4997.9     .07       0  5002.2     .16       0    5036     .07       0
  5826.3     .16       0
Bank Sta=4997.9,5002.2
XS Rating Curve= 0 ,0
Exp/Cntr=0.3,0.1

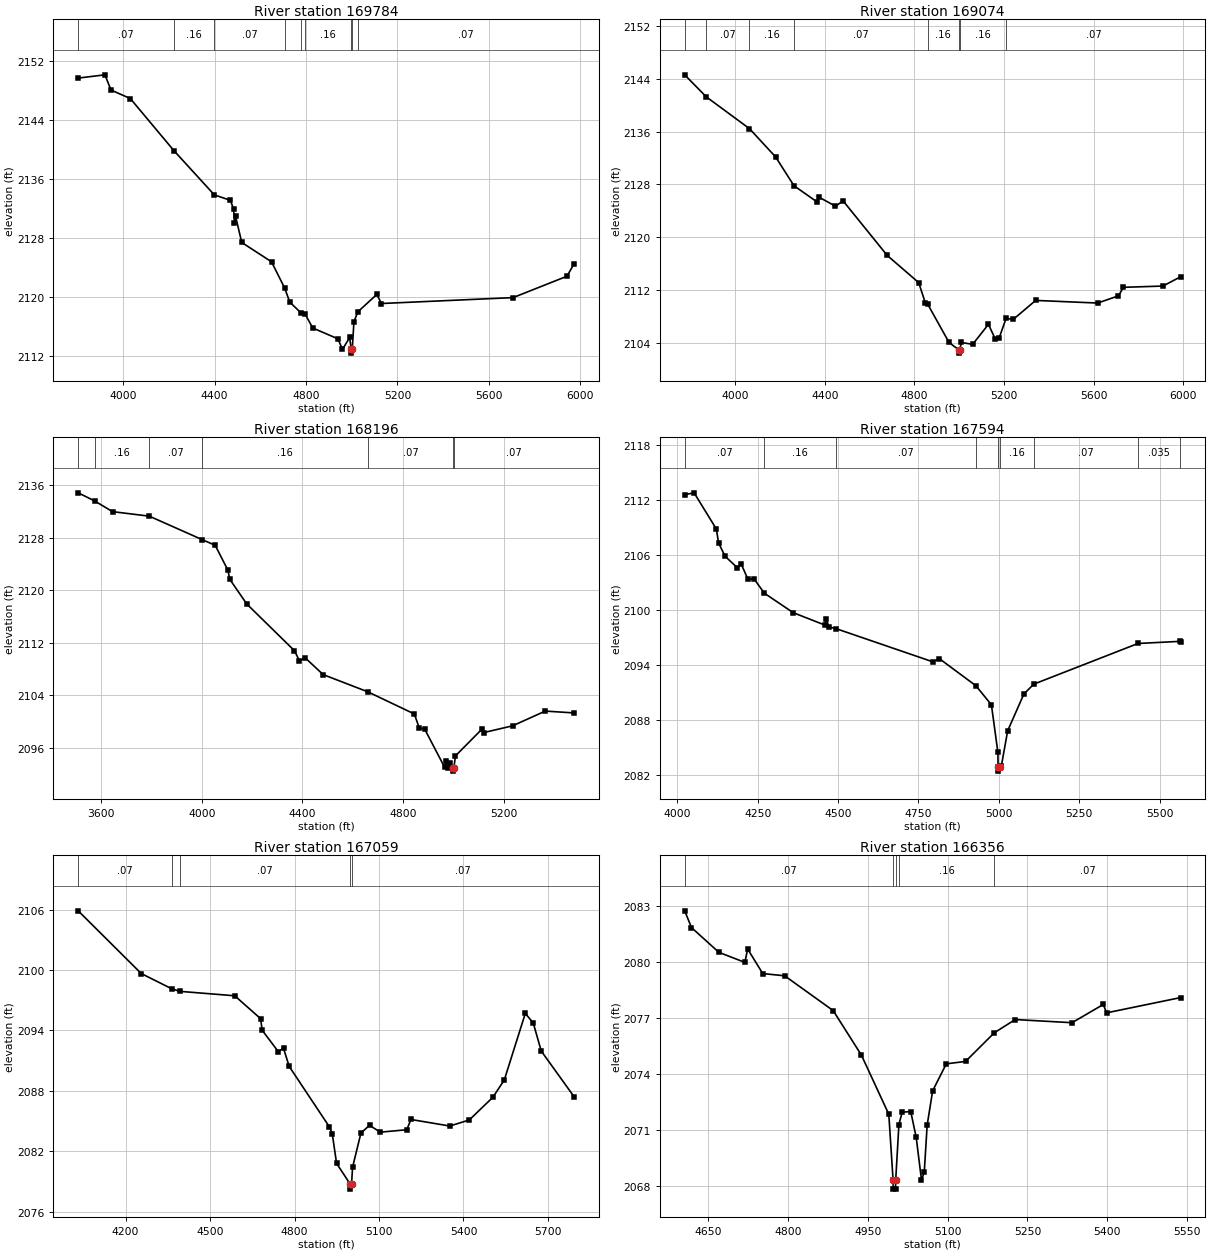
Type RM Length L Ch R = 1 ,169784  ,710,710,710
BEGIN DESCRIPTION:
Mapping XS 8194d900
END DESCRIPTION:
XS GIS Cut Line= 4
      1443362.28      6851352.66      1444039.33      6851413.42
      1445115.71      6851348.32      1445454.28      6851113.93
#Sta/Elev= 30
  3803.2 2149.74  3920.1 2150.18  3946.5 2148.12  4031.3 2146.96  4221.8  2139.9
  4398.6  2133.9  4468.6 2133.16    4483 2132.01  4486.8 2130.06  4491.8 2130.97
  4518.7 2127.44  4648.9 2124.82  4706.4 2121.26  4729.1 2119.34  4776.3 2117.94
  4794.9 2117.79  4829.3 2115.84  4939.5 2114.37  4959.5 2112.93  4990.7 2114.55
  4997.8 2112.93  4998.1 2112.43  5002.2 2112.93  5009.6 2116.68  5026.4 2118.02
  5109.8  2120.4  5129.8 2119.16  5705.8 2119.96  5941.6 2122.86  5973.1 2124.56
#Mann= 9 ,-1 , 0
  3803.2     .07       0  4221.8     .16       0  4398.6     .07       0
  4706.4     .16       0  4776.3     .07       0  4794.9     .16       0
  4997.8     .07       0  5002.2     .16       0  5026.4     .07       0
Bank Sta=4997.8,5002.2
XS Rating Curve= 0 ,0
Exp/Cntr=0.3,0.1

Type RM Length L Ch R = 1 ,169074  ,878,878,878
BEGIN DESCRIPTION:
Mapping XS a969e1e5
END DESCRIPTION:
XS GIS Cut Line= 4
      1443535.81      6851990.67      1444238.98      6852064.46
      1445371.79      6851964.64      1445614.82      6851686.89
#Sta/Elev= 30
  3774.9 2144.63  3871.2 2141.29  4064.1 2136.46  4180.9 2132.16  4262.6  2127.8
  4367.2  2125.3  4372.2  2126.1  4447.8 2124.69  4481.9  2125.5  4678.7 2117.22
  4819.3 2113.09  4849.4 2109.96  4859.6 2109.81  4954.5 2104.02  4997.8 2102.89
  4998.1 2102.39  5002.3 2102.89    5010 2104.01  5060.2 2103.72  5130.5 2106.76
  5160.6 2104.56  5178.9 2104.74  5209.3 2107.67  5240.9  2107.5  5341.3 2110.39
  5618.2 2109.99  5710.9 2111.09  5732.8 2112.38  5909.3 2112.57  5988.2 2113.98
#Mann= 8 ,-1 , 0
  3774.9     .16       0  3871.2     .07       0  4064.1     .16       0
  4262.6     .07       0  4859.6     .16       0  4997.8     .07       0
  5002.3     .16       0  5209.3     .07       0
Bank Sta=4997.8,5002.3
XS Rating Curve= 0 ,0
Exp/Cntr=0.3,0.1

Type RM Length L Ch R = 1 ,168196  ,602,602,602
BEGIN DESCRIPTION:
Mapping XS 122b7554
END DESCRIPTION:
XS GIS Cut Line= 4
      1443700.82      6852329.23      1444725.09      6852676.44
      1445354.43      6852806.65      1445579.53      6852702.76
#Sta/Elev= 30
  3508.6 2134.81  3574.6 2133.56    3645 2131.95  3791.4 2131.26  4001.7 2127.69
  4053.3 2126.83  4104.3 2123.01  4110.9 2121.68    4179  2117.9  4368.3 2110.81
  4388.3 2109.27  4410.5 2109.74  4482.6 2107.17  4660.8 2104.54  4845.3 2101.18
    4865 2099.02  4886.2 2098.89  4965.4 2093.09  4970.5 2093.97  4978.1 2092.99
  4988.3 2093.66  4997.6 2092.99    4998 2092.49  5002.4 2092.99  5008.7 2094.81
    5116 2098.95  5121.1 2098.35  5235.9 2099.38  5365.9 2101.62  5480.7 2101.34
#Mann= 7 ,-1 , 0
  3508.6     .07       0  3574.6     .16       0  3791.4     .07       0
  4001.7     .16       0  4660.8     .07       0  4997.6     .07       0
  5002.4     .07       0
Bank Sta=4997.6,5002.4
XS Rating Curve= 0 ,0
Exp/Cntr=0.3,0.1

Type RM Length L Ch R = 1 ,167594  ,535,535,535
BEGIN DESCRIPTION:
Mapping XS 65121eba
END DESCRIPTION:
XS GIS Cut Line= 3
      1444390.88      6853427.31      1445645.23      6853240.68
      1445830.96      6853037.67
#Sta/Elev= 30
  4022.4 2112.59  4051.8 2112.79  4121.1 2108.83  4127.7 2107.33  4147.9 2105.88
  4185.4 2104.64  4198.4 2105.02  4218.7 2103.39  4238.9 2103.37  4270.2 2101.84
  4360.2 2099.71  4457.8 2098.37  4462.9 2099.01  4471.4 2098.16  4494.1 2097.96
  4794.5 2094.35  4815.1 2094.69  4928.6 2091.74  4976.9 2089.66  4997.1 2084.46
  4997.6 2082.92    4998 2082.42  5002.5 2082.92  5007.6 2082.94  5027.5 2086.82
    5078 2090.84  5108.6 2091.91  5433.1 2096.35  5562.6 2096.58  5565.7 2096.54
#Mann= 9 ,-1 , 0
  4022.4     .07       0  4270.2     .16       0  4494.1     .07       0
  4928.6     .16       0  4997.6     .07       0  5002.5     .16       0
  5108.6     .07       0  5433.1    .035       0  5562.6     .07       0
Bank Sta=4997.6,5002.5
XS Rating Curve= 0 ,0
Exp/Cntr=0.3,0.1

Type RM Length L Ch R = 1 ,167059  ,703,703,703
BEGIN DESCRIPTION:
Mapping XS 3c4afb00
END DESCRIPTION:
XS GIS Cut Line= 4
      1444571.46      6853830.96      1445036.72      6853858.73
      1446078.39      6853657.34        1446251.      6853498.54
#Sta/Elev= 30
  4031.6 2105.88  4255.5 2099.65  4364.2 2098.13  4392.5 2097.88  4587.6 2097.44
  4679.3 2095.17  4685.2 2094.01    4742  2091.9  4760.8 2092.22  4781.1 2090.42
  4923.7 2084.42  4933.9 2083.75  4949.3 2080.79  4997.6 2078.73  4997.9 2078.23
  5002.5 2078.73  5006.2 2080.41  5035.8  2083.8  5066.3 2084.57  5104.7 2083.89
  5198.7 2084.13  5213.4 2085.15  5351.5  2084.5  5420.6  2085.1  5504.3 2087.35
    5545 2089.07  5619.7 2095.69    5648 2094.73  5676.3 2091.95  5793.2  2087.4
#Mann= 5 ,-1 , 0
  4031.6     .07       0  4364.2     .16       0  4392.5     .07       0
  4997.6     .07       0  5002.5     .07       0
Bank Sta=4997.6,5002.5
XS Rating Curve= 0 ,0
Exp/Cntr=0.3,0.1

Type RM Length L Ch R = 1 ,166356  ,523,523,523
BEGIN DESCRIPTION:
Mapping XS f66219db
END DESCRIPTION:
XS GIS Cut Line= 3
      1445682.56      6854240.68      1446374.52      6854070.06
      1446502.82      6853892.18
#Sta/Elev= 30
  4605.9 2082.76  4618.7 2081.86  4670.2 2080.53    4719 2079.99  4724.2 2080.71
  4752.6 2079.39  4793.8 2079.27    4885  2077.4    4938 2075.01  4989.5 2071.83
  4997.5 2068.31  4997.9 2067.81  5002.1 2067.81  5002.5 2068.31  5008.5 2071.28
  5014.6 2071.94  5030.7 2071.98    5041 2070.59  5050.9 2068.31  5056.1 2068.71
  5061.6 2071.25  5071.9 2073.09  5097.5 2074.54  5133.7 2074.67  5187.8 2076.21
  5227.1 2076.92  5333.8 2076.75  5392.6 2077.73  5398.8 2077.28  5537.9  2078.1
#Mann= 5 ,-1 , 0
  4605.9     .07       0  4997.5     .07       0  5002.5     .07       0
  5008.5     .16       0  5187.8     .07       0
Bank Sta=4997.5,5002.5
XS Rating Curve= 0 ,0
Exp/Cntr=0.3,0.1

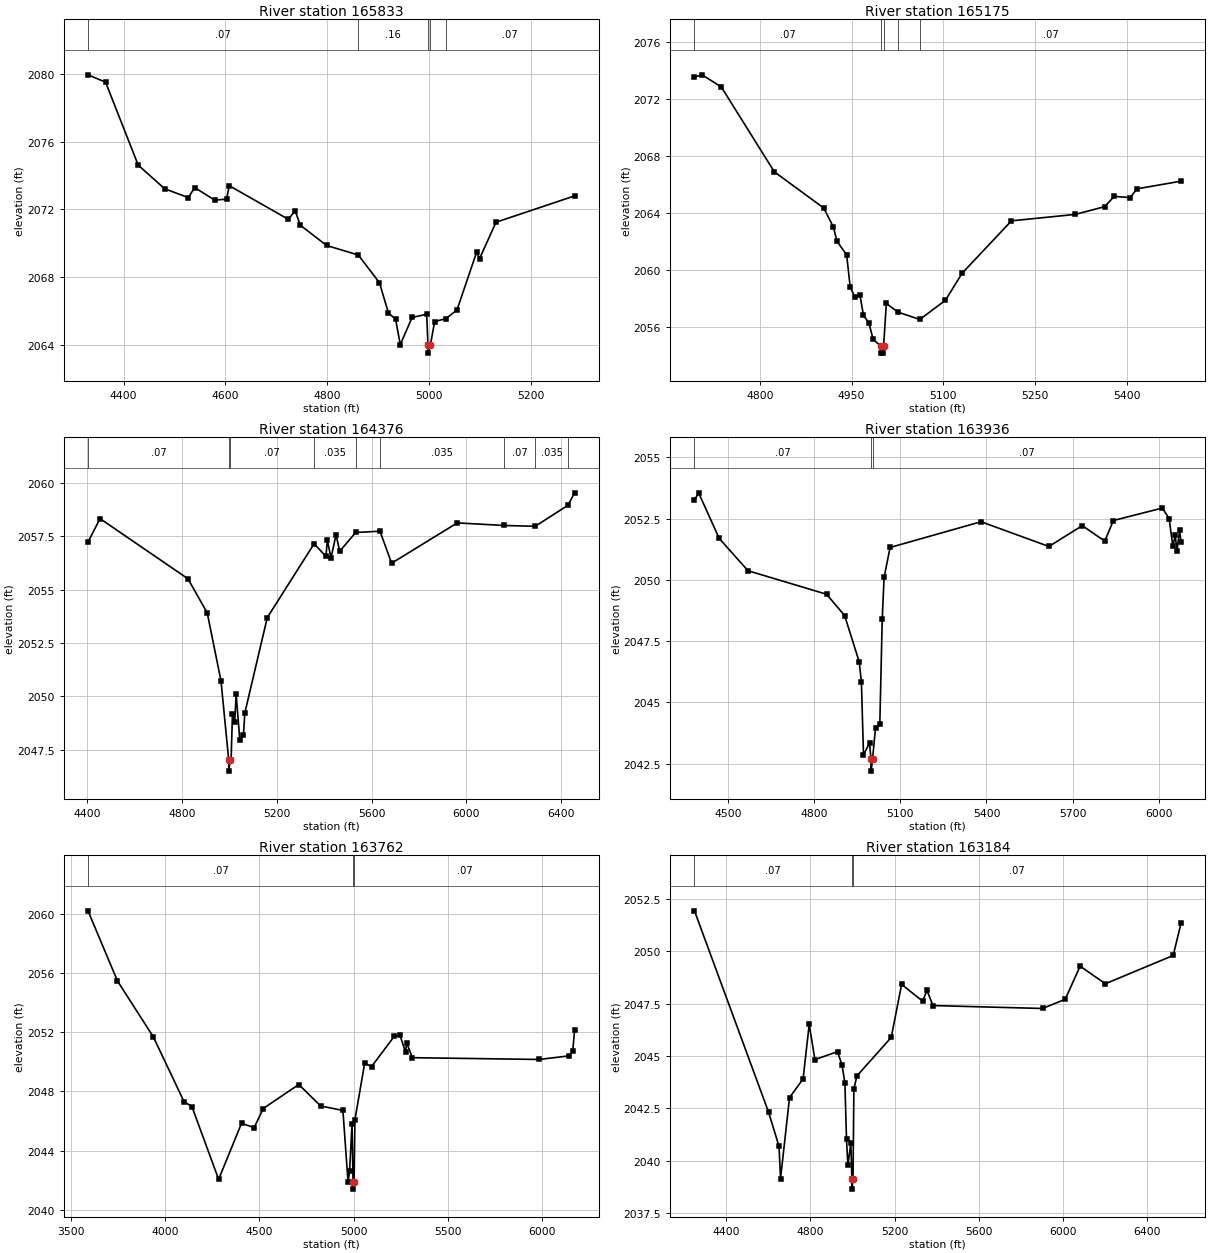
Type RM Length L Ch R = 1 ,165833  ,658,658,658
BEGIN DESCRIPTION:
Mapping XS 853adaee
END DESCRIPTION:
XS GIS Cut Line= 3
      1445793.78      6854785.01      1446558.95       6854442.5
      1446586.78      6854328.79
#Sta/Elev= 30
  4330.1 2079.93  4364.6  2079.5  4428.7 2074.61  4480.6 2073.22    4527  2072.7
  4539.6 2073.29  4578.9 2072.55  4602.1 2072.61  4607.5  2073.4  4723.5 2071.42
  4736.8 2071.93  4746.7 2071.08  4798.6 2069.88  4860.7 2069.32  4902.3 2067.69
    4920  2065.9    4934 2065.54  4943.2 2064.04  4966.4 2065.64  4995.1 2065.83
  4997.5 2064.04  4997.9 2063.54  5002.5 2064.04  5010.7  2065.4  5032.7 2065.57
  5054.5 2066.08  5093.3  2069.5  5098.8  2069.1  5131.2 2071.25  5285.5  2072.8
#Mann= 5 ,-1 , 0
  4330.1     .07       0  4860.7     .16       0  4997.5     .07       0
  5002.5     .16       0  5032.7     .07       0
Bank Sta=4997.5,5002.5
XS Rating Curve= 0 ,0
Exp/Cntr=0.3,0.1

Type RM Length L Ch R = 1 ,165175  ,799,799,799
BEGIN DESCRIPTION:
Mapping XS 94dd7122
END DESCRIPTION:
XS GIS Cut Line= 3
      1446176.86      6855227.84      1446705.63      6854927.46
      1446763.86      6854748.95
#Sta/Elev= 30
  4693.1 2073.52  4705.6 2073.67    4737 2072.82  4823.8 2066.87  4904.5 2064.34
  4920.4    2063  4926.2    2062    4942 2061.06  4947.8  2058.8  4955.5  2058.1
  4963.7 2058.24  4969.4 2056.85  4978.5 2056.26  4985.3 2055.14  4997.5 2054.67
  4997.9 2054.17  5002.2 2054.17  5002.5 2054.67  5006.9 2057.65  5026.1 2057.04
  5061.6 2056.53  5103.5 2057.87  5130.9 2059.77  5211.6 2063.44  5315.9 2063.89
  5363.8 2064.43  5379.7 2065.15  5405.8 2065.07  5416.8 2065.68    5489 2066.22
#Mann= 5 ,-1 , 0
  4693.1     .07       0  4997.5     .07       0  5002.5     .07       0
  5026.1     .16       0  5061.6     .07       0
Bank Sta=4997.5,5002.5
XS Rating Curve= 0 ,0
Exp/Cntr=0.3,0.1

Type RM Length L Ch R = 1 ,164376  ,440,440,440
BEGIN DESCRIPTION:
Mapping XS 1a16e3a5
END DESCRIPTION:
XS GIS Cut Line= 3
      1446495.04      6855768.47      1447550.61      6855122.62
       1447904.8      6854386.47
#Sta/Elev= 30
    4403 2057.23  4453.8 2058.33    4825 2055.51  4906.4 2053.91  4964.5 2050.72
  4997.3 2046.99  4997.7 2046.49  5002.8 2046.99  5007.1 2046.99  5012.9 2049.18
  5022.5 2048.79  5028.4 2050.11  5043.8 2047.96  5059.3 2048.18  5065.1 2049.22
  5159.9 2053.69  5357.5 2057.15  5407.6 2056.56  5413.4 2057.31  5428.9 2056.49
  5450.2 2057.57  5465.6  2056.8  5533.2 2057.68  5635.7 2057.74  5684.8 2056.24
  5961.9 2058.13  6157.9 2058.01  6291.1 2057.97  6429.7 2058.96  6457.4 2059.54
#Mann= 9 ,-1 , 0
    4403     .07       0  4997.3     .07       0  5002.8     .07       0
  5357.5    .035       0  5533.2     .07       0  5635.7    .035       0
  6157.9     .07       0  6291.1    .035       0  6429.7     .07       0
Bank Sta=4997.3,5002.8
XS Rating Curve= 0 ,0
Exp/Cntr=0.3,0.1

Type RM Length L Ch R = 1 ,163936  ,174,174,174
BEGIN DESCRIPTION:
Mapping XS 3bc1dcf9
END DESCRIPTION:
XS GIS Cut Line= 4
      1446739.23      6855954.78      1447062.59      6855922.75
      1447960.33      6855310.12      1448120.02      6855074.06
#Sta/Elev= 30
  4381.8 2053.26  4396.3 2053.55    4468 2051.69  4568.5 2050.37  4842.5 2049.41
  4905.4 2048.54  4956.3 2046.65  4963.9 2045.83  4971.2 2042.85  4992.2 2043.34
  4997.3 2042.69  4997.7 2042.19  5002.8 2042.69  5013.1 2043.95  5028.1 2044.11
  5036.5 2048.38    5043  2050.1    5064 2051.32    5381 2052.37  5617.7 2051.36
    5734 2052.21  5812.6 2051.58  5842.5 2052.42  6013.5 2052.93  6037.2 2052.49
  6049.7 2051.37  6058.2 2051.81  6064.3 2051.18  6073.2 2052.02  6078.6 2051.54
#Mann= 3 ,-1 , 0
  4381.8     .07       0  4997.3     .07       0  5002.8     .07       0
Bank Sta=4997.3,5002.8
XS Rating Curve= 0 ,0
Exp/Cntr=0.3,0.1

Type RM Length L Ch R = 1 ,163762  ,578,578,578
BEGIN DESCRIPTION:
Mapping XS 056acd84
END DESCRIPTION:
XS GIS Cut Line= 5
      1446265.23      6856769.44      1446804.32      6856261.61
      1447491.82      6855831.92      1447783.48      6855636.61
       1448179.3      6855079.35
#Sta/Elev= 30
  3588.7 2060.19  3745.2 2055.46  3936.1 2051.68  4098.8 2047.32  4141.2 2046.97
  4282.9 2042.07  4404.5 2045.85  4471.6 2045.56    4520 2046.85  4708.7 2048.47
  4825.4 2047.02  4943.3 2046.72  4970.5 2041.91  4978.7 2042.61  4991.7 2045.79
  4997.3 2041.91  4997.7 2041.41  5002.8 2041.91  5007.1 2046.09    5059 2049.91
  5095.5 2049.68  5216.1 2051.72  5246.1 2051.81  5276.1 2050.66  5282.1 2051.28
  5312.1 2050.28    5986 2050.16  6143.4  2050.4  6164.3  2050.7  6174.6 2052.16
#Mann= 3 ,-1 , 0
  3588.7     .07       0  4997.3     .07       0  5002.8     .07       0
Bank Sta=4997.3,5002.8
XS Rating Curve= 0 ,0
Exp/Cntr=0.3,0.1

Type RM Length L Ch R = 1 ,163184  ,871,871,871
BEGIN DESCRIPTION:
Mapping XS fa077003
END DESCRIPTION:
XS GIS Cut Line= 4
       1446799.1      6856735.58      1447299.23      6856355.96
      1447967.28       6855775.4      1448265.75      6855032.68
#Sta/Elev= 30
    4249 2051.93  4601.1 2042.33    4651 2040.69  4658.2 2039.15    4701 2043.02
  4765.4 2043.91  4794.5 2046.51  4821.6 2044.83    4929 2045.21  4950.8 2044.56
  4964.1 2043.72  4971.8 2041.03  4978.4 2039.78  4992.6 2040.87  4997.2 2039.15
  4997.7 2038.65  5002.8 2039.15  5006.9 2043.43  5021.1 2044.05  5184.5 2045.89
  5233.8 2048.42  5333.6 2047.62  5354.4 2048.13  5382.9 2047.41    5904 2047.27
  6011.5 2047.71  6082.5 2049.29  6202.4 2048.45  6524.9  2049.8  6562.4 2051.35
#Mann= 3 ,-1 , 0
    4249     .07       0  4997.2     .07       0  5002.8     .07       0
Bank Sta=4997.2,5002.8
XS Rating Curve= 0 ,0
Exp/Cntr=0.3,0.1

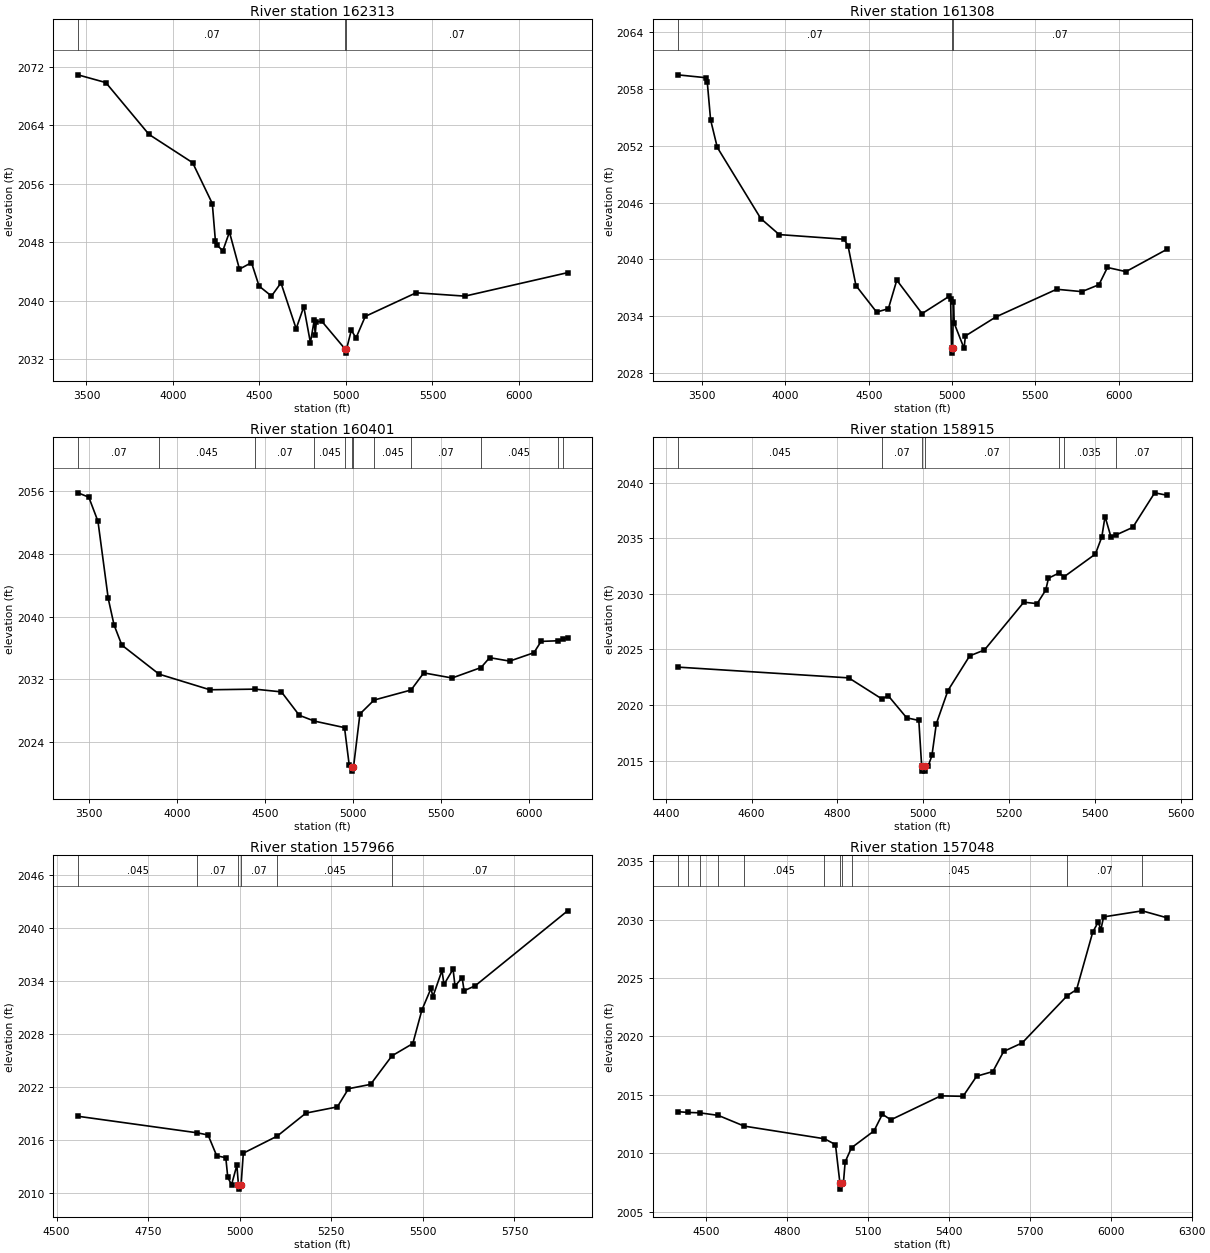
Type RM Length L Ch R = 1 ,162313  ,1005,1005,1005
BEGIN DESCRIPTION:
Mapping XS f287a8bd
END DESCRIPTION:
XS GIS Cut Line= 4
      1447543.67      6858282.34      1447696.44      6857358.73
        1448252.      6856310.12      1448390.88      6855615.72
#Sta/Elev= 30
  3450.3 2070.88  3611.7 2069.82    3861 2062.74  4113.5 2058.87  4227.3 2053.29
  4245.3 2048.16  4255.4 2047.57  4288.3 2046.84  4326.4 2049.39  4384.3 2044.32
  4453.8 2045.21  4497.8    2042  4569.5 2040.64  4624.2 2042.44  4712.1 2036.18
  4756.1 2039.18  4794.5 2034.27  4816.5 2037.34  4822.1 2035.38  4828.6 2037.11
  4860.5 2037.19  4997.2 2033.34  4997.7 2032.84  5002.8 2033.34  5030.8 2035.96
  5058.4 2034.93  5111.6 2037.86  5405.8 2041.09  5687.5 2040.63  6281.3 2043.84
#Mann= 3 ,-1 , 0
  3450.3     .07       0  4997.2     .07       0  5002.8     .07       0
Bank Sta=4997.2,5002.8
XS Rating Curve= 0 ,0
Exp/Cntr=0.3,0.1

Type RM Length L Ch R = 1 ,161308  ,907,907,907
BEGIN DESCRIPTION:
Mapping XS 74819135
END DESCRIPTION:
XS GIS Cut Line= 4
      1448460.33      6858615.66      1448536.72      6857789.29
      1448745.05      6856282.34      1448633.94      6855705.92
#Sta/Elev= 30
  3352.5 2059.48  3520.9 2059.18  3530.9 2058.76    3551 2054.74  3591.2 2051.82
  3852.3 2044.31  3962.7 2042.62  4351.3 2042.13  4375.5 2041.46  4423.2 2037.24
  4547.1 2034.44  4617.8  2034.8  4668.3 2037.81  4819.7 2034.28  4981.2 2036.09
  4991.3 2035.81  4996.7 2030.61  4997.2 2030.11  5003.3 2030.61    5008 2035.54
  5013.1 2033.25  5072.1 2030.61  5079.8 2031.92  5263.9 2033.94  5627.3 2036.85
  5778.7  2036.6  5881.2 2037.33  5932.1 2039.15  6043.2 2038.71  6290.7 2041.08
#Mann= 3 ,-1 , 0
  3352.5     .07       0  4996.7     .07       0  5003.3     .07       0
Bank Sta=4996.7,5003.3
XS Rating Curve= 0 ,0
Exp/Cntr=0.3,0.1

Type RM Length L Ch R = 1 ,160401  ,1486,1486,1486
BEGIN DESCRIPTION:
Mapping XS 79d14a0b
END DESCRIPTION:
XS GIS Cut Line= 4
      1448960.34      6858407.33      1449182.55      6857664.29
      1449370.05      6856567.07      1449258.94      6855678.17
#Sta/Elev= 30
  3436.3 2055.77  3498.2 2055.22  3550.4 2052.14  3608.7 2042.32  3641.8 2038.95
  3686.1 2036.38  3897.8 2032.68  4187.1 2030.69  4443.1 2030.77  4593.6 2030.42
  4695.1 2027.44  4781.3  2026.7  4952.3 2025.87  4979.1 2021.09  4996.6 2020.83
  4997.1 2020.33  5003.4 2020.83    5040 2027.61  5120.4 2029.38  5330.7 2030.66
  5402.8 2032.84  5564.1 2032.19  5728.5 2033.52  5777.5 2034.78  5891.6 2034.34
  6029.5 2035.41  6069.8 2036.85  6165.4 2036.93  6193.4  2037.1  6220.8 2037.34
#Mann= 12 ,-1 , 0
  3436.3     .07       0  3897.8    .045       0  4443.1     .07       0
  4781.3    .045       0  4952.3     .07       0  4996.6     .07       0
  5003.4     .07       0  5120.4    .045       0  5330.7     .07       0
  5728.5    .045       0  6165.4     .07       0  6193.4    .045       0
Bank Sta=4996.6,5003.4
XS Rating Curve= 0 ,0
Exp/Cntr=0.3,0.1

Type RM Length L Ch R = 1 ,158915  ,949,949,949
BEGIN DESCRIPTION:
Mapping XS 6abe13fe
END DESCRIPTION:
XS GIS Cut Line= 4
      1449923.32      6857445.17       1450064.3       6857303.2
      1450196.44       6856650.4      1450425.58      6856497.64
#Sta/Elev= 30
  4427.3 2023.41  4826.5 2022.44    4904 2020.54  4918.4 2020.84  4961.4 2018.85
  4989.8 2018.61  4996.4 2014.55  4996.9 2014.05  5003.2 2014.05  5003.7 2014.55
  5012.1 2014.55  5020.4 2015.46  5030.6 2018.31  5057.7  2021.3  5108.4 2024.42
  5142.8 2024.95  5234.6 2029.25  5265.6 2029.12  5285.7 2030.34  5292.1 2031.41
  5315.8 2031.86  5328.9 2031.55  5401.4 2033.58  5416.4 2035.12  5423.9 2036.96
  5437.4 2035.16  5450.2 2035.31  5488.5 2035.98  5539.6 2039.09  5568.8 2038.87
#Mann= 7 ,-1 , 0
  4427.3    .045       0    4904     .07       0  4996.4     .07       0
  5003.7     .07       0  5315.8    .045       0  5328.9    .035       0
  5450.2     .07       0
Bank Sta=4996.4,5003.7
XS Rating Curve= 0 ,0
Exp/Cntr=0.3,0.1

Type RM Length L Ch R = 1 ,157966  ,918,918,918
BEGIN DESCRIPTION:
Mapping XS eb184fdb
END DESCRIPTION:
XS GIS Cut Line= 4
      1450412.92       6857938.2      1450579.34      6857818.72
      1450911.72      6856942.07      1450918.67      6856747.61
#Sta/Elev= 30
  4558.1 2018.65  4883.4 2016.78  4913.5 2016.53  4937.1 2014.17  4961.9 2013.96
  4967.3 2011.73  4977.6  2010.9  4992.1  2013.1  4996.4  2010.9  4996.9  2010.4
  5003.7  2010.9  5009.7 2014.47  5102.1  2016.4  5180.8 2019.01  5266.4 2019.71
  5296.9 2021.77  5357.2 2022.26  5415.5 2025.49  5472.5 2026.88  5497.3 2030.68
  5522.1 2033.12  5527.4  2032.2  5552.2 2035.16  5557.6 2033.57  5582.4 2035.31
  5587.7 2033.39  5607.2 2034.34  5612.5 2032.86  5642.7 2033.42  5895.1 2041.91
#Mann= 6 ,-1 , 0
  4558.1    .045       0  4883.4     .07       0  4996.4     .07       0
  5003.7     .07       0  5102.1    .045       0  5415.5     .07       0
Bank Sta=4996.4,5003.7
XS Rating Curve= 0 ,0
Exp/Cntr=0.3,0.1

Type RM Length L Ch R = 1 ,157048  ,1378,1378,1378
BEGIN DESCRIPTION:
Mapping XS 7e4a2ce8
END DESCRIPTION:
XS GIS Cut Line= 4
      1451034.43      6858257.65      1451348.76      6858153.05
      1451529.78      6857435.12      1451495.08      6856692.51
#Sta/Elev= 30
  4394.2 2013.57  4432.7  2013.5  4475.8 2013.47  4545.2 2013.25  4641.6 2012.33
  4938.9 2011.25  4979.7 2010.75  4996.3 2007.44  4996.8 2006.94  5003.7 2007.44
  5009.1 2007.44  5015.6 2009.27  5039.2 2010.48  5122.6 2011.92  5153.5 2013.35
    5185 2012.87  5370.1 2014.92  5452.6 2014.88    5503  2016.6  5563.1    2017
  5603.1 2018.72  5671.8 2019.45  5839.2  2023.5  5873.4 2024.01  5933.5 2028.94
  5953.5 2029.78  5963.5 2029.14  5973.5 2030.23  6116.7 2030.75  6209.3 2030.15
#Mann= 11 ,-1 , 0
  4394.2    .045       0  4432.7     .07       0  4475.8    .045       0
  4545.2     .07       0  4641.6    .045       0  4938.9     .07       0
  4996.3     .07       0  5003.7     .07       0  5039.2    .045       0
  5839.2     .07       0  6116.7    .045       0
Bank Sta=4996.3,5003.7
XS Rating Curve= 0 ,0
Exp/Cntr=0.3,0.1